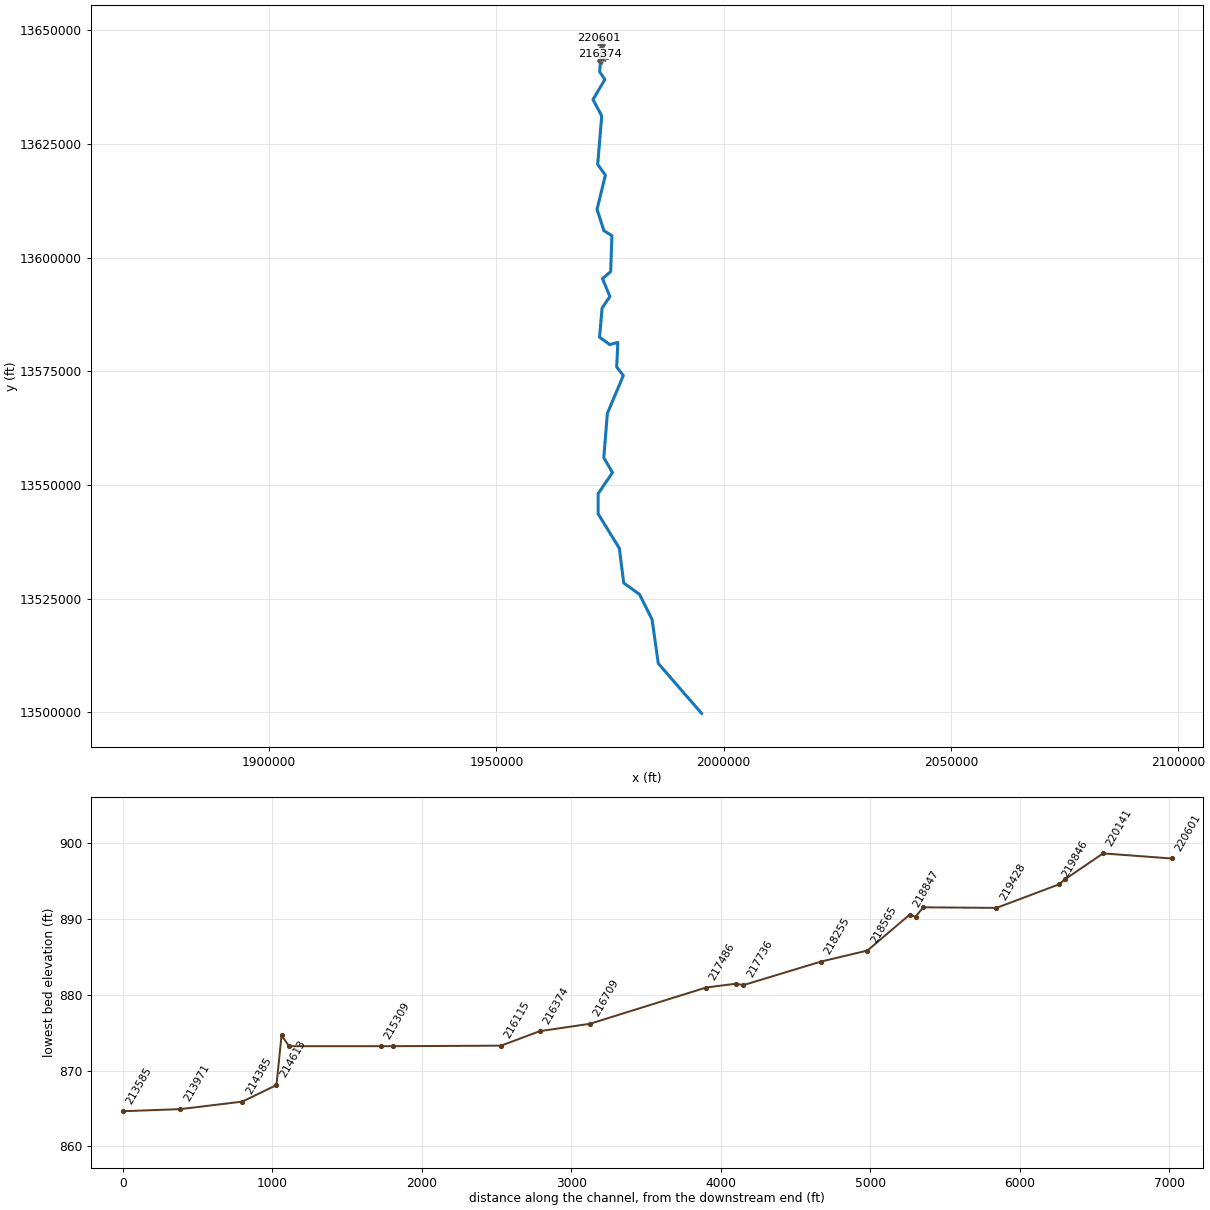
--- Black Creek.prj (project) ---

Proj Title=Black Creek Base Level Engineering
Current Plan=p02
Default Exp/Contr=0.3,0.1
English Units
Geom File=g01
Flow File=f01
Plan File=p02
Y Axis Title=Elevation
X Axis Title(PF)=Main Channel Distance
X Axis Title(XS)=Station
BEGIN DESCRIPTION:
Black Creek
END DESCRIPTION:
DSS File=dss
DSS Export Rating Curves= 0
DSS Export Rating Curve Sorted= 0
DSS Export Volume Flow Curves= 0
DXF OffsetX= 0
DXF OffsetY= 0
DXF ScaleX= 1
DXF ScaleY= 10

--- Black Creek.p02 (plan) ---

Plan Title=Multiple Plan
Program Version=5.07
Short Identifier=Multiple Plan
Geom File=g01
Flow File=f01
Subcritical Flow
K Sum by GR= 0
Std Step Tol= 0.01
Critical Tol= 0.01
Num of Std Step Trials= 20
Max Error Tol= 0.3
Flow Tol Ratio= 0.001
Split Flow NTrial= 30
Split Flow Tol= 0.02
Split Flow Ratio= 0.02
Log Output Level= 0
Friction Slope Method= 1
Unsteady Friction Slope Method= 2
Unsteady Bridges Friction Slope Method= 1
Parabolic Critical Depth
Global Vel Dist= 1 , 1 , 1
Global Log Level= 0
CheckData=True
Encroach Param=-1 ,0,0, 0
BEGIN DESCRIPTION:
Multiple Run
END DESCRIPTION:
Computation Interval=1MIN
Output Interval=1HOUR
Instantaneous Interval=1HOUR
Mapping Interval=1HOUR
Computation Time Step Use Courant=        0
Computation Time Step Use Time Series=    0
Computation Time Step Count To Double=0
Computation Time Step Max Doubling=0
Computation Time Step Max Halving=0
Computation Time Step Residence Courant=0
Run HTab= 0
Run UNet= 0
Run Sediment= 0
Run PostProcess= 0
Run WQNet= 0
Run RASMapper= 0
UNET Theta= 1
UNET Theta Warmup= 1
UNET ZTol= 0.02
UNET ZSATol= 0.02
UNET MxIter= 20
UNET Max Iter WO Improvement= 0
UNET MaxInSteps= 0
UNET DtIC= 0
UNET DtMin= 0
UNET MaxCRTS= 20
UNET WFStab= 2
UNET SFStab= 1
UNET WFX= 1
UNET SFX= 1
UNET 1D Methodology=Finite Difference
UNET DSS MLevel= 4
UNET Pardiso=0
UNET DZMax Abort= 100
UNET Use Existing IB Tables=-1
UNET Froude Reduction=False
UNET Froude Limit= 0.8
UNET Froude Power= 4
UNET D1 Cores= 0
UNET D2 Coriolis=0
UNET D2 Cores= 0
UNET D2 Theta= 1
UNET D2 Theta Warmup= 1
UNET D2 Z Tol= 0.01
UNET D2 Volume Tol= 0.01
UNET D2 Max Iterations= 20
UNET D2 Equation= 0
UNET D2 RampUpFraction=0.1
UNET D2 TimeSlices= 1
UNET D2 BCVolumeCheck=0
UNET D1D2 MaxIter= 0
UNET D1D2 ZTol=0.01
UNET D1D2 QTol=0.1
UNET D1D2 MinQTol=1
DSS File=dss
Write IC File= 0
Write IC File at Fixed DateTime=0
Write IC File at Sim End=0
Echo Input=False
Echo Parameters=False
Echo Output=False
Write Detailed= 0
HDF Write Warmup=0
HDF Write Time Slices=0
HDF Flush=0
HDF Face Node Velocities=0
HDF Compression= 1
HDF Chunk Size= 1
HDF Spatial Parts= 1
HDF Use Max Rows=0
HDF Fixed Rows= 1
Calibration Method= 0
Calibration Iterations= 20
Calibration Max Change=0.05
Calibration Tolerance=0.2
Calibration Maximum=1.5
Calibration Minimum=0.5
Calibration Optimization Method= 1
WQ AD Non Conservative
WQ ULTIMATE=-1
WQ Max Comp Step=1HOUR
WQ Output Interval=15MIN
WQ Output Selected Increments= 0
WQ Output face flow=0
WQ Output face velocity=0
WQ Output face area=0
WQ Output face dispersion=0
WQ Output cell volume=0
WQ Output cell surface area=0
WQ Output cell continuity=0
WQ Output cumulative cell continuity=0
WQ Output face conc=0
WQ Output face dconc_dx=0
WQ Output face courant=0
WQ Output face peclet=0
WQ Output face adv mass=0
WQ Output face disp mass=0
WQ Output cell mass=0
WQ Output cell source sink temp=0
WQ Output nsm pathways=0
WQ Output nsm derived pathways=0
WQ Output MaxMinRange=-1
WQ Daily Max Min Mean=-1
WQ Daily Range=0
WQ Daily Time=0
WQ Create Restart=0
WQ Fixed Restart=0
WQ System Summary=0
WQ Write To DSS=0
WQ Use Fixed Temperature=0
Sorting and Armoring Iterations= 10
XS Update Threshold= 0.02
Bed Roughness Predictor= 0
Hydraulics Update Threshold= 0.02
Energy Slope Method= 1
Volume Change Method= 1
Sediment Retention Method= 0
XS Weighting Method= 0
Number of US Weighted Cross Sections= 1
Number of DS Weighted Cross Sections= 1
Upstream XS Weight=0
Main XS Weight=1
Downstream XS Weight=0
Number of DS XS's Weighted with US Boundary= 1
Upstream Boundary Weight= 1
Weight of XSs Associated with US Boundary= 0
Number of US XS's Weighted with DS Boundary= 1
Downstream Boundary Weight= 0.5
Weight of XSs Associated with DS Boundary= 0.5
Percentile Method= 0
Sediment Output Level= 3
Mass or Volume Output= 0
Output Increment Type= 1
Profile and TS Output Increment= 1
XS Output Flag= 0
XS Output Increment= 10
Write Gradation File= 0
Read Gradation Hotstart= 0
Write HDF5 File= 1
Write Binary Output= 1
Write DSS Sediment File= 0
SV Curve= 0
Specific Gage Flag= 0

--- Black Creek.f01 (steady flow) ---

Flow Title=Multiple
Program Version=5.05
Number of Profiles= 7
Profile Names=10-year,25-year,50-year,1pct_min,100-year,1pct_plu,500-year
River Rch & RM=Black Creek,Reach-1         ,220601
     491     675     825     499     996    1988    1457
River Rch & RM=Black Creek,Reach-1         ,218938
     751    1059    1315     808    1612    3216    2430
River Rch & RM=Black Creek,Reach-1         ,215309
     989    1413    1771    1096    2187    4364    3350
River Rch & RM=Black Creek,Reach-1         ,209097
    1087    1561    1963    1219    2432    4852    3748
River Rch & RM=Black Creek,Reach-1         ,206605
    1219    1760    2221    1384    2761    5509    4284
River Rch & RM=Black Creek,Reach-1         ,203188
    1929    2840    3632    2288    4566    9110    7248
River Rch & RM=Black Creek,Reach-1         ,196560
    2047    3020    3867    2440    4868    9713    7746
River Rch & RM=Black Creek,Reach-1         ,195989
    2354    3491    4486    2839    5664   11300    9067
River Rch & RM=Black Creek,Reach-1         ,185872
    2394    3546    4553    2879    5744   11460    9180
River Rch & RM=Black Creek,Reach-1         ,182454
    2590    3852    4961    3145    6275   12520   10083
River Rch & RM=Black Creek,Reach-1         ,180161
    2659    3953    5088    3223    6430   12829   10316
River Rch & RM=Black Creek,Reach-1         ,175419
    2861    4267    5504    3493    6970   13907   11229
River Rch & RM=Black Creek,Reach-1         ,171121
    4367    6601    8593    5498   10969   21886   17948
River Rch & RM=Black Creek,Reach-1         ,169073
    4367    6601    8593    5498   10969   21886   17948
River Rch & RM=Black Creek,Reach-1         ,161260
    4367    6601    8593    5498   10969   21886   17948
River Rch & RM=Black Creek,Reach-1         ,159686
    4367    6601    8593    5498   10969   21886   17948
River Rch & RM=Black Creek,Reach-1         ,151262
    4367    6601    8593    5498   10969   21886   17948
River Rch & RM=Black Creek,Reach-1         ,145664
    4467    6750    8786    5619   11212   22370   18334
River Rch & RM=Black Creek,Reach-1         ,142105
    4564    6898    8981    5745   11464   22873   18754
River Rch & RM=Black Creek,Reach-1         ,139488
    4739    7171    9342    5979   11930   23804   19538
River Rch & RM=Black Creek,Reach-1         ,134083
    5409    8217   10733    6885   13738   27410   22593
River Rch & RM=Black Creek,Reach-1         ,132832
    5409    8217   10733    6885   13738   27410   22593
River Rch & RM=Black Creek,Reach-1         ,129709
    5515    8377   10941    7018   14002   27939   23024
River Rch & RM=Black Creek,Reach-1         ,128535
    5515    8377   10941    7018   14002   27939   23024
River Rch & RM=Black Creek,Reach-1         ,123956
    5550    8425   11000    7052   14070   28074   23112
River Rch & RM=Black Creek,Reach-1         ,117346
    5605    8505   11100    7113   14193   28319   23298
River Rch & RM=Black Creek,Reach-1         ,110146
    5953    9050   11826    7587   15138   30204   24902
River Rch & RM=Black Creek,Reach-1         ,108978
    5953    9050   11826    7587   15138   30204   24902
River Rch & RM=Black Creek,Reach-1         ,107706
    6025    9159   11969    7679   15322   30571   25206
River Rch & RM=Black Creek,Reach-1         ,103858
    6064    9216   12042    7724   15412   30750   25344
River Rch & RM=Black Creek,Reach-1         ,100659
    6134    9325   12187    7818   15600   31126   25661
River Rch & RM=Black Creek,Reach-1         ,95677
    6130    9316   12173    7808   15579   31084   25617
River Rch & RM=Black Creek,Reach-1         ,94139
    6986   10650   13943    8958   17873   35661   29474
River Rch & RM=Black Creek,Reach-1         ,90453
    7642   11675   15309    9848   19649   39206   32490
River Rch & RM=Black Creek,Reach-1         ,80482
    7642   11675   15309    9848   19649   39206   32490
River Rch & RM=Black Creek,Reach-1         ,74433
    7642   11675   15309    9848   19649   39206   32490
River Rch & RM=Black Creek,Reach-1         ,70286
    7560   11545   15134    9735   19425   38758   32122
River Rch & RM=Black Creek,Reach-1         ,68046
    7285   11099   14536    9353   18662   37235   30929
River Rch & RM=Black Creek,Reach-1         ,65587
    7285   11099   14536    9353   18662   37235   30929
River Rch & RM=Black Creek,Reach-1         ,56661
    7285   11099   14536    9353   18662   37235   30929
River Rch & RM=Black Creek,Reach-1         ,45499
    7285   11099   14536    9353   18662   37235   30929
River Rch & RM=Black Creek,Reach-1         ,42779
    6845   10400   13600    8747   17453   34823   28941
River Rch & RM=Black Creek,Reach-1         ,38978
    6831   10377   13568    8726   17410   34737   28865
River Rch & RM=Black Creek,Reach-1         ,35100
    6765   10265   13412    8620   17199   34318   28483
River Rch & RM=Black Creek,Reach-1         ,30185
    6732   10209   13334    8568   17094   34108   28294
River Rch & RM=Black Creek,Reach-1         ,28439
    6732   10209   13334    8568   17094   34108   28294
River Rch & RM=Black Creek,Reach-1         ,18600
    6382    9653   12593    8096   16154   32232   26827
River Rch & RM=Black Creek,Reach-1         ,11987
    6382    9650   12588    8092   16145   32214   26809
River Rch & RM=Black Creek,Reach-1         ,9113
    6382    9650   12588    8092   16145   32214   26809
Boundary for River Rch & Prof#=Black Creek,Reach-1         , 1
Up Type= 0
Dn Type= 3
Dn Slope=0.00063
Boundary for River Rch & Prof#=Black Creek,Reach-1         , 2
Up Type= 0
Dn Type= 3
Dn Slope=0.00063
Boundary for River Rch & Prof#=Black Creek,Reach-1         , 3
Up Type= 0
Dn Type= 3
Dn Slope=0.00063
Boundary for River Rch & Prof#=Black Creek,Reach-1         , 4
Up Type= 0
Dn Type= 3
Dn Slope=0.00063
Boundary for River Rch & Prof#=Black Creek,Reach-1         , 5
Up Type= 0
Dn Type= 3
Dn Slope=0.00063
Boundary for River Rch & Prof#=Black Creek,Reach-1         , 6
Up Type= 0
Dn Type= 3
Dn Slope=0.00063
Boundary for River Rch & Prof#=Black Creek,Reach-1         , 7
Up Type= 0
Dn Type= 3
Dn Slope=0.00063
DSS Import GetInterval= 0
DSS Import GetPeak= 0
DSS Import FillOption= 0

--- Black Creek.g01 (geometry) ---

Geom Title=Black Creek
Program Version=5.07

River Reach=Black Creek     ,Reach-1
Reach XY= 30
      1973207.44     13648188.72      1972716.72     13640794.44
       1973850.8     13639144.54       1971240.8     13634744.54
       1973160.8     13631134.54       1972270.8     13620474.54
       1973960.8     13618104.54       1972130.8     13610584.54
      1973641.56     13605892.76       1975400.8     13604814.54
       1975130.8     13596894.54       1973330.8     13595384.54
       1974960.8     13591424.54       1973240.8     13588904.54
       1972680.8     13582504.54       1974930.8     13580864.54
       1976700.8     13581354.54        1976451.     13575932.44
       1977910.8     13574074.54       1974400.8     13565754.54
       1973610.8     13556014.54       1975520.8     13552724.54
       1972380.8     13548114.54       1972370.8     13543674.54
       1977030.8     13536094.54       1978000.8     13528464.54
      1981462.13     13525979.05       1984230.8     13520464.54
       1985600.8     13510784.54      1995135.29     13499801.48

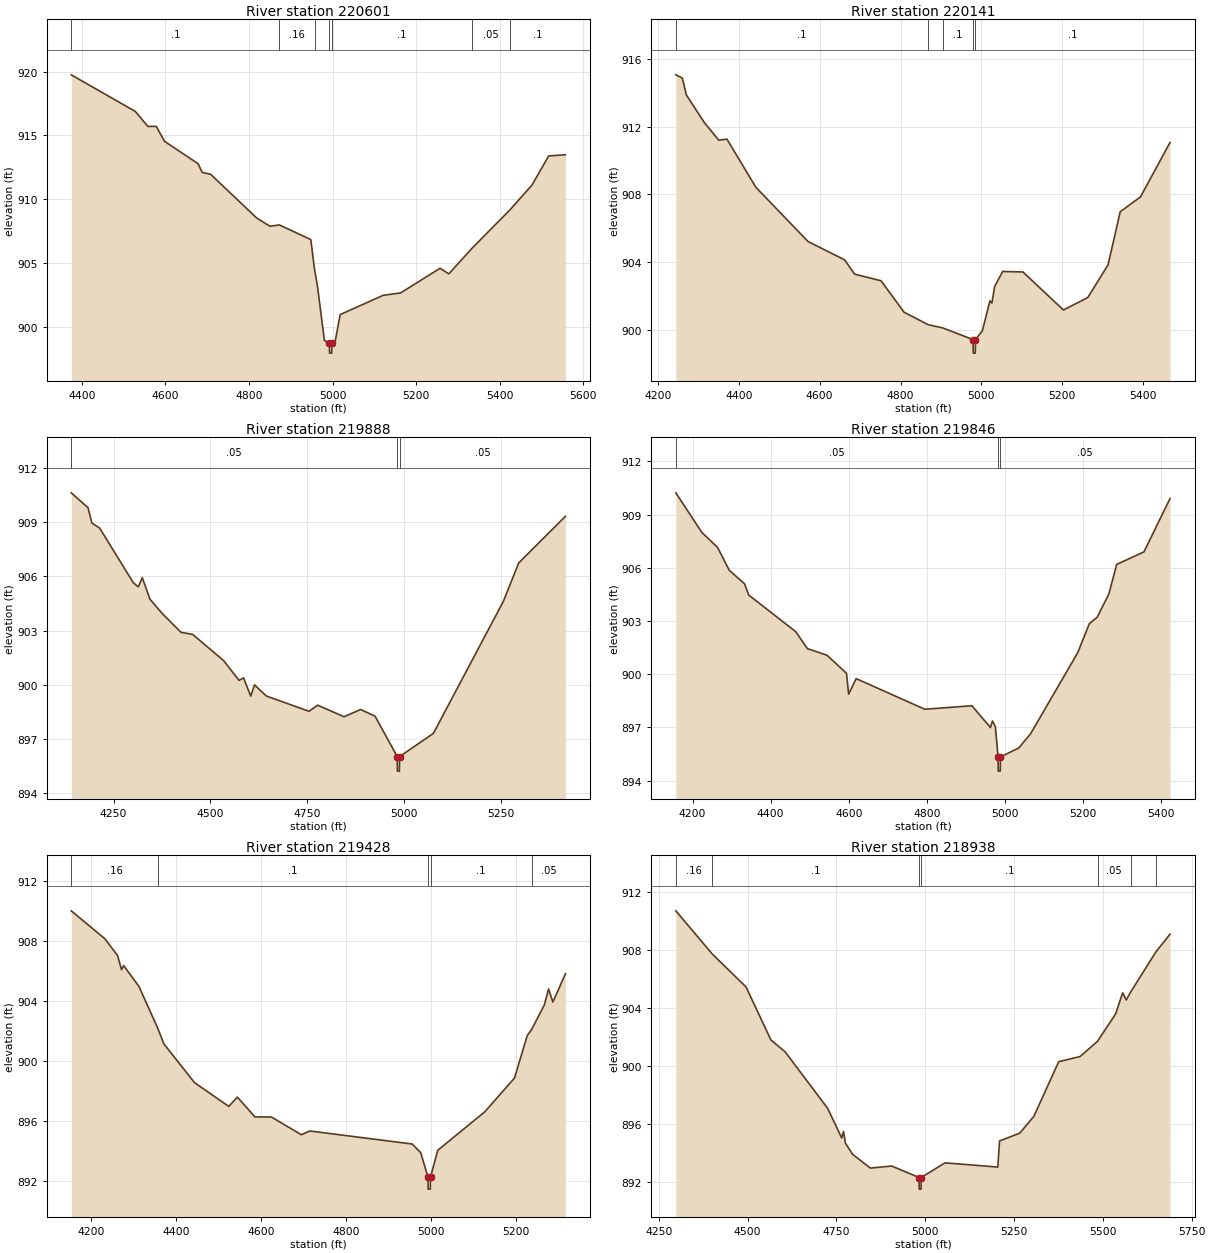
Type RM Length L Ch R = 1 ,220601  ,460,460,460
BEGIN DESCRIPTION:
Mapping XS 6efbf12d
END DESCRIPTION:
XS GIS Cut Line= 3
      1973748.28     13647969.54       1973289.9     13647966.07
       1972598.6     13648180.91
#Sta/Elev= 30
  4374.9  919.75  4528.2  916.88  4558.2  915.71  4578.2  915.71  4598.2  914.54
  4678.2  912.79  4688.2   912.1  4708.2  911.96  4818.2  908.54  4850.3  907.88
  4872.7  907.99    4948  906.84    4957   904.5  4964.1  903.16  4980.6  898.92
  4992.5  898.74    4993  897.94    4998  897.94  4998.5  898.74    5006  898.81
  5018.3  900.96  5121.2  902.47    5163  902.66  5257.3  904.59  5278.2  904.15
  5333.2  906.14  5424.5  909.17  5477.2  911.11  5517.1  913.39  5557.2  913.49
#Mann= 7 ,-1 , 0
  4374.9      .1       0  4872.7     .16       0    4957      .1       0
  4992.5     .07       0  4998.5      .1       0  5333.2     .05       0
  5424.5      .1       0
Bank Sta=4992.5,4998.5
XS Rating Curve= 0 ,0
Exp/Cntr=0.3,0.1

Type RM Length L Ch R = 1 ,220141  ,253,253,253
BEGIN DESCRIPTION:
Black Creek 240.0
END DESCRIPTION:
XS GIS Cut Line= 3
      1973710.92     13647695.67      1973110.22     13647647.06
      1972492.13      13647692.2
#Sta/Elev= 30
  4244.2  915.07  4260.2  914.88  4270.2  913.88  4314.9  912.24  4350.5   911.2
  4370.5  911.27  4442.1  908.42  4571.2  905.21  4661.5  904.13  4686.5  903.28
  4751.8  902.89  4808.7  901.03  4868.7  900.29  4904.5   900.1  4979.4  899.41
  4979.9  898.61  4984.9  898.61  4985.4  899.41  5002.5  899.94  5021.1   901.7
  5026.1  901.57  5032.6  902.54  5052.6  903.44  5102.8  903.41    5203  901.16
  5263.2   901.9  5313.3  903.83  5343.4  906.97  5393.5  907.85  5466.6  911.07
#Mann= 5 ,-1 , 0
  4244.2      .1       0  4868.7     .16       0  4904.5      .1       0
  4979.4     .07       0  4985.4      .1       0
Bank Sta=4979.4,4985.4
XS Rating Curve= 0 ,0
Exp/Cntr=0.3,0.1

Type RM Length L Ch R = 1 ,219888  ,42,42,42
BEGIN DESCRIPTION:
Mapping XS c5d4dc9e
END DESCRIPTION:
XS GIS Cut Line= 4
       1973738.3     13647423.97      1973293.38     13647413.12
      1972713.95      13647465.2      1972464.38     13647467.37
#Sta/Elev= 30
  4140.7  910.62    4184   909.8    4194  908.95    4214  908.67  4301.2  905.64
  4314.1  905.42  4324.1  905.93  4344.1  904.73  4374.1  903.98  4424.1   902.9
  4454.1  902.79  4534.1  901.34  4574.1  900.24  4585.8  900.38  4604.2  899.37
  4614.2  899.99  4644.4  899.38  4754.8  898.53  4777.1  898.87  4845.2  898.23
  4888.2  898.63  4925.5  898.26  4982.7  896.02  4983.2  895.22  4988.2  895.22
  4988.7  896.02  5076.1  897.31  5256.5   904.6  5296.5  906.74  5417.1  909.32
#Mann= 3 ,-1 , 0
  4140.7     .05       0  4982.7     .04       0  4988.7     .05       0
Bank Sta=4982.7,4988.7
XS Rating Curve= 0 ,0
Exp/Cntr=0.3,0.1

Type RM Length L Ch R = 1 ,219846  ,418,418,418
BEGIN DESCRIPTION:
Mapping XS 128b270e
END DESCRIPTION:
XS GIS Cut Line= 4
      1973731.77     13647397.93      1973289.04     13647378.39
      1972713.95     13647428.31       1972468.3       13647424.
#Sta/Elev= 30
  4157.1  910.23  4223.9  907.99    4264  907.15    4294  905.86    4333   905.1
  4344.1  904.46  4464.2   902.4  4494.2  901.44  4544.2  901.07  4594.3  900.05
  4599.8  898.87  4619.1  899.75    4795  898.02  4915.5  898.22  4963.2  896.99
  4968.2  897.36  4975.7  897.04  4982.7  895.33  4983.2  894.53  4988.2  894.53
  4988.7  895.33  5035.9  895.84    5066  896.64  5186.5   901.2  5216.5  902.85
  5236.5  903.21  5266.5  904.52  5286.5  906.19  5356.5   906.9  5423.2  909.91
#Mann= 3 ,-1 , 0
  4157.1     .05       0  4982.7     .04       0  4988.7     .05       0
Bank Sta=4982.7,4988.7
XS Rating Curve= 0 ,0
Exp/Cntr=0.3,0.1

Type RM Length L Ch R = 1 ,219428  ,490,490,490
BEGIN DESCRIPTION:
Black Creek 239.0
END DESCRIPTION:
XS GIS Cut Line= 3
      1973713.52     13647082.39      1973317.25     13647042.02
      1972555.52     13646990.37
#Sta/Elev= 30
  4154.2     910  4233.1  908.14  4263.3  907.01  4272.4  906.07  4277.4  906.35
  4313.5  904.95  4357.2  902.19    4372  901.12  4444.2  898.53  4524.6  896.95
  4544.7  897.57  4586.1  896.25  4624.9  896.24  4695.1  895.06  4715.1  895.31
  4955.7  894.44  4975.7  893.87  4992.8  892.23  4993.3  891.43  4998.3  891.43
  4998.8  892.23  5015.8  894.02  5126.1  896.58  5196.2  898.84  5226.3  901.68
  5236.7  902.09  5266.4  903.72  5276.4  904.79  5286.5  903.91    5316   905.8
#Mann= 5 ,-1 , 0
  4154.2     .16       0  4357.2      .1       0  4992.8     .07       0
  4998.8      .1       0  5236.7     .05       0
Bank Sta=4992.8,4998.8
XS Rating Curve= 0 ,0
Exp/Cntr=0.3,0.1

Type RM Length L Ch R = 1 ,218938  ,51,51,51
BEGIN DESCRIPTION:
Mapping XS e0f0b007
END DESCRIPTION:
XS GIS Cut Line= 4
      1973832.46     13646728.23      1973491.27     13646723.02
      1973043.36     13646712.61      1972441.76     13646699.58
#Sta/Elev= 30
  4298.1  910.68  4400.4  907.71  4495.6  905.44  4565.6  901.79  4605.6  900.97
  4725.6  897.07    4765  895.03    4770  895.48  4775.6  894.67  4795.6  893.91
  4845.7  892.96  4905.7   893.1  4982.7  892.31  4983.2  891.51  4988.2  891.51
  4988.7  892.31  5055.7  893.32  5204.3  893.03  5209.3  894.83  5265.8  895.36
  5305.8  896.52  5375.8  900.29  5435.8  900.64  5485.2   901.7  5535.8  903.57
  5555.8  905.03  5565.8  904.54  5579.2  905.12  5649.3  907.85  5689.1  909.07
#Mann= 7 ,-1 , 0
  4298.1     .16       0  4400.4      .1       0  4982.7     .07       0
  4988.7      .1       0  5485.2     .05       0  5579.2      .1       0
  5649.3     .05       0
Bank Sta=4982.7,4988.7
XS Rating Curve= 0 ,0
Exp/Cntr=0.3,0.1

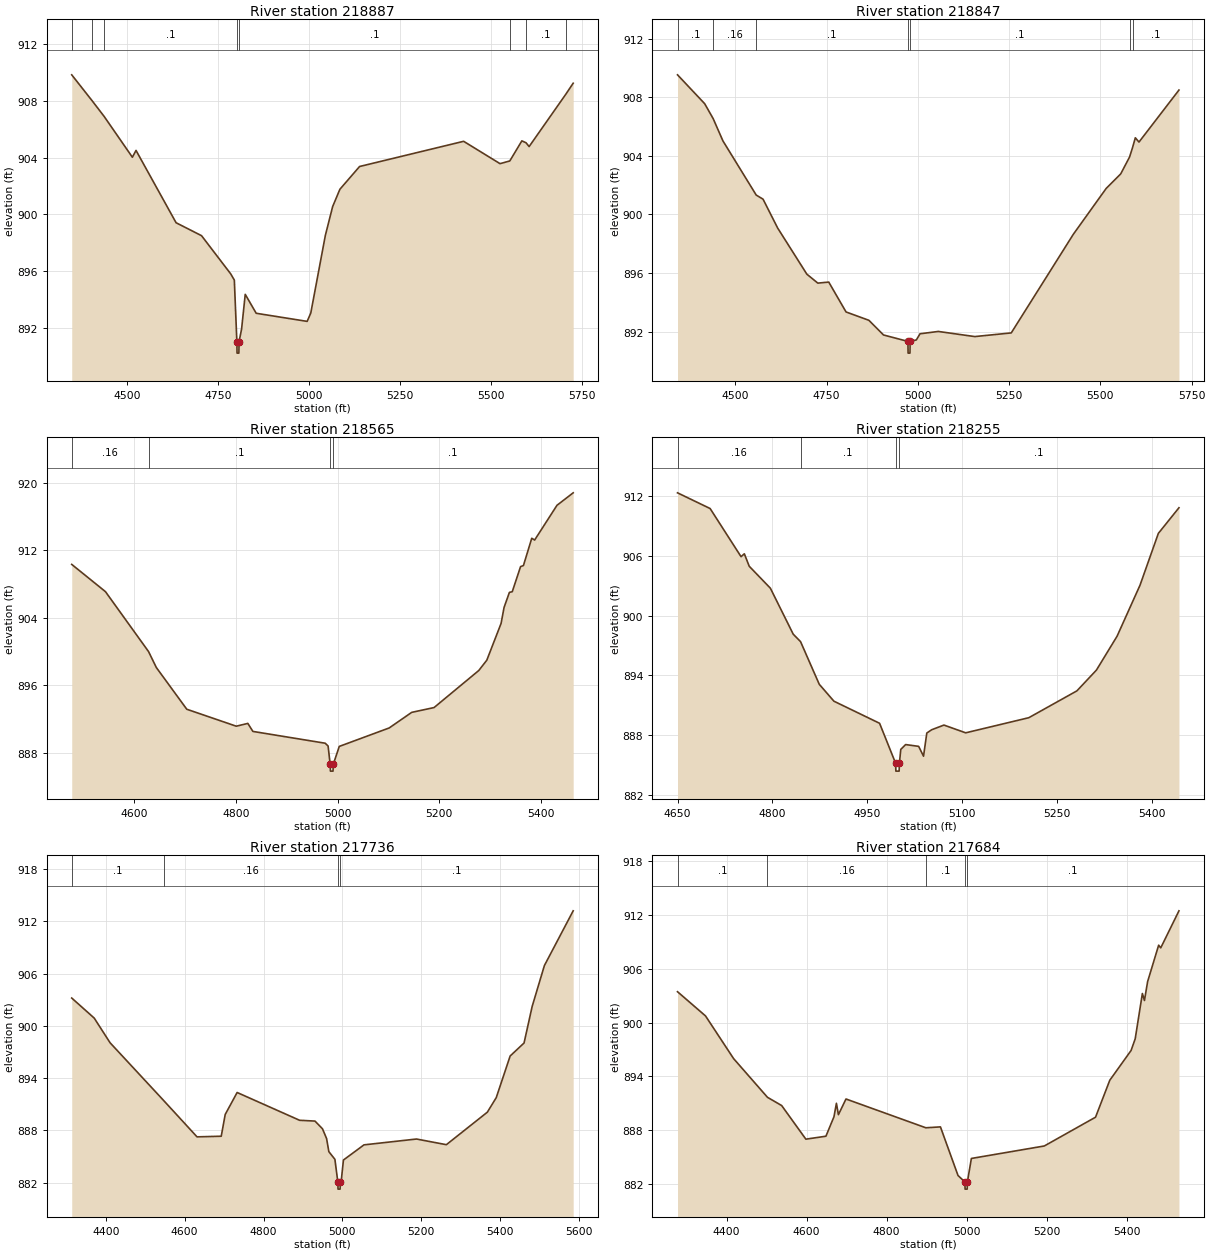
Type RM Length L Ch R = 1 ,218887  ,40,40,40
BEGIN DESCRIPTION:
Mapping XS e8bd99a7
END DESCRIPTION:
XS GIS Cut Line= 3
       1973811.6     13646699.59      1972907.94     13646665.73
      1972433.94     13646663.13
#Sta/Elev= 30
  4348.1  909.81  4403.8     908  4437.1  906.89  4514.8  904.02  4524.8   904.5
  4634.9  899.42  4704.9  898.51    4785  895.83    4795  895.39    4802  891.06
  4802.5  890.26  4807.5  890.26    4808  891.06    4815  891.96    4825  894.39
  4855.1  893.06  4995.2  892.49  5005.2  893.08  5045.2  898.53  5065.2  900.55
  5085.2  901.77  5139.3  903.37  5425.3  905.14  5525.3  903.57  5552.2  903.76
  5585.3  905.17  5596.7  905.04  5605.3  904.77  5705.7  908.43  5726.4  909.22
#Mann= 8 ,-1 , 0
  4348.1      .1       0  4403.8     .16       0  4437.1      .1       0
    4802     .07       0    4808      .1       0  5552.2     .05       0
  5596.7      .1       0  5705.7     .05       0
Bank Sta=4802,4808
XS Rating Curve= 0 ,0
Exp/Cntr=0.3,0.1

Type RM Length L Ch R = 1 ,218847  ,282,282,282
BEGIN DESCRIPTION:
Black Creek 238.0
END DESCRIPTION:
XS GIS Cut Line= 3
       1973819.4     13646637.08      1973355.22     13646635.65
       1972445.5     13646634.78
#Sta/Elev= 30
  4341.4  909.53  4415.8  907.56  4439.1  906.54  4465.8  905.02  4557.1  901.32
  4575.8  901.04  4615.8  899.07  4695.8  895.92  4725.8  895.31  4755.8  895.38
  4803.2  893.34  4865.8  892.77  4905.8  891.77  4972.7  891.33  4973.2  890.53
  4978.3  890.53  4978.8  891.33  4995.8  891.43  5005.8  891.85  5055.8  892.01
  5155.8  891.66  5255.8  891.91  5425.8  898.64  5515.8  901.77  5555.8  902.77
    5580  903.92  5588.1  904.56  5595.8  905.23  5605.8  904.94  5715.3  908.49
#Mann= 7 ,-1 , 0
  4341.4      .1       0  4439.1     .16       0  4557.1      .1       0
  4972.7     .07       0  4978.8      .1       0    5580     .05       0
  5588.1      .1       0
Bank Sta=4972.7,4978.8
XS Rating Curve= 0 ,0
Exp/Cntr=0.3,0.1

Type RM Length L Ch R = 1 ,218565  ,310,310,310
BEGIN DESCRIPTION:
Mapping XS 661f908f
END DESCRIPTION:
XS GIS Cut Line= 3
      1973681.37     13646475.63      1973301.17      13646457.4
      1972764.68     13646173.53
#Sta/Elev= 30
  4476.4  910.33  4542.8   907.1  4627.7  899.99    4643   898.1    4703  893.15
  4800.4  891.14  4823.2  891.47  4833.2  890.52  4975.6  889.12  4981.3  888.79
  4985.4  886.61  4985.9  885.81    4991  885.81  4991.5  886.61  5003.3  888.74
  5101.6  890.93    5146  892.78    5190  893.35    5278  897.74  5293.9  898.97
    5322  903.33  5327.9  905.23  5338.4  907.01    5344  907.09  5360.4  910.07
    5366  910.19  5382.4  913.43  5388.1  913.22  5432.1  917.34    5464  918.82
#Mann= 4 ,-1 , 0
  4476.4     .16       0  4627.7      .1       0  4985.4     .07       0
  4991.5      .1       0
Bank Sta=4985.4,4991.5
XS Rating Curve= 0 ,0
Exp/Cntr=0.3,0.1

Type RM Length L Ch R = 1 ,218255  ,519,519,519
BEGIN DESCRIPTION:
Black Creek 237.0
END DESCRIPTION:
XS GIS Cut Line= 3
      1973725.01       13646325.        1973325.       13646225.
      1972975.01       13646075.
#Sta/Elev= 30
  4649.8  912.34  4701.4  910.76  4750.3  905.92  4755.5  906.21  4763.2  904.96
  4796.7  902.75  4832.8  898.13  4844.4  897.38    4874  893.09  4897.2  891.39
  4969.4  889.17  4994.7  885.16  4995.2  884.36  5000.3  884.36  5000.8  885.16
  5002.9  886.54  5010.6  887.03  5031.2  886.85  5038.9  885.86  5044.1  888.19
  5051.8  888.52  5071.2  888.99  5105.6  888.21  5205.4  889.73  5281.5  892.43
  5312.4  894.52    5345  897.92  5381.3  903.05  5410.3  908.26  5442.9  910.84
#Mann= 4 ,-1 , 0
  4649.8     .16       0  4844.4      .1       0  4994.7     .07       0
  5000.8      .1       0
Bank Sta=4994.7,5000.8
XS Rating Curve= 0 ,0
Exp/Cntr=0.3,0.1

Type RM Length L Ch R = 1 ,217736  ,52,52,52
BEGIN DESCRIPTION:
Black Creek 236.0
END DESCRIPTION:
XS GIS Cut Line= 4
      1974081.57     13645672.66       1973472.2     13645743.84
      1973395.81     13645974.75      1972994.41     13645869.85
#Sta/Elev= 30
  4313.6  903.19  4370.6  900.89  4410.8  898.06  4547.1  891.41  4631.3  887.26
  4692.7  887.33  4702.8  889.83    4733  892.35  4891.5  889.16  4930.4  889.07
  4949.4  888.19  4959.9  887.06  4965.6  885.56    4981  884.68  4988.4  882.06
  4988.9  881.26  4994.1  881.26  4994.6  882.06  4997.3  882.33  5002.6   884.6
  5054.7  886.34  5187.9  887.01  5263.6  886.36  5367.5  890.09  5390.1  891.76
  5425.4  896.54  5460.6  898.03  5481.2  902.23  5512.2  906.92  5585.2   913.2
#Mann= 4 ,-1 , 0
  4313.6      .1       0  4547.1     .16       0  4988.4     .07       0
  4994.6      .1       0
Bank Sta=4988.4,4994.6
XS Rating Curve= 0 ,0
Exp/Cntr=0.3,0.1

Type RM Length L Ch R = 1 ,217684  ,198,198,198
BEGIN DESCRIPTION:
Mapping XS e00b7afa
END DESCRIPTION:
XS GIS Cut Line= 4
      1974074.76     13645650.09      1973435.39     13645698.27
      1973367.68     13645930.04      1973009.19     13645837.82
#Sta/Elev= 30
  4277.5  903.45  4347.5  900.75  4417.7  895.99  4502.2  891.68  4537.7  890.76
  4598.2  887.01  4648.3  887.34  4668.4  889.51  4674.5  891.01  4679.5  889.74
  4698.4  891.49  4897.9  888.28  4934.4  888.38  4978.3  882.96  4995.5  882.24
    4996  881.44  5001.2  881.44  5001.7  882.24  5011.7  884.86  5193.9  886.25
  5321.9  889.46  5357.5  893.58  5410.7   896.9    5421   898.2  5438.9  903.25
  5444.1  902.47    5452  904.58  5479.6  908.64  5484.8  908.34  5530.3  912.47
#Mann= 5 ,-1 , 0
  4277.5      .1       0  4502.2     .16       0  4897.9      .1       0
  4995.5     .07       0  5001.7      .1       0
Bank Sta=4995.5,5001.7
XS Rating Curve= 0 ,0
Exp/Cntr=0.3,0.1

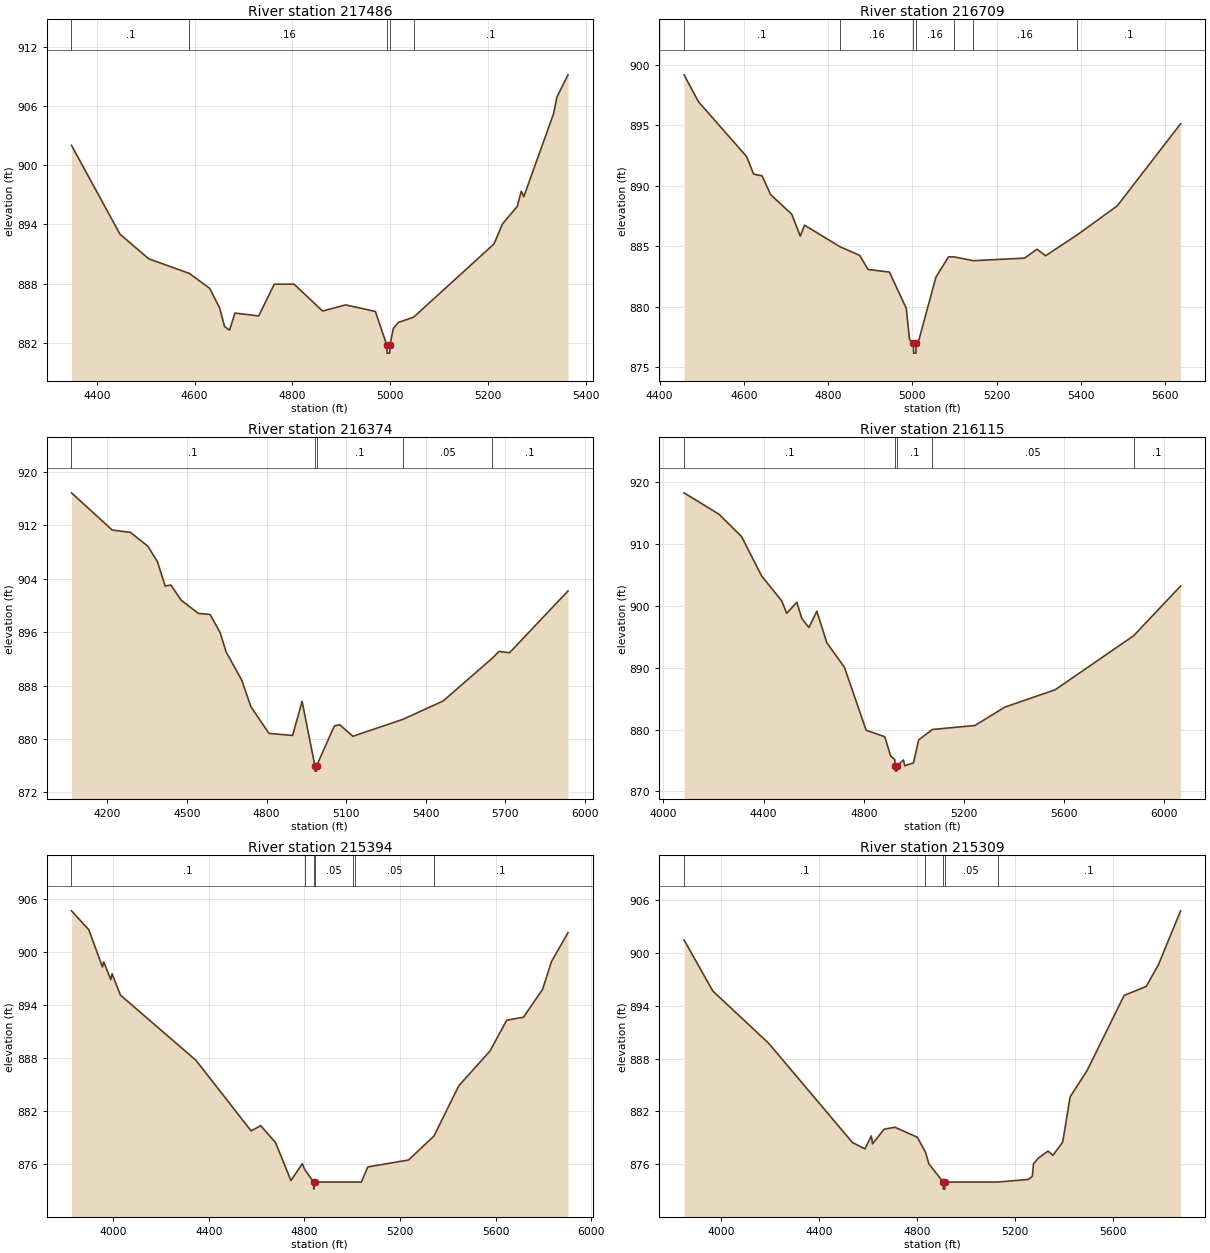
Type RM Length L Ch R = 1 ,217486  ,777,777,777
BEGIN DESCRIPTION:
Black Creek 235.0
END DESCRIPTION:
XS GIS Cut Line= 3
      1973983.09     13645501.66      1973475.32      13645592.8
      1972982.66     13645675.27
#Sta/Elev= 30
  4348.4  902.01  4447.6     893  4506.4   890.5  4589.2  889.03  4630.9  887.51
  4651.3  885.54  4661.4  883.65  4671.6  883.27  4682.7     885  4731.3  884.71
    4763  887.93  4803.7  887.93  4861.9  885.21  4909.1  885.83  4969.8  885.17
  4993.3  881.74  4993.8  880.94    4999  880.94  4999.5  881.74  5006.6  883.44
  5016.7  884.05  5047.9  884.58  5212.6  892.02  5229.6  894.03    5260  895.82
  5268.2  897.36  5273.3  896.79    5334  905.18  5341.2  906.92  5363.8  909.16
#Mann= 5 ,-1 , 0
  4348.4      .1       0  4589.2     .16       0  4993.3     .07       0
  4999.5     .16       0  5047.9      .1       0
Bank Sta=4993.3,4999.5
XS Rating Curve= 0 ,0
Exp/Cntr=0.3,0.1

Type RM Length L Ch R = 1 ,216709  ,335,335,335
BEGIN DESCRIPTION:
Black Creek 234.0
END DESCRIPTION:
XS GIS Cut Line= 3
      1974059.11     13645186.99        1973525.       13645125.
      1972885.01     13645087.16
#Sta/Elev= 30
  4458.1  899.19  4492.4  896.96  4606.8  892.42  4623.3  890.97  4643.4  890.83
  4663.6  889.28  4713.9  887.65    4734  885.84  4744.1  886.75  4828.5  884.96
    4875  884.25  4895.1  883.08  4945.5  882.87  4985.7  879.87  4993.3  877.29
  5002.6  876.96  5003.1  876.16  5008.6  876.16  5009.1  876.96  5015.8  877.27
  5055.9  882.43  5085.9  884.13  5098.2  884.13    5145  883.81  5266.3  884.02
  5296.3  884.76  5316.4  884.22  5391.3  885.94  5486.6  888.35  5636.9  895.14
#Mann= 7 ,-1 , 0
  4458.1      .1       0  4828.5     .16       0  5002.6     .07       0
  5009.1     .16       0  5098.2      .1       0    5145     .16       0
  5391.3      .1       0
Bank Sta=5002.6,5009.1
XS Rating Curve= 0 ,0
Exp/Cntr=0.3,0.1

Type RM Length L Ch R = 1 ,216374  ,259,259,259
BEGIN DESCRIPTION:
Black Creek 233.0
END DESCRIPTION:
XS GIS Cut Line= 3
       1974460.4     13645258.26      1973684.37     13644838.99
      1972694.83      13644784.3
#Sta/Elev= 30
  4064.3  916.84  4218.2  911.26  4286.4  910.93    4352  908.87  4388.7  906.52
  4417.7  902.89  4439.6  903.04  4477.7  900.78  4543.3  898.79  4587.1  898.64
  4625.2  895.91  4647.1  893.08  4706.9  888.78    4741  884.85  4809.2  880.84
  4898.3  880.53  4934.3  885.63  4982.5  875.99    4983  875.19  4988.5  875.19
    4989  875.99  5055.9  881.95  5075.9  882.14    5126  880.41  5314.5  882.94
  5466.5  885.69  5652.3  892.11  5676.8   893.1  5716.9  892.91  5937.4  902.16
#Mann= 5 ,-1 , 0
  4064.3      .1       0  4982.5     .07       0    4989      .1       0
  5314.5     .05       0  5652.3      .1       0
Bank Sta=4982.5,4989
XS Rating Curve= 0 ,0
Exp/Cntr=0.3,0.1

Type RM Length L Ch R = 1 ,216115  ,721,721,721
BEGIN DESCRIPTION:
Black Creek 232.0
END DESCRIPTION:
XS GIS Cut Line= 5
      1974603.66     13644615.03       1973895.3     13644664.51
      1973673.95     13644604.61      1973465.62     13644635.86
      1972634.92     13644677.53
#Sta/Elev= 30
  4082.9  918.24  4221.9   914.8  4312.1  911.19  4392.3  904.83  4472.5   900.8
  4492.6  898.77  4532.7  900.57  4552.7  897.96  4581.3  896.47  4612.8  899.12
  4652.9  894.01  4723.1  890.05  4809.5  879.89  4884.1  878.83  4907.3  875.75
  4923.9  875.15  4925.8  874.08  4926.3  873.28  4931.9  873.28  4932.4  874.08
  4958.6  875.08  4963.8  874.14  4998.5  874.61  5019.2  878.32  5074.2  880.01
  5243.6  880.65  5363.7  883.63    5564  886.42  5877.2  895.15  6064.7  903.18
#Mann= 5 ,-1 , 0
  4082.9      .1       0  4925.8     .07       0  4932.4      .1       0
  5074.2     .05       0  5877.2      .1       0
Bank Sta=4925.8,4932.4
XS Rating Curve= 0 ,0
Exp/Cntr=0.3,0.1

Type RM Length L Ch R = 1 ,215394  ,85,85,85
BEGIN DESCRIPTION:
Mapping XS 2b180b80
END DESCRIPTION:
XS GIS Cut Line= 6
        1974575.     13643656.69      1973791.14     13643865.03
      1973634.89      13643846.8      1973502.07     13644039.51
      1973093.22     13644065.55      1972628.53     13644070.74
#Sta/Elev= 30
  3825.6  904.65    3898  902.52  3955.1  898.31  3960.3  898.89  3990.1  896.88
  3995.3  897.54  4030.3  895.13  4346.4  887.76    4577  879.79  4617.1  880.38
  4679.1  878.47  4743.5  874.19  4791.4  876.08  4800.5  875.46  4838.5  874.01
    4839  873.21  4845.3  874.01    5003  874.01    5010  874.01  5038.1  874.01
  5065.3  875.72  5235.7   876.5    5342  879.22  5446.1   884.9  5576.1  888.81
  5646.1  892.29  5716.1  892.63  5796.1  895.77  5833.6  898.93  5902.6  902.19
#Mann= 7 ,-1 , 0
  3825.6      .1       0  4800.5     .05       0  4838.5    .033       0
  4845.3     .05       0    5003      .1       0    5010     .05       0
    5342      .1       0
Bank Sta=4838.5,4845.3
XS Rating Curve= 0 ,0
Exp/Cntr=0.3,0.1

Type RM Length L Ch R = 1 ,215309  ,612,612,612
BEGIN DESCRIPTION:
Black Creek 231.0
END DESCRIPTION:
XS GIS Cut Line= 6
      1974520.33     13643604.61      1973551.55     13643792.11
      1973522.91     13643893.68       1973455.2      13643971.8
      1973338.01      13643971.8      1972625.05       13644025.
#Sta/Elev= 30
  3848.2  901.42  3965.7  895.64  4193.6  889.73  4536.1  878.48    4587  877.77
  4612.9  879.24    4618  878.34  4664.7  879.99  4709.2  880.22  4800.9  879.08
  4833.9  877.41  4848.3  876.06  4906.5  874.01    4907  873.21  4912.8  873.21
  4913.3  874.01  5128.8  874.01  5254.3  874.31  5270.3  874.65  5275.3  876.07
  5294.4   876.7  5334.5  877.52  5354.6  877.04  5394.7  878.54  5424.8  883.65
    5495  886.68  5645.4  895.14  5735.7  896.16  5785.8  898.64    5876  904.72
#Mann= 5 ,-1 , 0
  3848.2      .1       0  4833.9     .05       0  4906.5    .033       0
  4913.3     .05       0  5128.8      .1       0
Bank Sta=4906.5,4913.3
XS Rating Curve= 0 ,0
Exp/Cntr=0.3,0.1

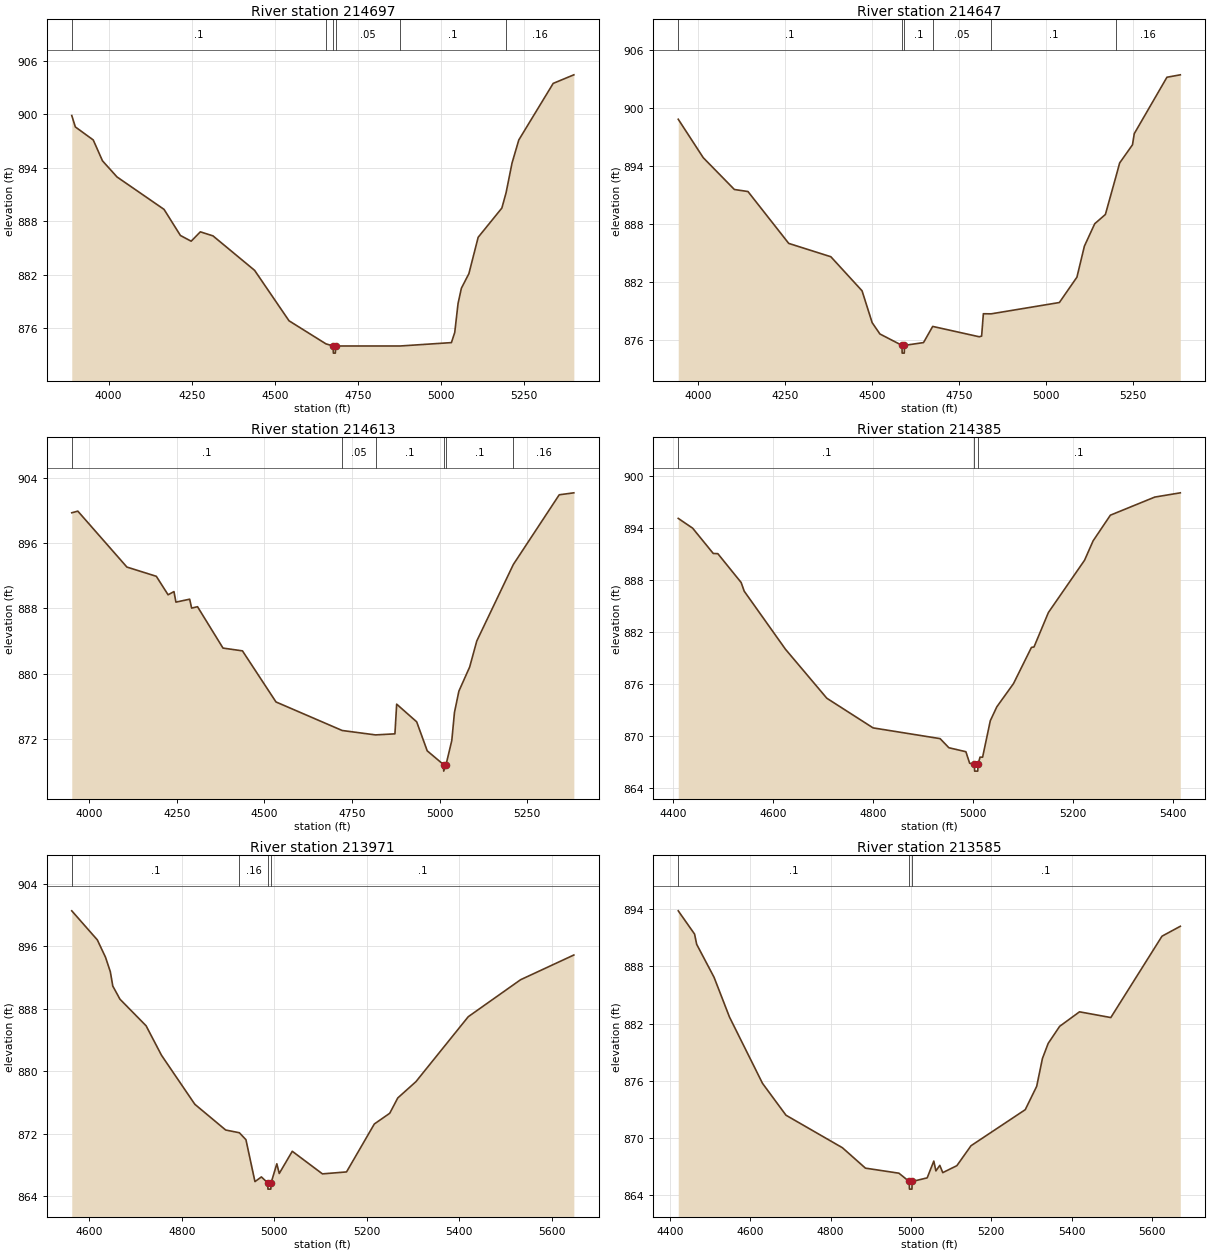
Type RM Length L Ch R = 1 ,214697  ,50,50,50
BEGIN DESCRIPTION:
Mapping XS 2f5a4afb
END DESCRIPTION:
XS GIS Cut Line= 6
      1973991.69     13643266.06      1973384.89      13643596.8
      1973298.95     13643609.82       1973080.2     13643612.43
      1972884.89     13643612.43      1972572.36     13643672.33
#Sta/Elev= 30
  3889.1  899.87  3899.9  898.59  3953.7  897.13  3981.5  894.79  4025.2  892.98
  4166.7  889.34    4216  886.41  4248.3  885.77  4275.8  886.82  4313.8  886.37
  4439.1   882.5  4542.6  876.84  4653.7  874.25  4675.4  874.01    4676  873.21
  4682.1  873.21  4682.6  874.01  4876.7  874.01  5031.1  874.39  5041.1  875.52
  5051.1  878.78  5061.1  880.49  5083.7  882.13  5111.6  886.21  5182.9  889.49
  5195.5   891.2  5213.4  894.53  5233.8  897.13  5337.3  903.48  5399.4  904.44
#Mann= 6 ,-1 , 0
  3889.1      .1       0  4653.7     .05       0  4675.4     .07       0
  4682.6     .05       0  4876.7      .1       0  5195.5     .16       0
Bank Sta=4675.4,4682.6
XS Rating Curve= 0 ,0
Exp/Cntr=0.3,0.1

Type RM Length L Ch R = 1 ,214647  ,34,34,34
BEGIN DESCRIPTION:
Black Creek 230.0
END DESCRIPTION:
XS GIS Cut Line= 5
      1973926.55     13643268.68      1973317.18     13643575.97
      1972983.84     13643565.55      1972869.26     13643573.36
      1972564.55     13643638.47
#Sta/Elev= 30
  3943.8  898.81  4015.8  894.83  4105.1  891.55  4144.1  891.34  4261.2  885.98
  4382.3   884.6  4471.9  881.08  4500.9  877.79  4523.2  876.62  4586.6  875.44
  4587.1  874.64  4593.2  874.64  4593.8  875.44  4648.5  875.73  4674.8   877.4
  4808.5  876.33  4815.4   876.4  4820.4  878.71  4842.7   878.7  5038.8  879.87
  5089.2  882.49  5110.6  885.69  5140.3  888.01    5171  888.97  5202.1  892.99
  5211.9  894.29  5248.8  896.17  5253.9  897.32  5347.8  903.15  5386.2   903.4
#Mann= 6 ,-1 , 0
  3943.8      .1       0  4586.6     .07       0  4593.8      .1       0
  4674.8     .05       0  4842.7      .1       0  5202.1     .16       0
Bank Sta=4586.6,4593.8
XS Rating Curve= 0 ,0
Exp/Cntr=0.3,0.1

Type RM Length L Ch R = 1 ,214613  ,228,228,228
BEGIN DESCRIPTION:
Mapping XS b399f054
END DESCRIPTION:
XS GIS Cut Line= 5
      1973910.96     13643240.02       1973330.2     13643529.09
      1973116.66     13643526.49      1972884.89     13643539.51
       1972554.2     13643609.81
#Sta/Elev= 30
  3950.5  899.69  3967.8  899.89  4107.8  893.05  4191.7  891.92  4225.3  889.66
  4242.1  890.05  4247.7  888.76  4286.9  889.12  4292.5  888.03  4309.3   888.2
    4382  883.14  4437.5   882.8  4533.2  876.55    4722  873.06  4817.2  872.52
  4872.5  872.65  4877.5  876.28  4934.6  874.12  4964.7  870.57  5011.2  868.89
  5011.7  868.09  5018.4  868.89  5034.8  871.84  5042.4  875.27    5055  877.87
  5085.7  880.82  5106.1  884.01  5210.3  893.36  5341.3  901.89    5383  902.13
#Mann= 6 ,-1 , 0
  3950.5      .1       0    4722     .05       0  4817.2      .1       0
  5011.2     .07       0  5018.4      .1       0  5210.3     .16       0
Bank Sta=5011.2,5018.4
XS Rating Curve= 0 ,0
Exp/Cntr=0.3,0.1

Type RM Length L Ch R = 1 ,214385  ,414,414,414
BEGIN DESCRIPTION:
Black Creek 229.0
END DESCRIPTION:
XS GIS Cut Line= 3
      1973462.99     13643180.14        1972875.       13643325.
      1972489.54      13643422.2
#Sta/Elev= 30
  4410.7  895.08  4439.5  893.95  4480.7  891.03  4489.8  891.01  4536.4  887.68
  4542.5  886.68  4624.9  879.98  4707.6  874.32    4800   870.9  4933.9  869.66
  4951.4  868.61  4985.4  868.15  4992.9  866.82  5002.4  866.71  5002.9  865.91
  5009.1  865.91  5009.6  866.71  5013.7  867.52  5018.8  867.52  5034.2  871.73
  5047.2  873.33  5080.5  876.01  5116.4  880.19  5121.5  880.24  5150.3  884.22
  5222.5  890.25  5239.6  892.49  5274.1  895.45  5362.8  897.54  5413.8  898.03
#Mann= 3 ,-1 , 0
  4410.7      .1       0  5002.4     .07       0  5009.6      .1       0
Bank Sta=5002.4,5009.6
XS Rating Curve= 0 ,0
Exp/Cntr=0.3,0.1

Type RM Length L Ch R = 1 ,213971  ,386,386,386
BEGIN DESCRIPTION:
Black Creek 228.0
END DESCRIPTION:
XS GIS Cut Line= 3
      1973375.02     13642824.99      1972697.39     13643023.89
      1972423.97     13643286.89
#Sta/Elev= 30
  4562.3  900.51  4617.6  896.79  4635.3  894.57  4645.7  892.72    4651  890.89
  4666.5  889.21    4723  885.81  4756.4  882.03  4828.4  875.77  4895.1  872.48
  4924.7  872.13  4938.9  871.24  4958.4  865.88  4972.3  866.48    4986  865.72
  4986.5  864.92  4992.7  864.92  4993.3  865.72  5005.7  868.16  5010.9  866.92
  5039.1  869.76  5104.3  866.87  5156.4  867.12  5216.5  873.25  5249.8  874.62
  5267.2  876.58  5306.4  878.66  5419.6  886.97  5532.8   891.7  5647.9  894.86
#Mann= 4 ,-1 , 0
  4562.3      .1       0  4924.7     .16       0    4986     .07       0
  4993.3      .1       0
Bank Sta=4986,4993.3
XS Rating Curve= 0 ,0
Exp/Cntr=0.3,0.1

Type RM Length L Ch R = 1 ,213585  ,278,278,278
BEGIN DESCRIPTION:
Black Creek 227.0
END DESCRIPTION:
XS GIS Cut Line= 3
       1973319.8     13642581.17      1972689.57      13642721.8
      1972297.52     13643181.37
#Sta/Elev= 30
  4420.7  893.82  4461.4  891.38  4466.6  890.31  4509.9  886.85  4548.3  882.68
  4630.5  875.73  4688.9  872.39  4829.4  868.98  4886.7  866.84    4970  866.31
  4995.7  865.44  4996.3  864.64  5002.5  864.64    5003  865.44  5040.4  865.82
  5056.9  867.58  5062.1  866.55  5071.8  867.13  5079.2  866.37  5114.3   867.1
  5149.5  869.19  5284.5  872.97    5313  875.42  5327.3  878.34  5341.6  879.92
  5370.2  881.71  5419.6  883.23  5497.5  882.63  5624.9  891.16  5670.5   892.2
#Mann= 3 ,-1 , 0
  4420.7      .1       0  4995.7     .07       0    5003      .1       0
Bank Sta=4995.7,5003
XS Rating Curve= 0 ,0
Exp/Cntr=0.3,0.1