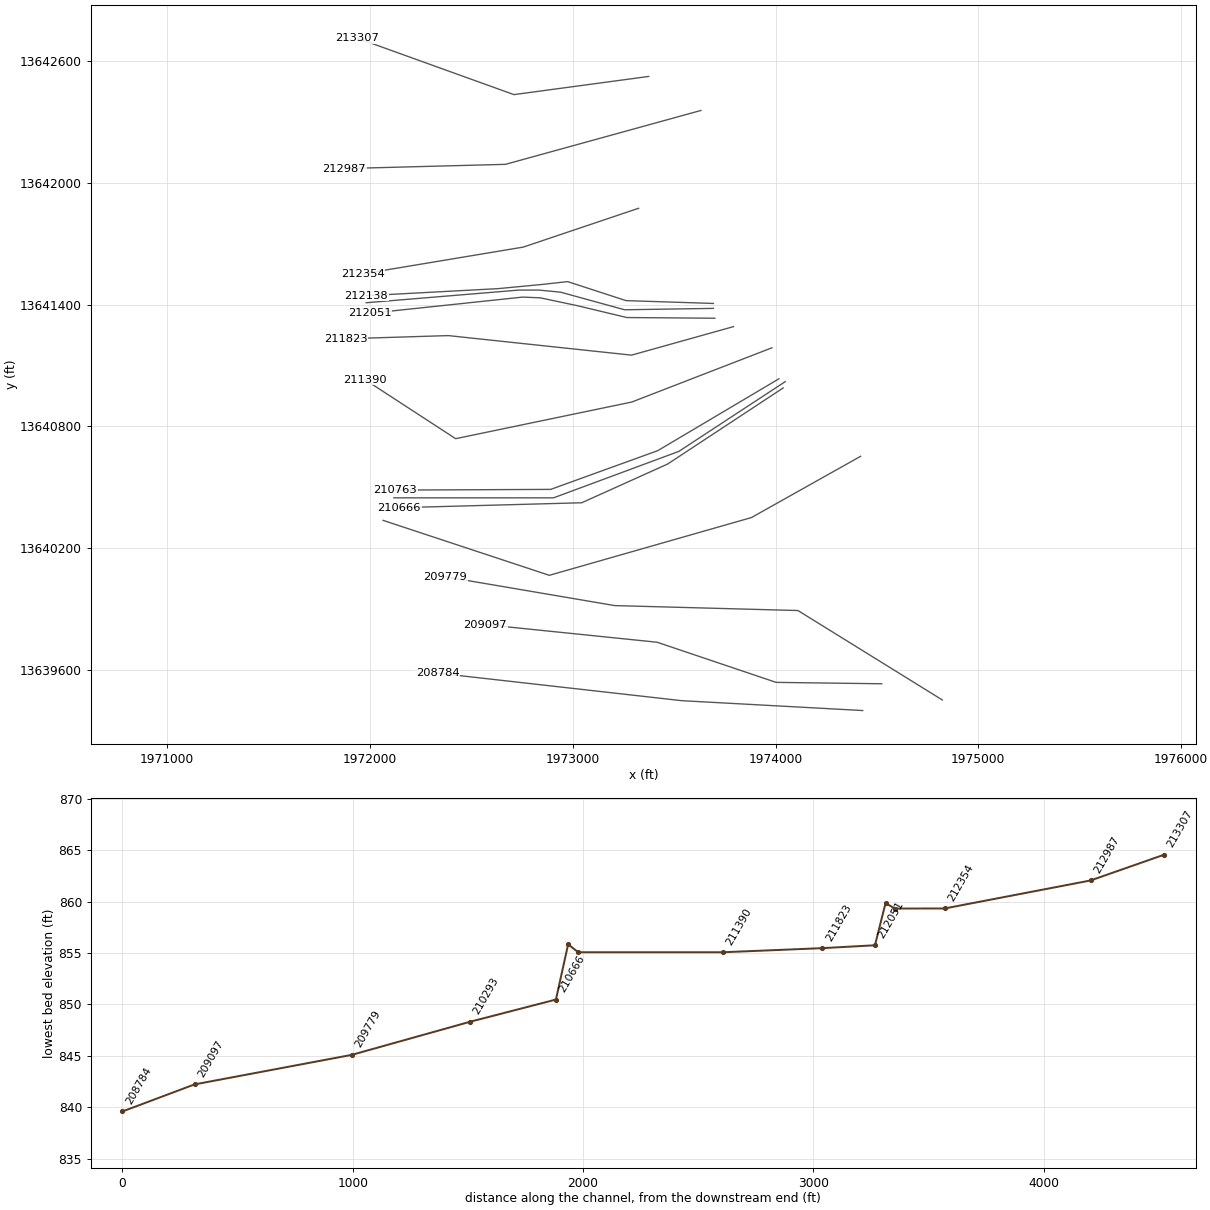
HEC-RAS study Black Creek.prj: Black Creek Base Level Engineering

--- Black Creek.g01 (geometry) --- (continued)

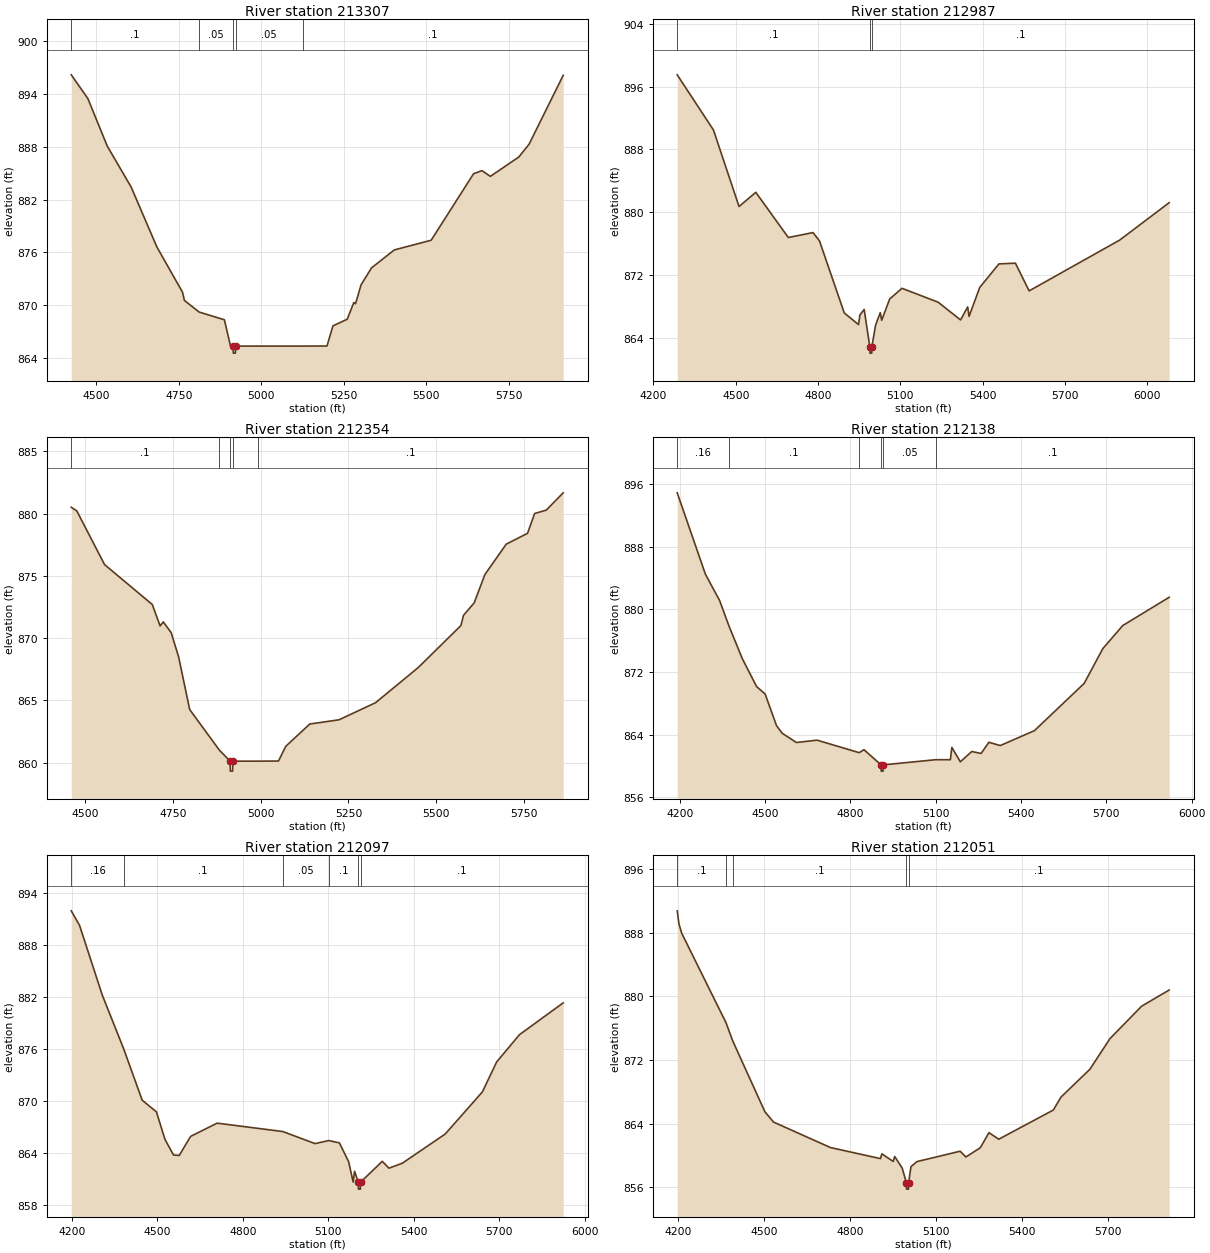
Type RM Length L Ch R = 1 ,213307  ,320,320,320
BEGIN DESCRIPTION:
Black Creek 226.0
END DESCRIPTION:
XS GIS Cut Line= 3
      1973374.96     13642524.99      1972710.41     13642435.34
      1971938.45     13642713.46
#Sta/Elev= 30
  4424.2  896.19  4474.6  893.49  4533.2   888.1  4605.8  883.43  4683.7  876.63
  4761.5  871.48  4767.2  870.55  4811.7  869.23  4888.3  868.35  4906.9  865.37
  4914.8  865.36  4915.4  864.56  4921.7  864.56  4922.3  865.36  5125.2  865.36
  5199.3  865.37  5217.4  867.66  5260.6  868.41  5280.7  870.31    5286  870.17
  5302.5  872.31  5334.4  874.25  5403.5  876.29  5515.1  877.39  5643.7  884.95
  5669.1   885.3  5694.5  884.65  5780.8  886.85    5812  888.31  5915.3  896.13
#Mann= 5 ,-1 , 0
  4424.2      .1       0  4811.7     .05       0  4914.8    .033       0
  4922.3     .05       0  5125.2      .1       0
Bank Sta=4914.8,4922.3
XS Rating Curve= 0 ,0
Exp/Cntr=0.3,0.1

Type RM Length L Ch R = 1 ,212987  ,633,633,633
BEGIN DESCRIPTION:
Black Creek 225.0
END DESCRIPTION:
XS GIS Cut Line= 3
      1973632.33     13642357.23      1972668.74     13642091.59
      1971874.45     13642070.76
#Sta/Elev= 30
  4286.6  897.51  4418.7  890.48    4512  880.73  4573.1  882.54  4691.8  876.78
  4781.7  877.41  4805.3  876.36  4895.8  867.17  4947.7  865.69  4953.2  866.94
  4968.4  867.61    4989  862.85  4989.6  862.05  4995.9  862.05  4996.5  862.85
  5009.9   865.6  5027.1  867.21  5032.3  866.24  5061.5  868.95  5106.2  870.31
  5238.1  868.54  5319.9  866.28  5345.9  867.94  5350.9  866.73  5389.9  870.42
  5459.9  873.42    5520  873.51    5570  869.98  5900.1  876.45  6080.7  881.22
#Mann= 3 ,-1 , 0
  4286.6      .1       0    4989     .07       0  4996.5      .1       0
Bank Sta=4989,4996.5
XS Rating Curve= 0 ,0
Exp/Cntr=0.3,0.1

Type RM Length L Ch R = 1 ,212354  ,216,216,216
BEGIN DESCRIPTION:
Black Creek 224.0
END DESCRIPTION:
XS GIS Cut Line= 3
      1973325.03     13641875.01      1972756.41     13641683.61
       1971964.7     13641551.66
#Sta/Elev= 30
  4459.8   880.5  4475.6  880.21  4554.8   875.9  4690.8   872.7  4713.1  870.98
  4722.3   871.3  4744.7  870.44  4765.8  868.51  4797.5  864.27  4881.7  861.03
  4912.7  860.13  4913.3  859.33  4919.8  859.33  4920.4  860.13  4992.6  860.13
  5050.7  860.14  5071.3  861.32  5139.9  863.11  5223.4  863.45  5327.4  864.82
  5449.1  867.64  5570.7  871.01  5578.2  871.83  5608.6  872.83  5639.1   875.1
  5699.9  877.54  5760.7  878.41    5781     880  5814.1  880.27  5862.4  881.66
#Mann= 5 ,-1 , 0
  4459.8      .1       0  4881.7     .05       0  4912.7     .07       0
  4920.4     .05       0  4992.6      .1       0
Bank Sta=4912.7,4920.4
XS Rating Curve= 0 ,0
Exp/Cntr=0.3,0.1

Type RM Length L Ch R = 1 ,212138  ,41,41,41
BEGIN DESCRIPTION:
Mapping XS b1644f6e
END DESCRIPTION:
XS GIS Cut Line= 6
      1973693.91     13641405.83      1973263.36     13641419.72
      1972975.16     13641513.47      1972850.16     13641499.58
      1972631.41     13641478.75      1971982.09     13641444.02
#Sta/Elev= 30
  4191.3  894.91  4290.3  884.51  4340.3  881.14  4373.1  877.89  4420.3  873.69
  4470.4  870.13  4500.4  869.18  4540.4  865.13  4560.4  864.16  4610.4  862.98
  4682.9  863.28    4831  861.68  4847.9  862.06  4907.9  860.12  4908.5  859.32
    4915  859.32  4915.6  860.12    5100  860.78  5151.7  860.78  5156.8  862.35
  5186.7  860.51  5226.9  861.83  5259.7  861.58  5287.1  863.01  5327.1  862.59
  5447.3   864.5  5622.1  870.54  5687.7  874.99  5757.8  877.94  5920.9  881.55
#Mann= 6 ,-1 , 0
  4191.3     .16       0  4373.1      .1       0    4831     .05       0
  4907.9    .033       0  4915.6     .05       0    5100      .1       0
Bank Sta=4907.9,4915.6
XS Rating Curve= 0 ,0
Exp/Cntr=0.3,0.1

Type RM Length L Ch R = 1 ,212097  ,46,46,46
BEGIN DESCRIPTION:
Mapping XS ee527b7d
END DESCRIPTION:
XS GIS Cut Line= 6
      1973693.95     13641381.52      1973256.41     13641374.58
      1972940.44     13641461.39       1972832.8      13641471.8
      1972735.58      13641471.8      1971982.13      13641409.3
#Sta/Elev= 30
  4197.7  891.98  4226.7  890.31  4306.7  882.24  4381.6  876.05  4446.7  870.11
  4496.7  868.76  4526.7  865.58  4556.7  863.78  4576.7  863.73  4616.7  865.93
  4709.8  867.46  4940.3  866.49  5053.3   865.1    5102  865.45    5139  865.18
  5171.3  863.01  5187.2  860.66  5192.2   861.9  5205.3  860.64  5205.9  859.84
  5212.4  859.84    5213  860.64  5289.5  863.05  5312.9  862.26  5359.7  862.83
  5510.2   866.2  5640.7  871.06  5690.8  874.52  5771.1  877.68  5924.5  881.35
#Mann= 6 ,-1 , 0
  4197.7     .16       0  4381.6      .1       0  4940.3     .05       0
    5102      .1       0  5205.3    .033       0    5213      .1       0
Bank Sta=5205.3,5213
XS Rating Curve= 0 ,0
Exp/Cntr=0.3,0.1

Type RM Length L Ch R = 1 ,212051  ,228,228,228
BEGIN DESCRIPTION:
Mapping XS d3e7b8dc
END DESCRIPTION:
XS GIS Cut Line= 6
      1973700.87     13641332.91      1973266.83     13641336.39
       1973020.3     13641395.41      1972839.75     13641433.61
      1972752.94     13641437.08      1971999.74     13641357.25
#Sta/Elev= 30
  4196.7  890.76  4202.6  889.13  4212.6  887.92  4367.1  876.67  4390.4  874.39
  4502.6  865.48  4532.6  864.19  4731.2  860.98  4905.7  859.59  4910.8  860.19
  4950.3  859.23  4955.4  859.86  4981.7  858.39  4996.2  856.55  4996.8  855.75
  5003.3  855.75  5003.9  856.55  5012.3  858.57  5032.8  859.21  5183.8  860.52
  5203.9  859.79  5254.2  860.96  5284.3  862.85  5318.6  862.03    5509   865.7
  5535.7  867.33  5636.3  870.82  5706.7  874.69  5817.3  878.77  5913.1   880.8
#Mann= 5 ,-1 , 0
  4196.7      .1       0  4367.1     .16       0  4390.4      .1       0
  4996.2     .07       0  5003.9      .1       0
Bank Sta=4996.2,5003.9
XS Rating Curve= 0 ,0
Exp/Cntr=0.3,0.1

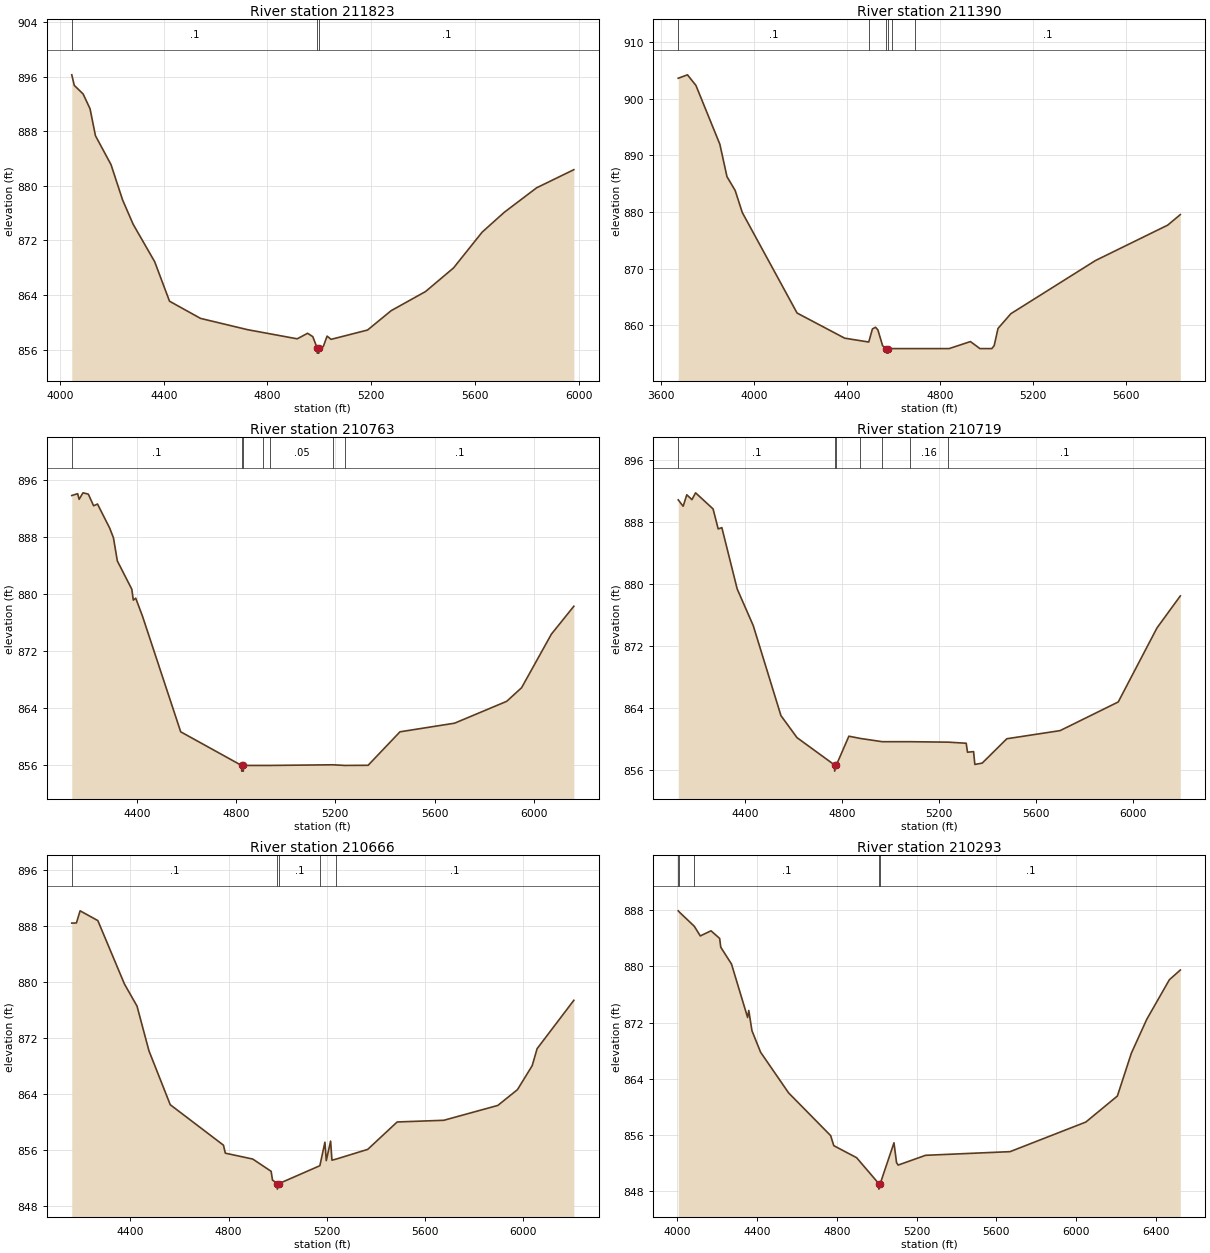
Type RM Length L Ch R = 1 ,211823  ,433,433,433
BEGIN DESCRIPTION:
Mapping XS 90645dd4
END DESCRIPTION:
XS GIS Cut Line= 4
      1973792.93      13641291.6      1973290.32     13641150.97
      1972386.67     13641247.33       1971881.5      13641231.7
#Sta/Elev= 30
  4045.4  896.31  4055.1  894.76  4089.2   893.5  4115.9  891.33  4136.7  887.38
  4196.8  883.13  4241.3  877.96  4282.1  874.38  4365.2  868.88  4422.4  863.09
  4541.7  860.57  4723.5  858.91  4914.6  857.57  4954.8  858.38  4974.9  857.89
  4991.1  856.27  4991.8  855.47  4998.3  855.47  4998.9  856.27  5015.2  856.43
    5030  857.97  5045.3  857.49  5186.1  858.86  5276.6  861.69  5409.7  864.51
  5517.8  867.98  5627.8  873.22    5713  876.13  5837.9  879.73  5981.5  882.39
#Mann= 3 ,-1 , 0
  4045.4      .1       0  4991.1     .07       0  4998.9      .1       0
Bank Sta=4991.1,4998.9
XS Rating Curve= 0 ,0
Exp/Cntr=0.3,0.1

Type RM Length L Ch R = 1 ,211390  ,627,627,627
BEGIN DESCRIPTION:
Mapping XS d1661463
END DESCRIPTION:
XS GIS Cut Line= 4
      1973982.11     13641187.08      1973291.14     13640919.72
      1972423.08     13640739.16      1971975.79     13641030.42
#Sta/Elev= 30
  3672.9  903.61  3712.7  904.21  3749.1  902.34  3852.1  891.95  3882.7  886.23
    3918  883.79  3948.6   879.9  4184.5  862.15  4389.4  857.71    4493  857.03
  4508.8  859.34  4522.2  859.64  4532.4  859.17  4552.8  856.37  4569.4  855.87
    4570  855.07  4576.5  855.07  4577.2  855.87  4592.9  855.87  4692.8  855.87
  4838.8  855.87  4930.8  857.11  4971.6  855.87  5022.7  855.87  5032.9  856.39
  5049.5  859.43  5104.7  862.03    5469  871.42  5779.9  877.67  5834.2  879.53
#Mann= 6 ,-1 , 0
  3672.9      .1       0    4493     .16       0  4569.4     .07       0
  4577.2     .16       0  4592.9     .05       0  4692.8      .1       0
Bank Sta=4569.4,4577.2
XS Rating Curve= 0 ,0
Exp/Cntr=0.3,0.1

Type RM Length L Ch R = 1 ,210763  ,44,44,44
BEGIN DESCRIPTION:
Mapping XS 2f0ff378
END DESCRIPTION:
XS GIS Cut Line= 4
       1974016.8     13641034.29      1973419.61     13640680.14
      1972891.83     13640489.16      1972124.51     13640485.69
#Sta/Elev= 30
  4138.1  893.76  4161.9  894.02  4167.7  893.23  4183.3  894.14  4204.7  893.96
  4226.2  892.32  4241.8  892.57  4291.3  889.16  4306.1  887.82  4321.7  884.58
  4380.1   880.6    4386  879.08  4395.8  879.35    4423  876.83    4577  860.59
  4822.2  855.87  4822.8  855.07  4829.4  855.07    4830  855.87  4908.6  855.87
  4938.2  855.87  5190.4  855.96  5237.6  855.87  5332.1  855.89  5460.5  860.59
  5680.5   861.8  5890.5  864.87  5950.5  866.78  6070.5   874.3    6161  878.22
#Mann= 7 ,-1 , 0
  4138.1      .1       0  4822.2    .033       0    4830      .1       0
  4908.6     .16       0  4938.2     .05       0  5190.4     .16       0
  5237.6      .1       0
Bank Sta=4822.2,4830
XS Rating Curve= 0 ,0
Exp/Cntr=0.3,0.1

Type RM Length L Ch R = 1 ,210719  ,53,53,53
BEGIN DESCRIPTION:
Mapping XS 4ff97281
END DESCRIPTION:
XS GIS Cut Line= 4
      1974048.08     13641020.41      1973523.77     13640676.66
      1972905.72      13640447.5      1972118.73      13640447.5
#Sta/Elev= 30
  4124.1  890.86  4144.4  890.04  4159.5  891.52  4180.6  890.89  4195.7  891.77
    4268  889.69  4289.1  887.11  4304.2  887.28  4367.4  879.37  4433.8  874.63
  4548.3     863  4614.7  860.16  4769.4  856.64    4770  855.84  4777.2  856.64
  4828.7  860.35  4875.7  860.06  4966.8  859.64  5079.3  859.64  5239.6  859.58
  5313.2  859.44  5318.5  858.28  5343.6  858.36  5348.9   856.7  5379.3  856.88
  5480.9  860.02  5700.9  861.07  5940.9  864.77  6100.9  874.33  6197.2  878.46
#Mann= 7 ,-1 , 0
  4124.1      .1       0  4769.4    .033       0  4777.2      .1       0
  4875.7     .16       0  4966.8     .05       0  5079.3     .16       0
  5239.6      .1       0
Bank Sta=4769.4,4777.2
XS Rating Curve= 0 ,0
Exp/Cntr=0.3,0.1

Type RM Length L Ch R = 1 ,210666  ,373,373,373
BEGIN DESCRIPTION:
Mapping XS ff79defb
END DESCRIPTION:
XS GIS Cut Line= 4
      1974037.64     13640989.15      1973468.22     13640614.16
      1973044.61     13640423.19       1972145.3     13640398.89
#Sta/Elev= 30
  4161.2  888.42  4180.1  888.44  4195.2  890.17  4267.4  888.78  4375.9  879.73
  4427.1  876.58  4475.7  870.21  4562.6  862.51  4779.4  856.74    4787   855.6
  4898.8  854.76  4973.7  853.01  4979.2  851.76  4998.4  851.27    4999  850.47
  5006.3  851.27  5172.2  853.81  5192.9  857.16  5198.4  854.54    5216  857.32
  5221.5   854.6  5238.3  854.75  5367.3  856.14  5487.3  860.05  5677.4  860.29
  5897.5  862.41  5977.5  864.66  6037.5  868.08  6057.5   870.5  6207.3  877.41
#Mann= 5 ,-1 , 0
  4161.2      .1       0  4998.4     .07       0  5006.3      .1       0
  5172.2     .16       0  5238.3      .1       0
Bank Sta=4998.4,5006.3
XS Rating Curve= 0 ,0
Exp/Cntr=0.3,0.1

Type RM Length L Ch R = 1 ,210293  ,514,514,514
BEGIN DESCRIPTION:
Mapping XS c7e4763e
END DESCRIPTION:
XS GIS Cut Line= 4
       1974419.6     13640652.35      1973881.41     13640350.27
      1972884.89     13640065.55      1972065.45     13640336.38
#Sta/Elev= 30
  4005.6  887.89  4009.8  887.75    4086   885.7  4116.2  884.32  4169.8  885.05
  4213.1  883.97  4218.9  882.71  4272.5  880.33  4353.4  872.72  4359.2  873.72
  4375.1  870.84  4418.5  867.78  4558.8     862  4769.6  855.92  4785.4  854.49
  4899.8  852.78  5010.3  849.11  5010.9  848.31  5018.2  849.11    5087   854.9
  5099.8  852.09  5107.8  851.73  5245.4  853.12  5668.8  853.64  6048.7  857.85
  6206.7  861.55    6277  867.66  6354.2  872.47  6467.4  878.09  6522.2  879.47
#Mann= 5 ,-1 , 0
  4005.6      .1       0  4009.8     .16       0    4086      .1       0
  5010.3     .07       0  5018.2      .1       0
Bank Sta=5010.3,5018.2
XS Rating Curve= 0 ,0
Exp/Cntr=0.3,0.1

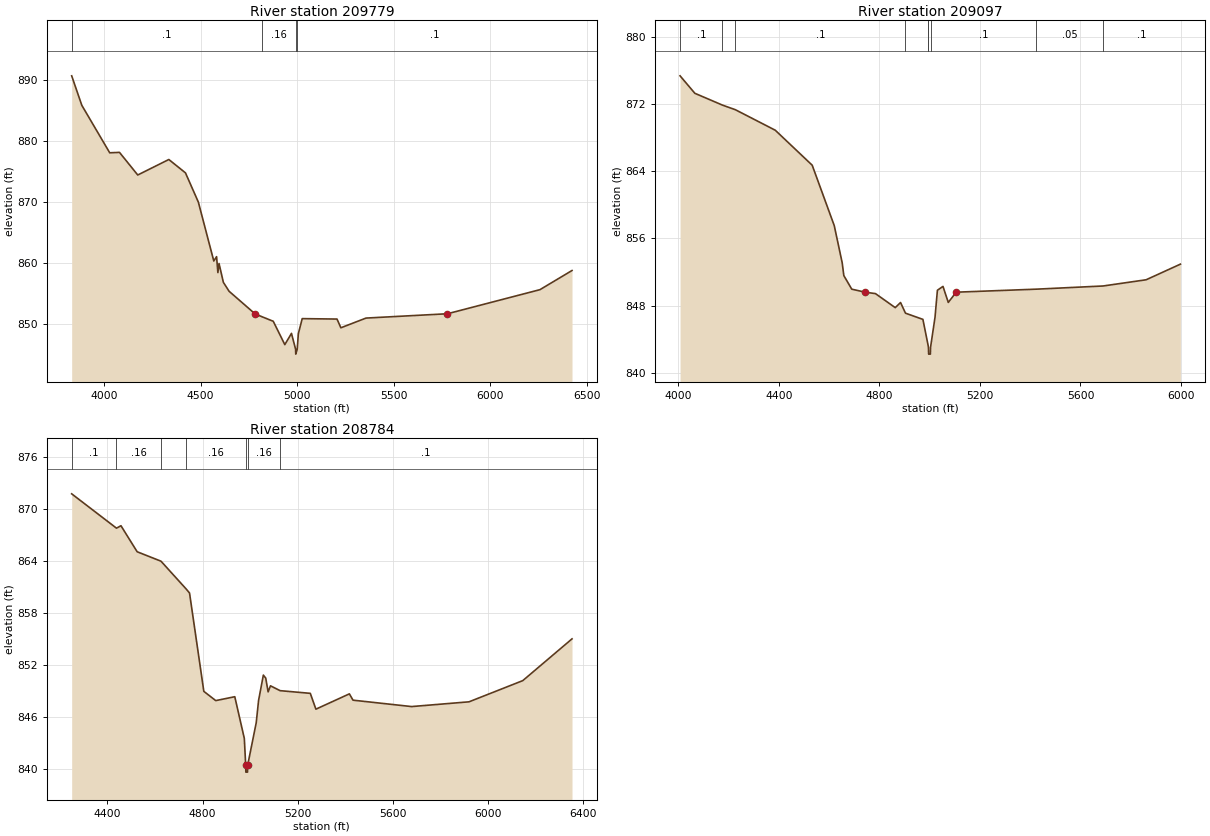
Type RM Length L Ch R = 1 ,209779  ,682,682,682
BEGIN DESCRIPTION:
Mapping XS 9cff2789
END DESCRIPTION:
XS GIS Cut Line= 4
      1974822.36     13639450.99      1974110.58     13639891.94
       1973207.8     13639916.25      1972371.03      13640058.6
#Sta/Elev= 30
  3832.8  890.72  3885.3  885.88  4029.7   878.1  4080.2  878.17  4174.7  874.46
  4335.5     877  4421.7  874.81  4488.4  870.01  4568.2  860.36  4582.6  861.07
  4589.4  858.46  4595.3  859.95  4617.8  856.86  4647.3   855.4 4781.02  851.71
  4815.2  851.25  4875.8  850.48  4935.8  846.65  4970.2  848.49  4991.6  845.89
  4992.3  845.09  4999.9  845.89  5005.8  848.44  5025.8  850.91  5205.9  850.84
  5225.9  849.41  5355.9     851 5777.59  851.71  6256.1  855.66    6422   858.8
#Mann= 4 ,-1 , 0
  3832.8      .1       0  4815.2     .16       0  4991.6     .07       0
  4999.9      .1       0
Bank Sta=4781.02,5777.59
XS Rating Curve= 0 ,0
Exp/Cntr=0.3,0.1

Type RM Length L Ch R = 1 ,209097  ,313,313,313
BEGIN DESCRIPTION:
Mapping XS f923c0cc
END DESCRIPTION:
XS GIS Cut Line= 4
      1974523.75     13639530.83      1974002.94     13639537.77
      1973416.14     13639735.69      1972569.41     13639822.45
#Sta/Elev= 30
  4006.5  875.38  4065.3   873.3  4175.3  871.89  4226.8  871.34  4385.3   868.9
  4532.4  864.73  4620.2  857.53  4651.8   853.1  4658.3  851.58  4689.8  849.96
 4742.83   849.6  4784.2  849.43  4862.9  847.76    4884  848.37  4903.6   847.1
    4973  846.36  4993.7  843.27  4995.1  843.02  4995.8  842.22  5002.7  842.22
  5003.4  843.02  5021.2  846.61  5030.7  849.83  5052.9  850.29    5074  848.38
 5105.48   849.6  5424.4  849.96  5690.4  850.34  5861.5  851.08  5997.8  852.94
#Mann= 9 ,-1 , 0
  4006.5      .1       0  4175.3     .16       0  4226.8      .1       0
  4903.6     .16       0  4993.7      .1       0  4995.1     .07       0
  5003.4      .1       0  5424.4     .05       0  5690.4      .1       0
Bank Sta=4742.83,5105.48
XS Rating Curve= 0 ,0
Exp/Cntr=0.3,0.1

Type RM Length L Ch R = 1 ,208784  ,465,465,465
BEGIN DESCRIPTION:
Black Creek 220.0
END DESCRIPTION:
XS GIS Cut Line= 3
      1974429.99     13639398.89      1973537.66      13639447.5
      1972334.55     13639583.27
#Sta/Elev= 30
  4249.7  871.77  4438.1   867.8    4457  868.08  4525.1  865.07  4625.4  863.98
  4731.4  860.76  4745.4   860.3  4805.5  848.93  4855.6  847.86  4935.7  848.31
  4975.8  843.49  4981.6  840.39  4982.3  839.59  4989.2  839.59  4989.9  840.39
  5025.8  845.29  5035.9   847.9  5055.9  850.81  5065.9  850.46  5075.9  848.87
  5085.9  849.57  5126.3  849.01  5253.3   848.7  5276.9  846.87  5417.7  848.64
    5433  847.91  5679.4  847.17  5920.9  847.72    6147  850.17  6354.1     855
#Mann= 7 ,-1 , 0
  4249.7      .1       0  4438.1     .16       0  4625.4      .1       0
  4731.4     .16       0  4981.6     .07       0  4989.9     .16       0
  5126.3      .1       0
Bank Sta=4981.6,4989.9
XS Rating Curve= 0 ,0
Exp/Cntr=0.3,0.1