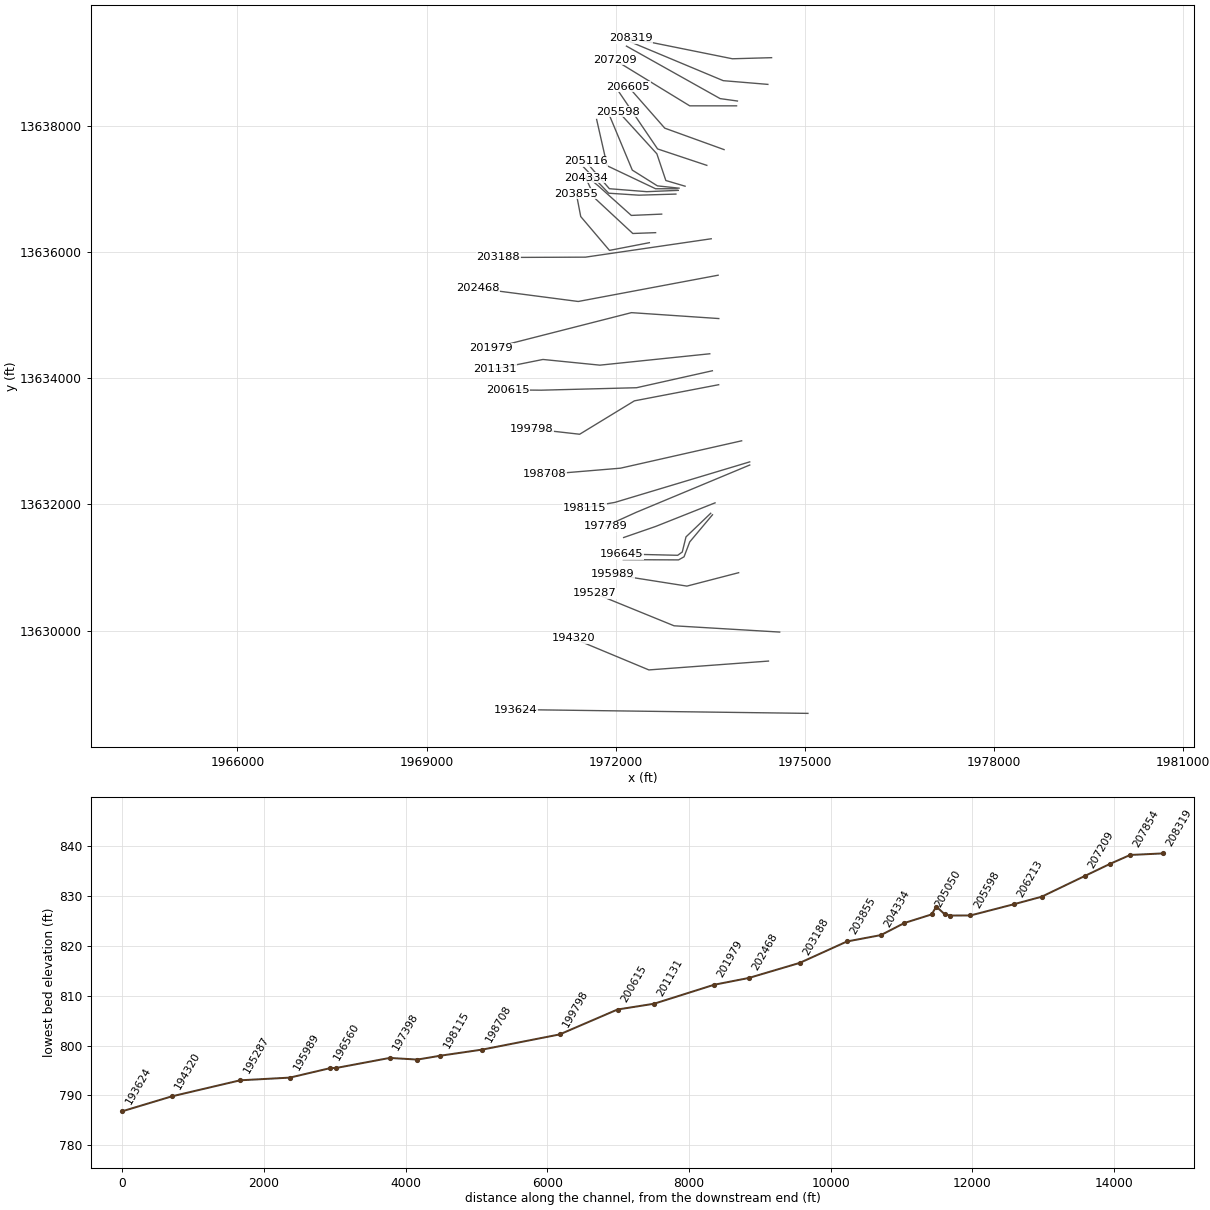
HEC-RAS study Black Creek.prj: Black Creek Base Level Engineering

--- Black Creek.g01 (geometry) --- (continued)

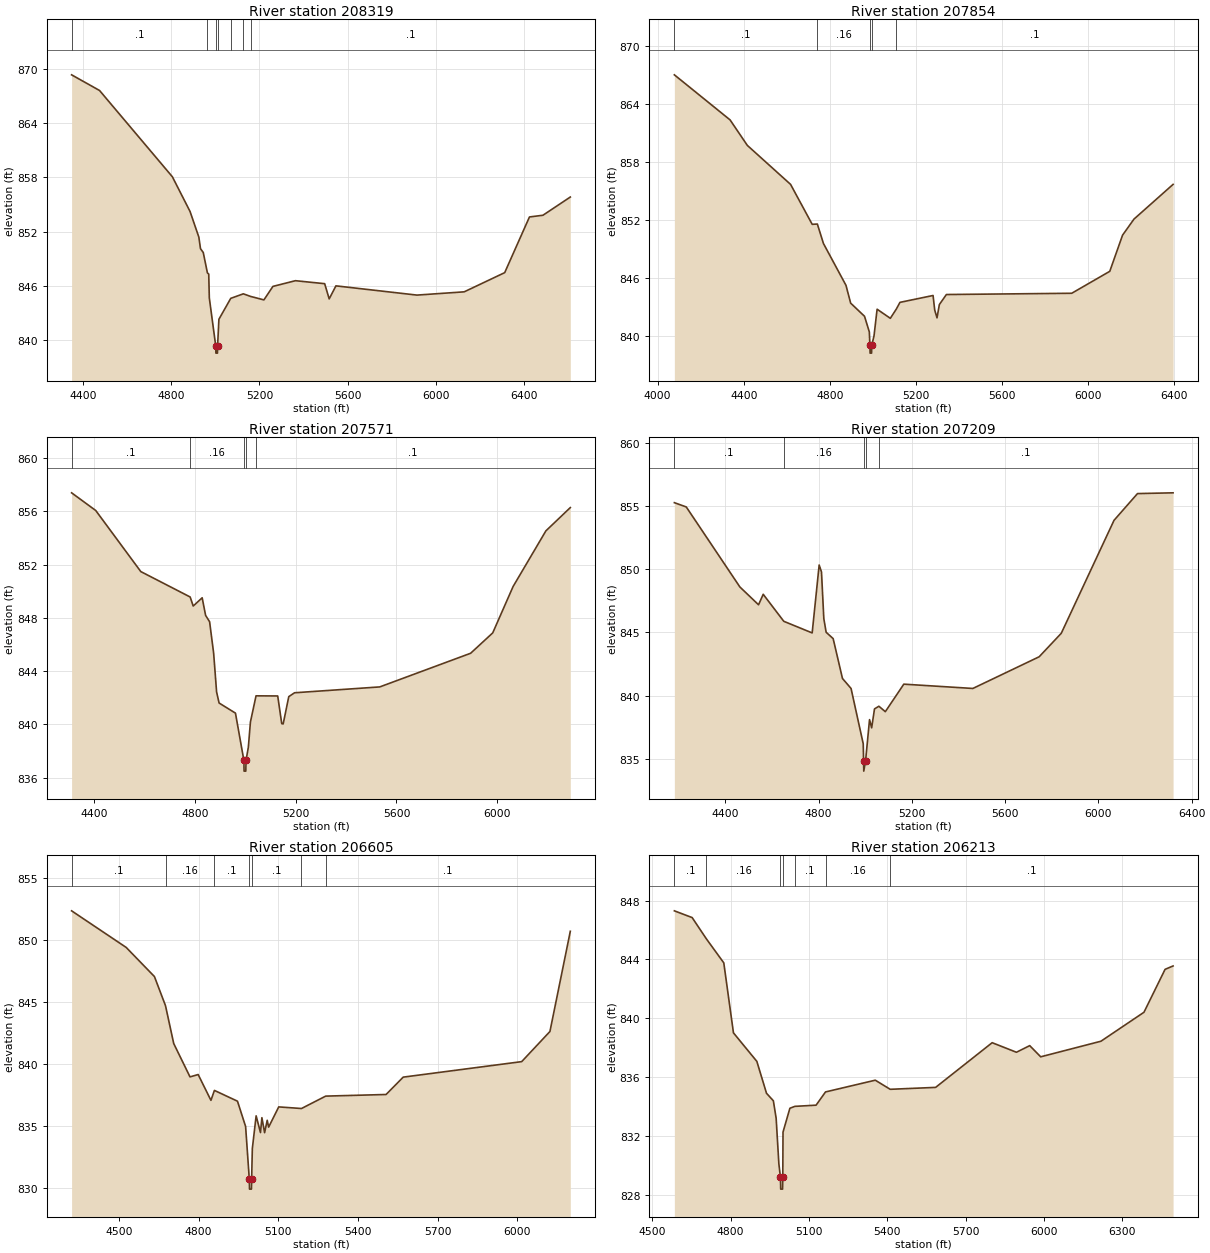
Type RM Length L Ch R = 1 ,208319  ,465,465,465
BEGIN DESCRIPTION:
Black Creek 219.0
END DESCRIPTION:
XS GIS Cut Line= 3
      1974471.66     13639086.38      1973850.16     13639069.02
      1972243.48     13639393.15
#Sta/Elev= 30
  4348.3  869.31    4475  867.58  4805.1  858.05  4885.2  854.22  4925.2  851.38
  4932.6  850.11  4945.2  849.68    4964  847.43    4970   847.3  4972.6  844.67
  5001.7  839.37  5002.5  838.57  5009.4  838.57  5010.1  839.37  5016.1  842.31
  5069.8  844.62  5126.7  845.12  5160.1  844.83  5220.1  844.45    5261  845.94
    5363  846.57  5495.6  846.24    5516  844.56  5546.6     846  5913.8  844.98
  6128.1  845.34  6311.7  847.46  6423.9  853.61  6485.1   853.8  6609.1  855.81
#Mann= 7 ,-1 , 0
  4348.3      .1       0    4964     .16       0  5001.7     .07       0
  5010.1     .16       0  5069.8      .1       0  5126.7     .16       0
  5160.1      .1       0
Bank Sta=5001.7,5010.1
XS Rating Curve= 0 ,0
Exp/Cntr=0.3,0.1

Type RM Length L Ch R = 1 ,207854  ,283,283,283
BEGIN DESCRIPTION:
Black Creek 218.0
END DESCRIPTION:
XS GIS Cut Line= 3
      1974412.71     13638662.77      1973704.33      13638721.8
      1972223.86     13639340.55
#Sta/Elev= 30
    4078  867.04  4336.6  862.38  4416.9  859.74  4617.6  855.71  4717.9  851.58
  4741.9  851.61  4770.1   849.6  4874.8  845.27  4896.5  843.43  4960.9  842.07
  4983.2  840.45  4985.9  839.06  4986.7  838.26  4993.6  838.26  4994.3  839.06
  5004.9  840.04  5019.3   842.8  5080.7  841.86  5108.9  842.83  5125.4  843.51
  5279.1  844.22  5286.7  842.72  5297.4  841.91  5308.3  843.28  5340.9  844.32
  5922.9  844.45  6099.5  846.72  6158.9  850.46  6211.9  852.12  6393.4  855.71
#Mann= 5 ,-1 , 0
    4078      .1       0  4741.9     .16       0  4985.9     .07       0
  4994.3     .16       0  5108.9      .1       0
Bank Sta=4985.9,4994.3
XS Rating Curve= 0 ,0
Exp/Cntr=0.3,0.1

Type RM Length L Ch R = 1 ,207571  ,362,362,362
BEGIN DESCRIPTION:
Black Creek 217.0
END DESCRIPTION:
XS GIS Cut Line= 3
      1973930.03     13638398.88      1973655.72     13638437.08
      1972169.67     13639269.78
#Sta/Elev= 30
  4309.9   857.4  4405.8  856.07  4584.7  851.48  4780.7  849.57  4792.8  848.89
  4828.4  849.51    4842  848.19  4857.9  847.71  4873.9  845.36  4885.7  842.43
  4895.6   841.6  4960.6  840.84  4994.1  837.28  4994.8  836.48  5001.7  836.48
  5002.5  837.28  5011.8  838.28    5020  840.17  5042.3  842.14  5128.4  842.13
  5144.4  840.05  5150.1  840.03  5172.3  842.08  5195.2  842.37  5533.6  842.81
  5894.5  845.34  5982.2  846.87  6063.2  850.36  6193.3  854.54  6290.3  856.29
#Mann= 5 ,-1 , 0
  4309.9      .1       0  4780.7     .16       0  4994.1     .07       0
  5002.5     .16       0  5042.3      .1       0
Bank Sta=4994.1,5002.5
XS Rating Curve= 0 ,0
Exp/Cntr=0.3,0.1

Type RM Length L Ch R = 1 ,207209  ,604,604,604
BEGIN DESCRIPTION:
Black Creek 216.0
END DESCRIPTION:
XS GIS Cut Line= 3
       1973916.1      13638322.5      1973173.08      13638322.5
      1971982.05     13639051.02
#Sta/Elev= 30
  4181.1  855.28  4232.2  854.94  4462.2   848.6  4542.2  847.19  4562.2  848.02
  4650.5  845.88  4772.2  844.96  4802.2  850.34  4812.2  849.79  4822.2  846.09
  4832.2  845.01  4862.2  844.51  4902.2  841.35    4939  840.56  4991.2  836.18
  4992.8  834.81  4993.5  834.01  5001.2  834.81  5018.3  838.09  5027.4  837.44
  5039.6  838.94  5058.5  839.15    5086  838.72  5165.3   840.9  5461.5  840.56
  5745.9  843.07  5840.7  844.93    6067  853.88  6167.7     856  6320.3  856.06
#Mann= 5 ,-1 , 0
  4181.1      .1       0  4650.5     .16       0  4992.8     .07       0
  5001.2     .16       0  5058.5      .1       0
Bank Sta=4992.8,5001.2
XS Rating Curve= 0 ,0
Exp/Cntr=0.3,0.1

Type RM Length L Ch R = 1 ,206605  ,392,392,392
BEGIN DESCRIPTION:
Black Creek 215.0
END DESCRIPTION:
XS GIS Cut Line= 3
       1973718.2     13637628.06      1972777.25     13637968.33
      1972198.73     13638626.93
#Sta/Elev= 30
  4322.2  852.32  4527.6  849.37    4634  847.02  4675.7  844.67  4706.6  841.62
  4767.9  838.93  4798.6  839.12  4846.7  837.04  4859.8  837.84  4946.6  836.97
  4977.2  834.93  4991.1  830.68  4991.9  829.88  4999.1  829.88  4999.9  830.68
  5002.5  833.15  5016.8  835.79  5033.2  834.44  5038.5  835.64  5048.7  834.43
  5058.5  835.43  5063.9  834.88  5101.9  836.51  5187.5  836.38  5278.7  837.38
  5505.9  837.51  5570.4  838.91  6016.4  840.16  6122.7  842.59  6199.4  850.67
#Mann= 7 ,-1 , 0
  4322.2      .1       0  4675.7     .16       0  4859.8      .1       0
  4991.1     .07       0  4999.9      .1       0  5187.5     .16       0
  5278.7      .1       0
Bank Sta=4991.1,4999.9
XS Rating Curve= 0 ,0
Exp/Cntr=0.3,0.1

Type RM Length L Ch R = 1 ,206213  ,615,615,615
BEGIN DESCRIPTION:
Mapping XS 0205ea61
END DESCRIPTION:
XS GIS Cut Line= 3
       1973444.5     13637378.46      1972663.29     13637638.86
      1972054.19     13638537.28
#Sta/Elev= 30
    4585   847.3  4653.1  846.84  4707.3   845.4  4774.2  843.76  4811.2     839
  4900.7  837.06  4937.7  834.89  4963.9  834.38  4974.6  833.19    4985  830.09
  4991.1  829.17    4992  828.37  4999.2  828.37    5000  829.17  5000.9  832.25
  5027.2  833.87  5046.3     834  5127.4  834.08  5163.5  834.98    5354  835.78
  5411.1  835.16    5585  835.29  5801.4  838.33  5894.3  837.68  5945.2  838.13
  5987.2  837.37  6217.8  838.43  6382.5   840.4  6463.3  843.32  6493.9  843.55
#Mann= 7 ,-1 , 0
    4585      .1       0  4707.3     .16       0  4991.1     .07       0
    5000     .16       0  5046.3      .1       0  5163.5     .16       0
  5411.1      .1       0
Bank Sta=4991.1,5000
XS Rating Curve= 0 ,0
Exp/Cntr=0.3,0.1

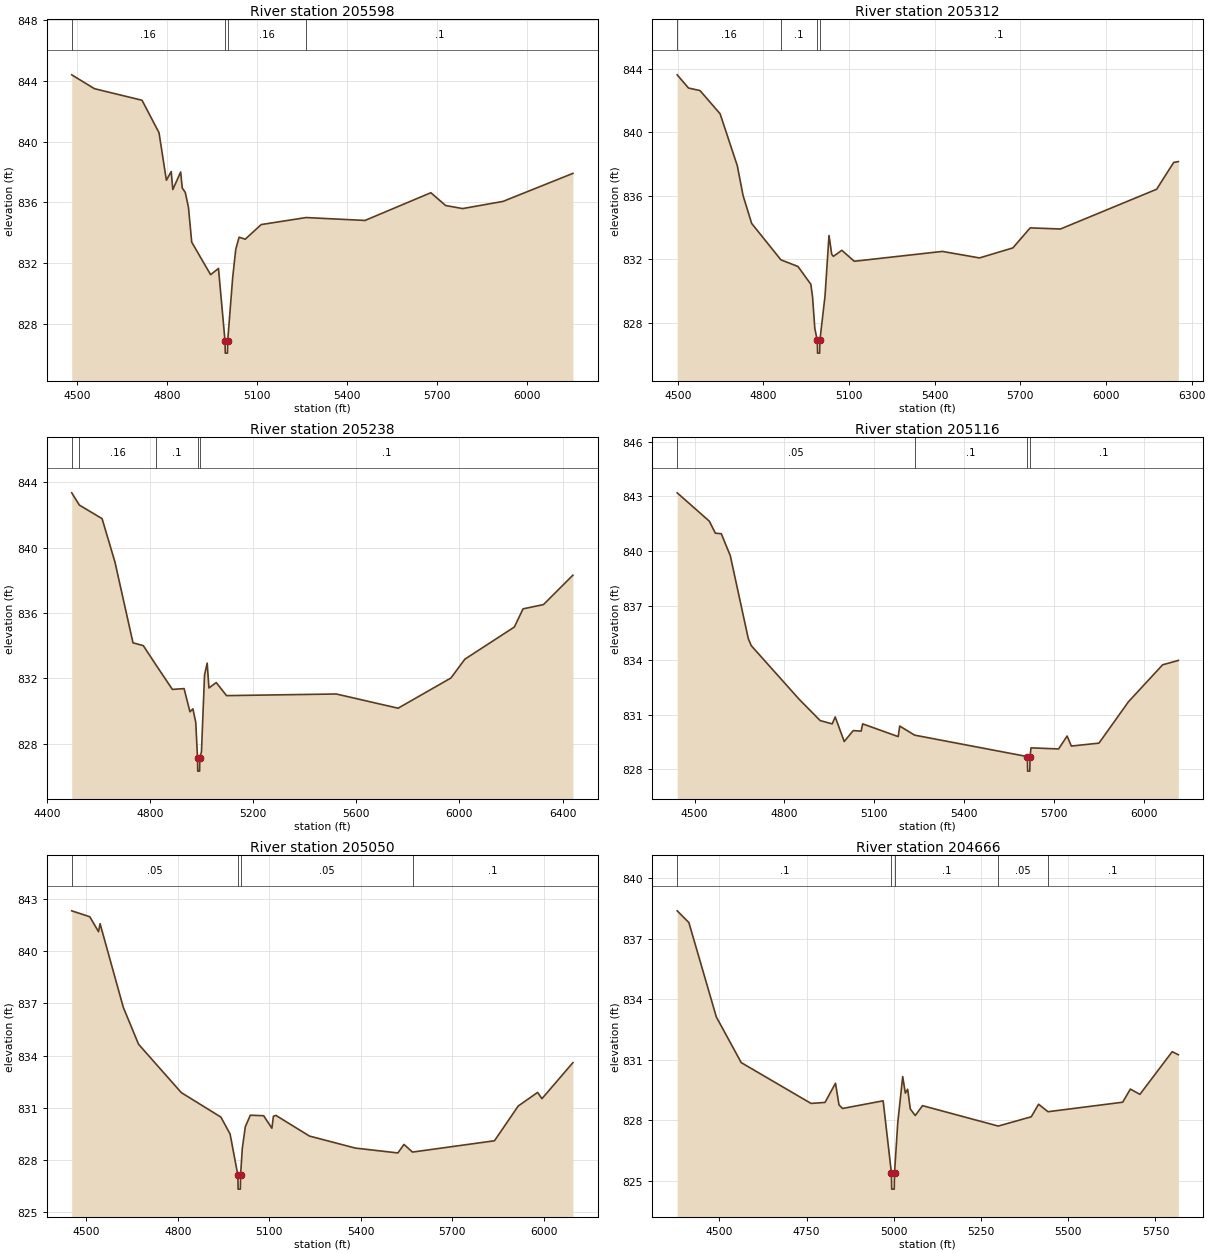
Type RM Length L Ch R = 1 ,205598  ,286,286,286
BEGIN DESCRIPTION:
Mapping XS aaa3d3f7
END DESCRIPTION:
XS GIS Cut Line= 4
       1973099.9     13637047.72      1972794.36     13637137.99
        1972652.      13637561.6      1972041.65     13638230.91
#Sta/Elev= 30
  4481.9  844.38  4557.7  843.47  4716.4  842.71    4773  840.58  4797.6  837.46
  4813.7  838.03    4819  836.85  4845.2     838  4850.5  836.95  4860.6  836.66
  4871.2  835.68    4882   833.4    4945  831.26  4971.3  831.67  4993.1  826.91
  4993.9  826.11  5001.2  826.11    5002  826.91  5018.9  831.12    5029  832.93
    5040  833.72  5060.6  833.59  5113.8  834.55  5263.5  835.01  5459.9  834.82
  5679.5  836.64  5728.8   835.8  5785.6   835.6  5920.1  836.07  6153.2  837.91
#Mann= 4 ,-1 , 0
  4481.9     .16       0  4993.1     .07       0    5002     .16       0
  5263.5      .1       0
Bank Sta=4993.1,5002
XS Rating Curve= 0 ,0
Exp/Cntr=0.3,0.1

Type RM Length L Ch R = 1 ,205312  ,74,74,74
BEGIN DESCRIPTION:
Mapping XS 113ce384
END DESCRIPTION:
XS GIS Cut Line= 4
      1973004.42     13637016.47      1972660.68     13637052.92
      1972262.24     13637302.92      1971900.56     13638170.07
#Sta/Elev= 30
  4497.9  843.61  4537.5  842.78  4577.8  842.62  4648.2  841.16  4708.5  837.89
  4728.6  836.02  4758.8  834.26  4861.2  831.97  4921.1  831.55  4966.1  830.43
    4972  829.65  4980.1  827.64  4988.8   826.9  4989.6   826.1  4996.9   826.1
  4997.7   826.9  5015.6  829.67  5029.7   833.5  5039.2  832.32  5045.1  832.19
  5074.6  832.57  5118.1  831.88  5426.8   832.5  5556.8  832.09  5673.8  832.72
  5734.4  833.98  5840.5  833.91  6177.3  836.41  6237.2   838.1  6253.5  838.15
#Mann= 4 ,-1 , 0
  4497.9     .16       0  4861.2      .1       0  4988.8     .07       0
  4997.7      .1       0
Bank Sta=4988.8,4997.7
XS Rating Curve= 0 ,0
Exp/Cntr=0.3,0.1

Type RM Length L Ch R = 1 ,205238  ,122,122,122
BEGIN DESCRIPTION:
Mapping XS bb65a056
END DESCRIPTION:
XS GIS Cut Line= 4
      1972972.75     13637007.37      1972631.56     13637007.37
      1971863.33     13637371.95      1971696.66     13638106.34
#Sta/Elev= 30
  4495.7  843.35  4525.4   842.6  4613.5  841.77  4663.5  839.11  4733.5  834.17
  4773.5     834  4820.9  832.86  4886.3  831.32  4931.7  831.37  4954.5  829.95
  4965.9  830.13    4977   829.3  4983.8  827.12  4984.6  826.32  4991.9  826.32
  4992.7  827.12  4999.1   827.5    5011   832.2  5021.3  832.93  5028.2  831.41
  5056.5  831.74  5096.4  830.94  5522.2  831.04  5762.1  830.17  5967.2  832.02
  6021.1  833.17  6213.3  835.14  6246.9  836.25  6326.1  836.51  6440.3  838.31
#Mann= 5 ,-1 , 0
  4495.7     .05       0  4525.4     .16       0  4820.9      .1       0
  4983.8     .07       0  4992.7      .1       0
Bank Sta=4983.8,4992.7
XS Rating Curve= 0 ,0
Exp/Cntr=0.3,0.1

Type RM Length L Ch R = 1 ,205116  ,66,66,66
BEGIN DESCRIPTION:
Mapping XS ba230d24
END DESCRIPTION:
XS GIS Cut Line= 4
      1972992.27     13636981.74      1972492.28     13636960.91
      1971898.83     13637007.74      1971519.53     13637444.26
#Sta/Elev= 30
  4442.1   843.2  4549.5  841.64  4569.5  840.98  4589.5  840.95  4619.5  839.74
  4679.6  835.18  4689.6  834.79  4849.7  831.84  4919.8  830.67  4959.9  830.49
  4969.9  830.87    5000  829.52  5030.1  830.12  5056.6  830.09  5061.6  830.49
  5180.3  829.79  5185.4  830.37    5235  829.87  5611.8  828.69  5612.6  827.89
  5619.9  827.89  5620.7  828.69  5623.9  829.17    5716  829.11  5744.5  829.82
  5758.7  829.27  5850.9  829.43  5949.6  831.71  6063.6  833.74  6116.1  833.98
#Mann= 4 ,-1 , 0
  4442.1     .05       0    5235      .1       0  5611.8     .04       0
  5620.7      .1       0
Bank Sta=5611.8,5620.7
XS Rating Curve= 0 ,0
Exp/Cntr=0.3,0.1

Type RM Length L Ch R = 1 ,205050  ,384,384,384
BEGIN DESCRIPTION:
Mapping XS c9b47560
END DESCRIPTION:
XS GIS Cut Line= 4
      1972954.13     13636922.72      1972367.28     13636905.35
      1971888.11      13636936.6      1971488.64     13637352.13
#Sta/Elev= 30
  4452.2  842.32  4511.4  841.98  4540.2  841.12  4545.2  841.58  4621.4  836.77
  4671.4  834.65  4811.5  831.87  4941.5  830.46  4971.6  829.49  4997.1  827.12
  4997.9  826.32  5005.2  826.32    5006  827.12  5011.6  828.66  5021.6  829.91
    5038  830.57  5081.7  830.54  5108.7  829.82  5113.7  830.51  5121.8  830.56
    5232  829.37  5382.3  828.68  5521.9   828.4  5541.9  828.89  5569.9  828.45
  5838.7   829.1  5916.7   831.1  5980.2  831.88  5994.4  831.52  6095.9  833.59
#Mann= 4 ,-1 , 0
  4452.2     .05       0  4997.1     .04       0    5006     .05       0
  5569.9      .1       0
Bank Sta=4997.1,5006
XS Rating Curve= 0 ,0
Exp/Cntr=0.3,0.1

Type RM Length L Ch R = 1 ,204666  ,332,332,332
BEGIN DESCRIPTION:
Mapping XS b83c7546
END DESCRIPTION:
XS GIS Cut Line= 4
      1972728.43     13636605.01      1972246.62     13636584.17
      1971723.18     13637052.92      1971528.96     13637213.48
#Sta/Elev= 30
  4378.8  838.37  4412.3  837.79    4491  833.12  4562.4  830.86  4762.6  828.84
  4802.6  828.89  4832.7  829.84  4842.7  828.77  4852.7  828.59  4969.3  828.97
    4993   825.4  4993.8   824.6  5001.1   824.6  5001.9   825.4  5011.2  827.89
  5025.4  830.17  5032.9  829.35  5039.6  829.54  5047.1  828.57  5061.3  828.24
  5082.2  828.73  5299.3  827.72    5394  828.18  5414.9   828.8    5442  828.43
    5656   828.9  5678.1  829.55  5705.5  829.29    5798   831.4  5815.7  831.25
#Mann= 5 ,-1 , 0
  4378.8      .1       0    4993     .07       0  5001.9      .1       0
  5299.3     .05       0    5442      .1       0
Bank Sta=4993,5001.9
XS Rating Curve= 0 ,0
Exp/Cntr=0.3,0.1

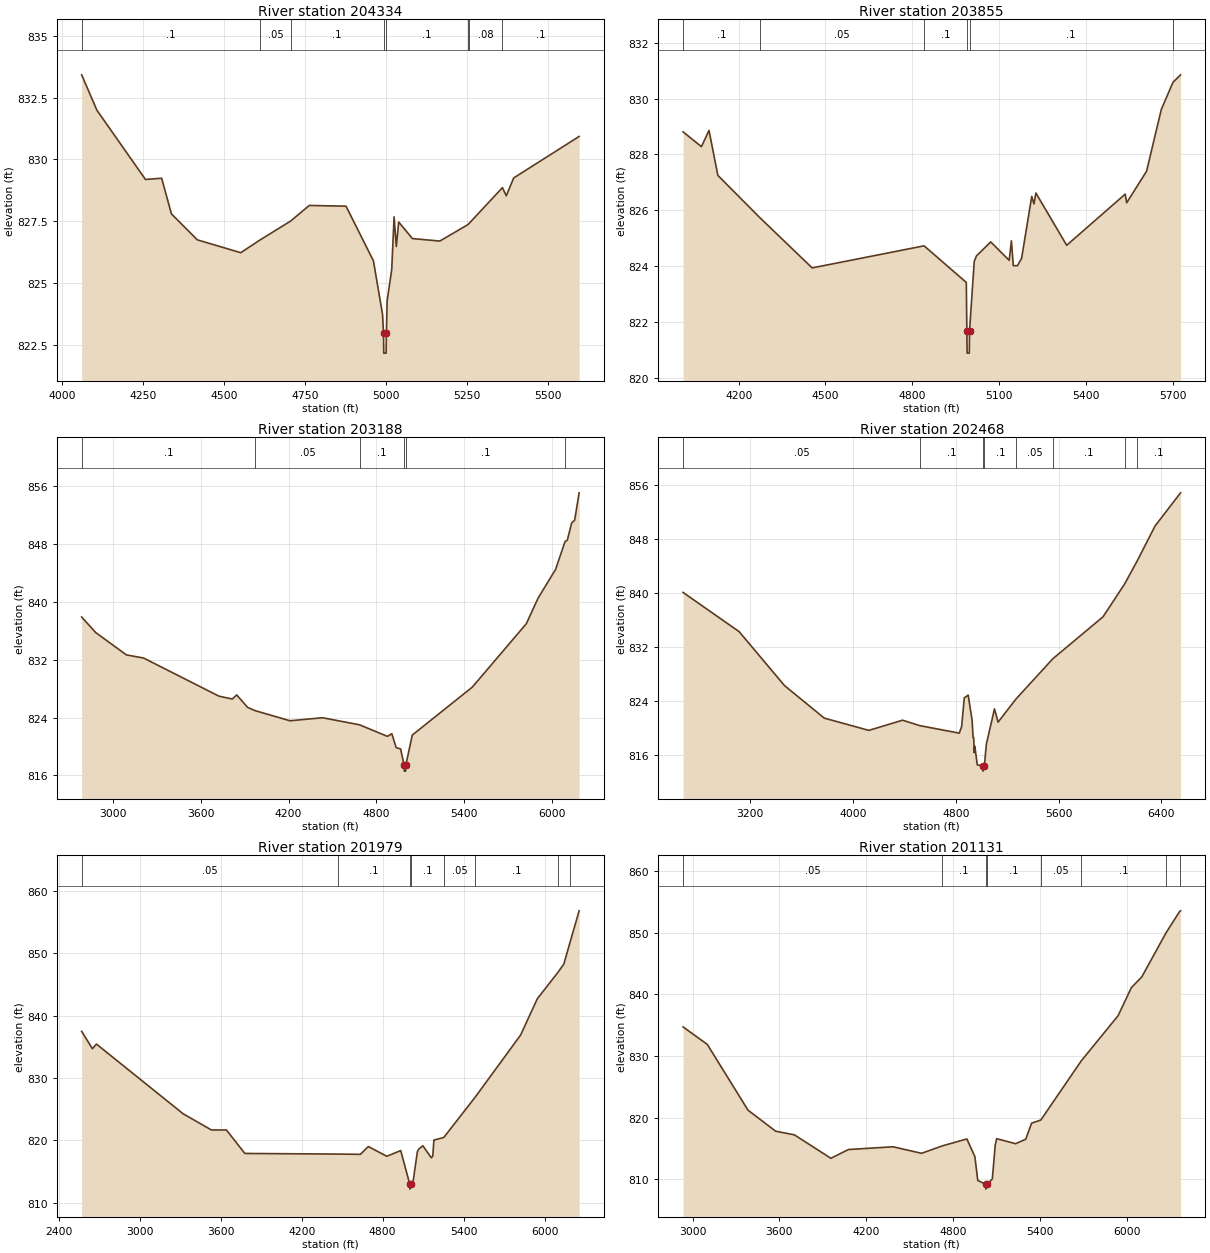
Type RM Length L Ch R = 1 ,204334  ,479,479,479
BEGIN DESCRIPTION:
Mapping XS 71d45b7f
END DESCRIPTION:
XS GIS Cut Line= 4
      1972632.08     13636310.74      1972270.06     13636297.71
      1971678.91     13636847.19      1971522.78     13637180.28
#Sta/Elev= 30
  4060.3  833.42  4107.4  831.99  4257.5  829.19  4307.5  829.24  4337.6   827.8
  4417.6  826.75  4551.8  826.23  4612.2  826.75  4706.1  827.51  4763.8  828.14
  4877.2  828.11  4961.9   825.9  4990.1  823.73    4993  822.97  4993.8  822.17
  5001.1  822.17  5001.9  822.97  5004.2  824.28  5018.4  825.55  5025.7  827.68
  5032.6  826.48  5039.9  827.47  5082.4   826.8  5166.9   826.7  5253.3  827.36
  5255.9  827.39  5360.5  828.86  5372.4  828.53  5395.2  829.25  5597.5  830.93
#Mann= 8 ,-1 , 0
  4060.3      .1       0  4612.2     .05       0  4706.1      .1       0
    4993     .07       0  5001.9      .1       0  5253.3     .05       0
  5255.9     .08       0  5360.5      .1       0
Bank Sta=4993,5001.9
XS Rating Curve= 0 ,0
Exp/Cntr=0.3,0.1

Type RM Length L Ch R = 1 ,203855  ,667,667,667
BEGIN DESCRIPTION:
Mapping XS d54751b2
END DESCRIPTION:
XS GIS Cut Line= 4
      1972533.06     13636151.88      1971900.26     13636029.49
      1971444.54     13636565.94      1971374.26     13636930.31
#Sta/Elev= 30
  4007.7  828.81  4071.1  828.28  4097.4  828.86    4128  827.25    4273  825.74
  4453.9  823.94  4840.8  824.73  4986.7  823.42  4988.6  821.69  4989.5  820.89
    4997  820.89  4997.8  821.69  5014.1  824.17  5021.8  824.37  5071.2  824.87
  5134.9  824.21  5142.6  824.91  5149.2  824.02  5163.5  824.02  5177.8  824.28
  5212.9   826.5  5220.6  826.23  5227.2  826.62  5333.7  824.75  5535.9  826.58
    5541  826.27  5609.8   827.4  5660.7  829.61    5701  830.58  5727.2  830.85
#Mann= 6 ,-1 , 0
  4007.7      .1       0    4273     .05       0  4840.8      .1       0
  4988.6     .07       0  4997.8      .1       0    5701     .05       0
Bank Sta=4988.6,4997.8
XS Rating Curve= 0 ,0
Exp/Cntr=0.3,0.1

Type RM Length L Ch R = 1 ,203188  ,720,720,720
BEGIN DESCRIPTION:
Black Creek 214.0
END DESCRIPTION:
XS GIS Cut Line= 3
      1973514.49     13636213.95      1971519.66     13635922.28
      1970134.21     13635917.07
#Sta/Elev= 30
  2785.1  837.92  2881.1  835.77  3090.9  832.68    3209  832.24  3724.5  826.96
  3815.4  826.57    3845  827.14  3919.9  825.41  3971.5  824.96  4209.6  823.56
  4431.9  823.98  4685.6     823  4875.8   821.4  4905.8  821.77  4935.8  819.84
  4965.8  819.66  4990.3  817.39  4991.1  816.59  5000.5  816.59  5001.2  817.39
  5045.8  821.58  5455.8  828.21  5825.8     837  5905.8  840.53  6025.8  844.52
  6089.8  848.34  6105.8  848.56  6135.8  850.96  6155.8  851.31  6186.6  855.11
#Mann= 6 ,-1 , 0
  2785.1      .1       0  3971.5     .05       0  4685.6      .1       0
  4990.3     .07       0  5001.2      .1       0  6089.8     .05       0
Bank Sta=4990.3,5001.2
XS Rating Curve= 0 ,0
Exp/Cntr=0.3,0.1

Type RM Length L Ch R = 1 ,202468  ,489,489,489
BEGIN DESCRIPTION:
Black Creek 213.0
END DESCRIPTION:
XS GIS Cut Line= 3
      1973623.82     13635635.82      1971405.08     13635219.16
       1969808.1     13635427.23
#Sta/Elev= 30
  2680.3  840.05  3116.6  834.23    3469  826.24    3778  821.42  4124.8   819.6
  4387.4  821.11  4519.3  820.31    4828  819.19  4846.3  820.16  4866.7  824.41
  4897.2  824.83  4927.7   821.1  4935.5  818.49  4940.4  818.49  4943.7   816.3
  4948.7  817.22  4968.2  814.48  5012.2  814.36  5012.9  813.56  5023.1  814.36
  5038.7  817.57  5101.7  822.79  5129.5  820.82  5270.3  824.28    5555  830.21
  5945.9  836.44  6113.8  841.31  6213.4  844.79  6349.7  849.88  6548.3  854.81
#Mann= 8 ,-1 , 0
  2680.3     .05       0  4519.3      .1       0  5012.2     .07       0
  5023.1      .1       0  5270.3     .05       0    5555      .1       0
  6113.8     .08       0  6213.4      .1       0
Bank Sta=5012.2,5023.1
XS Rating Curve= 0 ,0
Exp/Cntr=0.3,0.1

Type RM Length L Ch R = 1 ,201979  ,848,848,848
BEGIN DESCRIPTION:
Black Creek 212.0
END DESCRIPTION:
XS GIS Cut Line= 3
      1973634.27     13634948.32      1972248.83     13635042.07
        1970025.       13634475.
#Sta/Elev= 30
  2571.1   837.5  2650.6  834.72  2680.6  835.46  3322.1  824.29  3532.6  821.68
  3642.8  821.69  3779.5  817.92    4470  817.82  4634.5  817.78  4693.9  819.03
  4830.5  817.47  4933.7  818.38  5000.5     813  5001.3   812.2  5011.4     813
  5026.6  813.62  5056.6  818.17  5067.9  818.65  5097.5  819.15  5160.8  817.22
  5171.1  817.52  5179.2  820.06  5252.8  820.49  5486.7     827  5821.3  836.91
  5945.1  842.73  6098.3  846.98  6141.2  848.29  6187.2  851.77  6254.7  856.83
#Mann= 8 ,-1 , 0
  2571.1     .05       0    4470      .1       0  5000.5     .07       0
  5011.4      .1       0  5252.8     .05       0  5486.7      .1       0
  6098.3     .05       0  6187.2      .1       0
Bank Sta=5000.5,5011.4
XS Rating Curve= 0 ,0
Exp/Cntr=0.3,0.1

Type RM Length L Ch R = 1 ,201131  ,516,516,516
BEGIN DESCRIPTION:
Mapping XS 617c8fb3
END DESCRIPTION:
XS GIS Cut Line= 4
      1973491.43     13634389.73      1971748.35     13634209.17
      1970845.58     13634299.45      1970081.68     13634146.67
#Sta/Elev= 30
  2934.3   834.7  3101.6  831.87  3383.1   821.2  3574.1  817.79    3704  817.19
  3956.2  813.39  4076.8  814.81  4385.5  815.26  4583.1   814.2  4725.8   815.4
    4896  816.53  4951.4  813.66  4971.5  809.79  5026.3  809.19    5027  808.39
  5037.3  809.19    5072  810.04    5092  815.51  5102.1  816.57  5232.8  815.76
  5303.1  816.49  5343.3  819.09    5407  819.59  5686.7  829.19  5941.3  836.52
  6033.1  841.07  6105.3  842.82  6274.2  850.02  6366.6  853.42    6373  853.53
#Mann= 8 ,-1 , 0
  2934.3     .05       0  4725.8      .1       0  5026.3     .07       0
  5037.3      .1       0    5407     .05       0  5686.7      .1       0
  6274.2     .05       0  6366.6      .1       0
Bank Sta=5026.3,5037.3
XS Rating Curve= 0 ,0
Exp/Cntr=0.3,0.1

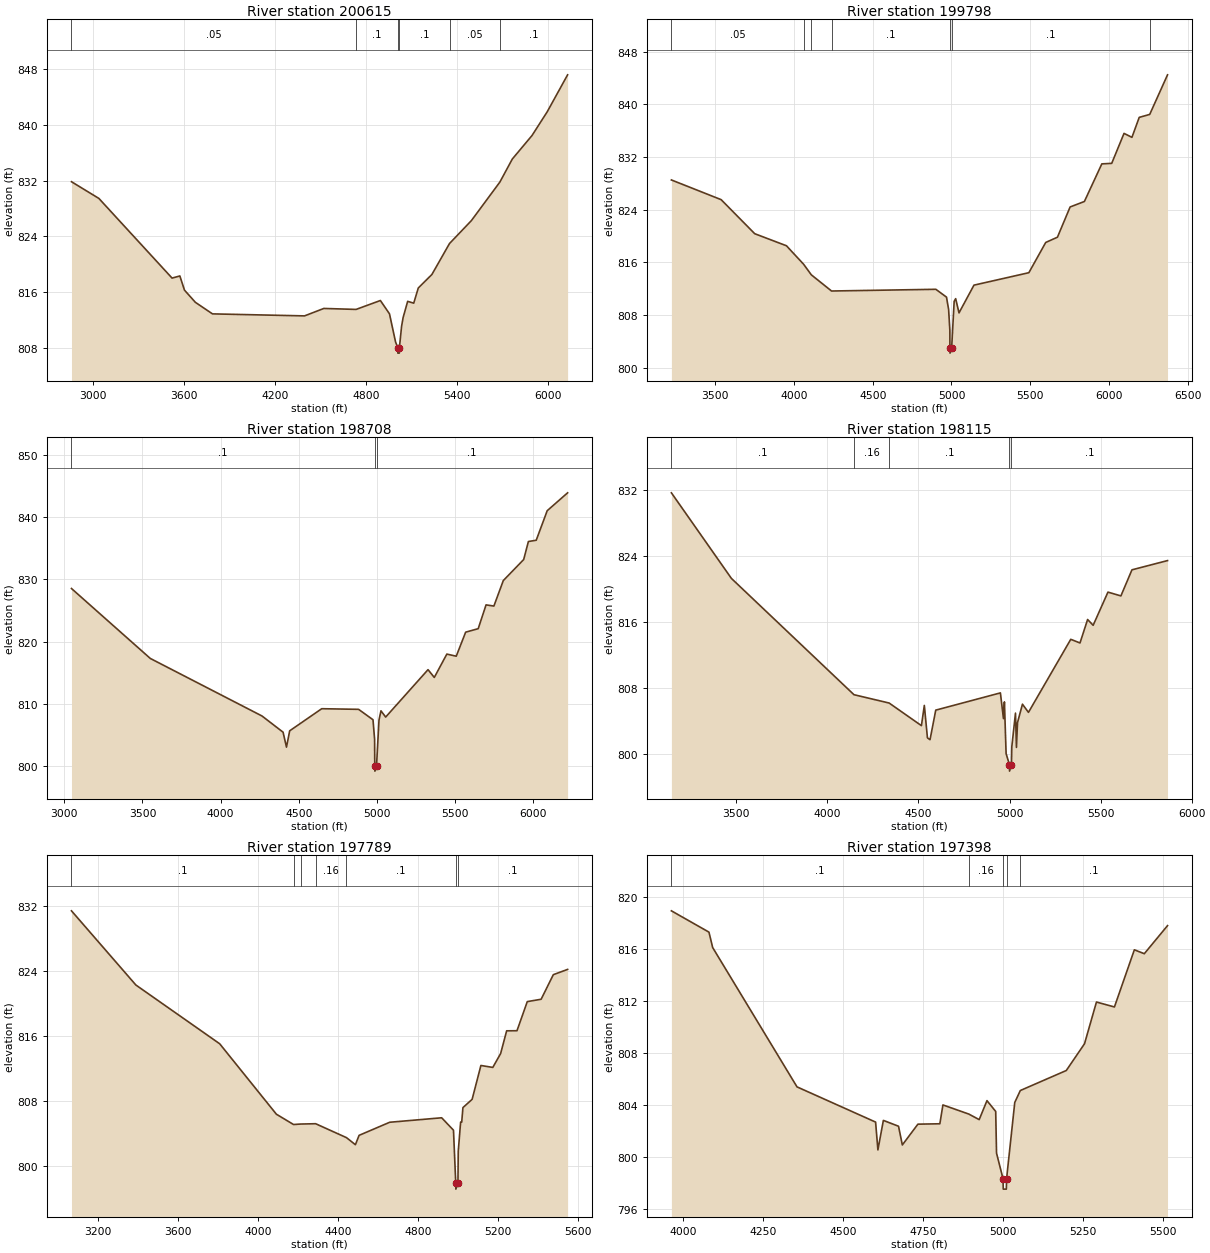
Type RM Length L Ch R = 1 ,200615  ,817,817,817
BEGIN DESCRIPTION:
Mapping XS 90a8a574
END DESCRIPTION:
XS GIS Cut Line= 4
      1973532.55     13634120.35      1972330.24     13633851.24
      1970819.82     13633812.18      1970290.32     13633816.52
#Sta/Elev= 30
  2858.2  831.86    3039  829.46  3521.8  818.01    3573  818.32  3603.7  816.28
  3675.5  814.53  3788.2  812.87  4395.6  812.58  4522.9  813.65  4735.5  813.51
  4895.8  814.79  4955.8  812.88  4995.8  808.84  5010.3  808.03    5011  807.23
  5020.6  807.23  5021.3  808.03  5035.8   811.1  5045.8  812.35  5075.8  814.67
  5115.8  814.41  5145.8  816.59  5235.9  818.54  5351.8  822.98    5496  826.27
    5684  831.81    5766  835.12    5896   838.5    5996   841.9  6130.7  847.22
#Mann= 6 ,-1 , 0
  2858.2     .05       0  4735.5      .1       0  5010.3     .07       0
  5021.3      .1       0  5351.8     .05       0    5684      .1       0
Bank Sta=5010.3,5021.3
XS Rating Curve= 0 ,0
Exp/Cntr=0.3,0.1

Type RM Length L Ch R = 1 ,199798  ,1090,1090,1090
BEGIN DESCRIPTION:
Mapping XS fb6bc21d
END DESCRIPTION:
XS GIS Cut Line= 4
      1973632.35     13633898.99      1972295.52     13633642.91
      1971427.46      13633113.4       1970660.5     13633200.06
#Sta/Elev= 30
  3221.9  828.52  3537.7  825.53  3750.9  820.36  3952.3  818.53  4061.4  815.72
  4110.1  814.12  4238.6  811.66  4900.8  811.92  4968.5  810.73  4981.9  808.85
  4989.8  805.69  4990.1  803.03  4990.9  802.23  5001.2  803.03  5017.1   810.1
  5026.6   810.5  5047.9  808.34  5142.8  812.55  5491.3  814.44  5598.4  819.03
  5672.8  819.83  5753.3  824.42  5843.9  825.25  5954.6  830.96  6017.4  831.04
  6095.5  835.59  6145.8  834.99    6192  838.02  6258.6  838.47  6371.7  844.48
#Mann= 7 ,-1 , 0
  3221.9     .05       0  4061.4      .1       0  4110.1     .16       0
  4238.6      .1       0  4990.1     .07       0  5001.2      .1       0
  6258.6     .16       0
Bank Sta=4990.1,5001.2
XS Rating Curve= 0 ,0
Exp/Cntr=0.3,0.1

Type RM Length L Ch R = 1 ,198708  ,593,593,593
BEGIN DESCRIPTION:
Black Creek 206.0
END DESCRIPTION:
XS GIS Cut Line= 3
      1973996.95     13633009.24        1972075.       13632575.
      1970874.96       13632475.
#Sta/Elev= 30
  3045.8  828.51  3550.2  817.28  4265.1  808.04  4399.8  805.44  4421.6  803.04
  4442.1  805.66  4647.1  809.21  4882.9  809.11  4975.2  807.44  4985.4  804.31
  4986.5  799.99  4987.2  799.19  4997.6  799.99  5013.6   807.4  5026.2  808.87
  5056.3  807.87  5327.3  815.48  5367.4  814.23  5447.7  817.98  5507.9  817.64
  5568.1   821.5  5648.4  822.06  5698.6  825.88  5748.7  825.69  5808.9  829.78
  5939.4  833.16  5969.5  836.05  6019.7  836.26  6089.9     841  6220.4  843.87
#Mann= 3 ,-1 , 0
  3045.8      .1       0  4986.5     .07       0  4997.6      .1       0
Bank Sta=4986.5,4997.6
XS Rating Curve= 0 ,0
Exp/Cntr=0.3,0.1

Type RM Length L Ch R = 1 ,198115  ,326,326,326
BEGIN DESCRIPTION:
Black Creek 205.0
END DESCRIPTION:
XS GIS Cut Line= 3
      1974124.96     13632674.99      1971987.36     13632032.67
      1971502.95     13631946.72
#Sta/Elev= 30
  3143.5  831.68    3473  821.31  4145.9  807.22  4339.1  806.21  4516.3  803.47
  4532.2  805.92  4549.3  801.99  4563.5  801.77  4594.9  805.35  4949.9  807.44
  4966.7  804.32  4971.9  806.35  4981.2  800.08  4999.4  798.76  5000.1  797.96
  5010.5  798.76  5012.5  800.91  5032.7  804.99    5038  800.83  5043.8  803.84
    5071  806.07    5104  805.08  5336.2  813.93  5386.9  813.49  5428.7  816.33
  5459.2  815.63  5540.4  819.65  5611.5  819.19  5672.2  822.35  5867.5  823.47
#Mann= 5 ,-1 , 0
  3143.5      .1       0  4145.9     .16       0  4339.1      .1       0
  4999.4     .07       0  5010.5      .1       0
Bank Sta=4999.4,5010.5
XS Rating Curve= 0 ,0
Exp/Cntr=0.3,0.1

Type RM Length L Ch R = 1 ,197789  ,391,391,391
BEGIN DESCRIPTION:
Black Creek 204.0
END DESCRIPTION:
XS GIS Cut Line= 3
      1974125.01     13632625.01        1972325.       13631875.
      1971839.92     13631655.12
#Sta/Elev= 30
  3067.1  831.39  3389.4  822.27  3808.7  815.05  4092.5  806.39  4178.4  805.12
    4214  805.18  4288.9  805.22  4443.1  803.51  4487.9  802.64  4506.3  803.79
  4659.6   805.4  4919.6  805.95  4978.7  804.42  4989.9  797.98  4990.6  797.18
    5001  797.98  5002.5  801.82  5014.4  805.42  5019.9  805.42  5025.9   807.2
    5072  808.22  5115.9  812.38  5175.4  812.14  5214.7  813.85  5244.7  816.64
  5296.4  816.65    5348  820.23  5417.3  820.52  5478.2  823.54  5549.7  824.19
#Mann= 7 ,-1 , 0
  3067.1      .1       0  4178.4     .16       0    4214      .1       0
  4288.9     .16       0  4443.1      .1       0  4989.9     .07       0
    5001      .1       0
Bank Sta=4989.9,5001
XS Rating Curve= 0 ,0
Exp/Cntr=0.3,0.1

Type RM Length L Ch R = 1 ,197398  ,753,753,753
BEGIN DESCRIPTION:
Black Creek 203.0
END DESCRIPTION:
XS GIS Cut Line= 3
      1973574.97     13632024.99      1972634.93     13631651.59
      1972125.03     13631475.01
#Sta/Elev= 30
    3964  818.93  4081.4  817.29  4093.1   816.1  4356.7  805.38  4602.4  802.67
  4609.6  800.53  4626.7   802.8  4674.1  802.35    4686  800.91  4734.7  802.51
  4803.3  802.54  4812.9  803.99  4893.5  803.29  4926.3  802.86  4950.6  804.32
  4977.9  803.49  4980.5  800.28  5000.8  798.31  5001.5  797.51  5011.2  797.51
  5011.9  798.31  5037.5  804.18  5054.9   805.1  5198.6  806.64  5255.6   808.7
  5292.9  811.91  5349.1  811.53  5411.4  815.93  5442.5  815.63  5515.1  817.79
#Mann= 5 ,-1 , 0
    3964      .1       0  4893.5     .16       0  5000.8     .07       0
  5011.9     .16       0  5054.9      .1       0
Bank Sta=5000.8,5011.9
XS Rating Curve= 0 ,0
Exp/Cntr=0.3,0.1

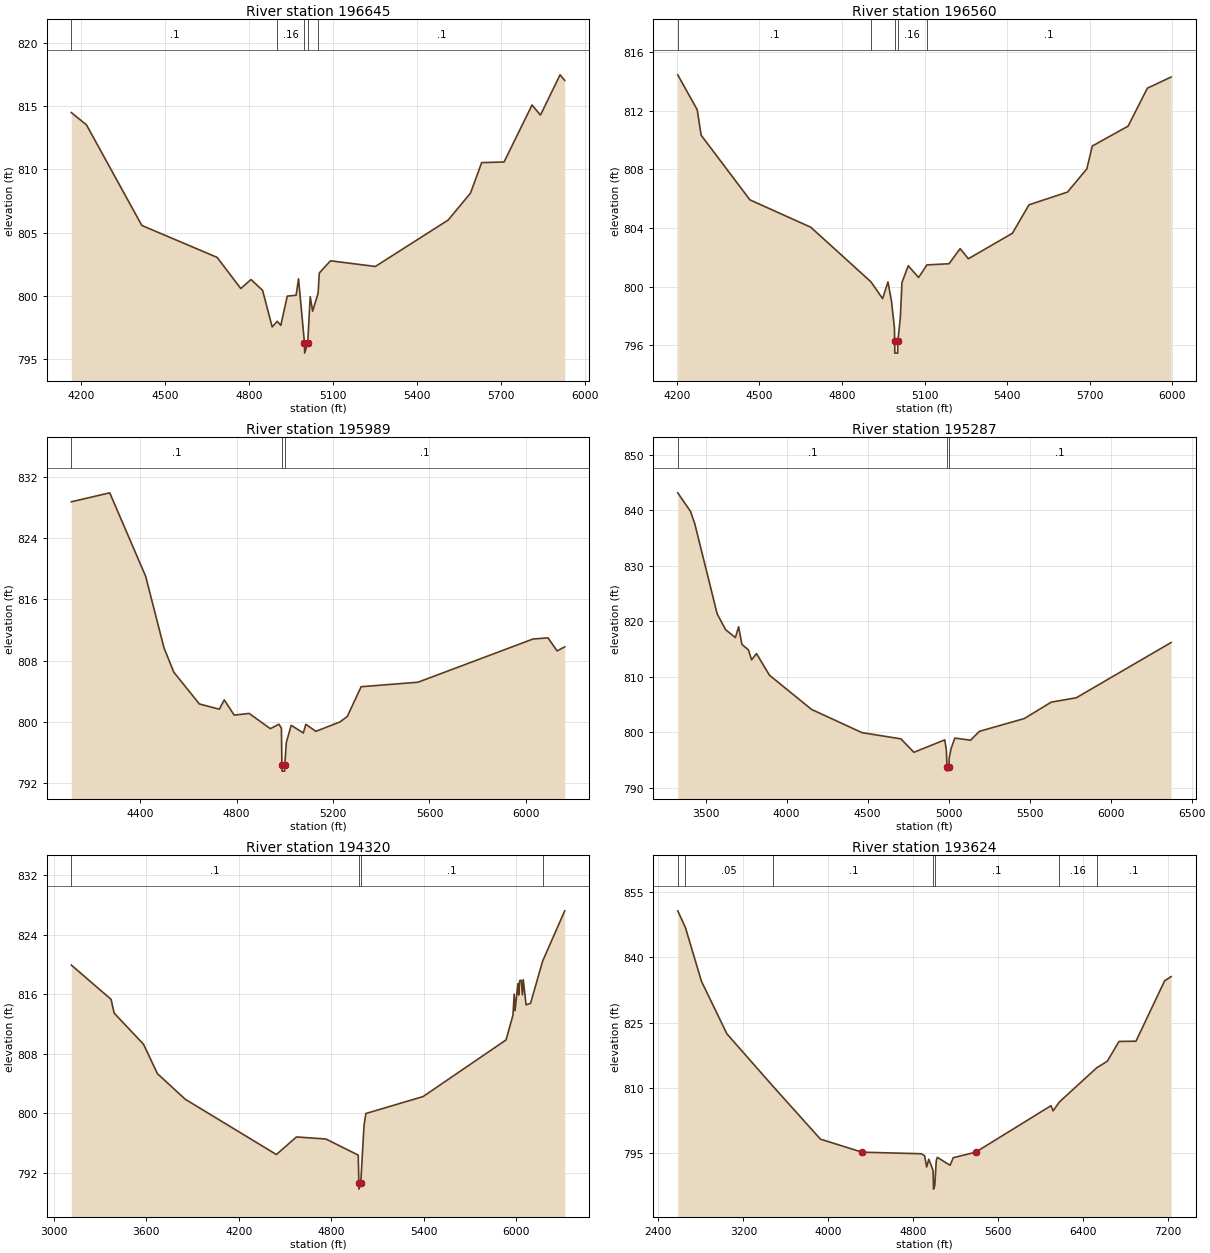
Type RM Length L Ch R = 1 ,196645  ,85,85,85
BEGIN DESCRIPTION:
Mapping XS 807d6c52
END DESCRIPTION:
XS GIS Cut Line= 5
      1973506.43      13631859.9       1973114.1     13631484.93
      1973055.07     13631245.34      1972982.15     13631193.26
      1972098.35     13631214.05
#Sta/Elev= 30
  4163.9  814.49    4218  813.52  4415.8  805.58  4684.7  803.06  4769.5   800.6
  4805.8  801.31  4847.3  800.46  4881.6  797.57  4899.9  798.01  4912.5  797.69
  4935.5     800  4967.2  800.07  4975.8  801.37  4997.1   796.3  4997.7   795.5
  5008.6   796.3  5017.6  799.96  5026.2  798.81  5045.8  800.24  5050.1  801.83
  5090.1  802.79  5250.2  802.34  5510.2     806  5590.3  808.13  5630.3  810.54
  5710.3  810.59  5810.3  815.09  5840.3  814.29  5910.4  817.47    5927  817.03
#Mann= 5 ,-1 , 0
  4163.9      .1       0  4899.9     .16       0  4997.1     .07       0
  5008.6     .16       0  5045.8      .1       0
Bank Sta=4997.1,5008.6
XS Rating Curve= 0 ,0
Exp/Cntr=0.3,0.1

Type RM Length L Ch R = 1 ,196560  ,571,571,571
BEGIN DESCRIPTION:
Mapping XS 4998dc0b
END DESCRIPTION:
XS GIS Cut Line= 5
      1973534.24     13631835.62      1973173.12     13631405.06
      1973082.85     13631168.95      1972996.04     13631120.34
      1972118.77     13631123.81
#Sta/Elev= 30
  4203.5  814.46  4274.2  812.08  4288.5  810.34  4465.5  805.93  4686.6  804.06
  4904.8  800.34  4947.5  799.19  4966.9  800.33  4979.6  799.02  4990.3   797.2
  4991.2  796.27  4991.8  795.47    5002  795.47  5002.7  796.27  5011.8   797.9
  5017.7  800.29  5040.5  801.43  5078.1  800.63  5108.1  801.49  5188.8  801.57
  5228.8   802.6  5258.8  801.91  5418.8  803.65  5478.8  805.59  5618.8  806.46
  5688.8  808.04  5708.8   809.6  5838.8  810.96  5908.8  813.55    5995  814.31
#Mann= 5 ,-1 , 0
  4203.5      .1       0  4904.8     .16       0  4991.2     .07       0
  5002.7     .16       0  5108.1      .1       0
Bank Sta=4991.2,5002.7
XS Rating Curve= 0 ,0
Exp/Cntr=0.3,0.1

Type RM Length L Ch R = 1 ,195989  ,702,702,702
BEGIN DESCRIPTION:
Black Creek 201.0
END DESCRIPTION:
XS GIS Cut Line= 3
      1973949.21     13630917.23      1973128.85     13630704.54
      1971943.94     13630891.18
#Sta/Elev= 30
    4114  828.76  4273.3  829.93  4422.4  819.02  4498.4  809.68    4539   806.5
  4645.2  802.34  4727.9  801.65  4748.5  802.87  4789.8  800.88  4851.8   801.1
  4939.7  799.11  4975.5  799.69  4985.6  799.17  4987.7  794.36  4988.3  793.56
    4999  793.56  4999.5  794.36  5005.9  797.29  5026.1  799.55  5076.7  798.55
  5086.9  799.68  5128.7  798.76  5228.6  799.99    5259   800.7  5316.3  804.59
  5552.5  805.18  6029.1  810.82  6091.6  810.98  6129.6  809.27    6161   809.8
#Mann= 3 ,-1 , 0
    4114      .1       0  4987.7     .07       0  4999.5      .1       0
Bank Sta=4987.7,4999.5
XS Rating Curve= 0 ,0
Exp/Cntr=0.3,0.1

Type RM Length L Ch R = 1 ,195287  ,967,967,967
BEGIN DESCRIPTION:
Black Creek 200.0
END DESCRIPTION:
XS GIS Cut Line= 3
      1974600.25     13629975.37        1972925.       13630075.
      1971658.78     13630591.18
#Sta/Elev= 30
  3327.6  843.13  3406.8  839.77    3433  837.54  3571.1  821.33  3623.4  818.48
  3683.5  817.07  3703.5  819.02  3723.5  815.84  3763.6  814.86  3783.7  813.06
  3813.7  814.19  3893.8  810.29  4154.3  804.12  4464.9  799.95  4705.3  798.83
  4785.4  796.41  4975.8  798.65  4985.8  796.82  4989.8  793.82  4990.3  793.02
  5001.8  793.82  5003.3  795.39  5015.1  797.09  5038.2  798.97  5135.4  798.59
  5189.4  800.18  5467.1  802.49  5632.9  805.44    5788  806.23  6373.2  816.18
#Mann= 3 ,-1 , 0
  3327.6      .1       0  4989.8     .07       0  5001.8      .1       0
Bank Sta=4989.8,5001.8
XS Rating Curve= 0 ,0
Exp/Cntr=0.3,0.1

Type RM Length L Ch R = 1 ,194320  ,696,696,696
BEGIN DESCRIPTION:
Black Creek 199.0
END DESCRIPTION:
XS GIS Cut Line= 3
      1974422.26     13629515.31        1972525.       13629375.
      1971325.04     13629874.98
#Sta/Elev= 30
  3113.4   819.9  3371.4  815.29  3391.4  813.44  3581.9  809.26  3672.2  805.31
  3852.7  801.87  4444.3  794.44  4574.6   796.8  4765.2  796.53  4975.7  794.36
  4979.8  790.59  4980.3  789.79  4991.8  790.59  5013.3  798.36  5025.1  799.95
  5396.6  802.23  5935.1  809.84    5980  813.18  5988.1  816.01  5993.6  813.77
    6012  817.41  6017.4  815.88  6023.3   817.8  6034.2  817.85  6041.2   815.9
  6046.6  817.94  6065.1  814.55  6094.3  814.77  6172.4  820.43  6315.8  827.19
#Mann= 4 ,-1 , 0
  3113.4      .1       0  4979.8     .07       0  4991.8      .1       0
  6172.4     .16       0
Bank Sta=4979.8,4991.8
XS Rating Curve= 0 ,0
Exp/Cntr=0.3,0.1

Type RM Length L Ch R = 1 ,193624  ,146,146,146
BEGIN DESCRIPTION:
Mapping XS 6a6b205f
END DESCRIPTION:
XS GIS Cut Line= 2
      1975048.29     13628685.74      1970404.29      13628746.5
#Sta/Elev= 30
  2582.3  850.62  2654.5   846.8  2805.6  834.46  3045.6   822.4  3480.7  810.35
  3925.7  798.27 4317.61  795.28  4875.8  794.92  4905.8  794.48  4925.8  791.89
  4945.8  793.65  4965.8  792.41  4985.8  791.09  4989.8  787.61  4990.3  786.81
  5001.8  787.61  5015.8  793.33  5025.8   794.1  5145.8  792.28  5175.8  794.01
 5386.92  795.28  6095.9  805.94  6115.9  804.75  6174.8  806.79  6525.8  814.62
  6625.9  816.13  6735.9  820.67    6896  820.73    7166  834.59  7226.7  835.53
#Mann= 7 ,-1 , 0
  2582.3     .08       0  2654.5     .05       0  3480.7      .1       0
  4989.8     .07       0  5001.8      .1       0  6174.8     .16       0
  6525.8      .1       0
Bank Sta=4317.61,5386.92
XS Rating Curve= 0 ,0
Exp/Cntr=0.3,0.1