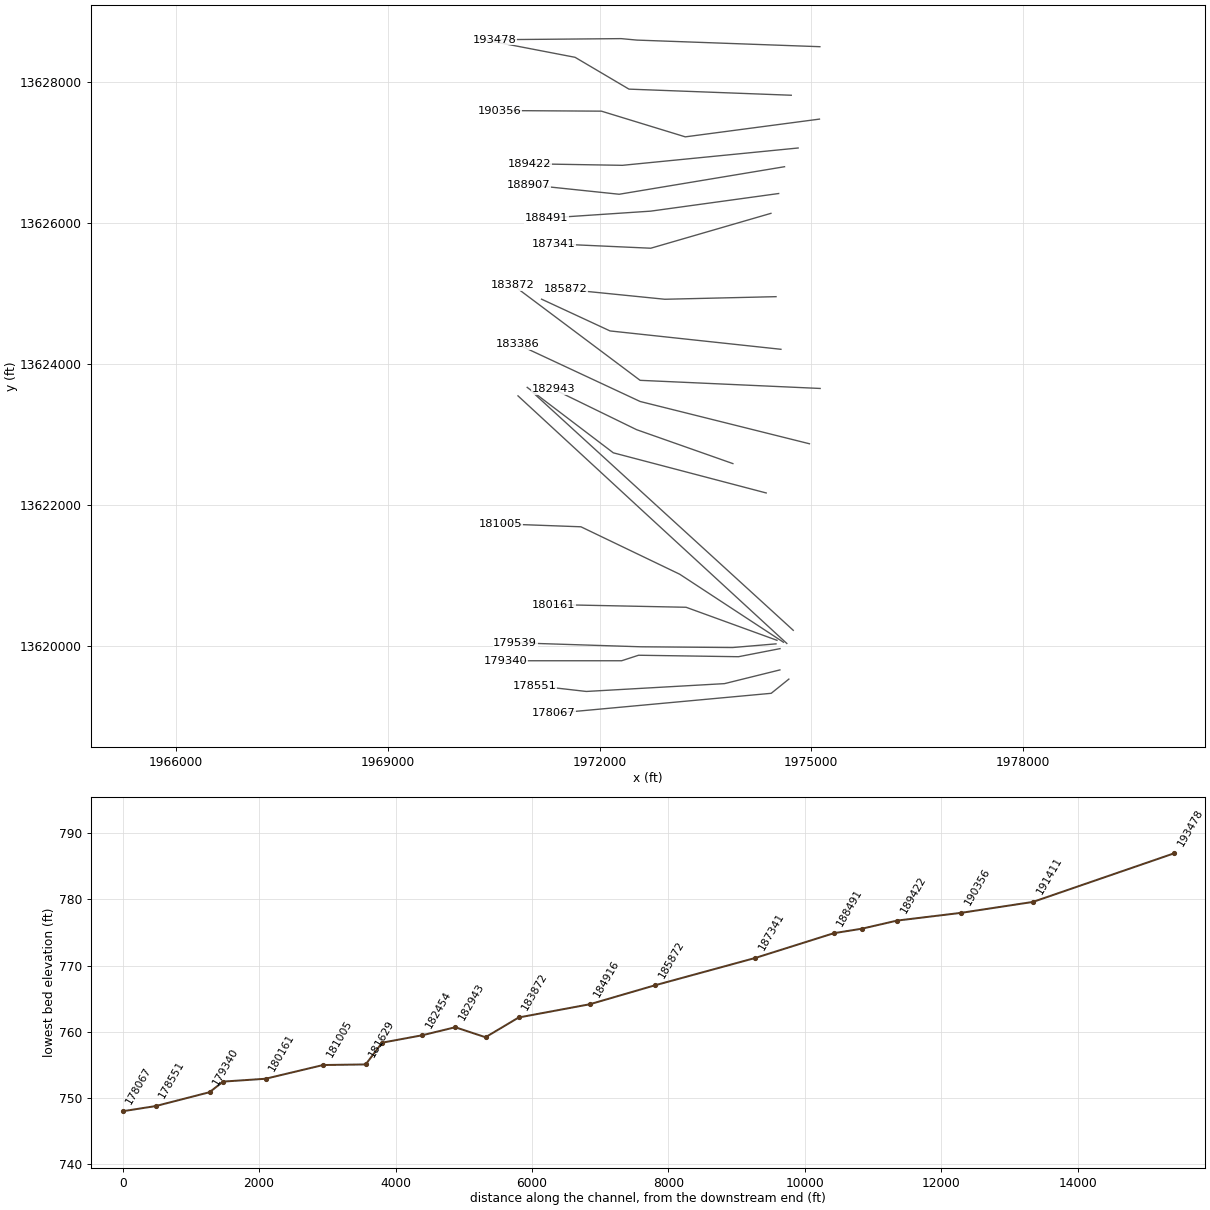
HEC-RAS study Black Creek.prj: Black Creek Base Level Engineering

--- Black Creek.g01 (geometry) --- (continued)

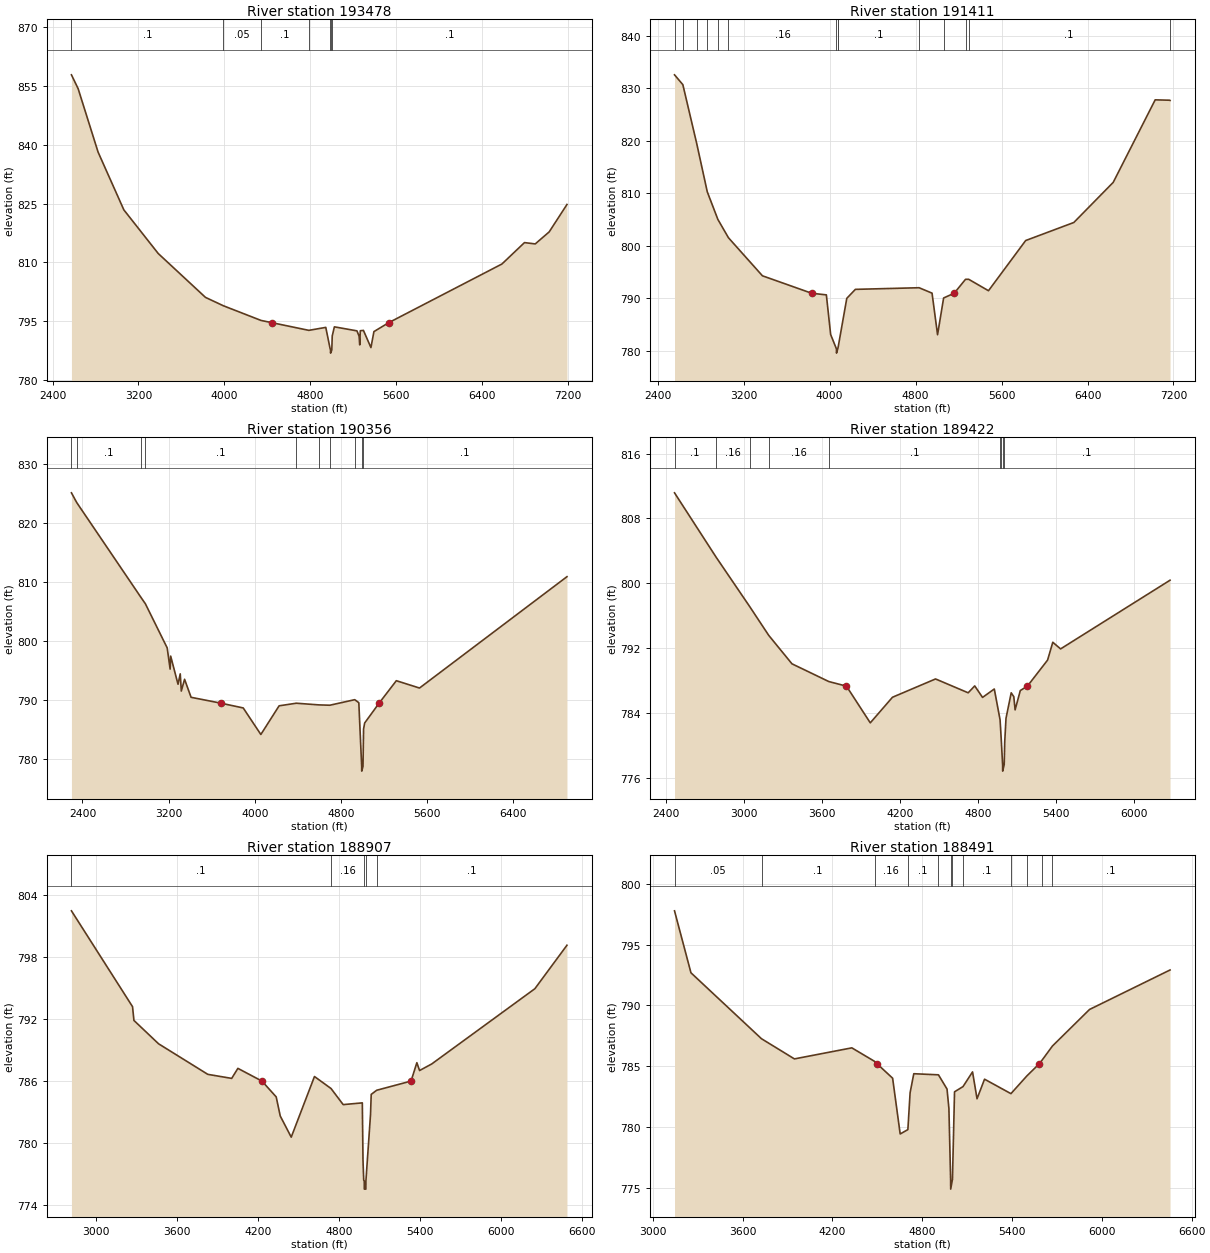
Type RM Length L Ch R = 1 ,193478  ,2067,2067,2067
BEGIN DESCRIPTION:
Mapping XS e2ab1fba
END DESCRIPTION:
XS GIS Cut Line= 4
      1975122.99     13628507.78      1972529.24     13628601.53
      1972305.28     13628622.37      1970509.22     13628606.75
#Sta/Elev= 30
  2575.4  857.77  2637.6  854.26  2823.6   838.1  3063.7  823.39  3383.9  812.28
  3824.2  801.11  3990.7  798.98    4342  795.24 4443.21  794.67    4787  792.72
  4944.9  793.47  4984.1  788.22    4989  787.72  4989.5  786.92    5001  787.72
    5005  791.28    5025  793.61  5235.4  792.59  5255.4  791.22  5261.4  789.01
  5266.4  792.62  5295.6  792.71  5365.6  788.33  5393.4   792.4 5531.25  794.67
  6586.1  809.61  6796.1  815.06  6896.1  814.72  7026.1  817.78  7191.9  824.76
#Mann= 7 ,-1 , 0
  2575.4      .1       0  3990.7     .05       0    4342      .1       0
    4787     .16       0  4984.1      .1       0    4989     .07       0
    5001      .1       0
Bank Sta=4443.21,5531.25
XS Rating Curve= 0 ,0
Exp/Cntr=0.3,0.1

Type RM Length L Ch R = 1 ,191411  ,1055,1055,1055
BEGIN DESCRIPTION:
Mapping XS cdad18bf
END DESCRIPTION:
XS GIS Cut Line= 4
      1974717.34     13627819.13      1972417.05     13627905.93
      1971653.16     13628357.32      1970255.55     13628626.43
#Sta/Elev= 30
  2555.8  832.54  2633.4  830.67  2762.1   819.5  2860.7  810.29  2959.3  805.04
  3057.8  801.55  3374.1  794.31 3832.68  790.99  3969.2  790.68  4009.2  783.14
  4063.1   780.4  4063.6   779.6  4075.3   780.4  4079.5   780.8  4159.3  790.02
  4239.3  791.73  4832.4  792.04    4953  791.01  5004.3   783.1  5060.7  790.09
 5158.87  790.99  5264.7  793.64  5293.7  793.65  5478.3  791.47  5824.6  801.02
  6272.7  804.45  6639.3  812.08    7030  827.78  7164.9  827.71  7168.3  827.67
#Mann= 14 ,-1 , 0
  2555.8      .1       0  2633.4     .16       0  2762.1      .1       0
  2860.7     .16       0  2959.3      .1       0  3057.8     .16       0
  4063.1     .07       0  4075.3     .16       0  4079.5      .1       0
  4832.4     .16       0  5060.7      .1       0  5264.7     .16       0
  5293.7      .1       0  7164.9     .05       0
Bank Sta=3832.68,5158.87
XS Rating Curve= 0 ,0
Exp/Cntr=0.3,0.1

Type RM Length L Ch R = 1 ,190356  ,934,934,934
BEGIN DESCRIPTION:
Mapping XS 242380d1
END DESCRIPTION:
XS GIS Cut Line= 4
      1975116.71     13627480.59      1973215.66     13627228.85
      1972026.42     13627593.43      1970585.46     13627602.11
#Sta/Elev= 30
  2297.4  825.04  2347.3  823.37    2943  807.35  2984.1  806.27  3186.8   798.8
    3214  795.21  3219.1  797.41  3287.4  792.65  3307.9  794.41  3317.9   791.5
  3348.2  793.49  3408.7  790.44 3687.83  789.44  3892.9  788.64  4056.6  784.15
  4226.2     789  4385.7  789.44  4593.6  789.16  4697.5   789.1  4928.8  790.04
  4966.6  789.53  4993.2  778.75  4993.7  777.95  5005.4  778.75  5010.7  785.08
  5021.1   786.1 5154.58  789.44    5315  793.25  5530.3  792.01  6899.9  810.85
#Mann= 10 ,-1 , 0
  2297.4     .16       0  2347.3      .1       0    2943     .16       0
  2984.1      .1       0  4385.7     .16       0  4593.6      .1       0
  4697.5     .16       0  4928.8      .1       0  4993.2     .07       0
  5005.4      .1       0
Bank Sta=3687.83,5154.58
XS Rating Curve= 0 ,0
Exp/Cntr=0.3,0.1

Type RM Length L Ch R = 1 ,189422  ,515,515,515
BEGIN DESCRIPTION:
Black Creek 194.0
END DESCRIPTION:
XS GIS Cut Line= 3
      1974814.58     13627070.86        1972325.       13626825.
      1971012.58      13626846.9
#Sta/Elev= 30
  2464.1  811.15  2782.9  803.24  3042.7  797.11  3189.4  793.55  3368.1  790.04
  3651.8  787.85 3787.67  787.28    3971  782.75  4141.8  785.91  4473.4  788.17
  4724.6  786.46  4774.9  787.31  4835.2  785.89  4925.6  786.93    4970  783.13
    4979  780.72  4989.6  777.59  4990.1  776.79  5001.9  777.59  5005.8  780.37
  5015.8  783.32  5055.8  786.46  5075.8  785.98  5085.8  784.35  5125.8  786.74
 5180.26  787.28  5335.8   790.5  5375.9   792.7  5435.9  791.88  6278.4  800.36
#Mann= 9 ,-1 , 0
  2464.1      .1       0  2782.9     .16       0  3042.7      .1       0
  3189.4     .16       0  3651.8      .1       0    4970     .16       0
    4979      .1       0  4989.6     .07       0  5001.9      .1       0
Bank Sta=3787.67,5180.26
XS Rating Curve= 0 ,0
Exp/Cntr=0.3,0.1

Type RM Length L Ch R = 1 ,188907  ,416,416,416
BEGIN DESCRIPTION:
Black Creek 193.0
END DESCRIPTION:
XS GIS Cut Line= 3
      1974621.93     13626805.24      1972278.16     13626414.61
      1970988.43     13626549.83
#Sta/Elev= 30
  2817.3  802.51  3270.2  793.23  3280.5   791.9    3463  789.64    3828  786.68
  4005.2  786.29    4051  787.26 4229.23  786.03  4334.9   784.5    4365  782.65
  4446.4   780.6  4618.7  786.47  4741.4  785.31  4831.6  783.75  4973.3  783.92
  4978.4  778.32  4983.7  776.43  4987.7  776.37  4988.2  775.57  4999.5  775.57
    5000  776.37  5034.2  782.81  5039.2  784.74  5079.7  785.14 5334.64  786.03
  5377.6  787.81  5397.7  787.05  5488.2  787.69  6252.3  794.97  6490.2  799.18
#Mann= 5 ,-1 , 0
  2817.3      .1       0  4741.4     .16       0  4987.7     .07       0
    5000     .16       0  5079.7      .1       0
Bank Sta=4229.23,5334.64
XS Rating Curve= 0 ,0
Exp/Cntr=0.3,0.1

Type RM Length L Ch R = 1 ,188491  ,1150,1150,1150
BEGIN DESCRIPTION:
Black Creek 192.0
END DESCRIPTION:
XS GIS Cut Line= 3
      1974538.59     13626425.03        1972725.       13626175.
      1971248.45     13626076.17
#Sta/Elev= 30
    3145  797.79  3254.8  792.69  3726.2  787.26  3946.1   785.6  4329.7  786.51
  4481.2   785.4 4500.86  785.17  4602.2  784.01  4652.7  779.42  4704.1  779.78
  4718.9  782.81  4743.6  784.38  4908.3  784.29  4965.6  783.12  4978.2  781.52
  4989.6  775.68  4990.1  774.88  5001.9  775.68  5015.8  782.89  5072.4  783.32
  5136.1  784.53  5166.2  782.32  5216.3  783.93  5392.6  782.74  5499.1   784.2
 5579.65  785.17    5602  785.52  5669.9  786.66  5917.8  789.67  6455.6  792.92
#Mann= 12 ,-1 , 0
    3145     .05       0  3726.2      .1       0  4481.2     .16       0
  4704.1      .1       0  4908.3     .16       0  4989.6     .07       0
  5001.9     .16       0  5072.4      .1       0  5392.6     .16       0
  5499.1      .1       0    5602     .16       0  5669.9      .1       0
Bank Sta=4500.86,5579.65
XS Rating Curve= 0 ,0
Exp/Cntr=0.3,0.1

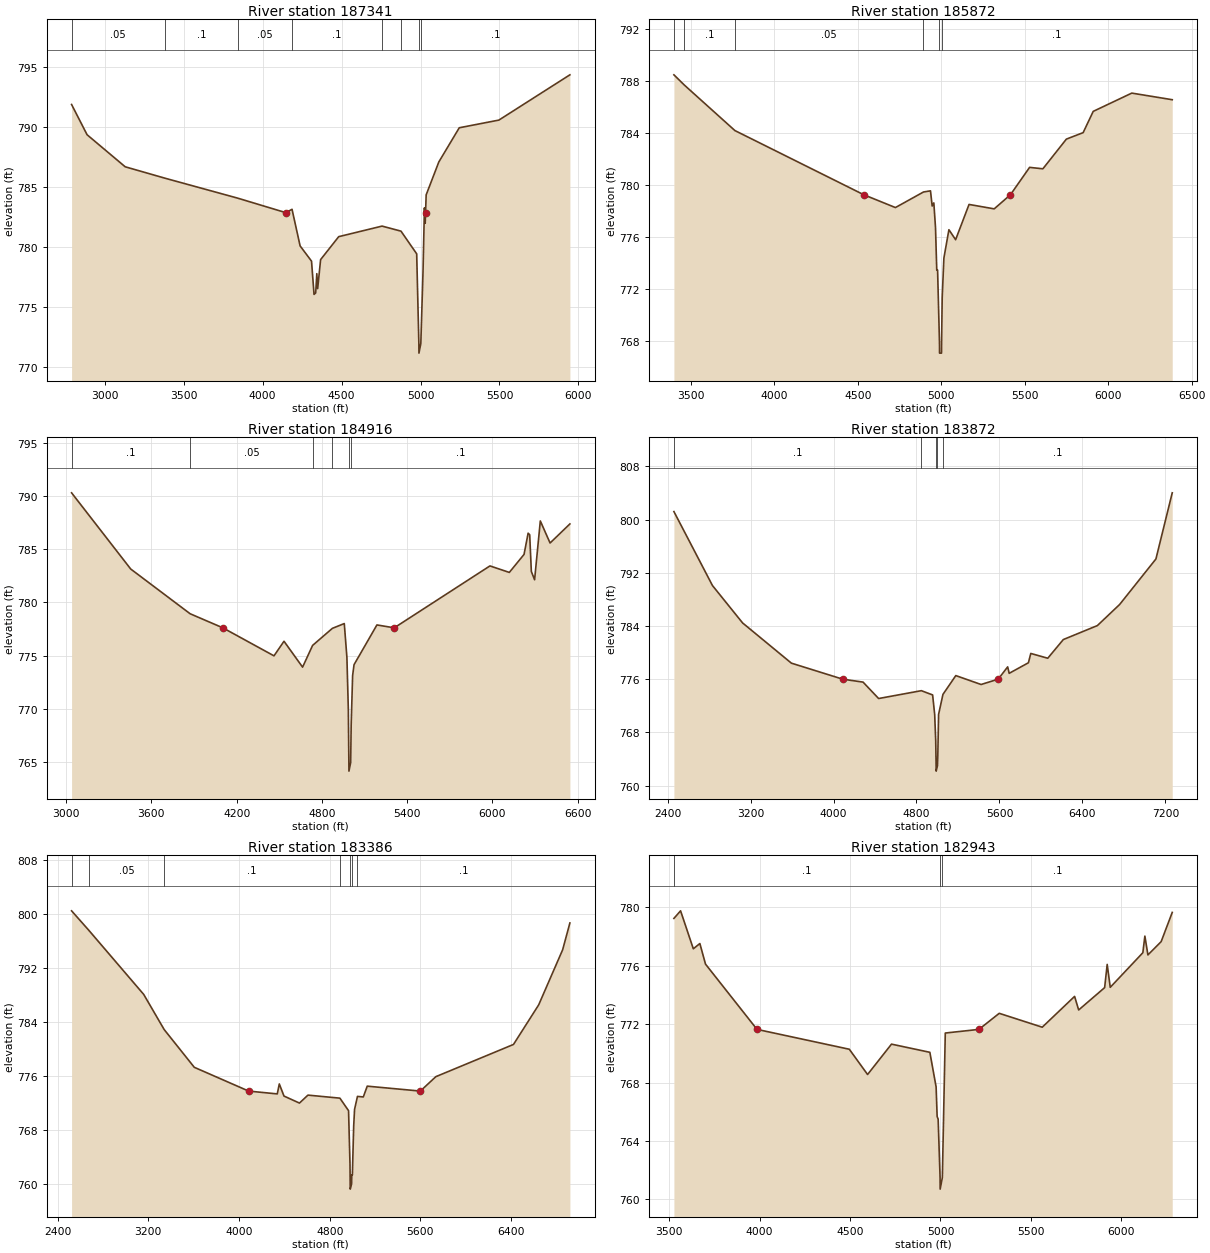
Type RM Length L Ch R = 1 ,187341  ,1469,1469,1469
BEGIN DESCRIPTION:
Black Creek 191.0
END DESCRIPTION:
XS GIS Cut Line= 3
      1974429.23     13626143.79      1972726.07     13625648.99
      1971345.87     13625711.49
#Sta/Elev= 30
  2790.7  791.86  2888.8  789.34  3130.2  786.67  3382.1  785.72    3842  784.06
 4147.28  782.85  4186.5  783.13  4237.7  780.08    4310  778.81  4325.9  776.04
  4336.3  776.16  4343.5  777.77  4348.8  776.52  4367.5  778.94  4482.1  780.85
  4756.5  781.73  4876.4  781.31  4975.8  779.42  4989.6  771.95  4990.1  771.15
  5001.9  771.95  5015.8  777.88  5024.8  783.25  5029.8  781.97 5032.04  782.85
  5035.8  784.33  5115.9  787.07  5245.4  789.92  5496.3  790.56  5945.9  794.33
#Mann= 8 ,-1 , 0
  2790.7     .05       0  3382.1      .1       0    3842     .05       0
  4186.5      .1       0  4756.5     .16       0  4876.4      .1       0
  4989.6     .07       0  5001.9      .1       0
Bank Sta=4147.28,5032.04
XS Rating Curve= 0 ,0
Exp/Cntr=0.3,0.1

Type RM Length L Ch R = 1 ,185872  ,956,956,956
BEGIN DESCRIPTION:
Black Creek 190.0
END DESCRIPTION:
XS GIS Cut Line= 3
      1974501.45     13624961.78        1972925.       13624925.
      1971524.05     13625065.94
#Sta/Elev= 30
  3398.8   788.5  3461.3  787.71  3764.1   784.2 4535.97  779.25  4725.6  778.26
  4893.6  779.46  4935.7  779.55  4945.7  778.38  4955.7  778.62  4965.7  776.72
  4973.2  773.44  4978.2  773.44  4989.5  767.83    4990  767.03  5001.6  767.03
  5002.1  767.83  5005.8  771.31  5015.9  774.36    5046  776.55  5086.2  775.78
  5166.6   778.5  5317.4  778.16 5414.62  779.25  5529.3  781.36  5608.9  781.25
  5749.6  783.54  5850.1  784.04  5910.4  785.68  6141.5  787.09  6383.7  786.58
#Mann= 6 ,-1 , 0
  3398.8     .16       0  3461.3      .1       0  3764.1     .05       0
  4893.6      .1       0  4989.5     .07       0  5002.1      .1       0
Bank Sta=4535.97,5414.62
XS Rating Curve= 0 ,0
Exp/Cntr=0.3,0.1

Type RM Length L Ch R = 1 ,184916  ,1044,1044,1044
BEGIN DESCRIPTION:
Black Creek 189.0
END DESCRIPTION:
XS GIS Cut Line= 3
      1974570.96     13624215.24      1972149.03     13624475.67
      1971178.43      13624926.3
#Sta/Elev= 30
  3038.6  790.29  3454.6  783.14  3872.8  778.94  4102.7  777.62  4462.7  774.99
  4533.1  776.36  4663.9  773.93  4734.4  775.97  4873.5  777.57  4957.2  778.02
  4975.7  774.85  4985.7  769.96  4989.5  764.97    4990  764.17  5002.1  764.97
  5005.8  768.56  5015.9  773.14  5025.9  774.16  5186.9  777.89 5308.91  777.62
    5982  783.43  6118.4  782.82    6222  784.51  6250.7   786.5  6261.7  786.36
  6273.3  782.91  6296.2  782.13  6336.5  787.65  6405.1  785.58  6544.6  787.37
#Mann= 6 ,-1 , 0
  3038.6      .1       0  3872.8     .05       0  4734.4      .1       0
  4873.5     .16       0  4989.5     .07       0  5002.1      .1       0
Bank Sta=4102.7,5308.91
XS Rating Curve= 0 ,0
Exp/Cntr=0.3,0.1

Type RM Length L Ch R = 1 ,183872  ,486,486,486
BEGIN DESCRIPTION:
Black Creek 188.0
END DESCRIPTION:
XS GIS Cut Line= 3
      1975126.47     13623659.69        1972575.       13623775.
      1970774.98     13625125.02
#Sta/Elev= 30
  2461.5  801.21  2833.3  790.08  3123.6  784.46  3594.1  778.41 4089.18     776
  4284.8  775.56    4435  773.09  4847.2  774.27  4955.5  773.63  4975.5  770.69
  4985.5  766.69  4989.3  762.97  4989.8  762.17  5001.9  762.97  5005.6  764.54
  5013.1   770.7  5055.1  773.71  5179.1  776.54  5422.9   775.2 5587.59     776
  5679.1  777.85  5693.7  776.88  5879.1  778.47    5902  779.87  6065.6  779.15
  6215.6  781.96  6543.7  784.06  6758.3  787.23  7108.3  794.08  7265.6  804.03
#Mann= 5 ,-1 , 0
  2461.5      .1       0  4847.2     .16       0  4989.3     .07       0
  5001.9     .16       0  5055.1      .1       0
Bank Sta=4089.18,5587.59
XS Rating Curve= 0 ,0
Exp/Cntr=0.3,0.1

Type RM Length L Ch R = 1 ,183386  ,443,443,443
BEGIN DESCRIPTION:
Black Creek 187.0
END DESCRIPTION:
XS GIS Cut Line= 3
      1974975.02     13622874.99        1972575.       13623475.
      1970834.19     13624288.27
#Sta/Elev= 30
  2523.3  800.49  2675.9  797.59  3159.8  788.08    3340  782.87  3605.6  777.27
 4085.14  773.74  4337.5  773.32  4355.5   774.8  4396.8     773  4533.3  771.96
  4608.1  773.14    4890  772.69  4966.3  770.83  4979.1   762.8  4980.6  759.99
  4981.1  759.19  4993.2  759.99  4994.6  761.28  4999.9  761.28  5011.4  768.48
  5019.3  771.03  5044.9  772.95  5096.5  772.87  5131.1  774.47 5599.49  773.74
  5736.3  775.88    6421  780.66  6643.2  786.53  6854.4   794.7  6918.6  798.69
#Mann= 7 ,-1 , 0
  2523.3      .1       0  2675.9     .05       0    3340      .1       0
    4890     .16       0  4980.6     .07       0  4993.2     .16       0
  5044.9      .1       0
Bank Sta=4085.14,5599.49
XS Rating Curve= 0 ,0
Exp/Cntr=0.3,0.1

Type RM Length L Ch R = 1 ,182943  ,489,489,489
BEGIN DESCRIPTION:
Black Creek 186.0
END DESCRIPTION:
XS GIS Cut Line= 3
      1973889.73     13622593.83        1972525.       13623075.
      1971349.04     13623648.91
#Sta/Elev= 30
    3526  779.24  3562.8  779.76  3633.3  777.16  3669.5  777.52  3700.7  776.11
 3985.57  771.64  4495.9  770.28  4596.9  768.55  4729.2  770.63  4941.3  770.07
  4975.9   767.7  4981.6  765.67  4987.1   765.5  4997.8   761.5  4998.3   760.7
  5010.4   761.5  5026.6  771.39 5212.68  771.64    5325  772.74  5562.8  771.79
  5741.7   773.9  5764.2  772.97  5907.8   774.5  5921.9  776.09  5938.8  774.52
  6119.1  776.89  6130.3  778.03  6147.1  776.74  6220.3  777.65  6281.6  779.65
#Mann= 3 ,-1 , 0
    3526      .1       0  4997.8     .07       0  5010.4      .1       0
Bank Sta=3985.57,5212.68
XS Rating Curve= 0 ,0
Exp/Cntr=0.3,0.1

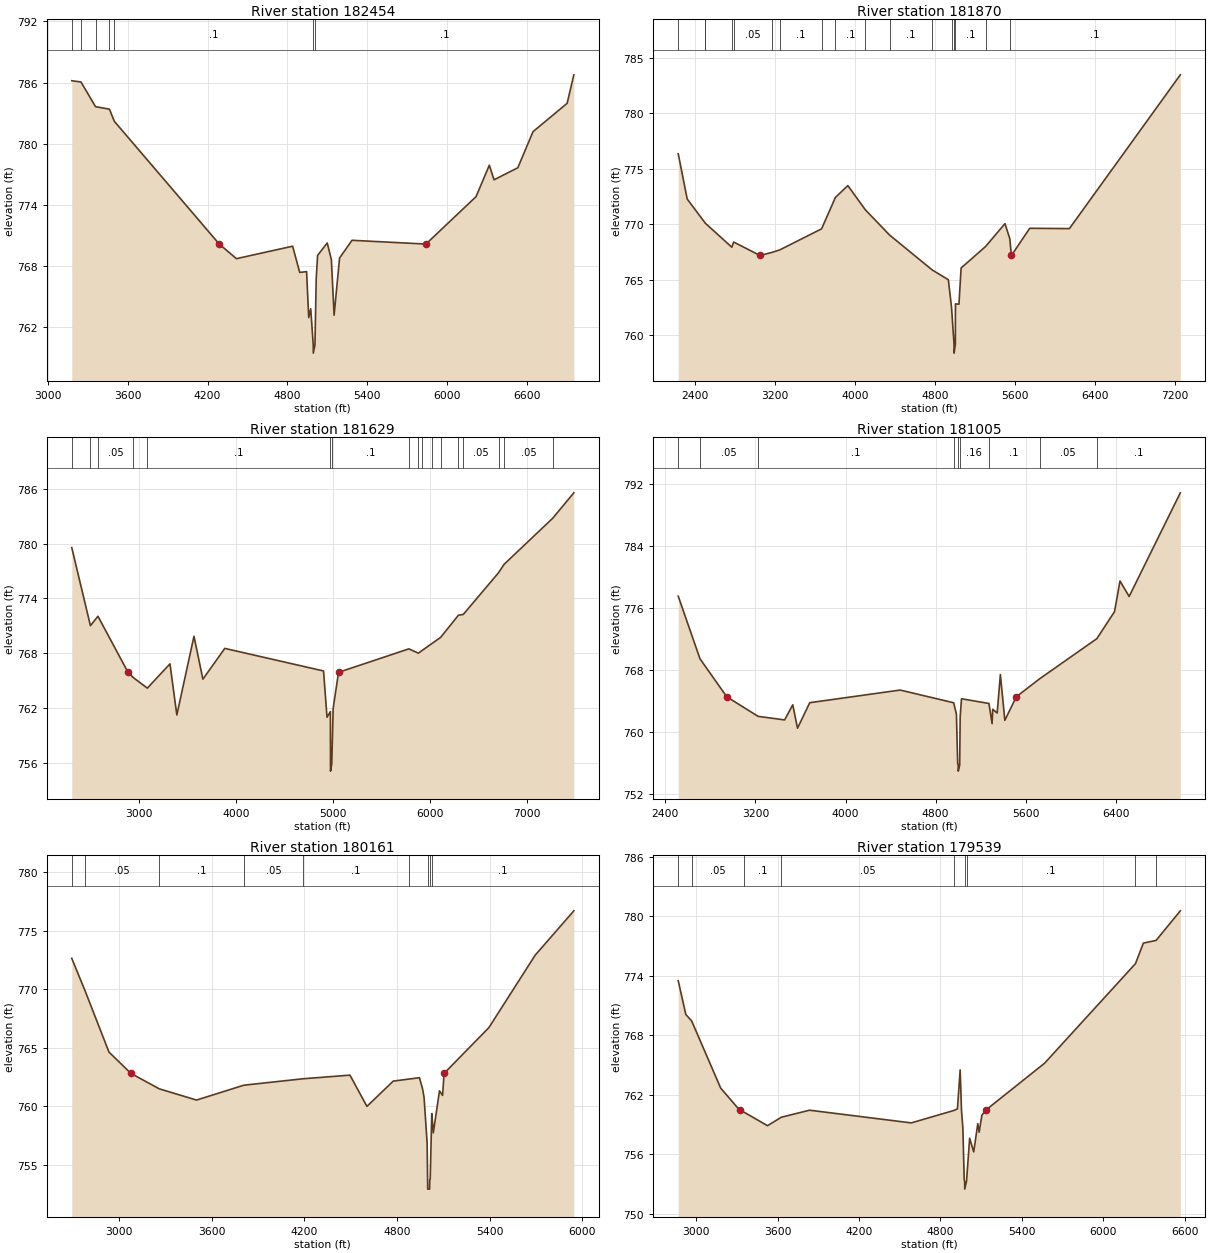
Type RM Length L Ch R = 1 ,182454  ,584,584,584
BEGIN DESCRIPTION:
Black Creek 185.0
END DESCRIPTION:
XS GIS Cut Line= 3
      1974361.99     13622177.16      1972195.27     13622746.62
      1970974.99     13623675.01
#Sta/Elev= 30
    3179  786.18  3248.2  786.06  3357.5  783.64  3462.3  783.39  3499.2   782.2
 4287.67  770.17  4416.6  768.74  4838.9  769.96  4892.3  767.39    4944  767.47
    4960  762.96    4975  763.83  4993.9  760.28  4994.4  759.48  5006.8  760.28
  5016.3  766.78  5026.7  769.06  5099.1  770.28  5130.1  768.65  5150.7   763.2
  5191.8   768.8  5285.2  770.54 5840.96  770.17  6217.6  774.82  6317.4   777.9
  6352.8  776.47  6531.5  777.65  6645.9  781.19  6902.3  783.97  6952.6  786.76
#Mann= 7 ,-1 , 0
    3179      .1       0  3248.2     .05       0  3357.5      .1       0
  3462.3     .05       0  3499.2      .1       0  4993.9     .07       0
  5006.8      .1       0
Bank Sta=4287.67,5840.96
XS Rating Curve= 0 ,0
Exp/Cntr=0.3,0.1

Type RM Length L Ch R = 1 ,181870  ,241,241,241
BEGIN DESCRIPTION:
Black Creek 184.0
END DESCRIPTION:
XS GIS Cut Line= 3
      1974745.42     13620228.92        1972725.       13622075.
      1971039.36     13623616.64
#Sta/Elev= 30
  2230.4  776.35    2320  772.27  2496.2  770.15  2497.3  770.12  2766.5  767.92
  2784.7  768.39  3047.8  767.18  3166.6  767.45  3245.6  767.68  3664.1  769.58
  3802.1  772.41  3926.5  773.48  4101.5   771.3  4343.8  769.02  4770.7  765.87
  4931.7  764.99  4963.3  762.52  4988.7  759.17  4989.3  758.37  5001.8  759.17
  5002.7  762.81  5037.8  762.78  5059.4  766.05  5303.4  767.98  5497.9  770.05
  5545.7  768.71 5562.53  767.18  5745.8  769.63  6142.3   769.6  7251.5  783.47
#Mann= 17 ,-1 , 0
  2230.4      .1       0  2496.2     .08       0  2497.3      .1       0
  2766.5     .08       0  2784.7     .05       0  3166.6     .08       0
  3245.6      .1       0  3664.1     .08       0  3802.1      .1       0
  4101.5     .08       0  4343.8      .1       0  4770.7     .08       0
  4963.3      .1       0  4988.7     .07       0  5001.8      .1       0
  5303.4     .08       0  5545.7      .1       0
Bank Sta=3047.8,5562.53
XS Rating Curve= 0 ,0
Exp/Cntr=0.3,0.1

Type RM Length L Ch R = 1 ,181629  ,624,624,624
BEGIN DESCRIPTION:
Black Creek 183.0
END DESCRIPTION:
XS GIS Cut Line= 3
      1974654.32     13620042.24      1972653.38     13621884.52
      1970844.34     13623554.67
#Sta/Elev= 30
  2303.8  779.57  2496.4  771.02  2574.1  772.05 2884.58  765.91  2936.8  765.35
    3084  764.18  3317.4  766.84  3388.3  761.24  3565.2  769.86  3657.1  765.16
  3883.3  768.53  4902.4  766.06  4938.2  760.99  4973.3  761.61    4974  755.89
  4974.6  755.09  4987.3  755.89  5001.7  761.97 5057.21  765.91  5782.8  768.48
  5881.1  768.01  5923.3  768.33    6019  769.05  6110.1  769.73  6294.9  772.17
  6344.6  772.25  6708.7  776.82  6765.9  777.74  7266.1  782.77  7485.8  785.57
#Mann= 17 ,-1 , 0
  2303.8      .1       0  2496.4     .08       0  2574.1     .05       0
  2936.8     .08       0    3084      .1       0    4974     .07       0
  4987.3      .1       0  5782.8     .05       0  5881.1      .1       0
  5923.3     .05       0    6019      .1       0  6110.1     .05       0
  6294.9      .1       0  6344.6     .05       0  6708.7      .1       0
  6765.9     .05       0  7266.1      .1       0
Bank Sta=2884.58,5057.21
XS Rating Curve= 0 ,0
Exp/Cntr=0.3,0.1

Type RM Length L Ch R = 1 ,181005  ,844,844,844
BEGIN DESCRIPTION:
Black Creek 182.0
END DESCRIPTION:
XS GIS Cut Line= 4
      1974606.53     13620059.64      1973136.25     13621024.39
      1971736.58     13621697.25      1970591.11     13621739.67
#Sta/Elev= 30
  2514.2  777.55  2707.3  769.48  2945.3  764.58  3223.2  762.06  3458.8   761.6
  3531.2  763.55  3573.3  760.53  3681.8  763.82  4484.9  765.45  4959.8  763.81
  4984.2  762.33  4995.3  755.96  4999.9   755.8  5000.5     755  5013.2   755.8
  5017.5     762  5029.2  764.33  5272.9  763.72  5300.9  761.12  5306.4  762.97
  5346.1  762.49  5374.3  767.45    5414  761.55 5515.81  764.58  5721.8  766.89
  6230.8  772.07  6387.7  775.55  6436.6  779.51  6517.8  777.51    6972  790.87
#Mann= 9 ,-1 , 0
  2514.2      .1       0  2707.3     .05       0  3223.2      .1       0
  4959.8     .16       0  4999.9     .07       0  5013.2     .16       0
  5272.9      .1       0  5721.8     .05       0  6230.8      .1       0
Bank Sta=2945.3,5515.81
XS Rating Curve= 0 ,0
Exp/Cntr=0.3,0.1

Type RM Length L Ch R = 1 ,180161  ,622,622,622
BEGIN DESCRIPTION:
Black Creek 181.0
END DESCRIPTION:
XS GIS Cut Line= 3
      1974514.76     13620086.88      1973226.52     13620555.64
      1971344.59     13620593.84
#Sta/Elev= 30
  2693.3  772.65  2780.9  769.83  2934.4  764.64 3076.53  762.82  3260.3   761.5
  3501.8  760.54  3808.1  761.81  4191.9  762.36  4495.8  762.67  4605.8     760
  4776.3  762.16    4881  762.34  4945.9  762.45  4965.9  761.52  4975.9  760.78
  4995.9  756.86  4998.9  753.73  4999.8  752.93    5012  752.93  5012.8  753.73
  5015.9  753.78  5025.9  759.39  5027.6  759.11  5035.9  757.74  5075.9  761.33
  5095.9  760.94 5105.77  762.82    5396  766.73    5696  772.92  5946.5  776.71
#Mann= 9 ,-1 , 0
  2693.3      .1       0  2780.9     .05       0  3260.3      .1       0
  3808.1     .05       0  4191.9      .1       0    4881     .16       0
  4998.9     .07       0  5012.8     .16       0  5027.6      .1       0
Bank Sta=3076.53,5105.77
XS Rating Curve= 0 ,0
Exp/Cntr=0.3,0.1

Type RM Length L Ch R = 1 ,179539  ,199,199,199
BEGIN DESCRIPTION:
Mapping XS dffe27d5
END DESCRIPTION:
XS GIS Cut Line= 4
      1974500.84     13620036.55      1973886.25     13619984.46
      1972589.37     13619994.88       1970802.9     13620052.17
#Sta/Elev= 30
  2867.6  773.49  2923.6  770.09  2966.5  769.44  3180.8  762.67 3320.14  760.46
  3350.1  760.27  3525.6  758.89  3627.6  759.74  3835.7  760.45  4585.7  759.17
  4901.2  760.43  4925.8  760.58  4945.9  764.51  4955.8  760.42  4965.8  758.63
  4975.8  753.42  4978.8   753.3  4979.7   752.5  4992.8   753.3  5015.8  757.63
  5045.8  756.25  5075.8   759.1  5085.8  758.23  5105.9  759.94  5134.9  760.46
  5568.1  765.18  6238.2  775.21  6296.5  777.28  6390.1  777.55  6568.7  780.53
#Mann= 9 ,-1 , 0
  2867.6      .1       0  2966.5     .05       0  3350.1      .1       0
  3627.6     .05       0  4901.2      .1       0  4978.8     .07       0
  4992.8      .1       0  6238.2     .16       0  6390.1      .1       0
Bank Sta=3320.14,5134.9
XS Rating Curve= 0 ,0
Exp/Cntr=0.3,0.1

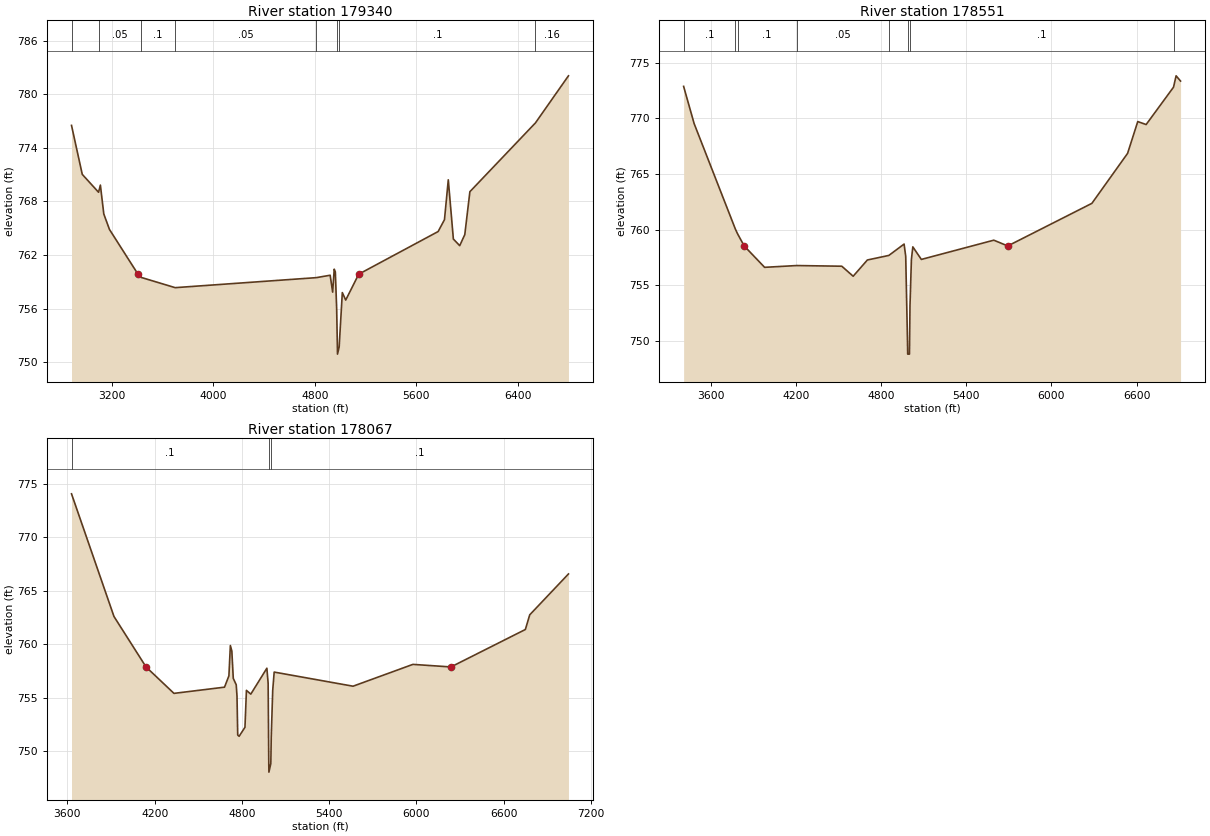
Type RM Length L Ch R = 1 ,179340  ,789,789,789
BEGIN DESCRIPTION:
Mapping XS 5eea1372
END DESCRIPTION:
XS GIS Cut Line= 5
      1974558.17     13619968.85      1973969.58     13619854.25
      1972552.91     13619875.09      1972313.33     13619796.96
      1970668.79     13619796.96
#Sta/Elev= 30
    2885   776.5  2969.7  771.02  3097.9  769.02  3112.4  769.82  3139.2  766.59
  3183.7  764.86 3408.31  759.85  3432.7  759.49  3701.3  758.34  4812.2  759.46
  4921.7  759.73  4941.3  757.84  4953.6  760.41  4962.4   760.1  4972.9  755.97
  4978.5   751.7  4979.4   750.9  4992.5   751.7  5017.4  757.79  5044.1  756.95
 5146.74  759.85  5771.8  764.62  5821.8  765.95  5851.8  770.41  5891.8  763.78
  5941.8  763.04  5981.8  764.28  6021.8  769.08    6538  776.78    6798  782.05
#Mann= 8 ,-1 , 0
    2885      .1       0  3097.9     .05       0  3432.7      .1       0
  3701.3     .05       0  4812.2      .1       0  4978.5     .07       0
  4992.5      .1       0    6538     .16       0
Bank Sta=3408.31,5146.74
XS Rating Curve= 0 ,0
Exp/Cntr=0.3,0.1

Type RM Length L Ch R = 1 ,178551  ,484,484,484
BEGIN DESCRIPTION:
Mapping XS a49c12ac
END DESCRIPTION:
XS GIS Cut Line= 4
      1974556.07     13619666.91      1973771.32     13619472.46
      1971812.99     13619361.35      1971083.79     13619444.68
#Sta/Elev= 30
  3406.3  772.87  3480.6  769.52  3770.8  760.06  3786.8  759.62 3833.46  758.53
  3977.4  756.61  4203.4  756.77  4521.6  756.71  4601.7  755.81  4701.9  757.27
  4853.3  757.68  4960.8   758.7  4972.3  757.59  4985.3  749.61  4986.2  748.81
  4998.4  748.81  4999.3  749.61  5002.4  753.16  5012.4  757.33  5022.4  758.45
  5082.5  757.32  5593.3  759.05 5691.68  758.53    6285  762.36  6536.6  766.85
  6608.4  769.71  6667.4  769.44  6860.5   772.8  6878.8  773.82  6910.2  773.35
#Mann= 8 ,-1 , 0
  3406.3      .1       0  3770.8     .05       0  3786.8      .1       0
  4203.4     .05       0  4853.3      .1       0  4985.3     .07       0
  4999.3      .1       0  6860.5     .16       0
Bank Sta=3833.46,5691.68
XS Rating Curve= 0 ,0
Exp/Cntr=0.3,0.1

Type RM Length L Ch R = 1 ,178067  ,736,736,736
BEGIN DESCRIPTION:
Black Creek 180.0
END DESCRIPTION:
XS GIS Cut Line= 3
      1974683.12     13619536.55      1974433.12     13619335.16
      1971349.87     13619050.44
#Sta/Elev= 30
  3628.2  774.04  3920.1  762.58 4140.72  757.86  4332.8  755.39  4680.4  755.97
  4710.6  757.03  4720.6  759.86  4730.7  759.35  4740.7  756.79  4760.8   756.2
  4766.2  755.15  4771.2   751.5  4780.9  751.38    4821  752.22  4831.1  755.67
  4861.2  755.32  4971.7  757.74  4980.4  756.34  4984.8  748.83  4985.7  748.03
  4998.8  748.83  5001.8  751.34  5011.8  755.66  5021.9  757.38  5564.2  756.06
  5975.9   758.1 6237.56  757.86  6749.2  761.36  6779.3  762.73  7045.6  766.55
#Mann= 3 ,-1 , 0
  3628.2      .1       0  4984.8     .07       0  4998.8      .1       0
Bank Sta=4140.72,6237.56
XS Rating Curve= 0 ,0
Exp/Cntr=0.3,0.1