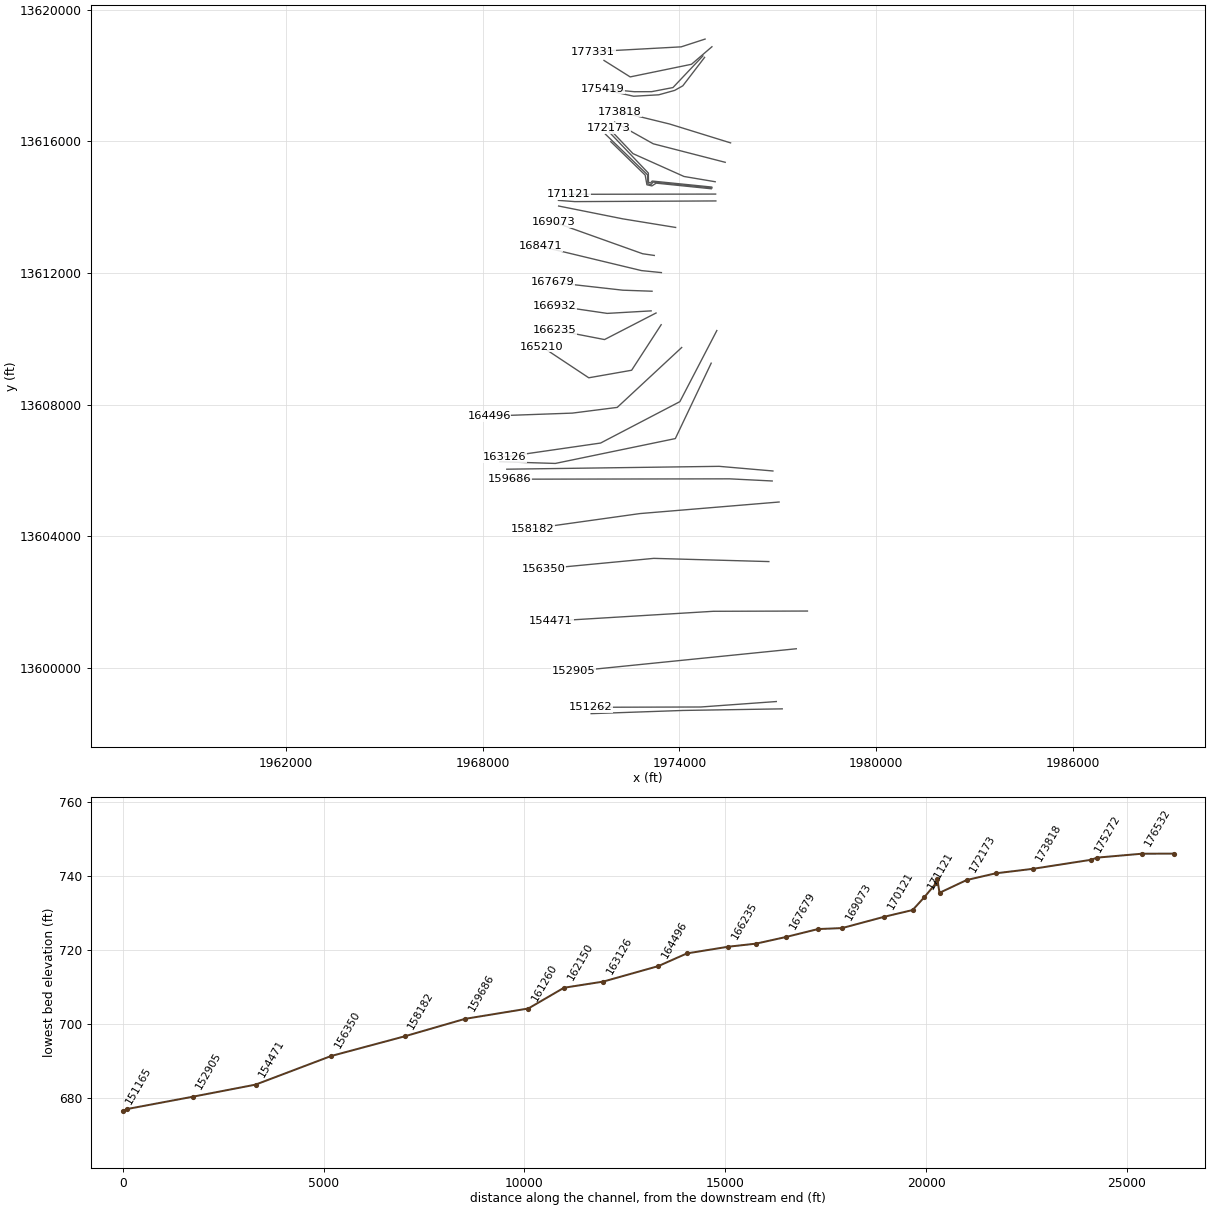
HEC-RAS study Black Creek.prj: Black Creek Base Level Engineering

--- Black Creek.g01 (geometry) --- (continued)

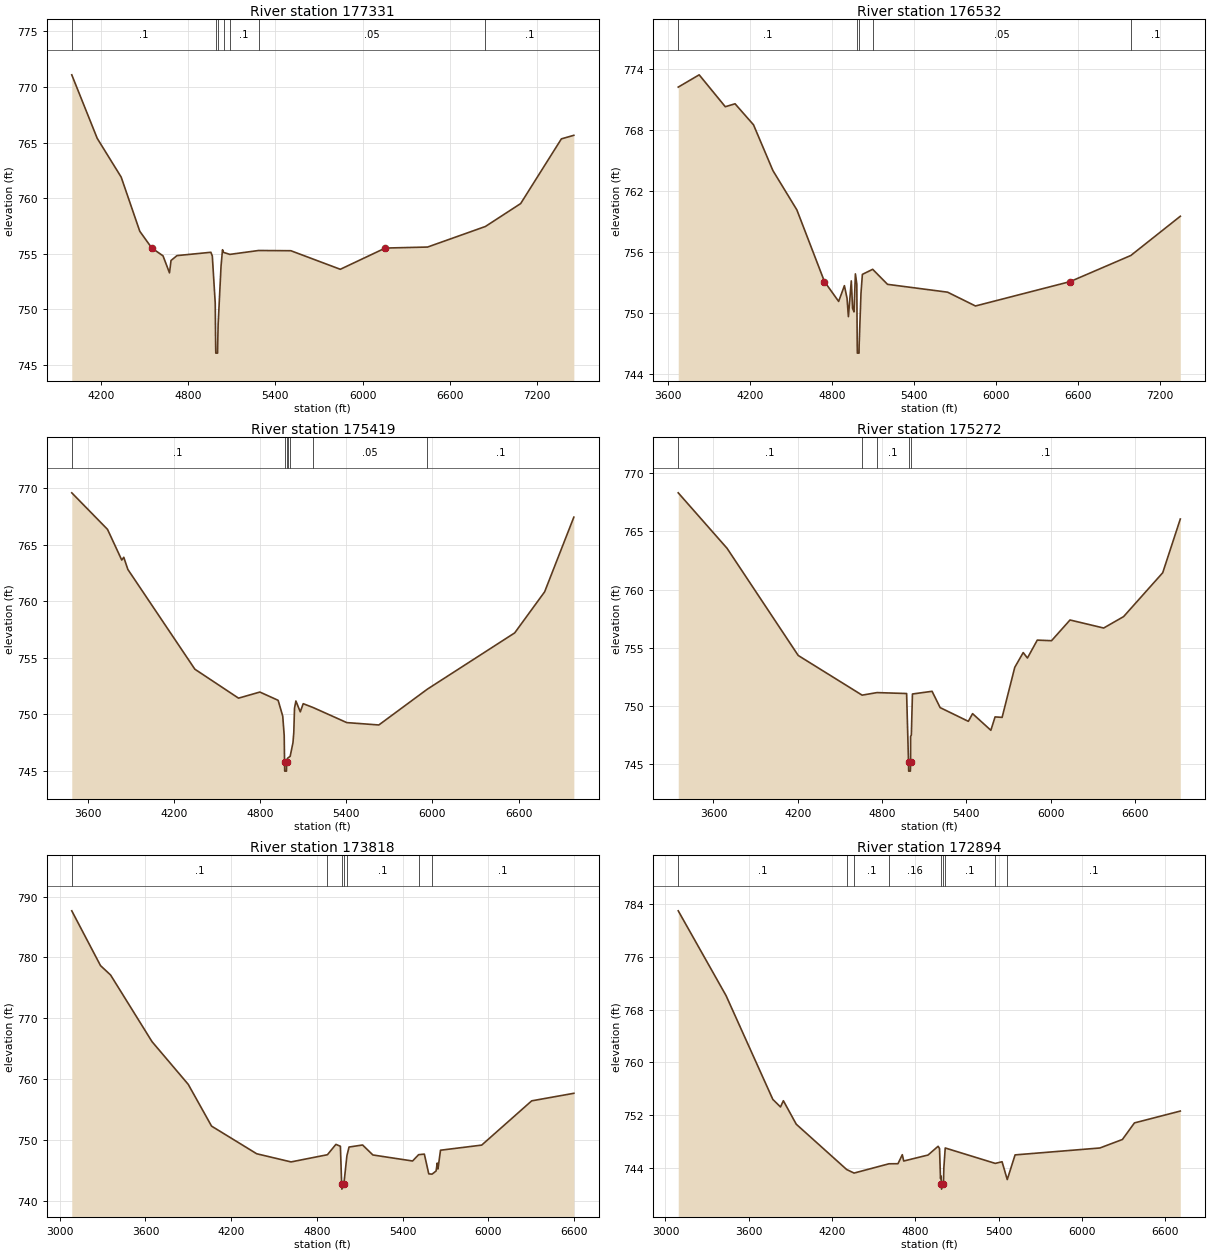
Type RM Length L Ch R = 1 ,177331  ,799,799,799
BEGIN DESCRIPTION:
Mapping XS c044850c
END DESCRIPTION:
XS GIS Cut Line= 3
      1974785.18     13619104.39      1974056.04     13618868.29
      1971369.31      13618722.5
#Sta/Elev= 30
    3998  771.09  4173.1  765.38  4338.3  761.89  4466.3  757.02 4549.26  755.51
  4626.3  754.81  4670.9  753.28  4681.4  754.39  4722.3  754.83  4955.7  755.13
  4965.7   754.8  4985.8  750.56  4988.7  746.86  4989.7  746.06  5001.9  746.06
  5002.8  746.86  5005.8  748.62  5025.8  753.87  5035.9  755.36    5043  755.12
  5086.5  754.94  5284.2  755.29  5506.5  755.27    5847   753.6 6156.75  755.51
  6447.9   755.6  6846.1  757.45  7088.9  759.51  7369.3  765.33  7455.1  765.65
#Mann= 7 ,-1 , 0
    3998      .1       0  4988.7     .07       0  5002.8      .1       0
    5043     .05       0  5086.5      .1       0  5284.2     .05       0
  6846.1      .1       0
Bank Sta=4549.26,6156.75
XS Rating Curve= 0 ,0
Exp/Cntr=0.3,0.1

Type RM Length L Ch R = 1 ,176532  ,1113,1113,1113
BEGIN DESCRIPTION:
Black Creek 179.0
END DESCRIPTION:
XS GIS Cut Line= 4
      1974993.85     13618871.59      1974370.62     13618338.63
      1972500.83     13617954.95      1971702.23     13618454.94
#Sta/Elev= 30
  3676.9  772.21    3830  773.42    4021  770.28  4092.3  770.57  4227.4   768.5
    4369     764  4544.2  760.13 4746.17  753.07  4849.8  751.12  4891.9  752.67
    4911  751.44  4921.2  749.62  4942.3  753.14  4951.8  750.44  4962.1  750.09
  4972.3  753.83  4982.5  752.82  4985.6  746.83  4986.6  746.03  4998.8  746.03
  4999.7  746.83  5013.1  751.93  5023.3  753.78  5098.6  754.28  5207.1   752.8
    5646  752.03  5850.2  750.67 6542.43  753.07  6986.1  755.64  7347.9   759.5
#Mann= 5 ,-1 , 0
  3676.9      .1       0  4985.6     .07       0  4999.7      .1       0
  5098.6     .05       0  6986.1      .1       0
Bank Sta=4746.17,6542.43
XS Rating Curve= 0 ,0
Exp/Cntr=0.3,0.1

Type RM Length L Ch R = 1 ,175419  ,147,147,147
BEGIN DESCRIPTION:
Black Creek 177.0
END DESCRIPTION:
XS GIS Cut Line= 5
      1974718.74     13618593.44      1973805.52      13617631.6
      1973154.47      13617506.6      1972623.96     13617505.21
      1971651.45     13617600.13
#Sta/Elev= 30
  3487.6  769.58  3736.6  766.35  3835.7  763.64  3849.9  763.88  3878.2  762.81
    4345  753.99  4649.1  751.43  4797.6  751.97  4924.9  751.24    4957  749.84
  4967.2  748.13  4969.6  745.78  4970.7  744.98    4983  744.98  4984.1  745.78
  4990.6  746.12  5008.7  746.29  5028.3   747.5    5034   748.4    5039  750.54
  5048.6  751.18  5079.2  750.22  5099.6  750.94  5168.8   750.6  5402.9  749.27
  5626.3  749.06  5963.6  752.22  6572.7   757.2  6781.1  760.83  6984.5  767.43
#Mann= 7 ,-1 , 0
  3487.6      .1       0  4969.6     .03       0  4984.1      .1       0
  4990.6     .05       0  5008.7      .1       0  5168.8     .05       0
  5963.6      .1       0
Bank Sta=4969.6,4984.1
XS Rating Curve= 0 ,0
Exp/Cntr=0.3,0.1

Type RM Length L Ch R = 1 ,175272  ,1454,1454,1454
BEGIN DESCRIPTION:
Mapping XS 5c1106e2
END DESCRIPTION:
XS GIS Cut Line= 6
       1974769.9     13618548.24      1974105.86     13617684.55
      1973858.47     13617545.66      1973372.36     13617411.11
      1972608.47     13617367.71      1971698.52     13617567.03
#Sta/Elev= 30
  3349.1  768.32  3696.8  763.55  4203.3  754.34  4658.1  750.93  4764.3  751.15
  4974.9  751.07  4988.4   745.2  4989.5   744.4  5001.8   744.4  5002.9   745.2
  5003.4  747.39  5008.6   747.5  5016.4  751.03  5156.2  751.26  5213.5  749.86
  5414.3  748.68  5444.4  749.34  5574.6  747.91  5604.6  749.06  5654.7  749.02
  5744.8  753.32  5804.9  754.59    5835  754.12  5905.1  755.66  6006.6  755.61
  6138.1  757.39  6377.8   756.7  6519.5  757.68    6798  761.45  6923.3  766.07
#Mann= 5 ,-1 , 0
  3349.1      .1       0  4658.1     .05       0  4764.3      .1       0
  4988.4     .07       0  5002.9      .1       0
Bank Sta=4988.4,5002.9
XS Rating Curve= 0 ,0
Exp/Cntr=0.3,0.1

Type RM Length L Ch R = 1 ,173818  ,924,924,924
BEGIN DESCRIPTION:
Black Creek 172.0
END DESCRIPTION:
XS GIS Cut Line= 3
      1975562.06      13615950.6      1973704.39     13616523.52
      1972178.29     13616896.38
#Sta/Elev= 30
  3084.3  787.66  3285.6  778.66  3356.1  777.12  3646.3  766.17  3899.7  759.16
    4063   752.3  4378.9  747.76  4619.5  746.42  4874.1   747.6  4933.5   749.3
  4964.9  748.99  4973.9  742.75  4975.3  741.95  4989.1  742.75  5010.5  747.43
  5025.4  748.86  5120.3   749.2  5192.4  747.56  5470.3  746.57  5512.5  747.61
  5552.7   747.7  5583.6  744.46  5606.7  744.41    5635  744.93  5642.8  746.23
    5648  745.26  5665.9  748.34  5954.2  749.18  6304.2  756.45  6599.3  757.69
#Mann= 7 ,-1 , 0
  3084.3      .1       0  4874.1     .16       0  4973.9     .07       0
  4989.1     .16       0  5010.5      .1       0  5512.5     .16       0
  5606.7      .1       0
Bank Sta=4973.9,4989.1
XS Rating Curve= 0 ,0
Exp/Cntr=0.3,0.1

Type RM Length L Ch R = 1 ,172894  ,721,721,721
BEGIN DESCRIPTION:
Mapping XS 776d41fc
END DESCRIPTION:
XS GIS Cut Line= 3
      1975398.85     13615360.33      1973204.39     13615922.83
      1972023.83     13616582.56
#Sta/Elev= 30
  3092.2  783.02  3436.8  770.14  3773.9  754.37  3829.1  753.22  3849.8  754.17
  3942.7   750.6  4305.8  743.72  4359.2  743.18  4610.6  744.59  4675.6   744.6
  4706.8  745.97  4716.9  745.01  4892.4  745.92  4964.7  747.25    4975   746.9
    4982  742.35  4987.1  742.71  4988.1  741.54  4989.5  740.74  5003.3  741.54
    5006  743.93  5016.1  746.99  5376.6  744.65  5425.6   744.9    5463  742.19
  5519.4  745.94  6130.5  746.99  6292.7  748.28  6379.5   750.8    6710   752.6
#Mann= 9 ,-1 , 0
  3092.2      .1       0  4305.8     .16       0  4359.2      .1       0
  4610.6     .16       0  4988.1     .07       0  5003.3     .16       0
  5016.1      .1       0  5376.6     .16       0    5463      .1       0
Bank Sta=4988.1,5003.3
XS Rating Curve= 0 ,0
Exp/Cntr=0.3,0.1

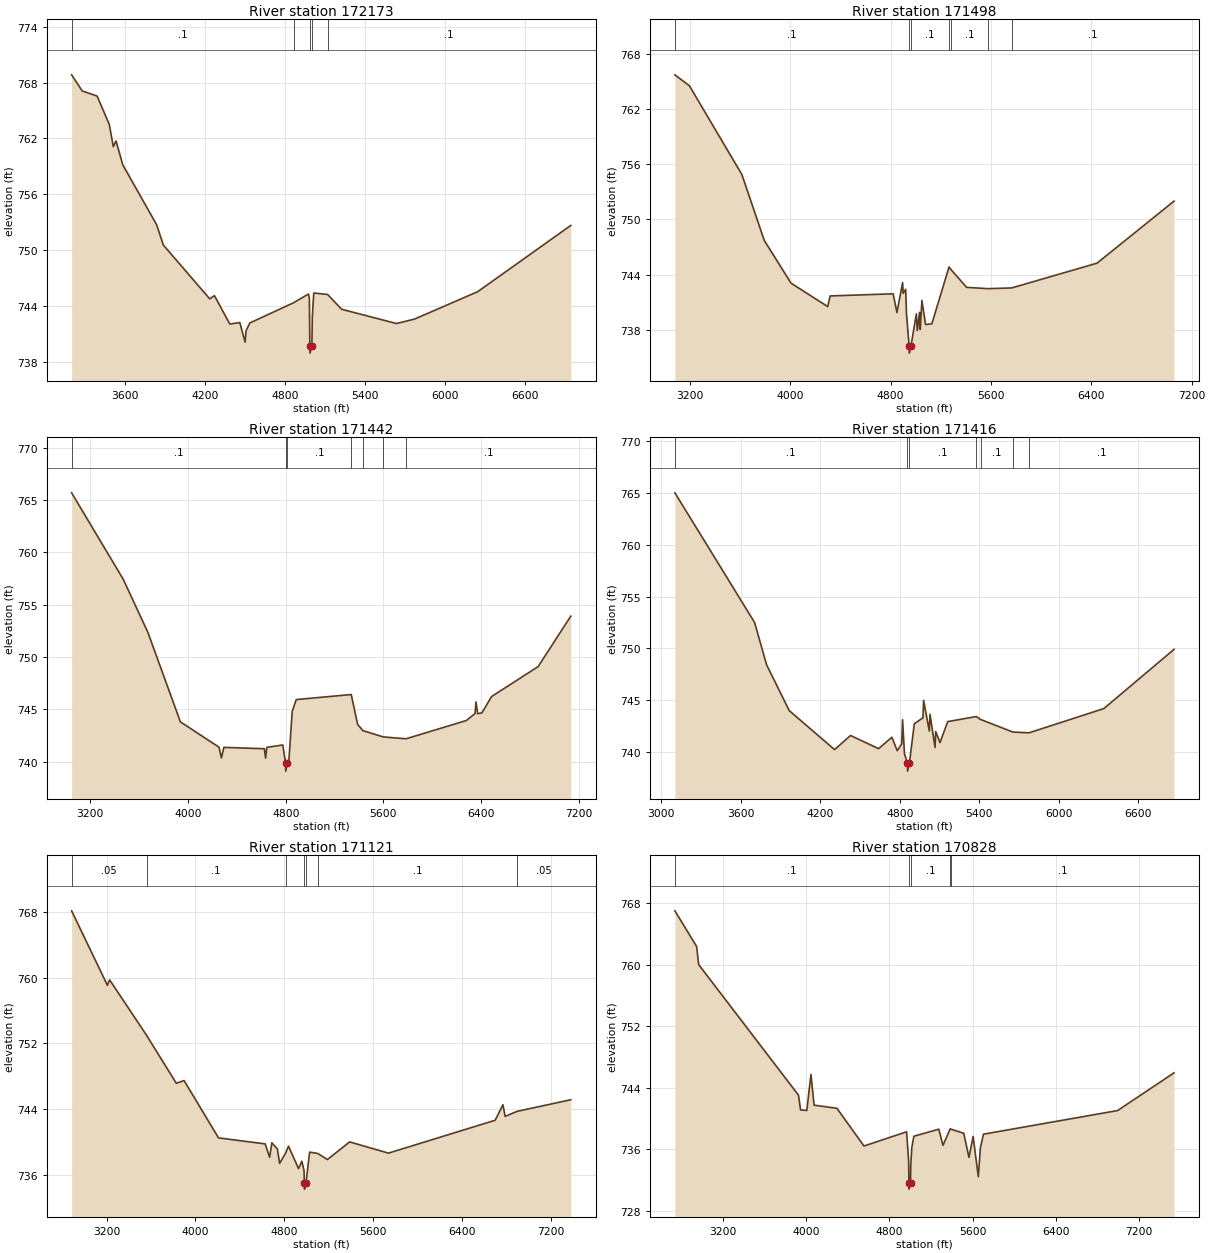
Type RM Length L Ch R = 1 ,172173  ,675,675,675
BEGIN DESCRIPTION:
Mapping XS 9c67c889
END DESCRIPTION:
XS GIS Cut Line= 4
      1975093.29     13614770.05      1974141.89     13614929.77
      1972586.33     13615624.22      1971844.25     13616400.98
#Sta/Elev= 30
  3201.8  768.83  3281.2   767.1  3392.7  766.55    3484  763.51  3514.4  761.11
  3534.7  761.73  3585.4  759.16  3838.9  752.73  3889.6  750.54  4237.5  744.76
  4272.6  745.11  4387.7  742.06  4462.8  742.21  4502.6  740.11  4509.3  741.33
    4538  742.17  4865.4  744.34  4977.8  745.28  4984.4  744.81  4987.7  739.73
  4989.1  738.93    5003  739.73  5006.5  742.88  5017.3  745.39  5121.1  745.23
  5226.4  743.64  5637.5  742.11  5772.9  742.59  6246.3  745.53  6944.3  752.65
#Mann= 5 ,-1 , 0
  3201.8      .1       0  4865.4     .16       0  4987.7     .07       0
    5003     .16       0  5121.1      .1       0
Bank Sta=4987.7,5003
XS Rating Curve= 0 ,0
Exp/Cntr=0.3,0.1

Type RM Length L Ch R = 1 ,171498  ,56,56,56
BEGIN DESCRIPTION:
Mapping XS 6e2096c5
END DESCRIPTION:
XS GIS Cut Line= 6
       1974986.1      13614608.5      1973171.84      13614790.8
      1973119.75     13614730.04      1973058.99     13614756.08
      1973054.98     13615032.86      1971856.76     13616284.53
#Sta/Elev= 30
  3080.2   765.7    3196  764.51    3614  754.88  3792.6  747.72  4005.9  743.08
  4298.9  740.53  4317.5  741.69    4820  741.92  4850.2  739.89  4895.5  743.14
  4899.6  741.97  4919.8  742.41  4926.4  739.78  4947.3  736.28  4948.7  735.48
  4962.6  736.28  5005.1  739.74  5012.5  737.93  5030.6  739.91    5036  738.05
  5049.2  741.21  5078.7  738.58  5128.7  738.67  5265.6  744.84  5281.3  744.55
  5405.9  742.62  5576.6  742.48  5765.4  742.56  6445.6  745.25  7059.3  751.99
#Mann= 7 ,-1 , 0
  3080.2      .1       0  4947.3     .07       0  4962.6      .1       0
  5265.6     .12       0  5281.3      .1       0  5576.6     .12       0
  5765.4      .1       0
Bank Sta=4947.3,4962.6
XS Rating Curve= 0 ,0
Exp/Cntr=0.3,0.1

Type RM Length L Ch R = 1 ,171442  ,26,26,26
BEGIN DESCRIPTION:
Mapping XS a51ab042
END DESCRIPTION:
XS GIS Cut Line= 6
      1974996.01     13614582.56      1973196.42     13614759.93
      1973127.41     13614672.69      1973040.17     13614710.45
      1973029.76     13614979.98      1971746.05      13616214.5
#Sta/Elev= 30
  3046.6   765.7  3469.6  757.43  3670.6  752.38  3937.5  743.81  4253.4  741.39
  4273.5  740.36  4293.6  741.37  4625.2  741.24  4635.3  740.34  4645.3  741.37
  4775.9   741.6  4798.4   739.9  4799.8   739.1  4813.7   739.9  4826.2  740.16
  4853.1  744.81  4886.2  745.94  5336.7  746.42  5388.8  743.57  5432.4  742.97
  5598.9  742.37  5785.4  742.19    6280  743.94  6350.7  744.61  6357.9  745.71
  6372.1  744.59  6407.3  744.67    6485  746.22  6867.1  749.09  7134.7  753.91
#Mann= 7 ,-1 , 0
  3046.6      .1       0  4798.4     .07       0  4813.7      .1       0
  5336.7     .12       0  5432.4      .1       0  5598.9     .12       0
  5785.4      .1       0
Bank Sta=4798.4,4813.7
XS Rating Curve= 0 ,0
Exp/Cntr=0.3,0.1

Type RM Length L Ch R = 1 ,171416  ,295,295,295
BEGIN DESCRIPTION:
Mapping XS cd27af43
END DESCRIPTION:
XS GIS Cut Line= 6
      1974973.08     13614556.42      1973294.08     13614727.38
      1973163.16     13614643.23      1973011.25     13614677.95
      1972958.14     13614972.17      1971909.38     13615988.17
#Sta/Elev= 30
  3103.7  765.03  3704.9  752.51  3795.3  748.43  3966.2     744    4308  740.24
  4428.6   741.6  4639.7  740.33  4740.2  741.43  4780.4  740.13  4814.4  740.79
  4820.8  743.12  4835.2  739.82  4857.4  738.96  4858.8  738.16  4872.7  738.96
  4909.2  742.73  4974.5  743.31  4979.6  744.99  5022.6  742.02  5027.7  743.65
  5065.6  740.45  5070.7  741.98  5103.3  740.92  5161.2  742.94  5376.8  743.43
  5408.7  743.15  5653.4  741.93  5775.2  741.86  6338.9   744.2  6868.4  749.92
#Mann= 7 ,-1 , 0
  3103.7      .1       0  4857.4     .07       0  4872.7      .1       0
  5376.8     .12       0  5408.7      .1       0  5653.4     .12       0
  5775.2      .1       0
Bank Sta=4857.4,4872.7
XS Rating Curve= 0 ,0
Exp/Cntr=0.3,0.1

Type RM Length L Ch R = 1 ,171121  ,293,293,293
BEGIN DESCRIPTION:
Mapping XS a29bc30a
END DESCRIPTION:
XS GIS Cut Line= 2
      1975107.15     13614395.05      1970614.15     13614388.11
#Sta/Elev= 30
  2885.6   768.1  3207.7  759.06  3227.7  759.72  3560.3  752.99  3827.8  747.17
  3897.8   747.5  4207.8  740.54  4627.8  739.81  4667.8  738.19  4687.8  739.94
  4737.8   739.2  4757.8  737.45  4810.8  738.67  4837.8  739.54  4927.8  736.81
  4957.8  737.71  4977.8  736.55  4980.1  735.12  4981.5  734.32  4995.4  735.12
  5027.8  738.81  5101.2  738.65  5187.8  737.91  5387.8  740.05  5737.8  738.69
  6697.8  742.68  6767.8  744.56  6787.8  743.15  6895.8  743.76  7378.6  745.17
#Mann= 7 ,-1 , 0
  2885.6     .05       0  3560.3      .1       0  4810.8     .12       0
  4980.1     .07       0  4995.4     .12       0  5101.2      .1       0
  6895.8     .05       0
Bank Sta=4980.1,4995.4
XS Rating Curve= 0 ,0
Exp/Cntr=0.3,0.1

Type RM Length L Ch R = 1 ,170828  ,707,707,707
BEGIN DESCRIPTION:
Mapping XS c7ebeadb
END DESCRIPTION:
XS GIS Cut Line= 3
      1975114.07     13614186.72      1970814.89     13614166.08
      1970313.19      13614203.2
#Sta/Elev= 30
  2736.7  766.99  2945.8  762.36  2965.8     760  3925.8  743.04  3945.8  741.13
  4005.8  741.05  4045.8  745.73  4075.8  741.74  4295.8  741.33  4555.8  736.43
  4965.8  738.28  4985.8  734.44  4988.1  731.63  4989.5  730.83  5003.4  731.63
  5005.8  733.91  5015.8  736.22  5035.8   737.7  5275.8  738.62  5315.8  736.52
    5386  738.68  5390.5  738.63  5515.8  738.09  5565.8  734.95  5605.8  737.68
  5655.8  732.44  5675.8  736.22  5705.8  737.97  6995.8  741.04    7539  745.94
#Mann= 5 ,-1 , 0
  2736.7      .1       0  4988.1     .07       0  5003.4      .1       0
    5386     .05       0  5390.5      .1       0
Bank Sta=4988.1,5003.4
XS Rating Curve= 0 ,0
Exp/Cntr=0.3,0.1

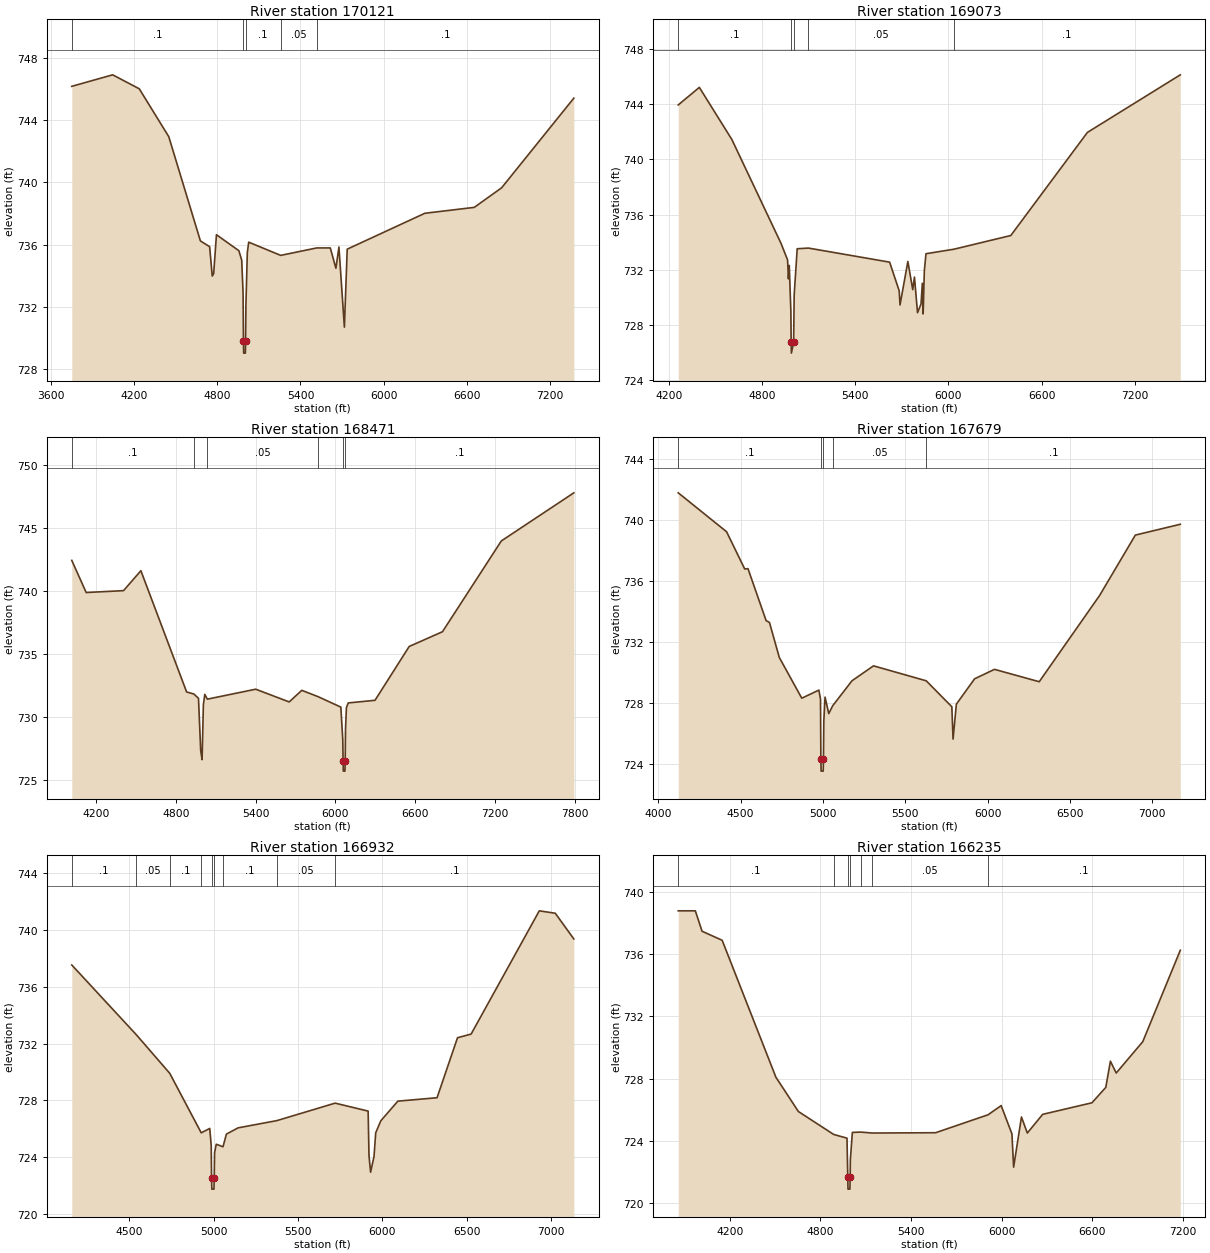
Type RM Length L Ch R = 1 ,170121  ,1048,1048,1048
BEGIN DESCRIPTION:
Black Creek 171.0
END DESCRIPTION:
XS GIS Cut Line= 3
      1973886.65     13613381.17      1972280.78     13613641.58
      1970319.53     13614032.09
#Sta/Elev= 30
    3748  746.18  4043.5  746.92  4235.7  746.02  4448.7  742.94  4677.2  736.23
  4743.9  735.86  4762.7  733.97  4772.9  734.12  4793.1  736.63  4955.2   735.6
  4975.5  734.99  4985.3  732.91  4988.1  729.81  4989.5  729.01    5002  729.01
  5003.4  729.81  5005.9  732.12    5016  735.47  5026.1  736.15  5257.3   735.3
  5517.7  735.78  5615.3  735.78    5656  734.47  5677.8  735.84  5717.2  730.68
  5737.6   735.7  6298.4  738.01  6655.3  738.39    6853  739.65  7374.6  745.42
#Mann= 5 ,-1 , 0
    3748      .1       0  4988.1     .07       0  5003.4      .1       0
  5257.3     .05       0  5517.7      .1       0
Bank Sta=4988.1,5003.4
XS Rating Curve= 0 ,0
Exp/Cntr=0.3,0.1

Type RM Length L Ch R = 1 ,169073  ,602,602,602
BEGIN DESCRIPTION:
Black Creek 170.0
END DESCRIPTION:
XS GIS Cut Line= 3
      1973235.67     13612530.46      1972879.74     13612582.55
      1970171.36     13613546.11
#Sta/Elev= 30
  4259.3  743.94  4395.3  745.21    4605  741.43  4921.2  733.92  4963.7  732.71
  4969.2  731.34  4974.5  732.31  4984.9  728.99  4986.8  726.76  4988.4  725.96
  5002.6  726.76  5006.2  730.16  5025.6  733.52  5098.3  733.57  5621.1  732.55
  5682.8  730.47  5688.1  729.45  5738.5   732.6    5770  730.56    5781  731.47
  5800.8  728.89  5823.4  729.52  5831.7  731.02    5837   728.8  5844.7  731.92
  5855.3  733.16  6036.5  733.49  6401.7  734.48  6895.4  741.95  7493.7  746.12
#Mann= 5 ,-1 , 0
  4259.3      .1       0  4986.8     .07       0  5002.6      .1       0
  5098.3     .05       0  6036.5      .1       0
Bank Sta=4986.8,5002.6
XS Rating Curve= 0 ,0
Exp/Cntr=0.3,0.1

Type RM Length L Ch R = 1 ,168471  ,792,792,792
BEGIN DESCRIPTION:
Black Creek 169.0
END DESCRIPTION:
XS GIS Cut Line= 3
      1973452.67     13612009.63      1972845.01      13612070.4
      1969763.41     13612808.25
#Sta/Elev= 30
  4014.8  742.41  4123.5  739.86  4404.4  740.01  4535.1  741.59  4879.4  731.97
  4933.5  731.81  4968.7  731.47  4985.4  727.31  4995.7   726.6  5005.6  730.98
  5016.2  731.78  5035.4   731.4  5399.3  732.19  5651.5  731.18  5746.3   732.1
  5866.2  731.61  6040.2  730.77  6054.8  728.19  6057.2  726.49  6058.8  725.69
  6071.4  725.69    6073  726.49  6075.4  729.01  6082.2  730.73  6095.9   731.1
  6297.5  731.31  6554.9  735.58  6805.4  736.75  7248.1  743.95  7794.2  747.77
#Mann= 6 ,-1 , 0
  4014.8      .1       0  4933.5     .12       0  5035.4     .05       0
  5866.2      .1       0  6057.2     .07       0    6073      .1       0
Bank Sta=6057.2,6073
XS Rating Curve= 0 ,0
Exp/Cntr=0.3,0.1

Type RM Length L Ch R = 1 ,167679  ,747,747,747
BEGIN DESCRIPTION:
Black Creek 168.0
END DESCRIPTION:
XS GIS Cut Line= 3
      1973168.36     13611443.58        1972275.       13611475.
      1970133.65     13611714.41
#Sta/Elev= 30
  4121.9   741.8  4415.4  739.25  4525.5  736.81  4545.5  736.83  4655.6  733.42
  4675.6  733.31  4735.6  731.01  4872.1  728.34  4975.8  728.87  4985.8  728.28
  4987.9  724.36  4989.5  723.56  5002.1  723.56  5003.7  724.36  5005.8  726.84
  5013.3  728.41  5035.9  727.33  5059.5  727.84  5176.8  729.48  5307.6  730.46
  5627.6  729.48  5783.2  727.78  5790.6  725.66  5810.7  727.95  5921.4  729.61
  6042.2  730.23  6313.8  729.42    6681  735.08  6897.5  739.03  7170.5  739.74
#Mann= 5 ,-1 , 0
  4121.9      .1       0  4987.9     .07       0  5003.7      .1       0
  5059.5     .05       0  5627.6      .1       0
Bank Sta=4987.9,5003.7
XS Rating Curve= 0 ,0
Exp/Cntr=0.3,0.1

Type RM Length L Ch R = 1 ,166932  ,697,697,697
BEGIN DESCRIPTION:
Black Creek 166.0
END DESCRIPTION:
XS GIS Cut Line= 3
      1973140.64     13610846.36      1971800.31     13610769.97
      1970182.25     13611006.08
#Sta/Elev= 30
  4158.8  737.53  4541.1  732.63  4739.8  729.91  4926.7  725.72  4977.1  726.03
  4985.8  724.84  4987.8  722.56  4989.5  721.76  5002.1  721.76  5003.7  722.56
  5005.8  724.33  5015.8  724.92  5055.7  724.74  5075.9  725.63  5145.1  726.07
  5375.1  726.58  5720.7  727.81  5916.5  727.25  5921.6  724.12  5931.1  722.95
  5951.3  724.05  5961.4  725.72  5991.8  726.57  6092.8  727.95  6325.2  728.19
  6446.5  732.41  6527.4  732.67  6931.6  741.34  7026.4  741.17  7136.5  739.36
#Mann= 9 ,-1 , 0
  4158.8      .1       0  4541.1     .05       0  4739.8      .1       0
  4926.7     .12       0  4987.8     .07       0  5003.7     .12       0
  5055.7      .1       0  5375.1     .05       0  5720.7      .1       0
Bank Sta=4987.8,5003.7
XS Rating Curve= 0 ,0
Exp/Cntr=0.3,0.1

Type RM Length L Ch R = 1 ,166235  ,1025,1025,1025
BEGIN DESCRIPTION:
Black Creek 165.0
END DESCRIPTION:
XS GIS Cut Line= 3
      1973289.93     13610782.14      1971718.71     13609974.83
      1970190.94     13610269.96
#Sta/Elev= 30
  3858.7  738.78  3971.9  738.78  4016.3  737.47  4149.4  736.89  4505.1   728.1
    4654   725.9  4887.2  724.43  4975.5  724.19  4980.5  721.72  4982.2  720.92
  4994.8  720.92  4996.5  721.72  4997.7   722.8    5011  724.56  5066.2  724.58
  5142.5  724.52  5561.9  724.54  5908.7  725.69  5995.6  726.28  6066.9  724.47
  6078.2  722.33    6130  725.55  6168.8  724.52  6270.6  725.72  6596.4  726.46
  6688.2  727.45  6718.7  729.13    6757  728.37  6932.6  730.38  7181.2  736.25
#Mann= 7 ,-1 , 0
  3858.7      .1       0  4887.2     .12       0  4980.5     .07       0
  4996.5     .12       0  5066.2      .1       0  5142.5     .05       0
  5908.7      .1       0
Bank Sta=4980.5,4996.5
XS Rating Curve= 0 ,0
Exp/Cntr=0.3,0.1

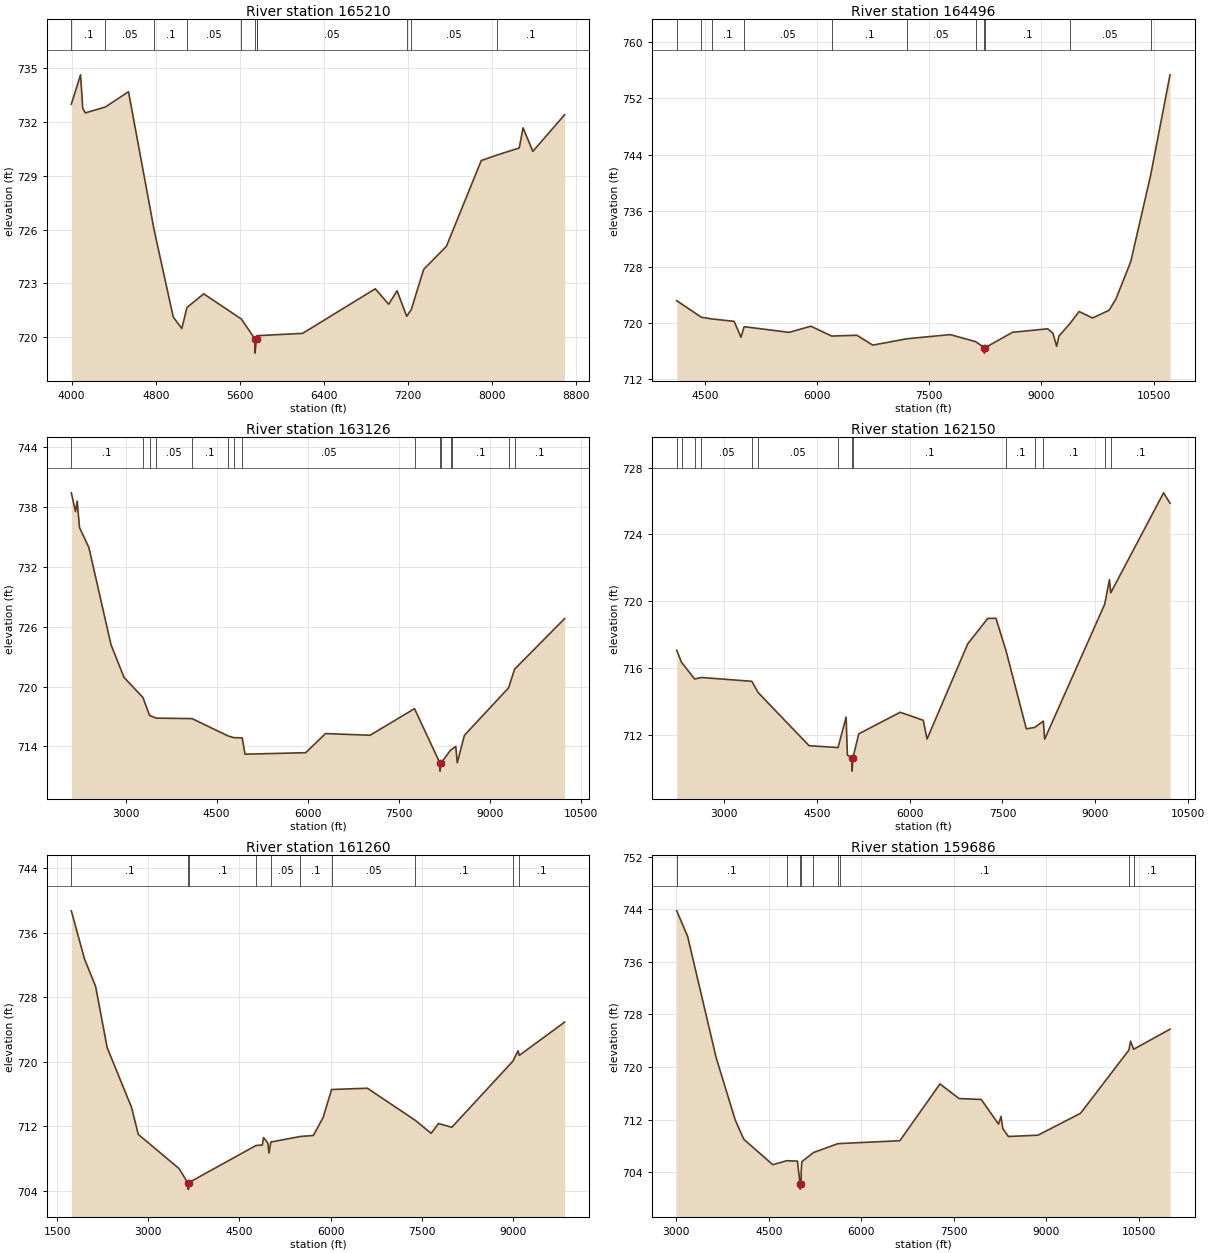
Type RM Length L Ch R = 1 ,165210  ,714,714,714
BEGIN DESCRIPTION:
Black Creek 164.0
END DESCRIPTION:
XS GIS Cut Line= 4
      1973446.13      13610426.2       1972545.1     13609042.54
      1971237.81     13608813.37      1969809.53     13609757.45
#Sta/Elev= 30
  3997.6  732.98  4085.3  734.61  4106.4  732.75  4130.3  732.49  4321.5  732.82
  4541.1  733.67  4786.5  725.93  4966.7  721.13  5048.3  720.49  5096.8  721.66
  5256.5  722.42  5614.1  721.02  5742.4  719.92  5744.1  719.12  5758.4  719.92
  5762.2  720.09  6197.1  720.22  6887.5   722.7  7015.3  721.84    7095  722.59
  7186.7  721.17  7229.1  721.53  7347.9  723.78  7564.5  725.07  7895.6  729.84
  8043.1  730.14  8256.7  730.54  8292.9  731.66  8386.1  730.35  8688.1  732.39
#Mann= 11 ,-1 , 0
  3997.6      .1       0  4321.5     .05       0  4786.5      .1       0
  5096.8     .05       0  5614.1      .1       0  5742.4     .07       0
  5758.4      .1       0  5762.2     .05       0  7186.7      .1       0
  7229.1     .05       0  8043.1      .1       0
Bank Sta=5742.4,5758.4
XS Rating Curve= 0 ,0
Exp/Cntr=0.3,0.1

Type RM Length L Ch R = 1 ,164496  ,1370,1370,1370
BEGIN DESCRIPTION:
Mapping XS fe954851
END DESCRIPTION:
XS GIS Cut Line= 4
       1974071.3     13609733.38      1972105.99     13607913.91
      1970737.93      13607740.3        1968200.       13607650.
#Sta/Elev= 30
    4123  723.17  4453.2   720.8    4592  720.57  4890.7  720.22  4982.5  717.95
  5024.1  719.46  5626.6  718.65  5916.8  719.53  6195.9  718.12  6532.1  718.24
  6744.7  716.83  7202.3  717.74    7780  718.33  8119.9  717.33  8235.2  716.49
  8236.9  715.69  8251.2  716.49  8613.5  718.66  9083.8  719.16  9153.8  718.54
  9203.8  716.66  9233.9  718.11  9381.8  719.91    9504  721.62  9684.1   720.7
  9904.3   721.8  9994.3  723.35 10194.5  728.73 10460.8  741.06 10719.8  755.37
#Mann= 11 ,-1 , 0
    4123      .1       0  4453.2     .05       0    4592      .1       0
  5024.1     .05       0  6195.9      .1       0  7202.3     .05       0
  8119.9      .1       0  8235.2     .07       0  8251.2      .1       0
  9381.8     .05       0 10460.8      .1       0
Bank Sta=8235.2,8251.2
XS Rating Curve= 0 ,0
Exp/Cntr=0.3,0.1

Type RM Length L Ch R = 1 ,163126  ,976,976,976
BEGIN DESCRIPTION:
Black Creek 161.0
END DESCRIPTION:
XS GIS Cut Line= 4
      1975143.17     13610248.51      1974015.59     13608087.96
      1971598.92     13606831.02      1968659.37     13606407.49
#Sta/Elev= 30
  2104.5  739.44  2173.3  737.56  2201.1  738.61  2239.6  735.95  2394.2  733.95
  2758.4   724.2  2973.6  720.91  3284.9   718.9  3394.7   717.1  3501.8  716.83
  4094.6  716.78    4693  715.03  4782.6  714.87    4921  714.85  4967.8  713.21
  5967.8  713.36  6293.8  715.28  7028.5  715.11  7761.1  717.78  8181.1  712.31
  8182.9  711.51  8197.2  712.31  8355.7  713.62  8381.6  713.73  8441.5  713.99
  8465.8  712.35    8583   715.1  9311.8  719.87  9410.7  721.74 10235.5  726.82
#Mann= 15 ,-1 , 0
  2104.5      .1       0  3284.9     .05       0  3394.7      .1       0
  3501.8     .05       0  4094.6      .1       0    4693     .05       0
  4782.6      .1       0    4921     .05       0  7761.1      .1       0
  8181.1    .035       0  8197.2      .1       0  8355.7     .12       0
  8381.6      .1       0  9311.8     .08       0  9410.7      .1       0
Bank Sta=8181.1,8197.2
XS Rating Curve= 0 ,0
Exp/Cntr=0.3,0.1

Type RM Length L Ch R = 1 ,162150  ,890,890,890
BEGIN DESCRIPTION:
Black Creek 160.0
END DESCRIPTION:
XS GIS Cut Line= 4
       1974971.3     13609258.07      1973877.57     13606966.44
      1970218.71     13606211.23      1968527.96     13606263.25
#Sta/Elev= 30
  2239.4  717.07  2318.3  716.35  2528.8  715.36  2636.1  715.45  3452.5  715.22
  3556.3  714.54  4377.1  711.37  4844.7  711.26  4975.3  713.08  4995.7  710.81
  5069.3  710.65  5071.1  709.85  5085.4  710.65  5179.5  712.08  5848.8  713.37
    6221  712.89  6282.3  711.77  6939.3  717.46  7262.5  718.98  7395.2  718.99
  7561.2     717  7885.4  712.38  8019.2  712.46  8160.4  712.84  8181.5  711.76
  9150.3  719.82  9228.7   721.3  9248.8  720.51 10102.3  726.49 10206.2  725.87
#Mann= 14 ,-1 , 0
  2239.4      .1       0  2318.3     .05       0  2528.8      .1       0
  2636.1     .05       0  3452.5      .1       0  3556.3     .05       0
  4844.7      .1       0  5069.3     .07       0  5085.4      .1       0
  7561.2      .1       0  8019.2     .12       0  8160.4      .1       0
  9150.3     .08       0  9248.8      .1       0
Bank Sta=5069.3,5085.4
XS Rating Curve= 0 ,0
Exp/Cntr=0.3,0.1

Type RM Length L Ch R = 1 ,161260  ,1574,1574,1574
BEGIN DESCRIPTION:
Black Creek 162.0
END DESCRIPTION:
XS GIS Cut Line= 3
      1976853.27     13605982.06       1975214.8     13606123.12
      1968738.51     13606036.34
#Sta/Elev= 30
  1731.8  738.69  1950.9  732.68  2131.5  729.34  2322.2  721.75  2723.7  714.35
  2834.1  711.02  3506.1  706.78  3648.1  705.04  3649.9  704.24  3662.5  704.24
  3664.3  705.04  4769.1  709.63  4876.3  709.71  4896.3  710.62  4966.3  709.95
  4986.3  708.71  5016.2  710.07  5504.7  710.76  5716.3  710.88  5876.4  713.09
  6016.4  716.57  6606.4  716.73  7397.7  712.74  7656.5  711.14  7776.5  712.36
  7996.5   711.9  9002.5  720.09  9086.6  721.37  9107.3   720.8  9853.2  724.91
#Mann= 10 ,-1 , 0
  1731.8      .1       0  3648.1     .07       0  3664.3      .1       0
  4769.1      .1       0  5016.2     .05       0  5504.7      .1       0
  6016.4     .05       0  7397.7      .1       0  9002.5     .05       0
  9107.3      .1       0
Bank Sta=3648.1,3664.3
XS Rating Curve= 0 ,0
Exp/Cntr=0.3,0.1

Type RM Length L Ch R = 1 ,159686  ,1504,1504,1504
BEGIN DESCRIPTION:
Black Creek 163.0
END DESCRIPTION:
XS GIS Cut Line= 3
      1976831.57     13605678.24      1975529.47     13605743.35
      1968834.61     13605732.49
#Sta/Elev= 30
  3007.6  743.75  3184.4  739.87  3646.8  721.45  3955.4  711.97  4095.5  709.02
  4565.8  705.16  4791.5  705.77  4965.8  705.71    5007  702.25  5009.3  701.45
  5024.6  702.25  5025.8  704.12  5035.8  705.62  5224.3  707.01  5615.2  708.34
  5657.5  708.38  6625.8  708.81  7275.8  717.44  7585.8  715.22  7945.8  715.08
  8225.8  711.33  8265.8   712.5  8295.8  710.64  8385.8  709.45  8865.8  709.65
  9555.8  712.98 10340.1  722.59 10365.8  723.94 10416.9  722.71 11006.2  725.76
#Mann= 9 ,-1 , 0
  3007.6      .1       0  4791.5     .05       0    5007     .04       0
  5024.6     .05       0  5224.3      .1       0  5615.2     .05       0
  5657.5      .1       0 10340.1     .05       0 10416.9      .1       0
Bank Sta=5007,5024.6
XS Rating Curve= 0 ,0
Exp/Cntr=0.3,0.1

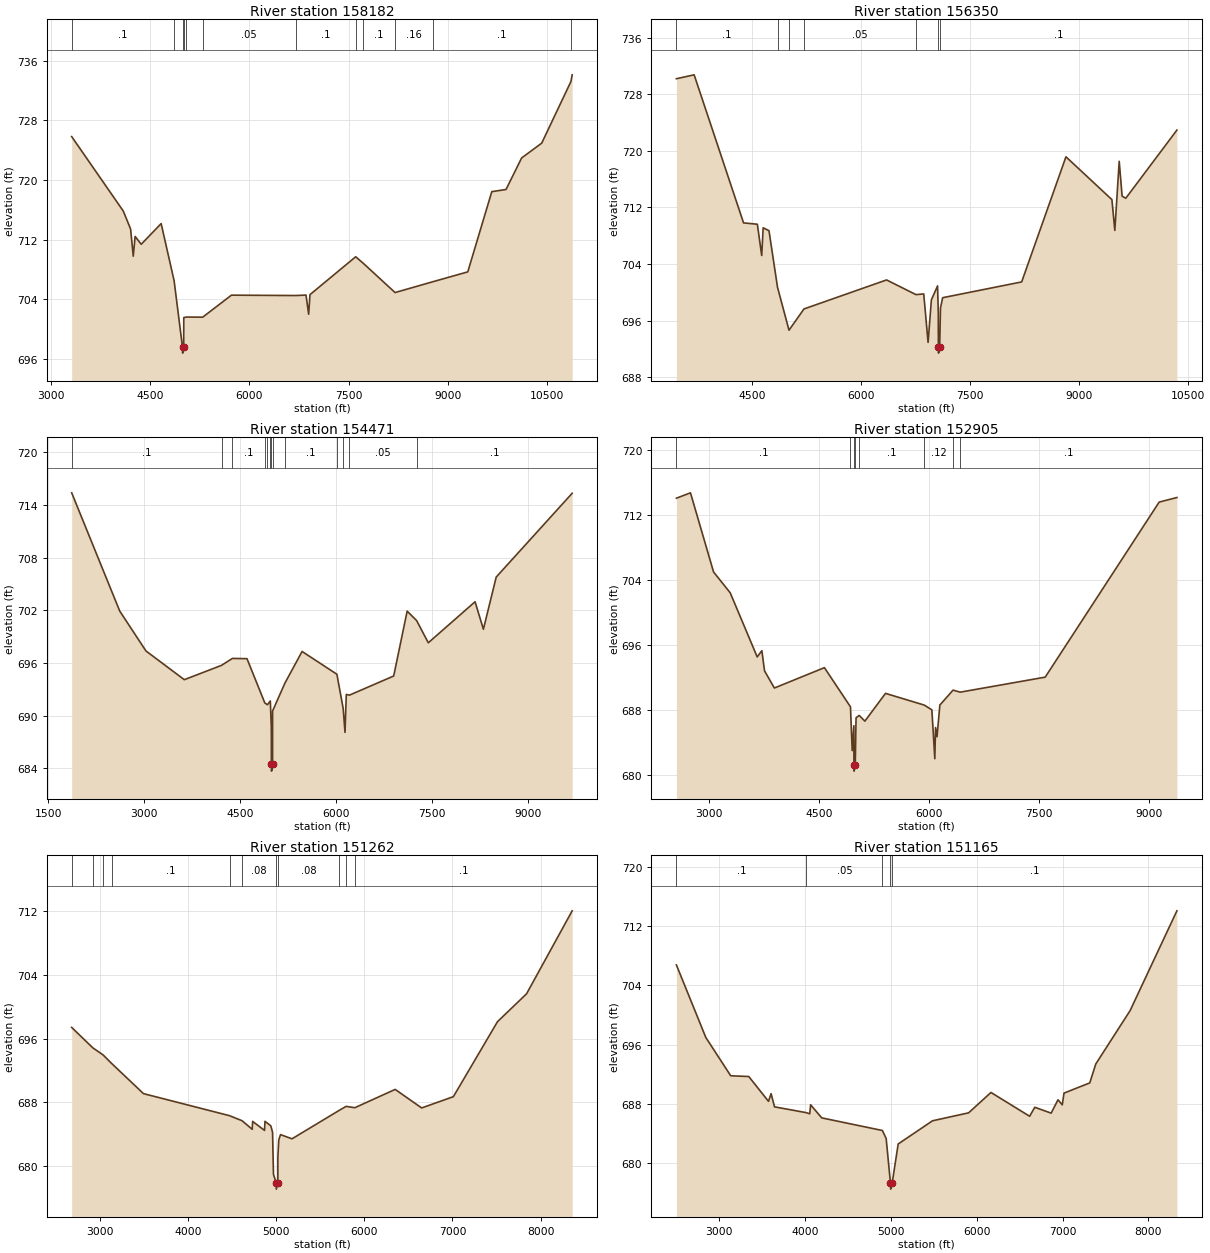
Type RM Length L Ch R = 1 ,158182  ,1832,1832,1832
BEGIN DESCRIPTION:
Black Creek 159.0
END DESCRIPTION:
XS GIS Cut Line= 3
      1977041.62     13605039.35      1972796.84     13604687.79
      1969529.26     13604232.15
#Sta/Elev= 30
  3317.5  725.83  4096.8  715.82  4207.2  713.41  4247.3  709.76  4275.6  712.41
  4367.7  711.36  4668.7  714.14  4864.4  706.45    4991  697.53  4993.4  696.73
  5008.7  697.53  5010.4   701.5  5049.2  701.58  5295.9  701.56    5730  704.52
  6700.4  704.47  6856.2  704.53  6896.3  701.96  6916.4  704.59  7606.6  709.68
  7717.8  708.83  8201.2  704.87  8777.9  706.34  9299.4  707.65  9662.1  718.43
  9876.8  718.72   10113  722.96 10415.9  724.95 10857.2  733.23   10876  734.13
#Mann= 12 ,-1 , 0
  3317.5      .1       0  4864.4     .16       0    4991     .07       0
  5008.7     .16       0  5049.2      .1       0  5295.9     .05       0
  6700.4      .1       0  7606.6     .05       0  7717.8      .1       0
  8201.2     .16       0  8777.9      .1       0 10857.2     .05       0
Bank Sta=4991,5008.7
XS Rating Curve= 0 ,0
Exp/Cntr=0.3,0.1

Type RM Length L Ch R = 1 ,156350  ,1879,1879,1879
BEGIN DESCRIPTION:
Black Creek 158.0
END DESCRIPTION:
XS GIS Cut Line= 3
      1976729.17     13603229.46      1973219.27     13603327.08
      1969854.11      13603008.1
#Sta/Elev= 30
  3453.1  730.18  3697.4  730.73  4377.6  709.81  4567.7  709.62  4627.7   705.2
  4647.7  709.12  4727.8  708.71  4845.4  700.71  5003.5  694.65  5209.3  697.65
  6346.7  701.75  6750.7  699.68  6858.6  699.77  6918.6  692.93    6964  698.94
    7049  700.91  7059.1  697.15  7060.1  692.21  7062.6  691.41  7078.1  692.21
  7089.2  697.79  7119.3  699.24  8207.1  701.47  8816.9  719.15  9449.7   713.1
  9489.9  708.75  9550.2  718.51  9590.3  713.59  9640.6  713.29 10344.6  722.92
#Mann= 7 ,-1 , 0
  3453.1      .1       0  4845.4     .16       0  5003.5      .1       0
  5209.3     .05       0  6750.7      .1       0  7060.1     .07       0
  7078.1      .1       0
Bank Sta=7060.1,7078.1
XS Rating Curve= 0 ,0
Exp/Cntr=0.3,0.1

Type RM Length L Ch R = 1 ,154471  ,1566,1566,1566
BEGIN DESCRIPTION:
Black Creek 157.0
END DESCRIPTION:
XS GIS Cut Line= 3
       1977906.3     13601726.53      1975036.42     13601719.04
      1970089.27     13601419.61
#Sta/Elev= 30
    1864  715.37  2615.3  701.91  3025.3  697.37  3625.3   694.1  4206.7  695.73
  4377.4  696.52  4605.3  696.49    4884  691.45  4925.6  691.25  4969.8  691.68
  4985.8  688.65  4986.8  684.49  4989.3  683.69  5004.8  684.49  5005.8  690.54
  5197.7   693.7  5466.7  697.31  6010.9  694.72  6109.3  690.82  6137.9   688.1
  6157.9  692.42  6207.6  692.34  6899.3  694.52  7109.7   701.9  7257.8  700.83
  7440.3   698.3  8171.6  702.97  8301.8  699.84  8502.2  705.78  9690.1  715.32
#Mann= 13 ,-1 , 0
    1864      .1       0  4206.7     .16       0  4377.4      .1       0
    4884     .16       0  4925.6      .1       0  4969.8     .16       0
  4986.8     .07       0  5004.8     .16       0  5197.7      .1       0
  6010.9     .05       0  6109.3     .16       0  6207.6     .05       0
  7257.8      .1       0
Bank Sta=4986.8,5004.8
XS Rating Curve= 0 ,0
Exp/Cntr=0.3,0.1

Type RM Length L Ch R = 1 ,152905  ,1643,1643,1643
BEGIN DESCRIPTION:
Black Creek 156.0
END DESCRIPTION:
XS GIS Cut Line= 2
      1977566.06      13600580.7      1970765.63     13599896.13
#Sta/Elev= 30
  2551.5  714.05  2743.5  714.71  3058.9  704.96  3286.3  702.39  3654.9  694.49
  3718.4  695.26  3755.1  692.77  3889.3  690.66  4572.7  693.17  4928.6  688.34
  4952.1  682.95  4974.7  686.01  4975.8  681.22  4978.3  680.42  4993.8  681.22
  5004.9     687  5048.1  687.28  5125.5  686.58  5406.9     690  5935.2  688.56
  6040.1  687.97  6080.3  681.95  6090.4  685.79  6110.5  684.66  6149.2  688.56
  6329.5   690.4    6428  690.15  7587.9     692  9144.3  713.57  9386.3  714.13
#Mann= 8 ,-1 , 0
  2551.5      .1       0  4928.6     .16       0  4975.8     .07       0
  4993.8     .16       0  5048.1      .1       0  5935.2     .12       0
  6329.5     .05       0    6428      .1       0
Bank Sta=4975.8,4993.8
XS Rating Curve= 0 ,0
Exp/Cntr=0.3,0.1

Type RM Length L Ch R = 1 ,151262  ,97,97,97
BEGIN DESCRIPTION:
Black Creek 155.0
END DESCRIPTION:
XS GIS Cut Line= 3
      1976956.78     13598977.07      1974652.22      13598811.4
      1971288.24     13598802.38
#Sta/Elev= 30
  2683.3   697.4  2923.3  694.83  3039.8  693.94  3138.2  692.85  3497.2  689.08
  4472.6  686.31  4614.4  685.68  4729.9   684.6  4734.9  685.59  4869.8  684.46
  4874.8   685.6  4940.9  685.03  4960.9  684.22    4971  678.94  5001.3  677.88
  5003.8  677.08  5020.7  677.88    5021  681.07    5031  683.25    5051  683.93
    5181   683.4  5718.4  686.99  5795.1  687.48  5893.4  687.31    6351  689.61
    6651  687.28    7011   688.7    7511  698.12    7841  701.63  8357.8  712.05
#Mann= 11 ,-1 , 0
  2683.3     .05       0  2923.3     .08       0  3039.8     .05       0
  3138.2      .1       0  4472.6     .05       0  4614.4     .08       0
  5001.3     .07       0  5020.7     .08       0  5718.4      .1       0
  5795.1     .05       0  5893.4      .1       0
Bank Sta=5001.3,5020.7
XS Rating Curve= 0 ,0
Exp/Cntr=0.3,0.1

Type RM Length L Ch R = 1 ,151165  ,1309,1309,1309
BEGIN DESCRIPTION:
Mapping XS 42406c9d
END DESCRIPTION:
XS GIS Cut Line= 3
      1977137.38     13598754.85       1974109.6     13598706.24
      1971310.96     13598609.01
#Sta/Elev= 30
  2503.1  706.74  2845.5  696.96  3135.6  691.79  3345.6  691.69  3575.6  688.34
  3605.6  689.38  3645.6   687.6  4017.3  686.81  4055.8  686.66  4065.7  687.88
  4195.7  686.11  4901.4  684.41  4945.8  683.33  4996.1   677.3  4998.6   676.5
  5015.5   677.3  5085.8  682.59  5485.9  685.72  5906.1  686.79  6166.2  689.54
  6616.5  686.33  6676.6  687.54  6867.3  686.75  6946.7  688.55  6996.8  687.87
  7016.8  689.45  7316.9  690.83    7387  693.38  7787.2  700.59  8331.6  714.04
#Mann= 5 ,-1 , 0
  2503.1      .1       0  4017.3     .05       0  4901.4      .1       0
  4996.1     .07       0  5015.5      .1       0
Bank Sta=4996.1,5015.5
XS Rating Curve= 0 ,0
Exp/Cntr=0.3,0.1