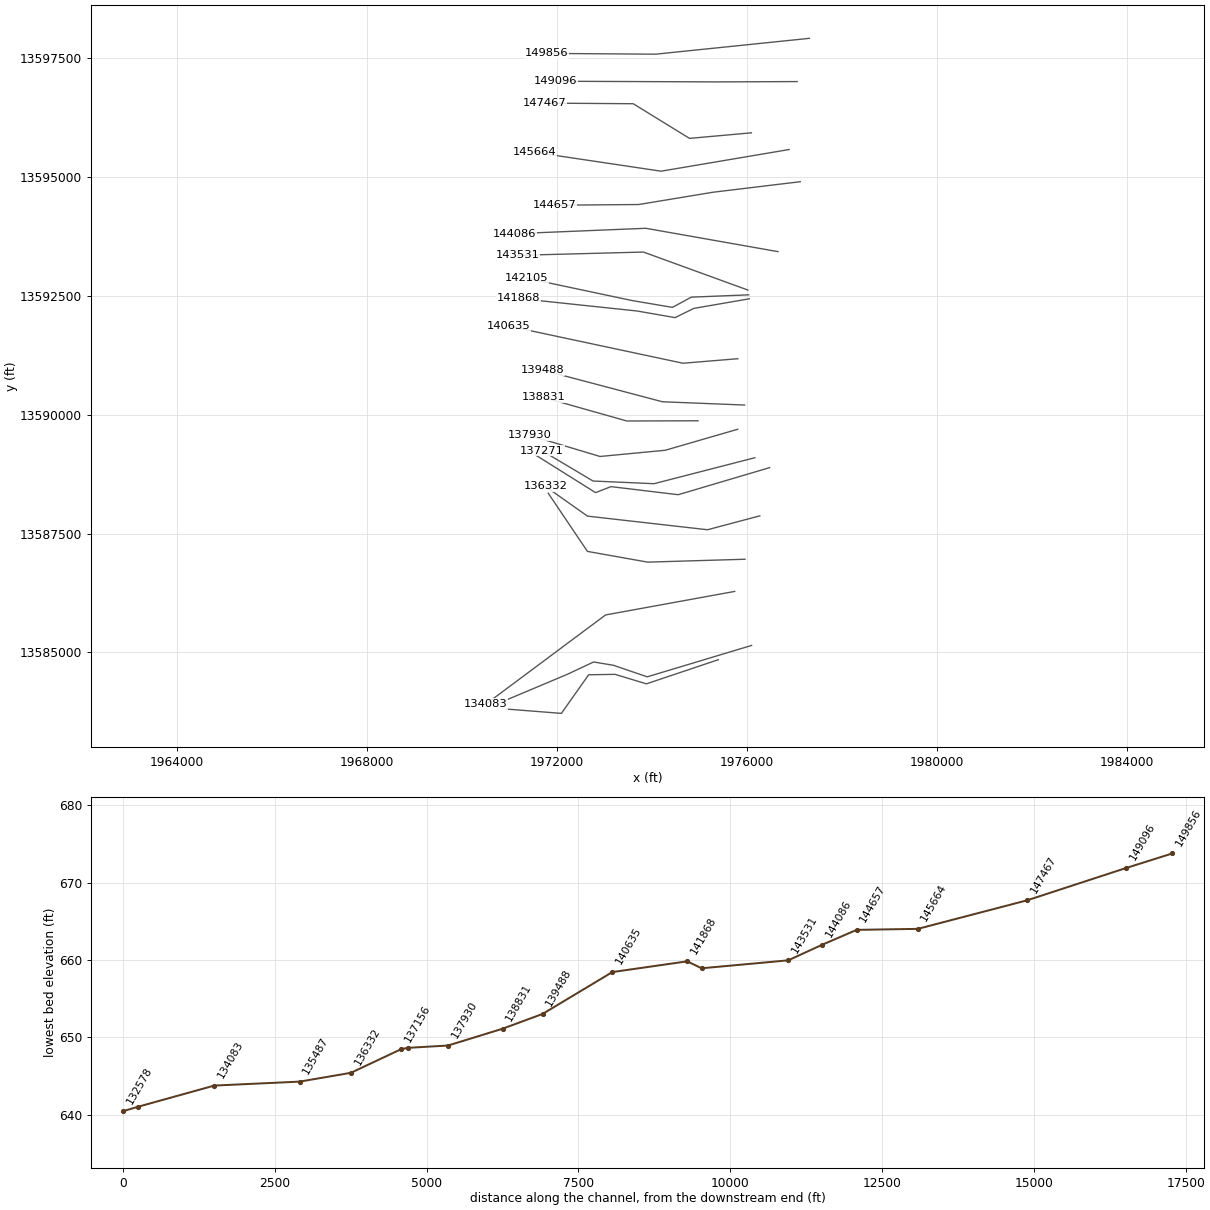
HEC-RAS study Black Creek.prj: Black Creek Base Level Engineering

--- Black Creek.g01 (geometry) --- (continued)

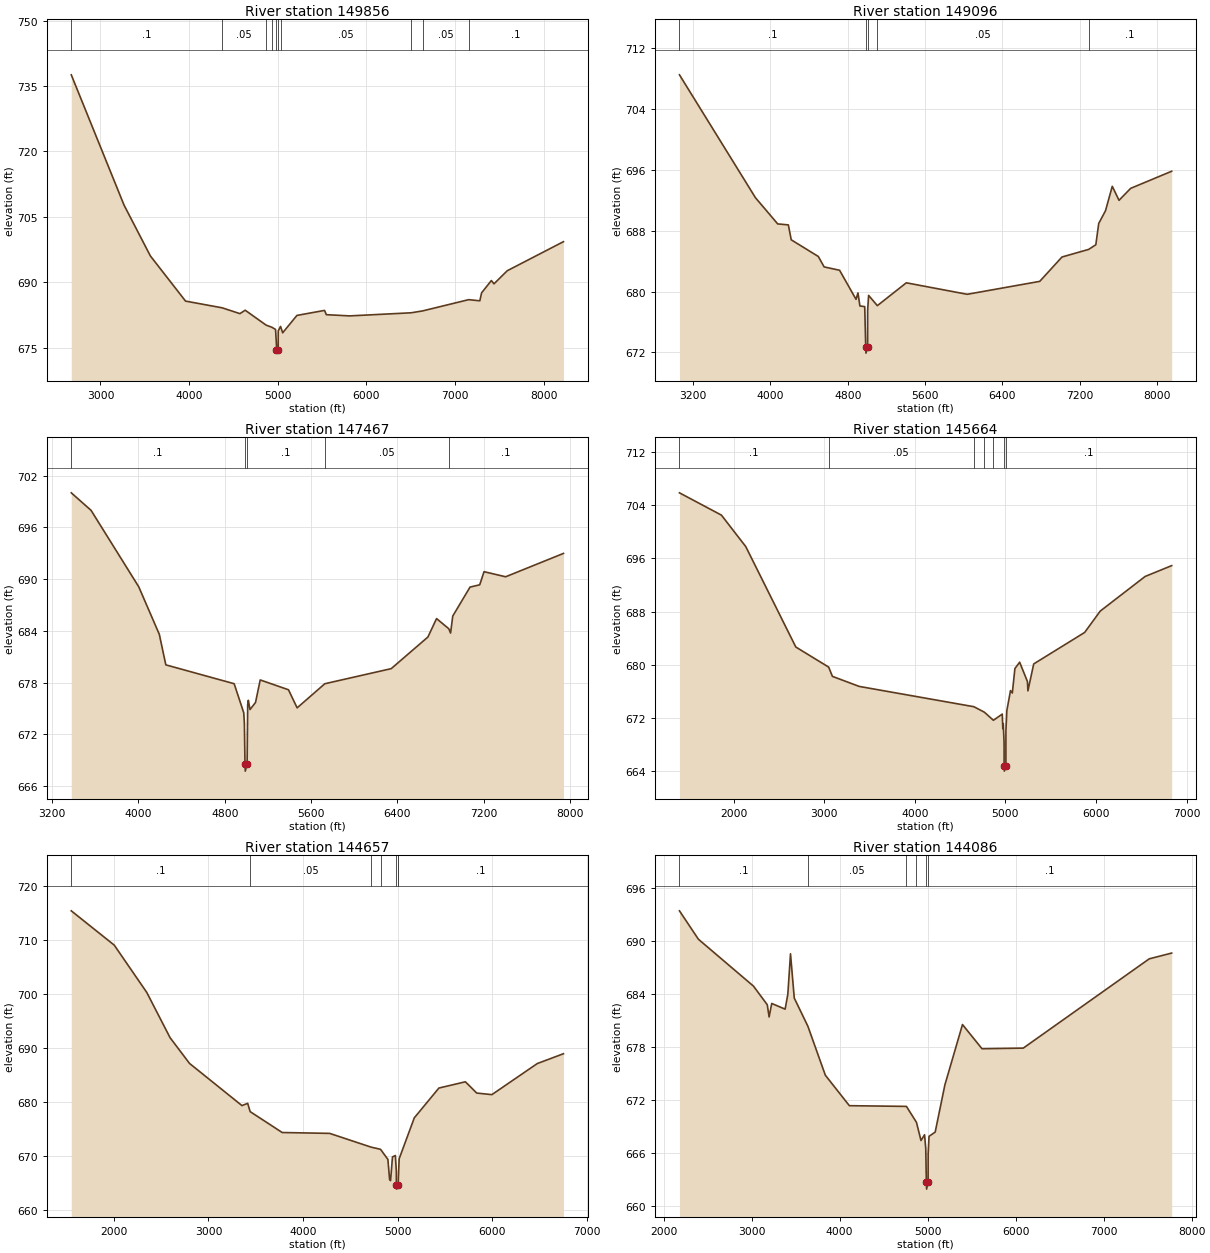
Type RM Length L Ch R = 1 ,149856  ,760,760,760
BEGIN DESCRIPTION:
Black Creek 154.0
END DESCRIPTION:
XS GIS Cut Line= 3
      1977317.94     13597921.51      1974081.82     13597588.18
      1971781.22     13597604.46
#Sta/Elev= 30
  2670.6  737.56  3266.3   707.7  3563.5  696.05  3960.3  685.71    4372  684.18
  4573.6  682.84  4633.1  683.62  4869.1  680.21  4933.6  679.72  4975.7  679.22
  4985.7  675.72  4986.1  674.59  4988.6  673.79  5005.5  674.59  5005.8  678.87
  5032.2  679.91  5056.1  678.45  5216.9  682.43  5528.6  683.58  5548.7   682.6
  5811.8  682.32  6504.8  683.03  6634.4  683.46  7154.7  686.04  7280.7  685.78
  7300.7   687.6  7410.7  690.42  7440.7  689.67  7590.1  692.67  8224.5  699.33
#Mann= 10 ,-1 , 0
  2670.6      .1       0    4372     .05       0  4869.1      .1       0
  4933.6     .07       0  4986.1     .07       0  5005.5     .07       0
  5032.2     .05       0  6504.8      .1       0  6634.4     .05       0
  7154.7      .1       0
Bank Sta=4986.1,5005.5
XS Rating Curve= 0 ,0
Exp/Cntr=0.3,0.1

Type RM Length L Ch R = 1 ,149096  ,1629,1629,1629
BEGIN DESCRIPTION:
Black Creek 153.0
END DESCRIPTION:
XS GIS Cut Line= 3
      1977060.98     13597011.79      1975394.32     13597004.85
      1971970.72     13597018.74
#Sta/Elev= 30
  3059.8  708.48  3845.8  692.33  4075.8  688.89  4185.8  688.76  4215.8   686.8
  4495.8  684.61  4555.8  683.24  4715.8   682.8  4885.8  678.98  4905.8  679.82
  4925.8  678.11  4975.8  678.02    4986  672.71  4988.5  671.91  5005.5  672.71
  5005.8  677.49  5015.8   679.5  5106.3  678.15  5405.8  681.15  6035.8  679.64
  6785.8  681.34  7015.8  684.54  7291.7  685.54  7365.8  686.15  7395.8  688.95
  7465.8  690.62  7535.8  693.83  7605.8  691.99  7725.8  693.56  8150.1  695.81
#Mann= 5 ,-1 , 0
  3059.8      .1       0    4986     .07       0  5005.5      .1       0
  5106.3     .05       0  7291.7      .1       0
Bank Sta=4986,5005.5
XS Rating Curve= 0 ,0
Exp/Cntr=0.3,0.1

Type RM Length L Ch R = 1 ,147467  ,1803,1803,1803
BEGIN DESCRIPTION:
Mapping XS 1339d556
END DESCRIPTION:
XS GIS Cut Line= 4
      1976097.44     13595933.67      1974795.36     13595816.48
      1973610.46     13596545.65      1971749.23     13596558.66
#Sta/Elev= 30
  3378.2  700.02  3561.4  697.99  4003.2  689.12  4193.9   683.6  4254.2  680.06
  4887.3  677.87  4976.1   674.5  4981.9  673.28  4987.6  668.53  4990.1  667.73
  5007.1  668.53  5012.7  675.45  5018.6  675.95    5034  674.87  5085.2   675.7
  5128.7  678.31  5390.5  677.17  5470.7  675.07  5727.2  677.87  6342.3  679.62
  6682.3  683.29  6762.3  685.43  6875.7  684.25  6892.3  683.75  6912.3  685.72
  7072.3  689.08  7162.3  689.35  7202.3  690.87  7402.3  690.28  7938.1  692.99
#Mann= 5 ,-1 , 0
  3378.2      .1       0  4987.6     .07       0  5007.1      .1       0
  5727.2     .05       0  6875.7      .1       0
Bank Sta=4987.6,5007.1
XS Rating Curve= 0 ,0
Exp/Cntr=0.3,0.1

Type RM Length L Ch R = 1 ,145664  ,1007,1007,1007
BEGIN DESCRIPTION:
Black Creek 152.0
END DESCRIPTION:
XS GIS Cut Line= 3
      1976891.67      13595582.1       1974196.4     13595126.38
        1971525.       13595525.
#Sta/Elev= 30
  1401.4  705.85  1864.6   702.5  2133.5  697.77    2686  682.68  3048.9  679.66
  3090.1  678.27  3385.8  676.76  4652.1  673.71  4767.7  672.89  4867.7  671.67
  4965.4   672.6  4971.5  670.41  4976.6  671.18  4985.6  668.32  4985.9  664.83
  4988.4  664.03  5005.7  664.83  5005.9  670.12    5016  673.11  5056.4  676.13
  5076.6  675.77    5105  679.44  5157.5   680.4  5243.5  677.49  5248.6  676.09
  5312.8  680.14  5875.4  684.87  6047.3  688.08  6542.7  693.28  6835.9  694.91
#Mann= 7 ,-1 , 0
  1401.4      .1       0  3048.9     .05       0  4652.1      .1       0
  4767.7     .16       0  4867.7      .1       0  4985.9     .07       0
  5005.7      .1       0
Bank Sta=4985.9,5005.7
XS Rating Curve= 0 ,0
Exp/Cntr=0.3,0.1

Type RM Length L Ch R = 1 ,144657  ,571,571,571
BEGIN DESCRIPTION:
Black Creek 151.0
END DESCRIPTION:
XS GIS Cut Line= 4
      1977126.13     13594905.03      1975290.15     13594683.67
        1973725.       13594425.      1971958.42     13594410.24
#Sta/Elev= 30
  1549.8  715.47  2004.2  709.11  2347.7  700.35  2593.9  691.97  2799.9  687.19
  3353.9  679.38  3414.4   679.8  3440.6  678.26  3779.3  674.39  4280.6  674.23
  4719.2  671.68  4818.4  671.28  4896.4  669.41  4914.5  665.67  4924.6  665.48
  4944.9  669.87  4975.3  670.13  4985.5  667.23  4985.6   664.7  4988.1   663.9
  5005.4   664.7  5007.5  666.19  5015.5  669.53  5175.5  677.11  5435.5  682.63
  5715.5  683.79  5835.5   681.7  5995.5  681.41  6475.5  687.17  6752.1  688.99
#Mann= 7 ,-1 , 0
  1549.8      .1       0  3440.6     .05       0  4719.2     .12       0
  4818.4     .16       0  4985.6     .07       0  5005.4     .16       0
  5007.5      .1       0
Bank Sta=4985.6,5005.4
XS Rating Curve= 0 ,0
Exp/Cntr=0.3,0.1

Type RM Length L Ch R = 1 ,144086  ,555,555,555
BEGIN DESCRIPTION:
Black Creek 150.0
END DESCRIPTION:
XS GIS Cut Line= 3
      1976657.34     13593433.67        1973875.       13593925.
      1971110.43     13593811.27
#Sta/Elev= 30
  2180.5  693.38  2396.1  690.17  3021.3  684.88    3178  682.78    3199   681.4
  3228.8  682.92  3381.1  682.28  3411.6  683.95  3442.1  688.53  3484.9  683.53
  3639.1  680.36  3838.1  674.82  4110.9  671.38  4759.4   671.3  4873.3   669.5
  4924.7  667.45  4965.3   668.1  4978.8  666.54  4985.8  662.76  4988.3  661.96
  5005.6  662.76  5005.9   665.9  5015.9  667.92    5086   668.4    5196  673.72
  5396.2  680.54  5617.8  677.81  6086.8  677.88    7518  687.96  7772.8  688.61
#Mann= 6 ,-1 , 0
  2180.5      .1       0  3639.1     .05       0  4759.4      .1       0
  4873.3     .16       0  4985.8     .07       0  5005.6      .1       0
Bank Sta=4985.8,5005.6
XS Rating Curve= 0 ,0
Exp/Cntr=0.3,0.1

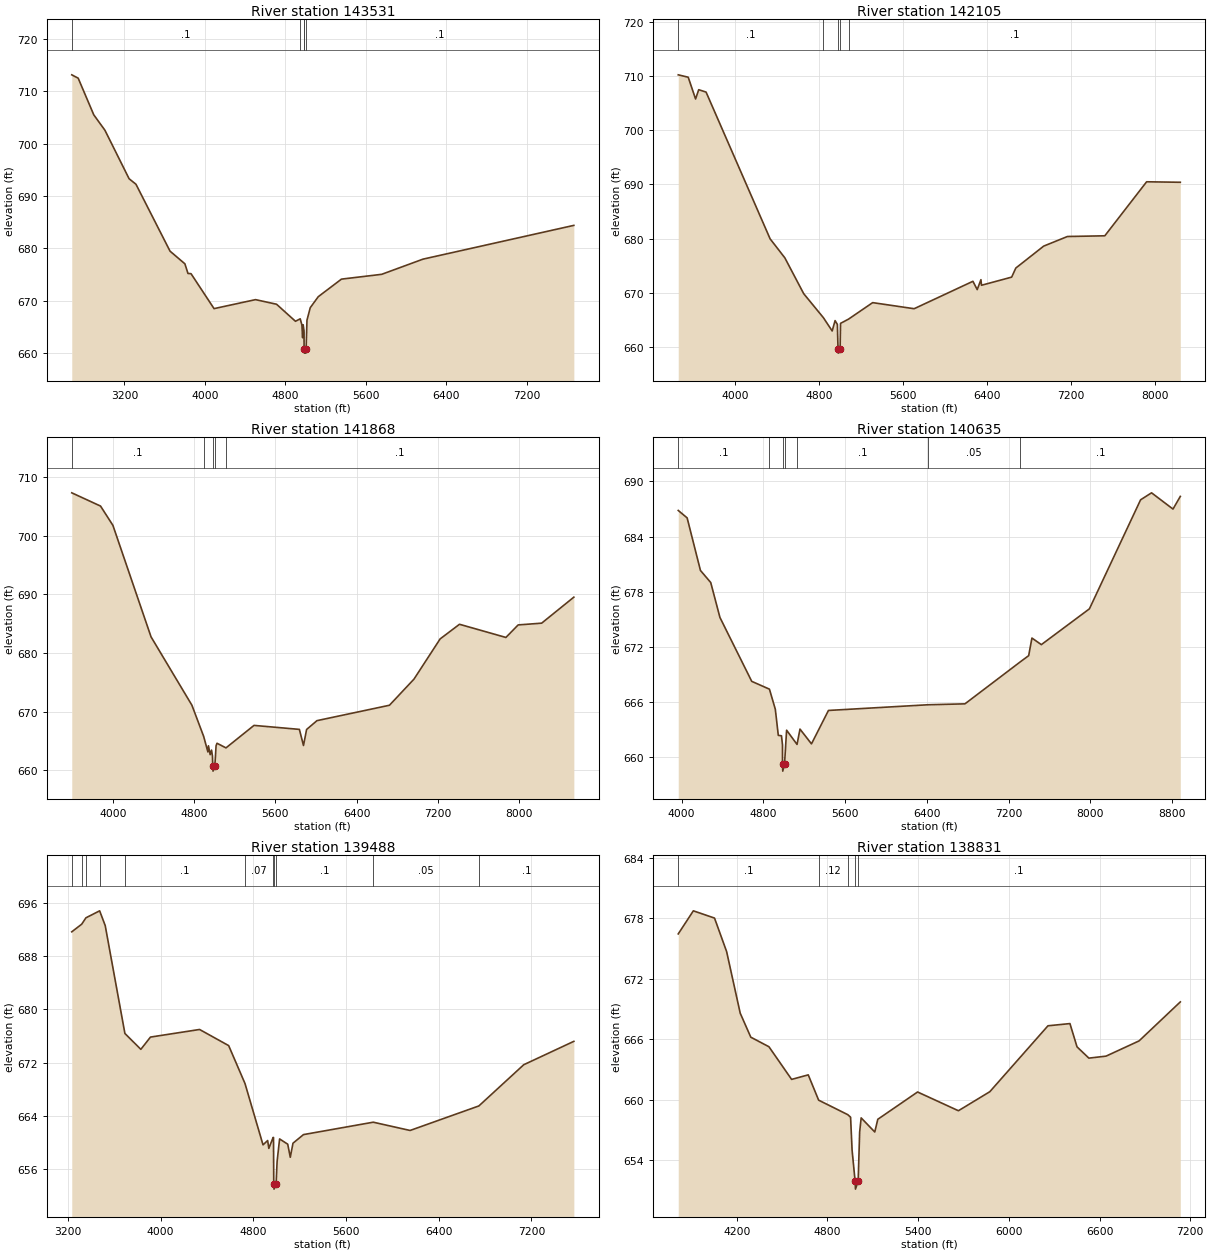
Type RM Length L Ch R = 1 ,143531  ,1426,1426,1426
BEGIN DESCRIPTION:
Black Creek 149.0
END DESCRIPTION:
XS GIS Cut Line= 3
      1976024.97     13592625.01        1973825.       13593425.
      1971175.52     13593355.54
#Sta/Elev= 30
  2675.9  713.18  2739.7  712.54  2894.7  705.53  3005.7  702.58  3245.8  693.31
  3314.3  692.25  3652.8  679.46  3800.5  677.04    3831   675.2  3861.6  675.15
  4090.4  668.47  4502.7  670.19  4711.6  669.31  4899.8  666.05  4947.1  666.52
  4963.6  665.35  4970.9   662.9  4976.2  665.37  4984.9  664.18  4985.6  660.76
  4988.1  659.96  5002.9  659.96  5005.4  660.76  5014.2  666.26  5046.8  668.65
  5126.8  670.76  5356.9  674.11  5757.1  675.03  6167.2  677.93  7667.2  684.39
#Mann= 5 ,-1 , 0
  2675.9      .1       0  4947.1     .16       0  4984.9      .1       0
  4985.6     .07       0  5005.4      .1       0
Bank Sta=4985.6,5005.4
XS Rating Curve= 0 ,0
Exp/Cntr=0.3,0.1

Type RM Length L Ch R = 1 ,142105  ,237,237,237
BEGIN DESCRIPTION:
Black Creek 148.0
END DESCRIPTION:
XS GIS Cut Line= 5
      1976040.17     13592524.81      1974831.82      13592476.2
      1974435.99     13592260.92      1973584.42     13592405.02
      1971370.89     13592873.77
#Sta/Elev= 30
  3459.4  710.19  3554.6  709.75  3624.7  705.74  3654.7  707.45  3724.8  707.01
  4335.3  679.98  4475.4  676.49  4655.5  669.88  4843.9  665.44  4926.9  663.01
  4954.6  664.92  4976.4  664.22  4982.6  659.73  4985.1  658.93  5002.6  659.73
  5006.6  664.41  5083.3   665.2    5313  668.23  5708.3  667.11  6268.6  672.16
  6309.5  670.63  6345.1  672.46  6350.4  671.43  6638.1  672.93  6677.5   674.6
  6943.2  678.64  7169.4  680.41  7525.9  680.54  7924.5  690.49  8245.6   690.4
#Mann= 5 ,-1 , 0
  3459.4      .1       0  4843.9     .16       0  4982.6     .07       0
  5002.6     .16       0  5083.3      .1       0
Bank Sta=4982.6,5002.6
XS Rating Curve= 0 ,0
Exp/Cntr=0.3,0.1

Type RM Length L Ch R = 1 ,141868  ,1233,1233,1233
BEGIN DESCRIPTION:
Mapping XS d492dd05
END DESCRIPTION:
XS GIS Cut Line= 5
      1976054.01     13592441.47      1974887.37     13592240.09
      1974491.54     13592045.65      1973692.93     13592184.53
      1971199.96     13592448.41
#Sta/Elev= 30
  3597.1  707.36  3880.2   705.1    4002  701.81  4377.5  682.76  4779.7  671.09
  4895.7  665.75    4937  663.11  4942.6  664.16  4959.5  662.64    4973  663.42
    4982  662.41  4985.3  660.63  4987.8  659.83  5005.3  660.63  5017.6  664.16
  5026.9  664.59  5115.2   663.8    5391  667.64  5837.6  666.96  5878.2  664.21
  5908.7  666.94  6010.7  668.45  6724.4  671.08  6965.7  675.54  7223.3  682.41
  7413.9  684.91  7870.7  682.66  7991.4   684.8  8222.7   685.1  8539.5  689.54
#Mann= 5 ,-1 , 0
  3597.1      .1       0  4895.7     .16       0  4985.3     .07       0
  5005.3     .16       0  5115.2      .1       0
Bank Sta=4985.3,5005.3
XS Rating Curve= 0 ,0
Exp/Cntr=0.3,0.1

Type RM Length L Ch R = 1 ,140635  ,1147,1147,1147
BEGIN DESCRIPTION:
Black Creek 147.0
END DESCRIPTION:
XS GIS Cut Line= 3
      1975811.84     13591181.06      1974657.34     13591085.58
      1970984.96     13591868.72
#Sta/Elev= 30
  3966.8  686.84  4053.9  686.03  4184.4   680.3  4284.7  678.99    4375  675.18
  4686.1  668.22  4859.4  667.37  4916.9  665.18  4946.1  662.34  4977.1  662.29
  4987.1   661.3  4987.2  659.24  4989.7  658.44  5007.2  659.24  5027.3   662.9
  5129.4  661.35  5158.3  663.02  5270.8  661.41  5436.8  665.05  6410.8  665.67
  6772.7  665.77  7314.7  670.35  7396.2  671.02  7428.2  672.94  7520.3  672.22
  7990.6  676.12  8491.6     688  8598.8  688.76  8808.6  686.99  8880.2  688.37
#Mann= 7 ,-1 , 0
  3966.8      .1       0  4859.4     .16       0  4987.2     .07       0
  5007.2     .16       0  5129.4      .1       0  6410.8     .05       0
  7314.7      .1       0
Bank Sta=4987.2,5007.2
XS Rating Curve= 0 ,0
Exp/Cntr=0.3,0.1

Type RM Length L Ch R = 1 ,139488  ,657,657,657
BEGIN DESCRIPTION:
Black Creek 146.0
END DESCRIPTION:
XS GIS Cut Line= 3
      1975953.35     13590206.24        1974225.       13590275.
       1971710.4     13590940.12
#Sta/Elev= 30
  3234.5  691.63  3320.4  692.78  3356.6  693.73  3474.9  694.78  3523.1  692.56
  3692.9  676.38  3830.3     674  3913.4  675.84    4337  676.98  4587.9  674.56
  4728.6  668.88  4884.2  659.67  4924.2  660.32  4934.2  659.14  4971.4  660.78
  4974.6  660.78  4976.8  653.83  4979.3  653.03    4997  653.83  5005.6  657.16
  5027.2  660.56  5097.3  659.77  5119.4  657.81  5142.7  659.92  5233.2  661.21
    5835  663.07  6152.8  661.83  6746.1  665.51    7133  671.69  7565.3   675.2
#Mann= 11 ,-1 , 0
  3234.5      .1       0  3320.4     .16       0  3356.6      .1       0
  3474.9     .16       0  3692.9      .1       0  4728.6     .07       0
  4971.4      .1       0  4976.8     .07       0    4997      .1       0
    5835     .05       0  6746.1      .1       0
Bank Sta=4976.8,4997
XS Rating Curve= 0 ,0
Exp/Cntr=0.3,0.1

Type RM Length L Ch R = 1 ,138831  ,901,901,901
BEGIN DESCRIPTION:
Black Creek 145.0
END DESCRIPTION:
XS GIS Cut Line= 3
      1974974.98       13589875.      1973475.92     13589870.73
      1971722.46     13590365.52
#Sta/Elev= 30
  3812.9  676.45  3912.9  678.74  4052.9  678.02  4132.9   674.7  4222.9  668.58
  4292.9   666.2  4412.9  665.25  4562.9  662.01  4672.9  662.46  4741.6  659.95
  4934.3  658.51  4952.9  658.26  4962.9  654.99  4982.8  651.92  4985.3  651.12
    5003  651.92  5012.9  656.78  5022.9  658.19  5112.9  656.79  5132.9  658.05
    5396  660.76  5666.2   658.9    5874  660.79  6258.5  667.33  6403.9  667.55
  6450.7  665.24  6529.1  664.12  6642.9  664.32  6861.1  665.83  7133.9   669.7
#Mann= 5 ,-1 , 0
  3812.9      .1       0  4741.6     .12       0  4934.3      .1       0
  4982.8     .07       0    5003      .1       0
Bank Sta=4982.8,5003
XS Rating Curve= 0 ,0
Exp/Cntr=0.3,0.1

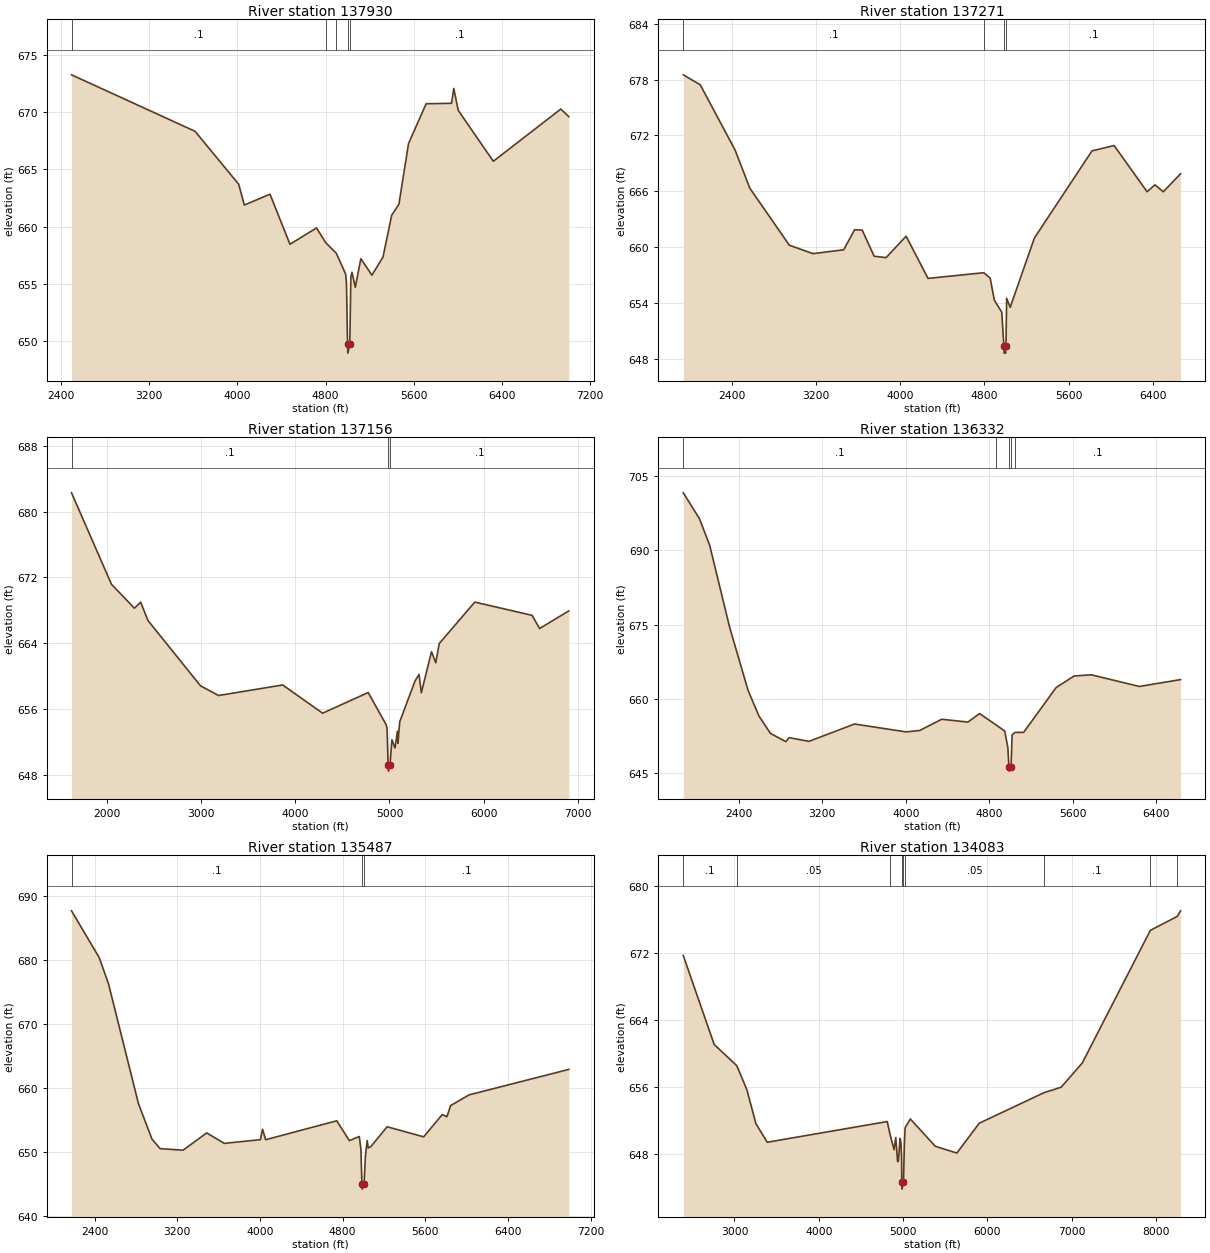
Type RM Length L Ch R = 1 ,137930  ,659,659,659
BEGIN DESCRIPTION:
Black Creek 144.0
END DESCRIPTION:
XS GIS Cut Line= 4
      1975810.96     13589697.11      1974283.21     13589254.41
      1972911.68      13589124.2      1971435.95     13589566.92
#Sta/Elev= 30
  2496.5  673.28  3616.7  668.34  4012.4  663.71  4063.1  661.89  4296.2  662.84
  4477.1  658.46  4718.1  659.89  4800.4  658.61  4897.1  657.68  4982.3  655.85
  4989.3  655.08  4999.3  649.74  5001.8  648.94  5019.6  649.74  5029.5  655.61
  5039.6  656.01  5069.7   654.7  5119.9   657.2  5220.4  655.76  5320.8  657.34
  5399.8  661.01  5464.8  661.95  5552.3  667.27  5711.9  670.75  5942.1  670.79
  5962.5  672.09    6003  670.17  6321.4  665.72  6933.4  670.29  7005.5  669.62
#Mann= 5 ,-1 , 0
  2496.5      .1       0  4800.4     .12       0  4897.1      .1       0
  4999.3     .07       0  5019.6      .1       0
Bank Sta=4999.3,5019.6
XS Rating Curve= 0 ,0
Exp/Cntr=0.3,0.1

Type RM Length L Ch R = 1 ,137271  ,115,115,115
BEGIN DESCRIPTION:
Black Creek 143.0
END DESCRIPTION:
XS GIS Cut Line= 4
      1976171.24     13589098.17      1974048.83     13588551.29
      1972764.11     13588607.71      1971692.09     13589245.72
#Sta/Elev= 30
  1939.4  678.51  2100.7  677.44  2431.2  670.45  2571.9  666.34  2947.5  660.22
    3172  659.32  3463.9  659.73  3567.1  661.88  3639.4  661.85    3753  659.04
  3866.6  658.89  4056.9  661.19  4265.1  656.66  4794.5  657.27  4855.7  656.69
  4895.7  654.31  4965.8  653.03  4985.6  649.44  4988.1  648.64  5003.4  648.64
  5005.9  649.44  5012.1  654.52  5045.8  653.56  5276.1     661  5823.3  670.35
  6033.2  670.92    6347  665.96  6420.7   666.7  6500.6  665.96  6664.6  667.89
#Mann= 4 ,-1 , 0
  1939.4      .1       0  4794.5     .07       0  4985.6     .07       0
  5005.9      .1       0
Bank Sta=4985.6,5005.9
XS Rating Curve= 0 ,0
Exp/Cntr=0.3,0.1

Type RM Length L Ch R = 1 ,137156  ,824,824,824
BEGIN DESCRIPTION:
Black Creek 142.0
END DESCRIPTION:
XS GIS Cut Line= 5
      1976480.22     13588888.95      1974556.89     13588319.58
      1973142.58     13588489.66      1972817.06     13588363.79
      1971551.43     13589157.19
#Sta/Elev= 30
  1628.3  682.28  2051.7  671.17    2295  668.26  2361.5  668.99  2438.4  666.77
  2996.6  658.82  3187.7  657.65  3867.7  658.93  4290.7   655.5  4774.2  658.01
  4965.6  654.08  4974.2  653.67  4985.6  649.26  4988.1  648.46  5005.9  649.26
    5026  652.28  5058.6  651.27  5084.1  653.31  5089.5  651.84  5108.7  654.46
  5270.5  659.41  5313.4  660.22  5337.6  657.98  5445.5  662.97  5490.7  661.62
  5527.3  663.96  5904.4     669  6512.5  667.39  6591.4  665.79  6901.4  667.93
#Mann= 3 ,-1 , 0
  1628.3      .1       0  4985.6     .07       0  5005.9      .1       0
Bank Sta=4985.6,5005.9
XS Rating Curve= 0 ,0
Exp/Cntr=0.3,0.1

Type RM Length L Ch R = 1 ,136332  ,845,845,845
BEGIN DESCRIPTION:
Black Creek 141.0
END DESCRIPTION:
XS GIS Cut Line= 4
      1976275.02       13587875.      1975173.83     13587582.54
      1972647.79       13587869.      1971762.35     13588494.01
#Sta/Elev= 30
  1867.5  701.58  2022.7  696.36  2120.9  690.97  2311.4  674.47  2488.3  661.72
  2592.6  656.54  2702.8  653.03  2850.5  651.36  2881.5  652.17  3072.1  651.42
  3508.9  654.92    4002  653.33  4132.9  653.61  4344.2  655.88  4595.8  655.31
  4706.5  657.03  4861.2  654.79  4948.1   653.5  4978.2  650.16  4988.2  646.21
  4990.7  645.41  5008.5  646.21  5018.5  652.73  5046.3  653.23  5129.2  653.23
  5441.2  662.29  5613.7  664.62  5777.6  664.85    6238   662.5  6632.9  663.88
#Mann= 5 ,-1 , 0
  1867.5      .1       0  4861.2     .12       0  4988.2     .07       0
  5008.5     .12       0  5046.3      .1       0
Bank Sta=4988.2,5008.5
XS Rating Curve= 0 ,0
Exp/Cntr=0.3,0.1

Type RM Length L Ch R = 1 ,135487  ,1404,1404,1404
BEGIN DESCRIPTION:
Mapping XS b993c6b8
END DESCRIPTION:
XS GIS Cut Line= 4
      1975962.65     13586961.89      1973914.03     13586901.13
      1972646.67     13587126.82      1971822.28     13588350.39
#Sta/Elev= 30
  2177.4  687.69  2445.2   680.4  2535.2  676.31  2825.3   657.6  2955.4  652.09
  3035.4  650.58  3256.8  650.35  3485.6  653.04  3655.7  651.41  4005.9  651.99
  4025.9  653.62  4055.9  651.98    4744  654.93  4865.9  651.84  4962.2  652.48
  4977.6  650.51  4987.7  645.07  4990.2  644.27    5008  645.07  5021.1  649.35
  5038.5  651.85  5048.7   650.7  5075.1  650.92  5231.5     654  5585.1  652.43
  5765.2   655.9    5810  655.56    5846  657.31  6025.9  658.98  6989.6  662.95
#Mann= 3 ,-1 , 0
  2177.4      .1       0  4987.7     .07       0    5008      .1       0
Bank Sta=4987.7,5008
XS Rating Curve= 0 ,0
Exp/Cntr=0.3,0.1

Type RM Length L Ch R = 1 ,134083  ,1251,1251,1251
BEGIN DESCRIPTION:
Black Creek 140.0
END DESCRIPTION:
XS GIS Cut Line= 3
      1975745.62     13586284.81      1973028.61     13585790.02
      1970511.25     13583915.01
#Sta/Elev= 30
    2393  671.66  2759.7  661.04  3028.5   658.5  3148.2  655.62  3254.8  651.58
  3389.7  649.36  4812.8  651.83  4849.1  650.19  4894.1  648.47  4914.4  649.93
  4935.7  647.06  4944.9  647.07  4965.2  649.83  4975.4  649.31  4983.9  647.46
  4985.6  644.56  4988.1  643.76  5005.9  644.56  5016.1  649.04  5024.9  651.07
  5087.2  652.14  5383.2  648.88  5639.7  648.07  5904.6  651.63  6671.1  655.27
  6876.4  655.93  7126.6  658.81  7935.7  674.67  8253.6  676.33  8293.6     677
#Mann= 9 ,-1 , 0
    2393      .1       0  3028.5     .05       0  4849.1      .1       0
  4985.6     .07       0  5005.9      .1       0  5024.9     .05       0
  6671.1      .1       0  7935.7     .05       0  8253.6      .1       0
Bank Sta=4985.6,5005.9
XS Rating Curve= 0 ,0
Exp/Cntr=0.3,0.1

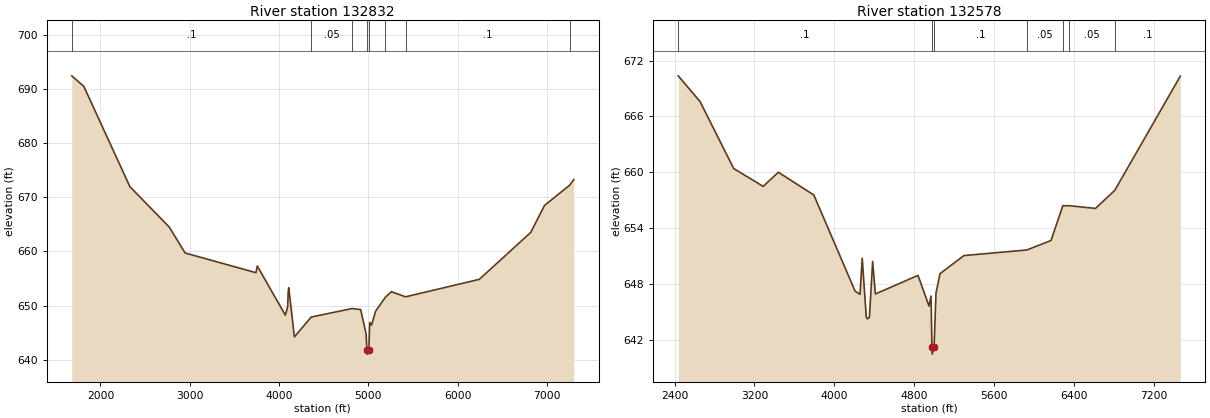
Type RM Length L Ch R = 1 ,132832  ,254,254,254
BEGIN DESCRIPTION:
Black Creek 139.0
END DESCRIPTION:
XS GIS Cut Line= 6
      1976101.04     13585148.26      1973905.35     13584487.93
      1973193.54     13584730.99      1972776.88     13584800.43
      1972221.32     13584540.02      1970798.86     13583941.54
#Sta/Elev= 30
  1678.5  692.46  1813.3  690.52  2329.6  671.98  2770.8  664.51  2948.3  659.72
    3742  656.08  3756.7  657.32  4071.3  648.23  4097.4  649.83  4102.6  652.45
  4109.1   653.3  4172.5  644.21  4360.6  647.88  4818.9  649.46  4914.6  649.26
  4975.5  644.77  4985.1  641.83  4987.7  641.03  5006.4  641.83    5016  646.89
  5036.3  646.39  5082.2  648.97  5189.6   651.5  5258.4  652.57  5417.6  651.62
  6243.7  654.85  6820.4  663.53  6973.7   668.5  7256.1  672.25  7302.7   673.3
#Mann= 8 ,-1 , 0
  1678.5      .1       0  4360.6     .05       0  4818.9      .1       0
  4985.1     .07       0  5006.4      .1       0  5189.6     .05       0
  5417.6      .1       0  7256.1     .05       0
Bank Sta=4985.1,5006.4
XS Rating Curve= 0 ,0
Exp/Cntr=0.3,0.1

Type RM Length L Ch R = 1 ,132578  ,468,468,468
BEGIN DESCRIPTION:
Black Creek 138.0
END DESCRIPTION:
XS GIS Cut Line= 6
      1975401.05     13584848.27      1973887.99     13584340.37
      1973228.27     13584540.02      1972672.71     13584531.34
      1972098.72     13583719.03      1970929.01     13583810.77
#Sta/Elev= 30
  2437.2  670.37  2655.8   667.6  2992.1   660.4  3287.4  658.48  3438.9     660
  3793.8  657.55  4206.7  647.21  4255.8  646.87  4277.8  650.76  4318.4  644.43
  4328.9  644.23  4349.8  644.41  4381.8  650.41  4409.5  646.91  4835.8  648.91
  4945.8  645.61  4965.8  646.69  4975.1  641.24  4977.7  640.44  4996.4  641.24
  5015.8     647  5055.8  649.09  5295.1  651.04  5924.3  651.64  6166.3  652.66
  6284.6   656.4  6350.2   656.4  6611.2  656.11    6804  658.05  7459.8  670.34
#Mann= 7 ,-1 , 0
  2437.2      .1       0  4975.1     .07       0  4996.4      .1       0
  5924.3     .05       0  6284.6      .1       0  6350.2     .05       0
    6804      .1       0
Bank Sta=4975.1,4996.4
XS Rating Curve= 0 ,0
Exp/Cntr=0.3,0.1