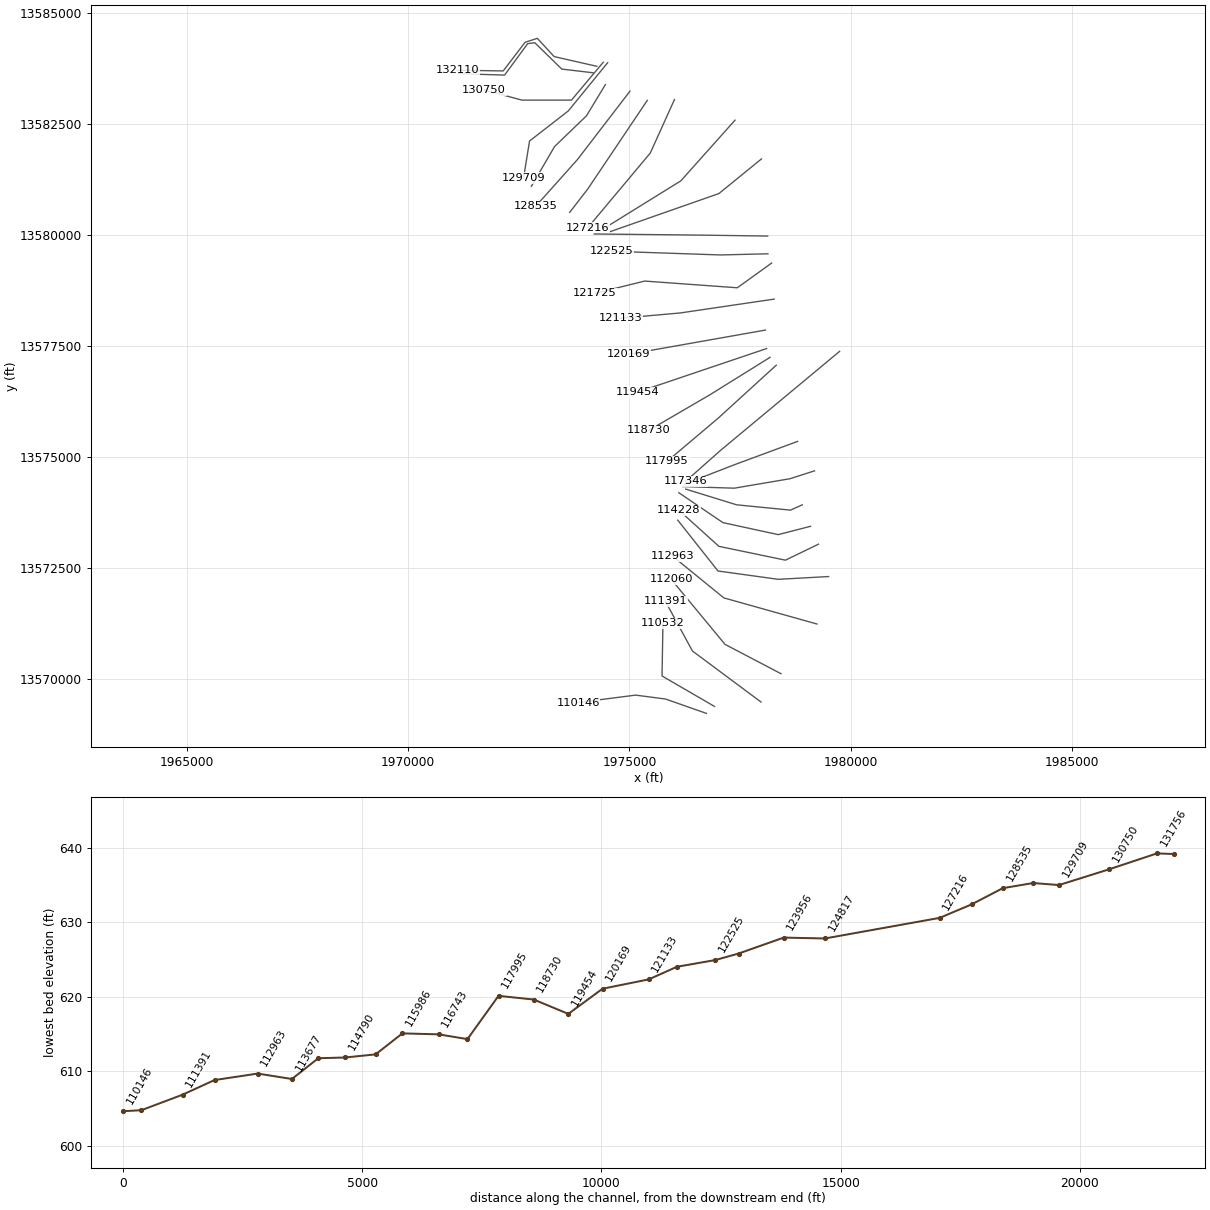
HEC-RAS study Black Creek.prj: Black Creek Base Level Engineering

--- Black Creek.g01 (geometry) --- (continued)

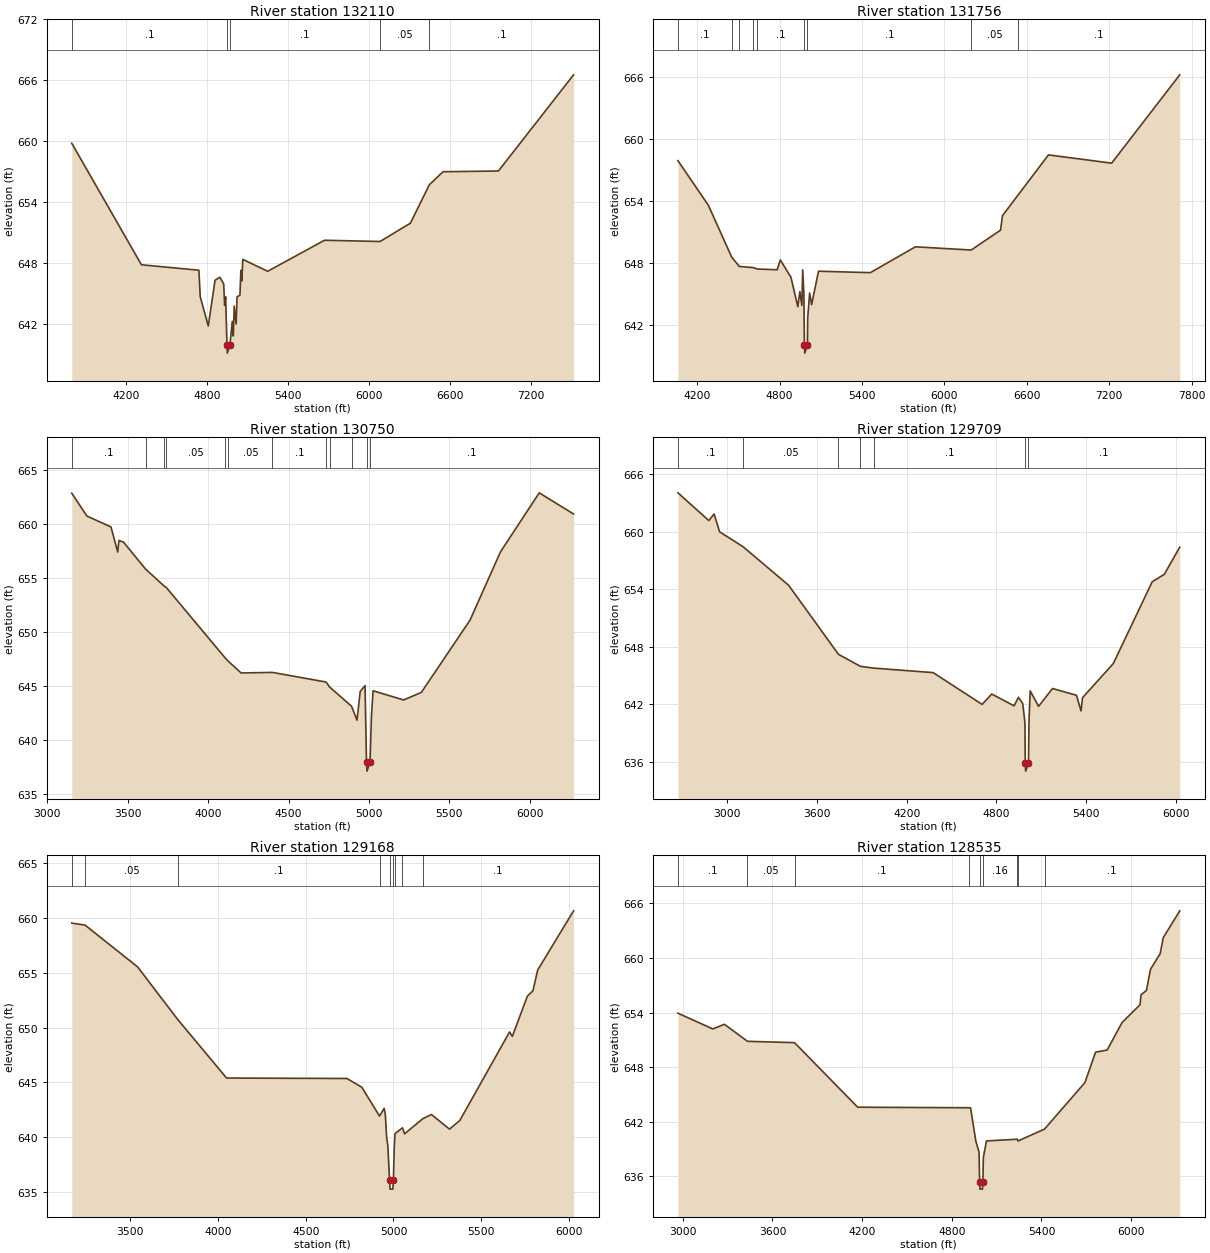
Type RM Length L Ch R = 1 ,132110  ,354,354,354
BEGIN DESCRIPTION:
Mapping XS 11a5a352
END DESCRIPTION:
XS GIS Cut Line= 6
      1974263.58     13583800.03      1973300.04     13584018.78
      1972919.83     13584430.24      1972643.79      13584341.7
        1972149.     13583695.86      1971108.69     13583711.47
#Sta/Elev= 30
    3799  659.81  4314.8  647.86  4740.3  647.32  4749.8  644.73  4809.6  641.84
  4859.8  646.34  4895.5  646.63  4923.8  645.98  4930.6  643.87    4938  644.71
  4948.1  639.97  4950.9  639.17  4969.8  639.97  4987.3  642.29  4994.7  640.85
  5001.5  643.78  5015.7  642.03  5022.5   644.7    5044  644.87  5050.8  647.31
  5058.2  646.29    5065  648.39  5249.3  647.22  5670.2  650.27  6081.5  650.15
  6305.7  651.95  6446.3  655.73  6547.3  657.01  6957.3  657.08  7513.7  666.54
#Mann= 5 ,-1 , 0
    3799      .1       0  4948.1     .07       0  4969.8      .1       0
  6081.5     .05       0  6446.3      .1       0
Bank Sta=4948.1,4969.8
XS Rating Curve= 0 ,0
Exp/Cntr=0.3,0.1

Type RM Length L Ch R = 1 ,131756  ,1006,1006,1006
BEGIN DESCRIPTION:
Mapping XS 8c0d44e4
END DESCRIPTION:
XS GIS Cut Line= 6
      1974180.23      13583654.2      1973471.91     13583737.53
      1972862.54     13584331.28      1972701.08     13584310.45
      1972180.25     13583602.11      1971139.31     13583633.34
#Sta/Elev= 30
  4059.2  657.88  4280.5  653.57  4450.8  648.54  4506.2  647.64  4605.6  647.53
  4638.2  647.39  4781.9  647.32    4805  648.27  4882.2  646.59  4932.4  643.75
    4947  645.21  4961.7  643.87  4967.9  647.31  4976.3  644.98  4980.2  640.05
  4982.9  639.25  5001.9  640.05  5004.2  642.63  5018.1  645.07  5032.7  643.95
  5082.9  647.18  5460.4  647.04  5788.4  649.54  6194.8  649.23  6408.2  651.15
  6422.9  652.56  6535.4  654.54  6757.4  658.44  7217.6  657.64  7713.5  666.19
#Mann= 9 ,-1 , 0
  4059.2      .1       0  4450.8     .05       0  4506.2      .1       0
  4605.6     .05       0  4638.2      .1       0  4980.2     .07       0
  5001.9      .1       0  6194.8     .05       0  6535.4      .1       0
Bank Sta=4980.2,5001.9
XS Rating Curve= 0 ,0
Exp/Cntr=0.3,0.1

Type RM Length L Ch R = 1 ,130750  ,1041,1041,1041
BEGIN DESCRIPTION:
Black Creek 136.0
END DESCRIPTION:
XS GIS Cut Line= 4
      1974410.53     13583892.41      1973691.81     13583038.28
      1972572.02     13583038.28      1971718.97     13583267.15
#Sta/Elev= 30
  3152.7  662.84    3247  660.72  3396.6  659.71  3438.2  657.39    3446  658.46
  3474.6   658.3  3612.2   655.8    3729  654.21  3739.6  654.12    4103  647.64
  4126.1  647.27  4205.5  646.19  4400.2  646.24  4733.7  645.35  4755.4  644.89
    4892  643.11  4925.8  641.82  4945.8  644.48  4975.8  645.01  4984.9   637.9
  4987.7   637.1  5006.6   637.9  5015.8  642.24  5025.8  644.54  5215.8  643.69
  5325.8  644.39    5628  651.07  5817.6   657.4  6058.7  662.87    6272  660.91
#Mann= 12 ,-1 , 0
  3152.7      .1       0  3612.2     .05       0    3729      .1       0
  3739.6     .05       0    4103      .1       0  4126.1     .05       0
  4400.2      .1       0  4733.7     .05       0  4755.4      .1       0
    4892     .12       0  4984.9     .07       0  5006.6      .1       0
Bank Sta=4984.9,5006.6
XS Rating Curve= 0 ,0
Exp/Cntr=0.3,0.1

Type RM Length L Ch R = 1 ,129709  ,541,541,541
BEGIN DESCRIPTION:
Black Creek 135.0
END DESCRIPTION:
XS GIS Cut Line= 4
      1974509.49       13583882.      1973618.89     13582793.49
      1972743.89     13582116.41      1972608.47     13581283.04
#Sta/Elev= 30
    2669  664.07  2875.9  661.17  2911.1  661.86  2947.7     660  3104.9  658.44
  3409.2  654.42    3743   647.2  3889.2  645.95  3978.6  645.76  4376.4  645.29
  4704.1  641.97  4768.4  643.05  4917.8  641.82  4946.8  642.71  4975.8  642.05
  4990.3  640.08  4992.5   635.8  4995.3     635  5014.2   635.8  5017.4  640.22
  5025.6  643.38  5081.7  641.77    5175  643.63  5335.5  642.92  5365.6  641.29
  5375.7  642.67  5581.8  646.24  5841.8  654.78  5922.8  655.56  6026.1  658.39
#Mann= 7 ,-1 , 0
    2669      .1       0  3104.9     .05       0    3743      .1       0
  3889.2     .05       0  3978.6      .1       0  4992.5     .07       0
  5014.2      .1       0
Bank Sta=4992.5,5014.2
XS Rating Curve= 0 ,0
Exp/Cntr=0.3,0.1

Type RM Length L Ch R = 1 ,129168  ,633,633,633
BEGIN DESCRIPTION:
Black Creek 134.0
END DESCRIPTION:
XS GIS Cut Line= 4
      1974457.45     13583387.27      1974030.35     13582684.12
      1973308.88     13581991.12      1972785.57     13581095.59
#Sta/Elev= 30
  3166.2  659.53  3241.9  659.35    3542  655.53  3769.7  650.75  4048.7   645.4
  4734.6  645.36  4819.5  644.56  4920.6  641.93  4946.9  642.64  4953.8  642.04
    4961     640  4967.9  639.21  4977.7  636.07  4980.4  635.27  4996.6  635.27
  4999.4  636.07  5004.5  639.12  5008.8  640.33  5051.3  640.86  5063.2  640.31
  5167.6   641.7  5216.4  642.07  5319.4  640.74  5378.1  641.53  5661.6   649.6
  5677.4   649.2  5763.3  652.87  5794.7  653.35    5822  655.25  6026.5  660.65
#Mann= 9 ,-1 , 0
  3166.2      .1       0  3241.9     .05       0  3769.7      .1       0
  4920.6     .07       0  4977.7     .07       0  4999.4     .07       0
  5008.8     .16       0  5051.3     .12       0  5167.6      .1       0
Bank Sta=4977.7,4999.4
XS Rating Curve= 0 ,0
Exp/Cntr=0.3,0.1

Type RM Length L Ch R = 1 ,128535  ,650,650,650
BEGIN DESCRIPTION:
Black Creek 133.0
END DESCRIPTION:
XS GIS Cut Line= 3
      1975014.71     13583241.38      1973827.23     13581699.74
      1972885.59     13580648.86
#Sta/Elev= 30
  2967.9  653.93  3200.9   652.2  3278.9  652.71  3432.9  650.84  3747.9  650.69
  4170.3  643.59  4912.3  643.53  4925.8  643.51  4960.9  639.85  4982.6  638.64
  4985.8  635.38  4988.7  634.58    5005  634.58  5007.8  635.38  5011.1  638.08
    5032  639.88  5238.8  640.07  5242.1  639.87  5420.1  641.18  5690.6   646.3
  5761.6  649.64  5839.4  649.88  5938.8   652.9  6059.2  654.86  6065.9  655.96
  6101.8  656.42  6129.4  658.76  6193.8  660.48  6214.7  662.24  6324.9  665.19
#Mann= 9 ,-1 , 0
  2967.9      .1       0  3432.9     .05       0  3747.9      .1       0
  4912.3     .16       0  4985.8     .07       0  5007.8     .16       0
  5238.8      .1       0  5242.1     .16       0  5420.1      .1       0
Bank Sta=4985.8,5007.8
XS Rating Curve= 0 ,0
Exp/Cntr=0.3,0.1

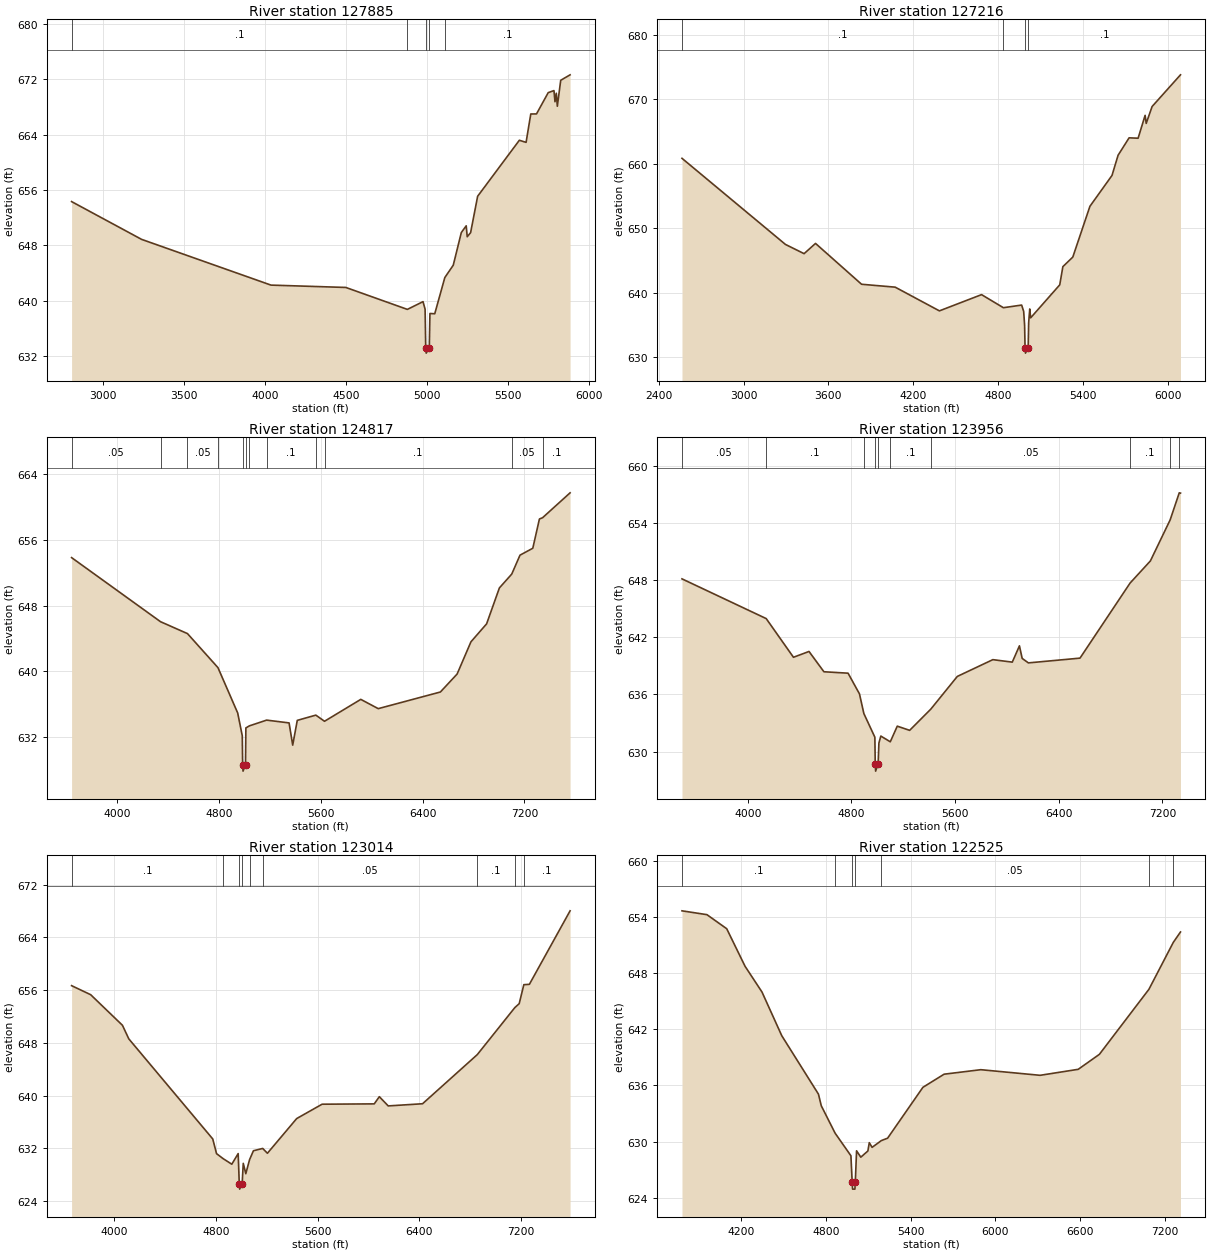
Type RM Length L Ch R = 1 ,127885  ,669,669,669
BEGIN DESCRIPTION:
Black Creek 132.0
END DESCRIPTION:
XS GIS Cut Line= 3
      1975405.37     13583033.11       1974061.6     13581038.28
      1973651.29     13580508.51
#Sta/Elev= 30
  2807.3  654.31  3239.1  648.85  4037.5  642.24  4499.2   641.9  4878.8  638.73
  4975.3  639.85  4988.1  638.76    4992  633.21  4994.9  632.41    5014  633.21
    5018  638.14  5047.7   638.1  5109.8  643.33  5161.9  645.12  5211.5  649.83
  5241.7  650.81    5248  649.23  5268.9  649.82  5312.3  655.08  5569.5  663.17
  5611.1  662.87  5640.1  666.97  5675.4  666.98  5747.8  670.06  5783.1  670.35
  5789.4  668.74  5797.6  669.97  5803.9  668.09  5824.8  671.84  5882.6  672.63
#Mann= 5 ,-1 , 0
  2807.3      .1       0  4878.8     .16       0    4992     .07       0
    5014     .16       0  5109.8      .1       0
Bank Sta=4992,5014
XS Rating Curve= 0 ,0
Exp/Cntr=0.3,0.1

Type RM Length L Ch R = 1 ,127216  ,2399,2399,2399
BEGIN DESCRIPTION:
Black Creek 131.0
END DESCRIPTION:
XS GIS Cut Line= 3
      1976019.08     13583051.33      1975472.19     13581844.71
      1974057.27     13580160.69
#Sta/Elev= 30
  2564.8  660.83  3296.4  647.46  3428.1  646.03  3508.9  647.62  3834.4  641.28
  4072.1  640.83  4384.7  637.15  4682.6  639.67  4837.1  637.64  4966.2  638.05
  4980.5  637.06    4987  634.97  4990.3  631.39  4993.2  630.59  5012.3  631.39
  5015.6  635.28  5023.4  637.45  5029.9  636.07  5235.5  641.19  5257.5  644.01
  5327.8   645.5  5448.8  653.38  5604.9  658.17  5647.8   661.3  5725.8  664.01
  5789.5  663.95    5839   667.5  5846.8  666.25  5888.4  668.87  6089.1  673.79
#Mann= 4 ,-1 , 0
  2564.8      .1       0  4837.1     .12       0  4990.3     .07       0
  5012.3      .1       0
Bank Sta=4990.3,5012.3
XS Rating Curve= 0 ,0
Exp/Cntr=0.3,0.1

Type RM Length L Ch R = 1 ,124817  ,861,861,861
BEGIN DESCRIPTION:
Mapping XS db24f053
END DESCRIPTION:
XS GIS Cut Line= 3
      1977387.12     13582586.03      1976163.16     13581218.84
      1974392.32     13580125.08
#Sta/Elev= 30
  3642.4  653.86  4341.4  646.04    4553  644.59  4792.4  640.44  4947.4  634.91
  4983.3  632.13  4986.3  628.62  4989.4  627.82  5008.7  628.62  5011.7  633.09
  5039.3  633.34  5174.5  634.04  5351.1   633.7  5379.6  630.99  5415.5  634.01
  5561.2  634.65  5629.5   633.9  5914.5  636.57  6051.6  635.44  6539.9  637.47
  6671.2  639.66  6779.9  643.59  6902.9  645.78  7003.3  650.16  7100.4  651.85
  7165.4  654.16  7265.8     655  7317.9  658.57  7342.4  658.72  7558.8  661.76
#Mann= 12 ,-1 , 0
  3642.4     .05       0  4341.4      .1       0    4553     .05       0
  4792.4      .1       0  4986.3     .07       0  5008.7      .1       0
  5039.3     .16       0  5174.5      .1       0  5561.2     .16       0
  5629.5      .1       0  7100.4     .05       0  7342.4      .1       0
Bank Sta=4986.3,5008.7
XS Rating Curve= 0 ,0
Exp/Cntr=0.3,0.1

Type RM Length L Ch R = 1 ,123956  ,942,942,942
BEGIN DESCRIPTION:
Mapping XS 00fb82d4
END DESCRIPTION:
XS GIS Cut Line= 3
      1977986.06     13581713.61      1977022.54     13580932.38
      1974561.61     13580073.01
#Sta/Elev= 30
  3492.8  648.12  4142.8  643.95  4353.1  639.89  4473.1   640.5  4588.1  638.37
  4774.5  638.22  4862.4  636.05  4896.5  633.98  4981.3   631.5  4984.2  628.74
  4987.2  627.94  5006.7  628.74  5012.4  630.88  5027.2  631.62  5100.3  631.02
  5154.3  632.66  5249.7  632.22  5412.6  634.44  5617.6  637.88  5891.8  639.64
  6041.8  639.38    6097  641.09  6118.2  639.77    6166   639.3  6564.4   639.8
    6951  647.68  7107.5     650  7260.2  654.31  7330.4  657.15  7339.9  657.12
#Mann= 10 ,-1 , 0
  3492.8     .05       0  4142.8      .1       0  4896.5     .16       0
  4984.2     .07       0  5006.7     .16       0  5100.3      .1       0
  5412.6     .05       0    6951      .1       0  7260.2     .05       0
  7330.4      .1       0
Bank Sta=4984.2,5006.7
XS Rating Curve= 0 ,0
Exp/Cntr=0.3,0.1

Type RM Length L Ch R = 1 ,123014  ,489,489,489
BEGIN DESCRIPTION:
Black Creek 130.0
END DESCRIPTION:
XS GIS Cut Line= 3
      1978124.97       13579975.      1976644.07     13579995.75
      1974204.85     13580021.79
#Sta/Elev= 30
  3665.7  656.66  3815.7  655.29  4065.7  650.65  4115.7  648.59  4775.8  633.41
  4805.8  631.18  4858.5  630.41  4925.8  629.58  4975.8  631.19  4984.5   626.6
  4987.6   625.8    5007   626.6  5015.8  629.71  5035.8  628.14  5065.4  630.27
  5095.8  631.62  5168.6  631.97  5205.8  631.24  5435.8   636.5  5635.8  638.68
  6045.9  638.73  6085.9  639.82  6155.9  638.42  6425.9  638.75  6856.2   646.2
  7151.5  653.33  7185.9  653.93  7222.4  656.81  7265.9  656.86  7586.1  668.01
#Mann= 9 ,-1 , 0
  3665.7      .1       0  4858.5     .12       0  4984.5     .07       0
    5007     .12       0  5065.4      .1       0  5168.6     .05       0
  6856.2      .1       0  7151.5     .05       0  7222.4      .1       0
Bank Sta=4984.5,5007
XS Rating Curve= 0 ,0
Exp/Cntr=0.3,0.1

Type RM Length L Ch R = 1 ,122525  ,800,800,800
BEGIN DESCRIPTION:
Black Creek 129.0
END DESCRIPTION:
XS GIS Cut Line= 3
       1978131.9     13579575.17        1977059.     13579549.13
      1974600.63     13579632.47
#Sta/Elev= 30
  3778.5  654.63  3955.4  654.22  4095.5  652.72  4225.5  648.71  4345.6  645.96
  4485.6   641.3  4745.7  635.06  4765.7  633.82  4863.5   630.9  4975.8  628.48
  4984.5  625.72  4987.6  624.92    5004  624.92    5007  625.72  5015.8  629.01
  5045.8  628.33  5095.9  628.99  5105.9  629.88  5125.9  629.38  5191.3   630.1
  5235.9  630.36  5486.1  635.79  5636.2  637.19  5896.3  637.67  6316.6  637.07
  6586.7  637.71  6736.8  639.31  7087.7  646.25  7260.5  651.26  7311.5  652.37
#Mann= 7 ,-1 , 0
  3778.5      .1       0  4863.5     .12       0  4984.5     .07       0
    5007     .12       0  5191.3     .05       0  7087.7      .1       0
  7260.5     .05       0
Bank Sta=4984.5,5007
XS Rating Curve= 0 ,0
Exp/Cntr=0.3,0.1

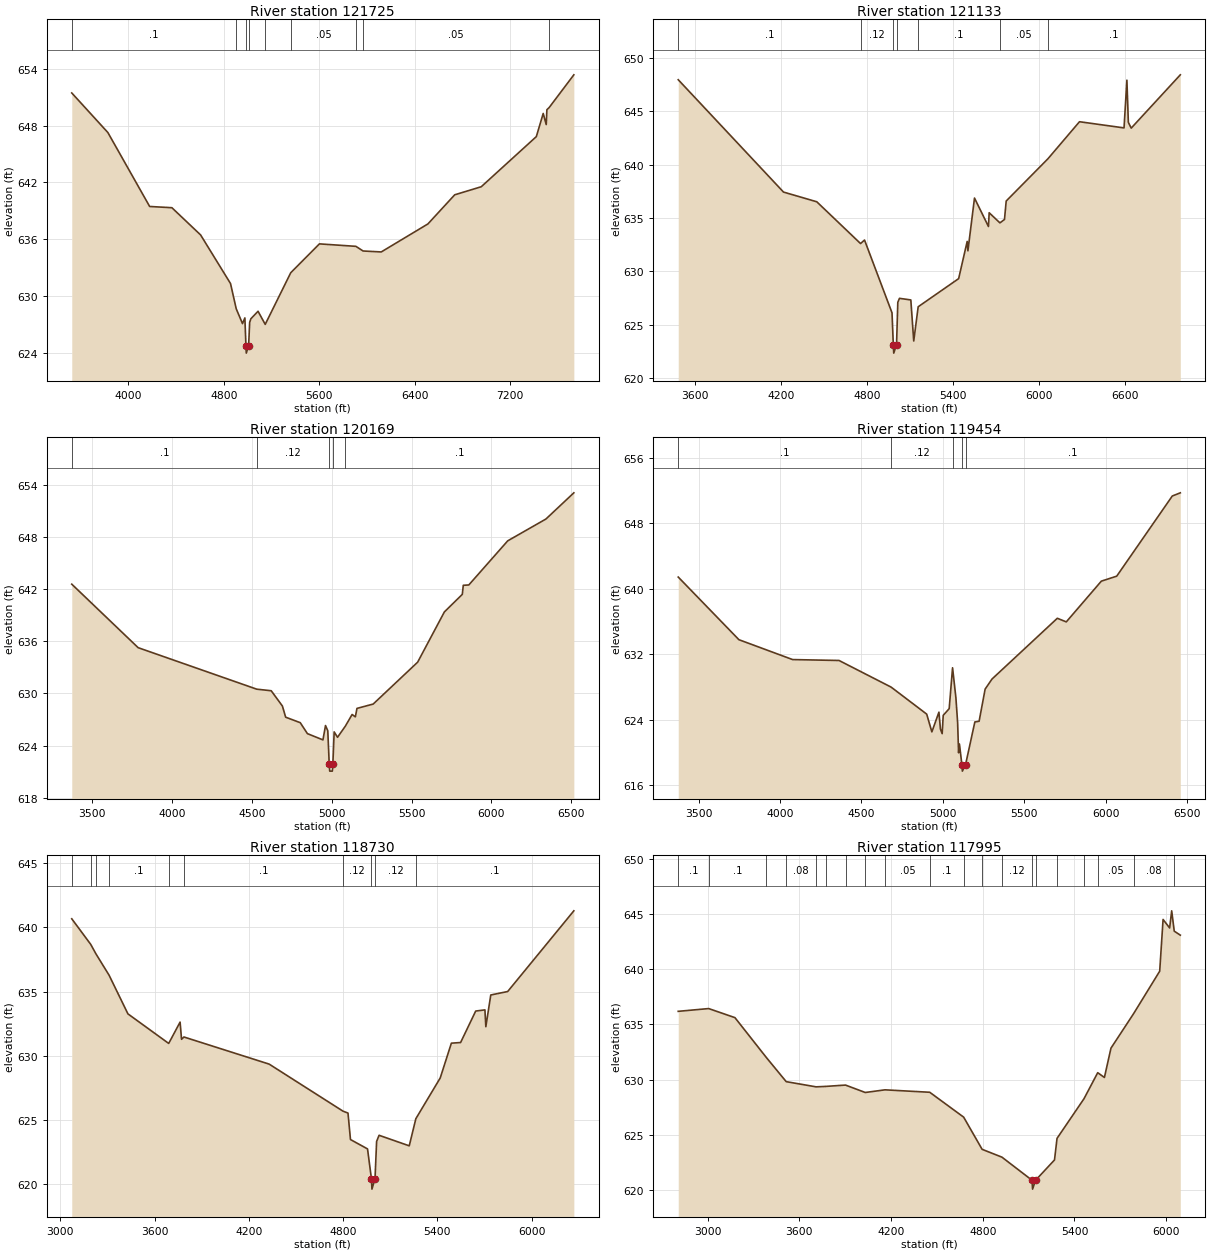
Type RM Length L Ch R = 1 ,121725  ,592,592,592
BEGIN DESCRIPTION:
Mapping XS 73c20d7d
END DESCRIPTION:
XS GIS Cut Line= 4
      1978215.27     13579366.86       1977439.2     13578809.55
      1975345.45     13578960.59      1974225.62     13578684.54
#Sta/Elev= 30
  3524.8  651.43  3827.4  647.26  4177.6  639.47    4364  639.34  4604.8  636.47
  4855.4  631.35  4903.2  628.69  4955.7  627.13  4975.7  627.73  4984.5  624.82
  4987.6  624.02  5007.1  624.82  5015.8  627.26  5025.9  627.64    5086  628.43
  5146.2  627.05  5360.1  632.49  5600.4  635.53  5906.3  635.27  5966.2  634.78
  6118.7  634.68  6509.7  637.63  6734.4   640.7  6956.9  641.55  7418.4  646.83
    7476  649.27  7501.4   648.1  7506.8  649.66  7525.7  649.89  7732.8  653.34
#Mann= 9 ,-1 , 0
  3524.8      .1       0  4903.2     .12       0  4984.5     .07       0
  5007.1     .12       0  5146.2      .1       0  5360.1     .05       0
  5906.3      .1       0  5966.2     .05       0  7525.7      .1       0
Bank Sta=4984.5,5007.1
XS Rating Curve= 0 ,0
Exp/Cntr=0.3,0.1

Type RM Length L Ch R = 1 ,121133  ,964,964,964
BEGIN DESCRIPTION:
Mapping XS 3d7d0d75
END DESCRIPTION:
XS GIS Cut Line= 3
      1978272.55     13578554.34      1976147.54     13578241.84
      1974793.39     13578122.05
#Sta/Elev= 30
  3482.1  647.97  4217.5  637.43  4449.9  636.52  4755.6   632.6  4783.5  632.93
  4975.5   626.1  4984.5  623.12  4987.6  622.32  5007.1  623.12    5016  627.09
  5027.6  627.46  5106.9  627.31  5127.2  623.46  5158.3  626.67    5441  629.31
  5500.6   632.8  5505.7  631.92  5551.7  636.87  5649.2   634.2  5654.2  635.49
  5729.4  634.54  5761.2  634.86  5773.1  636.59  6064.4  640.55  6285.1  644.03
  6596.3  643.45  6616.3  647.93  6626.4  643.97  6646.5  643.43  6989.4  648.43
#Mann= 7 ,-1 , 0
  3482.1      .1       0  4755.6     .12       0  4984.5     .07       0
  5007.1     .12       0  5158.3      .1       0  5729.4     .05       0
  6064.4      .1       0
Bank Sta=4984.5,5007.1
XS Rating Curve= 0 ,0
Exp/Cntr=0.3,0.1

Type RM Length L Ch R = 1 ,120169  ,715,715,715
BEGIN DESCRIPTION:
Mapping XS 753fa435
END DESCRIPTION:
XS GIS Cut Line= 2
      1978074.62     13577856.42      1974976.98     13577309.78
#Sta/Elev= 30
  3371.4  642.56  3787.3  635.26  4530.2  630.49  4620.9  630.31  4691.1  628.55
  4711.4  627.27  4802.8  626.64  4847.7  625.38    4945  624.66  4961.1  626.31
  4975.4  625.71  4984.4  621.87  4987.5  621.07  5003.9  621.07  5007.1  621.87
  5015.3  625.58  5036.4  624.96  5085.7  626.25  5127.7  627.58  5148.1  627.31
  5158.2  628.28  5259.8  628.78  5538.2  633.59  5705.8  639.37  5818.2  641.39
  5824.2  642.43  5858.9  642.47  6102.6  647.54  6342.1  650.05  6516.9  653.06
#Mann= 5 ,-1 , 0
  3371.4      .1       0  4530.2     .12       0  4984.4     .07       0
  5007.1     .12       0  5085.7      .1       0
Bank Sta=4984.4,5007.1
XS Rating Curve= 0 ,0
Exp/Cntr=0.3,0.1

Type RM Length L Ch R = 1 ,119454  ,724,724,724
BEGIN DESCRIPTION:
Mapping XS d9a81639
END DESCRIPTION:
XS GIS Cut Line= 2
      1978100.66     13577439.76      1975179.39     13576455.58
#Sta/Elev= 30
  3375.1  641.42  3747.7  633.76  4077.5  631.33  4362.4  631.22  4682.4  627.96
  4900.6  624.66  4932.3  622.49  4975.7   624.9    4985  622.83  4995.6  622.27
    5002  624.51  5038.7  625.33  5059.4  630.33    5080  626.64  5090.5  623.63
  5096.4  619.93  5101.7     621  5116.6  618.49  5119.7  617.69  5139.3  618.49
  5196.2   623.7  5222.4  623.79  5259.4  627.72  5301.6  628.95  5702.6  636.38
  5757.7  635.94  5972.8  640.92  6067.3  641.53  6408.4  651.33  6457.7  651.72
#Mann= 5 ,-1 , 0
  3375.1      .1       0  4682.4     .12       0  5059.4      .1       0
  5116.6     .07       0  5139.3      .1       0
Bank Sta=5116.6,5139.3
XS Rating Curve= 0 ,0
Exp/Cntr=0.3,0.1

Type RM Length L Ch R = 1 ,118730  ,735,735,735
BEGIN DESCRIPTION:
Black Creek 122.0
END DESCRIPTION:
XS GIS Cut Line= 3
      1978178.76     13577241.82      1976819.41     13576398.09
       1975439.6     13575596.24
#Sta/Elev= 30
  3073.1  640.66  3193.7  638.67    3227  637.93  3310.6  636.27  3430.6  633.26
  3690.1  630.96  3762.6  632.62  3771.9  631.28  3787.1  631.46  4329.5  629.35
  4799.3  625.69  4831.3  625.54  4847.1  623.48  4955.7  622.75  4980.6  620.42
  4983.7  619.62  5003.3  620.42  5013.5  623.33  5029.2  623.81  5221.2  622.99
  5263.2   625.1  5418.3  628.27  5489.4  630.98  5548.1  631.03  5644.2  633.48
  5702.9  633.57  5708.7  632.26  5740.2  634.73  5847.8     635  6268.9  641.28
#Mann= 10 ,-1 , 0
  3073.1     .05       0  3193.7      .1       0    3227     .05       0
  3310.6      .1       0  3690.1     .05       0  3787.1      .1       0
  4799.3     .12       0  4980.6     .07       0  5003.3     .12       0
  5263.2      .1       0
Bank Sta=4980.6,5003.3
XS Rating Curve= 0 ,0
Exp/Cntr=0.3,0.1

Type RM Length L Ch R = 1 ,117995  ,649,649,649
BEGIN DESCRIPTION:
Black Creek 124.0
END DESCRIPTION:
XS GIS Cut Line= 3
      1978319.43     13577064.77       1977001.7     13575866.84
      1975851.81     13574899.06
#Sta/Elev= 30
  2808.5  636.19  3007.5  636.44  3179.4  635.62  3385.6     632  3514.8  629.83
  3710.1  629.36  3773.3   629.4  3902.6  629.52  4031.8  628.85    4161  629.09
  4453.5  628.87  4675.3  626.62    4796  623.71  4925.8     623  5122.9  620.91
  5126.1  620.11  5145.6  620.91  5269.5  622.75    5286   624.7  5462.1  628.28
  5552.1  630.64  5595.9  630.21  5638.8  632.86  5786.8  635.98  5957.5  639.82
  5979.6   644.5  6022.5  643.73  6035.9  645.28  6052.7  643.44  6092.3  643.08
#Mann= 20 ,-1 , 0
  2808.5      .1       0  3007.5      .1       0  3385.6     .05       0
  3514.8     .08       0  3710.1      .1       0  3773.3     .08       0
  3902.6     .08       0  4031.8     .08       0    4161     .05       0
  4453.5      .1       0  4675.3      .1       0    4796     .08       0
  4925.8     .12       0  5122.9     .07       0  5145.6     .08       0
    5286     .08       0  5462.1      .1       0  5552.1     .05       0
  5786.8     .08       0  6052.7      .1       0
Bank Sta=5122.9,5145.6
XS Rating Curve= 0 ,0
Exp/Cntr=0.3,0.1

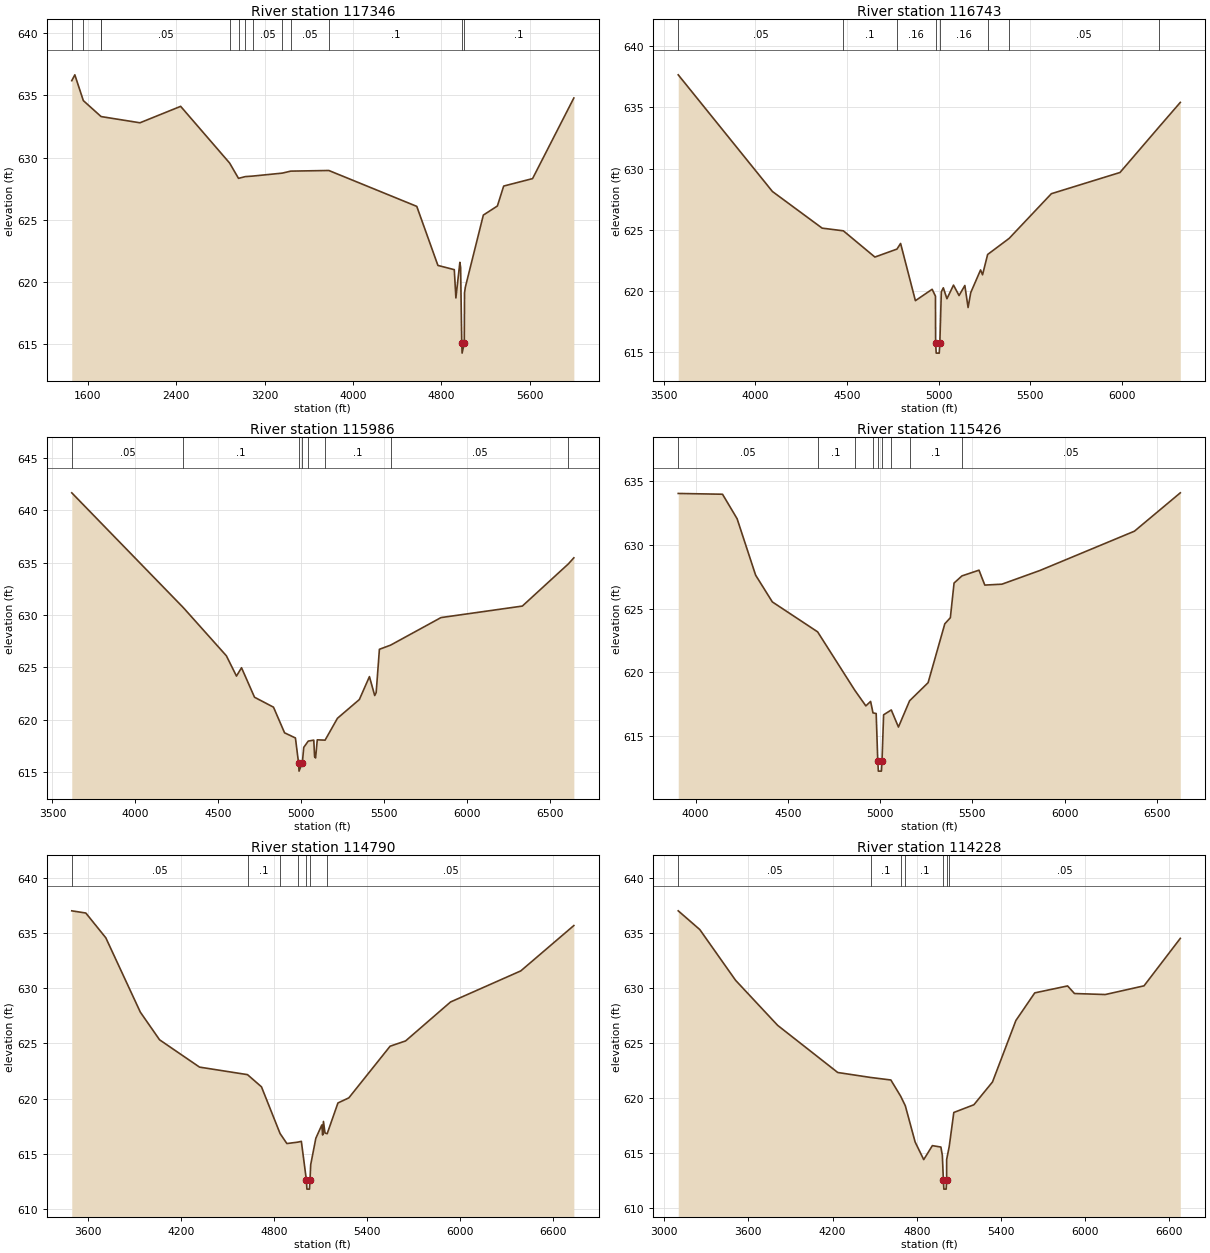
Type RM Length L Ch R = 1 ,117346  ,603,603,603
BEGIN DESCRIPTION:
Black Creek 123.0
END DESCRIPTION:
XS GIS Cut Line= 3
      1979751.74     13577377.29      1977069.41      13575153.3
      1976272.56     13574450.19
#Sta/Elev= 30
  1453.7  636.17  1481.4  636.64  1558.5  634.57  1717.8   633.3  1718.9  633.29
  2071.3  632.79  2439.9  634.11  2883.1  629.56  2963.8  628.33  3025.4  628.47
  3090.5  628.51  3360.7  628.75  3437.3  628.91    3782  628.96  4578.3  626.08
  4769.7  621.34  4918.1     621  4932.5  618.73  4968.6  621.59  4975.3  621.17
  4985.7   615.1  4988.9   614.3  5008.5   615.1  5010.7  619.13    5018  619.59
  5181.1  625.38  5308.3  626.11  5365.2  627.71    5627  628.31  6000.8  634.78
#Mann= 13 ,-1 , 0
  1453.7      .1       0  1558.5     .05       0  1717.8      .1       0
  1718.9     .05       0  2883.1      .1       0  2963.8     .05       0
  3025.4      .1       0  3090.5     .05       0  3360.7      .1       0
  3437.3     .05       0    3782      .1       0  4985.7     .07       0
  5008.5      .1       0
Bank Sta=4985.7,5008.5
XS Rating Curve= 0 ,0
Exp/Cntr=0.3,0.1

Type RM Length L Ch R = 1 ,116743  ,757,757,757
BEGIN DESCRIPTION:
Mapping XS b8e5b598
END DESCRIPTION:
XS GIS Cut Line= 3
      1978801.22     13575347.76      1977377.57     13574823.44
      1976239.34     13574382.72
#Sta/Elev= 30
  3579.7  637.65  4093.3  628.13  4364.3  625.14  4480.1  624.92    4652  622.78
  4772.4  623.43  4792.2  623.89  4872.9  619.22  4964.2  620.15  4982.3  619.59
  4983.2  615.74  4986.4  614.94  5002.9  614.94  5006.1  615.74  5014.3  619.94
  5025.1  620.27  5044.9  619.38  5080.7  620.49    5111  619.64  5142.5  620.46
  5160.2  618.66  5174.7  619.88  5228.3  621.73    5239  621.33  5266.8  622.99
  5383.9   624.3  5614.3  627.95  5988.4  629.68  6202.3  633.41  6317.4   635.4
#Mann= 8 ,-1 , 0
  3579.7     .05       0  4480.1      .1       0  4772.4     .16       0
  4983.2     .07       0  5006.1     .16       0  5266.8      .1       0
  5383.9     .05       0  6202.3      .1       0
Bank Sta=4983.2,5006.1
XS Rating Curve= 0 ,0
Exp/Cntr=0.3,0.1

Type RM Length L Ch R = 1 ,115986  ,560,560,560
BEGIN DESCRIPTION:
Black Creek 121.0
END DESCRIPTION:
XS GIS Cut Line= 4
      1979183.97     13574684.54      1978631.91     13574507.47
       1977371.5     13574293.92      1976204.81     13574330.38
#Sta/Elev= 30
  3616.5  641.66  4289.4  630.68  4548.1  626.09    4609  624.15  4639.4  624.95
  4717.7  622.13  4832.1  621.18  4898.8  618.73  4964.2  618.24  4982.9  615.87
  4986.1  615.07  5005.8  615.87  5014.4  617.34  5041.5  617.94  5074.8  618.03
  5079.8  616.44  5085.7  616.33  5095.8  618.06  5142.9  618.03  5217.5  620.12
  5349.4  621.91  5410.2   624.1    5442  622.29  5450.8  622.58  5470.3  626.71
  5537.9  627.11  5841.3  629.74  6331.6  630.84  6609.5  634.88  6641.9  635.45
#Mann= 8 ,-1 , 0
  3616.5     .05       0  4289.4      .1       0  4982.9     .07       0
  5005.8      .1       0  5041.5     .16       0  5142.9      .1       0
  5537.9     .05       0  6609.5      .1       0
Bank Sta=4982.9,5005.8
XS Rating Curve= 0 ,0
Exp/Cntr=0.3,0.1

Type RM Length L Ch R = 1 ,115426  ,636,636,636
BEGIN DESCRIPTION:
Black Creek 120.0
END DESCRIPTION:
XS GIS Cut Line= 4
      1978907.96     13573918.93      1978642.33     13573799.13
      1977423.58     13573918.92      1976272.55     13574273.09
#Sta/Elev= 30
  3906.3  634.04  4146.2  633.98  4225.2  632.06  4325.6  627.63  4416.1  625.53
  4661.5  623.18  4862.3  618.61  4922.8  617.37  4948.6  617.72  4961.5  616.82
  4978.8  616.77  4987.4  613.05  4990.6  612.25  5007.1  612.25  5010.4  613.05
    5019  616.67  5060.6  617.05  5099.4  615.71  5159.8  617.77  5260.1  619.19
  5350.6  623.81  5380.7  624.29  5400.8  627.01  5443.4  627.57  5535.9  628.02
  5567.3  626.85  5660.1  626.92  5866.8     628  6378.1  631.08  6626.6  634.09
#Mann= 9 ,-1 , 0
  3906.3     .05       0  4661.5      .1       0  4862.3     .07       0
  4961.5     .16       0  4987.4     .07       0  5010.4     .16       0
  5060.6     .12       0  5159.8      .1       0  5443.4     .05       0
Bank Sta=4987.4,5010.4
XS Rating Curve= 0 ,0
Exp/Cntr=0.3,0.1

Type RM Length L Ch R = 1 ,114790  ,562,562,562
BEGIN DESCRIPTION:
Black Creek 119.0
END DESCRIPTION:
XS GIS Cut Line= 4
      1979092.87     13573434.55      1978363.68     13573247.05
      1977113.68     13573517.88      1976117.12     13574191.52
#Sta/Elev= 30
  3497.2  636.99  3587.9  636.79  3716.6  634.55    3939  627.83  4062.9  625.33
  4320.4  622.86  4629.4  622.18  4719.4  621.08  4839.2  616.86  4883.1  615.95
  4954.5  616.08  4976.4  616.15    5009  612.63  5012.2  611.83  5028.7  611.83
    5032  612.63  5036.6  614.04  5069.7  616.43  5108.3  617.63  5113.7  616.72
  5118.8  617.95  5128.7   616.9  5142.7  616.84  5212.1  619.62  5282.2  620.08
  5548.2  624.75  5648.2  625.23  5937.7  628.75  6390.3  631.56    6732  635.66
#Mann= 7 ,-1 , 0
  3497.2     .05       0  4629.4      .1       0  4839.2     .12       0
  4954.5      .1       0    5009     .07       0    5032      .1       0
  5142.7     .05       0
Bank Sta=5009,5032
XS Rating Curve= 0 ,0
Exp/Cntr=0.3,0.1

Type RM Length L Ch R = 1 ,114228  ,551,551,551
BEGIN DESCRIPTION:
Black Creek 118.0
END DESCRIPTION:
XS GIS Cut Line= 4
      1979273.38     13573031.76      1978526.24     13572671.66
      1977023.41     13572983.16      1976120.65     13573795.64
#Sta/Elev= 30
  3100.3     637  3253.9   635.3  3509.2  630.69    3809   626.6  4237.3  622.32
  4471.3  621.87  4615.8  621.64  4685.7  620.17  4718.9   619.3  4788.8  616.01
  4850.1  614.41  4911.7  615.68  4972.6  615.55  4982.9  614.79  4990.3  612.53
  4993.6  611.73  5010.1  611.73  5013.3  612.53  5013.5  614.42  5031.8   615.6
  5064.6  618.69  5207.6  619.39  5340.3  621.46    5507  627.04  5641.5  629.55
  5875.5  630.18  5924.8  629.49  6144.6   629.4  6420.4  630.19    6679   634.5
#Mann= 7 ,-1 , 0
  3100.3     .05       0  4471.3      .1       0  4685.7     .16       0
  4718.9      .1       0  4990.3     .07       0  5013.3      .1       0
  5031.8     .05       0
Bank Sta=4990.3,5013.3
XS Rating Curve= 0 ,0
Exp/Cntr=0.3,0.1

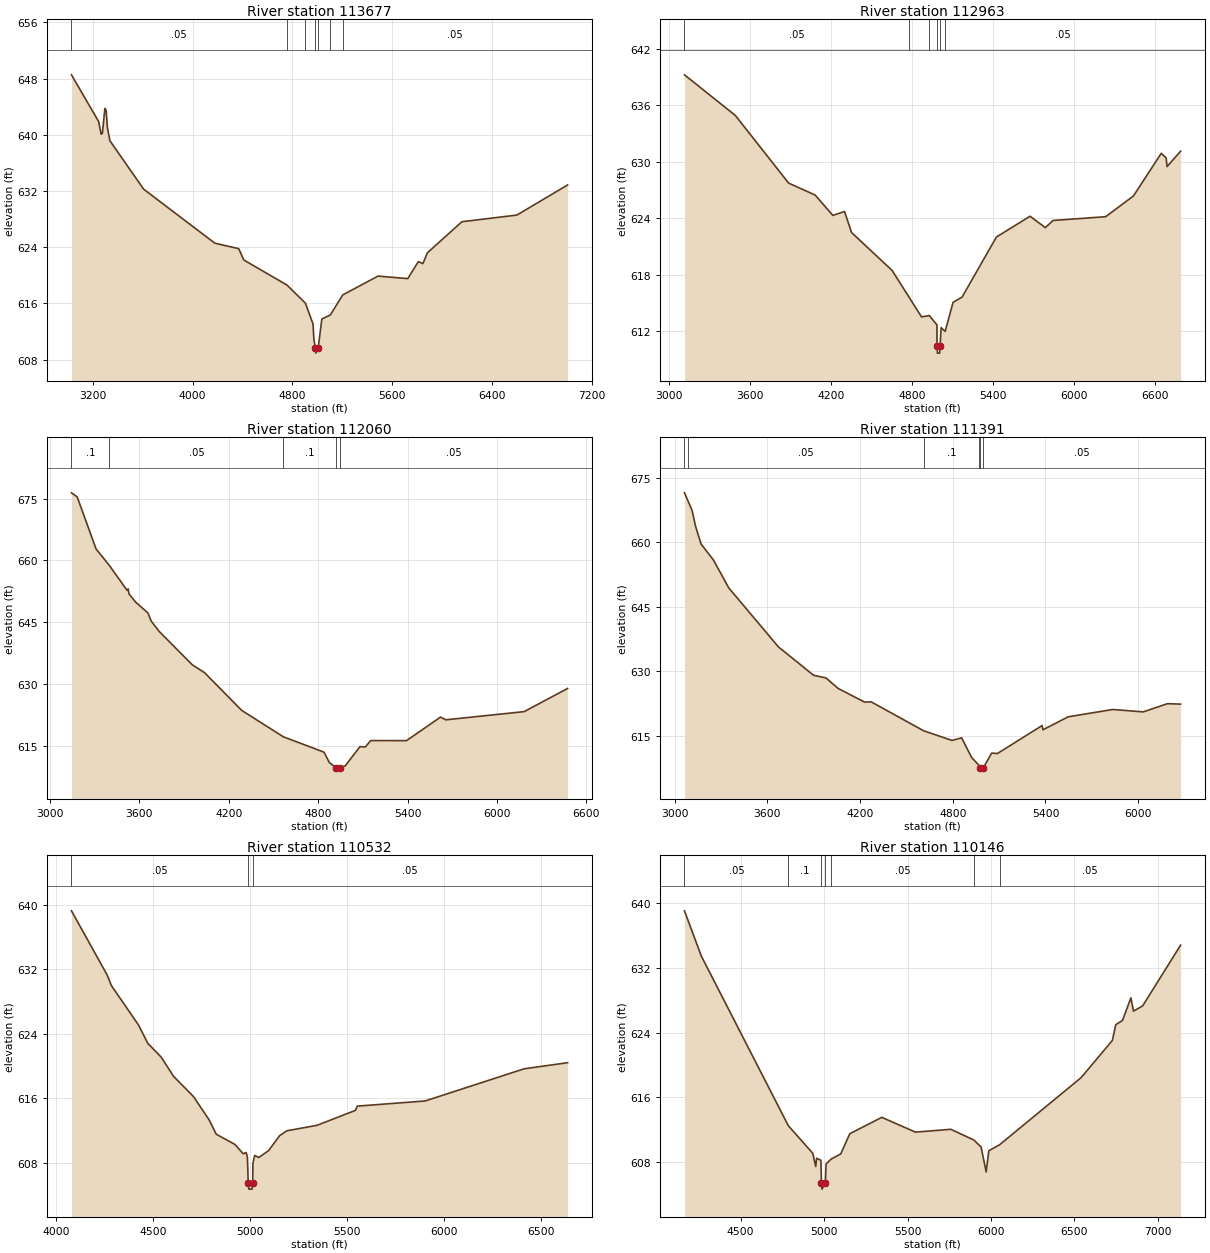
Type RM Length L Ch R = 1 ,113677  ,714,714,714
BEGIN DESCRIPTION:
Black Creek 117.0
END DESCRIPTION:
XS GIS Cut Line= 4
      1979502.55      13572302.6      1978363.68      13572240.1
      1977002.57      13572427.6      1976092.85     13573573.44
#Sta/Elev= 30
  3028.3  648.53  3246.2  641.88  3266.2  640.08  3276.2  640.22  3296.3  643.75
  3306.3  643.49  3316.3  641.05  3336.3  639.16  3606.7  632.27  4177.6  624.58
  4369.4   623.8  4409.8  622.19  4756.5  618.62  4904.1  616.04    4965  613.08
  4972.1  610.84  4983.7  609.74    4987  608.94  5006.8  609.74  5035.7   613.8
  5103.5  614.36  5203.3  617.22    5486   619.9  5724.3  619.54  5809.2  621.96
    5846  621.67  5881.3   623.2  6158.5  627.63  6599.3  628.58  7005.9  632.86
#Mann= 7 ,-1 , 0
  3028.3     .05       0  4756.5      .1       0  4904.1     .12       0
  4983.7     .07       0  5006.8     .12       0  5103.5      .1       0
  5203.3     .05       0
Bank Sta=4983.7,5006.8
XS Rating Curve= 0 ,0
Exp/Cntr=0.3,0.1

Type RM Length L Ch R = 1 ,112963  ,903,903,903
BEGIN DESCRIPTION:
Black Creek 116.0
END DESCRIPTION:
XS GIS Cut Line= 3
      1979238.73     13571233.15      1977134.52      13571821.7
      1975973.03     13572764.44
#Sta/Elev= 30
  3112.3  639.23    3490  634.91    3885  627.73  4081.9  626.46    4213   624.3
  4299.9  624.71  4351.8  622.48    4653  618.45  4781.2  615.55    4871  613.52
  4928.8  613.66  4985.3  612.67  4985.8  610.47  4989.1  609.67  5005.6  609.67
  5008.9  610.47  5016.4  612.38  5046.3  611.98    5105  615.06  5172.2  615.63
  5426.7     622    5676  624.21  5789.5     623    5847  623.76    6237  624.16
  6443.2  626.36  6649.4  630.89  6686.1  630.41  6692.5  629.48  6793.2  631.12
#Mann= 6 ,-1 , 0
  3112.3     .05       0  4781.2      .1       0  4928.8     .12       0
  4985.8     .07       0  5008.9     .12       0  5046.3     .05       0
Bank Sta=4985.8,5008.9
XS Rating Curve= 0 ,0
Exp/Cntr=0.3,0.1

Type RM Length L Ch R = 1 ,112060  ,669,669,669
BEGIN DESCRIPTION:
Black Creek 115.0
END DESCRIPTION:
XS GIS Cut Line= 3
      1978426.21     13570113.36      1977160.56     13570774.83
      1975947.02     13572238.37
#Sta/Elev= 30
  3144.7  676.44  3183.1  675.45  3309.9  662.79  3399.6  658.76  3518.4  652.72
  3525.1  653.09  3530.7  651.89  3574.9   649.9  3657.5  647.26  3679.6  645.28
  3732.8  642.77  3955.3  634.65  4037.4  632.74  4286.5  623.58  4566.6  617.14
  4839.6  613.41  4874.8  610.91  4920.6   609.6  4923.9   608.8  4940.4   608.8
  4943.7   609.6  4981.6  610.08  5080.6  614.75  5117.1  614.68  5152.2  616.23
  5393.1  616.21    5621  621.93  5656.2  621.27  6182.3  623.26    6474  628.89
#Mann= 5 ,-1 , 0
  3144.7      .1       0  3399.6     .05       0  4566.6      .1       0
  4920.6    .035       0  4943.7     .05       0
Bank Sta=4920.6,4943.7
XS Rating Curve= 0 ,0
Exp/Cntr=0.3,0.1

Type RM Length L Ch R = 1 ,111391  ,859,859,859
BEGIN DESCRIPTION:
Black Creek 114.0
END DESCRIPTION:
XS GIS Cut Line= 3
      1977975.02     13569474.98        1976425.       13570625.
      1975811.62     13571748.74
#Sta/Elev= 30
  3064.1  671.53    3087  669.65  3113.9  667.37  3136.1  663.72  3171.6  659.62
  3250.9  655.95  3350.5  649.43  3672.4   635.7  3899.7  629.11  3979.1   628.5
  4058.4  626.05  4229.5  622.88  4271.9  622.94  4612.3   616.2  4794.9  613.97
  4857.5  614.57  4922.1     610  4972.7  608.06  4975.2  607.63  4978.6  606.83
  4998.4  607.63  5051.6  611.02  5089.5  610.93    5378  617.42  5383.7  616.44
    5547  619.46  5835.5  621.16    6032   620.6  6189.5  622.51  6274.4  622.41
#Mann= 6 ,-1 , 0
  3064.1      .1       0    3087     .05       0  4612.3      .1       0
  4972.7     .05       0  4975.2    .035       0  4998.4     .05       0
Bank Sta=4975.2,4998.4
XS Rating Curve= 0 ,0
Exp/Cntr=0.3,0.1

Type RM Length L Ch R = 1 ,110532  ,386,386,386
BEGIN DESCRIPTION:
Black Creek 113.0
END DESCRIPTION:
XS GIS Cut Line= 3
      1976925.02     13569374.99      1975737.82     13570062.15
      1975758.65     13571249.64
#Sta/Elev= 30
  4077.5  639.22  4261.9  631.26  4283.4  629.96  4422.6  625.11  4471.5   622.8
  4539.7  621.12  4604.9   618.7  4706.8  616.22  4787.1  613.35  4824.4  611.55
  4920.6  610.29  4963.6  609.13  4978.8  609.28  4985.2  608.69  4989.3  605.55
  4992.7  604.75  5009.2  604.75  5012.5  605.55  5013.4  607.92  5022.5  608.92
    5044  608.67  5094.3  609.52  5152.1  611.39    5189  611.98  5343.9  612.65
  5542.1   614.5  5552.1  615.03  5902.1  615.67  6412.2  619.65  6636.9  620.41
#Mann= 3 ,-1 , 0
  4077.5     .05       0  4989.3    .035       0  5012.5     .05       0
Bank Sta=4989.3,5012.5
XS Rating Curve= 0 ,0
Exp/Cntr=0.3,0.1

Type RM Length L Ch R = 1 ,110146  ,471,471,471
BEGIN DESCRIPTION:
Black Creek 112.0
END DESCRIPTION:
XS GIS Cut Line= 4
       1976740.3     13569219.42      1975818.41     13569542.34
      1975141.32     13569630.88       1973839.6     13569464.26
#Sta/Elev= 30
  4163.7  639.08  4264.7  633.47  4785.7  612.47  4932.2  609.05    4950  607.41
  4955.3  608.43    4981  608.18  4984.2  605.41  4987.5  604.61  5007.4  605.41
  5012.1  607.73  5042.2  608.33  5099.8  608.97    5154  611.47  5345.6   613.5
  5547.4  611.67  5759.1  612.02  5897.6  610.69  5940.6  609.82  5970.9  606.74
  5986.9  609.36  6051.5  610.11  6539.8  618.42    6727  623.03  6747.2  624.98
  6787.5   625.5  6837.9   628.3  6853.6  626.66  6908.5  627.31  7135.7  634.83
#Mann= 7 ,-1 , 0
  4163.7     .05       0  4785.7      .1       0  4984.2     .07       0
  5007.4      .1       0  5042.2     .05       0  5897.6      .1       0
  6051.5     .05       0
Bank Sta=4984.2,5007.4
XS Rating Curve= 0 ,0
Exp/Cntr=0.3,0.1