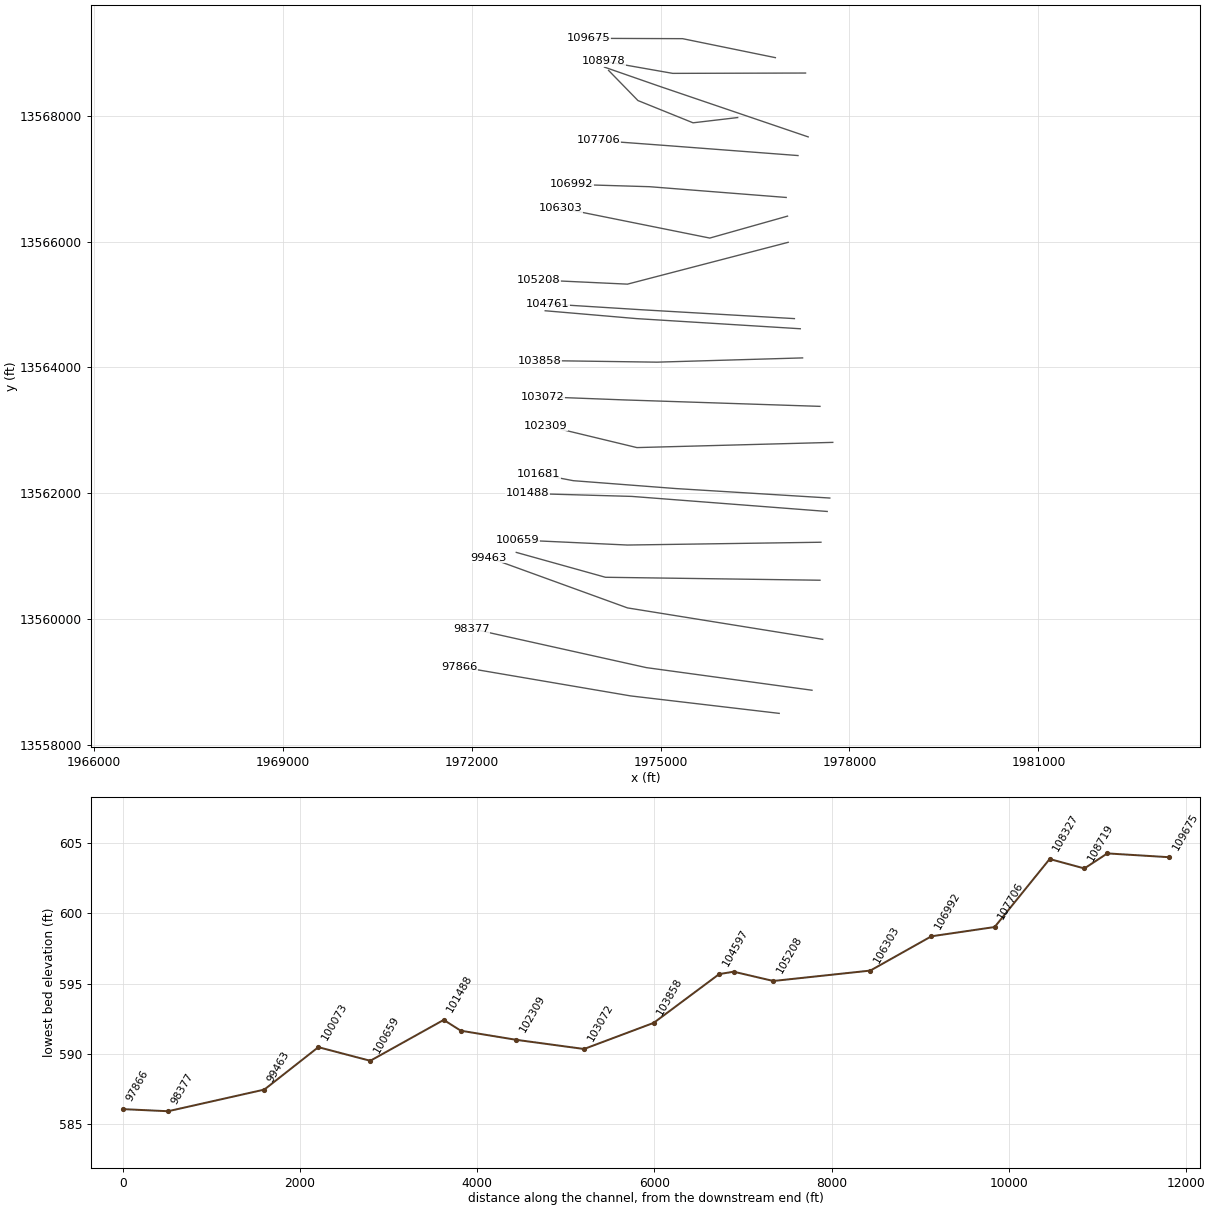
HEC-RAS study Black Creek.prj: Black Creek Base Level Engineering

--- Black Creek.g01 (geometry) --- (continued)

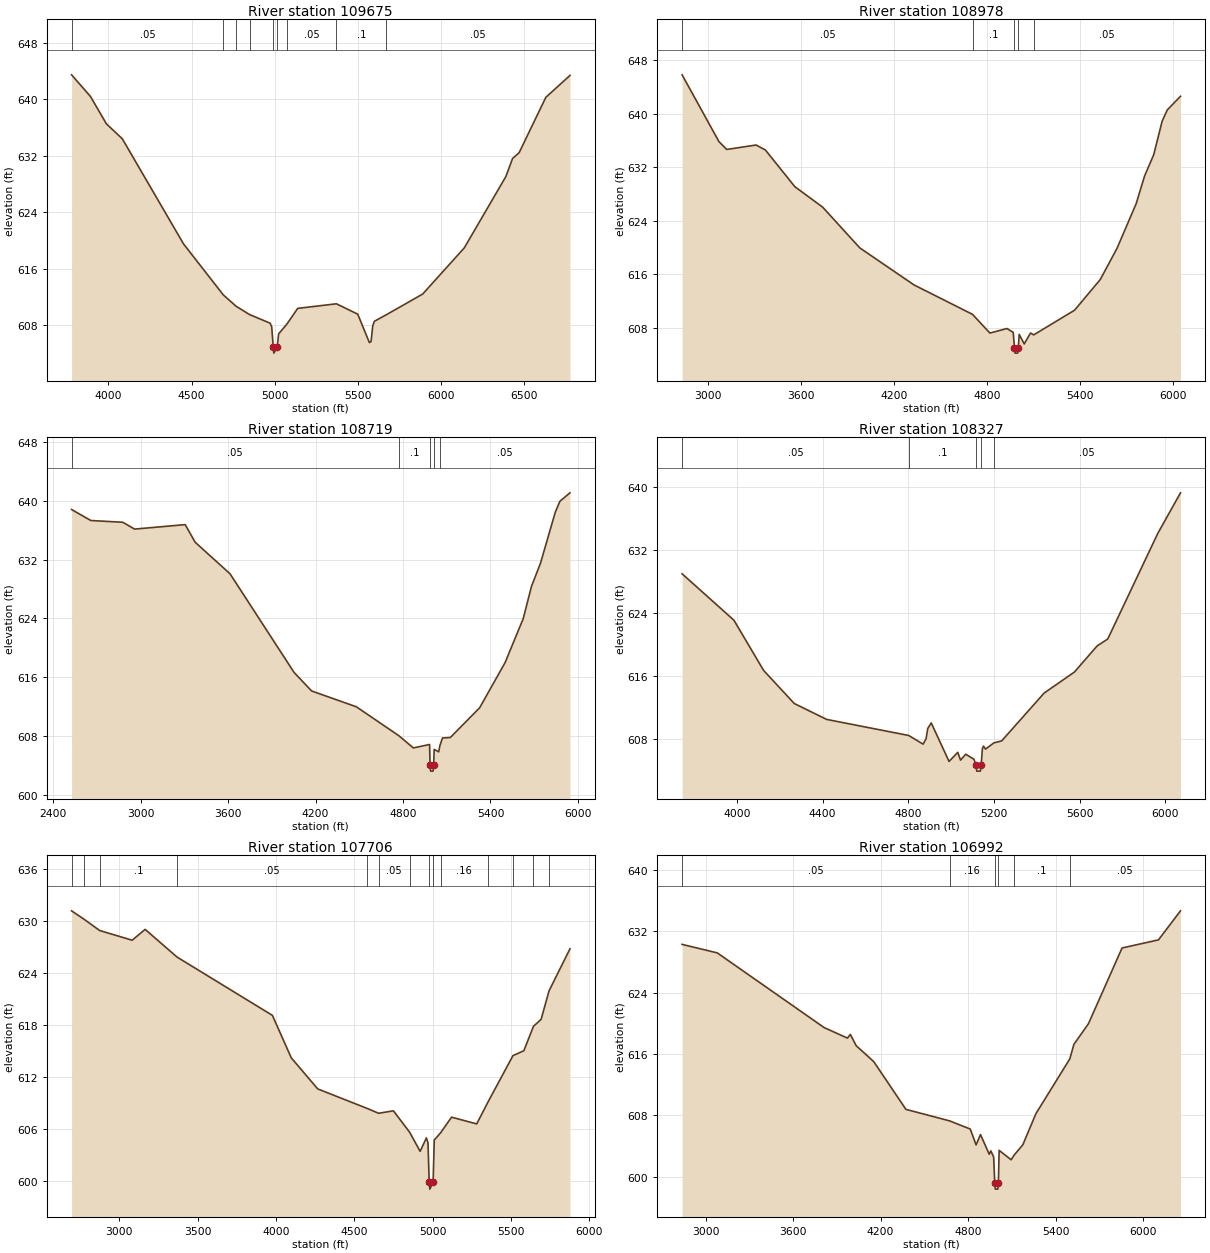
Type RM Length L Ch R = 1 ,109675  ,697,697,697
BEGIN DESCRIPTION:
Black Creek 111.0
END DESCRIPTION:
XS GIS Cut Line= 3
      1976823.61     13568927.76      1975349.66     13569229.84
      1973860.05     13569235.05
#Sta/Elev= 30
  3779.3  643.49  3892.7  640.42  3988.4  636.54  4084.1  634.41  4451.6  619.51
  4690.4  612.27  4767.8  610.65  4848.5  609.47  4972.2  608.25  4981.6  607.72
  4991.2   604.8  4994.5     604  5014.4   604.8  5023.2  606.74    5071  608.06
  5137.9  610.35  5370.2     611  5498.5  609.53  5568.5   605.5  5578.5  605.64
  5588.5  607.86  5598.5  608.52    5669  609.43  5888.5  612.38  6138.5  618.93
  6388.5  629.06  6428.5  631.61  6468.5  632.46  6628.6   640.3  6773.5   643.4
#Mann= 9 ,-1 , 0
  3779.3     .05       0  4690.4      .1       0  4767.8     .05       0
  4848.5      .1       0  4991.2     .07       0  5014.4      .1       0
    5071     .05       0  5370.2      .1       0    5669     .05       0
Bank Sta=4991.2,5014.4
XS Rating Curve= 0 ,0
Exp/Cntr=0.3,0.1

Type RM Length L Ch R = 1 ,108978  ,259,259,259
BEGIN DESCRIPTION:
Black Creek 110.0
END DESCRIPTION:
XS GIS Cut Line= 3
      1977302.82     13568682.97      1975193.41     13568677.76
      1974101.15      13568870.2
#Sta/Elev= 30
  2830.6  645.78  3068.4  635.82  3118.4  634.65  3308.4  635.31  3368.4  634.57
  3558.4   629.1  3738.4  626.04  3978.4  619.96  4328.4  614.44  4706.2  610.05
  4818.4  607.26  4928.4  607.94  4968.9  607.36  4976.9  605.07  4980.7  604.27
  4997.6  604.27  5001.5  605.07  5007.5  607.07  5039.9  605.64  5080.6  607.27
  5101.1  606.99  5364.9  610.67  5530.8  615.24    5639  619.89  5762.9  626.56
  5817.1  630.69  5876.3  633.87  5930.5  638.86    5964  640.55  6049.1  642.58
#Mann= 5 ,-1 , 0
  2830.6     .05       0  4706.2      .1       0  4976.9     .07       0
  5001.5      .1       0  5101.1     .05       0
Bank Sta=4976.9,5001.5
XS Rating Curve= 0 ,0
Exp/Cntr=0.3,0.1

Type RM Length L Ch R = 1 ,108719  ,392,392,392
BEGIN DESCRIPTION:
Black Creek 109.0
END DESCRIPTION:
XS GIS Cut Line= 3
      1977344.41     13567667.35        1974975.       13568475.
      1974110.09     13568776.71
#Sta/Elev= 30
    2526  638.83  2657.8  637.33  2877.2  637.09  2958.5  636.16  3305.5  636.77
  3373.5  634.38  3613.6  630.06  4052.5  616.64  4172.6  614.12  4479.9  611.96
  4770.9  608.03  4870.8  606.36  4982.3  606.83  4985.3     604  4989.1   603.2
    5006   603.2  5009.9     604  5013.6  606.16  5044.8  605.83  5052.9  606.68
  5070.6  607.71  5124.6  607.78  5325.8  611.83  5500.2  617.98  5624.5  623.96
  5681.3  628.36  5743.5  631.54  5844.8  638.48  5876.6  639.96  5945.3   641.1
#Mann= 5 ,-1 , 0
    2526     .05       0  4770.9      .1       0  4985.3     .07       0
  5009.9      .1       0  5052.9     .05       0
Bank Sta=4985.3,5009.9
XS Rating Curve= 0 ,0
Exp/Cntr=0.3,0.1

Type RM Length L Ch R = 1 ,108327  ,621,621,621
BEGIN DESCRIPTION:
Black Creek 108.0
END DESCRIPTION:
XS GIS Cut Line= 4
        1976225.       13567975.      1975516.32      13567891.3
      1974641.32     13568245.46      1974174.97     13568725.03
#Sta/Elev= 30
    3744  628.94  3985.7  623.05  4124.6  616.66  4267.6  612.46  4418.7  610.44
  4801.7   608.4    4869   607.3  4882.9  607.99  4890.6  609.28    4907  609.99
  4990.1   605.1  5030.8  606.26  5043.7  605.27  5067.9  606.02  5106.3  605.38
  5115.6  604.67  5119.4  603.87  5136.3  603.87  5140.2  604.67  5145.6  606.71
    5151  607.04  5160.3  606.67  5199.4  607.46  5235.8  607.71    5434  613.79
  5575.4  616.46  5681.4  619.78    5731  620.66  5964.4  634.07  6070.5  639.23
#Mann= 5 ,-1 , 0
    3744     .05       0  4801.7      .1       0  5115.6     .07       0
  5140.2      .1       0  5199.4     .05       0
Bank Sta=5115.6,5140.2
XS Rating Curve= 0 ,0
Exp/Cntr=0.3,0.1

Type RM Length L Ch R = 1 ,107706  ,714,714,714
BEGIN DESCRIPTION:
Black Creek 107.0
END DESCRIPTION:
XS GIS Cut Line= 3
      1977183.01     13567370.46       1975063.2     13567531.92
      1974011.45     13567610.02
#Sta/Elev= 30
  2696.3  631.13  2776.5  630.15  2875.4  628.86  3082.8  627.74  3165.7  628.99
  3369.9  625.79    3978  619.07  4098.4  614.17    4267  610.59  4583.9  608.33
  4655.4  607.78  4750.2  608.06  4853.1  605.61  4920.7  603.39  4960.8  604.94
  4970.9  604.37  4978.5  599.83  4982.4  599.03  5003.4  599.83    5011   604.7
  5050.8  605.51  5121.3  607.33  5281.7  606.55  5354.5   609.1  5513.2  614.43
  5582.5  614.99    5644  617.81  5692.8  618.61  5743.2  621.89  5876.9  626.75
#Mann= 14 ,-1 , 0
  2696.3     .05       0  2776.5     .08       0  2875.4      .1       0
  3369.9     .05       0  4583.9     .08       0  4655.4     .05       0
  4853.1     .12       0  4978.5     .07       0  5003.4     .12       0
  5050.8     .16       0  5354.5      .1       0  5513.2     .08       0
    5644     .05       0  5743.2      .1       0
Bank Sta=4978.5,5003.4
XS Rating Curve= 0 ,0
Exp/Cntr=0.3,0.1

Type RM Length L Ch R = 1 ,106992  ,689,689,689
BEGIN DESCRIPTION:
Black Creek 106.0
END DESCRIPTION:
XS GIS Cut Line= 3
      1976995.51      13566703.8        1974825.       13566875.
        1973584.     13566912.13
#Sta/Elev= 30
  2838.6  630.31  3079.9   629.2  3812.4  619.46  3972.6  618.08  3992.7  618.56
  4032.8  617.09  4153.2  615.01  4373.9  608.78  4673.3  607.28  4815.2  606.21
  4855.4  604.14  4885.4  605.49  4945.6  602.92  4956.5  603.36  4975.7  602.57
  4983.3  599.17  4987.3  598.37  5004.3  598.37  5008.2  599.17  5013.3  603.43
  5095.9   602.2  5114.9  602.78  5175.9  604.16    5266  608.23  5498.2  615.37
  5526.1  617.26  5626.1  619.96  5856.5  629.84  6106.3   630.9  6257.4  634.69
#Mann= 6 ,-1 , 0
  2838.6     .05       0  4673.3     .16       0  4983.3     .07       0
  5008.2     .16       0  5114.9      .1       0  5498.2     .05       0
Bank Sta=4983.3,5008.2
XS Rating Curve= 0 ,0
Exp/Cntr=0.3,0.1

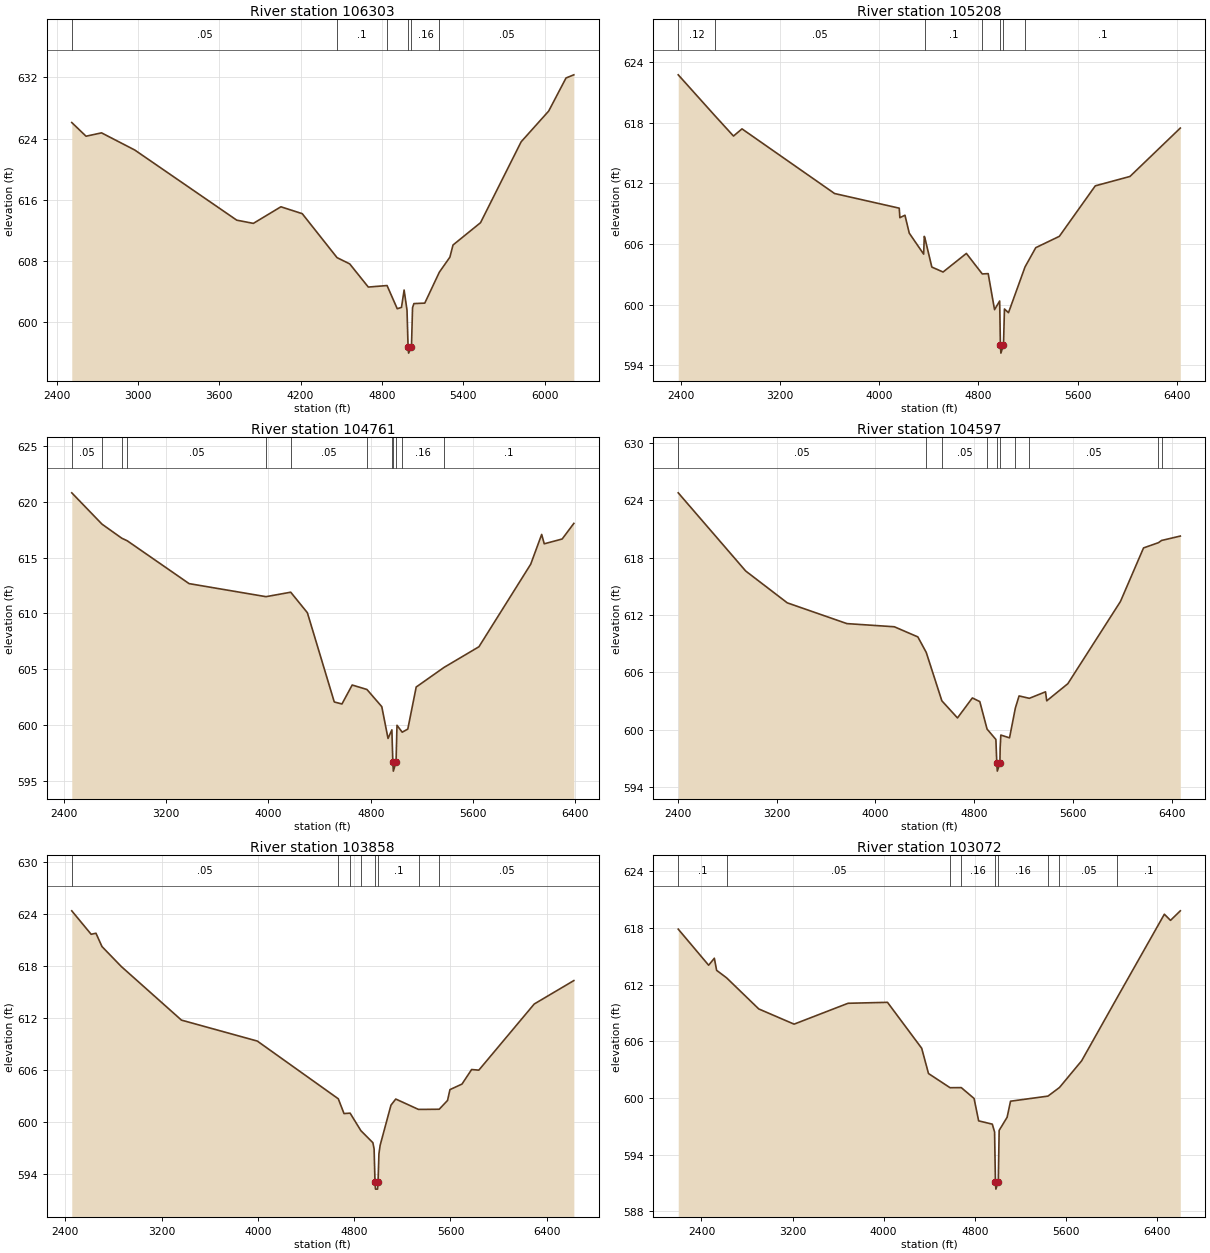
Type RM Length L Ch R = 1 ,106303  ,1095,1095,1095
BEGIN DESCRIPTION:
Mapping XS 794d57eb
END DESCRIPTION:
XS GIS Cut Line= 3
      1977016.32     13566406.92      1975781.95     13566057.96
      1973408.52     13566536.81
#Sta/Elev= 30
  2512.3  626.09  2617.6   624.3  2731.9  624.74  2977.5  622.49  3729.5  613.32
    3852   612.9  4055.1  615.07  4212.6  614.17  4469.3  608.42    4563   607.6
  4699.9  604.57  4838.3  604.77  4913.4  601.74  4944.7  601.91  4964.2  604.18
  4985.5  601.55  4993.5  596.73  4997.4  595.93  5018.4  596.73  5026.3  601.88
  5036.5  602.41  5116.5  602.47  5223.8  606.51  5301.8  608.48  5324.8  610.07
  5527.9  612.99  5827.5  623.57  6030.7  627.59  6158.7  631.92  6216.3  632.33
#Mann= 6 ,-1 , 0
  2512.3     .05       0  4469.3      .1       0  4838.3     .16       0
  4993.5     .07       0  5018.4     .16       0  5223.8     .05       0
Bank Sta=4993.5,5018.4
XS Rating Curve= 0 ,0
Exp/Cntr=0.3,0.1

Type RM Length L Ch R = 1 ,105208  ,447,447,447
BEGIN DESCRIPTION:
Black Creek 105.0
END DESCRIPTION:
XS GIS Cut Line= 3
      1977026.78     13565990.27        1974475.       13565325.
      1973059.02     13565391.25
#Sta/Elev= 30
  2375.5  622.74  2672.7  618.68  2821.7  616.68  2890.4  617.39  3638.1  610.99
  4160.2  609.54  4165.3   608.6  4206.5  608.84  4241.1  607.07  4357.4  604.99
  4362.6  606.75  4366.8  606.62  4423.5  603.71  4514.2  603.22  4702.5  605.06
  4830.6  603.03  4878.6  603.06  4929.9  599.49  4971.2  600.35  4977.2  595.99
  4981.2  595.19  5002.2  595.99    5010  599.56  5042.6  599.19    5176  603.72
  5262.8  605.63  5453.1  606.75  5743.4  611.75  6023.7  612.68  6430.1  617.47
#Mann= 7 ,-1 , 0
  2375.5     .12       0  2672.7     .05       0  4366.8      .1       0
  4830.6     .16       0  4977.2     .07       0  5002.2     .16       0
    5176      .1       0
Bank Sta=4977.2,5002.2
XS Rating Curve= 0 ,0
Exp/Cntr=0.3,0.1

Type RM Length L Ch R = 1 ,104761  ,164,164,164
BEGIN DESCRIPTION:
Black Creek 104.0
END DESCRIPTION:
XS GIS Cut Line= 3
       1977125.7     13564776.71      1974703.82     13564917.34
       1973203.8     13565011.09
#Sta/Elev= 30
  2460.8   620.8  2697.6  617.99  2852.3  616.73    2895   616.5    3379  612.66
  3980.8  611.49  4174.2  611.89  4304.6  610.05    4515  602.05  4575.1  601.87
  4655.2  603.57  4770.5  603.17  4886.8  601.63  4935.7  598.78  4965.7  599.55
  4967.9  598.71  4973.3  596.65  4977.3  595.85  4998.3  596.65  5005.8  599.96
  5046.6  599.34  5090.3  599.62  5156.1  603.39  5374.2  605.15  5647.1     607
  6052.2   614.4    6138  617.07  6158.1  616.23  6298.3  616.66  6389.7  618.06
#Mann= 12 ,-1 , 0
  2460.8     .05       0  2697.6      .1       0  2852.3     .08       0
    2895     .05       0  3980.8      .1       0  4174.2     .05       0
  4770.5     .08       0  4967.9     .05       0  4973.3     .04       0
  4998.3     .05       0  5046.6     .16       0  5374.2      .1       0
Bank Sta=4973.3,4998.3
XS Rating Curve= 0 ,0
Exp/Cntr=0.3,0.1

Type RM Length L Ch R = 1 ,104597  ,739,739,739
BEGIN DESCRIPTION:
Black Creek 103.0
END DESCRIPTION:
XS GIS Cut Line= 3
      1977219.47     13564615.26      1974620.49     13564776.71
      1973168.64     13564901.61
#Sta/Elev= 30
  2404.7  624.77  2950.2   616.6  3286.7  613.27  3769.1   611.1  4152.5  610.77
  4342.9  609.71  4410.8  608.09  4537.1  603.03  4663.5  601.24  4783.7  603.33
  4843.9  602.95    4903  600.07  4974.1  598.99  4981.6  596.48  4985.6  595.68
  5006.6  596.48  5008.7  598.12  5014.2  599.45  5084.5  599.16  5131.8  602.28
  5161.7  603.54  5244.8  603.29  5375.5  603.97  5385.6  603.03  5556.2  604.82
  5981.6  613.41  6168.4  619.01    6289  619.56  6314.2  619.79  6465.9  620.25
#Mann= 10 ,-1 , 0
  2404.7     .05       0  4410.8      .1       0  4537.1     .05       0
    4903     .16       0  4981.6     .07       0  5006.6     .16       0
  5131.8      .1       0  5244.8     .05       0    6289      .1       0
  6314.2     .05       0
Bank Sta=4981.6,5006.6
XS Rating Curve= 0 ,0
Exp/Cntr=0.3,0.1

Type RM Length L Ch R = 1 ,103858  ,786,786,786
BEGIN DESCRIPTION:
Black Creek 102.0
END DESCRIPTION:
XS GIS Cut Line= 3
      1977255.88     13564151.71      1974943.41     13564084.01
      1973085.76     13564110.02
#Sta/Elev= 30
  2453.9  624.37  2614.9  621.66  2654.9  621.78  2704.9  620.24    2865  617.94
  3365.2  611.74  3995.4  609.32  4668.2  602.65  4715.8  600.94  4766.5  600.99
  4855.8  598.97  4955.8  597.57  4965.8  596.84  4973.2  593.01  4977.2  592.21
  4994.3  592.21  4998.4  593.01  5005.8  596.28  5015.8  597.27  5105.8  601.91
  5145.8  602.62  5334.6  601.42  5506.6  601.44  5575.9  602.46  5595.9  603.71
  5695.9  604.35  5775.9  606.03  5835.9  605.96  6295.9   613.6  6625.2  616.31
#Mann= 8 ,-1 , 0
  2453.9     .05       0  4668.2      .1       0  4766.5     .16       0
  4855.8      .1       0  4973.2     .07       0  4998.4      .1       0
  5334.6      .1       0  5506.6     .05       0
Bank Sta=4973.2,4998.4
XS Rating Curve= 0 ,0
Exp/Cntr=0.3,0.1

Type RM Length L Ch R = 1 ,103072  ,763,763,763
BEGIN DESCRIPTION:
Black Creek 101.0
END DESCRIPTION:
XS GIS Cut Line= 3
      1977531.93     13563380.88        1974425.     13563483.33
      1973124.98     13563533.33
#Sta/Elev= 30
    2196  617.88  2463.1  614.06  2513.1   614.8  2533.1  613.52  2621.1  612.72
  2903.3  609.43  3213.5  607.82  3687.5  610.03  4033.9  610.13  4334.1  605.27
  4394.1  602.59  4583.3  601.09  4681.8   601.1  4794.3  599.95  4834.4  597.58
  4954.4  597.23  4974.4   596.4  4981.8  591.15  4985.9  590.35    5007  591.15
  5014.5  596.57  5084.5  597.96  5114.5  599.66  5443.3   600.2  5544.2  601.11
  5739.1  603.94  6053.4  610.68  6465.5  619.46  6519.7  618.81  6605.6  619.82
#Mann= 9 ,-1 , 0
    2196      .1       0  2621.1     .05       0  4583.3      .1       0
  4681.8     .16       0  4981.8     .07       0    5007     .16       0
  5443.3      .1       0  5544.2     .05       0  6053.4      .1       0
Bank Sta=4981.8,5007
XS Rating Curve= 0 ,0
Exp/Cntr=0.3,0.1

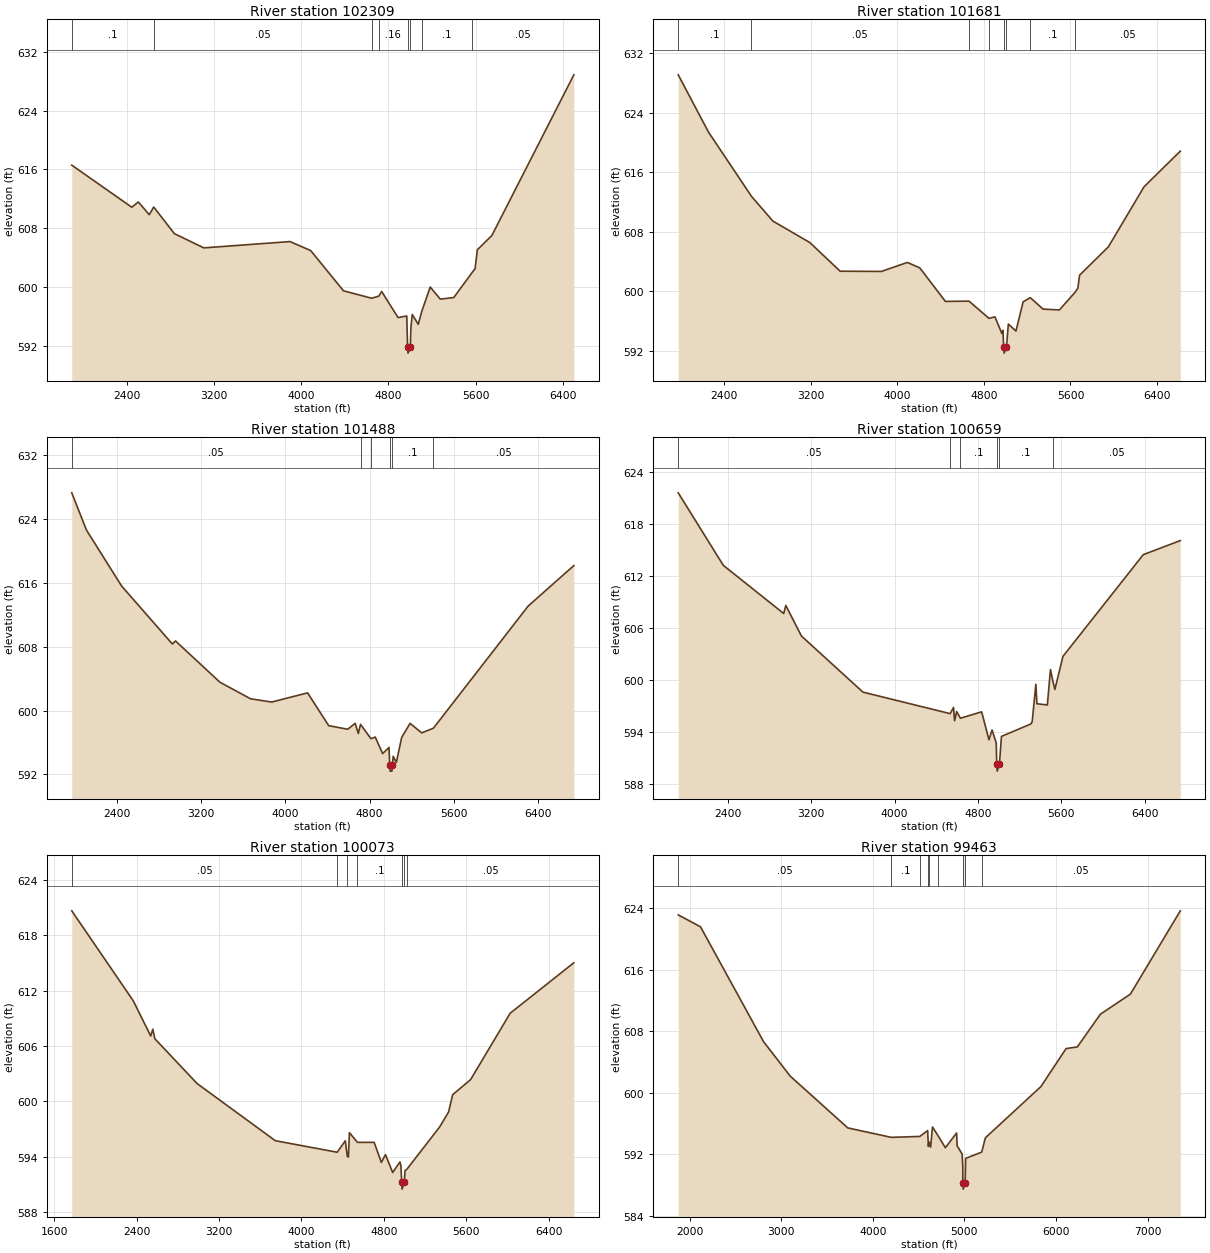
Type RM Length L Ch R = 1 ,102309  ,628,628,628
BEGIN DESCRIPTION:
Black Creek 100.0
END DESCRIPTION:
XS GIS Cut Line= 3
      1977735.12     13562807.97        1974625.       13562725.
      1973174.97     13563075.01
#Sta/Elev= 30
    1897  616.58  2447.3  610.85  2507.3  611.57  2607.4  609.84  2648.4  610.88
  2837.5  607.26  3107.6  605.32  3897.8  606.18  4087.9  604.95    4388  599.48
  4646.3  598.47  4712.2  598.76  4738.1  599.39  4888.2  595.84  4968.2  596.05
  4975.6   591.8  4979.7     591  5000.8   591.8  5005.7  594.38  5018.5  596.25
  5073.6  594.92  5105.2  596.65  5183.1  599.99  5275.7  598.35  5399.1  598.56
  5564.3  601.91  5594.6  602.49  5615.2  605.06  5748.9  607.02  6499.9  628.87
#Mann= 8 ,-1 , 0
    1897      .1       0  2648.4     .05       0  4646.3      .1       0
  4712.2     .16       0  4975.6     .07       0  5000.8     .16       0
  5105.2      .1       0  5564.3     .05       0
Bank Sta=4975.6,5000.8
XS Rating Curve= 0 ,0
Exp/Cntr=0.3,0.1

Type RM Length L Ch R = 1 ,101681  ,193,193,193
BEGIN DESCRIPTION:
Black Creek 99.0
END DESCRIPTION:
XS GIS Cut Line= 4
      1977688.16     13561922.55      1975240.28     13562073.59
      1973615.28     13562198.59      1973069.23      13562302.6
#Sta/Elev= 30
  1976.3  629.09  2257.3  621.35  2652.7  612.75  2851.1  609.41  3191.8  606.53
  3472.3  602.67    3853  602.64  4093.5  603.85  4208.4  603.11  4444.2  598.61
  4662.8  598.64  4846.7  596.33    4902  596.53  4965.7   594.3  4975.7  594.72
  4983.1  592.45  4987.2  591.65  5008.4  592.45  5025.9  595.56  5096.1  594.62
  5162.8  598.56  5228.9  599.11  5346.8  597.57  5497.3  597.46    5644  599.86
  5667.8  600.38  5684.3  602.14  5950.1  605.95  6278.9  614.02  6614.5  618.83
#Mann= 8 ,-1 , 0
  1976.3      .1       0  2652.7     .05       0  4662.8      .1       0
  4846.7     .16       0  4983.1     .07       0  5008.4     .16       0
  5228.9      .1       0    5644     .05       0
Bank Sta=4983.1,5008.4
XS Rating Curve= 0 ,0
Exp/Cntr=0.3,0.1

Type RM Length L Ch R = 1 ,101488  ,829,829,829
BEGIN DESCRIPTION:
Black Creek 98.0
END DESCRIPTION:
XS GIS Cut Line= 3
      1977646.55     13561709.01      1974542.37     13561948.59
      1972891.34     13561995.46
#Sta/Elev= 30
  1972.7  627.31  2112.6  622.63  2445.6  615.63  2927.1  608.36  2957.2  608.74
  3378.4  603.57  3669.3  601.49  3869.9  601.08  4210.9  602.23  4411.5  598.12
    4592  597.67  4662.2  598.41  4692.3  597.14  4713.3  598.28  4812.2  596.49
  4852.8  596.69    4923  594.62  4983.2  595.39  4990.6  593.22  4994.7  592.42
  5011.8  592.42  5015.9  593.22  5023.3  594.28  5053.4  593.51  5103.5  596.63
  5183.5  598.41  5293.6  597.22  5404.9   597.8    6304  613.11  6737.8  618.19
#Mann= 6 ,-1 , 0
  1972.7     .05       0  4713.3     .16       0  4812.2      .1       0
  4990.6     .07       0  5015.9      .1       0  5404.9     .05       0
Bank Sta=4990.6,5015.9
XS Rating Curve= 0 ,0
Exp/Cntr=0.3,0.1

Type RM Length L Ch R = 1 ,100659  ,586,586,586
BEGIN DESCRIPTION:
Black Creek 97.0
END DESCRIPTION:
XS GIS Cut Line= 3
       1977547.6     13561219.42        1974475.       13561175.
       1972729.9     13561255.88
#Sta/Elev= 30
  1923.5  621.56  2356.1  613.21  2936.2  607.66  2956.2  608.59  3106.2  605.07
  3696.3  598.61  4534.1  596.13  4566.4  596.85  4576.4  595.31  4596.4  596.37
  4632.4   595.6  4836.4  596.34  4906.4  593.12  4936.4  594.25  4976.4  592.76
  4981.3  590.31  4985.4  589.51  5006.6  590.31  5026.5  593.51  5306.8  594.93
  5321.1  595.17  5356.8  599.51  5366.8  597.27  5466.9  597.13    5497  601.21
  5518.8  599.93  5539.2  598.92  5617.1  602.73  6387.9  614.44  6743.4  616.06
#Mann= 6 ,-1 , 0
  1923.5     .05       0  4534.1     .08       0  4632.4      .1       0
  4981.3     .07       0  5006.6      .1       0  5518.8     .05       0
Bank Sta=4981.3,5006.6
XS Rating Curve= 0 ,0
Exp/Cntr=0.3,0.1

Type RM Length L Ch R = 1 ,100073  ,610,610,610
BEGIN DESCRIPTION:
Black Creek 96.0
END DESCRIPTION:
XS GIS Cut Line= 3
      1977531.99     13560615.26       1974125.7     13560662.13
      1972709.56     13561057.82
#Sta/Elev= 30
  1768.5  620.65  2365.5   610.9  2535.6  607.08  2555.6  607.82  2575.6  606.78
  2985.6  601.93  3745.7  595.73  4346.8  594.48  4425.7  595.72  4445.2  594.04
  4455.7  593.96  4465.7   596.6  4543.6  595.55  4705.8  595.55  4775.8  593.38
  4815.8  594.22  4885.8  592.28  4955.8  593.42  4965.8  593.03  4973.1  591.28
  4977.2  590.48  4998.4  591.28  5005.8  592.49  5023.3  592.63    5342  597.22
  5428.8  598.84  5468.1  600.71  5643.1  602.36  6027.2  609.55  6645.5  615.02
#Mann= 7 ,-1 , 0
  1768.5     .05       0  4346.8      .1       0  4445.2     .05       0
  4543.6      .1       0  4973.1     .07       0  4998.4      .1       0
  5023.3     .05       0
Bank Sta=4973.1,4998.4
XS Rating Curve= 0 ,0
Exp/Cntr=0.3,0.1

Type RM Length L Ch R = 1 ,99463   ,1086,1086,1086
BEGIN DESCRIPTION:
Black Creek 95.0
END DESCRIPTION:
XS GIS Cut Line= 3
      1977575.04     13559674.99        1974475.       13560175.
      1972275.04     13560974.99
#Sta/Elev= 30
  1875.9  623.16    2119  621.61  2807.8  606.65  3098.5  602.17  3726.6  595.43
    4202   594.2  4513.1  594.32  4598.5  595.08  4606.8  593.03  4613.2  593.61
  4631.1  592.92  4651.4  595.55  4713.4  594.39  4792.1  592.85  4914.7  594.77
  4920.8   593.1  4975.5  592.02  4982.6  590.27    4983  588.26  4987.2  587.46
  5008.4  588.26  5013.5  591.46    5189  592.28  5228.8  594.14  5835.3  600.81
    6110  605.76  6232.4  605.97  6484.4  610.23  6812.3  612.85  7356.9  623.69
#Mann= 9 ,-1 , 0
  1875.9     .05       0    4202      .1       0  4513.1     .05       0
  4598.5      .1       0  4613.2     .08       0  4713.4      .1       0
    4983     .07       0  5008.4      .1       0    5189     .05       0
Bank Sta=4983,5008.4
XS Rating Curve= 0 ,0
Exp/Cntr=0.3,0.1

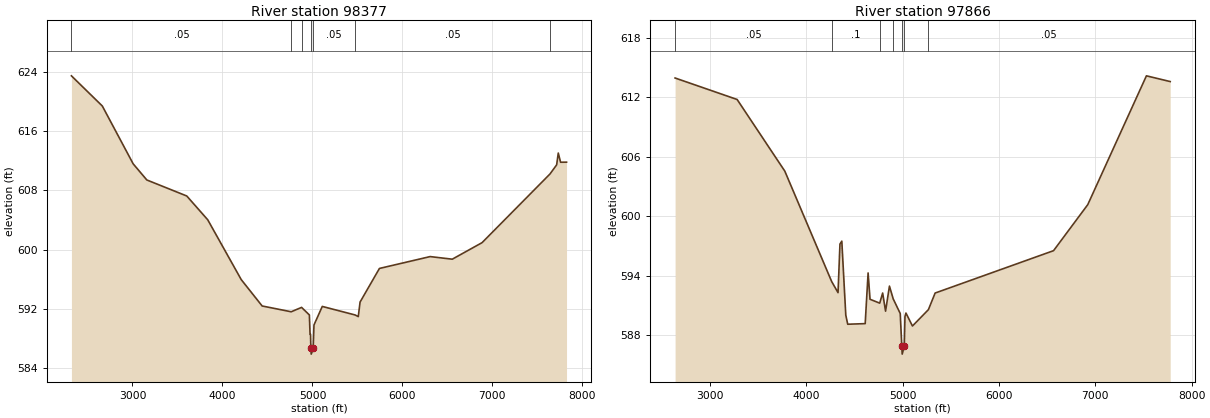
Type RM Length L Ch R = 1 ,98377   ,511,511,511
BEGIN DESCRIPTION:
Black Creek 94.0
END DESCRIPTION:
XS GIS Cut Line= 3
      1977405.22     13558865.26        1974775.       13559225.
      1971995.49     13559844.42
#Sta/Elev= 30
  2321.4  623.44  2664.8  619.37    3008  611.57  3159.4   609.4  3603.4  607.24
  3836.5  604.03    4209  595.96  4441.2  592.41  4764.1  591.63  4879.3  592.22
    4966   591.2  4973.6   588.6  4978.7   588.6  4982.5  586.72  4986.7  585.92
    5008  586.72  5017.1  589.85  5109.3  592.35  5474.1   591.2  5509.4  590.98
  5529.4  592.94  5744.5  597.47    6308  599.07  6553.9  598.72  6885.4  600.95
  7640.2  610.21  7714.1  611.44  7732.1  613.03  7757.6  611.79  7823.8   611.8
#Mann= 7 ,-1 , 0
  2321.4     .05       0  4764.1      .1       0  4879.3     .05       0
  4982.5     .07       0    5008     .05       0  5474.1     .05       0
  7640.2      .1       0
Bank Sta=4982.5,5008
XS Rating Curve= 0 ,0
Exp/Cntr=0.3,0.1

Type RM Length L Ch R = 1 ,97866   ,924,924,924
BEGIN DESCRIPTION:
Black Creek 93.0
END DESCRIPTION:
XS GIS Cut Line= 3
      1976884.35      13558497.2        1974525.       13558775.
      1971801.79     13559240.13
#Sta/Elev= 30
    2639  613.96  3282.8  611.79  3777.9  604.55  4263.6  593.41    4330  592.28
  4350.1  597.19  4369.2  597.48  4410.5  590.01  4430.6  589.09  4611.9  589.15
  4642.1  594.27  4662.2  591.61  4762.5  591.22  4793.1  592.24  4823.3  590.41
  4863.6  592.94  4902.7  591.65  4975.6  590.17  4991.8  586.87    4996  586.07
  5017.3  586.87  5024.8  589.88  5034.9  590.22  5102.3  588.91  5267.8  590.56
  5337.8  592.24  6566.8  596.52  6921.9  601.17  7530.6  614.18  7777.3   613.6
#Mann= 7 ,-1 , 0
    2639     .05       0  4263.6      .1       0  4762.5     .05       0
  4902.7      .1       0  4991.8     .07       0  5017.3      .1       0
  5267.8     .05       0
Bank Sta=4991.8,5017.3
XS Rating Curve= 0 ,0
Exp/Cntr=0.3,0.1