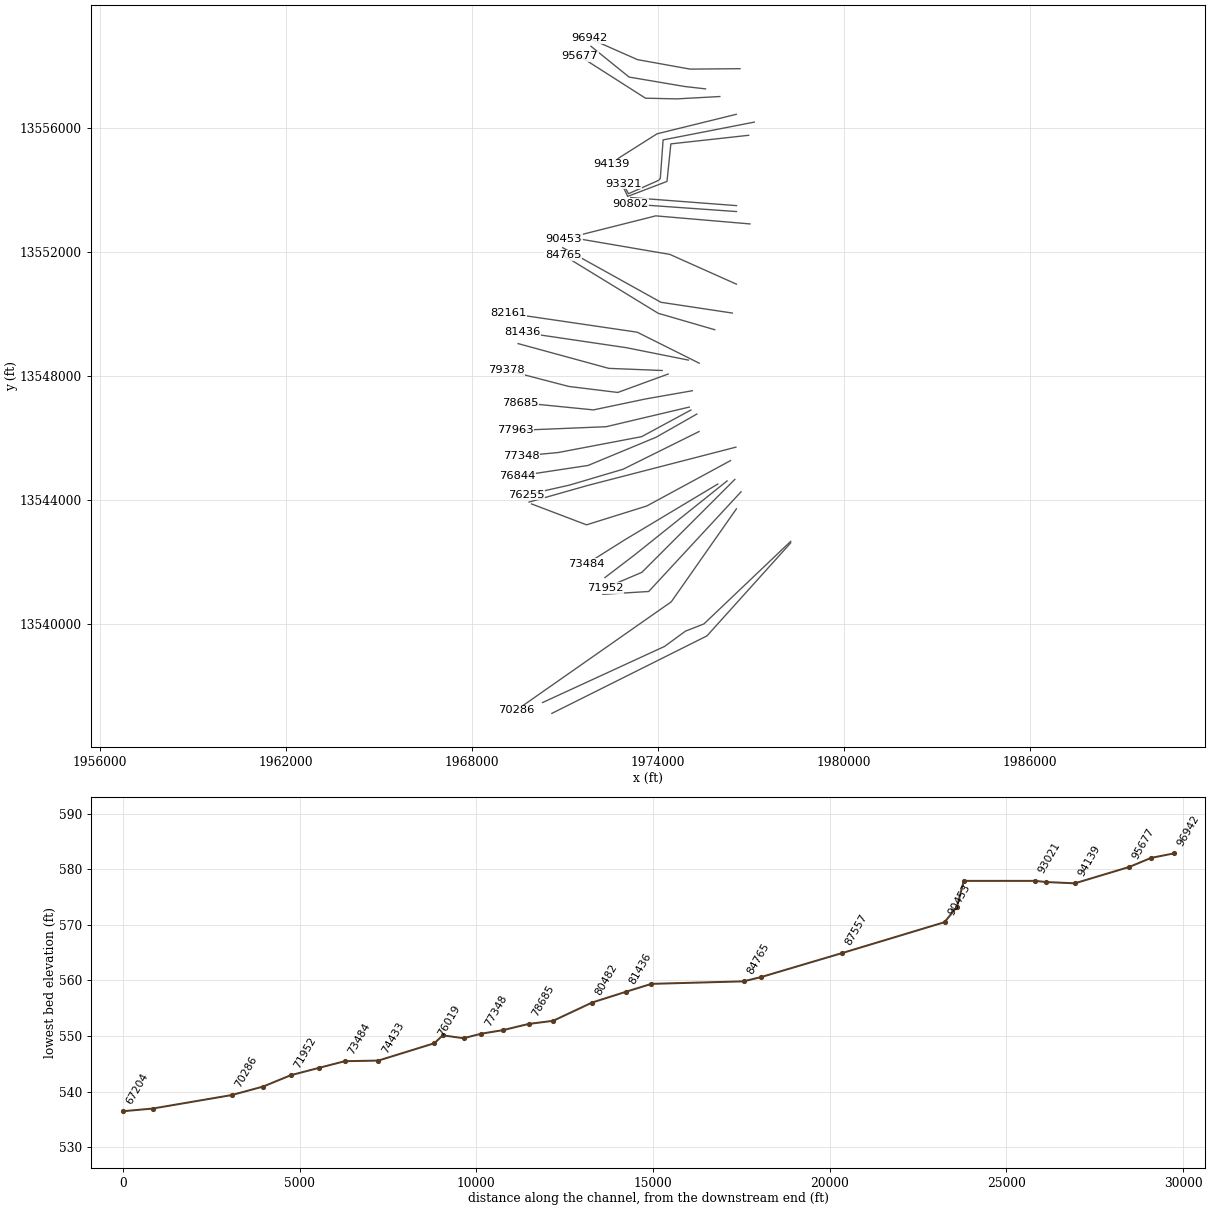
HEC-RAS study Black Creek.prj: Black Creek Base Level Engineering

--- Black Creek.g01 (geometry) --- (continued)

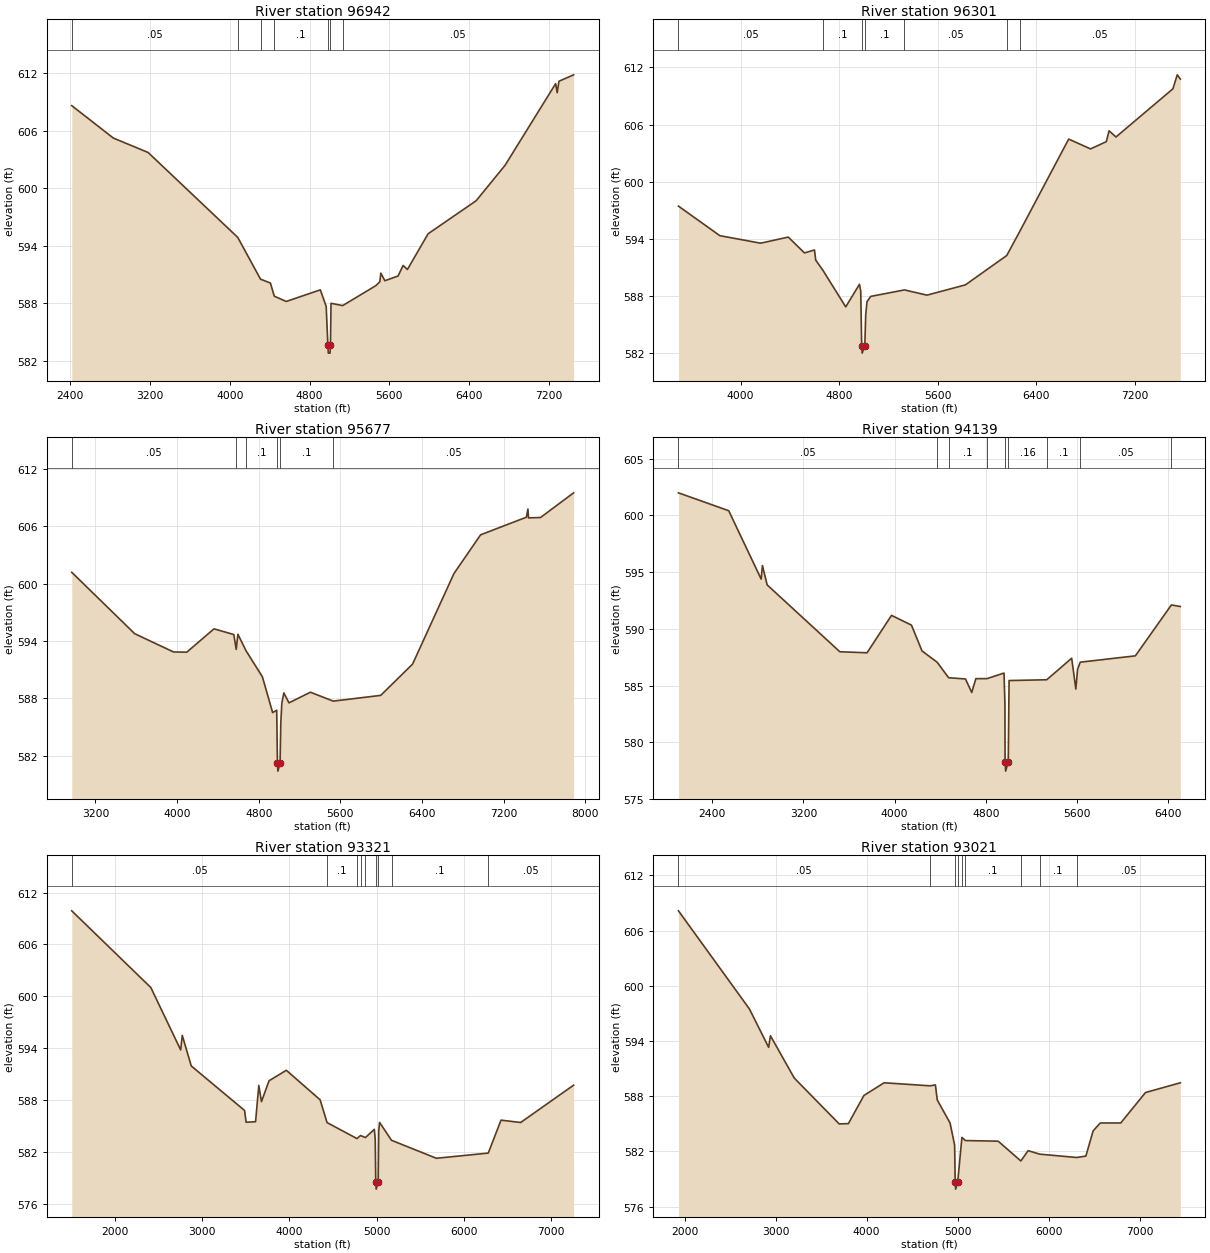
Type RM Length L Ch R = 1 ,96942   ,641,641,641
BEGIN DESCRIPTION:
Mapping XS cc46b33c
END DESCRIPTION:
XS GIS Cut Line= 4
      1976641.36     13557927.76      1975030.21     13557913.87
      1973335.77     13558219.42      1971780.21     13558906.93
#Sta/Elev= 30
  2413.9   608.6  2830.3  605.23  3180.3  603.72  4078.9  594.88  4307.4  590.53
  4406.4  590.13  4445.3  588.76  4565.3  588.21  4907.1  589.42  4965.8   587.7
    4983  583.63  4987.1  582.83  5004.3  582.83  5008.5  583.63  5014.3  588.02
  5131.4  587.78  5463.1  589.85  5503.8  590.26    5514  591.16  5554.6  590.37
  5686.7  590.86  5737.5  591.96  5780.5  591.54  5988.3  595.26  6470.2   598.7
  6760.8   602.4  7267.4  610.89  7282.9  609.95  7300.2  611.14  7447.6  611.81
#Mann= 7 ,-1 , 0
  2413.9     .05       0  4078.9      .1       0  4307.4     .05       0
  4445.3      .1       0    4983     .07       0  5008.5      .1       0
  5131.4     .05       0
Bank Sta=4983,5008.5
XS Rating Curve= 0 ,0
Exp/Cntr=0.3,0.1

Type RM Length L Ch R = 1 ,96301   ,624,624,624
BEGIN DESCRIPTION:
Mapping XS e1eabb07
END DESCRIPTION:
XS GIS Cut Line= 4
      1975528.82     13557275.87      1974862.13     13557352.26
      1973064.93     13557656.92      1971835.75     13558649.99
#Sta/Elev= 30
  3495.9  597.45  3831.9  594.35    4163  593.56  4387.2   594.2    4519  592.54
  4600.2  592.85  4610.3  591.78  4669.5   590.7  4853.7  586.88  4965.3  589.25
  4975.5  588.53  4983.2  582.83  4987.3  582.03  5008.7  582.83    5016  586.06
  5026.2  587.41  5056.6  587.98  5330.5  588.66    5513  588.11  5825.5  589.19
    6161  592.27  6266.7   594.8  6663.8  604.48  6841.3  603.45  6969.3  604.21
  6991.6  605.35  7047.6   604.7  7509.7  609.75  7545.3  611.22    7570  610.78
#Mann= 7 ,-1 , 0
  3495.9     .05       0  4669.5      .1       0  4983.2     .07       0
  5008.7      .1       0  5330.5     .05       0    6161      .1       0
  6266.7     .05       0
Bank Sta=4983.2,5008.7
XS Rating Curve= 0 ,0
Exp/Cntr=0.3,0.1

Type RM Length L Ch R = 1 ,95677   ,1538,1538,1538
BEGIN DESCRIPTION:
Black Creek 89.0
END DESCRIPTION:
XS GIS Cut Line= 4
      1975990.64     13557029.35      1974598.24     13556952.96
      1973592.28     13556975.93      1971472.17     13558330.68
#Sta/Elev= 30
  2967.9  601.18  3584.5  594.76    3965  592.85  4095.2  592.83  4361.5  595.27
  4555.7  594.67    4579  593.12  4595.7   594.7  4677.4  592.94  4835.8  590.25
  4935.8  586.51  4975.8  586.76  4982.9  581.19  4987.2  580.39  5008.6  581.19
  5015.8   585.4  5025.8  587.49  5045.8  588.57  5095.8  587.53  5305.9  588.64
  5529.9  587.71  5994.7  588.31  6306.8  591.58  6712.8  601.06  6973.4   605.1
  7421.7  606.94  7436.9   607.8  7442.9  606.87  7560.8  606.91  7884.6  609.49
#Mann= 6 ,-1 , 0
  2967.9     .05       0    4579     .08       0  4677.4      .1       0
  4982.9     .07       0  5008.6      .1       0  5529.9     .05       0
Bank Sta=4982.9,5008.6
XS Rating Curve= 0 ,0
Exp/Cntr=0.3,0.1

Type RM Length L Ch R = 1 ,94139   ,818,818,818
BEGIN DESCRIPTION:
Mapping XS 026bcd2f
END DESCRIPTION:
XS GIS Cut Line= 4
      1976519.66      13556455.1      1973965.25      13555825.7
      1972755.76     13555060.57      1972491.84     13554845.26
#Sta/Elev= 30
  2103.6     602  2544.5  600.42  2829.3  594.39  2840.1  595.59  2881.6  593.88
  3519.4  587.98  3758.2  587.89  3972.5  591.19  4147.6  590.33  4240.3  588.05
  4372.9  587.06  4473.4  585.69  4621.4  585.58  4676.3  584.39  4712.7  585.61
  4810.2  585.61  4959.5   586.1  4967.5  583.38  4968.9  578.25  4973.8  577.45
  4996.7  578.25  5003.9  585.44  5334.3  585.51  5553.2  587.41  5589.7  584.69
    5605  586.44  5628.2  587.06  6111.9  587.62  6427.8  592.11  6506.2  591.97
#Mann= 9 ,-1 , 0
  2103.6     .05       0  4372.9     .08       0  4473.4      .1       0
  4810.2     .16       0  4968.9     .07       0  4996.7     .16       0
  5334.3      .1       0  5628.2     .05       0  6427.8      .1       0
Bank Sta=4968.9,4996.7
XS Rating Curve= 0 ,0
Exp/Cntr=0.3,0.1

Type RM Length L Ch R = 1 ,93321   ,300,300,300
BEGIN DESCRIPTION:
Mapping XS 8bec680b
END DESCRIPTION:
XS GIS Cut Line= 6
      1977101.26     13556203.36      1974161.43     13555629.96
      1974071.16      13554386.9       1974015.6      13554324.4
       1973044.6     13553892.81      1972871.44      13554219.6
#Sta/Elev= 30
  1503.7  609.88  2410.5  601.01  2753.1  593.79  2771.6  595.47  2874.8  591.93
  3486.6  586.78  3504.1  585.42  3612.3  585.48  3649.7  589.68  3680.2   587.8
  3767.1  590.22  3965.5  591.43  4352.7  588.02  4432.7  585.38  4775.9  583.53
  4816.7  583.88  4873.1  583.65  4975.1   584.6  4985.2  583.46  4991.3  578.48
  4996.3  577.68  5019.1  578.48  5025.3   584.4  5035.3   585.4  5172.1  583.33
    5687  581.25  6282.1  581.85  6428.3  585.66    6654  585.39  7261.3  589.71
#Mann= 9 ,-1 , 0
  1503.7     .05       0  4432.7      .1       0  4775.9     .16       0
  4816.7      .1       0  4873.1     .16       0  4991.3     .07       0
  5019.1     .16       0  5172.1      .1       0  6282.1     .05       0
Bank Sta=4991.3,5019.1
XS Rating Curve= 0 ,0
Exp/Cntr=0.3,0.1

Type RM Length L Ch R = 1 ,93021   ,2021,2021,2021
BEGIN DESCRIPTION:
Mapping XS 76ce775b
END DESCRIPTION:
XS GIS Cut Line= 5
      1976918.98     13555778.02      1974411.43     13555501.48
      1974286.43     13554289.68      1973019.86     13553806.88
       1972842.9     13554180.31
#Sta/Elev= 30
  1933.6  608.14  2712.3  597.48  2923.8   593.3  2943.7  594.56  3205.2  589.96
  3698.2  584.98  3798.8  585.01  3969.9  588.07  4191.2  589.45  4696.2  589.12
  4754.4  589.22  4774.5  587.59  4915.3  585.08  4965.5  582.68  4971.7  578.69
  4976.7  577.89  4999.5  578.69  5045.6  583.51  5083.3  583.17    5444   583.1
  5692.6  580.95  5772.4  582.07  5901.1  581.69  6304.7  581.33  6406.4  581.48
    6486  584.22  6564.4  585.08  6789.1  585.08  7061.2  588.39  7443.3  589.45
#Mann= 9 ,-1 , 0
  1933.6     .05       0  4696.2      .1       0  4971.7     .07       0
  4999.5      .1       0  5045.6     .16       0  5083.3      .1       0
  5692.6     .05       0  5901.1      .1       0  6304.7     .05       0
Bank Sta=4971.7,4999.5
XS Rating Curve= 0 ,0
Exp/Cntr=0.3,0.1

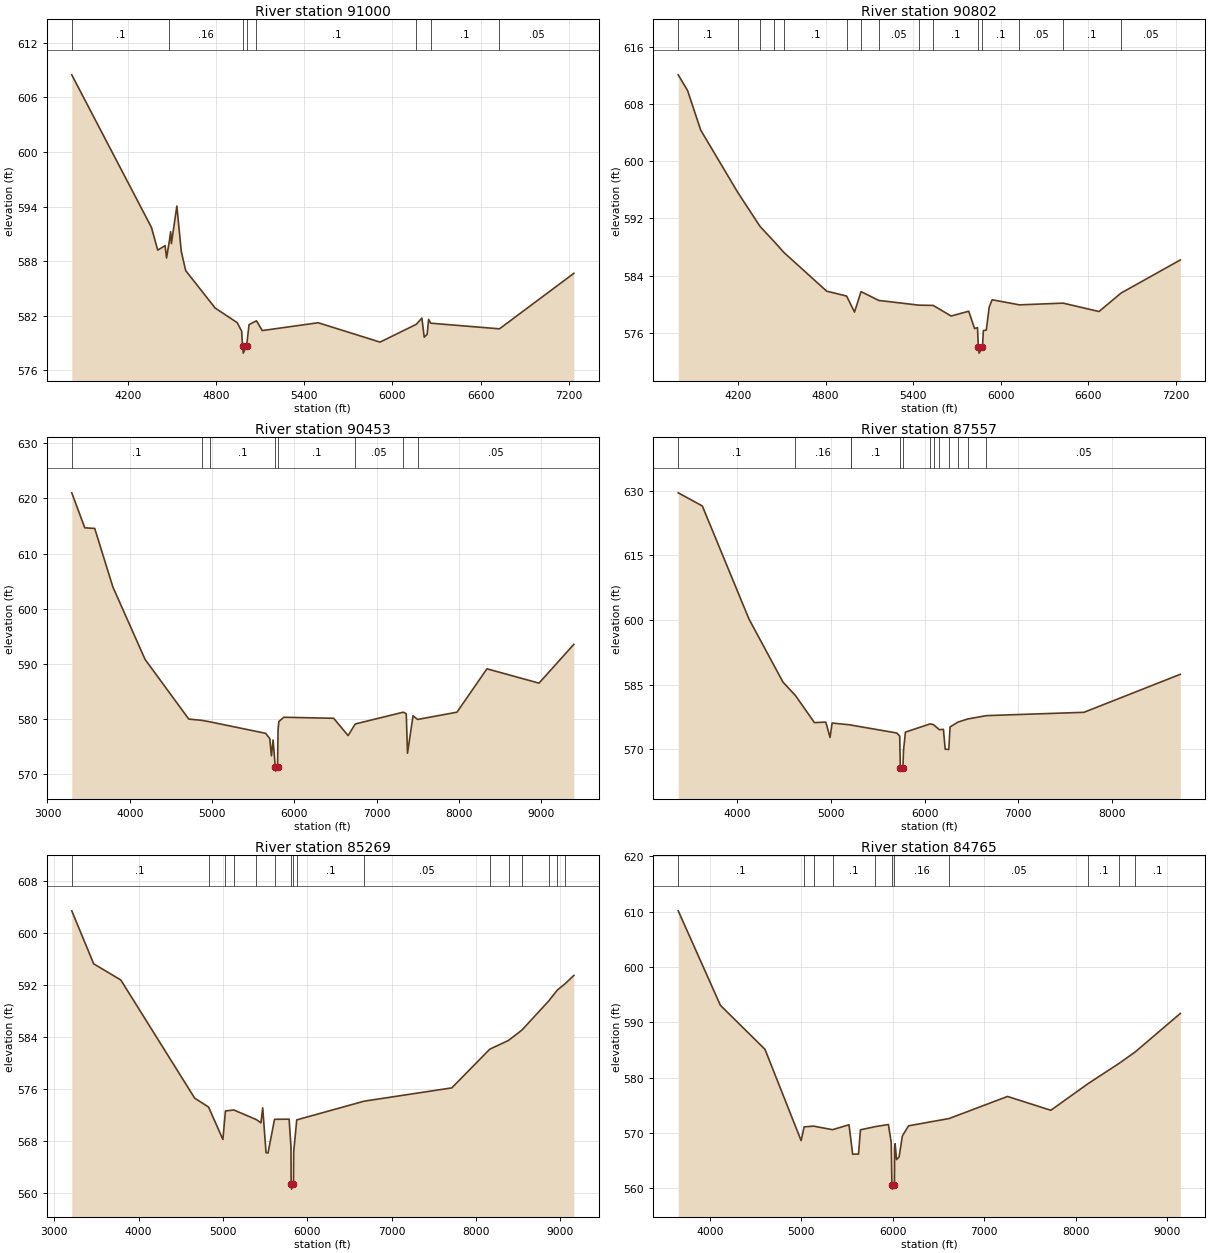
Type RM Length L Ch R = 1 ,91000   ,198,198,198
BEGIN DESCRIPTION:
Mapping XS 28013ef1
END DESCRIPTION:
XS GIS Cut Line= 2
      1976528.78     13553508.52       1973118.7     13553768.83
#Sta/Elev= 30
  3815.8  608.48  4358.5  591.71  4401.3  589.21  4451.4  589.71  4461.5  588.35
  4480.9  590.26  4489.4  591.24  4494.4  589.93  4531.7  594.06  4561.7  589.07
  4591.8  586.96  4792.4  582.85  4942.8  581.24  4972.9  580.31    4979  578.69
    4984  577.89    5007  578.69  5023.1  581.02  5074.1  581.44  5113.3  580.37
  5494.4  581.23  5915.7   579.1  6161.8  581.05  6200.8  581.74  6216.5  579.64
  6236.6  579.96  6246.6   581.6  6260.7  581.18  6729.2  580.56  7235.8  586.66
#Mann= 8 ,-1 , 0
  3815.8      .1       0  4480.9     .16       0    4979     .07       0
    5007     .16       0  5074.1      .1       0  6161.8     .05       0
  6260.7      .1       0  6729.2     .05       0
Bank Sta=4979,5007
XS Rating Curve= 0 ,0
Exp/Cntr=0.3,0.1

Type RM Length L Ch R = 1 ,90802   ,349,349,349
BEGIN DESCRIPTION:
Mapping XS e82a2d52
END DESCRIPTION:
XS GIS Cut Line= 2
       1976528.8     13553317.54        1973100.      13553560.6
#Sta/Elev= 30
  3791.2  612.05  3855.2  609.85  3945.4  604.32  4199.2  595.62    4351  590.89
  4449.9  588.72  4514.5  587.25  4807.5  581.84    4944  581.16    4998  578.92
  5042.8  581.78  5163.4  580.55  5438.1  579.89  5536.9  579.85  5659.6  578.37
    5780  579.04  5820.1  576.62  5840.1  576.75  5846.2  573.99  5851.2  573.19
  5874.2  573.99  5880.2  576.34  5900.3  576.41  5920.3  579.62  5940.4  580.64
  6127.5  579.93  6426.3  580.17  6672.2     579  6821.6  581.56  7228.6   586.2
#Mann= 15 ,-1 , 0
  3791.2      .1       0  4199.2     .05       0    4351     .08       0
  4449.9     .05       0  4514.5      .1       0    4944     .12       0
  5042.8      .1       0  5163.4     .05       0  5438.1     .08       0
  5536.9      .1       0  5846.2     .07       0  5874.2      .1       0
  6127.5     .05       0  6426.3      .1       0  6821.6     .05       0
Bank Sta=5846.2,5874.2
XS Rating Curve= 0 ,0
Exp/Cntr=0.3,0.1

Type RM Length L Ch R = 1 ,90453   ,2896,2896,2896
BEGIN DESCRIPTION:
Black Creek 85.0
END DESCRIPTION:
XS GIS Cut Line= 3
      1976962.86     13552918.23      1973924.63     13553178.65
      1970964.59     13552432.13
#Sta/Elev= 30
  3295.8  621.03  3454.2  614.67  3574.7  614.56  3795.5  603.92  4186.9  590.76
  4717.7  579.92  4874.6  579.69  4973.6  579.42  5652.3  577.33  5702.5  576.37
  5722.5  573.24  5742.6  576.12  5768.7  571.26  5773.7  570.46  5796.7  571.26
  5802.8  577.91  5812.9  579.47  5873.1  580.25  6478.9  580.06  6654.2  576.92
  6741.1  579.03  7325.1  581.17  7361.3  580.88  7376.1  573.71  7443.5  580.52
  7499.3  579.85  7977.4  581.17  8341.9  589.05  8974.6  586.45  9397.9   593.5
#Mann= 8 ,-1 , 0
  3295.8      .1       0  4874.6     .07       0  4973.6      .1       0
  5768.7     .07       0  5796.7      .1       0  6741.1     .05       0
  7325.1      .1       0  7499.3     .05       0
Bank Sta=5768.7,5796.7
XS Rating Curve= 0 ,0
Exp/Cntr=0.3,0.1

Type RM Length L Ch R = 1 ,87557   ,2288,2288,2288
BEGIN DESCRIPTION:
Black Creek 84.0
END DESCRIPTION:
XS GIS Cut Line= 3
      1976524.96     13550975.02      1974378.16     13551935.08
       1971411.6     13552442.89
#Sta/Elev= 30
  3369.8  629.55  3627.1   626.5  4125.6  600.22  4488.4  585.58  4621.8  582.46
  4824.2  576.18  4945.7  576.29    4991  572.73  5012.9  576.08  5214.1  575.64
  5216.1   575.6    5703  573.77  5734.8  573.06  5741.4  565.71  5746.4  564.91
  5769.4  565.71  5775.4  569.71  5795.7  573.97  6058.2  575.87  6095.7   575.7
  6158.6  574.53  6201.5  574.62  6220.8     570  6258.9  569.94  6272.6  575.18
  6359.2  576.32  6459.5  577.01  6660.2   577.8  7702.3  578.57  8731.2   587.4
#Mann= 13 ,-1 , 0
  3369.8      .1       0  4621.8     .16       0  5214.1     .12       0
  5216.1      .1       0  5741.4     .07       0  5769.4      .1       0
  6058.2     .12       0  6095.7      .1       0  6158.6     .07       0
  6258.9     .12       0  6359.2     .05       0  6459.5      .1       0
  6660.2     .05       0
Bank Sta=5741.4,5769.4
XS Rating Curve= 0 ,0
Exp/Cntr=0.3,0.1

Type RM Length L Ch R = 1 ,85269   ,504,504,504
BEGIN DESCRIPTION:
Black Creek 83.0
END DESCRIPTION:
XS GIS Cut Line= 3
      1976392.03     13550042.72       1974091.7     13550389.94
      1970923.25     13552152.11
#Sta/Elev= 30
  3208.7   603.4  3468.6  595.25  3790.4  592.76  4665.8  574.59  4830.5  573.22
  5000.2  568.24  5030.3  572.62  5130.3  572.77  5397.6  571.29  5450.8  570.79
  5472.3   573.1  5511.5  566.21  5535.1  566.15  5612.4  571.34  5785.4  571.36
  5807.2  567.11  5809.2   561.4  5814.2   560.6  5837.2   561.4  5839.2  566.26
  5875.6  571.25  6675.9  574.13  7713.6  576.17  8163.9  582.12  8386.2  583.47
  8545.2  585.06  8862.9  589.54  8965.7  591.23  9054.8  592.16  9160.6  593.47
#Mann= 16 ,-1 , 0
  3208.7      .1       0  4830.5     .07       0  5030.3     .12       0
  5130.3     .16       0  5397.6      .1       0  5612.4     .16       0
  5809.2     .07       0  5837.2     .16       0  5875.6      .1       0
  6675.9     .05       0  8163.9      .1       0  8386.2     .05       0
  8545.2      .1       0  8862.9     .05       0  8965.7      .1       0
  9054.8     .05       0
Bank Sta=5809.2,5837.2
XS Rating Curve= 0 ,0
Exp/Cntr=0.3,0.1

Type RM Length L Ch R = 1 ,84765   ,2604,2604,2604
BEGIN DESCRIPTION:
Black Creek 82.0
END DESCRIPTION:
XS GIS Cut Line= 3
      1975827.82     13549504.52      1974004.89     13550034.04
      1970942.83     13551909.03
#Sta/Elev= 30
  3654.8  610.15  4115.9  593.06  4603.3   585.1  4998.4  568.59  5031.4  571.08
  5134.8  571.21  5341.5  570.57  5521.7  571.46  5561.7  566.13  5625.6  566.16
  5646.9  570.55  5804.9  571.11  5952.5  571.51  5983.4   568.2  5990.7  560.62
  5995.7  559.82  6018.7  560.62  6020.1  567.27    6026  568.03  6041.4  565.16
  6068.9  565.62  6105.3  569.44  6172.9  571.27    6617  572.59  7254.4  576.58
  7728.2  574.08  8134.6  578.89    8478   582.6  8649.7  584.62  9143.6  591.59
#Mann= 11 ,-1 , 0
  3654.8      .1       0  5031.4     .12       0  5134.8     .16       0
  5341.5      .1       0  5804.9     .16       0  5990.7     .07       0
  6018.7     .16       0    6617     .05       0  8134.6      .1       0
    8478     .05       0  8649.7      .1       0
Bank Sta=5990.7,6018.7
XS Rating Curve= 0 ,0
Exp/Cntr=0.3,0.1

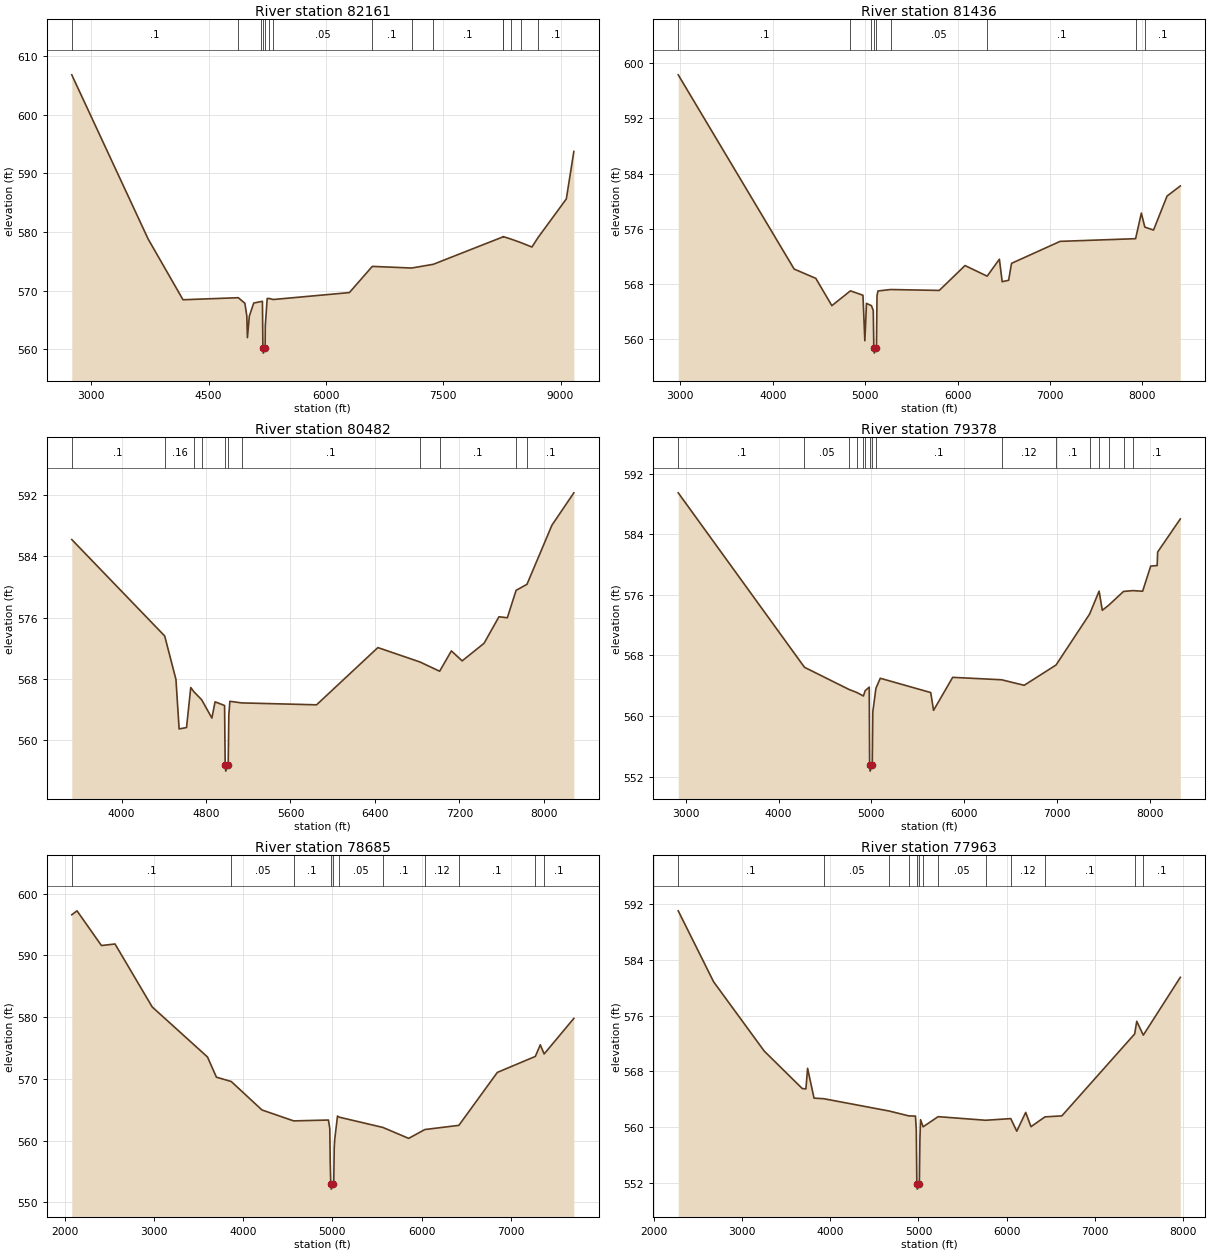
Type RM Length L Ch R = 1 ,82161   ,725,725,725
BEGIN DESCRIPTION:
Black Creek 81.0
END DESCRIPTION:
XS GIS Cut Line= 3
      1975324.98     13548425.01        1973325.       13549425.
        1969185.     13550034.04
#Sta/Elev= 30
  2749.6  606.82  3725.1  578.86  4172.3  568.47  4879.4  568.82  4963.3  567.87
  4988.2  565.72  4995.8  562.01  5020.5  565.69  5076.6  567.91  5169.9  568.16
  5187.8   568.2    5194  560.17    5199  559.37    5222  560.17  5224.6  564.05
  5248.4  568.68  5269.8   568.7  5325.1  568.51  6299.6  569.69  6592.7  574.16
  7096.1  573.88  7371.9  574.51    8266   579.2  8266.4  579.24  8365.9  578.82
  8495.6   578.2  8634.5  577.46  8710.6  579.04    9074  585.66  9170.2  593.75
#Mann= 15 ,-1 , 0
  2749.6      .1       0  4879.4     .12       0  5169.9     .07       0
    5194     .07       0    5222     .07       0  5269.8      .1       0
  5325.1     .05       0  6592.7      .1       0  7096.1     .05       0
  7371.9      .1       0    8266     .08       0  8266.4     .05       0
  8365.9      .1       0  8495.6     .12       0  8710.6      .1       0
Bank Sta=5194,5222
XS Rating Curve= 0 ,0
Exp/Cntr=0.3,0.1

Type RM Length L Ch R = 1 ,81436   ,954,954,954
BEGIN DESCRIPTION:
Black Creek 80.0
END DESCRIPTION:
XS GIS Cut Line= 3
        1974975.       13548525.        1972975.       13548925.
      1969618.25     13549420.92
#Sta/Elev= 30
  2976.5  598.33  4230.9  570.14  4465.4  568.79  4638.8  564.83  4839.9  566.98
  4975.3  566.34  4995.7  559.73  5013.6  565.16  5066.8  564.83  5086.9  564.13
  5092.9  558.74    5098  557.94  5121.3  558.74  5127.3  566.27  5137.4  566.96
    5275  567.17  5801.2  567.04  6079.6  570.65  6319.2  569.11  6451.5  571.57
  6481.9  568.31  6551.6  568.51  6582.9  570.97  7108.6  574.16  7925.4  574.55
  7987.7  578.26  8025.3  576.23  8119.4   575.8  8266.1  580.74  8409.3   582.2
#Mann= 9 ,-1 , 0
  2976.5      .1       0  4839.9     .16       0  5066.8      .1       0
  5092.9     .07       0  5121.3      .1       0    5275     .05       0
  6319.2      .1       0  7925.4     .08       0  8025.3      .1       0
Bank Sta=5092.9,5121.3
XS Rating Curve= 0 ,0
Exp/Cntr=0.3,0.1

Type RM Length L Ch R = 1 ,80482   ,1104,1104,1104
BEGIN DESCRIPTION:
Black Creek 79.0
END DESCRIPTION:
XS GIS Cut Line= 3
       1974130.8     13548188.55      1972408.54     13548257.99
      1969484.92     13549056.61
#Sta/Elev= 30
  3528.8  586.15  4408.7   573.6  4515.4  567.94  4545.4   561.5  4615.5  561.68
  4655.5  566.89  4687.3  566.31  4758.9   565.3  4855.7  562.92  4885.7  565.03
  4975.8  564.55  4981.6  556.81  4986.7  556.01    5010  556.81  5015.8  563.27
  5025.8   565.1  5136.1  564.89    5847  564.64  6427.5  572.09  6827.1  570.21
  7012.4  569.01  7123.4  571.66  7225.7  570.36  7433.1  572.65    7574   576.1
  7653.4  575.97  7736.4  579.54  7839.2  580.32  8075.8  588.02  8283.2  592.23
#Mann= 11 ,-1 , 0
  3528.8      .1       0  4408.7     .16       0  4687.3      .1       0
  4758.9     .16       0  4981.6     .07       0    5010     .16       0
  5136.1      .1       0  6827.1     .12       0  7012.4      .1       0
  7736.4     .08       0  7839.2      .1       0
Bank Sta=4981.6,5010
XS Rating Curve= 0 ,0
Exp/Cntr=0.3,0.1

Type RM Length L Ch R = 1 ,79378   ,693,693,693
BEGIN DESCRIPTION:
Black Creek 78.0
END DESCRIPTION:
XS GIS Cut Line= 4
      1974325.03     13548075.01      1972700.21     13547480.22
      1971116.87     13547674.66      1969096.05     13548202.44
#Sta/Elev= 30
  2917.7  589.49    4279  566.44  4757.8  563.52  4841.9  563.12  4914.5  562.65
  4933.5  563.35  4977.5  563.82  4981.6  553.52  4986.7  552.72    5010  553.52
  5015.9  560.55  5049.4  563.67  5096.5  564.99  5640.6   563.1  5670.8  560.75
  5877.1  565.11    6405  564.79  6648.2  564.06  6991.7  566.74  7353.6  573.47
  7456.1   576.5  7490.8  573.97  7558.6  574.63  7719.4  576.46  7820.5  576.57
  7925.5  576.49  8012.5  579.81  8082.2  579.88  8087.4  581.67  8331.8  586.04
#Mann= 16 ,-1 , 0
  2917.7      .1       0    4279     .05       0  4757.8      .1       0
  4841.9     .16       0  4914.5     .12       0  4933.5     .16       0
  4981.6     .07       0    5010     .16       0  5049.4      .1       0
    6405     .12       0  6991.7      .1       0  7353.6     .08       0
  7456.1     .05       0  7558.6      .1       0  7719.4     .12       0
  7820.5      .1       0
Bank Sta=4981.6,5010
XS Rating Curve= 0 ,0
Exp/Cntr=0.3,0.1

Type RM Length L Ch R = 1 ,78685   ,722,722,722
BEGIN DESCRIPTION:
Black Creek 77.0
END DESCRIPTION:
XS GIS Cut Line= 4
      1975103.01     13547535.78      1973602.98     13547271.88
      1971915.48     13546917.72      1969540.52     13547153.82
#Sta/Elev= 30
  2075.4  596.59  2134.3  597.23  2408.4  591.61  2560.8  591.86  2978.3  581.66
  3598.5  573.56  3698.6  570.29  3864.9  569.59  4209.5  564.98  4565.4  563.21
  4955.4  563.35  4970.8  561.99  4975.9  556.34  4982.1  552.96  4987.2  552.16
  5010.5  552.96  5015.5  553.46  5020.6  558.91  5026.9  560.33  5057.6     564
  5075.4  563.82  5566.5  562.15    5856  560.38  6037.2  561.81  6419.4  562.49
  6850.7  571.06    7277  573.65  7333.1  575.53  7376.2  574.05  7709.4  579.81
#Mann= 11 ,-1 , 0
  2075.4      .1       0  3864.9     .05       0  4565.4      .1       0
  4982.1     .07       0  5010.5      .1       0  5075.4     .05       0
  5566.5      .1       0  6037.2     .12       0  6419.4      .1       0
    7277     .05       0  7376.2      .1       0
Bank Sta=4982.1,5010.5
XS Rating Curve= 0 ,0
Exp/Cntr=0.3,0.1

Type RM Length L Ch R = 1 ,77963   ,615,615,615
BEGIN DESCRIPTION:
Black Creek 76.0
END DESCRIPTION:
XS GIS Cut Line= 3
      1975005.79     13547008.87        1972325.       13546375.
      1969380.81     13546253.66
#Sta/Elev= 30
  2271.8  591.06  2673.4  580.86  3248.8  570.89  3680.4  565.51  3721.5  565.46
  3740.7  568.42    3814  564.13  3923.9  564.05  4666.5  562.28  4889.7  561.58
  4965.7  561.55  4975.1  559.55  4981.4  551.85  4986.6  551.05  5009.9  551.85
  5016.2  558.24  5023.9  561.03  5052.5  560.01  5223.4  561.47  5762.7  560.95
    6048  561.19  6115.9  559.38  6217.5  562.08  6277.6  560.03  6436.8  561.44
  6627.9  561.58  7454.8  573.36  7478.6  575.18  7553.1  573.19  7973.2   581.5
#Mann= 13 ,-1 , 0
  2271.8      .1       0  3923.9     .05       0  4666.5      .1       0
  4889.7     .16       0  4981.4     .07       0  5009.9     .16       0
  5052.5      .1       0  5223.4     .05       0  5762.7      .1       0
    6048     .12       0  6436.8      .1       0  7454.8     .05       0
  7553.1      .1       0
Bank Sta=4981.4,5009.9
XS Rating Curve= 0 ,0
Exp/Cntr=0.3,0.1

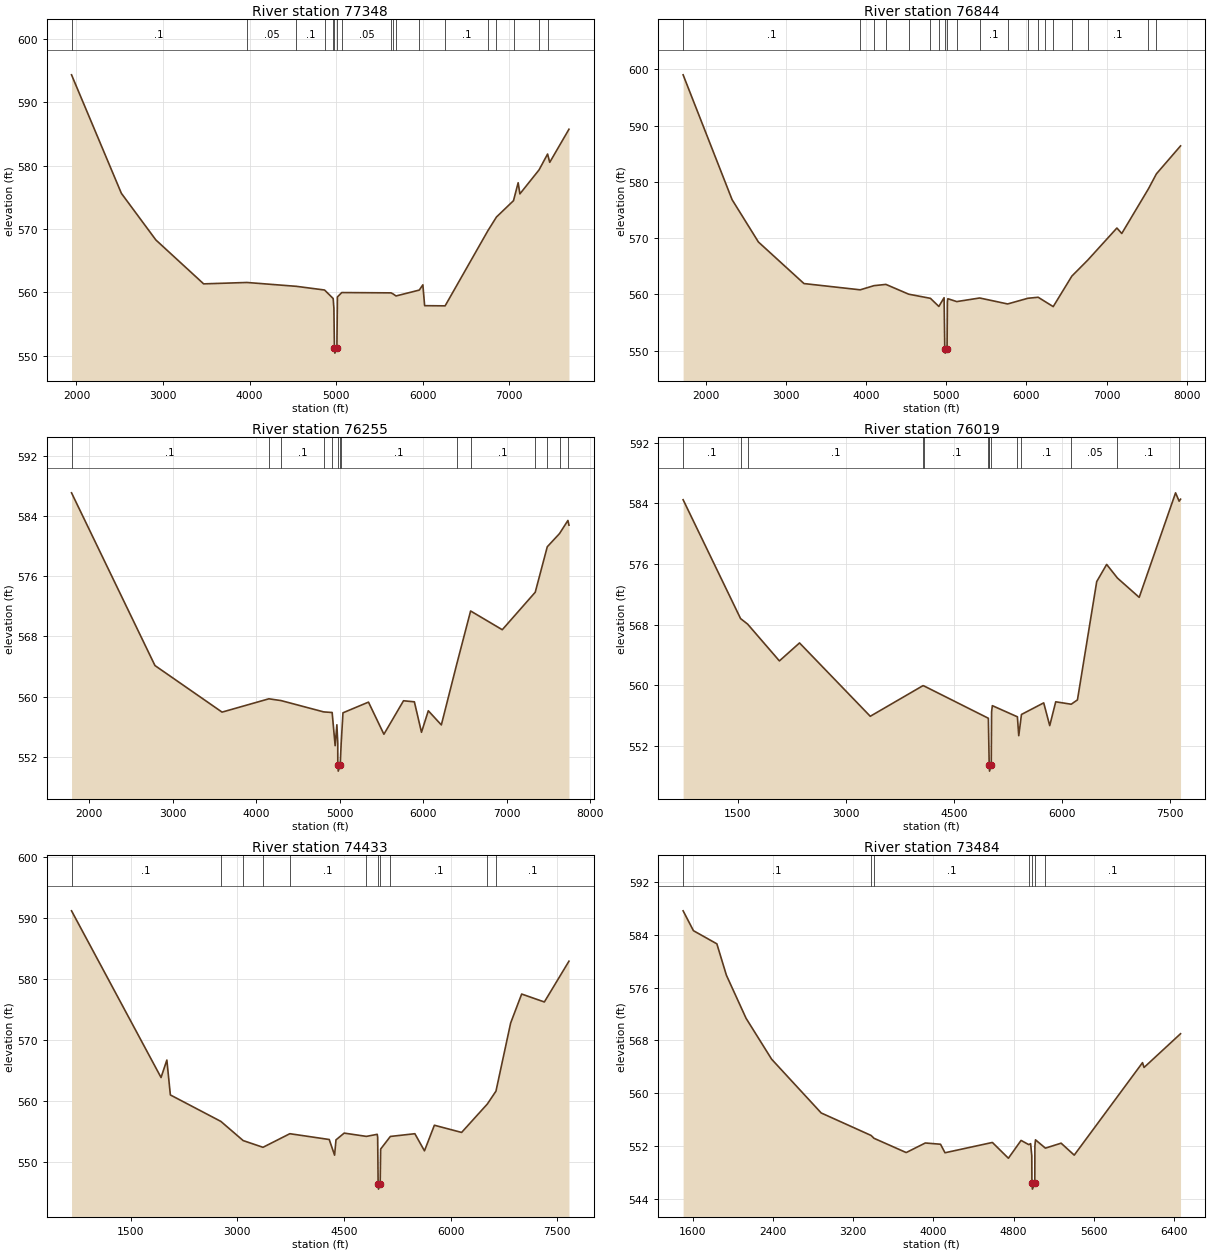
Type RM Length L Ch R = 1 ,77348   ,504,504,504
BEGIN DESCRIPTION:
Black Creek 75.0
END DESCRIPTION:
XS GIS Cut Line= 4
      1975057.88      13546913.4       1973469.3       13546054.
      1970778.33     13545541.85      1969580.45       13545429.
#Sta/Elev= 30
  1943.3  594.33  2519.3  575.63  2917.9  568.27  3470.1  561.34  3970.3  561.56
  4542.8  560.95  4867.4  560.37  4966.9  559.03  4975.4   557.5  4981.5  551.21
  4986.6  550.41    5010  551.21  5016.1  559.28  5066.4  559.97  5635.7  559.92
  5659.9  559.75  5692.8  559.43  5962.1  560.36  6003.5  561.19  6023.9   557.9
  6260.7  557.87  6755.5  569.74    6854  571.89    7051  574.47  7104.8   577.3
  7124.9  575.54  7346.4  579.33  7444.9  581.83  7469.7  580.52  7691.9  585.74
#Mann= 18 ,-1 , 0
  1943.3      .1       0  3970.3     .05       0  4542.8      .1       0
  4867.4     .16       0  4966.9     .07       0  4981.5     .07       0
    5010     .07       0  5066.4     .05       0  5635.7      .1       0
  5659.9     .05       0  5692.8      .1       0  5962.1     .05       0
  6260.7      .1       0  6755.5     .08       0    6854     .05       0
    7051      .1       0  7346.4     .08       0  7444.9      .1       0
Bank Sta=4981.5,5010
XS Rating Curve= 0 ,0
Exp/Cntr=0.3,0.1

Type RM Length L Ch R = 1 ,76844   ,589,589,589
BEGIN DESCRIPTION:
Black Creek 74.0
END DESCRIPTION:
XS GIS Cut Line= 4
      1975248.82     13546783.17      1973938.05     13546036.64
      1971741.87     13545125.18      1969450.18     13544777.95
#Sta/Elev= 30
  1718.9     599  2329.5  576.84    2658  569.32  3226.2  561.94  3927.6  560.83
  4099.7  561.57  4248.3  561.79  4533.1  560.05  4803.4  559.32  4908.5  557.88
  4973.8  559.43  4982.5  550.39  4987.6  549.59    5011  550.39  5015.2  558.67
  5020.6  559.25  5131.7  558.74  5417.6  559.38  5766.6  558.32  6019.3  559.33
  6147.4  559.51    6236  558.72    6335  557.85  6567.1  563.26  6766.1  566.11
  7129.2   571.8  7189.9  570.83    7523  578.77    7622  581.42    7923  586.38
#Mann= 20 ,-1 , 0
  1718.9      .1       0  3927.6     .05       0  4099.7      .1       0
  4248.3     .05       0  4533.1      .1       0  4803.4     .07       0
  4908.5     .16       0  4982.5     .07       0    5011     .16       0
  5131.7     .05       0  5417.6      .1       0  5766.6     .05       0
  6019.3      .1       0  6147.4     .12       0    6236     .07       0
    6335      .1       0  6567.1     .05       0  6766.1      .1       0
    7523     .08       0    7622      .1       0
Bank Sta=4982.5,5011
XS Rating Curve= 0 ,0
Exp/Cntr=0.3,0.1

Type RM Length L Ch R = 1 ,76255   ,236,236,236
BEGIN DESCRIPTION:
Black Creek 73.0
END DESCRIPTION:
XS GIS Cut Line= 4
      1975319.99     13546218.93      1972872.08     13545003.65
      1971144.65      13544491.5       1969755.8     13544179.01
#Sta/Elev= 30
  1785.9  587.09  2785.1  564.14    3589  557.95    4150  559.72    4297  559.48
    4806  557.98  4907.6   557.9  4943.5  553.49  4964.3  556.27  4974.8  553.86
  4975.5  550.91  4980.6  550.11    5004  550.91  5015.7  553.78  5037.3  557.86
  5342.9  559.28  5527.6  555.01  5762.6  559.46  5892.6  559.32  5977.7  555.27
  6059.5  558.13  6215.6  556.25  6399.5   564.3  6566.2  571.39  6945.5   568.9
  7340.3  573.88  7484.4  579.92  7631.6  581.68  7731.7  583.42  7744.2  582.79
#Mann= 14 ,-1 , 0
  1785.9      .1       0    4150     .05       0    4297      .1       0
    4806     .07       0  4907.6     .12       0  4975.5     .07       0
    5004     .12       0  5015.7      .1       0  6399.5     .05       0
  6566.2      .1       0  7340.3     .05       0  7484.4      .1       0
  7631.6     .08       0  7731.7     .05       0
Bank Sta=4975.5,5004
XS Rating Curve= 0 ,0
Exp/Cntr=0.3,0.1

Type RM Length L Ch R = 1 ,76019   ,1586,1586,1586
BEGIN DESCRIPTION:
Black Creek 72.0
END DESCRIPTION:
XS GIS Cut Line= 3
      1976509.24     13545715.46      1971747.08     13544484.56
      1969838.72     13543943.28
#Sta/Elev= 30
   741.2  584.47  1538.4   568.8  1636.5  568.07  2077.2  563.22  2356.5  565.59
  3338.1  555.92  4069.9  559.96  4089.7  559.89  4976.7  555.66  4987.3  550.13
  4988.2  549.49  4993.3  548.69  5016.7  549.49  5021.6  556.49    5032  557.32
  5379.8  555.85  5398.5  553.36  5436.1  556.16  5744.9  557.69  5828.3  554.69
  5911.5  557.83  6126.4  557.51  6212.9  558.08  6480.4  573.68  6618.3  575.94
  6768.2  574.14  7069.8   571.6  7574.6  585.38    7624  584.28  7643.5  584.54
#Mann= 14 ,-1 , 0
   741.2      .1       0  1538.4     .07       0  1636.5      .1       0
  4069.9     .05       0  4089.7      .1       0  4976.7     .05       0
  4987.3      .1       0  4988.2     .07       0  5016.7      .1       0
  5379.8     .05       0  5436.1      .1       0  6126.4     .05       0
  6768.2      .1       0    7624     .08       0
Bank Sta=4988.2,5016.7
XS Rating Curve= 0 ,0
Exp/Cntr=0.3,0.1

Type RM Length L Ch R = 1 ,74433   ,949,949,949
BEGIN DESCRIPTION:
Black Creek 71.0
END DESCRIPTION:
XS GIS Cut Line= 4
      1976335.65     13545281.44       1973633.8     13543816.59
      1971691.53     13543208.95      1969922.86     13543881.69
#Sta/Elev= 30
   666.1  591.22  1925.9  563.88  2007.7  566.74  2057.1  561.02  2767.7  556.68
    3082  553.53  3360.8  552.43  3738.7  554.66  4292.9  553.71  4368.3  551.14
  4387.9  553.65  4503.4  554.76    4816  554.22  4968.3  554.56  4974.6   554.1
  4981.2  546.47  4986.4  545.57  5009.9  546.47  5016.6  552.14  5153.2  554.21
  5498.2  554.66  5633.3  551.85  5772.8  556.05  6156.1  554.87    6518  559.53
  6639.6  561.64  6846.3  572.82  7001.3  577.57  7320.7  576.27  7666.9  582.96
#Mann= 11 ,-1 , 0
   666.1      .1       0  2767.7     .05       0    3082      .1       0
  3360.8     .05       0  3738.7      .1       0    4816     .16       0
  4981.2     .07       0  5009.9     .16       0  5153.2      .1       0
    6518     .05       0  6639.6      .1       0
Bank Sta=4981.2,5009.9
XS Rating Curve= 0 ,0
Exp/Cntr=0.3,0.1

Type RM Length L Ch R = 1 ,73484   ,730,730,730
BEGIN DESCRIPTION:
Black Creek 70.0
END DESCRIPTION:
XS GIS Cut Line= 3
      1975925.02     13544525.01        1972925.       13542725.
      1971690.11     13541947.41
#Sta/Elev= 30
  1505.3  587.62  1608.3  584.61  1841.6  582.62  1936.8  577.86  2133.1  571.33
  2387.7  565.14  2881.4     557    3379  553.59  3408.1  553.16  3728.9     551
  3919.3  552.45  4070.9  552.26  4115.6  550.97  4587.9  552.53  4747.3  550.14
  4873.7  552.84  4950.6   552.2  4968.9  552.35  4980.6  550.52  4981.8  546.36
  4986.9  545.46  5010.5  546.36  5011.5  552.01  5017.4  552.93  5116.3  551.67
  5272.9  552.42  5403.6  550.61  6084.1  564.62  6099.4  563.89  6463.2     569
#Mann= 7 ,-1 , 0
  1505.3      .1       0    3379     .05       0  3408.1      .1       0
  4950.6     .16       0  4981.8     .07       0  5010.5     .16       0
  5116.3      .1       0
Bank Sta=4981.8,5010.5
XS Rating Curve= 0 ,0
Exp/Cntr=0.3,0.1

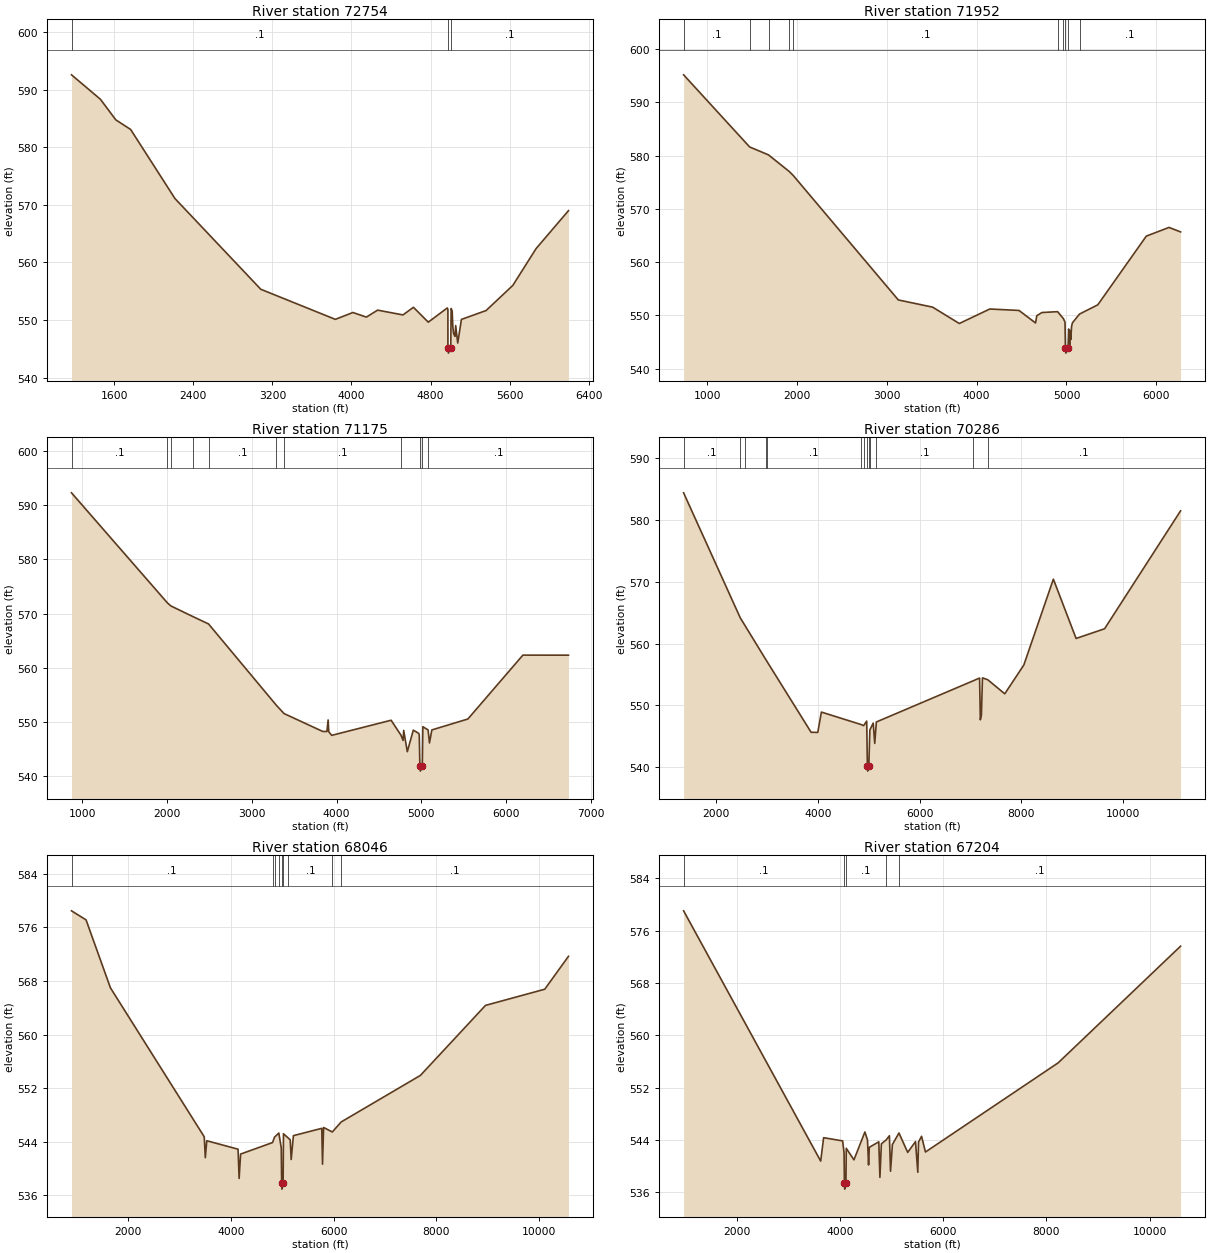
Type RM Length L Ch R = 1 ,72754   ,802,802,802
BEGIN DESCRIPTION:
Black Creek 69.0
END DESCRIPTION:
XS GIS Cut Line= 3
      1976225.03     13544625.02        1973225.       13542225.
      1972284.77      13541506.9
#Sta/Elev= 30
    1169  592.55  1461.2  588.31  1617.3  584.73  1766.9  583.07  2215.1  571.08
  3082.8  555.34  3836.7  550.12  4014.4  551.31  4150.5  550.51  4264.1  551.72
  4520.3  550.89  4626.7  552.21  4776.4  549.63  4968.5   552.1  4974.9  551.82
    4975  545.16  4980.1  544.26  5003.7  545.16  5007.7     552  5018.2  551.55
  5024.5  548.85  5032.7  547.64  5047.2  547.17  5053.5  549.04  5074.3  546.01
  5111.6  550.11    5361  551.65  5631.3  556.01  5866.6   562.4    6194  568.98
#Mann= 3 ,-1 , 0
    1169      .1       0    4975     .07       0  5003.7      .1       0
Bank Sta=4975,5003.7
XS Rating Curve= 0 ,0
Exp/Cntr=0.3,0.1

Type RM Length L Ch R = 1 ,71952   ,777,777,777
BEGIN DESCRIPTION:
Black Creek 68.0
END DESCRIPTION:
XS GIS Cut Line= 3
      1976475.04     13544675.04        1973475.       13541675.
       1972288.4     13541171.24
#Sta/Elev= 30
   738.5  595.16  1473.8  581.62  1683.8  580.13  1915.6     577  1959.3  576.26
  3128.6  552.91  3510.4  551.56  3807.4  548.49  4146.8  551.21  4472.1  550.94
  4655.9  548.59  4670.1  549.96  4726.6  550.55  4901.4  550.71  4966.4   549.4
  4983.9  548.75  4988.6  543.83  4993.7  542.93  5017.3  543.83  5024.8  547.46
  5035.5  544.47  5043.1  547.16  5048.5  545.49  5057.2  547.96  5066.7  548.62
  5145.4  550.26  5348.7  551.99    5889  564.89  6141.9  566.52  6270.3  565.68
#Mann= 10 ,-1 , 0
   738.5      .1       0  1473.8     .05       0  1683.8      .1       0
  1915.6     .05       0  1959.3      .1       0  4901.4     .07       0
  4966.4     .12       0  4988.6     .07       0  5017.3     .12       0
  5145.4      .1       0
Bank Sta=4988.6,5017.3
XS Rating Curve= 0 ,0
Exp/Cntr=0.3,0.1

Type RM Length L Ch R = 1 ,71175   ,889,889,889
BEGIN DESCRIPTION:
Black Creek 67.0
END DESCRIPTION:
XS GIS Cut Line= 3
      1976675.01     13544275.01      1973696.28     13541057.68
      1972218.55     13540967.49
#Sta/Elev= 30
   871.2  592.31  2002.2  571.99  2044.6  571.41  2299.7  569.48  2488.3  568.09
  3289.6  553.05  3379.8  551.53  3836.2  548.23  3885.6  548.22  3899.7  550.35
  3907.1  548.17  3942.3  547.51    4643   550.3  4759.4  547.54  4784.2  546.57
  4791.6  548.42  4834.1  544.49    4905  548.47  4968.5  547.88  4975.3  547.59
  4982.5   541.8  4987.6   540.9  5011.2   541.8  5017.8   549.1  5079.5  548.51
  5095.8  546.11  5123.8  548.51  5549.2  550.53  6198.1  562.33  6736.2  562.32
#Mann= 11 ,-1 , 0
   871.2      .1       0  2002.2     .05       0  2044.6      .1       0
  2299.7     .05       0  2488.3      .1       0  3289.6     .05       0
  3379.8      .1       0  4759.4     .12       0  4982.5     .07       0
  5011.2     .12       0  5079.5      .1       0
Bank Sta=4982.5,5011.2
XS Rating Curve= 0 ,0
Exp/Cntr=0.3,0.1

Type RM Length L Ch R = 1 ,70286   ,2240,2240,2240
BEGIN DESCRIPTION:
Black Creek 66.0
END DESCRIPTION:
XS GIS Cut Line= 3
        1976525.       13543725.        1974425.       13540725.
      1969424.96     13537224.97
#Sta/Elev= 30
  1363.4  584.43  2476.2   564.2  2574.3  562.88  2976.9  557.46  3011.4     557
  3868.8  545.66  3999.6  545.64  4071.1  548.93  4841.3  546.94  4901.6  546.74
  4961.3  547.47  4974.4  540.27  4979.6  539.37  5003.2  540.27    5023  546.03
  5089.5  547.15  5119.1  543.86  5151.2  547.33  7055.4     554  7179.4  554.44
  7194.2  547.68  7215.1  548.48  7236.1  554.47  7339.3  554.17  7674.2  551.89
  8048.7  556.55  8629.4  570.45  9075.8  560.85  9635.5  562.42 11128.7  581.51
#Mann= 13 ,-1 , 0
  1363.4      .1       0  2476.2     .05       0  2574.3      .1       0
  2976.9     .05       0  3011.4      .1       0  4841.3     .12       0
  4901.6     .16       0  4974.4     .07       0  5003.2     .16       0
    5023     .12       0  5151.2      .1       0  7055.4     .12       0
  7339.3      .1       0
Bank Sta=4974.4,5003.2
XS Rating Curve= 0 ,0
Exp/Cntr=0.3,0.1

Type RM Length L Ch R = 1 ,68046   ,842,842,842
BEGIN DESCRIPTION:
Black Creek 65.0
END DESCRIPTION:
XS GIS Cut Line= 5
      1978275.02     13542675.02       1975477.8     13540011.37
       1974880.6      13539777.8      1974210.44     13539286.54
      1970275.02     13537475.01
#Sta/Elev= 30
   902.9  578.47  1185.9  577.12  1659.9  566.98  3484.8  544.75  3505.9  541.63
  3534.2  544.16  4142.5   542.9  4163.5  538.54  4191.9  542.17  4813.4  543.89
  4851.5  544.69  4935.8  545.31  4983.2  543.08  4990.3  537.84  4995.5  536.94
  5019.1  537.84  5026.2   545.2  5121.1  544.55    5157  544.31  5176.1  541.36
  5219.5  544.92  5771.1  546.01  5785.6  540.67  5806.6  546.14  5976.3  545.47
  6147.8  546.96  7689.8  553.91  8956.5  564.36 10108.4  566.77   10570  571.68
#Mann= 9 ,-1 , 0
   902.9      .1       0  4813.4     .12       0  4851.5      .1       0
  4935.8     .12       0  4990.3     .07       0  5019.1     .12       0
  5121.1      .1       0  5976.3     .12       0  6147.8      .1       0
Bank Sta=4990.3,5019.1
XS Rating Curve= 0 ,0
Exp/Cntr=0.3,0.1

Type RM Length L Ch R = 1 ,67204   ,1617,1617,1617
BEGIN DESCRIPTION:
Black Creek 64.0
END DESCRIPTION:
XS GIS Cut Line= 3
      1978274.99     13542624.99        1975575.       13539625.
      1970575.03     13537125.02
#Sta/Elev= 30
   972.6  579.05  3627.8  540.75  3684.6  544.33  4053.1  543.84  4080.7  542.02
    4088  537.36  4093.2  536.46  4116.8  537.36  4123.3  542.71  4272.1  540.94
  4484.4  545.21  4534.4  543.98  4555.4  540.16  4569.6  542.86  4753.4   543.7
  4775.1  538.26  4803.5  543.39  4896.1  543.99    4959  544.63  4980.6   539.2
  5017.1  543.29  5144.2  545.05  5313.3  542.08  5464.3  543.73    5509  539.04
    5523  543.66  5581.7  544.55  5657.1  542.14  8228.6  555.79 10598.8  573.64
#Mann= 5 ,-1 , 0
   972.6      .1       0    4088     .07       0  4116.8      .1       0
  4896.1     .12       0  5144.2      .1       0
Bank Sta=4088,4116.8
XS Rating Curve= 0 ,0
Exp/Cntr=0.3,0.1