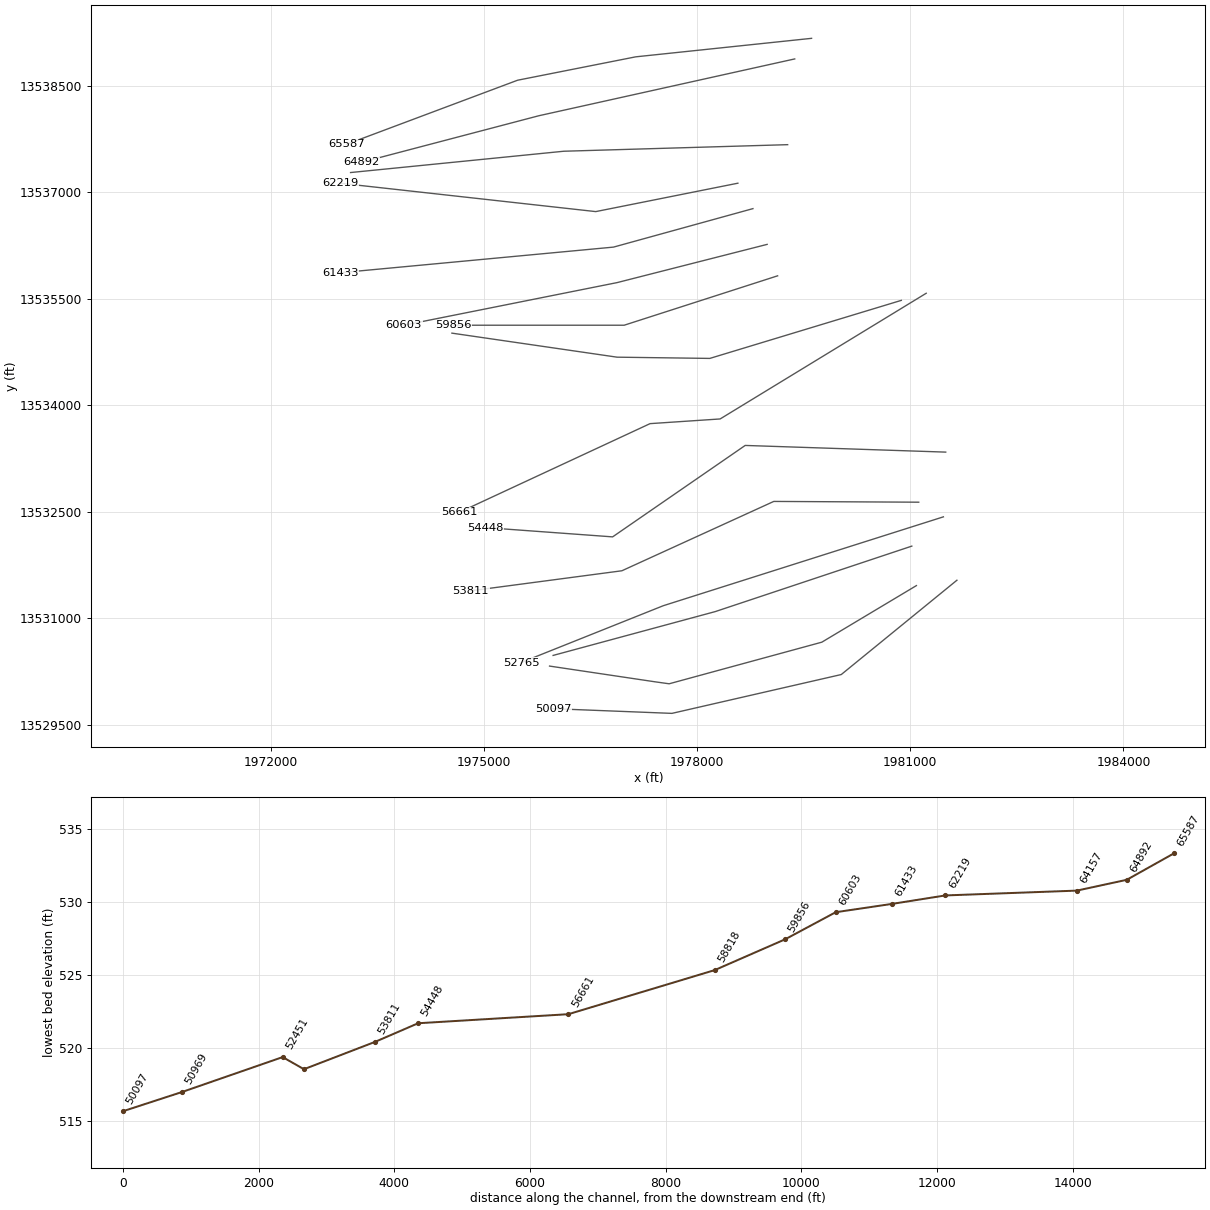
HEC-RAS study Black Creek.prj: Black Creek Base Level Engineering

--- Black Creek.g01 (geometry) --- (continued)

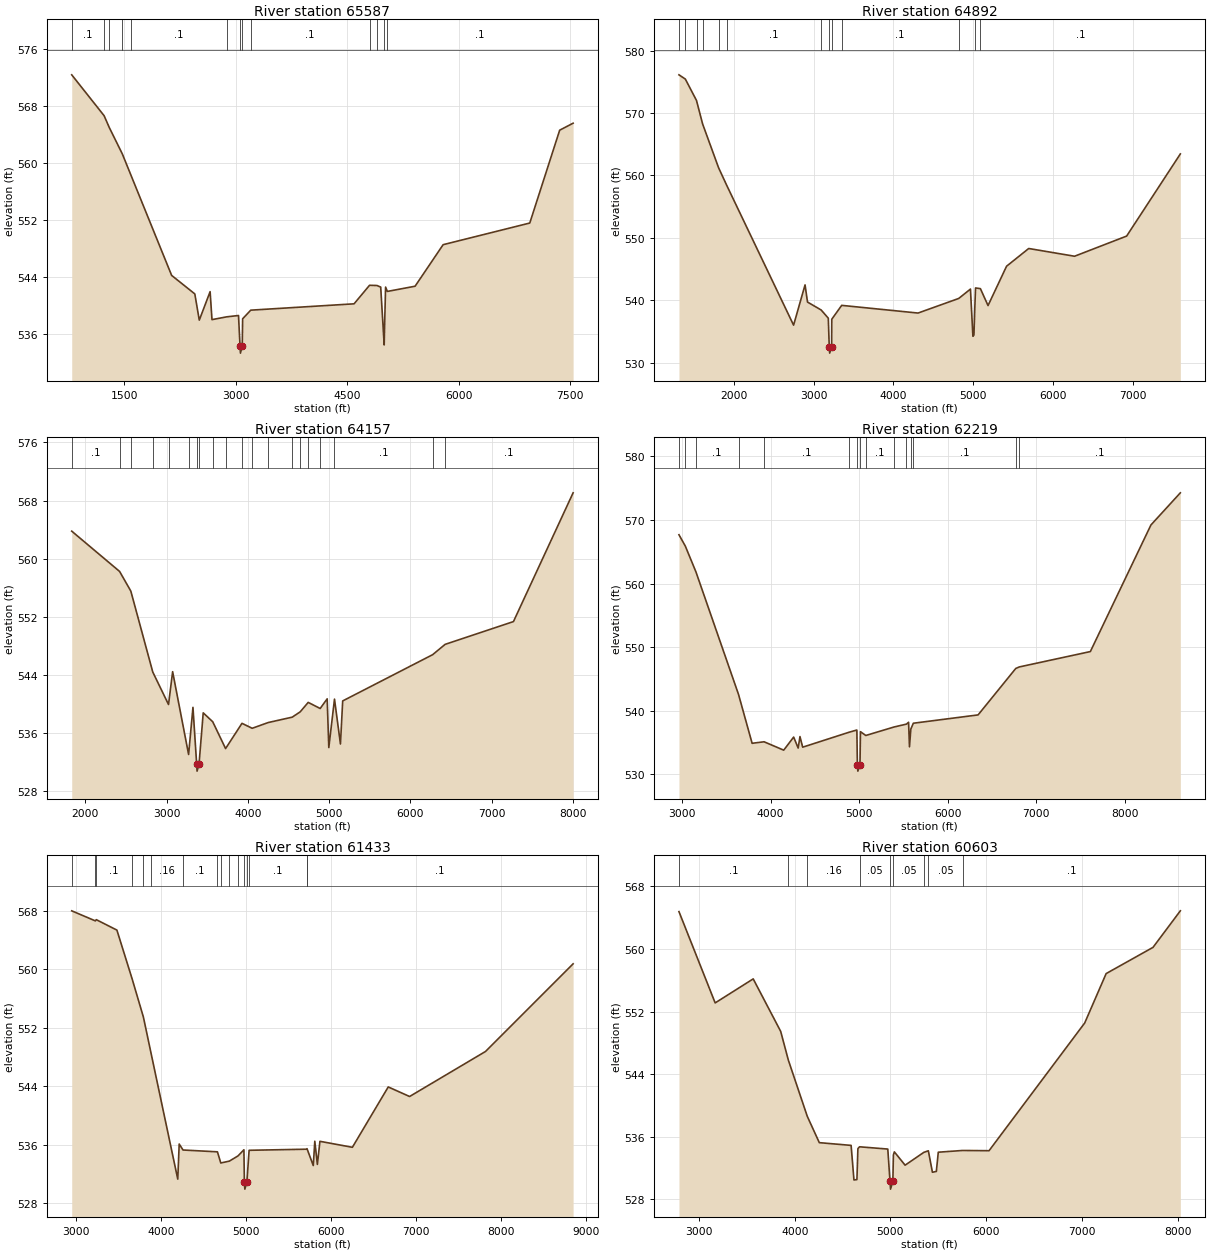
Type RM Length L Ch R = 1 ,65587   ,695,695,695
BEGIN DESCRIPTION:
Black Creek 63.0
END DESCRIPTION:
XS GIS Cut Line= 4
      1979611.86     13539164.89      1977137.85     13538904.47
        1975475.       13538575.      1973074.96     13537674.98
#Sta/Elev= 30
   791.3  572.41  1226.5  566.68  1297.7  564.99  1471.6  561.32  1585.6  558.39
  2135.5  544.26  2447.3  541.66  2507.6  537.98  2653.2  541.98  2678.5  538.05
  2874.2  538.44  3035.3  538.63  3055.9  534.35  3061.3  533.35  3085.5  534.35
  3090.8  538.17    3200  539.38  4590.1  540.27  4798.2  542.87  4897.9  542.84
  4948.5  542.62  4995.5   534.5  4998.5  536.16  5014.2  542.62  5038.1  542.01
  5411.1  542.74  5788.5  548.57  6954.4  551.61  7356.7  564.64  7537.4  565.62
#Mann= 13 ,-1 , 0
   791.3      .1       0  1226.5     .05       0  1297.7      .1       0
  1471.6     .05       0  1585.6      .1       0  2874.2     .16       0
  3055.9     .07       0  3085.5     .16       0    3200      .1       0
  4798.2     .12       0  4897.9     .07       0  4998.5     .12       0
  5038.1      .1       0
Bank Sta=3055.9,3085.5
XS Rating Curve= 0 ,0
Exp/Cntr=0.3,0.1

Type RM Length L Ch R = 1 ,64892   ,735,735,735
BEGIN DESCRIPTION:
Black Creek 62.0
END DESCRIPTION:
XS GIS Cut Line= 3
      1979374.96     13538874.99        1975775.       13538075.
      1973274.98     13537417.92
#Sta/Elev= 30
  1316.7  576.12  1396.4  575.44  1536.1  572.01  1612.4  568.26  1811.9  561.25
  1915.3  558.39  2750.8  536.02  2894.2  542.47    2925  539.72  3095.6  538.45
  3184.9  537.14    3197  532.54  3202.4  531.54  3226.6  532.54  3228.4  536.97
  3352.6  539.19  4307.9  537.96  4816.9   540.3  4963.5   541.8  4994.2  534.24
  5007.1  534.43  5017.1  538.49  5027.2  541.98  5087.9  541.87  5183.5  539.16
  5415.2  545.46  5692.5   548.3  6265.9  547.06  6917.5  550.29  7589.4  563.45
#Mann= 13 ,-1 , 0
  1316.7     .05       0  1396.4      .1       0  1536.1     .05       0
  1612.4      .1       0  1811.9     .05       0  1915.3      .1       0
  3095.6     .16       0    3197     .07       0  3226.6     .16       0
  3352.6      .1       0  4816.9     .07       0  5017.1     .12       0
  5087.9      .1       0
Bank Sta=3197,3226.6
XS Rating Curve= 0 ,0
Exp/Cntr=0.3,0.1

Type RM Length L Ch R = 1 ,64157   ,1938,1938,1938
BEGIN DESCRIPTION:
Black Creek 61.0
END DESCRIPTION:
XS GIS Cut Line= 3
      1979275.47     13537667.49        1976125.       13537575.
      1973124.99       13537275.
#Sta/Elev= 30
  1833.9  563.79  2422.9  558.25  2560.7  555.55  2830.4  544.43  3024.3  539.96
  3074.9  544.47  3271.4  533.09    3325  539.57  3370.2   531.8  3375.6   530.8
  3399.8   531.8  3451.2  538.81    3568  537.59  3726.2   533.9  3927.8  537.37
  4053.5  536.69  4250.9  537.48  4545.8  538.22    4644  538.95  4742.4  540.25
  4889.8  539.41  4975.7  540.74  4995.8  534.04  5065.8   540.7    5139  534.53
  5166.6  540.45  6273.2  546.81  6426.9  548.23    7267  551.36  8000.7  569.06
#Mann= 20 ,-1 , 0
  1833.9      .1       0  2422.9     .05       0  2560.7      .1       0
  2830.4     .16       0  3024.3     .16       0  3271.4      .1       0
  3370.2     .07       0  3399.8      .1       0    3568     .16       0
  3726.2      .1       0  3927.8      .1       0  4053.5     .05       0
  4250.9      .1       0  4545.8     .07       0    4644     .16       0
  4742.4      .1       0  4889.8     .16       0  5065.8      .1       0
  6273.2     .05       0  6426.9      .1       0
Bank Sta=3370.2,3399.8
XS Rating Curve= 0 ,0
Exp/Cntr=0.3,0.1

Type RM Length L Ch R = 1 ,62219   ,786,786,786
BEGIN DESCRIPTION:
Black Creek 60.0
END DESCRIPTION:
XS GIS Cut Line= 3
      1978575.01       13537125.        1976575.       13536725.
      1972974.97       13537125.
#Sta/Elev= 30
  2966.3  567.68  3037.9   565.9  3157.8  561.84    3639  542.54  3792.3  534.85
  3927.4  535.09  4149.3  533.77  4261.5  535.83  4312.4   534.1  4332.8  535.91
  4363.4  534.24  4889.1   536.6  4975.3  536.94  4980.9  531.47  4986.3  530.47
  5010.5  531.47    5016  536.68  5076.1  536.08    5396  537.42  5535.3  537.87
  5559.3  538.16  5569.4   534.3  5584.6  537.09    5613  538.01  6344.1  539.32
  6769.5  546.63  6809.1  546.87  7611.9  549.29    8296  569.22  8628.1  574.28
#Mann= 15 ,-1 , 0
  2966.3      .1       0  3037.9     .05       0  3157.8      .1       0
    3639     .16       0  3927.4      .1       0  4889.1     .16       0
  4980.9     .07       0  5010.5     .16       0  5076.1      .1       0
    5396     .16       0  5535.3     .12       0  5584.6     .16       0
    5613      .1       0  6769.5     .05       0  6809.1      .1       0
Bank Sta=4980.9,5010.5
XS Rating Curve= 0 ,0
Exp/Cntr=0.3,0.1

Type RM Length L Ch R = 1 ,61433   ,830,830,830
BEGIN DESCRIPTION:
Black Creek 59.0
END DESCRIPTION:
XS GIS Cut Line= 3
      1978787.18     13536766.89        1976825.       13536225.
      1972979.93     13535864.11
#Sta/Elev= 30
  2950.9  568.02  3229.2  566.64  3239.6  566.81  3482.3  565.38  3660.2  558.74
    3794  553.46  3880.6  548.69  4198.1  531.26    4215  536.07  4260.1  535.25
  4664.6     535  4704.3  533.47  4805.5  533.73  4906.6  534.44  4976.2  535.28
  4981.8  530.89  4987.2  529.89  5011.4  530.89  5037.2  535.21  5713.6  535.36
  5718.6  535.43  5792.1  533.12  5810.1  536.45  5840.3  533.28  5870.4  536.44
  6252.1  535.62  6673.9  543.89    6925  542.58  7818.1  548.75  8848.5  560.76
#Mann= 16 ,-1 , 0
  2950.9      .1       0  3229.2     .08       0  3239.6      .1       0
  3660.2     .05       0    3794      .1       0  3880.6     .16       0
  4260.1      .1       0  4664.6     .16       0  4704.3     .12       0
  4805.5     .07       0  4906.6     .16       0  4981.8     .07       0
  5011.4     .16       0  5037.2      .1       0  5713.6     .16       0
  5718.6      .1       0
Bank Sta=4981.8,5011.4
XS Rating Curve= 0 ,0
Exp/Cntr=0.3,0.1

Type RM Length L Ch R = 1 ,60603   ,747,747,747
BEGIN DESCRIPTION:
Black Creek 58.0
END DESCRIPTION:
XS GIS Cut Line= 3
      1978986.79      13536263.4        1976875.       13535725.
      1973874.95     13535124.99
#Sta/Elev= 30
  2790.4  564.79  3168.7  553.12  3566.2  556.19  3853.3  549.48  3933.3  545.81
    4131  538.63  4256.9  535.26  4589.1  534.91  4618.9  530.49  4649.8  530.54
  4660.1   534.5  4677.2  534.73  4972.3  534.44  4995.7  530.32  5001.1  529.32
  5025.3  530.32  5030.9   533.7  5041.1  534.08  5153.3  532.38  5349.2  534.02
  5396.2  534.22  5438.8  531.48  5479.6  531.58    5500  534.04  5753.6  534.26
  6030.3  534.23  7029.7  550.55  7254.1  556.87  7743.6  560.22  8029.2  564.89
#Mann= 9 ,-1 , 0
  2790.4      .1       0  3933.3     .05       0    4131     .16       0
  4677.2     .05       0  4995.7     .04       0  5025.3     .05       0
  5349.2     .08       0  5396.2     .05       0  5753.6      .1       0
Bank Sta=4995.7,5025.3
XS Rating Curve= 0 ,0
Exp/Cntr=0.3,0.1

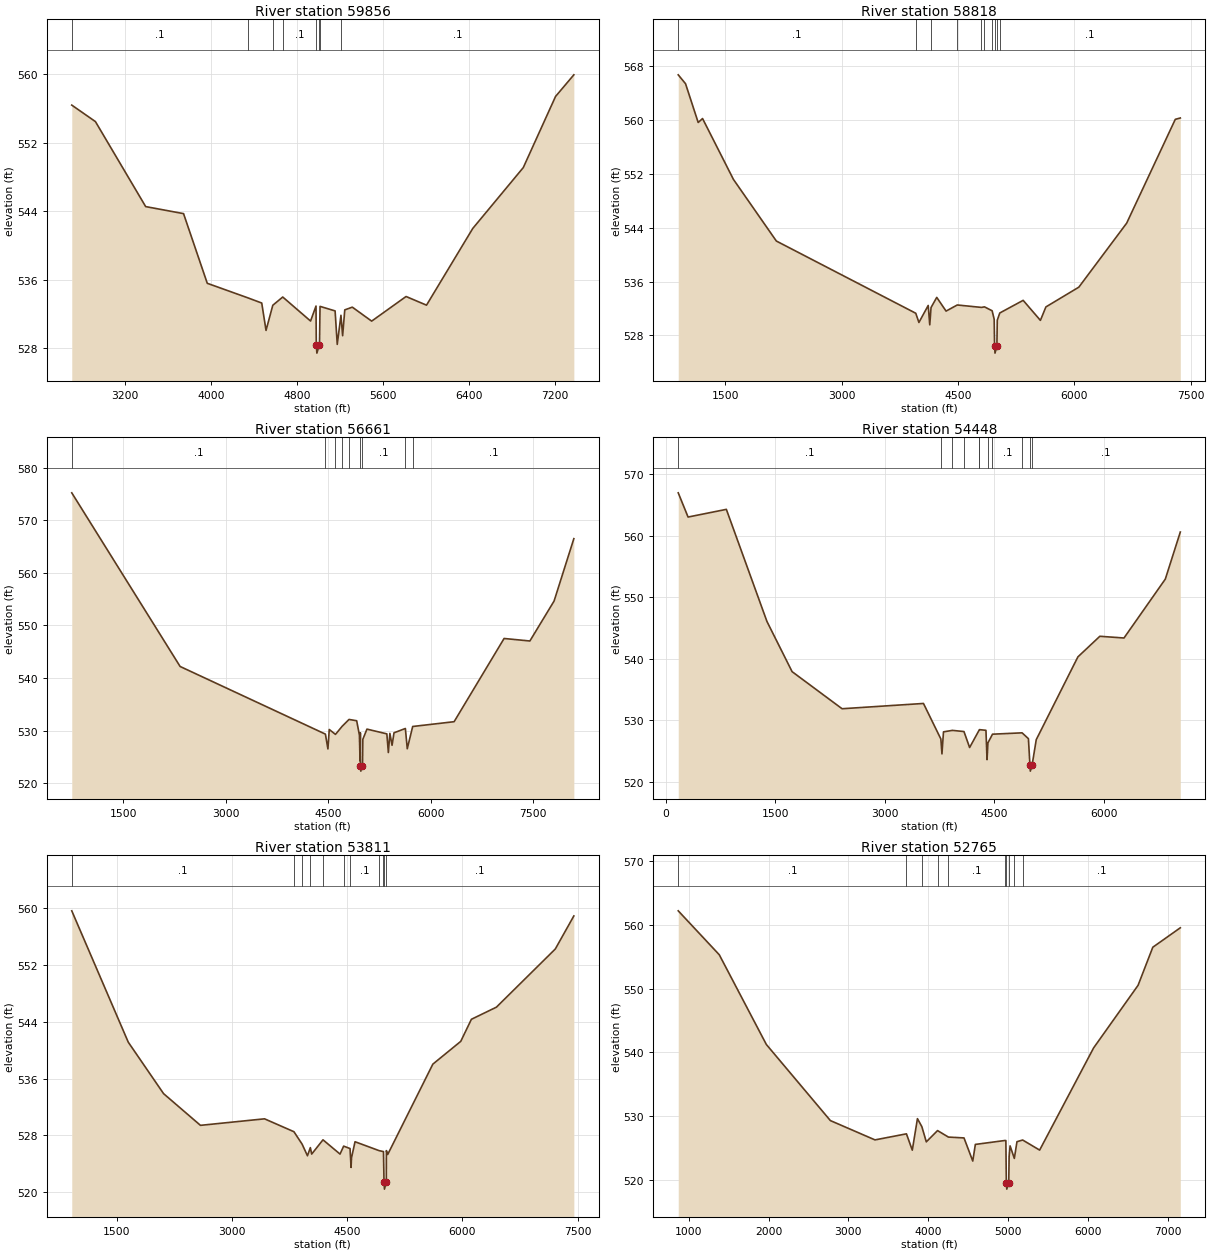
Type RM Length L Ch R = 1 ,59856   ,1038,1038,1038
BEGIN DESCRIPTION:
Black Creek 57.0
END DESCRIPTION:
XS GIS Cut Line= 3
      1979134.34     13535820.69        1976975.       13535125.
      1974575.04       13535125.
#Sta/Elev= 30
  2706.7  556.37  2926.6  554.45    3394  544.54  3746.1  543.72  3966.7   535.6
  4342.8  533.91  4473.1   533.3  4513.1  530.11    4576  533.04  4668.5     534
  4927.2   531.2  4977.8  532.95  4980.5  528.46  4985.9  527.46  5010.1  528.46
  5013.1  531.03  5015.3  532.91  5155.3  532.38  5175.3  528.48  5209.7  531.87
  5225.3  529.49  5245.3   532.5  5315.3  532.82  5495.3  531.19  5815.3  534.06
  6005.3  533.05  6435.3  541.99  6905.3  549.09  7205.3  557.38  7375.3   559.9
#Mann= 8 ,-1 , 0
  2706.7      .1       0  4342.8     .12       0    4576     .05       0
  4668.5      .1       0  4980.5     .07       0  5010.1      .1       0
  5013.1     .12       0  5209.7      .1       0
Bank Sta=4980.5,5010.1
XS Rating Curve= 0 ,0
Exp/Cntr=0.3,0.1

Type RM Length L Ch R = 1 ,58818   ,2157,2157,2157
BEGIN DESCRIPTION:
Black Creek 56.0
END DESCRIPTION:
XS GIS Cut Line= 4
      1980874.99       13535475.      1978179.52     13534657.51
        1976875.       13534675.      1974551.06     13535013.41
#Sta/Elev= 30
   894.2  566.74   988.2  565.42  1151.4  559.65  1207.7  560.24  1605.3  551.19
  2158.6  542.02  3955.1  531.28  3995.5  529.91  4115.5  532.44  4135.5  529.56
  4151.9  532.13  4225.5  533.64  4345.5   531.6  4489.8  532.51  4800.9  532.15
  4840.7  532.23  4939.1  531.65  4965.5  530.39  4970.7  526.35  4976.1  525.35
  5000.3  526.35  5005.5  530.25  5037.8  531.32  5338.9   533.2  5561.2  530.22
    5632  532.22  6056.4  535.16  6672.8  544.68  7299.4  560.12    7364  560.32
#Mann= 10 ,-1 , 0
   894.2      .1       0  3955.1     .07       0  4151.9     .05       0
  4489.8      .1       0  4800.9     .16       0  4840.7      .1       0
  4939.1     .12       0  4970.7     .07       0  5000.3     .12       0
  5037.8      .1       0
Bank Sta=4970.7,5000.3
XS Rating Curve= 0 ,0
Exp/Cntr=0.3,0.1

Type RM Length L Ch R = 1 ,56661   ,2213,2213,2213
BEGIN DESCRIPTION:
Black Creek 55.0
END DESCRIPTION:
XS GIS Cut Line= 4
      1981225.01       13535575.      1978325.35     13533805.08
      1977339.24      13533739.1      1974654.01     13532489.78
#Sta/Elev= 30
     750   575.2  2335.5  542.21  4461.6  529.36  4498.3  526.55  4518.1  530.24
  4608.7  529.31    4707  530.85  4807.1  532.15  4919.2   531.9  4959.3  529.17
  4968.3  524.29  4973.3   529.6  4974.5  523.33  4979.9  522.33  5004.3  523.33
  5009.4  528.38  5069.6  530.31  5360.7  529.41  5382.8  525.86  5404.8  529.51
    5437  527.24  5465.4  529.61  5631.9  530.43  5659.5  526.58  5738.8  530.81
  6345.1  531.72  7076.5  547.53  7453.7  547.05  7807.9  554.64  8097.1  566.49
#Mann= 9 ,-1 , 0
     750      .1       0  4461.6     .12       0  4608.7      .1       0
    4707     .05       0  4807.1      .1       0  4974.5     .07       0
  5004.3      .1       0  5631.9     .07       0  5738.8      .1       0
Bank Sta=4974.5,5004.3
XS Rating Curve= 0 ,0
Exp/Cntr=0.3,0.1

Type RM Length L Ch R = 1 ,54448   ,637,637,637
BEGIN DESCRIPTION:
Black Creek 54.0
END DESCRIPTION:
XS GIS Cut Line= 4
      1981499.82     13533338.06      1978677.95     13533432.07
      1976812.33     13532144.48      1975025.03       13532275.
#Sta/Elev= 30
   167.5  566.99   302.4  563.05   827.1   564.3    1383  546.08  1727.8   537.9
  2413.6  531.86  3529.1  532.72  3767.5  526.94  3782.5  524.51  3803.5   528.1
    3926  528.34  4084.2  528.15  4161.8  525.55  4294.7  528.43    4296  528.46
  4385.6  528.35  4400.4  523.57  4412.9  526.31  4475.3  527.72  4880.7  527.94
  4967.7  526.99  4988.6  522.71    4994  521.71  5018.4  522.71  5075.1  526.83
  5646.1   540.3  5946.9  543.65  6277.8  543.37  6844.1  552.95  7049.8  560.61
#Mann= 11 ,-1 , 0
   167.5      .1       0  3767.5     .12       0    3926     .05       0
  4084.2      .1       0  4294.7     .07       0    4296      .1       0
  4412.9     .12       0  4475.3      .1       0  4880.7     .07       0
  4988.6     .07       0  5018.4      .1       0
Bank Sta=4988.6,5018.4
XS Rating Curve= 0 ,0
Exp/Cntr=0.3,0.1

Type RM Length L Ch R = 1 ,53811   ,1046,1046,1046
BEGIN DESCRIPTION:
Black Creek 53.0
END DESCRIPTION:
XS GIS Cut Line= 4
       1981120.1     13532632.77      1979080.13     13532643.62
      1976942.54     13531667.05      1974815.76     13531384.93
#Sta/Elev= 30
   916.1  559.66  1651.2  541.15  2111.2  533.89  2591.2  529.42  3425.5  530.34
  3808.4  528.52    3915  526.76  3984.2  525.13  4021.6  526.28  4039.2  525.37
  4186.2  527.38  4408.1  525.37  4455.2  526.49  4538.4  526.15  4551.7  523.49
  4557.2  524.82  4603.3  527.11    4918  525.85  4973.6  525.72  4980.8  521.43
  4986.2  520.43  5010.6  521.43  5011.2  525.86  5028.6  525.31  5616.4  538.05
  5979.6  541.26    6118  544.37  6443.6  546.08  7210.3  554.28  7451.6  558.94
#Mann= 11 ,-1 , 0
   916.1      .1       0  3808.4     .07       0    3915     .12       0
  4021.6     .05       0  4186.2      .1       0  4455.2     .07       0
  4538.4      .1       0    4918     .07       0  4973.6      .1       0
  4980.8     .07       0  5010.6      .1       0
Bank Sta=4980.8,5010.6
XS Rating Curve= 0 ,0
Exp/Cntr=0.3,0.1

Type RM Length L Ch R = 1 ,52765   ,314,314,314
BEGIN DESCRIPTION:
Black Creek 52.0
END DESCRIPTION:
XS GIS Cut Line= 3
      1981467.24     13532426.59        1977525.       13531175.
      1975525.01     13530375.01
#Sta/Elev= 30
   868.1   562.2  1382.4  555.31  1972.1  541.24  2774.1  529.31  3333.1  526.28
  3727.2  527.23  3800.5  524.67    3865  529.61  3920.2  528.36    3976  525.97
  4116.9  527.74    4253  526.72  4448.2  526.59  4558.2  522.96  4590.5  525.57
  4957.7  526.18  4972.8  526.18  4978.8  519.56  4984.3  518.56  5008.7  519.56
  5013.7  523.65  5025.8  525.34  5078.8  523.38    5112     526  5183.4  526.26
    5396  524.68  6071.9   540.7  6629.2  550.52  6813.7  556.49  7158.3  559.54
#Mann= 10 ,-1 , 0
   868.1      .1       0  3727.2     .12       0  3920.2      .1       0
  4116.9     .05       0    4253      .1       0  4957.7     .12       0
  4978.8     .07       0  5008.7     .12       0  5078.8     .07       0
  5183.4      .1       0
Bank Sta=4978.8,5008.7
XS Rating Curve= 0 ,0
Exp/Cntr=0.3,0.1

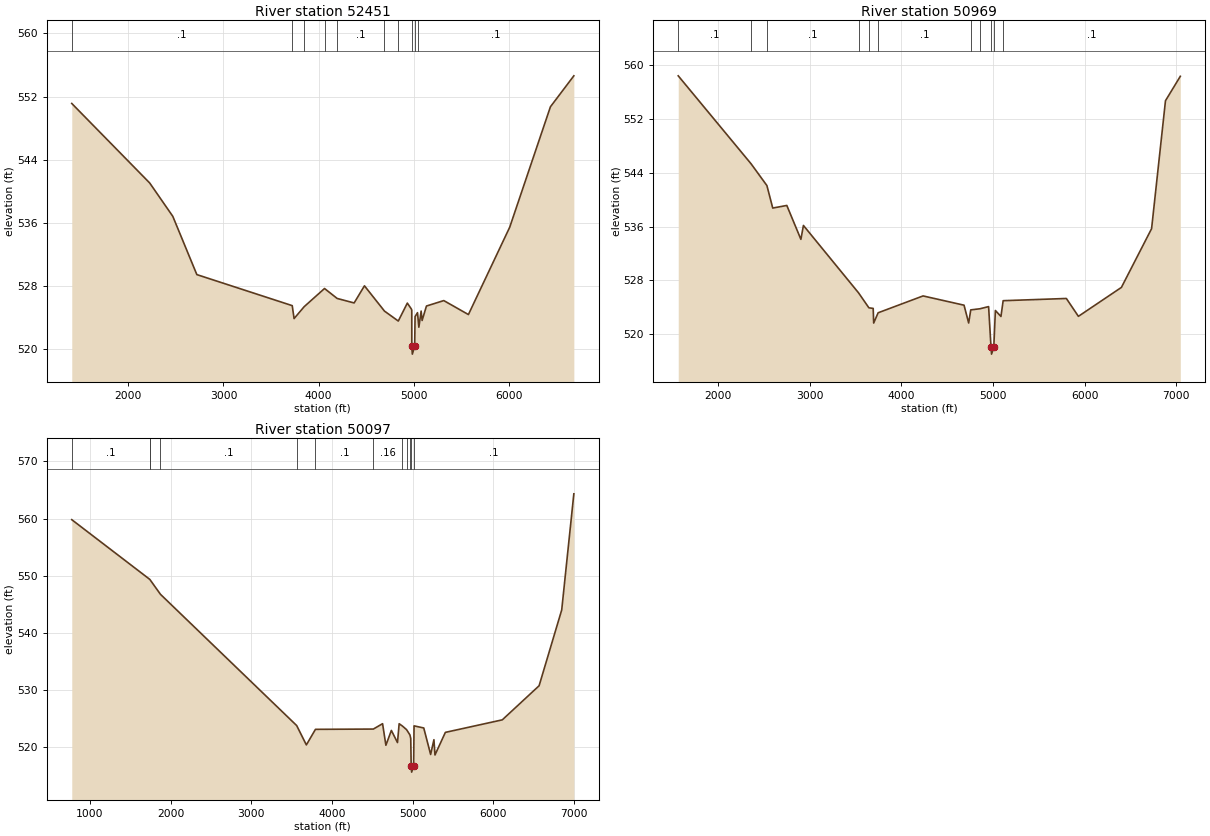
Type RM Length L Ch R = 1 ,52451   ,1482,1482,1482
BEGIN DESCRIPTION:
Black Creek 51.0
END DESCRIPTION:
XS GIS Cut Line= 3
      1981022.44     13532014.29      1978255.47     13531091.97
      1975974.99       13530475.
#Sta/Elev= 30
  1404.9  551.13  2224.4  541.06  2467.1  536.84    2720  529.46  3722.9  525.53
  3742.3  523.89  3848.7   525.4  4062.6   527.7  4195.2  526.44  4373.8  525.87
  4482.4  528.04  4692.8  524.84  4838.2  523.58  4933.2  525.85  4974.7  525.12
  4979.9  524.96  4980.4  520.39  4985.9  519.39  5010.3  520.39  5014.6  524.14
  5040.2  524.64  5054.5   522.8  5078.3  524.84  5088.6  523.65  5134.2  525.48
  5316.5  526.17  5575.5   524.4  6009.7  535.46  6437.8  550.71    6684  554.63
#Mann= 10 ,-1 , 0
  1404.9      .1       0  3722.9     .12       0  3848.7      .1       0
  4062.6     .05       0  4195.2      .1       0  4692.8     .07       0
  4838.2     .12       0  4980.4     .07       0  5010.3     .12       0
  5040.2      .1       0
Bank Sta=4980.4,5010.3
XS Rating Curve= 0 ,0
Exp/Cntr=0.3,0.1

Type RM Length L Ch R = 1 ,50969   ,872,872,872
BEGIN DESCRIPTION:
Black Creek 50.0
END DESCRIPTION:
XS GIS Cut Line= 5
      1981087.23     13531458.44       1979756.2     13530661.56
      1977607.76     13530075.62      1977403.77     13530104.26
      1975924.99       13530325.
#Sta/Elev= 30
  1565.4  558.46  2361.2  545.34  2533.1  542.11  2596.8  538.76  2750.4  539.15
  2904.1   534.1  2931.7  536.17  3533.7  526.12  3646.1   523.9    3693  523.81
  3698.4  521.63  3747.1  523.16  4237.4  525.67  4684.6  524.29    4735  521.64
  4757.8  523.59  4858.8  523.76  4952.6  524.08  4979.1     518  4984.6     517
    5009     518  5026.7   523.5  5087.4  522.61  5111.4  524.96  5801.2  525.29
  5932.6  522.63    6402  526.94  6731.4  535.69    6883  554.75  7044.8  558.39
#Mann= 11 ,-1 , 0
  1565.4      .1       0  2361.2     .05       0  2533.1      .1       0
  3533.7     .12       0  3646.1     .16       0  3747.1      .1       0
  4757.8     .07       0  4858.8     .16       0  4979.1     .07       0
    5009     .16       0  5111.4      .1       0
Bank Sta=4979.1,5009
XS Rating Curve= 0 ,0
Exp/Cntr=0.3,0.1

Type RM Length L Ch R = 1 ,50097   ,1616,1616,1616
BEGIN DESCRIPTION:
Black Creek 49.0
END DESCRIPTION:
XS GIS Cut Line= 4
      1981657.21     13531533.93      1980029.63     13530205.83
      1977646.82     13529658.95      1975974.97       13529725.
#Sta/Elev= 30
   776.7  559.82  1742.2  549.39  1747.8  549.29  1875.4  546.77  3562.6  523.82
  3682.4  520.44    3795  523.16    4512  523.21  4626.3  524.15  4667.4  520.38
  4735.2  522.97    4811  520.85  4831.5  524.14  4868.1  523.78  4922.7  523.12
    4965  522.19  4975.2  521.57  4980.7  516.68  4986.2  515.68  5010.6  516.68
  5016.2  523.77  5136.4   523.4  5221.4  518.77  5262.4  521.35  5275.3  518.68
    5404  522.63  6109.1  524.82  6564.9  530.78  6845.1  544.04  6995.3  564.34
#Mann= 12 ,-1 , 0
   776.7      .1       0  1742.2     .08       0  1747.8     .05       0
  1875.4      .1       0  3562.6     .12       0    3795      .1       0
    4512     .16       0  4868.1     .12       0  4922.7     .16       0
    4965      .1       0  4980.7     .07       0  5010.6      .1       0
Bank Sta=4980.7,5010.6
XS Rating Curve= 0 ,0
Exp/Cntr=0.3,0.1