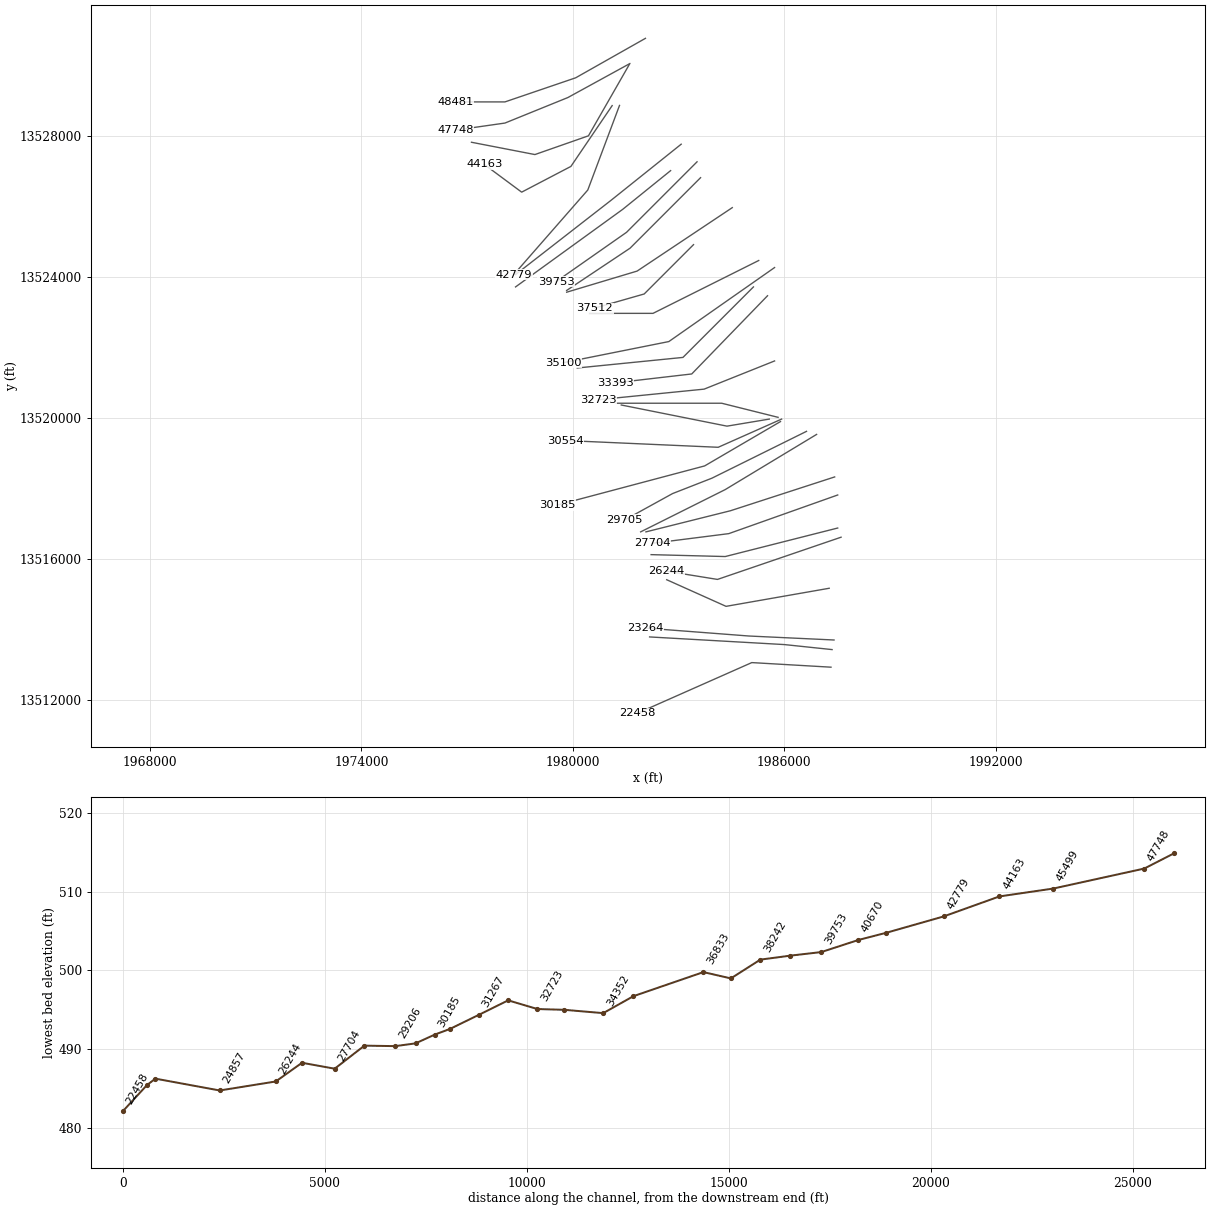
HEC-RAS study Black Creek.prj: Black Creek Base Level Engineering

--- Black Creek.g01 (geometry) --- (continued)

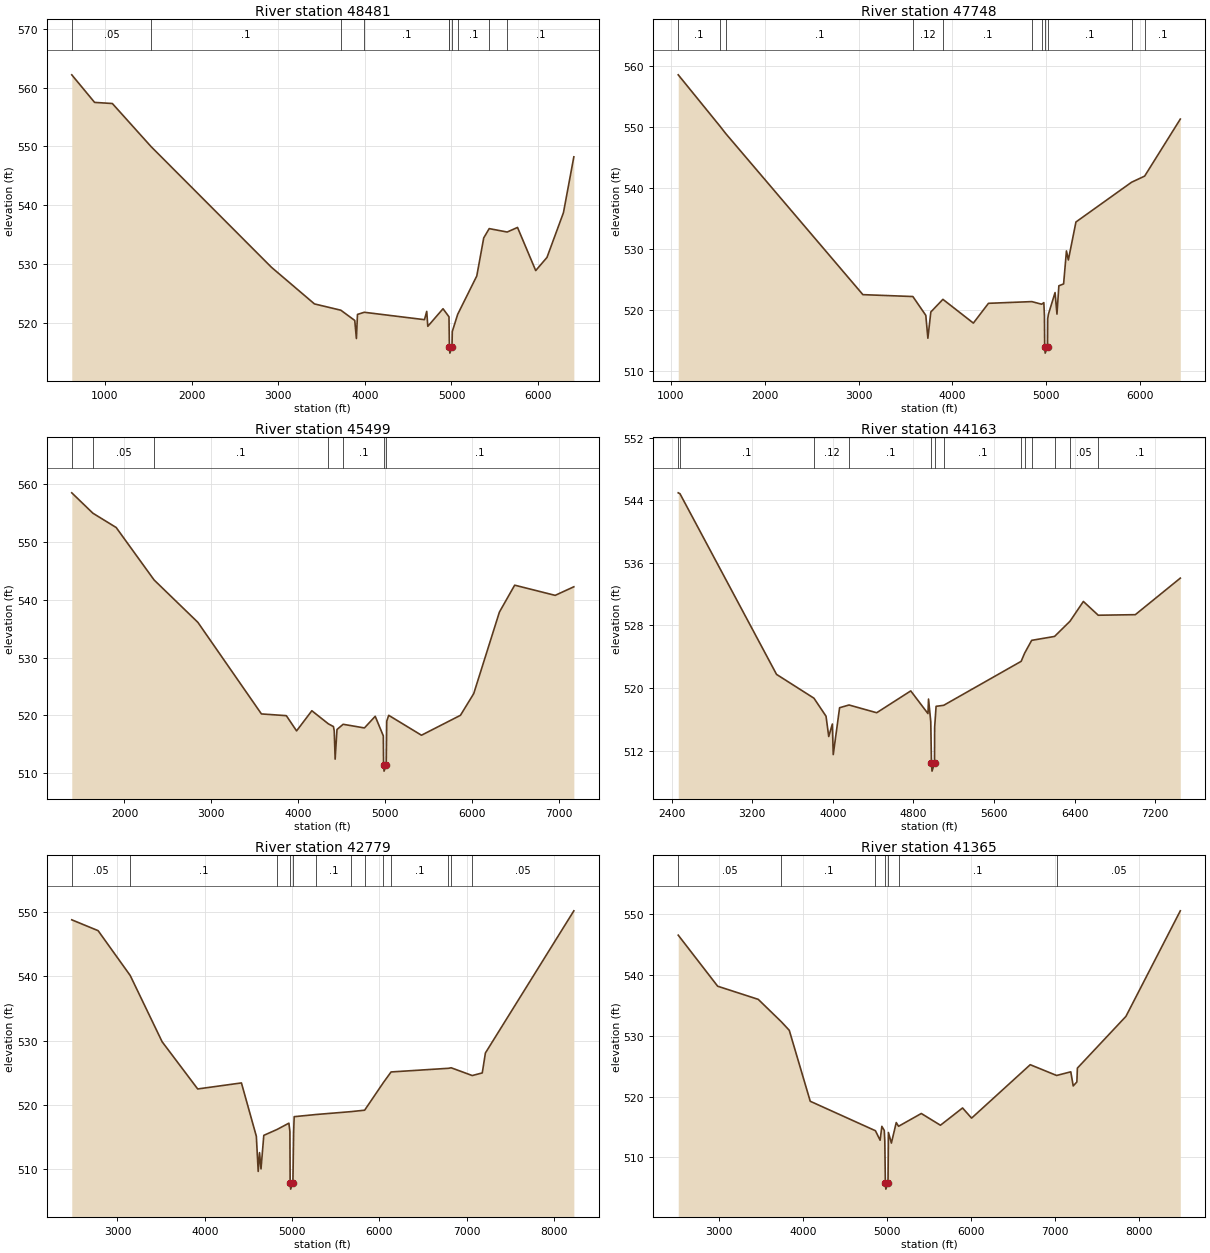
Type RM Length L Ch R = 1 ,48481   ,733,733,733
BEGIN DESCRIPTION:
Black Creek 48.0
END DESCRIPTION:
XS GIS Cut Line= 4
       1982060.9     13530778.75      1980081.72     13529658.95
        1978075.       13528975.      1976674.98       13528975.
#Sta/Elev= 30
     618  562.17   881.4  557.48  1086.3  557.29  1532.7  549.97  2922.6  529.43
  3418.9   523.2    3723  522.13  3883.8  520.39  3902.8  517.31  3915.1  521.41
  3992.9  521.78  4688.2  520.52  4714.3  521.93  4726.8  519.39  4902.4  522.38
  4971.2  521.01    4976  515.83  4981.5  514.83  5005.9  515.83  5009.4  518.51
  5071.3  521.42  5292.1  527.96  5372.1  534.43  5435.4  536.01  5642.7  535.43
  5762.1  536.21  5972.1  528.87  6102.1  531.11  6292.1  538.72  6412.1  548.22
#Mann= 10 ,-1 , 0
     618     .05       0  1532.7      .1       0    3723     .12       0
  3992.9      .1       0  4971.2     .16       0    4976     .07       0
  5005.9     .16       0  5071.3      .1       0  5435.4     .08       0
  5642.7      .1       0
Bank Sta=4976,5005.9
XS Rating Curve= 0 ,0
Exp/Cntr=0.3,0.1

Type RM Length L Ch R = 1 ,47748   ,2249,2249,2249
BEGIN DESCRIPTION:
Black Creek 47.0
END DESCRIPTION:
XS GIS Cut Line= 4
      1981618.18      13530062.6      1979860.36     13529099.06
        1978075.       13528375.      1976674.99       13528175.
#Sta/Elev= 30
  1080.6   558.5  1526.9  550.05  1586.8  548.87  3046.5  522.49  3578.8  522.18
  3716.4   519.1  3738.4  515.35  3769.9  519.65  3898.5  521.72  4222.7  517.83
  4383.5  521.07  4845.2  521.35    4950  520.92  4972.9  521.18  4979.4  519.06
  4982.1  513.91  4987.6  512.91    5012  513.91  5014.3  518.55  5021.9  519.29
  5092.6  522.83  5112.8   519.3    5133  523.94  5183.5  524.25  5213.8  529.65
    5234  528.17  5314.8  534.39  5906.6   540.9  6046.4  541.91    6426  551.25
#Mann= 11 ,-1 , 0
  1080.6      .1       0  1526.9     .05       0  1586.8      .1       0
  3578.8     .12       0  3898.5      .1       0  4845.2     .12       0
    4950      .1       0  4982.1     .07       0    5012      .1       0
  5906.6     .05       0  6046.4      .1       0
Bank Sta=4982.1,5012
XS Rating Curve= 0 ,0
Exp/Cntr=0.3,0.1

Type RM Length L Ch R = 1 ,45499   ,1336,1336,1336
BEGIN DESCRIPTION:
Black Creek 46.0
END DESCRIPTION:
XS GIS Cut Line= 4
      1981602.46     13530035.65      1980443.87     13528012.77
      1978924.77     13527481.09       1977124.5     13527830.03
#Sta/Elev= 30
  1394.2  558.45  1637.1  554.93    1905  552.46    2341   543.4  2844.5  536.08
  3575.5  520.26  3861.9  519.96  3979.8  517.33  4155.4  520.81  4345.1  518.55
  4403.6  518.08  4412.8  517.33  4423.4  512.45  4444.6  517.57  4515.2  518.47
  4760.1  517.84  4884.2  519.85  4977.3  516.47  4980.4  511.38    4986  510.38
  5010.6  511.38  5016.7  519.01  5039.3  520.02  5416.1  516.58  5864.3  520.02
  6017.2  523.77  6312.5  537.85    6488   542.5  6953.7  540.74  7168.6  542.22
#Mann= 7 ,-1 , 0
  1394.2      .1       0  1637.1     .05       0    2341      .1       0
  4345.1     .12       0  4515.2      .1       0  4980.4     .07       0
  5010.6      .1       0
Bank Sta=4980.4,5010.6
XS Rating Curve= 0 ,0
Exp/Cntr=0.3,0.1

Type RM Length L Ch R = 1 ,44163   ,1384,1384,1384
BEGIN DESCRIPTION:
Black Creek 45.0
END DESCRIPTION:
XS GIS Cut Line= 4
       1981116.6     13528869.95      1979945.61     13527144.28
      1978548.55     13526414.37      1977486.08     13527202.54
#Sta/Elev= 30
  2465.6  544.94  2483.1  544.82  3441.7  521.74  3812.9   518.7  3932.8   516.4
  3959.8   513.8  3995.7   515.4  4004.6  511.49  4067.6  517.48  4161.3  517.83
  4435.9  516.84    4774  519.63    4945  516.73  4950.6  518.59  4972.7  515.71
  4979.7  510.38  4985.3  509.38  5009.9  510.38  5011.2  514.96  5025.6  517.66
  5101.1  517.79  5870.2  523.41  5904.9  524.46  5974.4  526.09  6201.7  526.59
  6355.6  528.54  6487.9  531.06  6635.3   529.3  7003.3  529.37  7450.2  534.04
#Mann= 13 ,-1 , 0
  2465.6     .05       0  2483.1      .1       0  3812.9     .12       0
  4161.3      .1       0  4979.7     .07       0  5009.9     .12       0
  5101.1      .1       0  5870.2     .05       0  5904.9      .1       0
  5974.4     .05       0  6201.7      .1       0  6355.6     .05       0
  6635.3      .1       0
Bank Sta=4979.7,5009.9
XS Rating Curve= 0 ,0
Exp/Cntr=0.3,0.1

Type RM Length L Ch R = 1 ,42779   ,1414,1414,1414
BEGIN DESCRIPTION:
Black Creek 44.0
END DESCRIPTION:
XS GIS Cut Line= 3
        1981325.       13528875.        1980425.       13526475.
      1978325.03     13524075.04
#Sta/Elev= 30
  2476.2  548.81  2777.9  547.12  3145.9  540.13  3511.3  529.81  3918.9  522.45
    4420  523.39  4590.8  515.08  4612.2   509.6  4627.3  512.53  4644.2  509.99
  4676.3  515.22  4828.6  516.14  4963.8  517.12  4975.3  515.83  4978.2  507.84
  4984.3  506.84  5009.8  507.84    5018  515.63  5024.3  518.13  5276.7  518.47
  5670.3  518.91  5831.6  519.14  6047.5  523.47  6134.5   525.1    6792  525.67
  6823.1  525.75  7064.6  524.54  7179.2  524.95  7215.3  528.06  8228.4  550.21
#Mann= 13 ,-1 , 0
  2476.2     .05       0  3145.9      .1       0  4828.6     .16       0
  4978.2     .07       0  5009.8     .16       0  5276.7      .1       0
  5670.3     .16       0  5831.6      .1       0  6047.5     .16       0
  6134.5      .1       0    6792     .05       0  6823.1      .1       0
  7064.6     .05       0
Bank Sta=4978.2,5009.8
XS Rating Curve= 0 ,0
Exp/Cntr=0.3,0.1

Type RM Length L Ch R = 1 ,41365   ,695,695,695
BEGIN DESCRIPTION:
Black Creek 43.0
END DESCRIPTION:
XS GIS Cut Line= 3
      1983074.99     13527774.99        1981075.       13526175.
      1978374.97     13524074.97
#Sta/Elev= 30
  2514.7  546.52  2984.5  538.13  3467.9  535.97  3744.2  532.27  3837.7  530.88
  4087.5  519.22  4863.9  514.38  4919.9  512.82  4940.7   515.1  4969.5  514.42
  4975.9  512.69  4982.5  505.78  4988.5  504.78  5014.1  505.78  5019.1  514.09
  5054.3  512.35  5112.1  515.72  5139.9  515.11  5410.7  517.21  5638.8  515.28
  5902.1  518.12  6009.8  516.45  6708.4  525.23  7022.7  523.46  7191.6  524.06
  7220.5  521.74    7264  522.39  7270.3  524.67  7848.5  533.17  8496.5  550.52
#Mann= 7 ,-1 , 0
  2514.7     .05       0  3744.2      .1       0  4863.9     .16       0
  4982.5     .07       0  5014.1     .16       0  5139.9      .1       0
  7022.7     .05       0
Bank Sta=4982.5,5014.1
XS Rating Curve= 0 ,0
Exp/Cntr=0.3,0.1

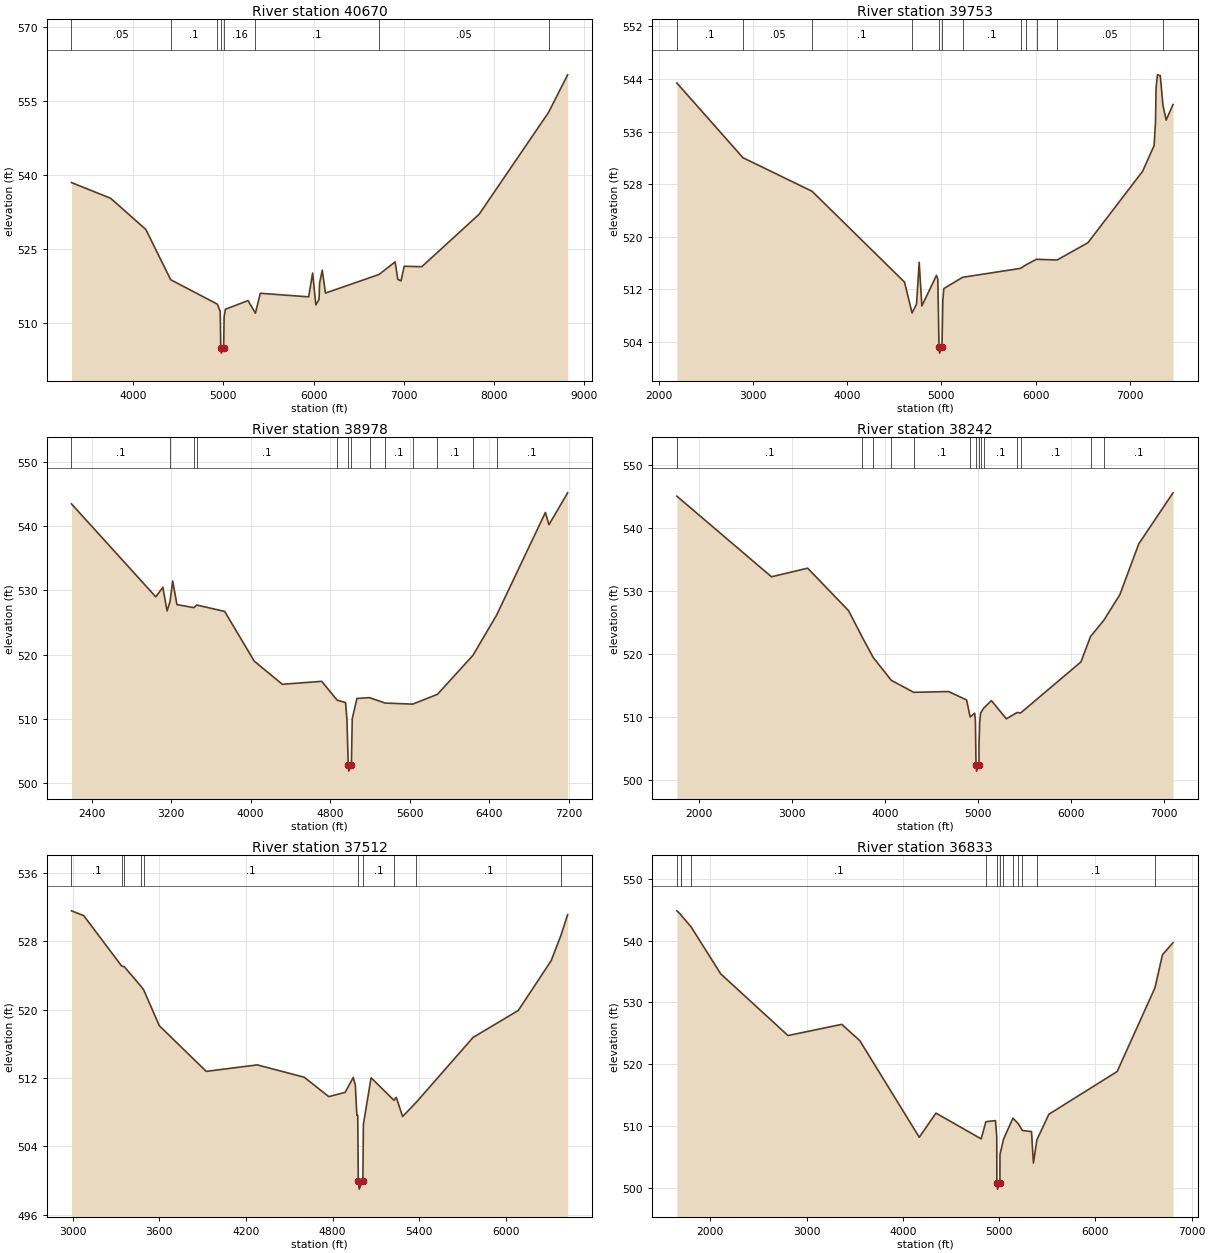
Type RM Length L Ch R = 1 ,40670   ,917,917,917
BEGIN DESCRIPTION:
Black Creek 42.0
END DESCRIPTION:
XS GIS Cut Line= 3
      1982775.02     13527025.01       1981414.9     13525925.79
        1978375.       13523725.
#Sta/Elev= 30
  3315.3   538.4  3749.4  535.22  4139.6  528.91  4415.7  518.72  4933.1  513.78
  4964.7  512.29  4970.9  504.86    4977  503.86  5002.6  504.86  5007.9  511.21
  5022.2  512.75  5273.1   514.5  5354.8  511.95  5409.2  515.98  5945.1  515.26
  5989.2  520.08  6024.8  513.63  6060.4  514.73  6066.6  518.05    6096  520.65
  6131.5  516.02  6724.5  519.78  6904.1  522.33  6933.5   518.8  6969.1  518.48
  7004.6  521.45  7199.5  521.36    7836  531.99  8605.2  552.61    8817  560.22
#Mann= 8 ,-1 , 0
  3315.3     .05       0  4415.7      .1       0  4933.1     .16       0
  4970.9     .07       0  5002.6     .16       0  5354.8      .1       0
  6724.5     .05       0  8605.2      .1       0
Bank Sta=4970.9,5002.6
XS Rating Curve= 0 ,0
Exp/Cntr=0.3,0.1

Type RM Length L Ch R = 1 ,39753   ,775,775,775
BEGIN DESCRIPTION:
Black Creek 41.0
END DESCRIPTION:
XS GIS Cut Line= 3
        1983525.       13527275.        1981525.       13525275.
      1979525.03     13523875.02
#Sta/Elev= 30
  2190.6  543.38    2893  532.02  3626.2  526.93  4608.9  513.12  4688.6  508.43
  4736.2  509.77  4764.5  516.13  4792.8   509.5  4948.3  514.15  4962.5  513.56
  4974.9  503.33  4980.9  502.33  5006.6  503.33  5015.5  510.37  5026.4  512.14
    5225  513.85  5840.9  515.21  5900.2  515.76  6010.7  516.59  6229.2  516.48
  6556.6  519.11  7137.3  529.96  7259.4  533.87  7274.2  537.42  7280.3  542.67
  7295.1  544.62  7324.8   544.5  7353.6  539.98  7387.5  537.74  7460.3  540.11
#Mann= 12 ,-1 , 0
  2190.6      .1       0    2893     .05       0  3626.2      .1       0
  4688.6     .16       0  4974.9     .07       0  5006.6     .16       0
    5225      .1       0  5840.9     .05       0  5900.2     .08       0
  6010.7      .1       0  6229.2     .05       0  7353.6      .1       0
Bank Sta=4974.9,5006.6
XS Rating Curve= 0 ,0
Exp/Cntr=0.3,0.1

Type RM Length L Ch R = 1 ,38978   ,736,736,736
BEGIN DESCRIPTION:
Black Creek 40.0
END DESCRIPTION:
XS GIS Cut Line= 3
      1983625.01     13526825.01        1981625.       13524825.
      1979824.98     13523624.99
#Sta/Elev= 30
  2198.5  543.48    3047     529  3117.8  530.49  3160.2  526.81  3189.9  528.26
  3216.8  531.47  3259.2   527.8  3430.5  527.32  3459.6  527.73    3740  526.73
    4037     519  4319.8  515.39  4715.8  515.85  4871.2  512.92  4956.2  512.54
  4970.4  509.83  4982.8  502.87  4988.9  501.87  5014.5  502.87  5023.4  510.06
  5070.5  513.18    5197  513.31    5353  512.47  5631.4   512.3  5880.8  513.83
  6237.8   519.9  6475.7  526.16  6966.4  542.14  7002.5  540.24  7190.3   545.2
#Mann= 13 ,-1 , 0
  2198.5      .1       0  3189.9     .05       0  3430.5     .08       0
  3459.6      .1       0  4871.2     .16       0  4982.8     .07       0
  5014.5     .16       0    5197     .05       0    5353      .1       0
  5631.4     .12       0  5880.8      .1       0  6237.8     .05       0
  6475.7      .1       0
Bank Sta=4982.8,5014.5
XS Rating Curve= 0 ,0
Exp/Cntr=0.3,0.1

Type RM Length L Ch R = 1 ,38242   ,730,730,730
BEGIN DESCRIPTION:
Black Creek 39.0
END DESCRIPTION:
XS GIS Cut Line= 3
      1984524.98     13525974.98        1981825.       13524175.
      1979825.03     13523575.01
#Sta/Elev= 30
    1762  545.09    2779  532.27  3168.1  533.64  3608.3  526.87    3757   522.6
  3872.7  519.44  4066.9  515.81  4308.1   513.9  4682.5  514.02  4876.3  512.69
  4914.6  509.98  4963.4  510.58  4970.9  509.43  4977.6  502.37  4983.6  501.37
  5009.3  502.37  5009.6  505.51  5017.4  509.19  5027.5  510.63  5058.6  511.35
  5142.7  512.59  5303.6  509.69  5418.7  510.69  5457.4  510.62  6105.8  518.74
  6208.2  522.77  6351.4  525.36  6523.4  529.42    6727  537.51    7095  545.62
#Mann= 14 ,-1 , 0
    1762      .1       0    3757     .05       0  3872.7      .1       0
  4066.9     .05       0  4308.1      .1       0  4914.6     .16       0
  4977.6     .07       0  5009.3     .16       0  5027.5     .12       0
  5058.6      .1       0  5418.7     .12       0  5457.4      .1       0
  6208.2     .05       0  6351.4      .1       0
Bank Sta=4977.6,5009.3
XS Rating Curve= 0 ,0
Exp/Cntr=0.3,0.1

Type RM Length L Ch R = 1 ,37512   ,679,679,679
BEGIN DESCRIPTION:
Black Creek 38.0
END DESCRIPTION:
XS GIS Cut Line= 3
      1983424.97     13524924.97        1982025.       13523525.
      1980624.98       13523125.
#Sta/Elev= 30
  2992.1  531.58  3076.9  531.02  3339.8  525.11  3357.8  525.04  3474.2  522.73
  3492.6  522.31  3600.2  518.13  3925.4  512.78    4279  513.54  4604.3  512.09
    4774  509.82  4887.1  510.32  4943.7  512.07  4957.8  511.15  4968.4  507.63
  4974.6  507.63  4978.2  499.99  4984.3  498.99  5009.9  499.99  5013.6  506.58
  5066.9  512.03    5226  509.38  5241.1  509.74  5285.3  507.49  5380.3  509.17
  5772.8  516.75  6086.1  519.91  6313.6  525.73  6379.7  528.62    6428  531.12
#Mann= 10 ,-1 , 0
  2992.1      .1       0  3339.8     .08       0  3357.8     .05       0
  3474.2     .08       0  3492.6      .1       0  4978.2     .07       0
  5009.9      .1       0    5226     .12       0  5380.3      .1       0
  6379.7     .05       0
Bank Sta=4978.2,5009.9
XS Rating Curve= 0 ,0
Exp/Cntr=0.3,0.1

Type RM Length L Ch R = 1 ,36833   ,1733,1733,1733
BEGIN DESCRIPTION:
Black Creek 37.0
END DESCRIPTION:
XS GIS Cut Line= 3
      1985274.98     13524474.99        1982275.       13522975.
      1980474.98       13522975.
#Sta/Elev= 30
  1652.4  544.82  1693.7  544.22  1697.7   544.1  1801.9  542.19    2108  534.62
  2806.8  524.64  3365.8  526.45    3553  523.81  4170.8  508.18    4344  512.09
  4813.6  507.92  4862.6   510.7  4961.8  510.88  4975.7  508.27  4976.7  500.79
  4982.7  499.79  5008.4  500.79    5009  505.36  5045.3  507.85  5143.6  511.27
  5198.9  510.38    5242  509.28  5336.5   509.1  5356.5     504  5392.8  507.78
  5516.5   511.9  6226.5  518.82  6619.1  532.37  6696.5   537.7  6806.5  539.66
#Mann= 13 ,-1 , 0
  1652.4      .1       0  1693.7     .08       0  1697.7     .05       0
  1801.9      .1       0  4862.6     .16       0  4976.7     .07       0
  5008.4     .16       0  5045.3      .1       0  5143.6     .12       0
  5198.9      .1       0    5242     .12       0  5392.8      .1       0
  6619.1     .05       0
Bank Sta=4976.7,5008.4
XS Rating Curve= 0 ,0
Exp/Cntr=0.3,0.1

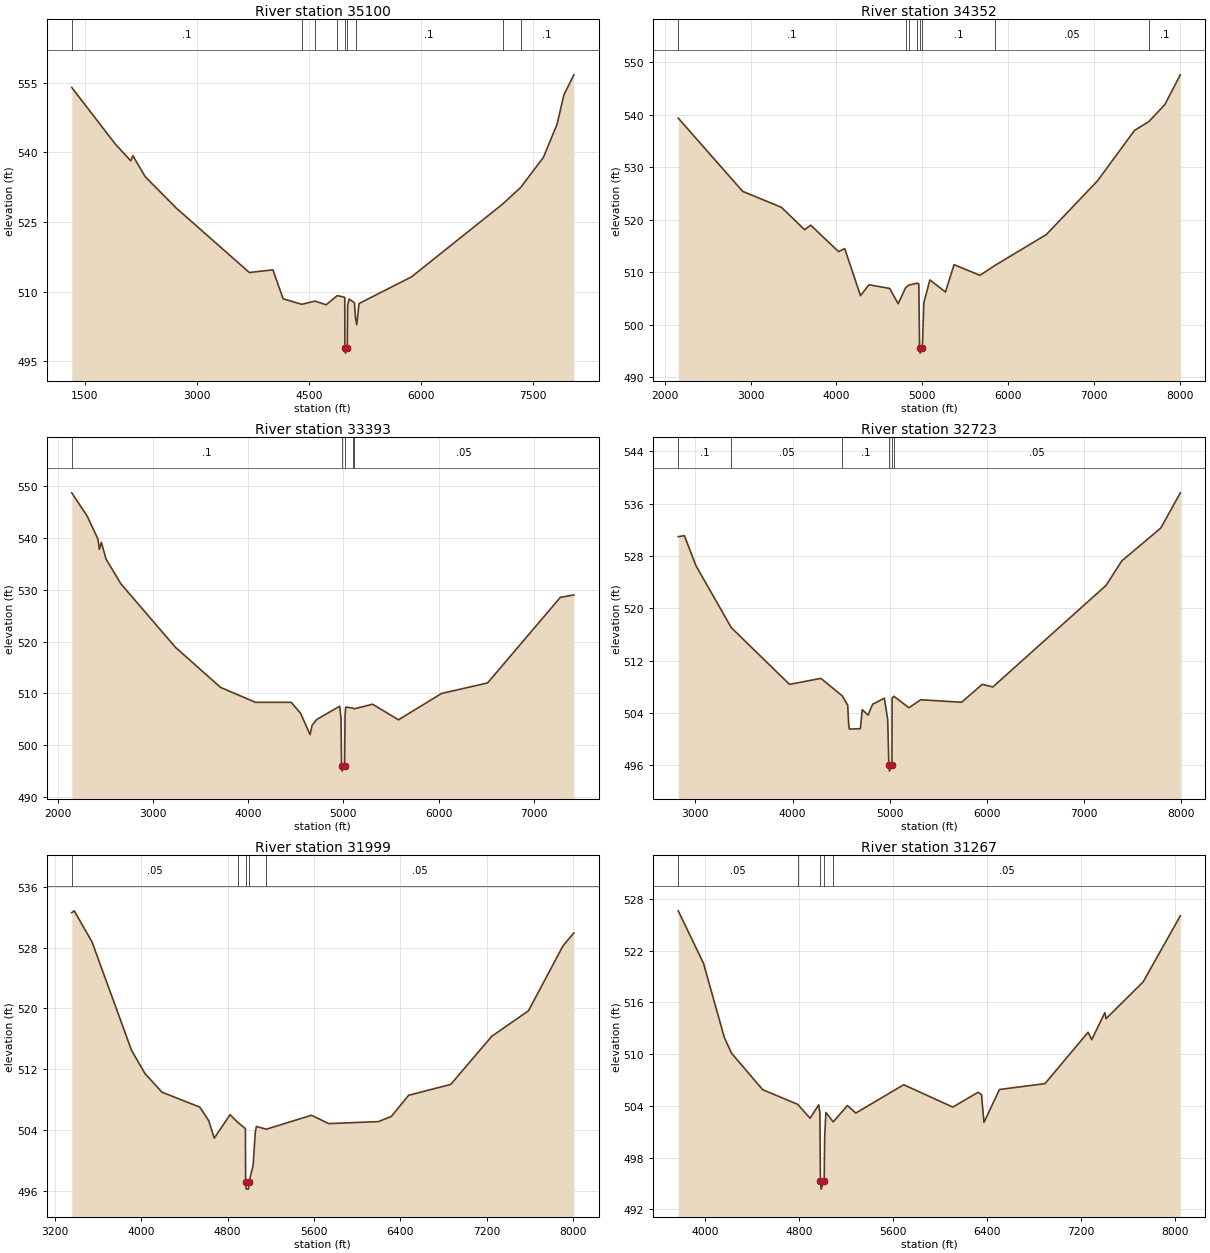
Type RM Length L Ch R = 1 ,35100   ,748,748,748
BEGIN DESCRIPTION:
Black Creek 36.0
END DESCRIPTION:
XS GIS Cut Line= 3
      1985724.96     13524274.97        1982725.       13522175.
      1979725.03     13521575.01
#Sta/Elev= 30
  1323.6  553.97  1905.5   541.8  2113.9  538.16  2141.4  539.28  2307.5  534.74
  2724.3  527.97  3700.8  514.11  4016.4  514.68  4153.3  508.44  4402.8  507.26
  4580.5  507.95  4727.9  507.15  4877.3  509.13  4978.1  508.77  4979.8  497.74
  4985.9  496.74  5011.6  497.74  5016.1  506.98  5036.5  508.39  5107.9  507.59
    5122  504.33  5138.5  502.85  5169.1  507.42  5872.7  513.18    7094  528.89
  7332.8  532.43    7637  538.91  7820.6  546.07  7912.4  552.42  8044.9   556.7
#Mann= 9 ,-1 , 0
  1323.6      .1       0  4402.8     .16       0  4580.5      .1       0
  4877.3     .16       0  4979.8     .07       0  5011.6     .16       0
    5122      .1       0    7094     .05       0  7332.8      .1       0
Bank Sta=4979.8,5011.6
XS Rating Curve= 0 ,0
Exp/Cntr=0.3,0.1

Type RM Length L Ch R = 1 ,34352   ,959,959,959
BEGIN DESCRIPTION:
Black Creek 35.0
END DESCRIPTION:
XS GIS Cut Line= 3
      1985124.98     13523724.98        1983125.       13521725.
      1980124.97       13521425.
#Sta/Elev= 30
  2158.2  539.35  2907.7   525.4  3360.3  522.35    3629  518.09  3699.7  518.96
  4024.9  513.91  4095.6   514.5  4279.5  505.54  4378.5  507.61  4618.9  506.91
  4717.9     504  4803.2  507.01  4840.8  507.54    4938  507.92  4958.3  507.76
  4967.2  495.59  4973.3  494.59    4999  495.59  5016.8  504.17  5087.1  508.53
    5268  506.23  5368.5  511.43    5670  509.41  5850.2  511.35  6441.3  517.16
  7036.8  527.38  7468.9  537.01  7636.5   538.7  7820.7  541.91  8001.6  547.59
#Mann= 8 ,-1 , 0
  2158.2      .1       0  4803.2     .07       0  4840.8     .12       0
    4938      .1       0  4967.2     .07       0    4999      .1       0
  5850.2     .05       0  7636.5      .1       0
Bank Sta=4967.2,4999
XS Rating Curve= 0 ,0
Exp/Cntr=0.3,0.1

Type RM Length L Ch R = 1 ,33393   ,670,670,670
BEGIN DESCRIPTION:
Black Creek 34.0
END DESCRIPTION:
XS GIS Cut Line= 3
        1985525.       13523475.      1983374.76     13521255.82
      1981204.65     13521004.09
#Sta/Elev= 30
  2146.7  548.69  2309.4  544.18  2422.6  539.73  2436.7  537.79  2457.8  539.14
  2507.5  535.89  2662.9  531.13  3235.7   518.9  3709.6  511.16  4077.4  508.28
  4452.2  508.28  4551.2  506.15  4650.2  502.05  4671.4  503.85    4721  504.98
  4961.3  507.53  4975.4  505.18  4980.8  496.01  4986.9  495.01  5012.6  496.01
  5017.9  505.94    5025  507.37  5099.3  507.18    5114  507.02    5307  507.92
  5578.8  504.91  6031.8  509.99    6515  512.02  7279.2  528.52  7421.4     529
#Mann= 5 ,-1 , 0
  2146.7      .1       0  4980.8     .07       0  5012.6      .1       0
  5099.3      .1       0    5114     .05       0
Bank Sta=4980.8,5012.6
XS Rating Curve= 0 ,0
Exp/Cntr=0.3,0.1

Type RM Length L Ch R = 1 ,32723   ,724,724,724
BEGIN DESCRIPTION:
Black Creek 33.0
END DESCRIPTION:
XS GIS Cut Line= 3
        1985725.       13521625.        1983725.       13520825.
      1980725.03       13520525.
#Sta/Elev= 30
  2823.4  530.95  2886.7   531.1  3006.5  526.49    3370  517.04  3969.1  508.37
  4292.2  509.29  4513.7  506.59  4568.2  505.18    4579  502.08  4585.7  501.53
  4698.8   501.6  4717.6  504.51  4776.9  503.68  4825.3  505.33  4945.2  506.27
    4980  503.02  4991.7  496.11  4997.8  495.11  5023.5  496.11  5025.2  506.27
  5043.9  506.55  5198.6   504.8  5319.2  506.02  5741.3  505.64  5952.3  508.37
  6062.9  507.98  7228.6  523.51  7389.4  527.24  7791.4  532.26  7992.4  537.65
#Mann= 6 ,-1 , 0
  2823.4      .1       0    3370     .05       0  4513.7      .1       0
  4991.7     .07       0  5023.5      .1       0  5043.9     .05       0
Bank Sta=4991.7,5023.5
XS Rating Curve= 0 ,0
Exp/Cntr=0.3,0.1

Type RM Length L Ch R = 1 ,31999   ,732,732,732
BEGIN DESCRIPTION:
Black Creek 32.0
END DESCRIPTION:
XS GIS Cut Line= 3
      1985825.03     13520024.99        1984225.       13520425.
      1981224.98       13520425.
#Sta/Elev= 30
  3356.7  532.62  3379.9  532.86  3544.9  528.74  3910.8  514.47  4034.5  511.44
  4191.7  508.98  4542.1  507.01  4624.6  505.24  4676.1  502.93    4823  506.01
  4891.6  505.02  4964.7  504.18  4966.8  497.21    4973  496.21  4992.6  496.21
  4998.7  497.21    5036  499.32    5056  503.69    5066  504.46  5158.8   504.1
    5576  505.94    5736  504.84    6196   505.1    6316  505.78    6476  508.57
    6866     510    7246  516.34    7586   519.7    7906  528.26    8006  529.95
#Mann= 5 ,-1 , 0
  3356.7     .05       0  4891.6      .1       0  4966.8     .07       0
  4998.7      .1       0  5158.8     .05       0
Bank Sta=4966.8,4998.7
XS Rating Curve= 0 ,0
Exp/Cntr=0.3,0.1

Type RM Length L Ch R = 1 ,31267   ,713,713,713
BEGIN DESCRIPTION:
Black Creek 31.0
END DESCRIPTION:
XS GIS Cut Line= 3
      1985574.97     13519974.99        1984375.       13519775.
      1981375.03     13520374.99
#Sta/Elev= 30
    3769  526.62  3984.4  520.53  4161.8  511.93  4222.6  510.12  4488.8  505.88
  4786.4  504.19  4891.7  502.58  4965.2  504.13  4975.4  503.24  4979.8  495.36
  4985.9  494.36  5011.7  495.36  5016.1  500.35  5026.3  503.25  5089.2  502.16
  5209.9  504.05  5281.3  503.18  5689.2  506.46  6107.3  503.87  6321.5  505.58
  6352.1  505.32  6372.5   502.1    6505  505.91  6892.6  506.59  7259.7  512.55
  7290.3  511.68  7402.5  514.82  7412.7  514.12  7728.8  518.39  8044.9  526.04
#Mann= 5 ,-1 , 0
    3769     .05       0  4786.4      .1       0  4979.8     .07       0
  5011.7      .1       0  5089.2     .05       0
Bank Sta=4979.8,5011.7
XS Rating Curve= 0 ,0
Exp/Cntr=0.3,0.1

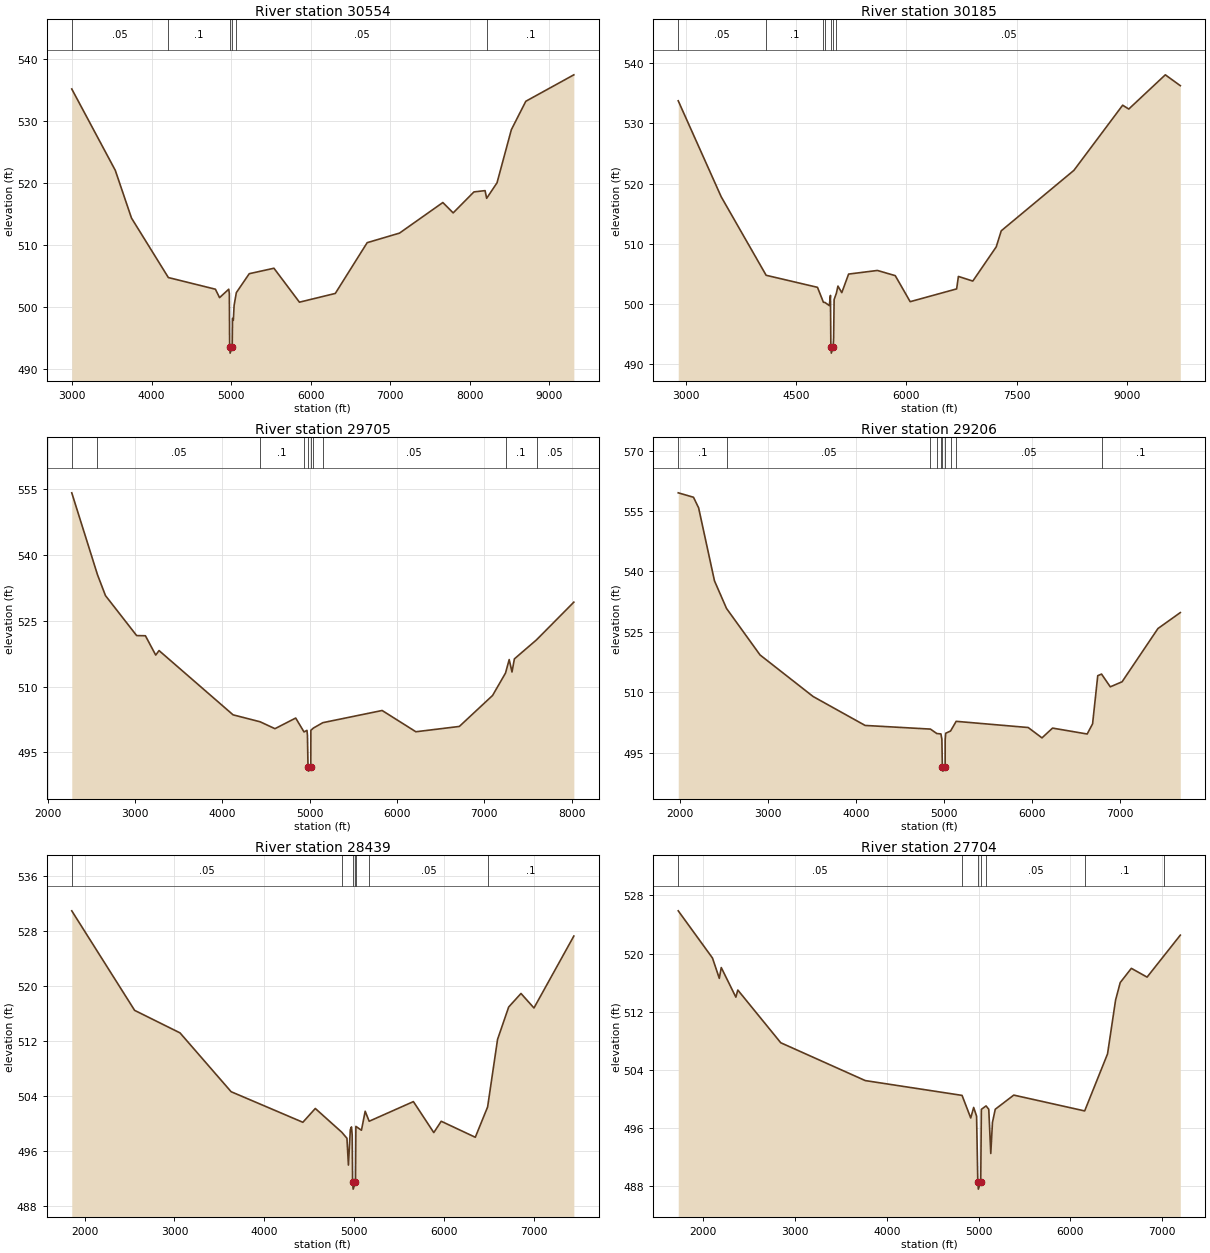
Type RM Length L Ch R = 1 ,30554   ,369,369,369
BEGIN DESCRIPTION:
Black Creek 30.0
END DESCRIPTION:
XS GIS Cut Line= 3
      1985924.99     13519974.99        1984125.       13519175.
       1979790.7     13519366.84
#Sta/Elev= 30
  2997.9  535.15    3545  522.03  3748.2  514.35  4211.5  504.76  4802.8  502.88
  4854.8  501.52  4970.2  502.88  4977.7  502.18  4981.7  493.58  4987.9  492.58
  5013.6  493.58  5017.7  498.17  5027.7  497.87  5037.7  500.28  5065.7  502.33
  5227.9  505.38  5538.2  506.26  5858.5  500.79    6309   502.2  6709.4  510.38
  7115.5  511.92  7660.3  516.85    7790  515.18  8050.7  518.56  8190.8  518.77
  8210.7  517.53    8341  520.03  8521.1  528.59  8702.8  533.17  9306.2  537.43
#Mann= 6 ,-1 , 0
  2997.9     .05       0  4211.5      .1       0  4981.7     .07       0
  5013.6      .1       0  5065.7     .05       0  8210.7      .1       0
Bank Sta=4981.7,5013.6
XS Rating Curve= 0 ,0
Exp/Cntr=0.3,0.1

Type RM Length L Ch R = 1 ,30185   ,480,480,480
BEGIN DESCRIPTION:
Mapping XS a0f925b1
END DESCRIPTION:
XS GIS Cut Line= 3
      1985893.15     13519905.03      1983740.38     13518646.35
      1979558.17     13517535.72
#Sta/Elev= 30
  2900.6  533.76  3484.3  517.83  4094.8   504.8  4792.6   502.8    4873  500.32
  4894.3  500.29  4952.9  499.77  4968.6  501.46  4974.1  492.88  4980.3  491.88
    5006  492.88  5011.6  494.43  5018.3  500.77  5049.2  501.83  5070.3  503.01
  5122.6  501.92  5215.2     505  5606.8   505.6  5848.8  504.74  6051.7  500.42
  6682.9  502.54  6706.8  504.61  6902.5  503.84  7220.9  509.52  7288.7  512.18
  8276.3  522.22  8938.4  533.03  9021.2  532.39  9517.8  538.07  9721.5  536.27
#Mann= 7 ,-1 , 0
  2900.6     .05       0  4094.8      .1       0    4873     .07       0
  4894.3      .1       0  4974.1     .07       0    5006      .1       0
  5049.2     .05       0
Bank Sta=4974.1,5006
XS Rating Curve= 0 ,0
Exp/Cntr=0.3,0.1

Type RM Length L Ch R = 1 ,29705   ,499,499,499
BEGIN DESCRIPTION:
Black Creek 29.0
END DESCRIPTION:
XS GIS Cut Line= 4
      1986631.02     13519627.26      1983948.72     13518299.13
      1982830.73     13517861.83      1981466.15     13517109.93
#Sta/Elev= 30
  2273.7   554.1  2568.4  535.46  2659.8  530.71  3016.9  521.61  3117.3  521.57
  3235.5  517.17  3273.5   518.2  4121.6  503.57  4431.4  501.99  4601.4  500.42
    4839  502.84  4934.2  499.68    4968  500.04  4973.6  498.91    4980  491.76
  4986.2  490.76  5011.9  491.76  5012.8  500.05  5042.3  500.57  5150.3  501.79
  5829.2  504.56  6215.7  499.72  6713.6  500.93  7094.4  507.98  7242.5  513.08
  7284.7  516.15  7316.8  513.32  7344.3  516.31  7597.7  520.64  8025.3  529.22
#Mann= 10 ,-1 , 0
  2273.7      .1       0  2568.4     .05       0  4431.4      .1       0
  4934.2     .12       0    4980     .07       0  5011.9     .12       0
  5042.3      .1       0  5150.3     .05       0  7242.5      .1       0
  7597.7     .05       0
Bank Sta=4980,5011.9
XS Rating Curve= 0 ,0
Exp/Cntr=0.3,0.1

Type RM Length L Ch R = 1 ,29206   ,767,767,767
BEGIN DESCRIPTION:
Black Creek 28.0
END DESCRIPTION:
XS GIS Cut Line= 3
       1986917.5     13519540.47        1984325.       13517975.
      1981924.97     13516774.99
#Sta/Elev= 30
  1975.4  559.54  2149.1  558.44  2207.3  555.81  2387.8  537.67  2524.7  530.82
    2906  519.27  3509.5  508.95  4101.4  501.76  4844.8  500.85  4916.9  499.75
  4963.9  499.65  4974.8  498.36  4980.2  491.41  4986.3  490.41  5012.1  491.41
  5012.3  498.22  5017.9  499.81  5073.7  500.38  5137.4  502.78    5957  501.24
  6113.5  498.67  6233.7   501.1  6627.8  499.63  6689.3  502.17    6748  514.12
    6791  514.52  6890.6  511.35  7024.7   512.6  7432.8  525.83  7687.2  529.79
#Mann= 10 ,-1 , 0
  1975.4      .1       0  2524.7     .05       0  4844.8      .1       0
  4916.9     .07       0  4963.9     .12       0  4980.2     .07       0
  5012.1     .12       0  5073.7      .1       0  5137.4     .05       0
    6791      .1       0
Bank Sta=4980.2,5012.1
XS Rating Curve= 0 ,0
Exp/Cntr=0.3,0.1

Type RM Length L Ch R = 1 ,28439   ,735,735,735
BEGIN DESCRIPTION:
Black Creek 27.0
END DESCRIPTION:
XS GIS Cut Line= 3
      1987429.65     13518333.86        1984475.       13517375.
      1982075.01       13516775.
#Sta/Elev= 30
  1858.4  530.98  2557.2  516.49  3061.8  513.21  3629.5  504.65  4426.8   500.2
  4565.2  502.21  4860.3  498.74  4916.8  497.87  4933.2  493.97  4954.2  499.13
  4967.3  499.53  4975.1  498.34  4979.7  491.47  4985.9  490.47  5011.6  491.47
  5013.8  495.28  5016.3   499.6  5078.1  499.04  5119.4  501.81  5163.8  500.35
  5655.4  503.21  5882.1   498.7  5964.6  500.35  6343.4  498.02  6480.2  502.43
  6590.8  512.27  6714.5  516.98  6851.1  518.95  6995.4  516.84  7438.6  527.31
#Mann= 7 ,-1 , 0
  1858.4     .05       0  4860.3     .12       0  4979.7     .07       0
  5011.6     .12       0  5013.8      .1       0  5163.8     .05       0
  6480.2      .1       0
Bank Sta=4979.7,5011.6
XS Rating Curve= 0 ,0
Exp/Cntr=0.3,0.1

Type RM Length L Ch R = 1 ,27704   ,810,810,810
BEGIN DESCRIPTION:
Black Creek 26.0
END DESCRIPTION:
XS GIS Cut Line= 3
      1987516.43      13517821.7        1984425.       13516725.
      1982256.04     13516450.17
#Sta/Elev= 30
  1730.1  525.88    2103  519.38  2177.3  516.58  2198.5  518.07  2357.6  513.99
  2378.9  514.97  2846.4  507.71  3766.3   502.5  4820.3  500.46  4914.8  497.35
  4946.6   498.8  4978.5   497.6  4991.7  488.55  4997.8  487.55  5023.6  488.55
  5030.5  498.54  5081.6  499.01  5111.1  498.55    5133  492.46  5151.4  496.74
  5181.7  498.55  5383.3   500.5  6155.3  498.32  6404.4  506.18    6492   513.6
  6542.4     516  6663.4  517.96  6834.8  516.75  7020.1  519.71  7196.6  522.53
#Mann= 7 ,-1 , 0
  1730.1     .05       0  4820.3      .1       0  4991.7     .07       0
  5023.6      .1       0  5081.6     .05       0  6155.3      .1       0
  7020.1     .05       0
Bank Sta=4991.7,5023.6
XS Rating Curve= 0 ,0
Exp/Cntr=0.3,0.1

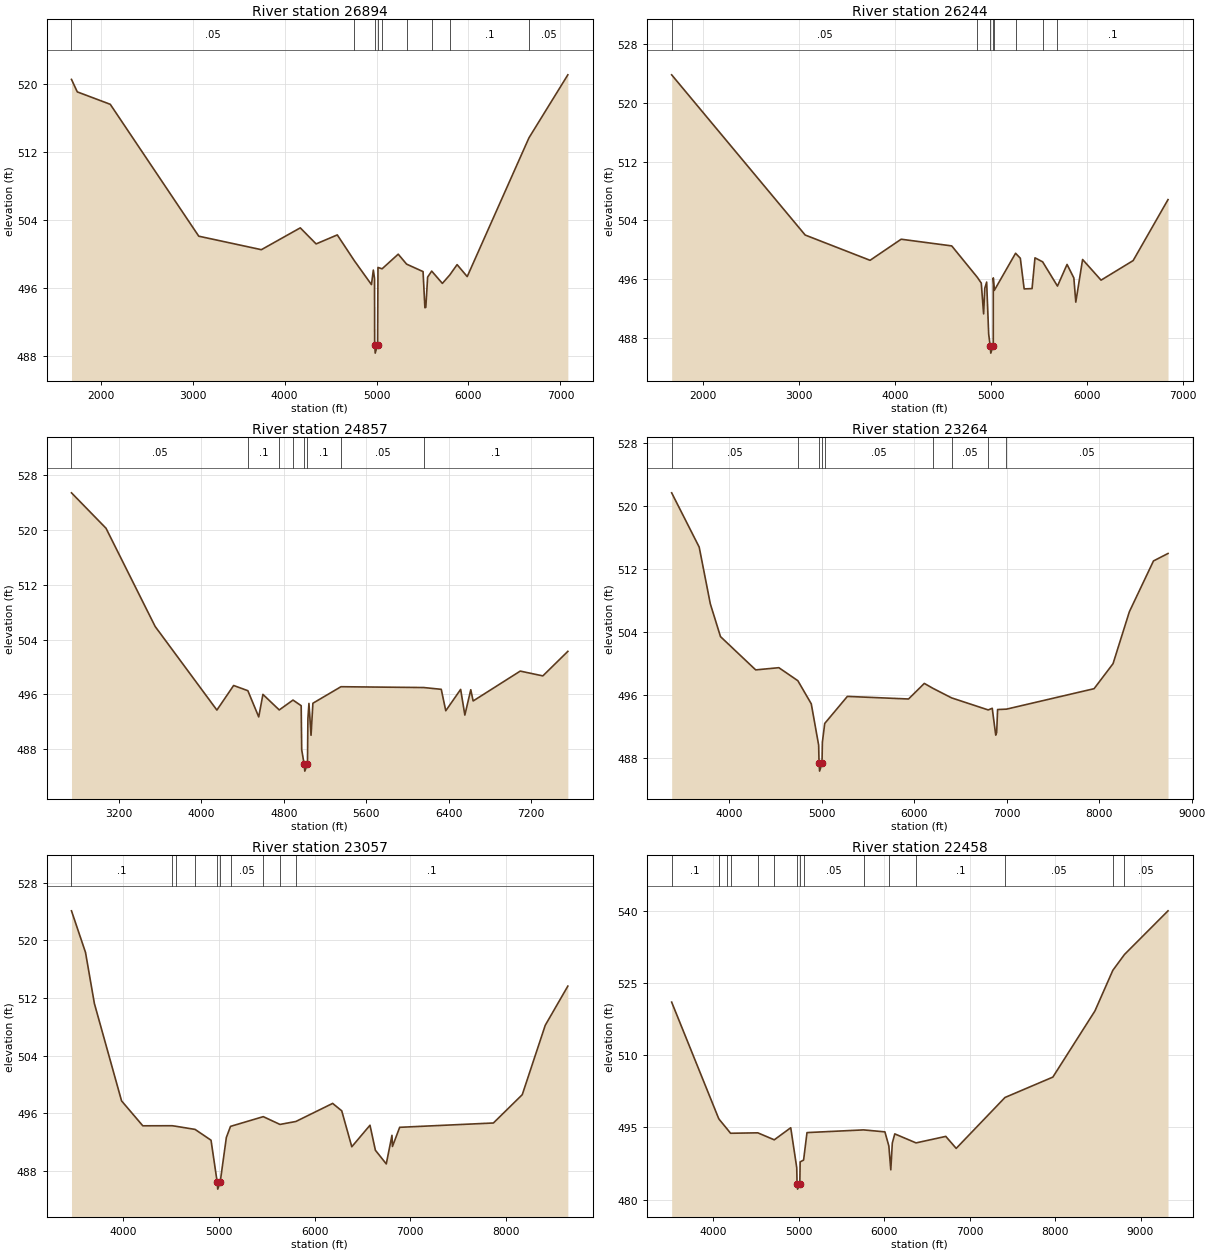
Type RM Length L Ch R = 1 ,26894   ,650,650,650
BEGIN DESCRIPTION:
Black Creek 25.0
END DESCRIPTION:
XS GIS Cut Line= 3
       1987516.4     13516884.19        1984325.       13516075.
      1982221.28     13516128.99
#Sta/Elev= 30
  1683.4  520.53  1746.7  519.06    2105   517.6  3067.2  502.07  3748.1  500.48
  4171.1  503.05  4343.2  501.16  4573.4  502.22  4759.6  499.17  4944.8  496.37
  4965.5  498.08  4978.3  497.09  4979.8   489.3  4985.9   488.3  5011.8   489.3
  5015.8  498.39  5060.5  498.23  5235.9  499.95    5327  498.78    5506   497.9
    5526  493.65    5536  493.69  5555.7  497.25  5599.9  497.96    5716  496.51
    5796   497.5  5876.1  498.72  5986.1  497.31  6657.4  513.65  7080.2  521.07
#Mann= 9 ,-1 , 0
  1683.4     .05       0  4759.6      .1       0  4979.8     .07       0
  5011.8      .1       0  5060.5     .05       0    5327      .1       0
  5599.9     .05       0    5796      .1       0  6657.4     .05       0
Bank Sta=4979.8,5011.8
XS Rating Curve= 0 ,0
Exp/Cntr=0.3,0.1

Type RM Length L Ch R = 1 ,26244   ,1387,1387,1387
BEGIN DESCRIPTION:
Black Creek 24.0
END DESCRIPTION:
XS GIS Cut Line= 3
      1987611.94     13516623.79      1984104.97     13515425.86
      1982656.01     13515660.13
#Sta/Elev= 30
  1674.7   523.8  3066.4     502  3742.7  498.56  4066.7  501.43  4593.9  500.52
  4861.7  496.23  4901.8  495.46  4926.2  491.27  4938.4  494.75  4957.9   495.6
    4979  488.53  4994.7  486.93  5000.9  485.93  5026.7  486.93  5027.1  496.17
  5037.8  494.47  5259.4  499.52  5308.9  498.84  5348.9  494.67  5431.2  494.71
  5461.6   498.9  5541.6  498.35  5696.1  495.05  5795.9     498  5866.8  496.16
  5887.1  492.87    5958  498.67  6150.5  495.86  6484.7  498.52  6848.4  506.82
#Mann= 8 ,-1 , 0
  1674.7     .05       0  4861.7      .1       0  4994.7     .07       0
  5026.7      .1       0  5037.8     .05       0  5259.4      .1       0
  5541.6     .05       0  5696.1      .1       0
Bank Sta=4994.7,5026.7
XS Rating Curve= 0 ,0
Exp/Cntr=0.3,0.1

Type RM Length L Ch R = 1 ,24857   ,1593,1593,1593
BEGIN DESCRIPTION:
Black Creek 22.0
END DESCRIPTION:
XS GIS Cut Line= 3
      1987275.02       13515175.      1984348.02     13514661.98
      1982664.02     13515417.17
#Sta/Elev= 30
  2738.3  525.41  3073.4  520.24  3550.5   505.9  4149.5   493.7    4312  497.29
    4450  496.53  4555.6   492.7  4596.2  495.99  4754.7  493.72  4888.1  495.16
  4967.6  494.34  4972.6   487.9  4996.5  485.79  5002.6  484.79  5028.5  485.79
  5032.8  492.44  5042.9  494.67  5063.2  490.02  5081.3   494.7  5353.6  497.11
  6157.3  496.99    6327  496.73  6370.8   493.6  6515.2  496.72    6556  492.97
  6613.4  496.67  6636.5  495.03  7093.4  499.39  7312.9  498.69  7555.5  502.27
#Mann= 8 ,-1 , 0
  2738.3     .05       0    4450      .1       0  4754.7     .05       0
  4888.1      .1       0  4996.5     .07       0  5028.5      .1       0
  5353.6     .05       0  6157.3      .1       0
Bank Sta=4996.5,5028.5
XS Rating Curve= 0 ,0
Exp/Cntr=0.3,0.1

Type RM Length L Ch R = 1 ,23264   ,207,207,207
BEGIN DESCRIPTION:
Black Creek 23.0
END DESCRIPTION:
XS GIS Cut Line= 3
      1987412.31     13513707.11      1984999.06     13513819.96
      1982058.18     13514045.52
#Sta/Elev= 30
  3378.4  521.67    3676  514.77  3796.2  507.56  3906.3  503.39  4286.7  499.16
    4537  499.44  4742.1  497.79  4887.4  494.85  4967.4  489.59  4971.5  487.29
  4977.6  486.29  5003.5  487.29  5007.5  489.95  5032.9  492.35  5277.8  495.79
  5938.8  495.46  6109.3  497.44  6206.9  496.79  6404.6   495.6    6800  494.07
  6843.7  494.28  6881.5  490.86  6891.6  491.21  6901.6  494.12  6997.7  494.17
  7944.6  496.77  8149.4  499.95  8325.8  506.55  8586.5  513.01  8743.8  513.96
#Mann= 9 ,-1 , 0
  3378.4     .05       0  4742.1      .1       0  4971.5     .07       0
  5003.5      .1       0  5032.9     .05       0  6206.9      .1       0
  6404.6     .05       0    6800      .1       0  6997.7     .05       0
Bank Sta=4971.5,5003.5
XS Rating Curve= 0 ,0
Exp/Cntr=0.3,0.1

Type RM Length L Ch R = 1 ,23057   ,599,599,599
BEGIN DESCRIPTION:
Black Creek 21.0
END DESCRIPTION:
XS GIS Cut Line= 3
      1987356.94     13513434.76      1986006.01     13513576.91
      1982178.95     13513793.86
#Sta/Elev= 30
  3456.1  524.11  3602.8  518.34  3695.8  511.24  3979.9  497.73  4202.1  494.27
    4509  494.28  4550.3   494.2  4748.7  493.77  4915.7  492.27  4979.8  486.48
  4985.9  485.48  5011.8  486.48  5075.9  492.65  5119.5  494.19  5461.9  495.54
    5637  494.46  5803.2  494.87  6187.7  497.38  6282.7  496.35    6388  491.36
  6578.3  494.35  6634.7  490.88  6748.6  488.98  6808.2  492.95  6813.2   491.4
  6888.8  494.06  7869.1  494.66  8170.9  498.59  8411.3  508.22  8647.7  513.66
#Mann= 10 ,-1 , 0
  3456.1      .1       0    4509     .05       0  4550.3     .08       0
  4748.7      .1       0  4979.8     .07       0  5011.8      .1       0
  5119.5     .05       0  5461.9     .08       0    5637     .05       0
  5803.2      .1       0
Bank Sta=4979.8,5011.8
XS Rating Curve= 0 ,0
Exp/Cntr=0.3,0.1

Type RM Length L Ch R = 1 ,22458   ,340,340,340
BEGIN DESCRIPTION:
Black Creek 20.0
END DESCRIPTION:
XS GIS Cut Line= 3
      1987326.51     13512935.63      1985078.27     13513065.84
      1981824.97     13511624.99
#Sta/Elev= 30
  3511.8  520.99  4060.5  496.89  4069.4  496.62  4161.5  494.64  4201.1  493.76
    4520  493.85  4712.9   492.4  4905.6  494.91  4975.9  486.62  4979.8  483.16
  4985.9  482.16  5011.8  483.16  5015.8  487.82    5056  488.19    5096   493.9
  5757.8  494.46    6008  494.05  6054.2  491.11  6076.8  486.17  6094.6  491.73
  6123.4  493.63  6372.4  491.76  6720.5  493.11  6842.4  490.62  7413.4  501.19
  7973.6  505.42  8466.6  519.17  8675.7  527.59    8812  530.88  9321.9  539.95
#Mann= 16 ,-1 , 0
  3511.8      .1       0  4060.5     .16       0  4069.4      .1       0
  4161.5     .16       0  4201.1      .1       0    4520     .07       0
  4712.9      .1       0  4979.8     .07       0  5011.8      .1       0
    5056     .05       0  5757.8      .1       0  6054.2     .07       0
  6372.4      .1       0  7413.4     .05       0  8675.7     .08       0
    8812     .05       0
Bank Sta=4979.8,5011.8
XS Rating Curve= 0 ,0
Exp/Cntr=0.3,0.1