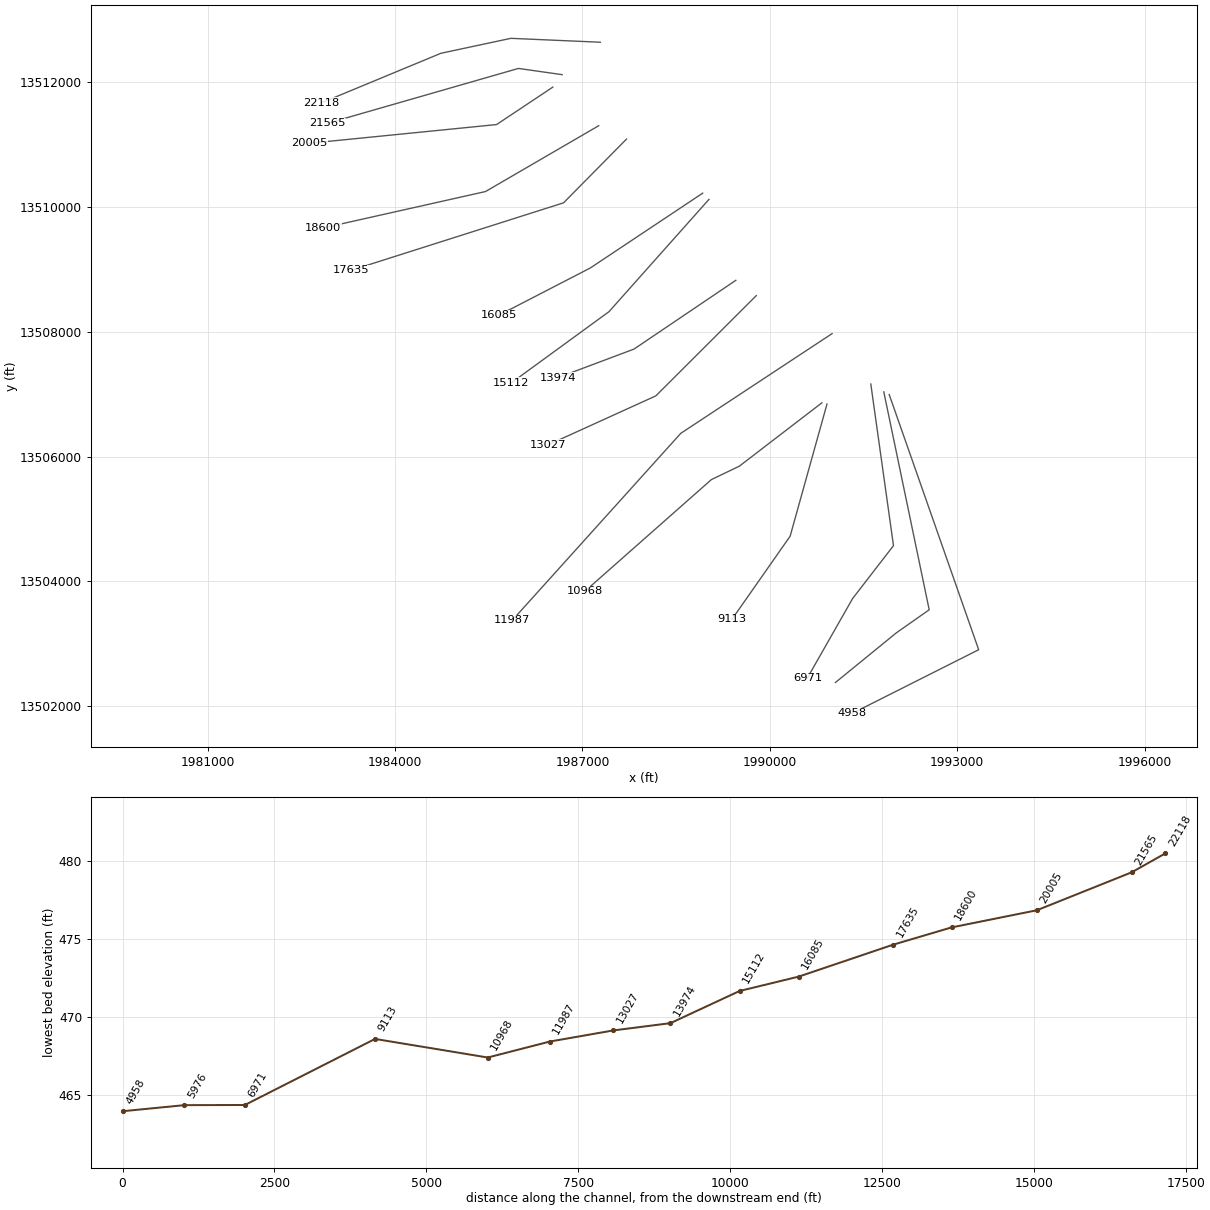
HEC-RAS study Black Creek.prj: Black Creek Base Level Engineering

--- Black Creek.g01 (geometry) --- (continued)

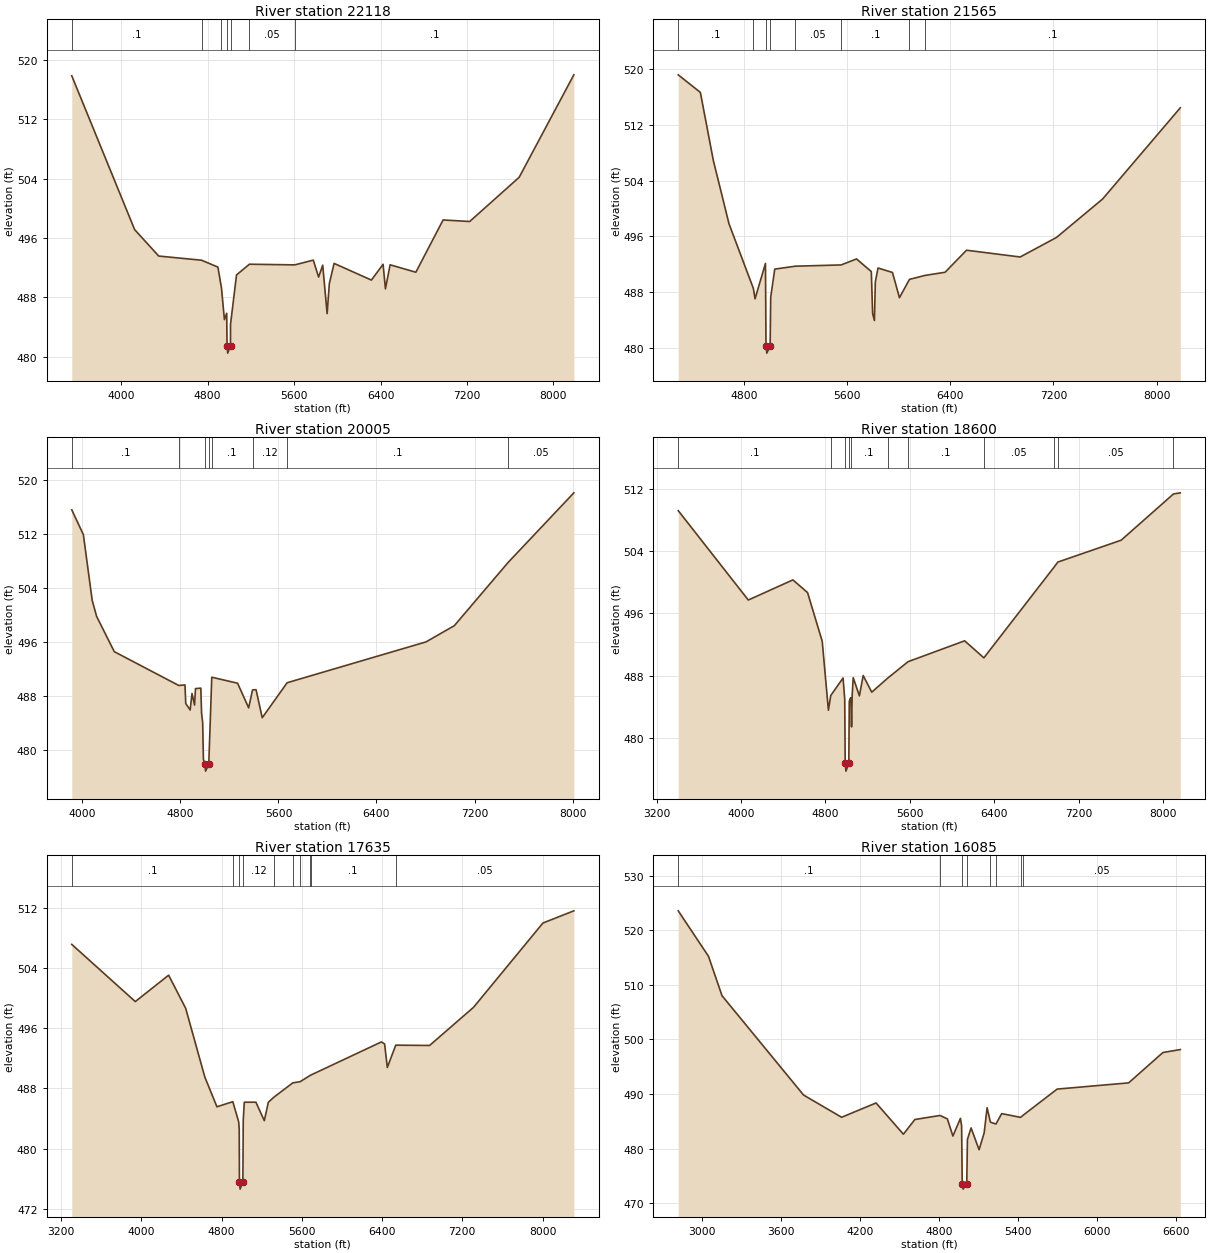
Type RM Length L Ch R = 1 ,22118   ,553,553,553
BEGIN DESCRIPTION:
Black Creek 19.0
END DESCRIPTION:
XS GIS Cut Line= 4
      1987286.12     13512645.03       1985853.8     13512707.53
        1984734.     13512467.95      1982824.96     13511674.98
#Sta/Elev= 30
  3542.8  517.87  4124.5  497.13  4347.3  493.56  4743.9     493  4895.2  492.07
  4928.3  489.24  4955.3  484.99  4976.5  485.85  4979.7  481.47  4985.9  480.47
  5011.7  481.47  5011.8  484.35  5067.3  491.01  5186.3  492.46  5606.4  492.37
  5777.6  493.01  5827.1  490.73  5864.9  492.33  5905.8   485.8  5926.3  489.85
  5970.4  492.57  6315.4  490.32  6423.7  492.45  6445.4  489.14  6488.7  492.38
  6726.9  491.38    6979  498.43    7225  498.22  7682.8  504.18  8188.8     518
#Mann= 7 ,-1 , 0
  3542.8      .1       0  4743.9     .12       0  4928.3      .1       0
  4979.7     .07       0  5011.7      .1       0  5186.3     .05       0
  5606.4      .1       0
Bank Sta=4979.7,5011.7
XS Rating Curve= 0 ,0
Exp/Cntr=0.3,0.1

Type RM Length L Ch R = 1 ,21565   ,1560,1560,1560
BEGIN DESCRIPTION:
Black Creek 18.0
END DESCRIPTION:
XS GIS Cut Line= 3
      1986675.02       13512125.        1985975.       13512225.
      1982911.07     13511342.94
#Sta/Elev= 30
  4288.5  519.18  4460.2  516.66  4561.3  506.86  4682.5  497.81  4871.3  488.55
  4884.5  487.05  4965.3  492.13  4969.5  480.26  4975.7  479.26  5001.5  480.26
    5006  487.27  5037.3  491.31  5196.9  491.73  5552.1  491.91    5672  492.77
  5786.5  490.96  5796.9  484.93  5810.7  483.94  5817.7  489.47  5838.5  491.47
  5950.7  490.83    6005  487.21  6082.7  489.84  6204.3  490.41  6358.8  490.86
  6525.3  494.02  6941.6  493.05  7223.2  495.85  7580.8  501.36    8184  514.45
#Mann= 8 ,-1 , 0
  4288.5      .1       0  4871.3     .12       0  4969.5     .07       0
  5001.5     .12       0  5196.9     .05       0  5552.1      .1       0
  6082.7     .12       0  6204.3      .1       0
Bank Sta=4969.5,5001.5
XS Rating Curve= 0 ,0
Exp/Cntr=0.3,0.1

Type RM Length L Ch R = 1 ,20005   ,1405,1405,1405
BEGIN DESCRIPTION:
Black Creek 17.0
END DESCRIPTION:
XS GIS Cut Line= 3
      1986524.99     13511924.99        1985625.       13511325.
      1982625.02       13511025.
#Sta/Elev= 30
  3913.7  515.59  4008.3  511.91  4080.4  502.16  4116.5  499.78  4260.7  494.55
  4787.2  489.53  4837.6  489.62  4843.6  486.86  4879.7   485.9  4894.7  488.34
  4915.7  486.63  4923.2  489.07  4966.8  489.14  4972.8  485.45  4981.8  484.03
  4987.8   478.6  4999.5  477.83  5005.6  476.83  5031.5  477.83    5056  490.76
  5266.7  489.87  5357.1  486.22  5388.7  488.88  5417.4  488.91  5467.7  484.75
    5671  489.94  6804.3     496  7035.5  498.41  7472.4  507.75  8010.3  518.11
#Mann= 8 ,-1 , 0
  3913.7      .1       0  4787.2     .12       0  4999.5     .07       0
  5031.5     .12       0    5056      .1       0  5388.7     .12       0
    5671      .1       0  7472.4     .05       0
Bank Sta=4999.5,5031.5
XS Rating Curve= 0 ,0
Exp/Cntr=0.3,0.1

Type RM Length L Ch R = 1 ,18600   ,965,965,965
BEGIN DESCRIPTION:
Black Creek 16.0
END DESCRIPTION:
XS GIS Cut Line= 3
      1987260.09     13511306.52      1985447.55     13510250.94
      1982850.36     13509667.61
#Sta/Elev= 30
  3404.8  509.21    4069  497.72  4491.7  500.31  4630.7  498.68  4769.7  492.42
  4828.4  483.56  4850.5  485.45  4967.4   487.7  4983.1  484.96  4987.5  476.73
  4994.4  475.73  5021.8  476.73  5026.1  484.71    5038  485.16  5041.9  485.06
  5047.6  481.42  5053.9  485.56  5063.4  487.74  5122.1  485.41  5158.1  488.02
  5239.1  485.88    5391  487.69  5583.7   489.8  6119.9  492.48  6301.9  490.29
  6962.9  501.87  7003.3   502.6  7603.3  505.41  8099.1  511.35  8164.2   511.5
#Mann= 11 ,-1 , 0
  3404.8      .1       0  4850.5     .12       0  4987.5     .07       0
  5021.8     .12       0    5038      .1       0    5391     .05       0
  5583.7      .1       0  6301.9     .05       0  6962.9     .08       0
  7003.3     .05       0  8099.1      .1       0
Bank Sta=4987.5,5021.8
XS Rating Curve= 0 ,0
Exp/Cntr=0.3,0.1

Type RM Length L Ch R = 1 ,17635   ,1550,1550,1550
BEGIN DESCRIPTION:
Black Creek 15.0
END DESCRIPTION:
XS GIS Cut Line= 3
      1987704.46     13511091.19      1986697.55     13510070.38
      1983294.78     13508987.05
#Sta/Elev= 30
  3307.2  507.14  3940.5  499.54  4272.8  503.05  4442.6  498.65  4633.5  489.52
  4754.2  485.56  4912.7  486.24  4971.2  483.55  4976.5  482.57  4978.4  475.62
  4985.3  474.62  5012.8  475.62  5016.6  483.78  5027.1  486.17  5142.8  486.17
  5226.5  483.72  5266.5  486.16  5323.5  486.85  5510.5  488.74    5584   488.9
  5686.1  489.75  5687.9  489.76  6393.6  494.18  6425.8  493.91  6452.8  490.79
  6536.7  493.75  6874.1  493.71  7311.6  498.77    8004  509.98  8312.1   511.6
#Mann= 10 ,-1 , 0
  3307.2      .1       0  4912.7     .12       0  4978.4     .07       0
  5012.8     .12       0  5323.5      .1       0  5510.5     .05       0
    5584      .1       0  5686.1     .05       0  5687.9      .1       0
  6536.7     .05       0
Bank Sta=4978.4,5012.8
XS Rating Curve= 0 ,0
Exp/Cntr=0.3,0.1

Type RM Length L Ch R = 1 ,16085   ,973,973,973
BEGIN DESCRIPTION:
Black Creek 14.0
END DESCRIPTION:
XS GIS Cut Line= 3
      1988924.98     13510224.99        1987125.       13509025.
      1985663.38     13508269.16
#Sta/Elev= 30
  2820.7  523.55  3050.5  515.21  3152.7  508.01  3771.6  489.81  4060.1  485.74
  4321.5  488.36  4528.8  482.64  4615.9  485.33  4806.6  486.07  4862.3  485.45
  4904.4   482.3  4961.5  485.54  4970.5  484.13  4975.1  473.58    4982  472.58
  5009.5  473.58  5014.4  481.67  5042.2  483.79    5103   479.8  5141.6   482.9
  5163.8  487.48    5189  484.85  5230.6   484.5  5274.5  486.41  5417.6  485.72
  5439.5  486.16  5695.2   490.9  6237.5  492.04  6497.6   497.6  6629.5  498.14
#Mann= 8 ,-1 , 0
  2820.7      .1       0  4806.6     .12       0  4975.1     .07       0
  5009.5     .12       0    5189      .1       0  5230.6     .12       0
  5417.6      .1       0  5439.5     .05       0
Bank Sta=4975.1,5009.5
XS Rating Curve= 0 ,0
Exp/Cntr=0.3,0.1

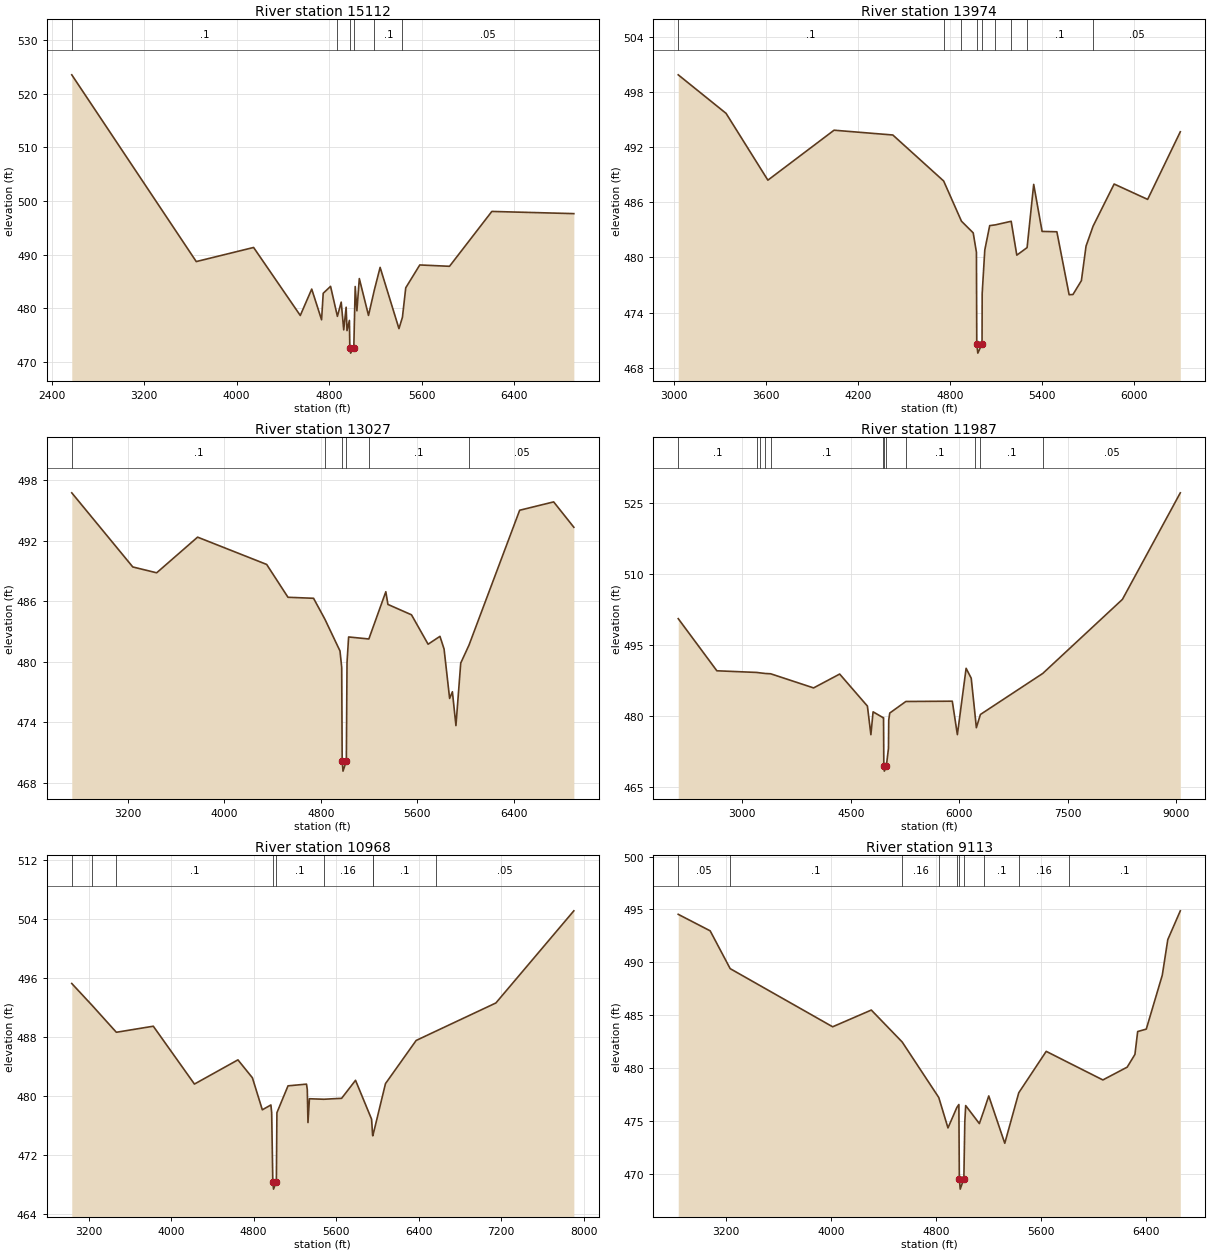
Type RM Length L Ch R = 1 ,15112   ,1138,1138,1138
BEGIN DESCRIPTION:
Black Creek 13.0
END DESCRIPTION:
XS GIS Cut Line= 3
      1989025.02     13510125.03        1987425.       13508325.
      1985863.06     13507184.94
#Sta/Elev= 30
  2573.9  523.55  3650.6  488.73  4146.5  491.36  4550.3  478.68    4649   483.6
  4734.3  477.88  4748.5  482.82  4812.1  484.11  4871.2  478.52  4904.1  481.17
  4925.8     476  4946.7  480.22  4954.2  475.86  4975.1  477.76  4978.6  472.66
  4985.5  471.66    5013  472.66  5025.1  484.08  5039.8  479.55  5060.7  485.56
  5140.2  478.69  5190.9  483.45  5240.6  487.65  5403.6  476.23  5433.5  478.34
  5462.3  483.84  5583.6   488.1  5840.8  487.85  6206.9  498.08    6916  497.67
#Mann= 6 ,-1 , 0
  2573.9      .1       0  4871.2     .12       0  4978.6     .07       0
    5013     .12       0  5190.9      .1       0  5433.5     .05       0
Bank Sta=4978.6,5013
XS Rating Curve= 0 ,0
Exp/Cntr=0.3,0.1

Type RM Length L Ch R = 1 ,13974   ,947,947,947
BEGIN DESCRIPTION:
Black Creek 12.0
END DESCRIPTION:
XS GIS Cut Line= 3
      1989455.09     13508827.31        1987825.       13507725.
      1986600.95     13507264.83
#Sta/Elev= 30
  3027.7  499.85  3339.9  495.66  3612.6   488.4  4044.2  493.83  4427.6  493.31
  4759.3  488.31  4875.5  483.94  4952.1  482.67  4973.1  480.56  4975.3   470.6
  4982.2   469.6  5009.7   470.6  5010.6  476.07  5027.6   480.8  5059.6  483.46
    5096  483.54  5199.8  483.93  5236.5  480.25  5303.6  481.07  5346.7  487.94
  5401.5  482.83  5497.9  482.79  5577.9  475.95  5602.8  475.97  5657.9  477.48
  5688.2  481.23  5733.9  483.39  5871.5  487.98  6090.1  486.31  6303.2  493.66
#Mann= 9 ,-1 , 0
  3027.7      .1       0  4759.3     .12       0  4875.5     .16       0
  4975.3     .07       0  5009.7     .16       0    5096     .16       0
  5199.8     .12       0  5303.6      .1       0  5733.9     .05       0
Bank Sta=4975.3,5009.7
XS Rating Curve= 0 ,0
Exp/Cntr=0.3,0.1

Type RM Length L Ch R = 1 ,13027   ,1040,1040,1040
BEGIN DESCRIPTION:
Black Creek 11.0
END DESCRIPTION:
XS GIS Cut Line= 3
      1989783.24     13508582.54        1988175.       13506975.
      1986455.09      13506191.9
#Sta/Elev= 30
  2734.3  496.76  3240.4   489.4  3438.4  488.82  3777.8  492.36  4350.6  489.65
  4527.4  486.39  4739.5  486.29  4833.2  484.22  4958.7  481.06  4972.8  479.43
  4976.9  470.13  4983.8  469.13  5011.3  470.13    5017  479.91  5030.2  482.45
    5198  482.25  5338.7  486.94  5356.2  485.68  5551.6  484.65  5689.4  481.73
  5787.7  482.51  5821.7  481.26  5867.8  476.35  5890.9  477.01  5920.2  473.65
    5960  479.86  6028.5  481.64  6448.6  495.03  6730.7  495.86    6898  493.34
#Mann= 6 ,-1 , 0
  2734.3      .1       0  4833.2     .12       0  4976.9     .07       0
  5011.3     .12       0    5198      .1       0  6028.5     .05       0
Bank Sta=4976.9,5011.3
XS Rating Curve= 0 ,0
Exp/Cntr=0.3,0.1

Type RM Length L Ch R = 1 ,11987   ,1019,1019,1019
BEGIN DESCRIPTION:
Black Creek 10.0
END DESCRIPTION:
XS GIS Cut Line= 3
      1990996.81     13507973.18        1988575.       13506375.
        1985875.       13503375.
#Sta/Elev= 30
  2115.7  500.56  2649.5  489.57  3199.8  489.22  3241.9  489.14  3318.2     489
  3392.7  488.94  3986.2  485.96  4346.4  488.88  4729.8  482.13  4777.9   476.1
  4808.1  480.92  4950.9  479.65  4952.6  479.68  4956.5  469.42  4963.4  468.42
  4990.9  469.42  5020.7  473.23  5024.4   479.2  5038.6  480.66  5260.8   483.1
  5902.6  483.16  5972.9  476.11  6093.6  490.09  6164.2     488  6209.8  481.38
  6235.2  477.57  6291.2  480.36  7152.7  489.01  8253.3  504.62  9053.4  527.08
#Mann= 12 ,-1 , 0
  2115.7      .1       0  3199.8     .07       0  3241.9      .1       0
  3318.2     .07       0  3392.7      .1       0  4950.9     .12       0
  4956.5     .07       0  4990.9     .12       0  5260.8      .1       0
  6209.8     .05       0  6291.2      .1       0  7152.7     .05       0
Bank Sta=4956.5,4990.9
XS Rating Curve= 0 ,0
Exp/Cntr=0.3,0.1

Type RM Length L Ch R = 1 ,10968   ,1855,1855,1855
BEGIN DESCRIPTION:
Black Creek 9.0
END DESCRIPTION:
XS GIS Cut Line= 4
      1990833.58     13506863.78      1989512.41     13505848.17
      1989064.49     13505632.89      1987040.15     13503842.92
#Sta/Elev= 30
  3037.4  495.27  3232.9  492.33  3469.4  488.66  3827.6  489.48  4226.3  481.64
  4647.7  484.92    4788  482.49  4884.1  478.15  4967.2  478.81  4974.7  477.76
  4985.7   468.4  4992.6   467.4  5020.1   468.4  5025.5  477.76  5133.2   481.4
  5312.2  481.63  5319.8  480.89  5326.4  476.42  5340.6  479.65  5479.4  479.58
  5652.7  479.71  5787.3  482.15  5942.9  476.88  5953.1  474.68  5955.1  474.63
  6077.6   481.7  6374.8  487.55  6570.5  488.84  7147.5  492.63    7903  505.12
#Mann= 9 ,-1 , 0
  3037.4      .1       0  3232.9     .05       0  3469.4      .1       0
  4985.7     .07       0  5020.1      .1       0  5479.4     .16       0
  5953.1     .07       0  5955.1      .1       0  6570.5     .05       0
Bank Sta=4985.7,5020.1
XS Rating Curve= 0 ,0
Exp/Cntr=0.3,0.1

Type RM Length L Ch R = 1 ,9113    ,2142,2142,2142
BEGIN DESCRIPTION:
Black Creek 8.0
END DESCRIPTION:
XS GIS Cut Line= 3
      1990915.19     13506844.68        1990325.       13504725.
      1989394.34     13503393.28
#Sta/Elev= 30
  2836.5  494.54  3079.8  492.98  3232.3  489.41    4013  483.92  4307.4   485.5
  4542.9  482.48  4821.5  477.24  4891.5  474.37  4959.1   476.3  4974.5  476.58
    4978  469.59    4985  468.59  5012.5  469.59  5019.7  474.93  5026.4  476.48
  5130.6  474.78  5169.5  476.17  5202.1  477.39  5324.2  472.92  5430.8  477.69
  5639.9   481.6  5812.3  480.52  6071.6   478.9  6256.8  480.11  6315.8  481.31
  6336.7  483.47  6402.2   483.7  6524.3   488.8  6566.1  492.15  6661.5  494.87
#Mann= 10 ,-1 , 0
  2836.5     .05       0  3232.3      .1       0  4542.9     .16       0
  4821.5      .1       0  4959.1     .16       0    4978     .07       0
  5012.5     .16       0  5169.5      .1       0  5430.8     .16       0
  5812.3      .1       0
Bank Sta=4978,5012.5
XS Rating Curve= 0 ,0
Exp/Cntr=0.3,0.1

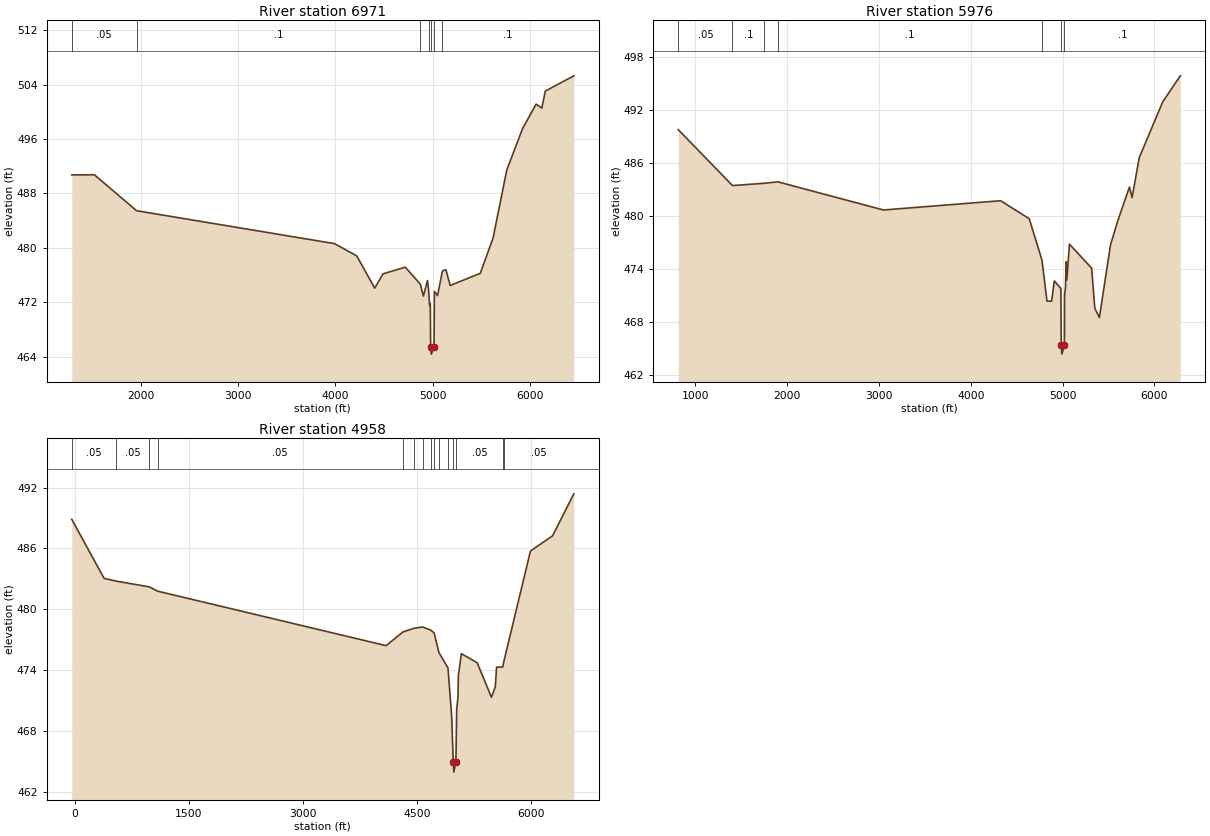
Type RM Length L Ch R = 1 ,6971    ,995,995,995
BEGIN DESCRIPTION:
Black Creek 7.0
END DESCRIPTION:
XS GIS Cut Line= 4
      1991616.56     13507164.75      1991979.71     13504573.44
        1991325.       13503725.      1990600.01     13502450.02
#Sta/Elev= 30
  1293.6  490.73  1525.6  490.75  1959.4  485.46    3991  480.62  4219.2  478.82
    4404  474.07  4489.3  476.17  4717.4  477.16  4871.8  474.67    4904   472.9
  4945.7  475.19  4956.5  473.95  4968.3   471.5  4974.7   471.8  4978.3  465.36
  4985.3  464.36  5012.8  465.36  5017.2  473.58    5049  472.97  5099.8  476.61
  5135.4  476.77  5178.7  474.46  5488.1  476.25  5619.8  481.47  5759.6  491.43
    5921  497.51  6060.9  501.14    6120  500.56  6155.3  503.06  6448.6  505.31
#Mann= 7 ,-1 , 0
  1293.6     .05       0  1959.4      .1       0  4871.8     .12       0
  4956.5     .16       0  4978.3     .07       0  5012.8     .16       0
  5099.8      .1       0
Bank Sta=4978.3,5012.8
XS Rating Curve= 0 ,0
Exp/Cntr=0.3,0.1

Type RM Length L Ch R = 1 ,5976    ,1018,1018,1018
BEGIN DESCRIPTION:
Black Creek 6.0
END DESCRIPTION:
XS GIS Cut Line= 4
      1991824.53     13507039.07      1992551.52     13503545.16
        1992025.       13503175.      1991050.52     13502379.52
#Sta/Elev= 30
     813   489.8  1404.2  483.46  1750.6  483.72  1899.2  483.88  3048.9  480.69
  4325.5  481.74  4637.2   479.7  4776.5  474.99  4830.6  470.35  4881.2  470.36
  4910.8  472.65  4982.2  471.79  4985.9  465.35  4992.9  464.35  5020.4  465.35
  5022.3  471.05  5032.5   471.9    5039  474.82  5046.9  472.75  5075.6  476.82
  5316.9   474.1    5352  469.54  5401.6  468.49  5522.9  476.74  5601.2  479.43
    5729  483.29  5757.7  482.09    5836  486.62  6091.6  492.95  6283.3   495.9
#Mann= 7 ,-1 , 0
     813     .05       0  1404.2      .1       0  1750.6     .05       0
  1899.2      .1       0  4776.5     .16       0  4985.9     .07       0
  5020.4      .1       0
Bank Sta=4985.9,5020.4
XS Rating Curve= 0 ,0
Exp/Cntr=0.3,0.1

Type RM Length L Ch R = 1 ,4958    ,0,0,0
BEGIN DESCRIPTION:
Black Creek 5.0
END DESCRIPTION:
XS GIS Cut Line= 3
      1991911.32     13506995.69      1993343.62     13502904.96
      1991319.32     13501884.27
#Sta/Elev= 30
   -36.5  488.87   388.2  483.05   540.6  482.79   983.1  482.21  1092.2  481.79
  4096.4  476.42  4317.5  477.77  4462.3  478.13  4574.9  478.26  4683.3  477.95
  4727.4  477.68  4791.7  475.73  4910.2  474.22  4957.7  469.53  4979.5  464.96
  4986.5  463.96    5014  464.96  5024.6  470.18  5041.3  471.32  5046.9  473.49
  5085.9  475.63  5292.9  474.75  5481.8  471.33    5532  472.36  5548.7   474.3
  5630.8  474.32  5641.9  474.78  5994.8  485.75  6284.8  487.24  6564.8  491.38
#Mann= 15 ,-1 , 0
   -36.5     .05       0   540.6     .05       0   983.1     .05       0
  1092.2     .05       0  4317.5     .05       0  4462.3     .05       0
  4574.9     .05       0  4683.3     .05       0  4727.4     .05       0
  4791.7     .05       0  4910.2     .05       0  4979.5     .03       0
    5014     .05       0  5630.8     .05       0  5641.9     .05       0
Bank Sta=4979.5,5014
XS Rating Curve= 0 ,0
Exp/Cntr=0.3,0.1
LCMann Table=0

Chan Stop Cuts=-1
Use User Specified Reach Order=0
Composite Channel Slope=5