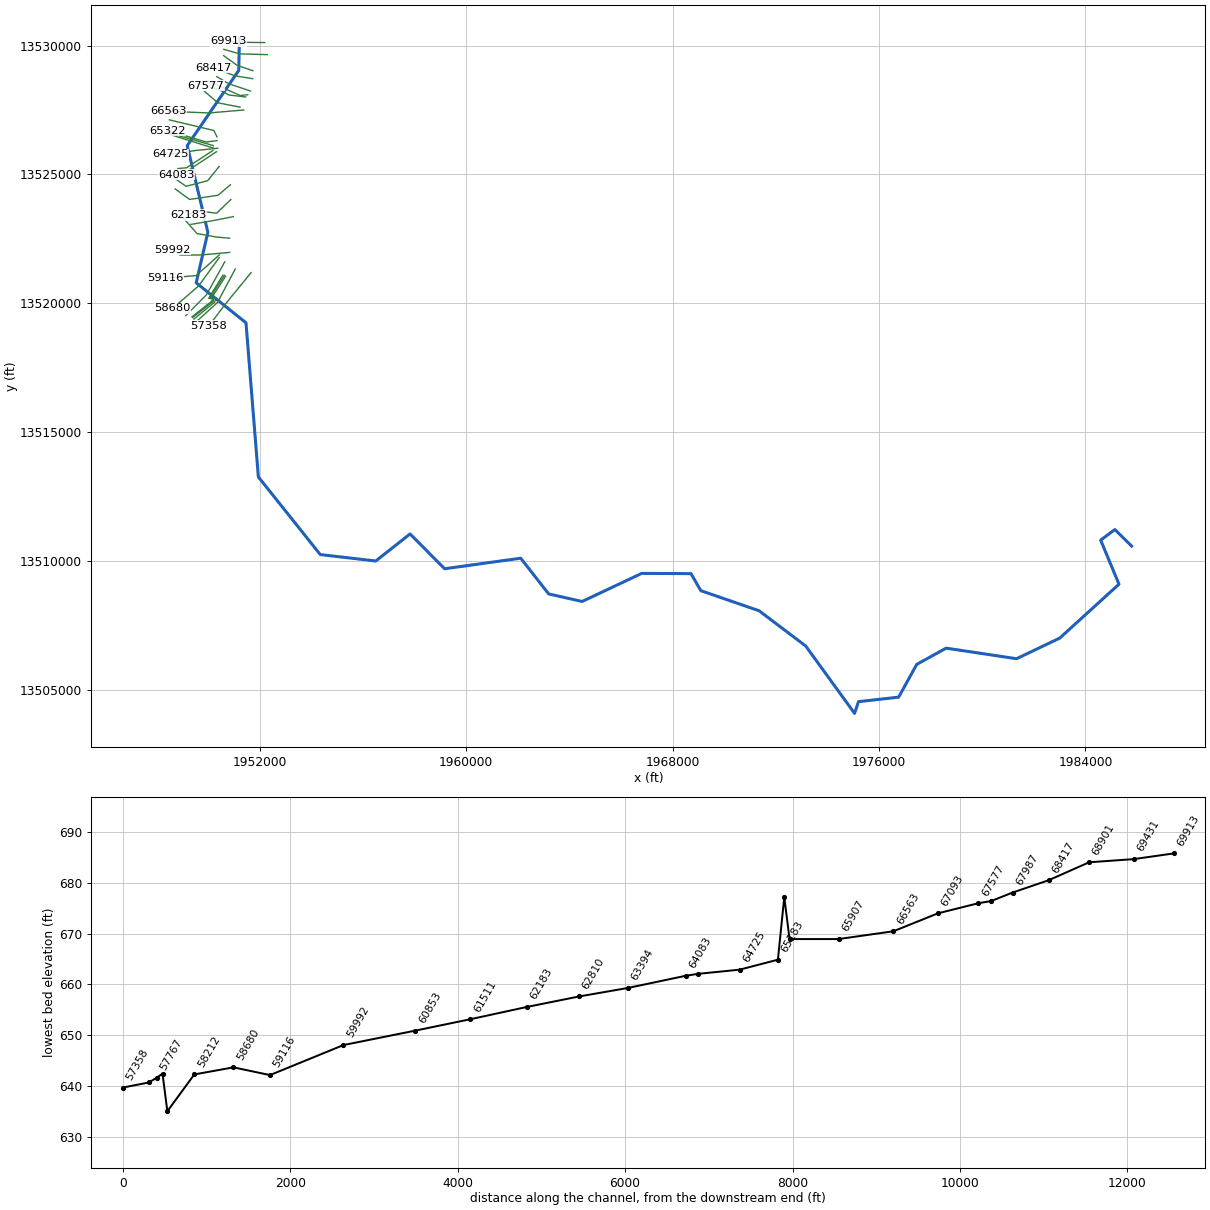
--- Buckhorn Creek.prj (project) ---

Proj Title=Buckhorn Creek Base Level Engineering
Current Plan=p01
Default Exp/Contr=0.3,0.1
English Units
Geom File=g01
Flow File=f01
Plan File=p01
Y Axis Title=Elevation
X Axis Title(PF)=Main Channel Distance
X Axis Title(XS)=Station
BEGIN DESCRIPTION:
Buckhorn Creek
END DESCRIPTION:
DSS Export Rating Curves= 0
DSS Export Rating Curve Sorted= 0
DSS Export Volume Flow Curves= 0
DXF OffsetX= 0
DXF OffsetY= 0
DXF ScaleX= 1
DXF ScaleY= 10

--- Buckhorn Creek.p01 (plan) ---

Plan Title=Multiple Run
Short Identifier=Multiple
Geom File=g01
Flow File=f01
Subcritical Flow
K Sum by GR= 0
Std Step Tol= 0.01
Critical Tol= 0.01
Num of Std Step Trials= 20
Max Error Tol= 0.3
Flow Tol Ratio= 0.001
Split Flow NTrial= 30
Split Flow Tol= 0.02
Split Flow Ratio= 0.02
Log Output Level= 0
Friction Slope Method= 1
Unsteady Friction Slope Method= 2
Unsteady Bridges Friction Slope Method= 1
Parabolic Critical Depth
Global Vel Dist=  1 , 1 , 1
Global Log Level= 0
CheckData=True
Encroach Param= -1, 0, 0, 0
BEGIN DESCRIPTION:
Multiple Run
END DESCRIPTION:

--- Buckhorn Creek.f01 (steady flow) ---

Flow Title=Multiple
Program Version=5.05
Number of Profiles= 7
Profile Names=10-year,25-year,50-year,1pct_min,100-year,1pct_plu,500-year
River Rch & RM=Buckhorn Creek,Reach-1         ,69913
     117     156     187     113     225     448     330
River Rch & RM=Buckhorn Creek,Reach-1         ,69431
     138     186     225     136     271     541     402
River Rch & RM=Buckhorn Creek,Reach-1         ,65322
     208     287     353     216     431     861     658
River Rch & RM=Buckhorn Creek,Reach-1         ,59116
     245     341     421     259     518    1033     797
River Rch & RM=Buckhorn Creek,Reach-1         ,58680
     287     402     499     308     616    1228     956
River Rch & RM=Buckhorn Creek,Reach-1         ,54990
     330     465     578     358     715    1427    1116
River Rch & RM=Buckhorn Creek,Reach-1         ,44840
     631     915    1160     732    1461    2915    2364
River Rch & RM=Buckhorn Creek,Reach-1         ,42590
     777    1134    1445     916    1828    3647    2982
River Rch & RM=Buckhorn Creek,Reach-1         ,38222
     815    1191    1519     964    1924    3838    3144
River Rch & RM=Buckhorn Creek,Reach-1         ,36430
     816    1193    1521     965    1926    3843    3146
River Rch & RM=Buckhorn Creek,Reach-1         ,34817
     856    1253    1599    1015    2026    4043    3314
River Rch & RM=Buckhorn Creek,Reach-1         ,31373
     909    1332    1701    1081    2156    4303    3532
River Rch & RM=Buckhorn Creek,Reach-1         ,27084
     988    1449    1853    1178    2350    4688    3852
River Rch & RM=Buckhorn Creek,Reach-1         ,20209
    1084    1594    2041    1299    2591    5171    4256
River Rch & RM=Buckhorn Creek,Reach-1         ,19330
    1084    1594    2041    1299    2591    5171    4256
River Rch & RM=Buckhorn Creek,Reach-1         ,13673
    1123    1653    2119    1349    2692    5371    4426
River Rch & RM=Buckhorn Creek,Reach-1         ,11043
    1136    1669    2137    1359    2711    5409    4446
Boundary for River Rch & Prof#=Buckhorn Creek,Reach-1         , 1
Up Type= 0
Dn Type= 3
Dn Slope=0.00212
Boundary for River Rch & Prof#=Buckhorn Creek,Reach-1         , 2
Up Type= 0
Dn Type= 3
Dn Slope=0.00212
Boundary for River Rch & Prof#=Buckhorn Creek,Reach-1         , 3
Up Type= 0
Dn Type= 3
Dn Slope=0.00212
Boundary for River Rch & Prof#=Buckhorn Creek,Reach-1         , 4
Up Type= 0
Dn Type= 3
Dn Slope=0.00212
Boundary for River Rch & Prof#=Buckhorn Creek,Reach-1         , 5
Up Type= 0
Dn Type= 3
Dn Slope=0.00212
Boundary for River Rch & Prof#=Buckhorn Creek,Reach-1         , 6
Up Type= 0
Dn Type= 3
Dn Slope=0.00212
Boundary for River Rch & Prof#=Buckhorn Creek,Reach-1         , 7
Up Type= 0
Dn Type= 3
Dn Slope=0.00212
DSS Import GetInterval= 0
DSS Import GetPeak= 0
DSS Import FillOption= 0

--- Buckhorn Creek.g01 (geometry) ---

Geom Title=Existing Conditions

River Reach=Buckhorn Creek,Reach-1
Reach XY= 30
      1951205.82     13530278.17      1951180.80     13529034.54
      1949182.64     13526116.44      1949982.99     13522755.33
      1949530.80     13520794.54      1951460.80     13519244.54
      1951940.80     13513264.54      1954340.80     13510254.54
      1956490.80     13510004.54      1957820.80     13511054.54
      1959160.80     13509704.54      1962109.16     13510113.27
      1963193.36     13508728.14      1964490.80     13508434.54
      1966800.80     13509524.54      1968710.80     13509514.54
      1969090.80     13508854.54      1971350.80     13508074.54
      1973160.80     13506704.54      1975050.80     13504094.54
      1975203.16     13504548.86      1976760.80     13504724.54
      1977460.80     13505994.54      1978600.80     13506624.54
      1981330.80     13506214.54      1983005.71     13507015.28
      1985300.80     13509104.54      1984590.80     13510814.54
      1985140.80     13511224.54      1985790.80     13510584.54

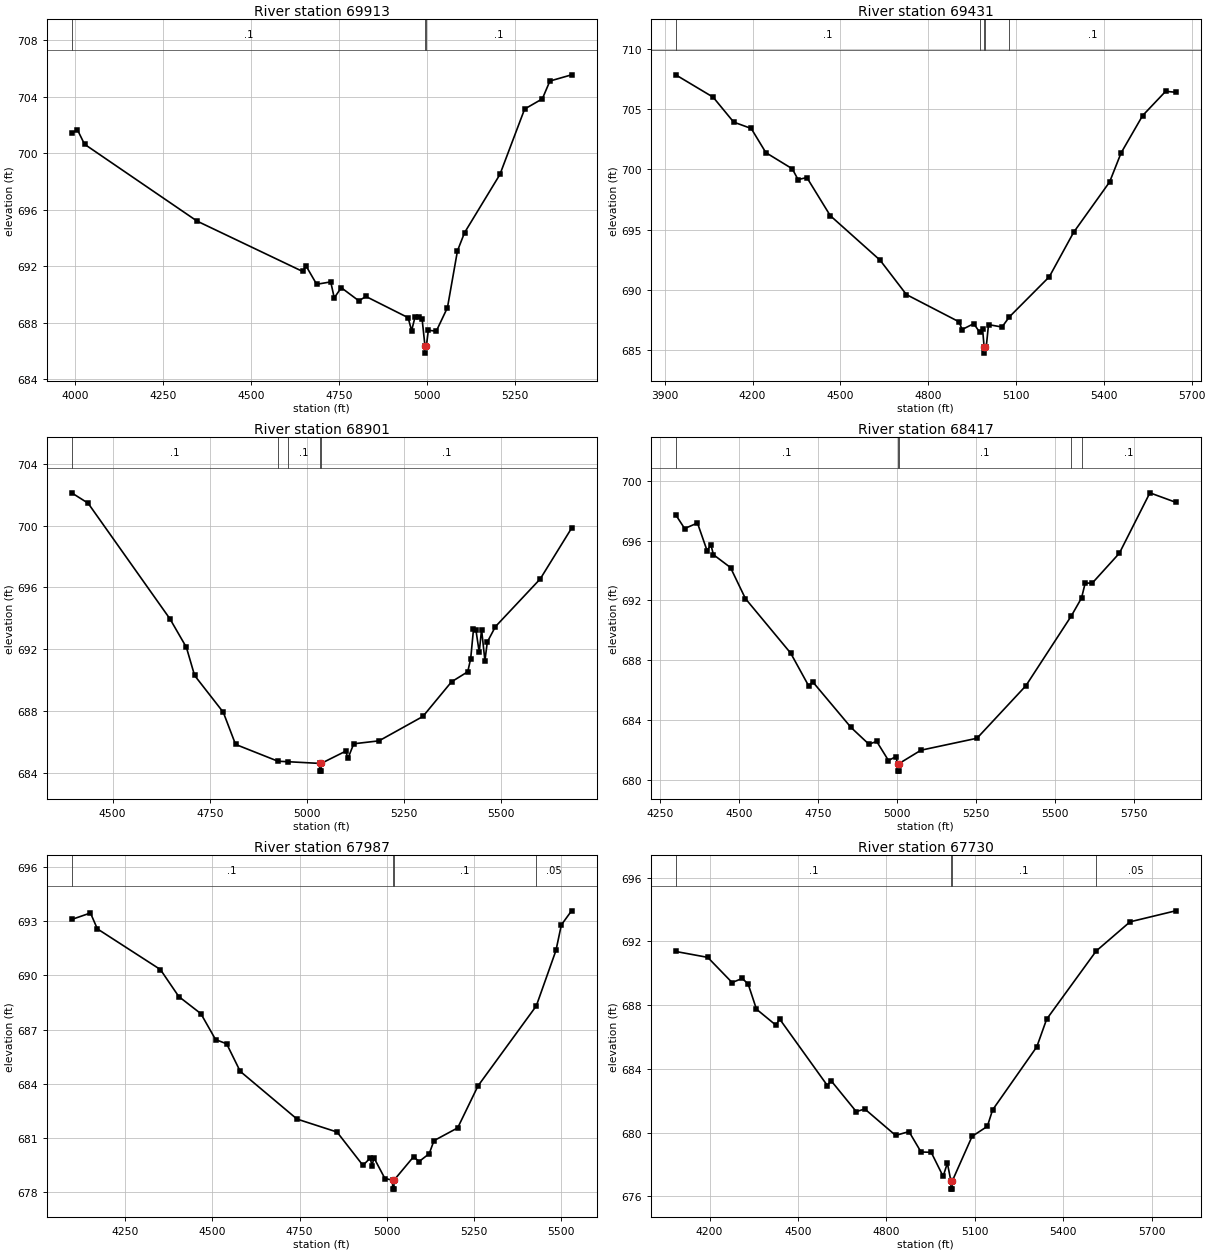
Type RM Length L Ch R = 1,69913,482,482,482
BEGIN DESCRIPTION:
Buckhorn Creek 113.0
END DESCRIPTION:
XS GIS Cut Line= 3
      1952191.65     13530114.65      1951175.00     13530125.00
      1950772.36     13530166.74
#Sta/Elev= 30
  3989.1  701.43  4005.7  701.65  4025.7  700.64  4345.8  695.20  4645.8  691.64
  4655.8  692.02  4685.8  690.73  4725.8  690.90  4735.8  689.77  4755.8  690.49
  4805.8  689.56  4825.8  689.87  4945.8  688.37  4955.8  687.45  4965.8  688.44
  4975.8  688.41  4985.8  688.24  4993.8  686.36  4994.0  685.86  4997.8  686.36
  5003.3  687.48  5025.9  687.41  5057.7  689.08  5086.2  693.10  5106.3  694.38
  5206.9  698.50  5277.2  703.13  5327.5  703.85  5349.0  705.11  5410.6  705.55
#Mann=3,-1,0
  3989.1     0.1       0  4993.8    0.07       0  4997.8     0.1       0
Bank Sta=4993.8,4997.8
Exp/Cntr=0.3,0.1

Type RM Length L Ch R = 1,69431,530,530,530
BEGIN DESCRIPTION:
Buckhorn Creek 112.0
END DESCRIPTION:
XS GIS Cut Line= 3
      1952282.84     13529645.90      1951225.00     13529675.00
      1950599.38     13529849.72
#Sta/Elev= 30
  3937.4  707.87  4065.3  706.01  4135.3  703.94  4195.3  703.41  4245.4  701.40
  4335.4  700.06  4355.4  699.16  4385.4  699.33  4465.4  696.16  4635.5  692.46
  4725.5  689.60  4905.6  687.33  4915.6  686.69  4955.6  687.18  4975.5  686.48
  4985.6  686.76  4991.1  685.23  4991.3  684.73  4995.2  685.23  4998.2  685.23
  5006.0  687.10  5052.1  686.90  5077.5  687.75  5213.7  691.08  5296.7  694.77
  5419.7  698.96  5459.0  701.38  5532.5  704.48  5611.2  706.50  5645.2  706.42
#Mann=5,-1,0
  3937.4     0.1       0  4975.5    0.07       0  4991.1    0.07       0
  4995.2    0.07       0  5077.5     0.1       0
Bank Sta=4991.1,4995.2
Exp/Cntr=0.3,0.1

Type RM Length L Ch R = 1,68901,484,484,484
BEGIN DESCRIPTION:
Buckhorn Creek 111.0
END DESCRIPTION:
XS GIS Cut Line= 3
      1951725.04     13529024.99      1951125.00     13529225.00
      1950594.41     13529606.85
#Sta/Elev= 30
  4394.7  702.12  4436.9  701.45  4647.7  693.96  4689.9  692.12  4711.0  690.30
  4784.8  687.92  4816.4  685.84  4925.6  684.75  4950.8  684.72  5032.5  684.61
  5032.8  684.11  5036.4  684.11  5036.7  684.61  5099.6  685.40  5105.8  684.95
  5120.5  685.88  5185.5  686.07  5298.5  687.65  5372.1  689.89  5413.8  690.54
  5421.4  691.39  5428.6  693.29  5434.7  693.27  5443.3  691.81  5449.4  693.27
  5458.0  691.26  5464.2  692.47  5485.0  693.46  5600.4  696.55  5680.9  699.83
#Mann=5,-1,0
  4394.7     0.1       0  4925.6    0.07       0  4950.8     0.1       0
  5032.5    0.07       0  5036.7     0.1       0
Bank Sta=5032.5,5036.7
Exp/Cntr=0.3,0.1

Type RM Length L Ch R = 1,68417,430,430,430
BEGIN DESCRIPTION:
Buckhorn Creek 110.0
END DESCRIPTION:
XS GIS Cut Line= 3
      1951722.89     13528712.74      1951025.00     13528825.00
      1950209.10     13529142.05
#Sta/Elev= 30
  4298.6  697.72  4326.8  696.80  4367.4  697.17  4397.7  695.33  4410.1  695.70
  4418.0  695.05  4472.0  694.19  4519.3  692.11  4662.6  688.46  4719.5  686.27
  4732.0  686.55  4853.5  683.49  4910.1  682.37  4934.6  682.56  4972.0  681.28
  4995.3  681.54  5000.8  681.07  5001.1  680.57  5004.7  680.57  5005.0  681.07
  5074.8  681.97  5252.2  682.77  5406.8  686.28  5550.6  690.95  5583.0  692.15
  5594.6  693.15  5617.0  693.15  5702.8  695.15  5799.4  699.19  5880.8  698.56
#Mann=5,-1,0
  4298.6     0.1       0  5000.8    0.07       0  5005.0     0.1       0
  5550.6    0.05       0  5583.0     0.1       0
Bank Sta=5000.8,5005
Exp/Cntr=0.3,0.1

Type RM Length L Ch R = 1,67987,257,257,257
BEGIN DESCRIPTION:
Buckhorn Creek 109.0
END DESCRIPTION:
XS GIS Cut Line= 3
      1951636.12     13528235.30      1950775.00     13528525.00
      1950325.29     13528795.23
#Sta/Elev= 30
  4096.4  693.11  4150.3  693.47  4170.0  692.59  4350.8  690.33  4403.6  688.83
  4466.9  687.88  4509.1  686.44  4540.7  686.21  4579.6  684.68  4742.4  682.03
  4857.2  681.31  4931.5  679.46  4952.2  679.86  4957.7  679.44  4963.0  679.88
  4994.5  678.73  5016.4  678.64  5016.7  678.14  5020.4  678.14  5020.7  678.64
  5076.8  679.94  5092.4  679.67  5121.6  680.11  5135.1  680.83  5203.1  681.54
  5261.4  683.87  5428.5  688.31  5484.9  691.39  5500.4  692.81  5529.6  693.59
#Mann=4,-1,0
  4096.4     0.1       0  5016.4    0.07       0  5020.7     0.1       0
  5428.5    0.05       0
Bank Sta=5016.4,5020.7
Exp/Cntr=0.3,0.1

Type RM Length L Ch R = 1,67730,153,153,153
BEGIN DESCRIPTION:
Mapping XS 0c23d956
END DESCRIPTION:
XS GIS Cut Line= 4
      1951529.08     13528092.70      1951237.45     13528057.98
      1950355.50     13528453.82      1949959.82     13528634.30
#Sta/Elev= 30
  4085.2  691.37  4193.8  691.00  4276.4  689.42  4310.9  689.68  4331.0  689.32
  4359.0  687.75  4425.4  686.74  4437.3  687.14  4599.5  682.96  4611.8  683.27
  4697.6  681.32  4726.3  681.49  4831.0  679.83  4876.3  680.07  4917.1  678.79
  4951.6  678.77  4992.1  677.26  5006.4  678.09  5018.6  676.96  5018.9  676.46
  5022.6  676.46  5022.9  676.96  5090.3  679.77  5142.1  680.40  5159.8  681.43
  5309.8  685.39  5343.1  687.12  5511.2  691.40  5626.0  693.23  5780.5  693.92
#Mann=4,-1,0
  4085.2     0.1       0  5018.6    0.07       0  5022.9     0.1       0
  5511.2    0.05       0
Bank Sta=5018.6,5022.9
Exp/Cntr=0.3,0.1

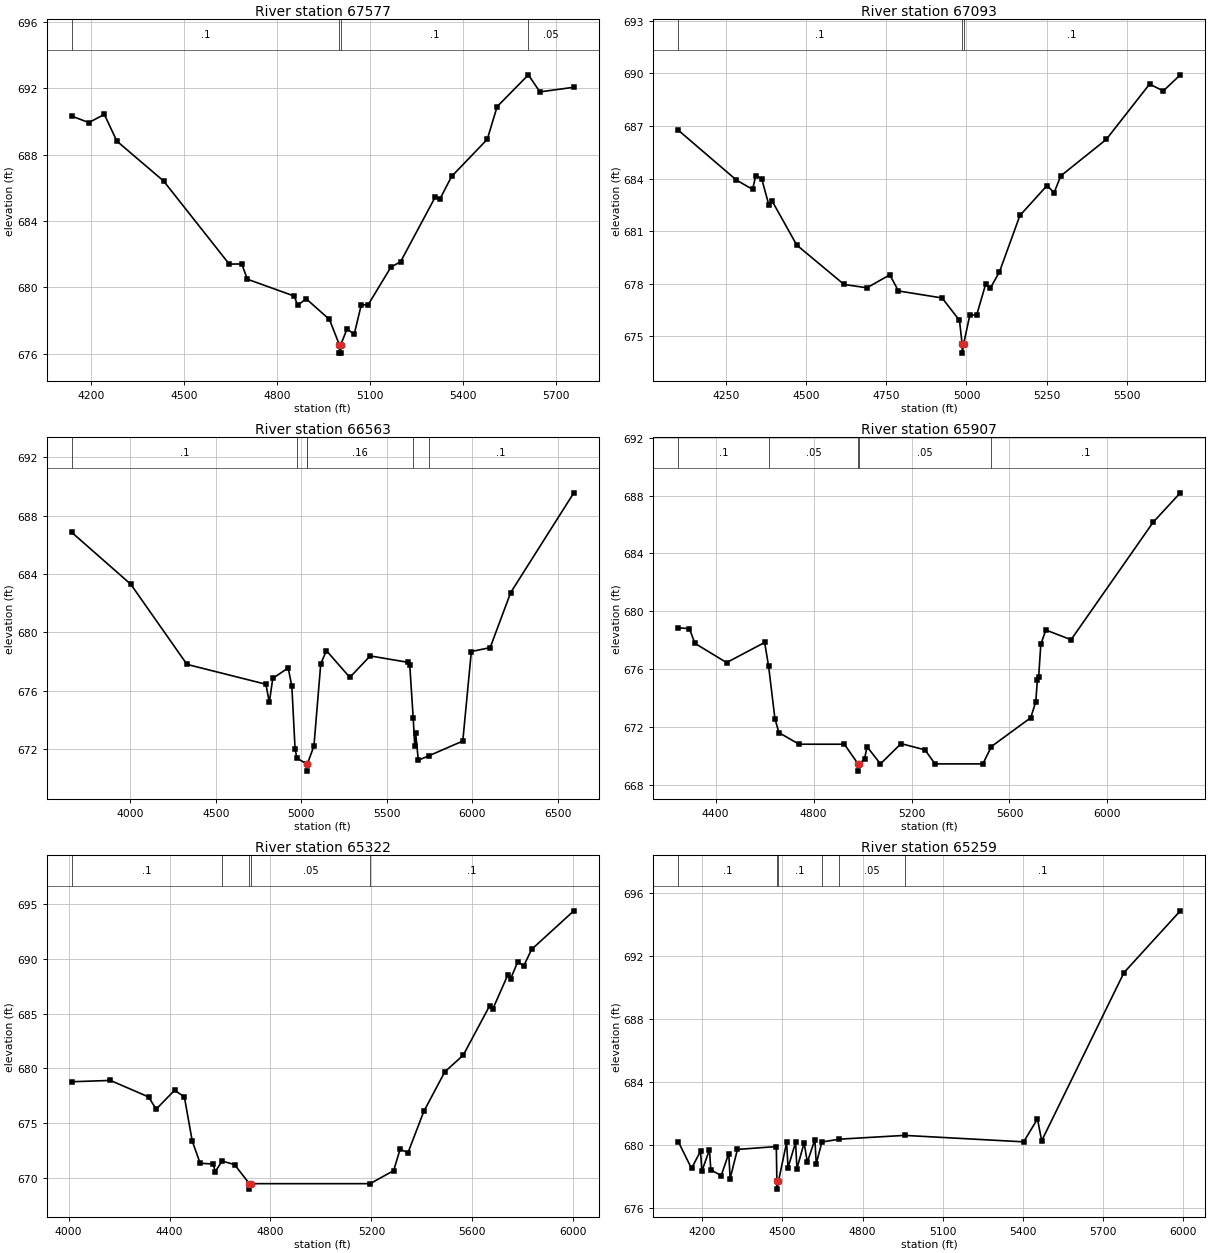
Type RM Length L Ch R = 1,67577,484,484,484
BEGIN DESCRIPTION:
Buckhorn Creek 108.0
END DESCRIPTION:
XS GIS Cut Line= 4
      1951449.43     13528005.28      1950806.89     13528078.82
      1950473.56     13528259.37      1949911.10     13528446.86
#Sta/Elev= 30
  4138.0  690.33  4192.8  689.94  4243.1  690.43  4283.4  688.82  4434.3  686.41
  4645.7  681.40  4686.0  681.41  4704.1  680.49  4855.5  679.47  4866.0  678.91
  4893.6  679.31  4968.8  678.06  5000.8  676.53  5001.1  676.03  5004.8  676.03
  5005.1  676.53  5025.7  677.50  5048.5  677.16  5071.2  678.93  5093.9  678.96
  5166.7  681.21  5198.3  681.55  5309.9  685.45  5324.8  685.32  5362.6  686.69
  5477.6  688.93  5509.3  690.90  5610.1  692.82  5647.2  691.79  5756.7  692.07
#Mann=4,-1,0
  4138.0     0.1       0  5000.8    0.07       0  5005.1     0.1       0
  5610.1    0.05       0
Bank Sta=5000.8,5005.1
Exp/Cntr=0.3,0.1

Type RM Length L Ch R = 1,67093,530,530,530
BEGIN DESCRIPTION:
Buckhorn Creek 107.0
END DESCRIPTION:
XS GIS Cut Line= 3
      1951232.45     13527610.31      1950375.00     13527775.00
      1949849.28     13528224.03
#Sta/Elev= 30
  4101.9  686.76  4282.6  683.92  4333.5  683.38  4343.7  684.17  4362.1  683.98
  4384.4  682.48  4394.6  682.71  4471.2  680.20  4618.6  677.95  4689.9  677.76
  4761.2  678.50  4788.0  677.58  4924.1  677.18  4978.3  675.90  4986.6  674.53
  4986.9  674.03  4990.9  674.53  5010.7  676.22  5031.6  676.19  5060.1  677.98
  5074.4  677.74  5102.9  678.67  5166.6  681.89  5251.2  683.60  5273.1  683.19
  5293.9  684.15  5435.6  686.23  5570.6  689.39  5613.4  689.00  5666.4  689.92
#Mann=3,-1,0
  4101.9     0.1       0  4986.6    0.07       0  4990.9     0.1       0
Bank Sta=4986.6,4990.9
Exp/Cntr=0.3,0.1

Type RM Length L Ch R = 1,66563,656,656,656
BEGIN DESCRIPTION:
Buckhorn Creek 106.0
END DESCRIPTION:
XS GIS Cut Line= 3
      1951376.24     13527499.13      1950034.52     13527384.62
      1948445.98     13527445.38
#Sta/Elev= 30
  3658.1  686.85  4003.1  683.30  4331.8  677.81  4793.4  676.45  4813.5  675.21
  4833.6  676.85  4923.9  677.57  4945.2  676.30  4964.1  672.01  4974.9  671.38
  5032.0  671.00  5032.3  670.50  5036.4  671.00  5074.3  672.22  5114.3  677.86
  5147.4  678.75  5284.4  676.92  5403.3  678.39  5624.7  677.95  5634.7  677.78
  5654.8  674.15  5664.2  672.20  5669.2  673.12  5684.7  671.25  5744.6  671.54
  5944.9  672.56  5994.9  678.69  6105.0  678.96  6225.1  682.73  6594.4  689.56
#Mann=6,-1,0
  3658.1     0.1       0  4974.9    0.16       0  5032.0    0.07       0
  5036.4    0.16       0  5654.8    0.05       0  5744.6     0.1       0
Bank Sta=5032,5036.4
Exp/Cntr=0.3,0.1

Type RM Length L Ch R = 1,65907,585,585,585
BEGIN DESCRIPTION:
Mapping XS e8a821f9
END DESCRIPTION:
XS GIS Cut Line= 3
      1950338.09     13526455.12      1950216.82     13526702.33
      1948491.14     13527115.51
#Sta/Elev= 30
  4247.6  678.86  4293.1  678.81  4315.6  677.79  4445.0  676.46  4600.4  677.85
  4616.6  676.20  4642.4  672.58  4658.5  671.62  4740.8  670.82  4925.8  670.82
  4981.7  669.46  4982.0  668.96  4986.1  669.46  5008.1  669.79  5018.4  670.65
  5073.1  669.46  5157.2  670.86  5254.9  670.43  5296.0  669.46  5491.4  669.46
  5526.1  670.66  5686.8  672.65  5707.3  673.76  5713.9  675.27  5719.1  675.47
  5727.9  677.73  5748.5  678.71  5851.3  678.04  6186.6  686.16  6297.4  688.19
#Mann=5,-1,0
  4247.6     0.1       0  4616.6    0.05       0  4981.7   0.033       0
  4986.1    0.05       0  5526.1     0.1       0
Bank Sta=4981.7,4986.1
Exp/Cntr=0.3,0.1

Type RM Length L Ch R = 1,65322,63,63,63
BEGIN DESCRIPTION:
Mapping XS c1ee2e34
END DESCRIPTION:
XS GIS Cut Line= 3
      1950336.98     13526309.73      1949918.20     13526257.88
      1948414.69     13526702.34
#Sta/Elev= 30
  4012.6  678.78  4165.7  678.90  4316.9  677.39  4347.1  676.27  4420.0  678.00
  4458.8  677.40  4490.0  673.36  4521.3  671.33  4573.5  671.25  4580.9  670.55
  4608.6  671.53  4657.9  671.20  4716.3  669.46  4716.8  668.96  4722.2  669.46
  5195.0  669.46  5288.2  670.65  5313.8  672.61  5345.1  672.29  5407.7  676.06
  5491.1  679.69  5564.1  681.21  5668.4  685.71  5680.4  685.39  5741.4  688.58
  5752.1  688.20  5780.2  689.76  5804.0  689.38  5835.2  690.89  6002.4  694.41
#Mann=5,-1,0
  4012.6     0.1       0  4608.6    0.05       0  4716.3   0.033       0
  4722.2    0.05       0  5195.0     0.1       0
Bank Sta=4716.3,4722.2
Exp/Cntr=0.3,0.1

Type RM Length L Ch R = 1,65259,76,76,76
BEGIN DESCRIPTION:
Mapping XS e6adf8d8
END DESCRIPTION:
XS GIS Cut Line= 4
      1950197.89     13526116.10      1949327.93     13526368.99
      1948907.79     13526483.58      1948393.93     13526646.76
#Sta/Elev= 30
  4109.6  680.24  4159.4  678.53  4193.0  679.63  4198.2  678.36  4226.5  679.72
  4231.7  678.44  4270.5  678.08  4298.8  679.48  4304.0  677.89  4331.3  679.74
  4476.9  679.92  4479.1  677.72  4479.6  677.22  4485.0  677.72  4515.6  680.18
  4520.8  678.58  4549.1  680.18  4554.3  678.52  4581.2  680.16  4593.1  678.93
  4621.4  680.36  4626.6  678.84  4647.7  680.21  4713.2  680.39  4957.8  680.63
  5403.4  680.22  5455.1  681.67  5471.0  680.29  5779.2  690.96  5990.2  694.88
#Mann=6,-1,0
  4109.6     0.1       0  4479.1    0.07       0  4485.0     0.1       0
  4647.7    0.16       0  4713.2    0.05       0  4957.8     0.1       0
Bank Sta=4479.1,4485
Exp/Cntr=0.3,0.1

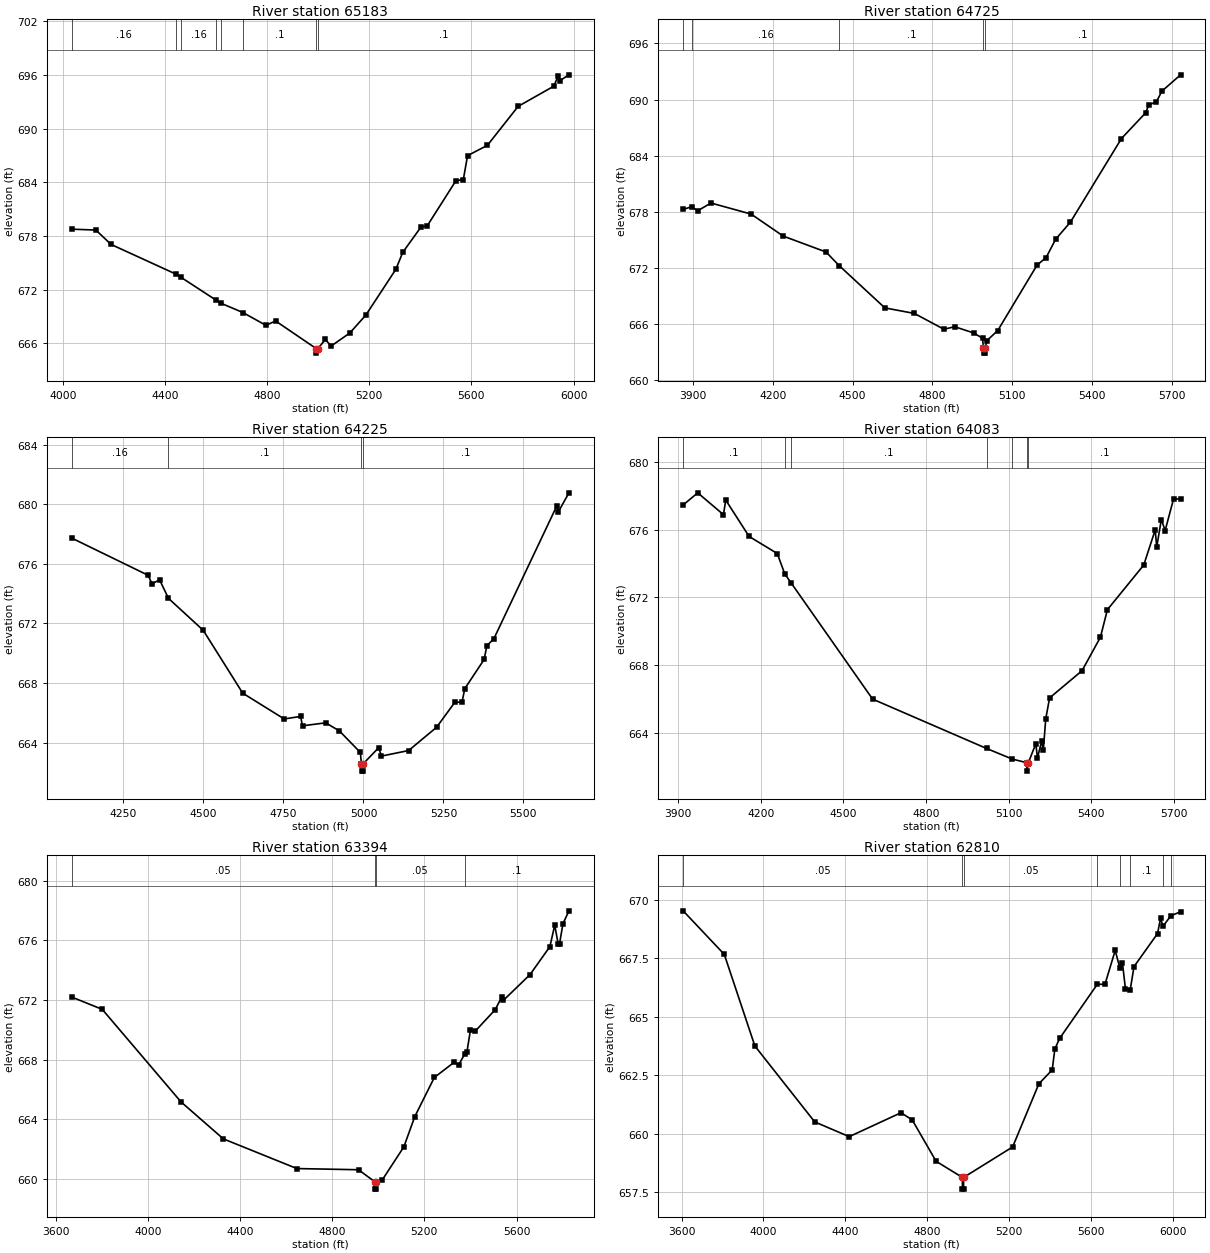
Type RM Length L Ch R = 1,65183,458,458,458
BEGIN DESCRIPTION:
Mapping XS 2082a0be
END DESCRIPTION:
XS GIS Cut Line= 3
      1950225.47     13526013.10      1948788.00     13526461.01
      1948368.94     13526603.00
#Sta/Elev= 30
  4034.0  678.76  4129.2  678.66  4189.0  677.05  4444.4  673.71  4462.9  673.37
  4599.3  670.83  4620.2  670.46  4705.4  669.43  4795.3  668.00  4833.1  668.49
  4992.7  665.39  4993.2  664.89  4998.6  665.39  5028.2  666.42  5050.5  665.68
  5123.8  667.14  5186.7  669.15  5304.0  674.26  5331.3  676.17  5401.6  678.96
  5427.6  679.16  5539.6  684.19  5568.4  684.31  5585.0  686.99  5662.7  688.14
  5783.1  692.50  5922.9  694.76  5940.2  695.94  5945.5  695.36  5982.1  696.03
#Mann=8,-1,0
  4034.0    0.16       0  4444.4     0.1       0  4462.9    0.16       0
  4599.3     0.1       0  4620.2    0.16       0  4705.4     0.1       0
  4992.7    0.07       0  4998.6     0.1       0
Bank Sta=4992.7,4998.6
Exp/Cntr=0.3,0.1

Type RM Length L Ch R = 1,64725,500,500,500
BEGIN DESCRIPTION:
Mapping XS ab4b5ba5
END DESCRIPTION:
XS GIS Cut Line= 3
      1950369.01     13526014.99      1949536.26     13525931.49
      1948515.45     13525782.19
#Sta/Elev= 30
  3863.7  678.26  3896.0  678.56  3918.4  678.12  3968.2  678.95  4119.1  677.77
  4239.6  675.42  4400.4  673.72  4450.1  672.26  4621.5  667.75  4732.2  667.16
  4843.4  665.47  4883.8  665.74  4954.6  665.08  4988.6  664.51  4992.0  663.42
  4992.5  662.92  4997.4  662.92  4997.9  663.42  5005.1  664.26  5045.5  665.33
  5193.3  672.32  5227.4  673.13  5263.3  675.09  5318.4  676.90  5510.4  685.84
  5601.4  688.59  5612.9  689.43  5641.8  689.76  5662.0  690.89  5732.3  692.64
#Mann=5,-1,0
  3863.7     0.1       0  3896.0    0.16       0  4450.1     0.1       0
  4992.0    0.07       0  4997.9     0.1       0
Bank Sta=4992,4997.9
Exp/Cntr=0.3,0.1

Type RM Length L Ch R = 1,64225,142,142,142
BEGIN DESCRIPTION:
Buckhorn Creek 100.0
END DESCRIPTION:
XS GIS Cut Line= 3
      1950175.03     13525925.02      1949157.79     13525257.88
      1948821.03     13525226.64
#Sta/Elev= 30
  4087.6  677.73  4326.8  675.23  4339.3  674.65  4362.7  674.93  4390.6  673.68
  4499.1  671.54  4622.7  667.32  4752.3  665.59  4803.5  665.76  4809.5  665.13
  4881.9  665.33  4924.7  664.79  4990.4  663.34  4993.5  662.59  4994.0  662.09
  4999.0  662.09  4999.5  662.59  5047.6  663.66  5056.3  663.10  5141.1  663.47
  5228.5  665.03  5285.7  666.71  5308.0  666.72  5316.9  667.63  5377.2  669.58
  5385.8  670.51  5407.3  670.96  5604.5  679.89  5609.5  679.50  5642.3  680.76
#Mann=4,-1,0
  4087.6    0.16       0  4390.6     0.1       0  4993.5    0.07       0
  4999.5     0.1       0
Bank Sta=4993.5,4999.5
Exp/Cntr=0.3,0.1

Type RM Length L Ch R = 1,64083,689,689,689
BEGIN DESCRIPTION:
Buckhorn Creek 99.0
END DESCRIPTION:
XS GIS Cut Line= 3
      1950314.05     13525879.41      1949192.51     13525136.35
      1948759.28     13524980.39
#Sta/Elev= 30
  3918.5  677.46  3971.5  678.18  4064.8  676.89  4073.3  677.75  4158.0  675.60
  4260.3  674.59  4287.3  673.39  4310.2  672.86  4606.3  665.98  5020.1  663.06
  5113.9  662.43  5165.8  662.22  5166.3  661.72  5171.8  662.22  5198.9  663.34
  5204.9  662.50  5220.0  663.49  5226.0  662.95  5235.0  664.82  5248.9  666.05
  5366.7  667.66  5433.4  669.64  5458.8  671.27  5590.7  673.91  5632.4  675.99
  5637.7  674.96  5654.5  676.60  5668.4  675.95  5699.1  677.83  5724.3  677.81
#Mann=7,-1,0
  3918.5     0.1       0  4287.3    0.16       0  4310.2     0.1       0
  5020.1    0.07       0  5113.9     0.1       0  5165.8    0.07       0
  5171.8     0.1       0
Bank Sta=5165.8,5171.8
Exp/Cntr=0.3,0.1

Type RM Length L Ch R = 1,63394,584,584,584
BEGIN DESCRIPTION:
Buckhorn Creek 98.0
END DESCRIPTION:
XS GIS Cut Line= 4
      1950421.65     13525306.46      1949973.76     13524754.41
      1949136.95     13524539.13      1948658.89     13524875.16
#Sta/Elev= 30
  3668.4  672.21  3801.7  671.38  4143.7  665.17  4327.6  662.69  4646.5  660.70
  4914.3  660.62  4984.2  659.82  4984.7  659.32  4989.7  659.32  4990.2  659.82
  5018.2  659.96  5111.1  662.16  5158.6  664.19  5243.3  666.81  5328.5  667.82
  5349.4  667.66  5374.5  668.37  5385.1  668.55  5399.9  669.98  5420.9  669.92
  5507.1  671.35  5536.7  672.23  5542.8  671.98  5658.7  673.71  5745.0  675.59
  5765.9  677.03  5780.7  675.78  5786.8  675.78  5801.6  677.12  5827.7  677.99
#Mann=4,-1,0
  3668.4    0.05       0  4984.2   0.035       0  4990.2    0.05       0
  5374.5     0.1       0
Bank Sta=4984.2,4990.2
Exp/Cntr=0.3,0.1

Type RM Length L Ch R = 1,62810,627,627,627
BEGIN DESCRIPTION:
Buckhorn Creek 97.0
END DESCRIPTION:
XS GIS Cut Line= 4
      1950855.72     13524598.17      1950376.54     13524191.91
      1949275.84     13524028.71      1948718.37     13524435.56
#Sta/Elev= 30
  3607.2  669.52  3808.4  667.66  3957.8  663.75  4250.3  660.51  4419.0  659.88
  4671.7  660.90  4726.5  660.60  4843.5  658.83  4971.9  658.14  4972.4  657.64
  4977.6  657.64  4978.1  658.14  5217.6  659.44  5346.1  662.14  5411.1  662.73
  5423.9  663.62  5447.1  664.07  5632.0  666.39  5668.8  666.38  5719.0  667.83
  5741.9  667.07  5754.5  667.29  5769.2  666.17  5792.3  666.15  5810.9  667.14
  5926.0  668.55  5940.6  669.21  5952.5  668.86  5991.1  669.31  6038.3  669.48
#Mann=8,-1,0
  3607.2    0.05       0  4971.9   0.035       0  4978.1    0.05       0
  5632.0     0.1       0  5741.9    0.05       0  5792.3     0.1       0
  5952.5    0.05       0  5991.1     0.1       0
Bank Sta=4971.9,4978.1
Exp/Cntr=0.3,0.1

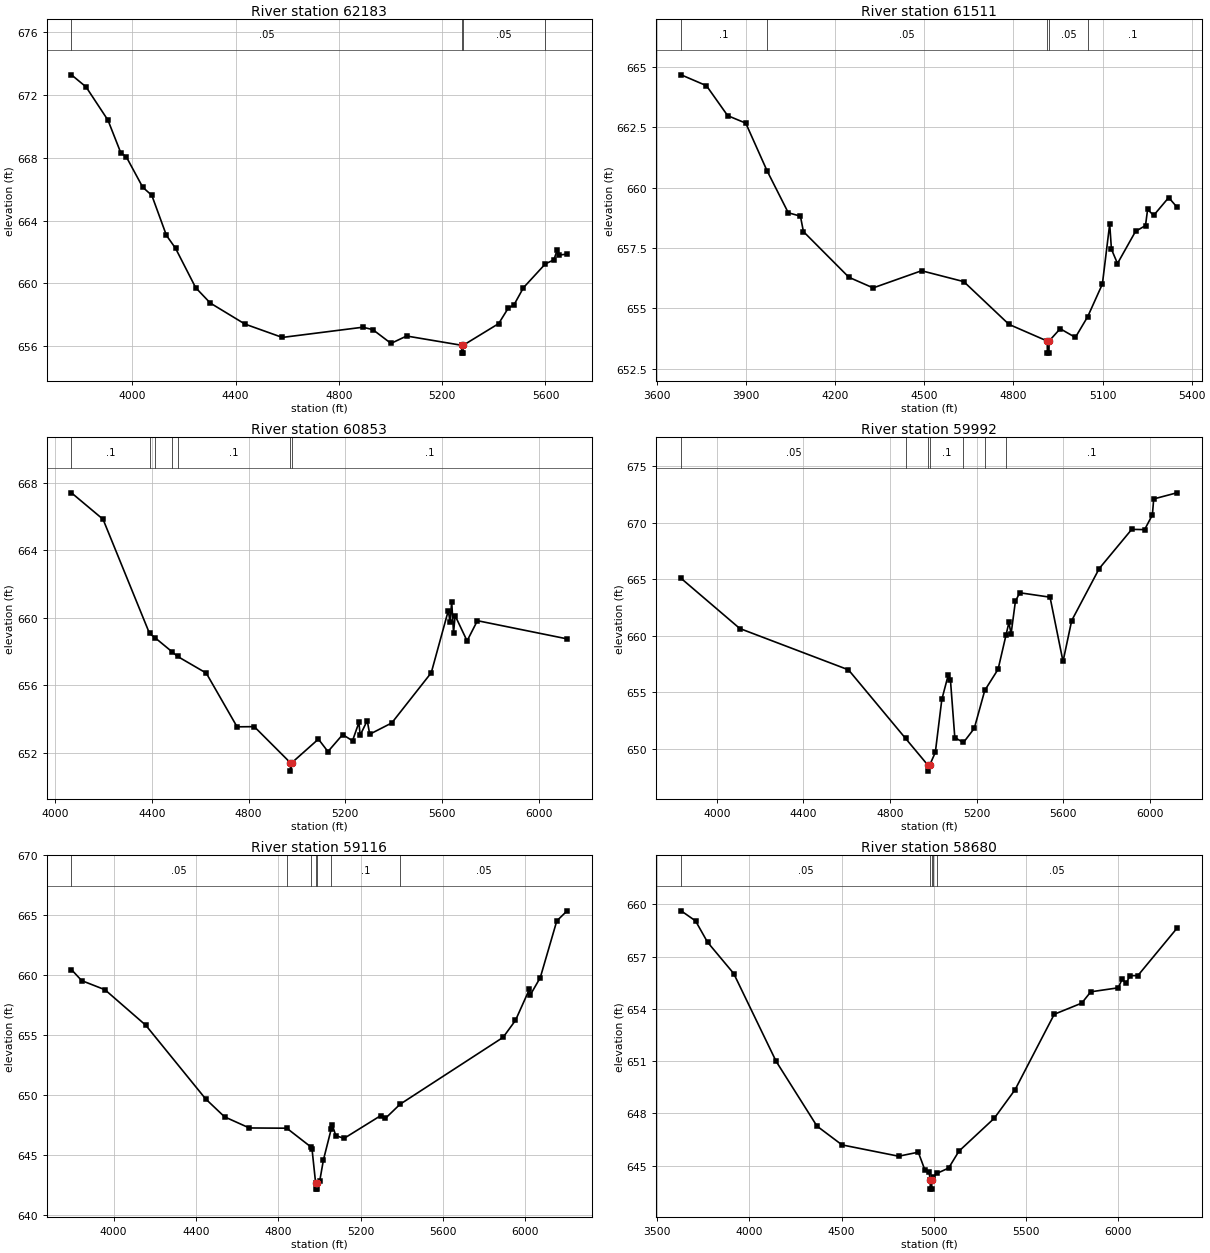
Type RM Length L Ch R = 1,62183,672,672,672
BEGIN DESCRIPTION:
Buckhorn Creek 96.0
END DESCRIPTION:
XS GIS Cut Line= 4
      1950875.02     13524025.02      1950320.98     13523493.99
      1949518.90     13523598.16      1949222.01     13523426.28
#Sta/Elev= 30
  3764.6  673.29  3821.1  672.52  3906.0  670.40  3955.7  668.32  3976.8  668.07
  4040.6  666.13  4075.8  665.61  4132.4  663.06  4167.6  662.24  4245.6  659.73
  4302.2  658.75  4436.5  657.41  4581.1  656.56  4892.7  657.21  4931.3  657.06
  5001.9  656.18  5062.4  656.65  5275.3  656.06  5275.8  655.56  5281.0  655.56
  5281.5  656.06  5418.7  657.44  5456.0  658.43  5477.6  658.62  5514.8  659.73
  5599.8  661.25  5632.5  661.50  5645.8  662.15  5654.0  661.81  5683.9  661.87
#Mann=4,-1,0
  3764.6    0.05       0  5275.3   0.035       0  5281.5    0.05       0
  5599.8     0.1       0
Bank Sta=5275.3,5281.5
Exp/Cntr=0.3,0.1

Type RM Length L Ch R = 1,61511,658,658,658
BEGIN DESCRIPTION:
Buckhorn Creek 95.0
END DESCRIPTION:
XS GIS Cut Line= 3
      1950968.57     13523363.79      1950225.50     13523214.48
      1949328.08     13523062.02
#Sta/Elev= 30
  3681.9  664.67  3767.1  664.22  3838.5  662.98  3899.4  662.67  3971.0  660.70
  4042.5  658.96  4083.3  658.82  4093.5  658.18  4246.5  656.29  4328.1  655.85
  4491.0  656.56  4633.1  656.11  4785.2  654.34  4914.0  653.65  4914.5  653.15
  4919.7  653.15  4920.2  653.65  4957.6  654.16  5008.7  653.80  5050.2  654.66
  5099.6  656.01  5124.2  658.49  5130.1  657.45  5150.4  656.86  5211.2  658.19
  5244.7  658.43  5251.8  659.10  5272.1  658.85  5322.8  659.59  5350.1  659.20
#Mann=5,-1,0
  3681.9     0.1       0  3971.0    0.05       0  4914.0   0.035       0
  4920.2    0.05       0  5050.2     0.1       0
Bank Sta=4914,4920.2
Exp/Cntr=0.3,0.1

Type RM Length L Ch R = 1,60853,861,861,861
BEGIN DESCRIPTION:
Buckhorn Creek 94.0
END DESCRIPTION:
XS GIS Cut Line= 4
      1950825.01     13522525.00      1950315.77     13522572.12
      1949561.10     13522705.29      1949053.99     13523287.05
#Sta/Elev= 30
  4067.9  667.42  4198.5  665.85  4390.8  659.07  4413.4  658.82  4484.2  657.98
  4506.6  657.71  4625.2  656.72  4752.7  653.53  4823.8  653.54  4972.9  651.40
  4973.4  650.90  4979.3  651.40  5089.0  652.80  5128.4  652.06  5189.4  653.07
  5230.0  652.70  5256.5  653.79  5261.6  653.03  5290.9  653.90  5301.1  653.09
  5392.3  653.76  5555.6  656.74  5625.9  660.42  5633.5  659.77  5640.1  660.95
  5647.7  659.11  5654.3  660.13  5703.7  658.63  5746.4  659.83  6117.4  658.75
#Mann=7,-1,0
  4067.9     0.1       0  4390.8    0.05       0  4413.4     0.1       0
  4484.2    0.05       0  4506.6     0.1       0  4972.9    0.07       0
  4979.3     0.1       0
Bank Sta=4972.9,4979.3
Exp/Cntr=0.3,0.1

Type RM Length L Ch R = 1,59992,876,876,876
BEGIN DESCRIPTION:
Buckhorn Creek 93.0
END DESCRIPTION:
XS GIS Cut Line= 4
      1950824.98     13521975.00      1949725.00     13521875.00
      1948907.21     13521874.26      1948602.41     13522080.45
#Sta/Elev= 30
  3834.8  665.07  4105.9  660.64  4608.0  656.99  4871.8  650.93  4976.1  648.54
  4976.6  648.04  4982.6  648.54  5009.3  649.70  5039.3  654.37  5069.3  656.56
  5079.3  656.06  5099.3  651.00  5139.4  650.57  5189.3  651.82  5237.7  655.17
  5299.3  657.04  5336.0  660.07  5349.3  661.18  5359.3  660.16  5379.3  663.05
  5399.3  663.80  5539.3  663.41  5599.3  657.73  5639.3  661.34  5766.6  665.94
  5916.7  669.40  5976.3  669.38  6012.2  670.68  6018.3  672.09  6125.1  672.63
#Mann=7,-1,0
  3834.8    0.05       0  4871.8     0.1       0  4976.1    0.07       0
  4982.6     0.1       0  5139.4    0.07       0  5237.7    0.12       0
  5336.0     0.1       0
Bank Sta=4976.1,4982.6
Exp/Cntr=0.3,0.1

Type RM Length L Ch R = 1,59116,436,436,436
BEGIN DESCRIPTION:
Buckhorn Creek 92.0
END DESCRIPTION:
XS GIS Cut Line= 3
      1950424.97     13521874.97      1949525.00     13521075.00
      1948324.97     13520975.00
#Sta/Elev= 30
  3795.5  660.46  3845.2  659.54  3958.1  658.78  4156.7  655.81  4447.3  649.66
  4539.3  648.16  4659.7  647.23  4841.7  647.21  4958.4  645.65  4964.1  645.51
  4981.9  642.62  4982.4  642.12  4989.3  642.12  4989.8  642.62  5002.1  642.83
  5019.7  644.56  5057.3  647.12  5062.3  647.50  5079.9  646.59  5120.0  646.36
  5298.1  648.26  5320.7  648.03  5392.0  649.21  5892.7  654.80  5952.9  656.22
  6020.6  658.82  6025.7  658.37  6073.3  659.79  6153.6  664.53  6203.8  665.37
#Mann=7,-1,0
  3795.5    0.05       0  4841.7     0.1       0  4958.4    0.12       0
  4981.9    0.07       0  4989.8    0.12       0  5057.3     0.1       0
  5392.0    0.05       0
Bank Sta=4981.9,4989.8
Exp/Cntr=0.3,0.1

Type RM Length L Ch R = 1,58680,468,468,468
BEGIN DESCRIPTION:
Buckhorn Creek 91.0
END DESCRIPTION:
XS GIS Cut Line= 3
      1950424.99     13521774.99      1949625.00     13520675.00
      1948618.95     13519802.23
#Sta/Elev= 30
  3629.0  659.63  3707.4  659.05  3772.3  657.83  3914.5  656.03  4144.8  650.99
  4366.6  647.27  4502.6  646.19  4810.2  645.54  4916.9  645.77  4952.4  644.76
  4975.6  644.62  4981.7  644.15  4982.2  643.65  4989.9  643.65  4990.4  644.15
  4996.5  644.32  5019.4  644.56  5081.8  644.86  5137.7  645.83  5329.6  647.72
  5442.6  649.36  5655.3  653.69  5804.4  654.33  5853.8  654.98  6002.9  655.21
  6023.8  655.70  6045.7  655.46  6066.5  655.91  6109.3  655.91  6321.0  658.62
#Mann=5,-1,0
  3629.0    0.05       0  4981.7    0.07       0  4990.4    0.05       0
  4996.5     0.1       0  5019.4    0.05       0
Bank Sta=4981.7,4990.4
Exp/Cntr=0.3,0.1

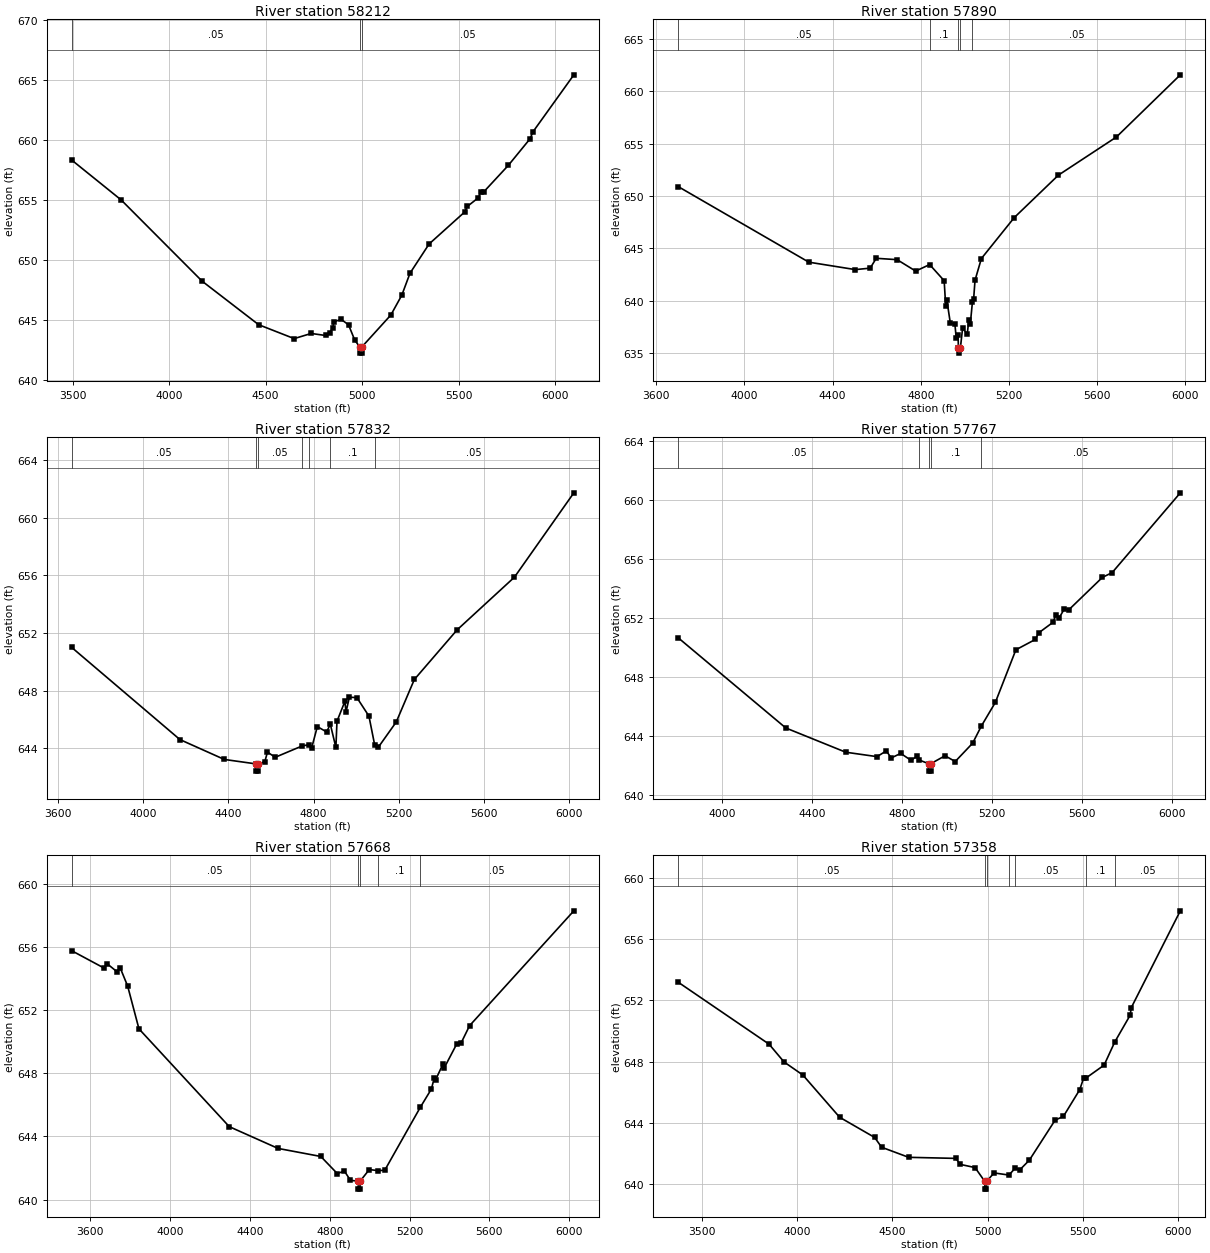
Type RM Length L Ch R = 1,58212,322,322,322
BEGIN DESCRIPTION:
Buckhorn Creek 90.0
END DESCRIPTION:
XS GIS Cut Line= 3
      1950638.70     13521608.58      1949925.00     13520325.00
      1949125.02     13519525.02
#Sta/Elev= 30
  3496.0  658.34  3751.8  655.02  4170.9  648.25  4463.7  644.62  4647.8  643.46
  4735.8  643.89  4810.3  643.72  4832.0  643.93  4848.0  644.38  4853.7  644.87
  4891.5  645.06  4929.2  644.61  4961.8  643.32  4988.5  642.75  4989.0  642.25
  4996.8  642.25  4997.3  642.75  5148.5  645.43  5205.1  647.08  5247.5  648.91
  5346.5  651.35  5530.3  654.01  5544.5  654.48  5601.1  655.20  5615.2  655.71
  5629.3  655.69  5756.6  657.90  5869.8  660.13  5883.9  660.69  6096.0  665.45
#Mann=3,-1,0
  3496.0    0.05       0  4988.5   0.035       0  4997.3    0.05       0
Bank Sta=4988.5,4997.3
Exp/Cntr=0.3,0.1

Type RM Length L Ch R = 1,57890,58,58,58
BEGIN DESCRIPTION:
Mapping XS 96ed8a61
END DESCRIPTION:
XS GIS Cut Line= 6
      1950568.52     13521096.68      1950013.83     13520193.02
      1950157.06     13520172.18      1950167.47     13520133.12
      1950110.18     13520062.81      1949373.55     13519479.75
#Sta/Elev= 30
  3700.5  650.90  4292.6  643.68  4503.4  642.97  4570.8  643.11  4598.1  644.05
  4692.8  643.92  4776.8  642.83  4840.3  643.45  4906.1  641.91  4913.0  639.51
  4918.1  640.08  4934.2  637.84  4954.5  637.81  4960.9  636.42  4968.8  636.72
  4970.9  635.49  4971.4  634.99  4979.7  635.49  4989.7  637.38  5010.5  636.80
  5018.4  638.19  5024.8  637.82  5034.3  639.89  5039.6  640.13  5046.0  641.95
  5074.9  644.03  5223.9  647.94  5424.3  652.00  5687.1  655.64  5976.7  661.58
#Mann=5,-1,0
  3700.5    0.05       0  4840.3     0.1       0  4970.9    0.07       0
  4979.7     0.1       0  5034.3    0.05       0
Bank Sta=4970.9,4979.7
Exp/Cntr=0.3,0.1

Type RM Length L Ch R = 1,57832,65,65,65
BEGIN DESCRIPTION:
Mapping XS d0c3a4e4
END DESCRIPTION:
XS GIS Cut Line= 6
      1950625.79     13521086.22      1950055.50     13520203.43
      1950170.08     13520229.47      1950203.93     13520140.93
      1950190.91     13520075.83      1949383.60     13519445.60
#Sta/Elev= 30
  3664.2  651.00  4172.0  644.61  4380.5  643.23  4530.3  642.92  4530.8  642.42
  4538.6  642.42  4539.1  642.92  4570.5  643.07  4583.1  643.74  4619.4  643.38
  4746.3  644.17  4780.2  644.26  4790.8  644.04  4817.2  645.51  4860.7  645.14
  4878.3  645.67  4904.4  644.06  4909.5  645.88  4946.7  647.26  4951.8  646.52
  4967.7  647.55  5003.0  647.52  5059.5  646.24  5086.3  644.25  5102.8  644.06
  5187.8  645.83  5272.8  648.78  5473.5  652.22  5742.9  655.88  6021.7  661.73
#Mann=7,-1,0
  3664.2    0.05       0  4530.3    0.07       0  4539.1    0.05       0
  4746.3     0.1       0  4780.2    0.05       0  4878.3     0.1       0
  5086.3    0.05       0
Bank Sta=4530.3,4539.1
Exp/Cntr=0.3,0.1

Type RM Length L Ch R = 1,57767,99,99,99
BEGIN DESCRIPTION:
Mapping XS 7da7815e
END DESCRIPTION:
XS GIS Cut Line= 6
      1950670.10     13521049.82      1950180.50     13520291.97
      1950256.02     13520219.06      1950284.66     13520159.16
      1950245.60     13520044.58      1949443.52     13519390.94
#Sta/Elev= 30
  3805.2  650.66  4282.9  644.56  4549.1  642.92  4688.0  642.62  4729.6  643.01
  4751.0  642.53  4793.4  642.84  4839.1  642.37  4867.4  642.67  4872.5  642.41
  4917.8  642.14  4918.3  641.64  4926.1  641.64  4926.6  642.14  4990.2  642.68
  5035.4  642.29  5112.8  643.53  5151.5  644.69  5213.7  646.29  5304.9  649.85
  5391.4  650.55  5405.8  650.99  5469.8  651.71  5483.0  652.22  5497.0  652.01
  5519.5  652.60  5540.3  652.56  5689.2  654.75  5732.4  655.07  6035.2  660.47
#Mann=5,-1,0
  3805.2    0.05       0  4872.5     0.1       0  4917.8    0.07       0
  4926.6     0.1       0  5151.5    0.05       0
Bank Sta=4917.8,4926.6
Exp/Cntr=0.3,0.1

Type RM Length L Ch R = 1,57668,310,310,310
BEGIN DESCRIPTION:
Buckhorn Creek 89.0
END DESCRIPTION:
XS GIS Cut Line= 3
      1951044.92     13521332.49      1950357.44     13520035.66
      1949582.87     13519328.67
#Sta/Elev= 30
  3507.2  655.77  3667.8  654.68  3684.1  654.95  3733.8  654.44  3750.1  654.68
  3787.3  653.53  3843.9  650.82  4296.6  644.62  4541.2  643.24  4755.5  642.73
  4837.8  641.65  4873.9  641.80  4903.8  641.22  4943.4  641.16  4943.9  640.66
  4951.7  640.66  4952.2  641.16  4998.4  641.90  5044.1  641.83  5076.1  641.86
  5254.3  645.85  5309.9  647.01  5324.0  647.71  5330.8  647.59  5366.6  648.56
  5373.4  648.33  5437.5  649.88  5458.5  649.92  5501.1  651.02  6023.7  658.30
#Mann=5,-1,0
  3507.2    0.05       0  4943.4   0.035       0  4952.2    0.05       0
  5044.1     0.1       0  5254.3    0.05       0
Bank Sta=4943.4,4952.2
Exp/Cntr=0.3,0.1

Type RM Length L Ch R = 1,57358,510,510,510
BEGIN DESCRIPTION:
Buckhorn Creek 88.0
END DESCRIPTION:
XS GIS Cut Line= 3
      1951659.50     13521191.88      1950625.00     13519925.00
      1950025.00     13519125.00
#Sta/Elev= 30
  3375.3  653.19  3852.1  649.14  3930.4  647.98  4029.7  647.12  4222.6  644.36
  4406.4  643.04  4442.8  642.40  4584.9  641.74  4832.8  641.67  4855.1  641.28
  4933.4  641.07  4984.8  640.16  4985.3  639.66  4993.4  639.66  4993.9  640.16
  5032.8  640.72  5111.5  640.58  5144.6  641.04  5168.2  640.92  5218.2  641.55
  5353.6  644.17  5397.4  644.42  5482.8  646.16  5503.6  646.93  5515.1  646.92
  5610.9  647.77  5666.7  649.28  5747.4  651.03  5753.6  651.53  6010.9  657.86
#Mann=7,-1,0
  3375.3    0.05       0  4984.8   0.035       0  4993.9    0.05       0
  5111.5    0.16       0  5144.6    0.05       0  5515.1     0.1       0
  5666.7    0.05       0
Bank Sta=4984.8,4993.9
Exp/Cntr=0.3,0.1