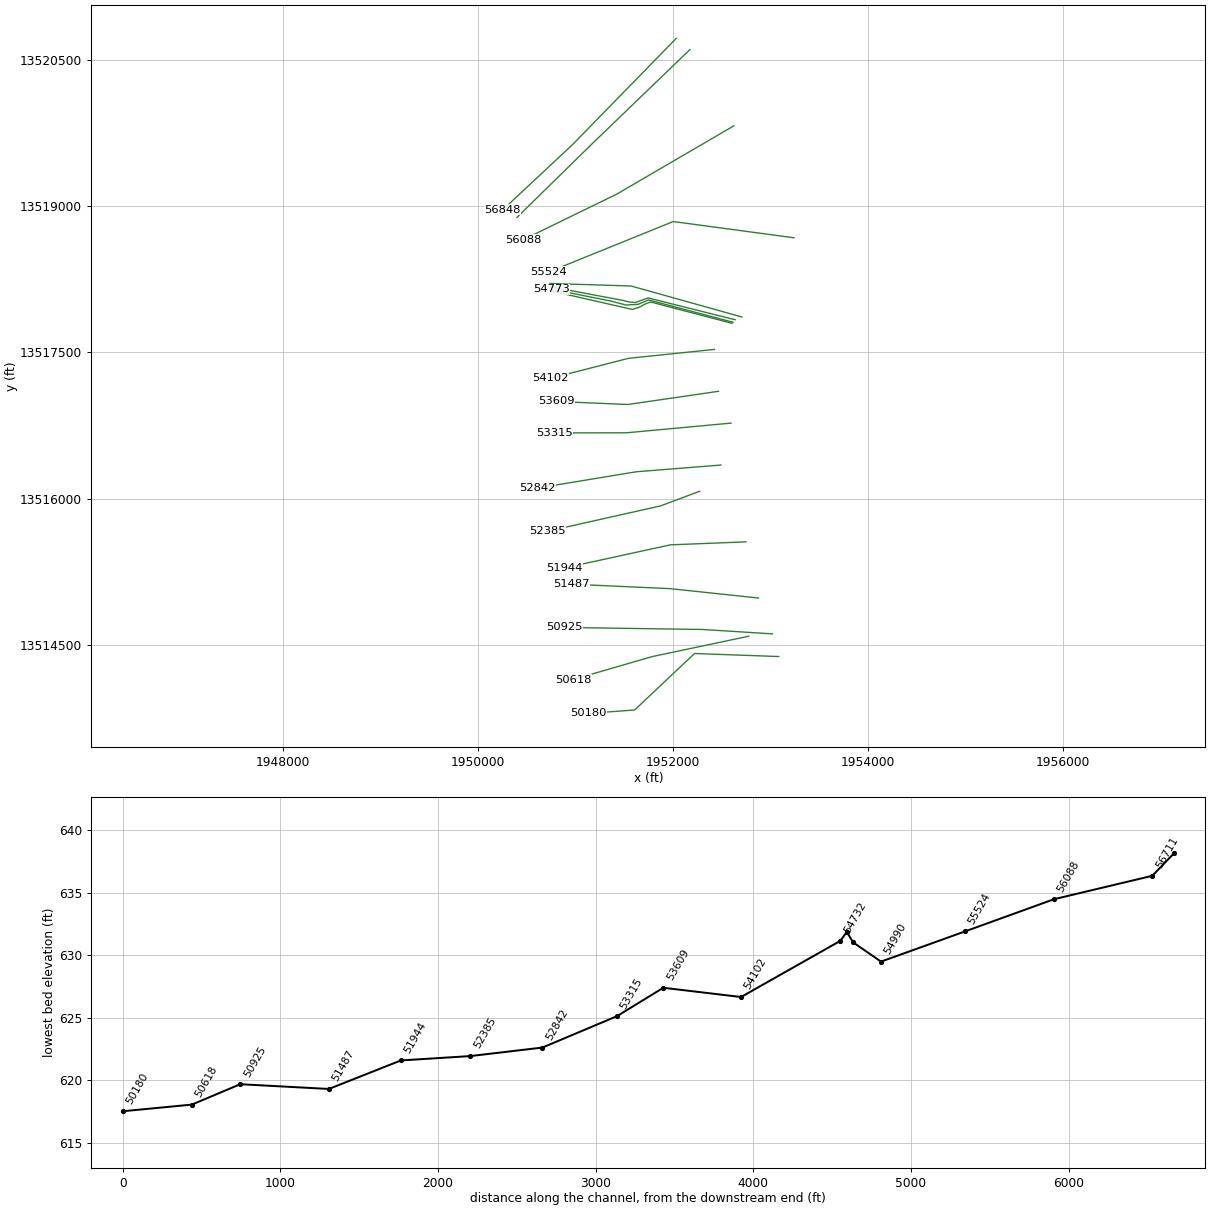
HEC-RAS study Buckhorn Creek.prj: Buckhorn Creek Base Level Engineering

--- Buckhorn Creek.g01 (geometry) --- (continued)

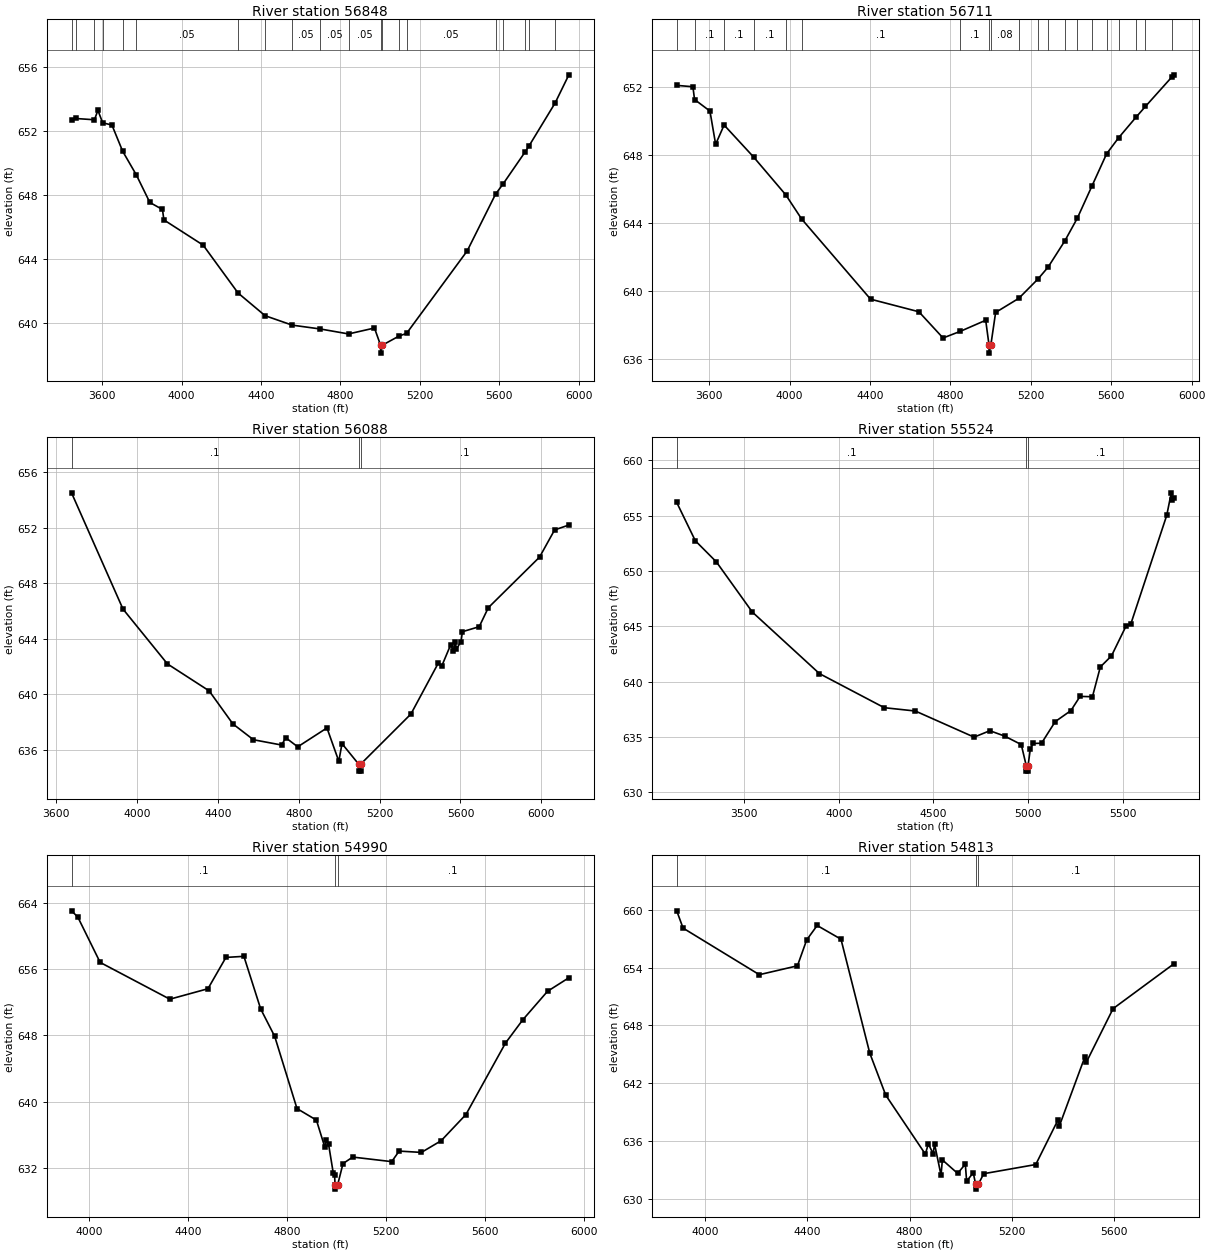
Type RM Length L Ch R = 1,56848,137,137,137
BEGIN DESCRIPTION:
Buckhorn Creek 87.0
END DESCRIPTION:
XS GIS Cut Line= 3
      1952034.54     13520723.18      1950966.82     13519629.41
      1950253.30     13518962.77
#Sta/Elev= 30
  3445.8  652.73  3466.3  652.81  3561.3  652.73  3578.6  653.32  3602.7  652.54
  3649.3  652.40  3703.4  650.76  3771.9  649.29  3840.2  647.56  3903.9  647.12
  3910.9  646.47  4108.9  644.89  4284.5  641.90  4420.8  640.48  4557.2  639.89
  4698.8  639.65  4841.0  639.34  4971.6  639.71  5002.3  638.64  5002.8  638.14
  5011.5  638.64  5097.3  639.22  5133.1  639.37  5438.7  644.53  5581.6  648.08
  5620.2  648.73  5731.1  650.73  5750.9  651.11  5881.6  653.78  5950.8  655.54
#Mann=20,-1,0
  3445.8    0.08       0  3466.3     0.1       0  3561.3    0.08       0
  3602.7     0.1       0  3703.4    0.08       0  3771.9    0.05       0
  4284.5    0.05       0  4420.8    0.05       0  4557.2    0.05       0
  4698.8    0.05       0  4841.0    0.05       0  5002.3    0.04       0
  5011.5    0.05       0  5097.3    0.16       0  5133.1    0.05       0
  5581.6    0.08       0  5620.2    0.05       0  5731.1    0.08       0
  5750.9    0.05       0  5881.6    0.05       0
Bank Sta=5002.3,5011.5
Exp/Cntr=0.3,0.1

Type RM Length L Ch R = 1,56711,623,623,623
BEGIN DESCRIPTION:
Buckhorn Creek 86.0
END DESCRIPTION:
XS GIS Cut Line= 3
      1952175.11     13520608.54      1951175.15     13519645.03
      1950399.55     13518885.05
#Sta/Elev= 30
  3438.0  652.08  3518.5  652.00  3526.7  651.25  3603.3  650.57  3631.6  648.62
  3673.7  649.75  3820.6  647.87  3980.5  645.65  4059.5  644.23  4402.4  639.52
  4642.9  638.78  4763.1  637.24  4849.0  637.63  4975.3  638.28  4991.6  636.85
  4992.1  636.35  5001.2  636.85  5024.7  638.74  5140.1  639.57  5235.9  640.71
  5285.7  641.40  5369.4  642.95  5431.3  644.28  5502.9  646.14  5576.9  648.06
  5636.5  649.00  5722.5  650.20  5770.0  650.84  5903.6  652.60  5912.5  652.70
#Mann=20,-1,0
  3438.0     0.1       0  3526.7     0.1       0  3673.7     0.1       0
  3820.6     0.1       0  3980.5    0.05       0  4059.5     0.1       0
  4849.0     0.1       0  4991.6    0.07       0  5001.2    0.08       0
  5140.1     0.1       0  5235.9    0.08       0  5285.7     0.1       0
  5369.4    0.05       0  5431.3     0.1       0  5502.9    0.08       0
  5576.9     0.1       0  5636.5    0.05       0  5722.5     0.1       0
  5770.0    0.05       0  5903.6    0.05       0
Bank Sta=4991.6,5001.2
Exp/Cntr=0.3,0.1

Type RM Length L Ch R = 1,56088,564,564,564
BEGIN DESCRIPTION:
Buckhorn Creek 85.0
END DESCRIPTION:
XS GIS Cut Line= 3
      1952624.96     13519824.98      1951425.00     13519125.00
      1950461.63     13518655.46
#Sta/Elev= 30
  3675.4  654.52  3930.0  646.15  4150.0  642.20  4356.3  640.26  4473.8  637.88
  4575.5  636.74  4714.4  636.36  4735.9  636.88  4794.6  636.23  4939.3  637.59
  4998.0  635.19  5013.7  636.46  5096.3  634.98  5096.8  634.48  5105.5  634.48
  5106.0  634.98  5354.7  638.59  5489.9  642.25  5506.8  642.03  5551.9  643.59
  5565.2  643.12  5574.5  643.77  5580.0  643.27  5602.6  643.81  5609.7  644.52
  5692.7  644.88  5737.8  646.25  5991.2  649.89  6065.8  651.85  6136.3  652.20
#Mann=3,-1,0
  3675.4     0.1       0  5096.3    0.07       0  5106.0     0.1       0
Bank Sta=5096.3,5106
Exp/Cntr=0.3,0.1

Type RM Length L Ch R = 1,55524,534,534,534
BEGIN DESCRIPTION:
Buckhorn Creek 84.0
END DESCRIPTION:
XS GIS Cut Line= 3
      1953242.82     13518676.29      1952003.27     13518842.95
      1950725.03     13518325.01
#Sta/Elev= 30
  3142.4  656.18  3240.7  652.72  3352.1  650.81  3542.1  646.28  3897.0  640.72
  4240.0  637.64  4404.2  637.34  4714.9  634.98  4798.1  635.56  4875.8  635.08
  4964.3  634.31  4990.6  632.41  4991.1  631.91  4999.8  631.91  5000.3  632.41
  5012.5  633.94  5027.8  634.41  5071.5  634.43  5143.8  636.38  5226.9  637.38
  5275.2  638.66  5340.7  638.63  5382.4  641.32  5441.4  642.32  5519.1  645.04
  5543.2  645.18  5733.5  655.01  5757.6  657.05  5763.0  656.38  5772.3  656.60
#Mann=3,-1,0
  3142.4     0.1       0  4990.6    0.07       0  5000.3     0.1       0
Bank Sta=4990.6,5000.3
Exp/Cntr=0.3,0.1

Type RM Length L Ch R = 1,54990,177,177,177
BEGIN DESCRIPTION:
Buckhorn Creek 83.0
END DESCRIPTION:
XS GIS Cut Line= 3
      1952706.37     13517863.79      1951570.98     13518181.49
      1950738.79     13518207.50
#Sta/Elev= 30
  3927.6  663.00  3952.8  662.26  4043.3  656.79  4325.3  652.36  4479.4  653.62
  4552.1  657.39  4624.8  657.52  4692.6  651.19  4749.4  647.88  4839.5  639.19
  4918.1  637.80  4952.2  634.53  4957.4  635.42  4967.4  634.87  4986.4  631.40
  4991.6  631.25  4993.4  629.99  4993.9  629.49  5003.8  629.99  5025.7  632.57
  5065.0  633.35  5222.6  632.80  5252.7  634.07  5342.7  633.91  5422.7  635.32
  5522.8  638.47  5682.9  647.08  5752.9  649.88  5852.9  653.31  5939.2  654.94
#Mann=3,-1,0
  3927.6     0.1       0  4993.4    0.07       0  5003.8     0.1       0
Bank Sta=4993.4,5003.8
Exp/Cntr=0.3,0.1

Type RM Length L Ch R = 1,54813,40,40,40
BEGIN DESCRIPTION:
Buckhorn Creek 82.0
END DESCRIPTION:
XS GIS Cut Line= 6
      1952638.73     13517835.13      1951745.46     13518059.10
      1951615.25     13518012.22      1951550.15     13518017.43
      1951490.25     13518033.05      1950742.89     13518173.67
#Sta/Elev= 30
  3888.2  659.88  3913.0  658.09  4211.6  653.26  4360.8  654.18  4396.9  656.86
  4438.0  658.36  4531.2  656.94  4643.9  645.13  4706.5  640.77  4861.5  634.66
  4873.2  635.72  4892.2  634.70  4897.5  635.72  4922.9  632.48  4928.2  634.06
  4987.9  632.66  5018.0  633.62  5023.2  631.85  5049.1  632.73  5058.4  631.53
  5058.9  631.03  5068.8  631.53  5090.2  632.63  5293.8  633.58  5381.5  638.24
  5386.6  637.61  5486.4  644.76  5491.5  644.17  5596.5  649.74  5835.2  654.40
#Mann=3,-1,0
  3888.2     0.1       0  5058.4    0.07       0  5068.8     0.1       0
Bank Sta=5058.4,5068.8
Exp/Cntr=0.3,0.1

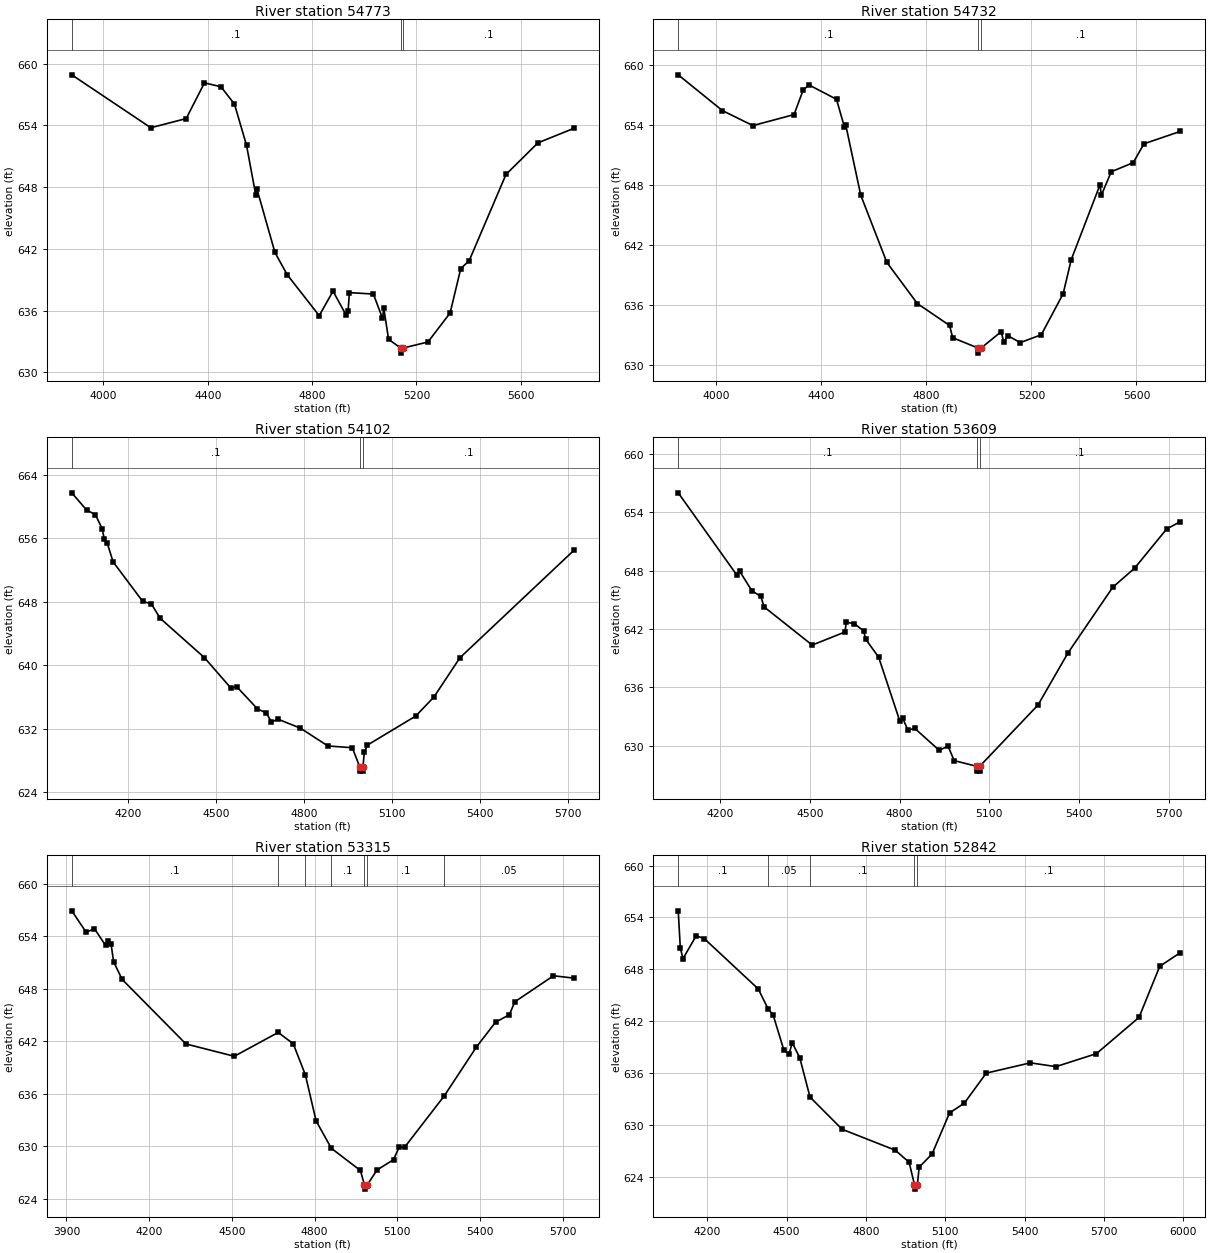
Type RM Length L Ch R = 1,54773,41,41,41
BEGIN DESCRIPTION:
Mapping XS ab031b1c
END DESCRIPTION:
XS GIS Cut Line= 6
      1952617.88     13517809.09      1951749.80     13518038.26
      1951642.16     13517993.12      1951517.16     13517986.18
      1951374.80     13518024.37      1950749.91     13518149.35
#Sta/Elev= 30
  3878.9  658.90  4181.8  653.76  4317.4  654.65  4387.6  658.12  4450.7  657.74
  4502.4  656.06  4548.7  652.06  4583.8  647.27  4589.0  647.77  4657.6  641.64
  4704.6  639.48  4827.3  635.50  4880.3  637.88  4930.7  635.54  4938.0  635.96
  4943.0  637.74  5034.9  637.60  5069.7  635.26  5074.9  636.20  5093.3  633.20
  5139.3  632.36  5139.8  631.86  5149.7  632.36  5244.0  632.94  5329.0  635.76
  5369.8  640.07  5402.1  640.84  5543.2  649.22  5665.5  652.29  5803.3  653.70
#Mann=3,-1,0
  3878.9     0.1       0  5139.3    0.07       0  5149.7     0.1       0
Bank Sta=5139.3,5149.7
Exp/Cntr=0.3,0.1

Type RM Length L Ch R = 1,54732,630,630,630
BEGIN DESCRIPTION:
Mapping XS 0c9010e7
END DESCRIPTION:
XS GIS Cut Line= 6
      1952607.47     13517798.67      1951770.64     13518017.43
      1951708.14     13517993.12      1951652.58     13517961.87
      1951583.14     13517941.04      1950760.22     13518128.54
#Sta/Elev= 30
  3854.6  659.00  4022.9  655.42  4139.0  653.92  4295.6  655.02  4330.9  657.51
  4353.3  657.98  4457.4  656.55  4487.5  653.78  4492.7  653.97  4549.7  646.96
  4649.3  640.22  4765.4  636.11  4888.0  633.92  4900.0  632.69  4997.4  631.65
  4997.9  631.15  5007.8  631.65  5084.5  633.29  5094.8  632.23  5109.3  632.91
  5157.1  632.20  5237.4  632.99  5320.6  637.09  5351.4  640.50  5461.1  648.00
  5466.2  646.95  5503.8  649.30  5587.5  650.21  5628.6  652.10  5766.9  653.34
#Mann=3,-1,0
  3854.6     0.1       0  4997.4    0.07       0  5007.8     0.1       0
Bank Sta=4997.4,5007.8
Exp/Cntr=0.3,0.1

Type RM Length L Ch R = 1,54102,493,493,493
BEGIN DESCRIPTION:
Buckhorn Creek 81.0
END DESCRIPTION:
XS GIS Cut Line= 3
      1952425.12     13517530.45      1951544.94     13517439.30
      1950742.89     13517233.58
#Sta/Elev= 30
  4007.6  661.72  4058.0  659.56  4088.1  658.98  4111.2  657.21  4118.3  655.94
  4128.4  655.42  4148.5  653.03  4249.0  648.07  4279.2  647.72  4309.3  645.91
  4460.1  640.96  4550.6  637.12  4570.7  637.28  4641.1  634.50  4671.3  633.99
  4688.9  632.85  4711.5  633.20  4787.8  632.07  4881.5  629.83  4964.7  629.61
  4990.4  627.16  4990.9  626.66  5000.4  626.66  5000.9  627.16  5005.6  629.02
  5016.3  629.94  5181.5  633.61  5243.4  636.01  5331.8  640.94  5720.5  654.47
#Mann=3,-1,0
  4007.6     0.1       0  4990.4    0.07       0  5000.9     0.1       0
Bank Sta=4990.4,5000.9
Exp/Cntr=0.3,0.1

Type RM Length L Ch R = 1,53609,294,294,294
BEGIN DESCRIPTION:
Buckhorn Creek 80.0
END DESCRIPTION:
XS GIS Cut Line= 3
      1952468.57     13517100.77      1951538.00     13516965.35
      1950799.23     13516996.56
#Sta/Elev= 30
  4059.3  655.99  4254.9  647.56  4265.0  647.93  4305.4  645.94  4335.7  645.34
  4346.6  644.27  4507.5  640.35  4616.9  641.69  4621.9  642.70  4649.0  642.54
  4679.3  641.81  4687.0  640.93  4729.9  639.10  4800.6  632.54  4810.7  632.82
  4827.2  631.63  4851.1  631.78  4932.0  629.55  4962.3  629.95  4982.5  628.48
  5057.4  627.90  5057.9  627.40  5067.6  627.40  5068.1  627.90  5262.9  634.19
  5363.0  639.53  5513.1  646.29  5585.9  648.24  5693.3  652.27  5739.1  653.03
#Mann=3,-1,0
  4059.3     0.1       0  5057.4    0.07       0  5068.1     0.1       0
Bank Sta=5057.4,5068.1
Exp/Cntr=0.3,0.1

Type RM Length L Ch R = 1,53315,473,473,473
BEGIN DESCRIPTION:
Buckhorn Creek 79.0
END DESCRIPTION:
XS GIS Cut Line= 3
      1952597.00     13516774.37      1951525.00     13516675.00
      1950781.10     13516673.68
#Sta/Elev= 30
  3919.2  656.89  3971.5  654.44  4001.6  654.85  4041.7  652.94  4051.8  653.50
  4061.8  653.07  4070.9  651.07  4102.0  649.06  4333.0  641.70  4508.5  640.29
  4667.7  643.01  4722.3  641.72  4766.2  638.17  4805.0  632.93  4860.3  629.79
  4965.7  627.26  4980.4  625.63  4980.9  625.13  4991.1  625.63  5025.8  627.31
  5085.8  628.49  5105.8  629.89  5125.8  629.90  5269.8  635.77  5385.8  641.32
  5455.8  644.18  5505.8  645.03  5525.8  646.51  5665.8  649.48  5739.7  649.21
#Mann=7,-1,0
  3919.2     0.1       0  4667.7    0.08       0  4766.2    0.05       0
  4860.3     0.1       0  4980.4    0.07       0  4991.1     0.1       0
  5269.8    0.05       0
Bank Sta=4980.4,4991.1
Exp/Cntr=0.3,0.1

Type RM Length L Ch R = 1,52842,457,457,457
BEGIN DESCRIPTION:
Buckhorn Creek 78.0
END DESCRIPTION:
XS GIS Cut Line= 3
      1952492.82     13516343.82      1951625.00     13516275.00
      1950610.95     13516107.71
#Sta/Elev= 30
  4090.6  654.77  4098.4  650.50  4108.5  649.24  4158.6  651.89  4188.7  651.57
  4393.1  645.75  4430.2  643.45  4449.5  642.73  4489.7  638.71  4509.7  638.23
  4521.6  639.53  4549.9  637.81  4588.9  633.25  4710.4  629.53  4911.0  627.12
  4963.7  625.72  4983.8  623.12  4984.3  622.62  4994.6  623.12  5001.7  625.16
  5050.3  626.68  5116.5  631.42  5172.5  632.56  5255.1  636.02  5422.1  637.21
  5518.6  636.77  5671.7  638.27  5832.8  642.46  5911.1  648.36  5988.9  649.94
#Mann=5,-1,0
  4090.6     0.1       0  4430.2    0.05       0  4588.9     0.1       0
  4983.8    0.07       0  4994.6     0.1       0
Bank Sta=4983.8,4994.6
Exp/Cntr=0.3,0.1

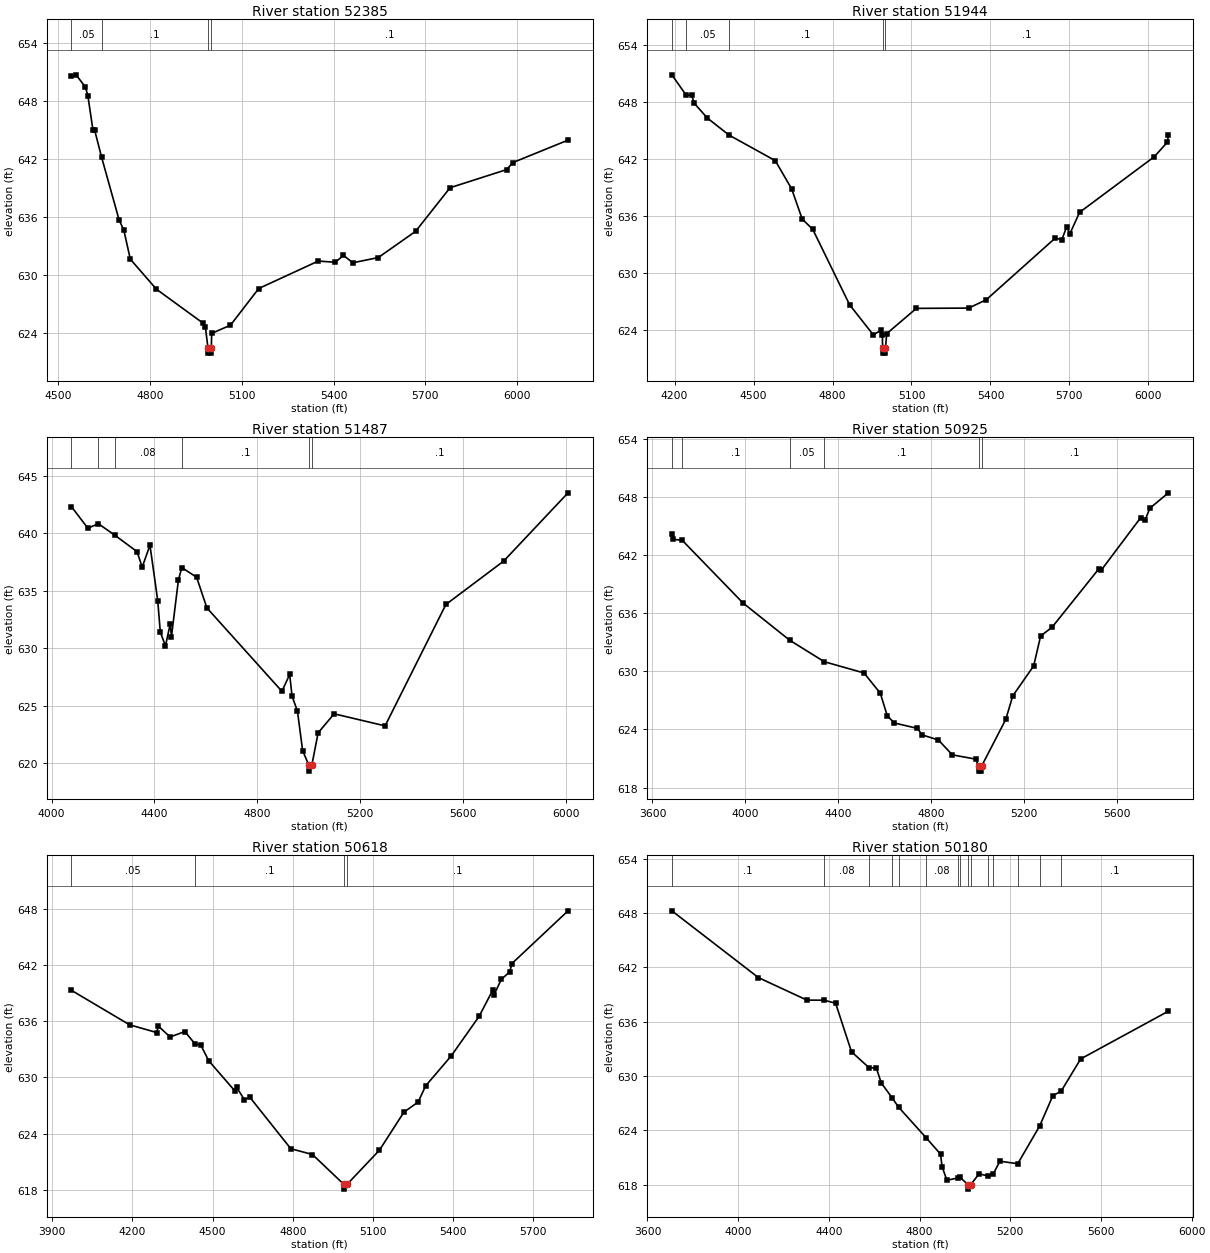
Type RM Length L Ch R = 1,52385,441,441,441
BEGIN DESCRIPTION:
Buckhorn Creek 77.0
END DESCRIPTION:
XS GIS Cut Line= 3
      1952274.98     13516074.99      1951875.00     13515925.00
      1950709.06     13515663.47
#Sta/Elev= 30
  4543.8  650.58  4558.9  650.71  4589.2  649.44  4597.2  648.57  4614.1  644.96
  4619.4  645.00  4641.9  642.22  4699.5  635.69  4714.7  634.66  4736.0  631.65
  4821.5  628.54  4973.5  625.04  4981.2  624.64  4989.8  622.44  4990.3  621.94
  5000.1  621.94  5000.6  622.44  5001.7  623.98  5063.2  624.83  5155.5  628.62
  5350.2  631.46  5405.8  631.33  5432.2  632.05  5462.9  631.28  5546.1  631.82
  5667.9  634.53  5780.6  639.04  5965.1  640.91  5985.6  641.64  6165.9  643.96
#Mann=4,-1,0
  4543.8    0.05       0  4641.9     0.1       0  4989.8    0.07       0
  5000.6     0.1       0
Bank Sta=4989.8,5000.6
Exp/Cntr=0.3,0.1

Type RM Length L Ch R = 1,51944,457,457,457
BEGIN DESCRIPTION:
Buckhorn Creek 76.0
END DESCRIPTION:
XS GIS Cut Line= 3
      1952749.79     13515555.62      1951975.00     13515525.00
      1950889.38     13515288.41
#Sta/Elev= 30
  4189.6  650.88  4243.9  648.74  4264.4  648.77  4274.5  647.89  4324.5  646.33
  4406.7  644.54  4582.4  641.85  4644.7  638.88  4684.8  635.70  4724.8  634.62
  4864.9  626.68  4955.0  623.51  4984.4  624.00  4989.5  623.48  4990.2  622.09
  4990.7  621.59  5000.7  621.59  5001.2  622.09  5005.9  623.64  5118.5  626.30
  5317.7  626.33  5384.6  627.22  5645.8  633.69  5671.2  633.54  5689.7  634.88
  5701.9  634.16  5738.8  636.41  6023.0  642.27  6072.1  643.79  6076.1  644.50
#Mann=5,-1,0
  4189.6     0.1       0  4243.9    0.05       0  4406.7     0.1       0
  4990.2    0.07       0  5001.2     0.1       0
Bank Sta=4990.2,5001.2
Exp/Cntr=0.3,0.1

Type RM Length L Ch R = 1,51487,562,562,562
BEGIN DESCRIPTION:
Buckhorn Creek 75.0
END DESCRIPTION:
XS GIS Cut Line= 3
      1952878.27     13514979.24      1951975.00     13515075.00
      1950954.69     13515121.59
#Sta/Elev= 30
  4077.6  642.33  4141.2  640.46  4182.0  640.85  4244.8  639.87  4332.3  638.42
  4352.4  637.07  4382.6  638.98  4412.7  634.16  4422.8  631.41  4442.9  630.21
  4461.1  632.11  4466.1  631.03  4493.2  635.96  4506.3  637.03  4563.9  636.19
  4603.8  633.52  4895.4  626.26  4925.6  627.73  4934.6  625.85  4955.8  624.53
  4975.9  621.09  5000.4  619.81  5000.9  619.31  5011.5  619.81  5036.0  622.64
  5098.3  624.30  5296.3  623.25  5532.7  633.82  5757.4  637.60  6007.3  643.54
#Mann=6,-1,0
  4077.6    0.08       0  4182.0     0.1       0  4244.8    0.08       0
  4506.3     0.1       0  5000.4    0.07       0  5011.5     0.1       0
Bank Sta=5000.4,5011.5
Exp/Cntr=0.3,0.1

Type RM Length L Ch R = 1,50925,307,307,307
BEGIN DESCRIPTION:
Buckhorn Creek 74.0
END DESCRIPTION:
XS GIS Cut Line= 3
      1953020.60     13514611.18      1952305.36     13514656.32
      1950885.17     13514677.15
#Sta/Elev= 30
  3683.5  644.19  3689.1  643.61  3728.1  643.51  3989.7  637.04  4190.5  633.20
  4339.5  630.98  4510.5  629.82  4580.5  627.73  4610.5  625.41  4640.5  624.66
  4740.6  624.10  4760.6  623.43  4830.6  622.90  4890.6  621.37  4990.6  620.93
  5005.0  620.19  5005.5  619.69  5015.7  619.69  5016.2  620.19  5120.6  625.03
  5150.6  627.45  5240.6  630.55  5270.6  633.63  5320.6  634.56  5520.6  640.55
  5530.6  640.40  5700.7  645.83  5720.7  645.63  5740.7  646.82  5820.5  648.41
#Mann=6,-1,0
  3683.5    0.05       0  3728.1     0.1       0  4190.5    0.05       0
  4339.5     0.1       0  5005.0    0.07       0  5016.2     0.1       0
Bank Sta=5005,5016.2
Exp/Cntr=0.3,0.1

Type RM Length L Ch R = 1,50618,438,438,438
BEGIN DESCRIPTION:
Buckhorn Creek 72.0
END DESCRIPTION:
XS GIS Cut Line= 3
      1952777.61     13514586.88      1951786.11     13514377.78
      1950975.50     13514142.43
#Sta/Elev= 30
  3972.3  639.30  4189.6  635.62  4291.5  634.79  4296.7  635.49  4341.3  634.32
  4396.2  634.90  4434.7  633.57  4455.3  633.49  4485.6  631.78  4585.1  628.50
  4590.2  628.93  4618.8  627.63  4640.0  627.86  4792.6  622.38  4873.6  621.76
  4991.5  618.56  4992.0  618.06  5002.8  618.56  5124.2  622.22  5215.9  626.29
  5268.8  627.36  5297.2  629.10  5392.9  632.30  5497.0  636.52  5547.7  639.30
  5552.9  638.83  5580.3  640.48  5611.5  641.28  5620.0  642.17  5829.7  647.80
#Mann=4,-1,0
  3972.3    0.05       0  4434.7     0.1       0  4991.5    0.07       0
  5002.8     0.1       0
Bank Sta=4991.5,5002.8
Exp/Cntr=0.3,0.1

Type RM Length L Ch R = 1,50180,138,138,138
BEGIN DESCRIPTION:
Buckhorn Creek 73.0
END DESCRIPTION:
XS GIS Cut Line= 4
      1953086.64     13514378.54      1952222.02     13514409.79
      1951607.44     13513829.93      1951129.13     13513795.27
#Sta/Elev= 30
  3707.7  648.23  4089.6  640.86  4303.3  638.38  4378.7  638.37  4429.8  638.04
  4499.9  632.68  4576.6  630.94  4609.7  630.88  4630.8  629.26  4679.5  627.58
  4707.9  626.56  4828.2  623.22  4892.5  621.39  4899.4  620.00  4920.8  618.50
  4970.5  618.78  4976.9  618.85  5014.3  618.03  5014.8  617.53  5025.6  618.03
  5062.4  619.21  5101.8  618.99  5125.5  619.23  5154.3  620.61  5233.0  620.33
  5329.5  624.49  5387.7  627.83  5424.8  628.35  5510.5  631.89  5897.4  637.16
#Mann=15,-1,0
  3707.7     0.1       0  4378.7    0.08       0  4576.6    0.05       0
  4679.5    0.08       0  4707.9    0.05       0  4828.2    0.08       0
  4970.5     0.1       0  4976.9    0.08       0  5014.3    0.07       0
  5025.6    0.08       0  5101.8     0.1       0  5125.5    0.08       0
  5233.0     0.1       0  5329.5    0.05       0  5424.8     0.1       0
Bank Sta=5014.3,5025.6
Exp/Cntr=0.3,0.1