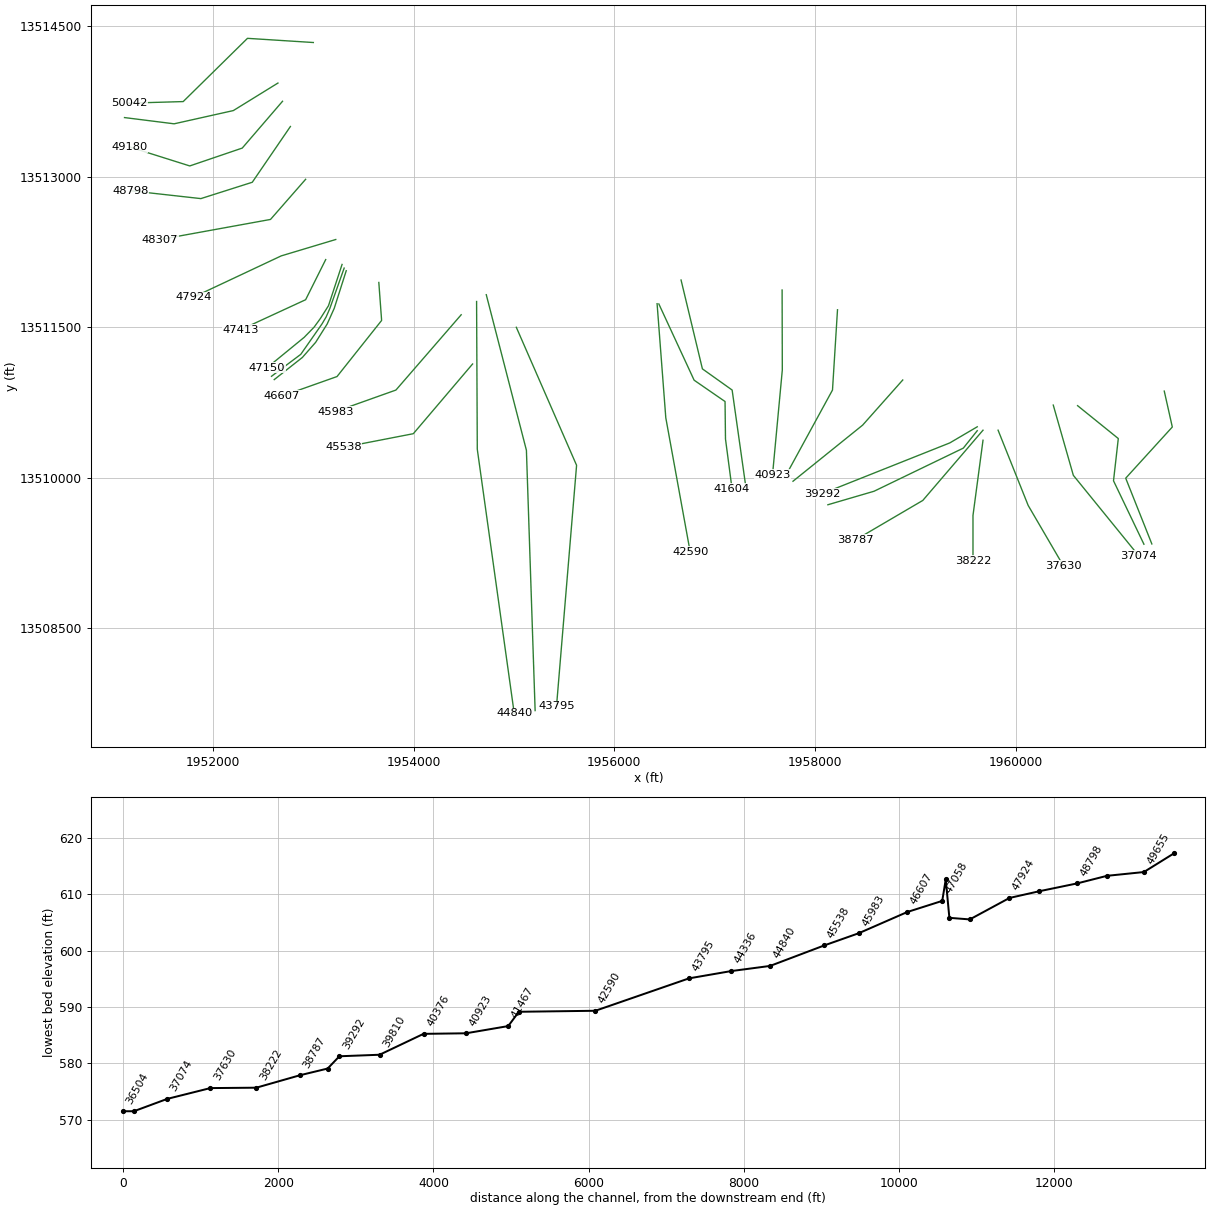
HEC-RAS study Buckhorn Creek.prj: Buckhorn Creek Base Level Engineering

--- Buckhorn Creek.g01 (geometry) --- (continued)

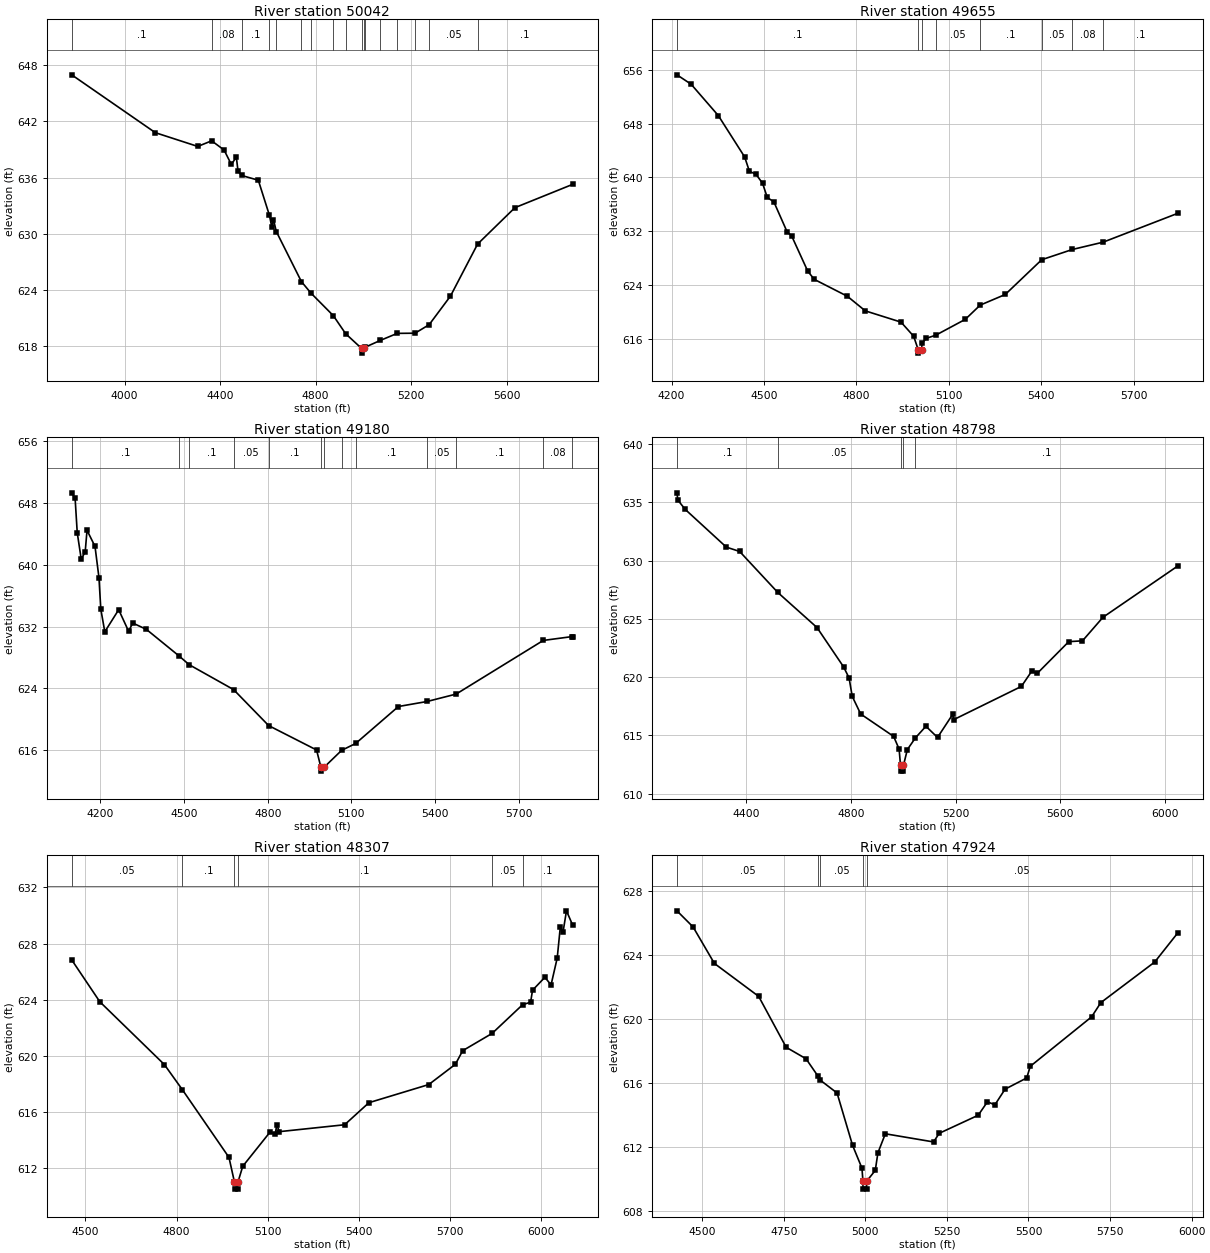
Type RM Length L Ch R = 1,50042,387,387,387
BEGIN DESCRIPTION:
Mapping XS b86b20b2
END DESCRIPTION:
XS GIS Cut Line= 4
      1953001.86     13514337.96      1952345.58     13514379.63
      1951704.95     13513749.42      1951163.33     13513733.79
#Sta/Elev= 30
  3778.4  646.98  4128.6  640.80  4306.3  639.33  4364.5  639.93  4416.5  638.95
  4446.8  637.41  4467.9  638.18  4475.1  636.66  4490.0  636.23  4559.9  635.72
  4606.6  631.96  4616.5  630.70  4623.5  631.50  4635.3  630.24  4740.4  624.89
  4780.5  623.66  4874.2  621.25  4925.8  619.32  4992.6  617.75  4993.1  617.25
  5003.9  617.75  5008.0  617.89  5071.1  618.61  5141.7  619.36  5216.4  619.38
  5275.5  620.29  5364.6  623.34  5478.3  628.90  5634.7  632.79  5876.5  635.28
#Mann=17,-1,0
  3778.4     0.1       0  4364.5    0.08       0  4490.0     0.1       0
  4606.6    0.08       0  4635.3     0.1       0  4740.4    0.08       0
  4780.5     0.1       0  4874.2    0.05       0  4925.8     0.1       0
  4992.6    0.07       0  5003.9     0.1       0  5008.0    0.05       0
  5071.1     0.1       0  5141.7    0.08       0  5216.4     0.1       0
  5275.5    0.05       0  5478.3     0.1       0
Bank Sta=4992.6,5003.9
Exp/Cntr=0.3,0.1

Type RM Length L Ch R = 1,49655,475,475,475
BEGIN DESCRIPTION:
Buckhorn Creek 71.0
END DESCRIPTION:
XS GIS Cut Line= 4
      1952649.10     13513934.09      1952204.66     13513659.79
      1951614.39     13513527.85      1951120.30     13513590.04
#Sta/Elev= 30
  4217.6  655.23  4263.5  653.84  4351.7  649.19  4437.3  643.04  4452.7  640.91
  4474.0  640.48  4495.3  639.14  4510.7  637.03  4531.9  636.39  4575.0  631.93
  4589.9  631.31  4641.9  626.10  4663.2  624.88  4770.3  622.38  4828.6  620.21
  4944.5  618.54  4985.4  616.45  5000.3  614.44  5000.8  613.94  5011.6  614.44
  5012.5  615.42  5026.4  616.13  5057.6  616.61  5153.0  618.95  5201.2  621.06
  5282.6  622.64  5401.0  627.80  5500.5  629.32  5600.0  630.40  5842.7  634.69
#Mann=8,-1,0
  4217.6     0.1       0  5000.3    0.07       0  5011.6     0.1       0
  5057.6    0.05       0  5201.2     0.1       0  5401.0    0.05       0
  5500.5    0.08       0  5600.0     0.1       0
Bank Sta=5000.3,5011.6
Exp/Cntr=0.3,0.1

Type RM Length L Ch R = 1,49180,382,382,382
BEGIN DESCRIPTION:
Buckhorn Creek 70.0
END DESCRIPTION:
XS GIS Cut Line= 4
      1952694.96     13513752.66      1952293.49     13513286.09
      1951770.49     13513108.14      1951171.51     13513296.95
#Sta/Elev= 30
  4097.4  649.32  4109.6  648.60  4117.2  644.15  4131.5  640.74  4145.7  641.66
  4152.3  644.47  4180.9  642.38  4195.1  638.33  4201.7  634.25  4216.0  631.32
  4265.8  634.18  4301.6  631.37  4315.8  632.46  4365.2  631.63  4481.5  628.21
  4518.4  627.06  4677.8  623.83  4803.4  619.17  4975.2  616.01  4990.8  613.77
  4991.3  613.27  5002.2  613.77  5065.0  615.96  5115.3  616.85  5268.7  621.64
  5371.4  622.29  5475.6  623.25  5788.0  630.20  5892.1  630.70  5893.4  630.70
#Mann=13,-1,0
  4097.4     0.1       0  4481.5    0.05       0  4518.4     0.1       0
  4677.8    0.05       0  4803.4     0.1       0  4990.8    0.07       0
  5002.2     0.1       0  5065.0    0.05       0  5115.3     0.1       0
  5371.4    0.05       0  5475.6     0.1       0  5788.0    0.08       0
  5892.1    0.05       0
Bank Sta=4990.8,5002.2
Exp/Cntr=0.3,0.1

Type RM Length L Ch R = 1,48798,491,491,491
BEGIN DESCRIPTION:
Buckhorn Creek 69.0
END DESCRIPTION:
XS GIS Cut Line= 4
      1952773.12     13513500.97      1952393.32     13512945.38
      1951881.17     13512782.62      1951180.19     13512860.75
#Sta/Elev= 30
  4134.7  635.81  4138.0  635.19  4166.2  634.39  4323.6  631.15  4374.4  630.78
  4520.4  627.26  4670.3  624.25  4771.8  620.88  4792.9  619.93  4804.9  618.35
  4837.4  616.83  4963.3  614.91  4984.3  613.82  4989.6  612.43  4990.1  611.93
  5000.5  611.93  5001.0  612.43  5015.8  613.78  5046.5  614.78  5086.8  615.78
  5131.2  614.82  5188.8  616.79  5194.2  616.36  5451.9  619.20  5492.2  620.53
  5512.3  620.31  5633.0  623.04  5685.5  623.11  5763.8  625.13  6050.4  629.54
#Mann=5,-1,0
  4134.7     0.1       0  4520.4    0.05       0  4989.6   0.035       0
  5001.0    0.05       0  5046.5     0.1       0
Bank Sta=4989.6,5001
Exp/Cntr=0.3,0.1

Type RM Length L Ch R = 1,48307,383,383,383
BEGIN DESCRIPTION:
Buckhorn Creek 68.0
END DESCRIPTION:
XS GIS Cut Line= 3
      1952925.02     13512975.02      1952575.00     13512575.00
      1951474.96     13512374.99
#Sta/Elev= 30
  4454.9  626.84  4547.5  623.86  4760.1  619.39  4819.4  617.60  4972.7  612.79
  4990.8  611.03  4991.3  610.53  5001.8  610.53  5002.3  611.03  5018.2  612.16
  5108.4  614.60  5124.9  614.42  5130.0  615.09  5138.9  614.62  5353.6  615.11
  5433.6  616.68  5630.6  617.97  5718.2  619.41  5742.4  620.38  5839.3  621.61
  5939.6  623.65  5966.0  623.83  5972.3  624.68  6013.0  625.60  6033.3  625.06
  6053.6  626.97  6063.8  629.18  6072.7  628.81  6084.1  630.33  6104.5  629.31
#Mann=6,-1,0
  4454.9    0.05       0  4819.4     0.1       0  4990.8    0.07       0
  5002.3     0.1       0  5839.3    0.05       0  5939.6     0.1       0
Bank Sta=4990.8,5002.3
Exp/Cntr=0.3,0.1

Type RM Length L Ch R = 1,47924,511,511,511
BEGIN DESCRIPTION:
Buckhorn Creek 67.0
END DESCRIPTION:
XS GIS Cut Line= 3
      1953224.96     13512374.99      1952681.95     13512211.87
      1951805.69     13511799.77
#Sta/Elev= 30
  4422.6  626.74  4472.1  625.73  4537.4  623.45  4673.1  621.39  4757.3  618.21
  4818.2  617.49  4855.3  616.39  4860.1  616.18  4913.3  615.35  4960.8  612.08
  4989.6  610.65  4992.6  609.84  4993.1  609.34  5003.7  609.34  5004.2  609.84
  5030.4  610.51  5038.5  611.61  5061.3  612.80  5209.1  612.29  5226.4  612.83
  5345.9  613.96  5374.2  614.80  5397.0  614.61  5428.2  615.59  5494.5  616.29
  5505.5  617.02  5693.4  620.11  5721.7  621.00  5886.9  623.54  5957.9  625.37
#Mann=5,-1,0
  4422.6    0.05       0  4855.3     0.1       0  4860.1    0.05       0
  4992.6   0.035       0  5004.2    0.05       0
Bank Sta=4992.6,5004.2
Exp/Cntr=0.3,0.1

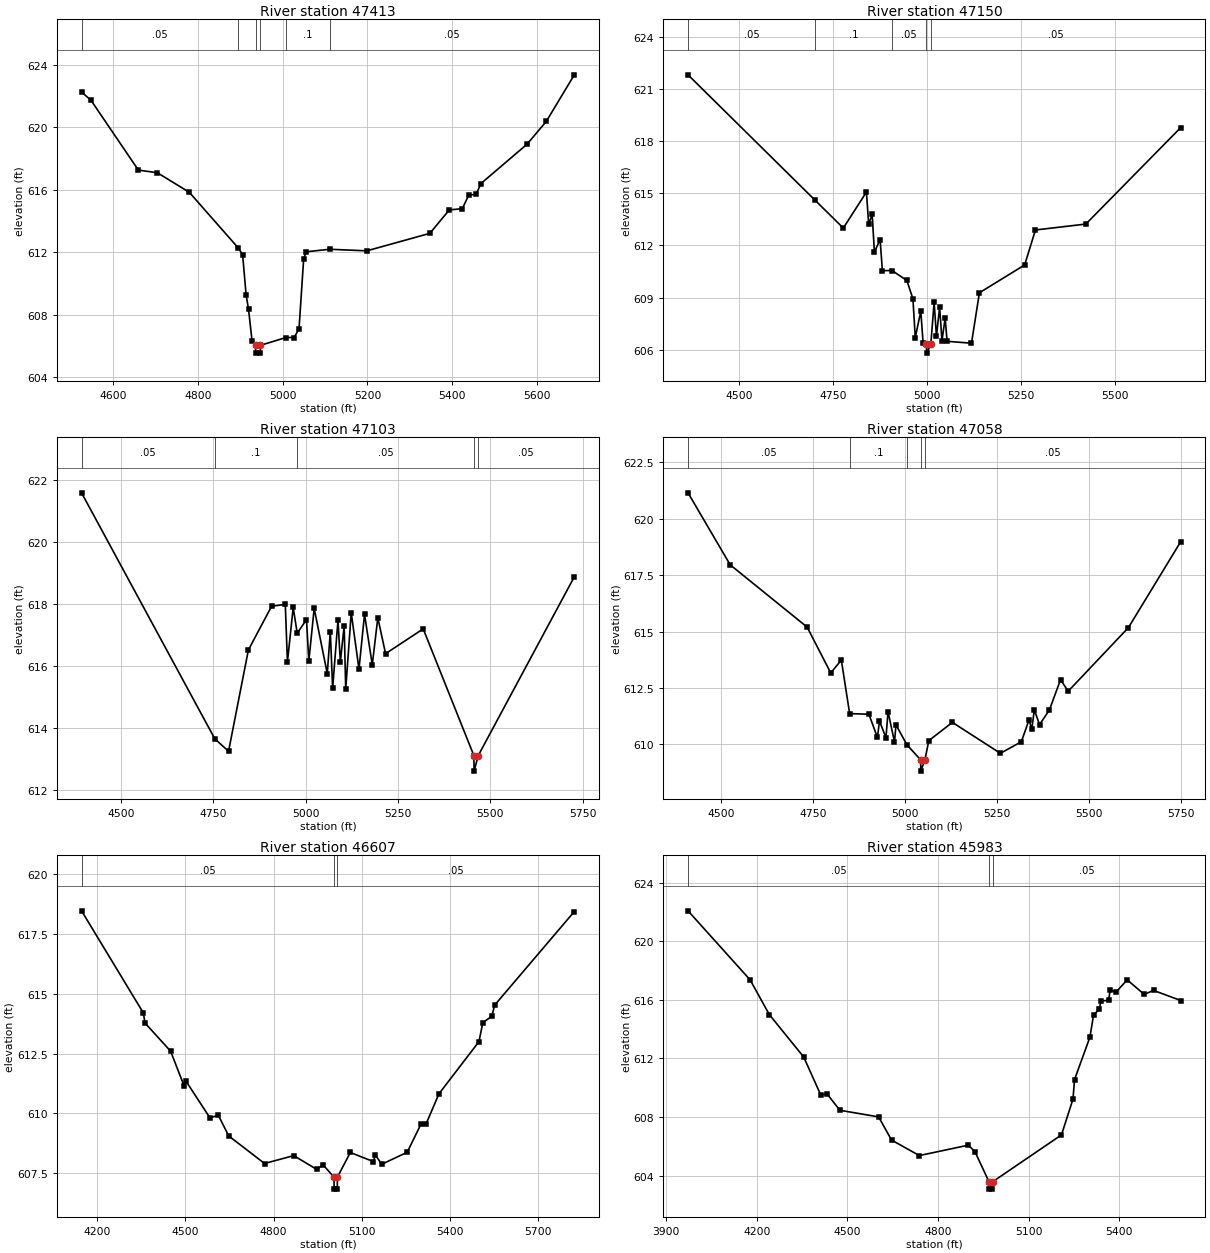
Type RM Length L Ch R = 1,47413,263,263,263
BEGIN DESCRIPTION:
Buckhorn Creek 66.0
END DESCRIPTION:
XS GIS Cut Line= 3
      1953124.99     13512174.98      1952925.00     13511775.00
      1952274.99     13511474.99
#Sta/Elev= 30
  4525.1  622.25  4547.4  621.72  4659.2  617.25  4704.0  617.08  4779.4  615.83
  4894.8  612.27  4905.2  611.84  4913.6  609.24  4919.2  608.35  4927.6  606.30
  4935.7  606.03  4936.2  605.53  4946.9  605.53  4947.4  606.03  5007.7  606.53
  5026.9  606.53  5038.4  607.09  5049.4  611.57  5055.4  612.02  5110.9  612.18
  5198.5  612.08  5347.2  613.20  5393.1  614.70  5423.9  614.78  5439.0  615.65
  5456.4  615.70  5467.9  616.39  5576.7  618.91  5622.1  620.37  5688.2  623.35
#Mann=6,-1,0
  4525.1    0.05       0  4894.8     0.1       0  4935.7    0.03       0
  4947.4     0.1       0  5007.7     0.1       0  5110.9    0.05       0
Bank Sta=4935.7,4947.4
Exp/Cntr=0.3,0.1

Type RM Length L Ch R = 1,47150,47,47,47
BEGIN DESCRIPTION:
Mapping XS 5bd37e82
END DESCRIPTION:
XS GIS Cut Line= 6
      1953288.05     13512126.54      1953152.65     13511715.13
      1953071.92     13511587.52      1953009.42     13511501.59
      1952910.46     13511400.02      1952539.03     13511096.12
#Sta/Elev= 30
  4363.1  621.81  4700.5  614.62  4776.6  613.00  4838.2  615.07  4844.1  613.23
  4853.5  613.78  4859.4  611.62  4874.6  612.34  4880.6  610.55  4906.1  610.56
  4945.8  609.99  4962.0  608.93  4968.2  606.70  4982.9  608.22  4989.1  606.39
  4997.9  606.31  4998.4  605.81  5009.6  606.31  5018.4  608.74  5024.6  606.78
  5033.1  608.46  5039.3  606.53  5047.8  607.82  5053.0  606.49  5117.9  606.38
  5139.0  609.28  5259.5  610.88  5288.2  612.89  5422.4  613.23  5675.2  618.78
#Mann=5,-1,0
  4363.1    0.05       0  4700.5     0.1       0  4906.1    0.05       0
  4997.9   0.033       0  5009.6    0.05       0
Bank Sta=4997.9,5009.6
Exp/Cntr=0.3,0.1

Type RM Length L Ch R = 1,47103,45,45,45
BEGIN DESCRIPTION:
Mapping XS d22ef5ba
END DESCRIPTION:
XS GIS Cut Line= 6
      1953308.90     13512090.13      1953165.67     13511686.48
      1953129.21     13511603.15      1953087.55     13511532.84
      1952876.61     13511230.75      1952584.97     13511012.02
#Sta/Elev= 30
  4393.5  621.60  4754.4  613.66  4791.5  613.26  4845.2  616.53  4908.0  617.94
  4945.1  618.00  4950.9  616.14  4966.5  617.90  4977.4  617.07  5002.5  617.51
  5008.8  616.17  5023.3  617.87  5058.7  615.77  5067.0  617.11  5073.3  615.30
  5087.8  617.50  5094.1  616.14  5104.5  617.31  5108.7  615.26  5123.6  617.73
  5144.6  615.91  5159.6  617.68  5180.6  616.05  5195.6  617.57  5216.6  616.41
  5318.5  617.21  5455.7  613.12  5456.2  612.62  5467.4  613.12  5727.6  618.89
#Mann=5,-1,0
  4393.5    0.05       0  4754.4     0.1       0  4977.4    0.05       0
  5455.7   0.033       0  5467.4    0.05       0
Bank Sta=5455.7,5467.4
Exp/Cntr=0.3,0.1

Type RM Length L Ch R = 1,47058,451,451,451
BEGIN DESCRIPTION:
Mapping XS e83d3064
END DESCRIPTION:
XS GIS Cut Line= 6
      1953329.74     13512064.09      1953209.94     13511689.09
      1953139.63     13511532.84      1953025.05     13511350.55
      1952892.24     13511199.50      1952612.16     13510979.07
#Sta/Elev= 30
  4410.7  621.15  4525.2  617.96  4734.2  615.20  4798.2  613.17  4827.0  613.74
  4849.5  611.37  4901.9  611.34  4925.0  610.31  4930.5  611.04  4948.2  610.30
  4953.7  611.46  4971.3  610.11  4975.3  610.87  5004.9  609.99  5042.2  609.32
  5042.7  608.82  5053.9  609.32  5064.4  610.17  5128.5  610.98  5258.8  609.61
  5315.7  610.12  5336.6  611.09  5344.2  610.67  5350.9  611.54  5365.1  610.88
  5391.9  611.53  5422.1  612.87  5442.9  612.36  5606.5  615.18  5748.6  618.99
#Mann=5,-1,0
  4410.7    0.05       0  4849.5     0.1       0  5004.9    0.05       0
  5042.2    0.07       0  5053.9    0.05       0
Bank Sta=5042.2,5053.9
Exp/Cntr=0.3,0.1

Type RM Length L Ch R = 1,46607,624,624,624
BEGIN DESCRIPTION:
Mapping XS 93782b54
END DESCRIPTION:
XS GIS Cut Line= 4
      1953654.39     13511946.94      1953682.17     13511568.43
      1953237.72     13511009.40      1952689.54     13510815.11
#Sta/Elev= 30
  4147.0  618.46  4357.4  614.19  4362.4  613.78  4449.8  612.60  4495.9  611.14
  4500.9  611.37  4583.3  609.82  4612.2  609.92  4647.4  609.06  4769.2  607.91
  4868.5  608.24  4947.0  607.66  4967.8  607.86  5005.2  607.34  5005.7  606.84
  5016.4  606.84  5016.9  607.34  5060.7  608.37  5139.2  607.99  5145.6  608.26
  5168.0  607.88  5254.2  608.38  5300.4  609.54  5317.9  609.55  5362.1  610.82
  5498.2  613.00  5511.2  613.79  5542.1  614.06  5551.3  614.52  5822.3  618.43
#Mann=3,-1,0
  4147.0    0.05       0  5005.2   0.035       0  5016.9    0.05       0
Bank Sta=5005.2,5016.9
Exp/Cntr=0.3,0.1

Type RM Length L Ch R = 1,45983,445,445,445
BEGIN DESCRIPTION:
Buckhorn Creek 63.0
END DESCRIPTION:
XS GIS Cut Line= 3
      1954474.98     13511624.98      1953825.00     13510875.00
      1953222.93     13510660.43
#Sta/Elev= 30
  3972.6  622.07  4178.2  617.36  4241.8  614.99  4355.8  612.09  4411.8  609.52
  4433.7  609.56  4475.4  608.46  4603.7  608.01  4646.4  606.43  4738.6  605.37
  4900.9  606.08  4922.8  605.63  4969.2  603.58  4969.7  603.08  4980.5  603.08
  4981.0  603.58  5209.2  606.78  5247.2  609.22  5252.5  610.56  5303.5  613.46
  5315.4  614.97  5334.3  615.35  5339.7  615.91  5365.2  615.97  5370.5  616.67
  5389.7  616.52  5426.8  617.36  5483.1  616.37  5513.9  616.64  5604.2  615.95
#Mann=3,-1,0
  3972.6    0.05       0  4969.2   0.035       0  4981.0    0.05       0
Bank Sta=4969.2,4981
Exp/Cntr=0.3,0.1

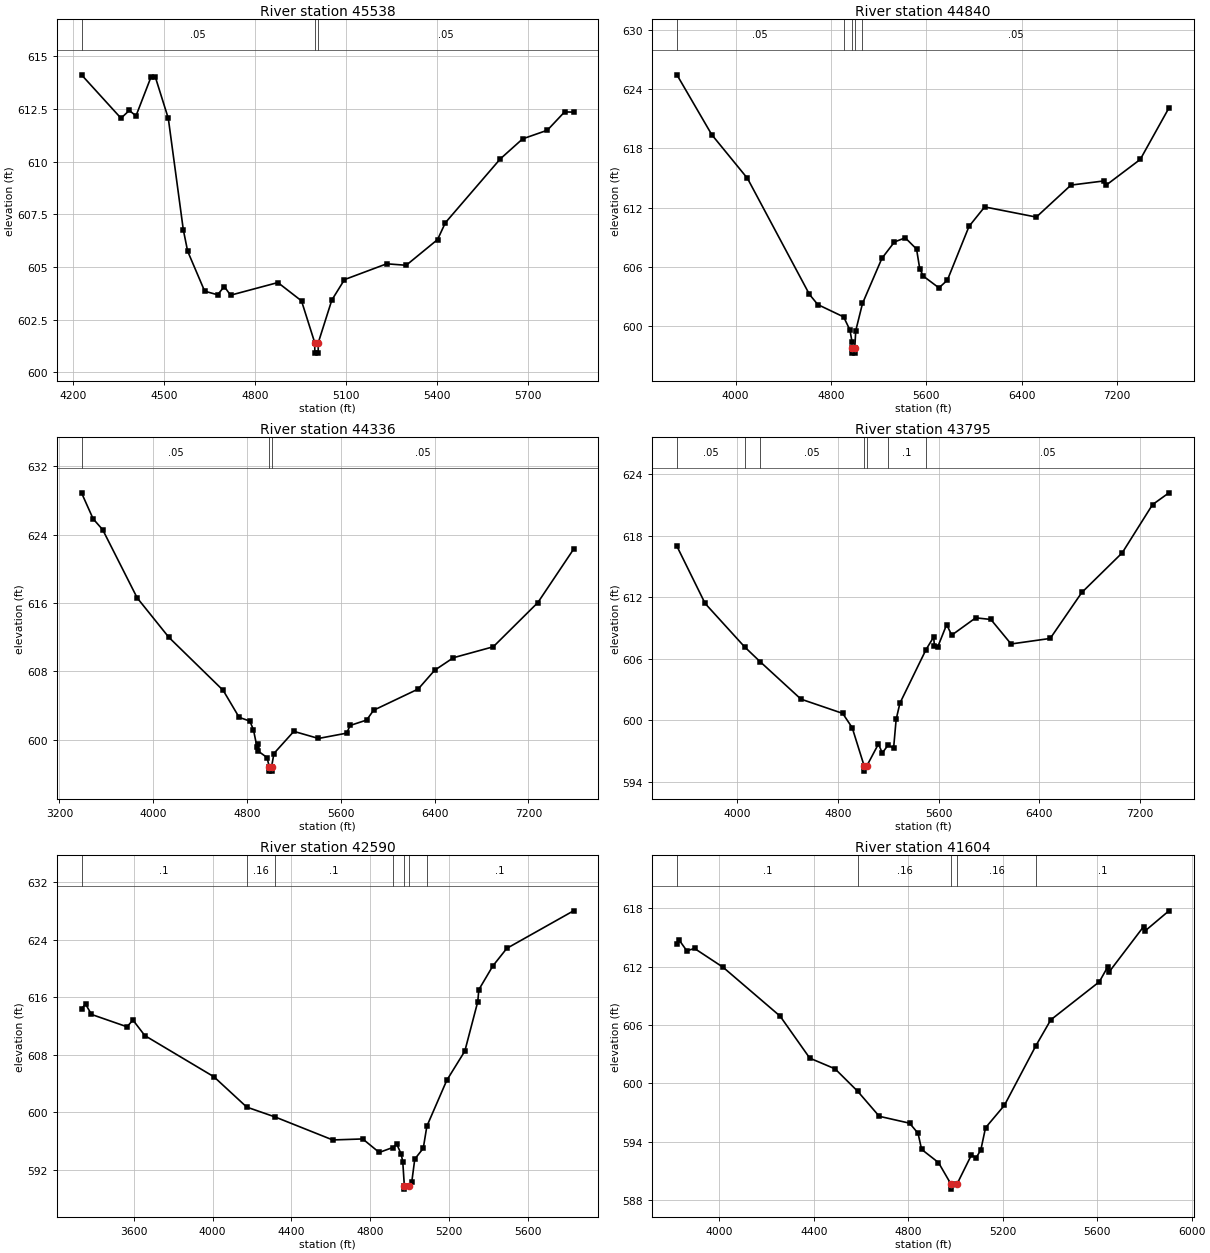
Type RM Length L Ch R = 1,45538,698,698,698
BEGIN DESCRIPTION:
Buckhorn Creek 62.0
END DESCRIPTION:
XS GIS Cut Line= 3
      1954588.42     13511134.41      1953998.14     13510439.96
      1953300.18     13510304.53
#Sta/Elev= 30
  4228.5  614.12  4358.7  612.06  4386.1  612.43  4408.1  612.17  4457.5  614.01
  4471.8  614.02  4514.7  612.05  4564.1  606.77  4578.4  605.75  4634.6  603.85
  4677.2  603.68  4699.2  604.07  4720.0  603.66  4876.0  604.26  4953.9  603.39
  4997.4  601.41  4997.9  600.91  5008.8  600.91  5009.3  601.41  5053.9  603.43
  5095.6  604.40  5234.8  605.15  5299.1  605.08  5402.5  606.30  5428.3  607.10
  5609.4  610.13  5683.0  611.08  5764.5  611.49  5821.4  612.36  5850.9  612.35
#Mann=3,-1,0
  4228.5    0.05       0  4997.4   0.035       0  5009.3    0.05       0
Bank Sta=4997.4,5009.3
Exp/Cntr=0.3,0.1

Type RM Length L Ch R = 1,44840,504,504,504
BEGIN DESCRIPTION:
Buckhorn Creek 61.0
END DESCRIPTION:
XS GIS Cut Line= 3
      1954628.56     13511757.22      1954635.51     13510285.01
      1955003.57     13507653.05
#Sta/Elev= 30
  3507.1  625.46  3799.3  619.40  4099.3  614.97  4619.3  603.22  4689.3  602.19
  4906.3  600.94  4959.3  599.61  4976.8  598.41  4979.1  597.77  4979.6  597.27
  4999.2  597.27  4999.7  597.77  5008.2  599.55  5064.6  602.30  5227.6  606.87
  5332.7  608.53  5423.6  608.95  5518.4  607.81  5544.8  605.84  5575.1  605.07
  5706.3  603.88  5777.0  604.66  5958.8  610.11  6089.9  612.08  6523.6  611.05
  6814.4  614.29  7089.7  614.71  7110.3  614.29  7396.1  616.89  7636.9  622.11
#Mann=5,-1,0
  3507.1    0.05       0  4906.3     0.1       0  4979.1    0.07       0
  4999.7     0.1       0  5064.6    0.05       0
Bank Sta=4979.1,4999.7
Exp/Cntr=0.3,0.1

Type RM Length L Ch R = 1,44336,541,541,541
BEGIN DESCRIPTION:
Buckhorn Creek 60.0
END DESCRIPTION:
XS GIS Cut Line= 3
      1954725.01     13511824.95      1955125.00     13510275.00
      1955211.90     13507680.89
#Sta/Elev= 30
  3388.8  628.89  3487.8  625.85  3569.2  624.58  3863.8  616.60  4133.3  612.00
  4597.1  605.79  4733.0  602.64  4824.3  602.20  4855.3  601.18  4885.3  599.17
  4890.5  599.52  4896.6  598.68  4971.8  597.93  4989.2  596.85  4989.7  596.35
  5009.4  596.35  5009.9  596.85  5029.6  598.41  5199.6  601.00  5409.8  600.17
  5649.9  600.79  5679.9  601.69  5820.0  602.32  5880.0  603.47  6260.2  605.95
  6400.3  608.14  6560.4  609.61  6900.6  610.89  7280.8  616.06  7585.1  622.29
#Mann=3,-1,0
  3388.8    0.05       0  4989.2   0.035       0  5009.9    0.05       0
Bank Sta=4989.2,5009.9
Exp/Cntr=0.3,0.1

Type RM Length L Ch R = 1,43795,1205,1205,1205
BEGIN DESCRIPTION:
Buckhorn Creek 59.0
END DESCRIPTION:
XS GIS Cut Line= 3
      1955024.39     13511500.29      1955625.00     13510125.00
      1955425.00     13507725.04
#Sta/Elev= 30
  3520.6  616.99  3744.6  611.41  4058.0  607.18  4181.0  605.74  4506.0  602.08
  4837.6  600.69  4913.3  599.29  5008.2  595.56  5008.7  595.06  5028.9  595.56
  5121.7  597.71  5151.8  596.83  5198.1  597.59  5242.1  597.31  5262.2  600.10
  5292.3  601.69  5500.0  606.92  5560.7  608.15  5565.7  607.30  5593.3  607.19
  5663.5  609.35  5703.7  608.32  5894.3  610.01  6014.8  609.85  6175.3  607.46
  6486.4  608.00  6737.2  612.48  7058.4  616.35  7299.2  621.05  7429.6  622.20
#Mann=7,-1,0
  3520.6    0.05       0  4058.0     0.1       0  4181.0    0.05       0
  5008.2   0.035       0  5028.9    0.05       0  5198.1     0.1       0
  5500.0    0.05       0
Bank Sta=5008.2,5028.9
Exp/Cntr=0.3,0.1

Type RM Length L Ch R = 1,42590,986,986,986
BEGIN DESCRIPTION:
Buckhorn Creek 58.0
END DESCRIPTION:
XS GIS Cut Line= 3
      1956427.18     13511735.49      1956513.98     13510598.38
      1956757.03     13509261.61
#Sta/Elev= 30
  3334.4  614.40  3354.9  615.05  3385.0  613.61  3565.6  611.89  3595.6  612.83
  3655.8  610.67  4006.8  604.94  4173.6  600.72  4318.4  599.34  4610.4  596.15
  4762.8  596.29  4846.6  594.41  4915.2  595.10  4935.6  595.57  4958.4  594.16
  4966.1  593.10  4974.0  589.81  4974.5  589.31  4998.8  589.81  5011.7  590.27
  5027.1  593.49  5070.2  594.99  5088.5  598.06  5189.7  604.45  5281.2  608.50
  5347.1  615.39  5352.4  617.05  5423.5  620.35  5494.6  622.80  5833.5  628.02
#Mann=7,-1,0
  3334.4     0.1       0  4173.6    0.16       0  4318.4     0.1       0
  4915.2    0.16       0  4974.0    0.07       0  4998.8    0.16       0
  5088.5     0.1       0
Bank Sta=4974,4998.8
Exp/Cntr=0.3,0.1

Type RM Length L Ch R = 1,41604,137,137,137
BEGIN DESCRIPTION:
Buckhorn Creek 57.0
END DESCRIPTION:
XS GIS Cut Line= 5
      1956444.67     13511732.72      1956796.24     13510973.16
      1957104.40     13510760.48      1957108.74     13510387.22
      1957173.84     13509892.48
#Sta/Elev= 30
  3820.1  614.35  3827.9  614.80  3861.9  613.64  3894.7  613.88  4015.9  611.94
  4257.1  606.92  4382.7  602.60  4489.8  601.50  4585.7  599.19  4677.0  596.62
  4805.5  595.91  4841.3  594.87  4856.2  593.22  4927.8  591.86  4981.0  589.63
  4981.5  589.13  5005.9  589.63  5067.0  592.63  5087.0  592.35  5107.0  593.15
  5127.0  595.44  5207.0  597.75  5340.3  603.88  5403.4  606.54  5608.8  610.45
  5644.2  611.97  5649.3  611.43  5796.5  616.13  5801.6  615.66  5903.8  617.75
#Mann=5,-1,0
  3820.1     0.1       0  4585.7    0.16       0  4981.0    0.07       0
  5005.9    0.16       0  5340.3     0.1       0
Bank Sta=4981,5005.9
Exp/Cntr=0.3,0.1

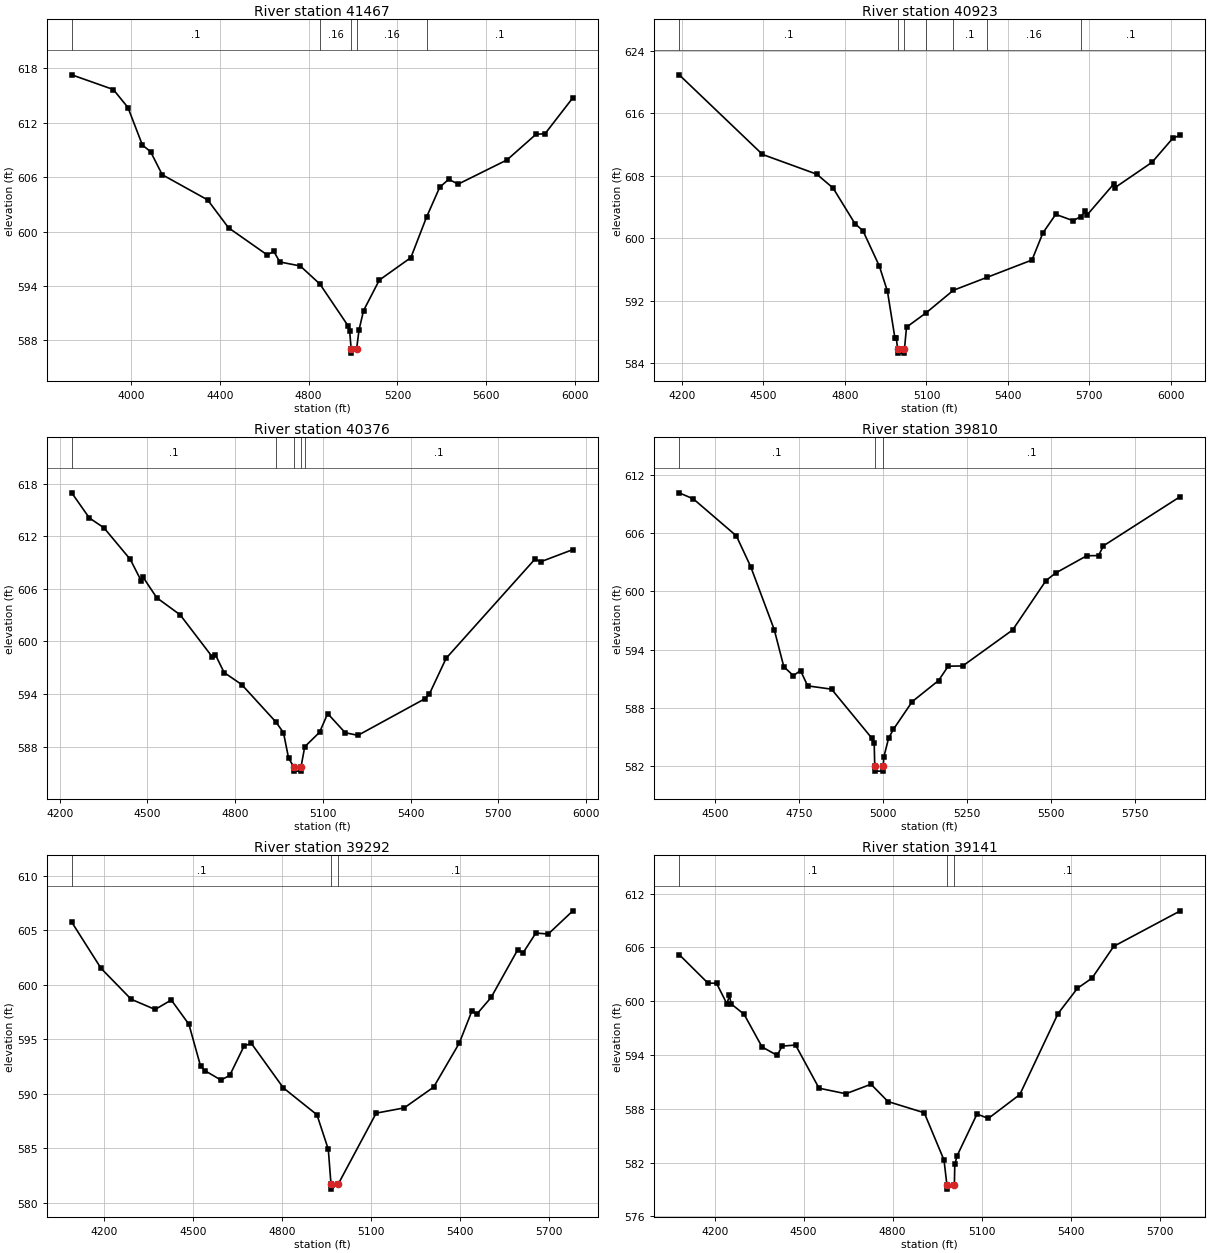
Type RM Length L Ch R = 1,41467,544,544,544
BEGIN DESCRIPTION:
Buckhorn Creek 56.0
END DESCRIPTION:
XS GIS Cut Line= 4
      1956666.04     13511971.38      1956878.71     13511086.01
      1957175.00     13510875.00      1957312.74     13509901.10
#Sta/Elev= 30
  3732.7  617.30  3920.1  615.68  3986.1  613.69  4051.1  609.55  4088.0  608.82
  4140.4  606.28  4345.0  603.50  4439.2  600.42  4613.4  597.43  4643.3  597.82
  4670.1  596.65  4762.3  596.21  4850.9  594.21  4978.7  589.57  4984.9  589.04
  4991.5  587.09  4992.0  586.59  5016.4  587.09  5027.2  589.16  5047.6  591.29
  5118.6  594.65  5260.7  597.13  5331.3  601.60  5390.8  604.90  5431.2  605.77
  5473.9  605.24  5693.8  607.91  5824.1  610.73  5865.5  610.81  5990.6  614.77
#Mann=5,-1,0
  3732.7     0.1       0  4850.9    0.16       0  4991.5    0.07       0
  5016.4    0.16       0  5331.3     0.1       0
Bank Sta=4991.5,5016.4
Exp/Cntr=0.3,0.1

Type RM Length L Ch R = 1,40923,547,547,547
BEGIN DESCRIPTION:
Buckhorn Creek 55.0
END DESCRIPTION:
XS GIS Cut Line= 3
      1957672.98     13511871.56      1957675.00     13511075.00
      1957577.49     13510031.31
#Sta/Elev= 30
  4189.9  620.93  4496.5  610.74  4696.5  608.21  4756.5  606.43  4836.5  601.90
  4866.5  600.96  4926.5  596.46  4956.5  593.22  4984.0  587.24  4989.0  587.24
  4994.0  585.81  4994.5  585.31  5018.6  585.31  5019.1  585.81  5026.6  588.63
  5099.6  590.49  5198.9  593.35  5323.1  595.01  5488.6  597.23  5528.8  600.70
  5575.9  603.07  5639.3  602.27  5667.6  602.76  5684.9  603.45  5689.9  602.93
  5788.8  606.93  5793.9  606.49  5930.6  609.74  6006.8  612.81  6034.7  613.21
#Mann=7,-1,0
  4189.9     0.1       0  4994.0    0.07       0  5019.1     0.1       0
  5099.6    0.16       0  5198.9     0.1       0  5323.1    0.16       0
  5667.6     0.1       0
Bank Sta=4994,5019.1
Exp/Cntr=0.3,0.1

Type RM Length L Ch R = 1,40376,566,566,566
BEGIN DESCRIPTION:
Buckhorn Creek 54.0
END DESCRIPTION:
XS GIS Cut Line= 3
      1958225.00     13511674.99      1958175.00     13510875.00
      1957738.10     13510074.75
#Sta/Elev= 30
  4241.2  616.94  4301.3  614.08  4351.4  612.95  4441.6  609.34  4479.2  606.87
  4484.2  607.37  4531.8  604.98  4611.9  603.03  4722.1  598.22  4732.1  598.50
  4762.2  596.45  4822.3  595.08  4938.8  590.83  4965.1  589.60  4982.6  586.69
  5000.1  585.71  5000.6  585.21  5024.7  585.21  5025.2  585.71  5037.8  587.99
  5088.3  589.63  5116.3  591.77  5176.1  589.59  5219.7  589.29  5448.5  593.46
  5464.3  594.03  5521.3  598.08  5824.3  609.36  5846.1  609.10  5954.5  610.47
#Mann=5,-1,0
  4241.2     0.1       0  4938.8    0.12       0  5000.1    0.07       0
  5025.2    0.12       0  5037.8     0.1       0
Bank Sta=5000.1,5025.2
Exp/Cntr=0.3,0.1

Type RM Length L Ch R = 1,39810,518,518,518
BEGIN DESCRIPTION:
Buckhorn Creek 53.0
END DESCRIPTION:
XS GIS Cut Line= 3
      1958875.03     13510975.03      1958475.00     13510525.00
      1957781.52     13509966.24
#Sta/Elev= 30
  4392.5  610.16  4434.8  609.53  4562.7  605.73  4605.4  602.56  4675.6  596.07
  4704.0  592.26  4732.5  591.33  4753.8  591.86  4775.1  590.28  4846.2  589.94
  4966.6  584.88  4973.3  584.39  4974.9  582.00  4975.4  581.50  4999.7  581.50
  5000.2  582.00  5001.8  582.93  5016.2  584.89  5030.6  585.81  5086.6  588.66
  5165.0  590.83  5193.8  592.31  5236.9  592.33  5385.7  596.04  5484.9  601.12
  5513.7  601.90  5606.4  603.68  5641.6  603.70  5656.0  604.70  5885.2  609.78
#Mann=3,-1,0
  4392.5     0.1       0  4974.9    0.07       0  5000.2     0.1       0
Bank Sta=4974.9,5000.2
Exp/Cntr=0.3,0.1

Type RM Length L Ch R = 1,39292,151,151,151
BEGIN DESCRIPTION:
Buckhorn Creek 52.0
END DESCRIPTION:
XS GIS Cut Line= 3
      1959617.39     13510508.73      1959343.99     13510348.16
      1958069.01     13509840.77
#Sta/Elev= 30
  4089.8  605.75  4188.6  601.51  4290.1  598.67  4370.9  597.73  4425.4  598.60
  4484.8  596.37  4524.2  592.52  4538.7  592.11  4592.7  591.25  4622.3  591.67
  4670.9  594.38  4695.2  594.62  4803.1  590.53  4916.4  588.06  4954.7  584.88
  4963.6  581.73  4964.1  581.23  4988.9  581.73  5116.1  588.21  5210.4  588.69
  5309.8  590.60  5396.0  594.63  5439.0  597.61  5455.9  597.32  5503.6  598.84
  5593.5  603.23  5611.2  602.93  5654.3  604.75  5696.0  604.66  5779.1  606.79
#Mann=3,-1,0
  4089.8     0.1       0  4963.6    0.07       0  4988.9     0.1       0
Bank Sta=4963.6,4988.9
Exp/Cntr=0.3,0.1

Type RM Length L Ch R = 1,39141,354,354,354
BEGIN DESCRIPTION:
Mapping XS d27d87aa
END DESCRIPTION:
XS GIS Cut Line= 4
      1959617.40     13510469.66      1959478.53     13510296.08
      1958588.78     13509866.39      1958129.39     13509732.04
#Sta/Elev= 30
  4080.6  605.19  4177.6  602.01  4206.4  602.00  4241.6  599.69  4249.6  600.64
  4256.0  599.69  4299.2  598.54  4359.8  594.90  4410.6  593.96  4427.6  594.99
  4472.8  595.11  4551.8  590.30  4642.2  589.68  4727.0  590.74  4784.3  588.81
  4906.5  587.56  4973.1  582.28  4982.7  579.55  4983.2  579.05  5008.0  579.55
  5009.4  581.82  5017.5  582.79  5084.2  587.42  5122.4  586.93  5228.5  589.59
  5357.4  598.62  5422.9  601.44  5472.0  602.57  5545.0  606.11  5769.6  610.07
#Mann=3,-1,0
  4080.6     0.1       0  4982.7    0.07       0  5008.0     0.1       0
Bank Sta=4982.7,5008
Exp/Cntr=0.3,0.1

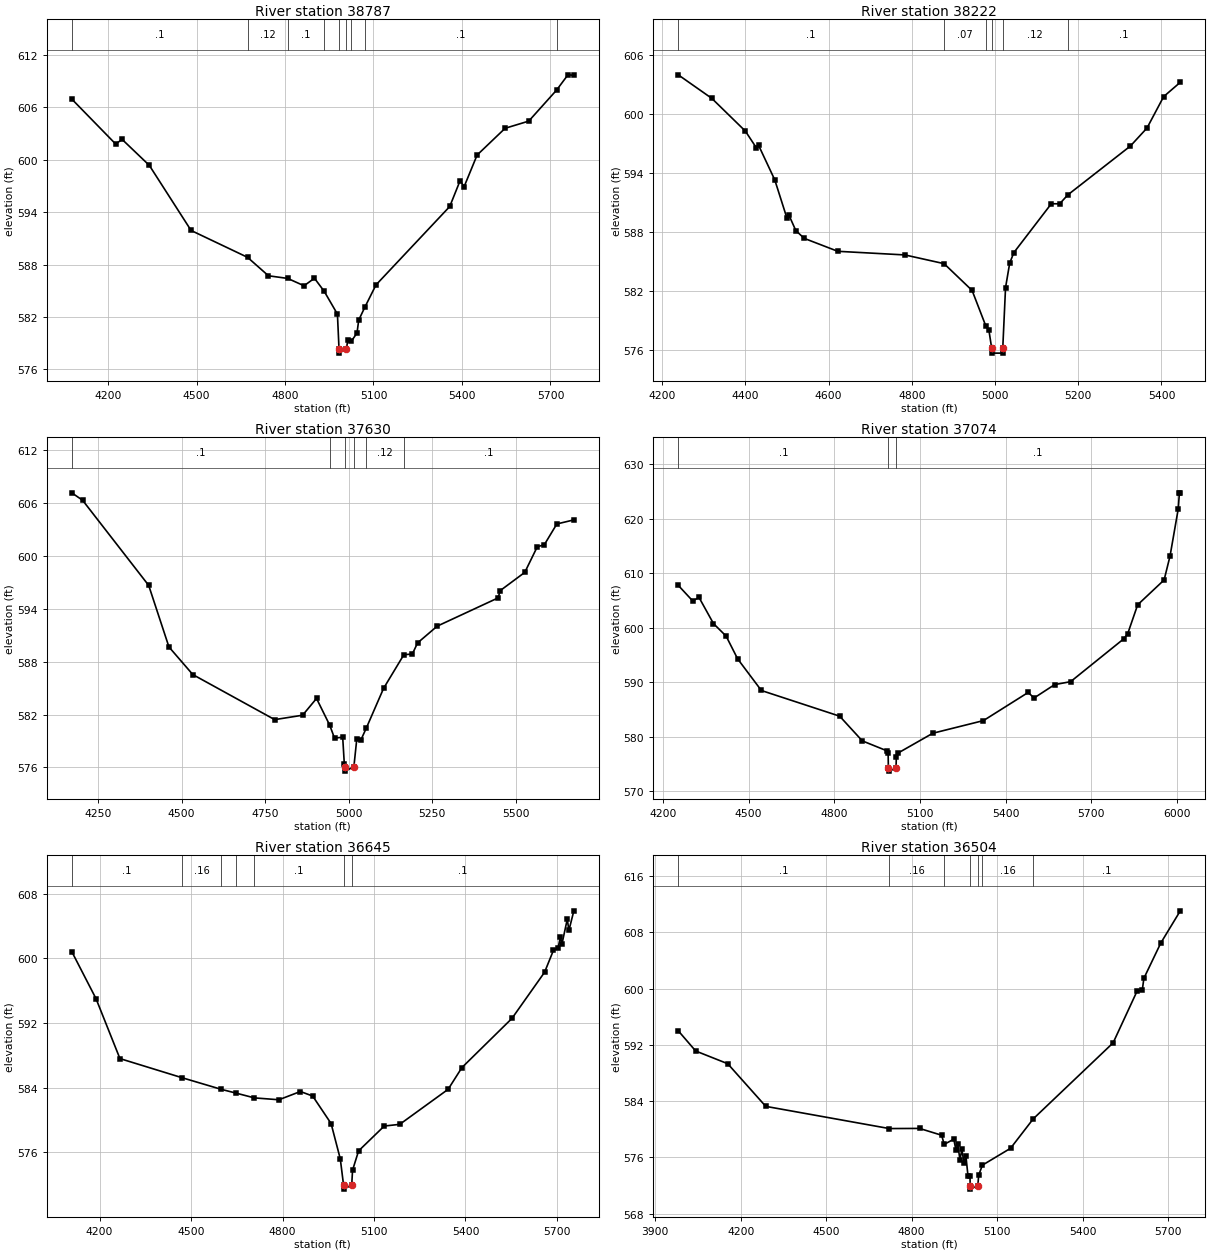
Type RM Length L Ch R = 1,38787,565,565,565
BEGIN DESCRIPTION:
Buckhorn Creek 51.0
END DESCRIPTION:
XS GIS Cut Line= 3
      1959675.02     13510475.02      1959075.00     13509775.00
      1958402.12     13509380.26
#Sta/Elev= 30
  4077.1  606.91  4225.9  601.77  4247.8  602.30  4340.0  599.33  4481.6  591.89
  4673.0  588.82  4743.9  586.71  4809.0  586.41  4864.6  585.57  4899.8  586.43
  4932.8  584.94  4977.7  582.33  4983.1  578.37  4983.6  577.87  5008.4  578.37
  5012.7  579.38  5025.3  579.25  5044.1  580.17  5049.9  581.65  5070.4  583.10
  5108.5  585.67  5358.5  594.63  5393.3  597.56  5407.4  596.91  5451.2  600.51
  5546.2  603.57  5626.3  604.39  5720.8  607.94  5759.2  609.68  5779.2  609.63
#Mann=9,-1,0
  4077.1     0.1       0  4673.0    0.12       0  4809.0     0.1       0
  4932.8    0.07       0  4983.1    0.07       0  5008.4    0.07       0
  5025.3    0.12       0  5070.4     0.1       0  5720.8    0.08       0
Bank Sta=4983.1,5008.4
Exp/Cntr=0.3,0.1

Type RM Length L Ch R = 1,38222,592,592,592
BEGIN DESCRIPTION:
Buckhorn Creek 50.0
END DESCRIPTION:
XS GIS Cut Line= 3
      1959675.00     13510375.00      1959575.00     13509625.00
      1959575.00     13509175.04
#Sta/Elev= 30
  4238.7  604.02  4319.4  601.62  4400.1  598.28  4426.6  596.57  4431.6  596.85
  4470.7  593.31  4499.7  589.44  4504.8  589.71  4521.2  588.15  4541.4  587.35
  4622.1  586.03  4783.5  585.66  4877.6  584.77  4944.9  582.04  4977.5  578.46
  4985.2  578.01  4992.0  576.15  4992.5  575.65  5018.1  575.65  5018.6  576.15
  5025.3  582.33  5035.3  584.83  5045.3  585.90  5135.3  590.88  5155.3  590.87
  5174.9  591.78  5325.3  596.76  5365.3  598.60  5405.3  601.80  5445.3  603.26
#Mann=6,-1,0
  4238.7     0.1       0  4877.6    0.07       0  4977.5    0.12       0
  4992.0    0.07       0  5018.6    0.12       0  5174.9     0.1       0
Bank Sta=4992,5018.6
Exp/Cntr=0.3,0.1

Type RM Length L Ch R = 1,37630,556,556,556
BEGIN DESCRIPTION:
Buckhorn Creek 49.0
END DESCRIPTION:
XS GIS Cut Line= 3
      1959825.00     13510475.01      1960125.00     13509725.00
      1960475.00     13509125.01
#Sta/Elev= 30
  4171.6  607.14  4203.9  606.30  4401.8  596.64  4462.4  589.66  4533.8  586.53
  4778.8  581.42  4862.3  581.92  4904.0  583.82  4943.6  580.78  4957.8  579.32
  4982.3  579.43  4987.2  576.36  4989.2  576.08  4989.7  575.58  5015.8  576.08
  5024.5  579.23  5037.3  579.16  5053.2  580.48  5104.7  584.97  5165.3  588.78
  5190.7  588.86  5206.4  590.12  5265.1  592.02  5447.0  595.22  5454.0  596.06
  5527.2  598.12  5564.4  601.01  5585.9  601.27  5623.1  603.61  5674.0  604.07
#Mann=6,-1,0
  4171.6     0.1       0  4943.6    0.12       0  4989.2    0.07       0
  5015.8    0.12       0  5053.2    0.12       0  5165.3     0.1       0
Bank Sta=4989.2,5015.8
Exp/Cntr=0.3,0.1

Type RM Length L Ch R = 1,37074,429,429,429
BEGIN DESCRIPTION:
Buckhorn Creek 48.0
END DESCRIPTION:
XS GIS Cut Line= 3
      1960374.99     13510725.02      1960575.00     13510025.00
      1961224.99     13509225.01
#Sta/Elev= 30
  4253.3  607.74  4304.0  604.88  4326.1  605.52  4376.8  600.72  4421.0  598.43
  4461.3  594.26  4544.5  588.45  4818.8  583.74  4898.1  579.21  4984.6  577.38
  4988.5  577.03  4989.5  574.16  4990.0  573.66  5016.2  574.16  5017.3  576.21
  5023.7  576.99  5145.1  580.61  5322.5  582.93  5479.1  588.09  5499.9  587.08
  5571.8  589.53  5627.8  590.07  5813.1  597.89  5827.5  598.82  5862.7  604.17
  5955.4  608.73  5976.2  613.14  6004.9  621.78  6008.9  624.71  6012.1  624.71
#Mann=3,-1,0
  4253.3     0.1       0  4989.5    0.07       0  5016.2     0.1       0
Bank Sta=4989.5,5016.2
Exp/Cntr=0.3,0.1

Type RM Length L Ch R = 1,36645,141,141,141
BEGIN DESCRIPTION:
Mapping XS 82b8e484
END DESCRIPTION:
XS GIS Cut Line= 4
      1960617.26     13510719.29      1961023.04     13510391.63
      1960975.30     13509970.62      1961278.38     13509338.48
#Sta/Elev= 30
  4109.0  600.84  4188.5  595.02  4266.9  587.61  4469.3  585.26  4599.0  583.81
  4646.8  583.35  4707.9  582.75  4788.2  582.52  4858.6  583.54  4898.9  582.98
  4959.3  579.58  4989.5  575.20  5000.2  571.97  5000.7  571.47  5026.9  571.97
  5029.7  573.81  5049.5  576.20  5133.6  579.27  5184.4  579.48  5343.0  583.81
  5388.3  586.50  5552.4  592.58  5659.4  598.29  5688.4  601.00  5703.7  601.32
  5711.0  602.61  5716.6  601.83  5733.7  604.83  5739.2  603.47  5755.3  605.88
#Mann=7,-1,0
  4109.0     0.1       0  4469.3    0.16       0  4599.0     0.1       0
  4646.8    0.16       0  4707.9     0.1       0  5000.2    0.07       0
  5026.9     0.1       0
Bank Sta=5000.2,5026.9
Exp/Cntr=0.3,0.1

Type RM Length L Ch R = 1,36504,74,74,74
BEGIN DESCRIPTION:
Mapping XS de7f4827
END DESCRIPTION:
XS GIS Cut Line= 4
      1961480.95     13510864.70      1961561.24     13510506.64
      1961096.83     13509996.66      1961357.24     13509341.30
#Sta/Elev= 30
  3981.0  594.01  4042.2  591.13  4154.6  589.32  4288.1  583.25  4721.8  580.09
  4827.7  580.11  4905.4  579.14  4914.3  577.84  4948.0  578.58  4955.4  577.06
  4962.1  577.83  4969.6  575.63  4976.3  577.12  4983.8  575.17  4990.5  576.20
  4998.0  573.27  5004.7  573.39  5005.6  571.97  5006.1  571.47  5032.3  571.97
  5035.4  573.46  5048.3  574.88  5147.1  577.28  5227.0  581.48  5507.1  592.29
  5590.8  599.62  5609.7  599.88  5615.1  601.48  5674.4  606.50  5742.9  611.08
#Mann=7,-1,0
  3981.0     0.1       0  4721.8    0.16       0  4914.3    0.12       0
  5005.6    0.07       0  5032.3    0.12       0  5048.3    0.16       0
  5227.0     0.1       0
Bank Sta=5005.6,5032.3
Exp/Cntr=0.3,0.1