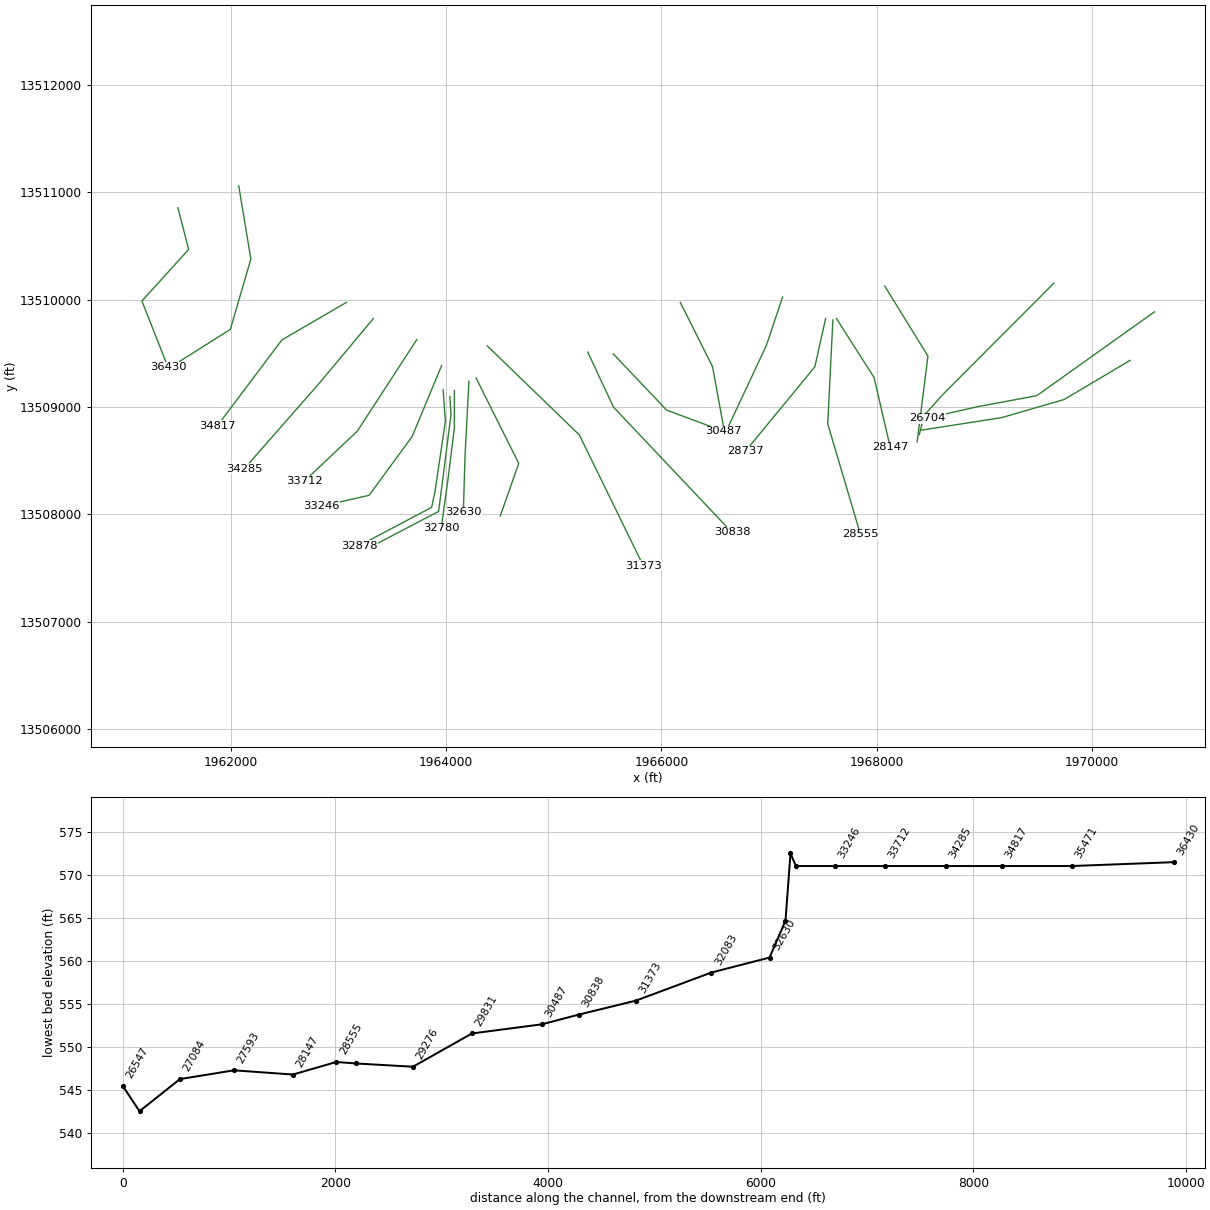
HEC-RAS study Buckhorn Creek.prj: Buckhorn Creek Base Level Engineering

--- Buckhorn Creek.g01 (geometry) --- (continued)

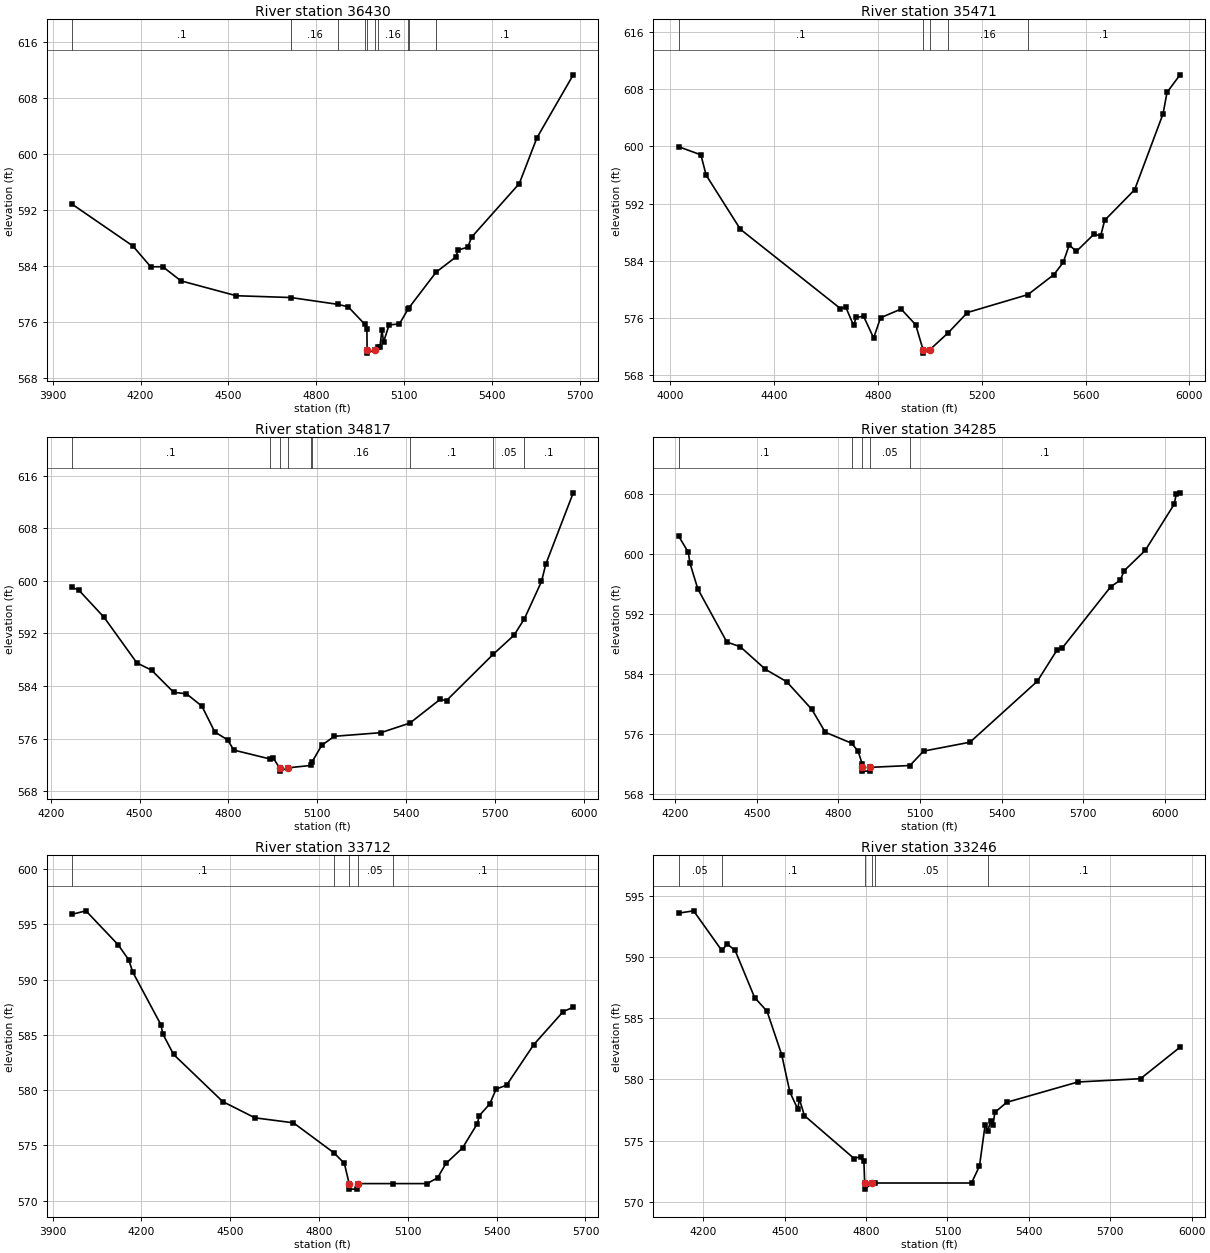
Type RM Length L Ch R = 1,36430,959,959,959
BEGIN DESCRIPTION:
Mapping XS dc91f68a
END DESCRIPTION:
XS GIS Cut Line= 4
      1961509.15     13510856.04      1961608.98     13510467.58
      1961174.95     13509987.98      1961417.92     13509369.73
#Sta/Elev= 30
  3965.2  592.85  4173.7  586.84  4234.7  583.86  4276.0  583.86  4338.0  581.84
  4526.8  579.71  4713.3  579.45  4874.6  578.47  4909.2  578.11  4964.8  575.67
  4972.9  574.95  4973.6  571.99  4974.1  571.49  5000.5  571.99  5011.5  572.32
  5017.4  572.35  5024.3  574.87  5029.7  573.06  5048.6  575.53  5083.9  575.67
  5112.8  577.74  5116.5  577.98  5209.4  583.09  5276.3  585.24  5284.9  586.26
  5317.2  586.66  5330.5  588.10  5493.1  595.76  5553.5  602.33  5677.4  611.34
#Mann=10,-1,0
  3965.2     0.1       0  4713.3    0.16       0  4874.6     0.1       0
  4964.8    0.12       0  4973.6    0.07       0  5000.5    0.12       0
  5011.5    0.16       0  5112.8    0.12       0  5116.5    0.16       0
  5209.4     0.1       0
Bank Sta=4973.6,5000.5
Exp/Cntr=0.3,0.1

Type RM Length L Ch R = 1,35471,654,654,654
BEGIN DESCRIPTION:
Buckhorn Creek 45.0
END DESCRIPTION:
XS GIS Cut Line= 4
      1962074.03     13511059.93      1962186.87     13510378.54
      1961995.90     13509723.16      1961524.96     13509424.98
#Sta/Elev= 30
  4032.9  599.97  4119.0  598.83  4139.3  595.98  4271.0  588.40  4656.2  577.29
  4676.5  577.52  4706.9  574.92  4717.0  576.06  4745.5  576.19  4784.2  573.16
  4810.6  575.99  4889.9  577.22  4946.0  575.01  4974.2  571.54  4974.7  571.04
  5001.1  571.54  5070.9  573.88  5145.2  576.73  5378.1  579.24  5478.3  582.05
  5513.8  583.75  5537.3  586.20  5564.4  585.29  5631.3  587.67  5658.4  587.52
  5673.7  589.66  5789.0  593.94  5898.3  604.58  5913.6  607.58  5963.6  610.04
#Mann=5,-1,0
  4032.9     0.1       0  4974.2    0.07       0  5001.1     0.1       0
  5070.9    0.16       0  5378.1     0.1       0
Bank Sta=4974.2,5001.1
Exp/Cntr=0.3,0.1

Type RM Length L Ch R = 1,34817,532,532,532
BEGIN DESCRIPTION:
Buckhorn Creek 44.0
END DESCRIPTION:
XS GIS Cut Line= 3
      1963075.04     13509975.02      1962475.00     13509625.00
      1961874.98     13508824.98
#Sta/Elev= 30
  4270.6  598.98  4293.8  598.61  4380.2  594.42  4490.6  587.51  4540.6  586.39
  4615.1  583.03  4658.1  582.81  4710.6  580.92  4754.0  576.99  4797.0  575.81
  4818.5  574.24  4942.2  572.87  4951.6  573.02  4973.0  571.54  4973.5  571.04
  5001.2  571.54  5077.5  571.90  5082.5  572.42  5115.3  574.97  5158.0  576.34
  5315.3  576.89  5413.3  578.35  5515.3  581.95  5537.1  581.78  5695.6  588.85
  5765.3  591.72  5800.5  594.24  5858.0  599.89  5872.6  602.53  5965.3  613.38
#Mann=9,-1,0
  4270.6     0.1       0  4942.2    0.05       0  4973.0   0.033       0
  5001.2    0.05       0  5077.5     0.1       0  5082.5    0.16       0
  5413.3     0.1       0  5695.6    0.05       0  5800.5     0.1       0
Bank Sta=4973,5001.2
Exp/Cntr=0.3,0.1

Type RM Length L Ch R = 1,34285,573,573,573
BEGIN DESCRIPTION:
Buckhorn Creek 43.0
END DESCRIPTION:
XS GIS Cut Line= 3
      1963325.03     13509825.03      1962825.00     13509225.00
      1962124.99     13508424.99
#Sta/Elev= 30
  4212.3  602.41  4248.1  600.24  4254.7  598.74  4283.3  595.34  4390.0  588.26
  4439.5  587.63  4531.9  584.62  4610.0  582.97  4702.4  579.28  4751.9  576.23
  4848.9  574.76  4873.0  573.68  4887.3  572.04  4887.4  571.54  4887.9  571.04
  4915.2  571.04  4915.7  571.54  5063.3  571.79  5113.4  573.71  5284.3  574.90
  5532.0  583.04  5603.2  587.14  5624.1  587.49  5801.5  595.63  5836.7  596.51
  5850.9  597.76  5928.7  600.49  6035.0  606.64  6042.6  608.00  6056.4  608.16
#Mann=5,-1,0
  4212.3     0.1       0  4848.9    0.05       0  4887.4   0.033       0
  4915.7    0.05       0  5063.3     0.1       0
Bank Sta=4887.4,4915.7
Exp/Cntr=0.3,0.1

Type RM Length L Ch R = 1,33712,466,466,466
BEGIN DESCRIPTION:
Buckhorn Creek 42.0
END DESCRIPTION:
XS GIS Cut Line= 3
      1963727.66     13509627.67      1963175.00     13508775.00
      1962682.58     13508309.10
#Sta/Elev= 30
  3964.8  595.90  4012.7  596.22  4121.5  593.15  4157.7  591.77  4170.6  590.69
  4265.9  585.92  4272.5  585.08  4308.7  583.23  4474.9  578.96  4583.7  577.49
  4713.6  577.04  4850.7  574.32  4885.7  573.37  4901.8  571.54  4902.3  571.04
  4929.6  571.04  4930.1  571.54  5050.0  571.54  5164.8  571.54  5200.4  572.06
  5228.7  573.36  5284.9  574.77  5334.7  576.96  5341.6  577.69  5377.1  578.76
  5398.2  580.09  5433.8  580.45  5525.6  584.12  5624.7  587.10  5658.8  587.50
#Mann=5,-1,0
  3964.8     0.1       0  4850.7    0.05       0  4901.8   0.033       0
  4930.1    0.05       0  5050.0     0.1       0
Bank Sta=4901.8,4930.1
Exp/Cntr=0.3,0.1

Type RM Length L Ch R = 1,33246,368,368,368
BEGIN DESCRIPTION:
Buckhorn Creek 41.0
END DESCRIPTION:
XS GIS Cut Line= 4
      1963958.58     13509386.38      1963684.26     13508724.89
      1963284.96     13508178.02      1962840.47     13508077.32
#Sta/Elev= 30
  4108.3  593.58  4163.9  593.77  4267.9  590.53  4287.9  591.06  4317.2  590.53
  4388.8  586.69  4434.6  585.57  4488.7  582.02  4519.0  578.96  4548.3  577.56
  4553.7  578.43  4572.2  577.05  4755.6  573.54  4779.5  573.70  4791.8  573.34
  4794.6  571.54  4795.1  571.04  4822.9  571.54  4831.1  571.54  5188.6  571.54
  5218.0  572.93  5238.9  576.31  5248.2  575.79  5259.7  576.64  5268.2  576.26
  5274.4  577.30  5318.4  578.13  5580.8  579.79  5811.8  580.06  5957.3  582.63
#Mann=6,-1,0
  4108.3    0.05       0  4267.9     0.1       0  4794.6   0.033       0
  4822.9     0.1       0  4831.1    0.05       0  5248.2     0.1       0
Bank Sta=4794.6,4822.9
Exp/Cntr=0.3,0.1

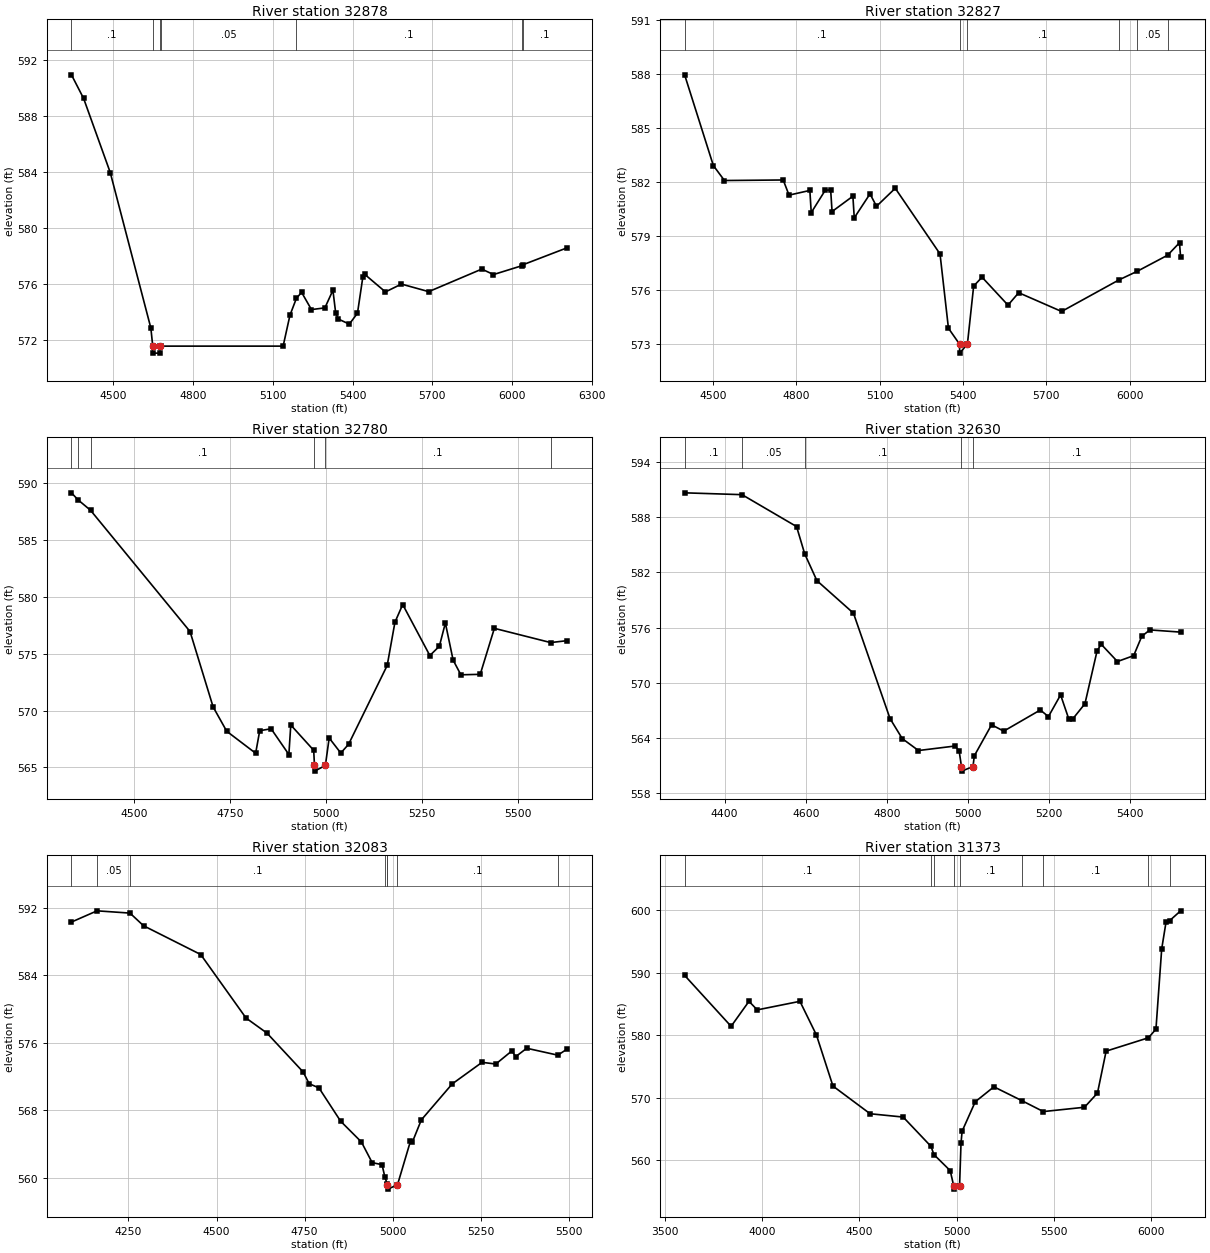
Type RM Length L Ch R = 1,32878,51,51,51
BEGIN DESCRIPTION:
Mapping XS 265b10d0
END DESCRIPTION:
XS GIS Cut Line= 5
      1963972.46     13509160.65      1963993.29     13508865.52
      1963896.07     13508209.27      1963865.58     13508065.99
      1963193.68     13507709.89
#Sta/Elev= 30
  4341.9  590.91  4387.7  589.22  4487.9  583.93  4640.6  572.83  4647.7  571.54
  4648.2  571.04  4675.6  571.04  4676.1  571.54  4678.8  571.54  5138.3  571.54
  5164.0  573.75  5188.4  574.96  5207.8  575.38  5244.8  574.15  5295.4  574.27
  5325.6  575.53  5336.2  573.88  5346.4  573.47  5387.3  573.11  5418.0  573.89
  5438.5  576.51  5445.6  576.66  5523.2  575.41  5583.5  575.97  5686.0  575.43
  5885.8  577.04  5929.8  576.65  6036.7  577.28  6039.4  577.34  6208.1  578.57
#Mann=7,-1,0
  4341.9     0.1       0  4647.7   0.033       0  4676.1     0.1       0
  4678.8    0.05       0  5188.4     0.1       0  6036.7    0.05       0
  6039.4     0.1       0
Bank Sta=4647.7,4676.1
Exp/Cntr=0.3,0.1

Type RM Length L Ch R = 1,32827,47,47,47
BEGIN DESCRIPTION:
Mapping XS 9dc82ade
END DESCRIPTION:
XS GIS Cut Line= 5
      1964034.96     13509098.16      1964045.38     13508928.02
      1963968.99     13508327.33      1963930.35     13508027.87
      1963303.48     13507699.70
#Sta/Elev= 30
  4398.3  587.94  4501.7  582.91  4541.7  582.08  4753.2  582.11  4774.2  581.27
  4849.1  581.53  4854.1  580.30  4904.5  581.54  4924.0  581.56  4929.1  580.36
  5004.0  581.21  5009.0  580.01  5065.7  581.34  5089.0  580.65  5156.5  581.65
  5317.7  578.01  5348.0  573.89  5387.9  573.01  5388.4  572.51  5416.3  573.01
  5438.8  576.23  5469.0  576.72  5562.4  575.17  5600.9  575.86  5755.4  574.82
  5961.9  576.57  6027.9  577.05  6137.1  577.94  6179.8  578.63  6183.8  577.82
#Mann=6,-1,0
  4398.3     0.1       0  5387.9    0.07       0  5416.3     0.1       0
  5961.9    0.08       0  6027.9    0.05       0  6137.1     0.1       0
Bank Sta=5387.9,5416.3
Exp/Cntr=0.3,0.1

Type RM Length L Ch R = 1,32780,150,150,150
BEGIN DESCRIPTION:
Mapping XS cd44cb1d
END DESCRIPTION:
XS GIS Cut Line= 4
      1964076.63     13509153.76      1964076.63     13508803.02
      1964017.60     13508327.33      1963953.94     13507870.01
#Sta/Elev= 30
  4337.6  589.12  4354.5  588.51  4387.2  587.59  4646.4  576.94  4706.5  570.32
  4742.0  568.18  4817.3  566.25  4827.9  568.23  4857.6  568.40  4903.8  566.14
  4908.8  568.73  4968.5  566.51  4970.5  565.18  4971.0  564.68  4998.9  565.18
  5008.8  567.59  5039.0  566.27  5059.2  567.03  5159.9  573.96  5180.1  577.76
  5200.3  579.31  5271.0  574.83  5295.8  575.65  5311.4  577.69  5331.6  574.43
  5351.8  573.14  5402.2  573.18  5439.0  577.22  5585.6  575.97  5629.4  576.14
#Mann=6,-1,0
  4337.6     0.1       0  4354.5    0.05       0  4387.2     0.1       0
  4970.5    0.07       0  4998.9     0.1       0  5585.6    0.08       0
Bank Sta=4970.5,4998.9
Exp/Cntr=0.3,0.1

Type RM Length L Ch R = 1,32630,547,547,547
BEGIN DESCRIPTION:
Buckhorn Creek 40.0
END DESCRIPTION:
XS GIS Cut Line= 3
      1964212.04     13509240.56      1964175.00     13508525.00
      1964160.41     13508019.32
#Sta/Elev= 30
  4301.3  590.66  4442.8  590.46  4577.2  586.99  4597.2  584.03  4627.3  581.11
  4717.4  577.57  4807.5  566.11  4837.6  563.93  4877.6  562.63  4967.7  563.12
  4977.8  562.60  4983.6  560.89  4984.1  560.39  5012.0  560.89  5015.3  562.06
  5057.8  565.43  5087.8  564.74  5177.9  567.04  5197.9  566.32  5227.9  568.68
  5247.9  566.09  5257.9  566.07  5287.9  567.72  5317.9  573.48  5327.9  574.19
  5368.0  572.31  5408.0  572.95  5428.0  575.06  5448.0  575.75  5523.7  575.51
#Mann=5,-1,0
  4301.3     0.1       0  4442.8    0.05       0  4597.2     0.1       0
  4983.6    0.07       0  5012.0     0.1       0
Bank Sta=4983.6,5012
Exp/Cntr=0.3,0.1

Type RM Length L Ch R = 1,32083,710,710,710
BEGIN DESCRIPTION:
Buckhorn Creek 39.0
END DESCRIPTION:
XS GIS Cut Line= 3
      1964278.00     13509271.79      1964675.00     13508475.00
      1964503.28     13507986.20
#Sta/Elev= 30
  4088.1  590.31  4160.8  591.64  4254.2  591.37  4292.8  589.87  4455.1  586.46
  4583.8  578.93  4643.1  577.15  4746.1  572.53  4762.9  571.15  4790.8  570.65
  4852.4  566.70  4911.3  564.24  4941.9  561.79  4969.9  561.55  4978.2  560.04
  4984.8  559.25  4985.3  559.15  4985.8  558.65  5013.7  559.15  5050.5  564.32
  5055.8  564.20  5081.5  566.86  5169.1  571.12  5253.9  573.68  5293.0  573.48
  5338.7  575.04  5349.3  574.35  5380.7  575.35  5469.1  574.53  5496.4  575.28
#Mann=8,-1,0
  4088.1     0.1       0  4160.8    0.05       0  4254.2     0.1       0
  4978.2    0.12       0  4984.8     0.1       0  4985.3    0.07       0
  5013.7     0.1       0  5469.1    0.08       0
Bank Sta=4985.3,5013.7
Exp/Cntr=0.3,0.1

Type RM Length L Ch R = 1,31373,535,535,535
BEGIN DESCRIPTION:
Buckhorn Creek 38.0
END DESCRIPTION:
XS GIS Cut Line= 3
      1964382.20     13509569.75      1965237.22     13508740.78
      1965831.86     13507521.12
#Sta/Elev= 30
  3601.9  589.58  3840.7  581.43  3932.5  585.43  3975.0  584.06  4194.2  585.43
  4279.0  580.04  4363.9  571.87  4554.8  567.44  4724.6  566.91  4867.5  562.22
  4882.4  560.91  4966.1  558.34  4984.3  555.88  4984.8  555.38  5014.2  555.88
  5021.7  562.76  5027.3  564.65  5094.9  569.36  5190.6  571.75  5336.5  569.50
  5444.5  567.79  5655.9  568.48  5722.6  570.75  5767.1  577.46  5984.6  579.60
  6023.0  580.98  6052.5  593.81  6075.0  598.15  6092.7  598.32  6149.7  599.91
#Mann=9,-1,0
  3601.9     0.1       0  4867.5    0.12       0  4882.4     0.1       0
  4984.3    0.07       0  5014.2     0.1       0  5336.5    0.08       0
  5444.5     0.1       0  5984.6    0.05       0  6092.7     0.1       0
Bank Sta=4984.3,5014.2
Exp/Cntr=0.3,0.1

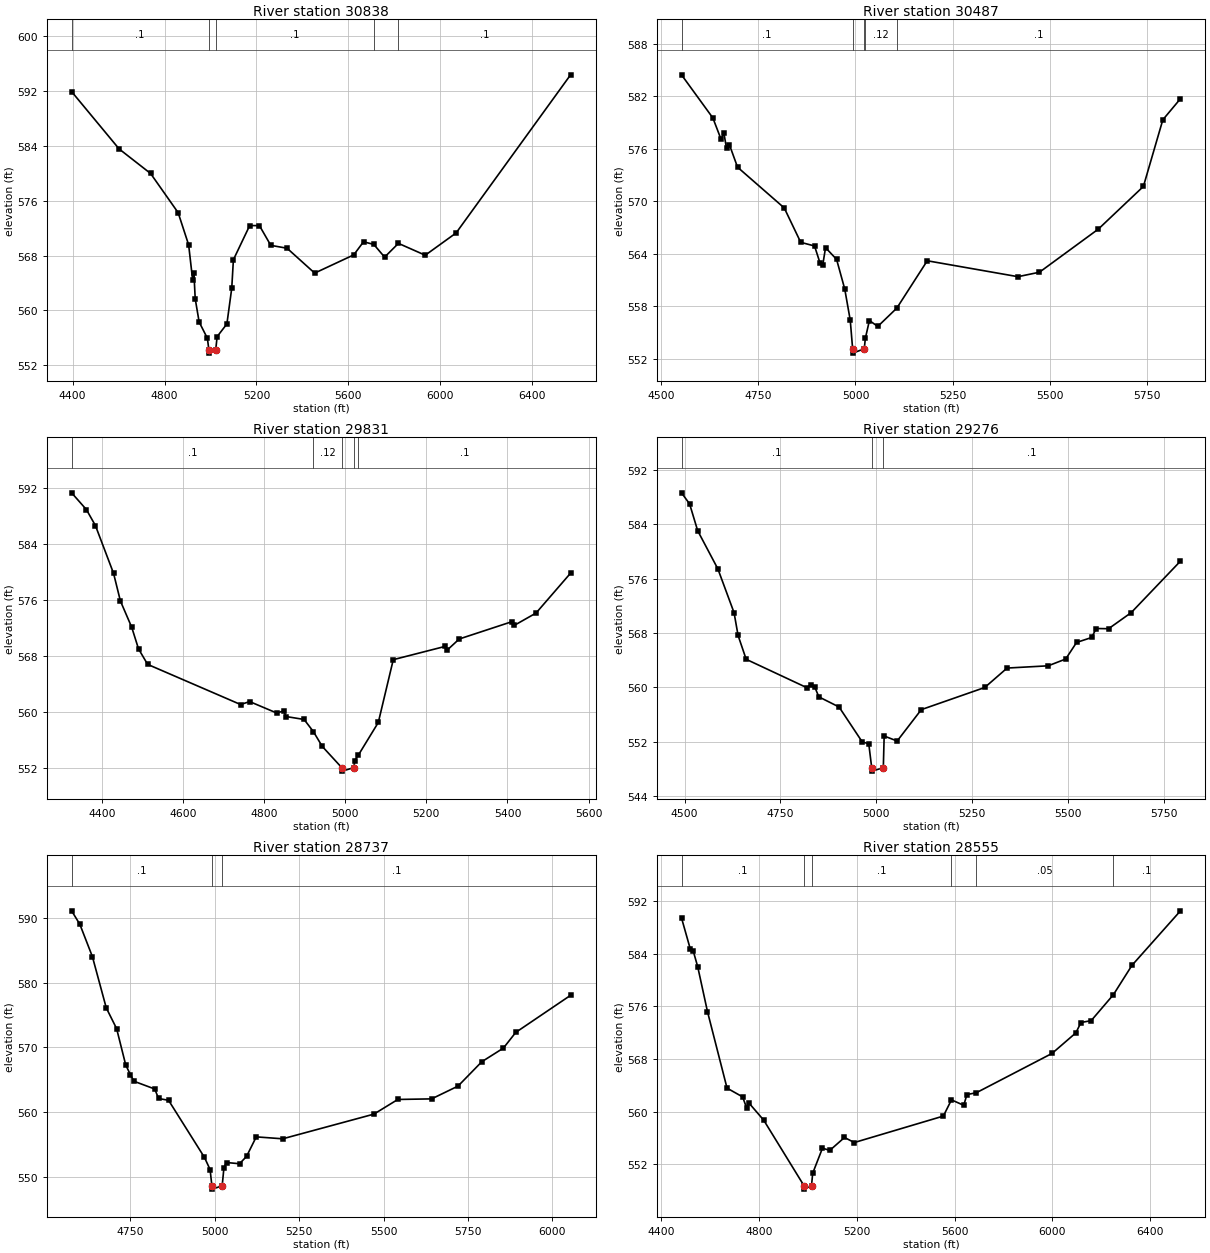
Type RM Length L Ch R = 1,30838,351,351,351
BEGIN DESCRIPTION:
Buckhorn Creek 37.0
END DESCRIPTION:
XS GIS Cut Line= 3
      1965315.35     13509512.47      1965554.17     13509000.00
      1966655.64     13507831.90
#Sta/Elev= 30
  4395.8  591.93  4602.6  583.56  4739.4  579.98  4859.3  574.26  4905.0  569.56
  4922.3  564.46  4927.9  565.45  4933.6  561.68  4950.7  558.30  4986.5  555.93
  4992.9  554.26  4993.4  553.76  5022.9  554.26  5028.9  556.17  5071.4  558.02
  5092.5  563.23  5099.7  567.39  5170.6  572.38  5213.0  572.37  5262.4  569.49
  5333.2  569.07  5453.3  565.44  5623.3  568.10  5665.8  570.01  5710.5  569.63
  5757.6  567.77  5817.7  569.78  5934.4  568.05  6068.7  571.30  6566.7  594.38
#Mann=5,-1,0
  4395.8     0.1       0  4992.9    0.07       0  5022.9     0.1       0
  5710.5    0.08       0  5817.7     0.1       0
Bank Sta=4992.9,5022.9
Exp/Cntr=0.3,0.1

Type RM Length L Ch R = 1,30487,656,656,656
BEGIN DESCRIPTION:
Buckhorn Creek 36.0
END DESCRIPTION:
XS GIS Cut Line= 3
      1965551.75     13509495.68      1966048.27     13508971.38
      1966574.96     13508775.02
#Sta/Elev= 30
  4552.3  584.44  4633.0  579.51  4654.0  577.08  4661.3  577.79  4668.2  576.03
  4675.5  576.46  4696.5  573.88  4816.7  569.22  4859.1  565.29  4894.7  564.87
  4908.9  562.91  4915.8  562.69  4923.0  564.68  4951.4  563.34  4972.4  559.95
  4986.6  556.38  4992.7  553.12  4993.2  552.62  5022.7  553.12  5025.4  554.30
  5035.9  556.35  5057.4  555.67  5106.5  557.77  5184.8  563.18  5418.2  561.36
  5473.5  561.87  5625.1  566.80  5741.1  571.68  5791.1  579.30  5836.5  581.71
#Mann=5,-1,0
  4552.3     0.1       0  4992.7    0.07       0  5022.7     0.1       0
  5025.4    0.12       0  5106.5     0.1       0
Bank Sta=4992.7,5022.7
Exp/Cntr=0.3,0.1

Type RM Length L Ch R = 1,29831,555,555,555
BEGIN DESCRIPTION:
Buckhorn Creek 35.0
END DESCRIPTION:
XS GIS Cut Line= 3
      1966175.00     13509974.99      1966475.00     13509375.00
      1966575.00     13508825.03
#Sta/Elev= 30
  4325.7  591.26  4362.0  588.88  4384.4  586.59  4429.1  579.77  4445.9  575.84
  4473.8  572.09  4490.6  569.00  4513.0  566.79  4742.2  561.06  4764.5  561.48
  4831.6  559.84  4848.4  560.16  4854.0  559.35  4898.7  558.93  4921.8  557.18
  4943.4  555.09  4991.5  552.06  4992.0  551.56  5021.8  552.06  5023.2  553.07
  5032.2  553.82  5081.6  558.50  5118.5  567.46  5246.8  569.36  5251.9  568.85
  5281.1  570.41  5412.0  572.90  5417.0  572.36  5470.4  574.11  5555.5  579.80
#Mann=5,-1,0
  4325.7     0.1       0  4921.8    0.12       0  4991.5    0.07       0
  5021.8    0.12       0  5032.2     0.1       0
Bank Sta=4991.5,5021.8
Exp/Cntr=0.3,0.1

Type RM Length L Ch R = 1,29276,539,539,539
BEGIN DESCRIPTION:
Buckhorn Creek 34.0
END DESCRIPTION:
XS GIS Cut Line= 3
      1967125.01     13510025.04      1966975.00     13509575.00
      1966625.01     13508825.03
#Sta/Elev= 30
  4492.0  588.65  4513.1  587.02  4534.2  583.07  4586.9  577.45  4629.1  571.01
  4639.6  567.66  4660.7  564.15  4818.8  559.98  4829.4  560.39  4839.9  560.04
  4850.4  558.62  4903.1  557.13  4963.7  551.98  4980.6  551.73  4988.3  548.19
  4988.8  547.69  5018.6  548.19  5020.8  552.86  5054.7  552.12  5117.7  556.74
  5283.3  560.00  5341.6  562.86  5448.8  563.19  5494.5  564.19  5522.9  566.63
  5562.3  567.36  5574.1  568.68  5606.4  568.65  5665.5  571.02  5794.0  578.60
#Mann=3,-1,0
  4492.0     0.1       0  4988.3    0.07       0  5018.6     0.1       0
Bank Sta=4988.3,5018.6
Exp/Cntr=0.3,0.1

Type RM Length L Ch R = 1,28737,182,182,182
BEGIN DESCRIPTION:
Buckhorn Creek 33.0
END DESCRIPTION:
XS GIS Cut Line= 3
      1967525.00     13509825.02      1967425.00     13509375.00
      1966781.13     13508589.71
#Sta/Elev= 30
  4577.0  591.15  4601.4  589.06  4638.5  584.06  4679.5  576.13  4710.2  572.91
  4737.1  567.29  4751.2  565.76  4761.4  564.77  4822.9  563.57  4834.4  562.10
  4863.9  561.82  4970.1  552.98  4986.8  551.10  4992.1  548.57  4992.6  548.07
  5022.5  548.57  5027.8  551.41  5035.4  552.19  5073.9  552.00  5094.7  553.14
  5123.4  556.16  5201.6  555.86  5471.5  559.68  5542.3  561.95  5642.3  562.04
  5720.5  564.02  5790.8  567.79  5854.7  569.90  5891.3  572.33  6053.5  578.07
#Mann=3,-1,0
  4577.0     0.1       0  4992.1    0.07       0  5022.5     0.1       0
Bank Sta=4992.1,5022.5
Exp/Cntr=0.3,0.1

Type RM Length L Ch R = 1,28555,408,408,408
BEGIN DESCRIPTION:
Mapping XS bb4a6419
END DESCRIPTION:
XS GIS Cut Line= 3
      1967592.25     13509811.11      1967544.51     13508843.21
      1967848.34     13507814.52
#Sta/Elev= 30
  4482.8  589.40  4519.0  584.65  4531.2  584.32  4549.0  582.01  4589.0  575.19
  4669.1  563.57  4732.8  562.24  4749.2  560.57  4759.2  561.29  4819.3  558.70
  4984.3  548.74  4984.8  548.24  5014.7  548.74  5019.6  550.65  5059.6  554.46
  5089.6  554.12  5149.7  556.08  5189.8  555.31  5554.3  559.33  5587.4  561.79
  5637.7  560.96  5650.6  562.59  5689.2  562.87  5999.1  568.84  6096.5  571.96
  6117.3  573.53  6159.1  573.81  6250.2  577.76  6325.9  582.20  6524.5  590.48
#Mann=6,-1,0
  4482.8     0.1       0  4984.3    0.07       0  5014.7     0.1       0
  5587.4    0.08       0  5689.2    0.05       0  6250.2     0.1       0
Bank Sta=4984.3,5014.7
Exp/Cntr=0.3,0.1

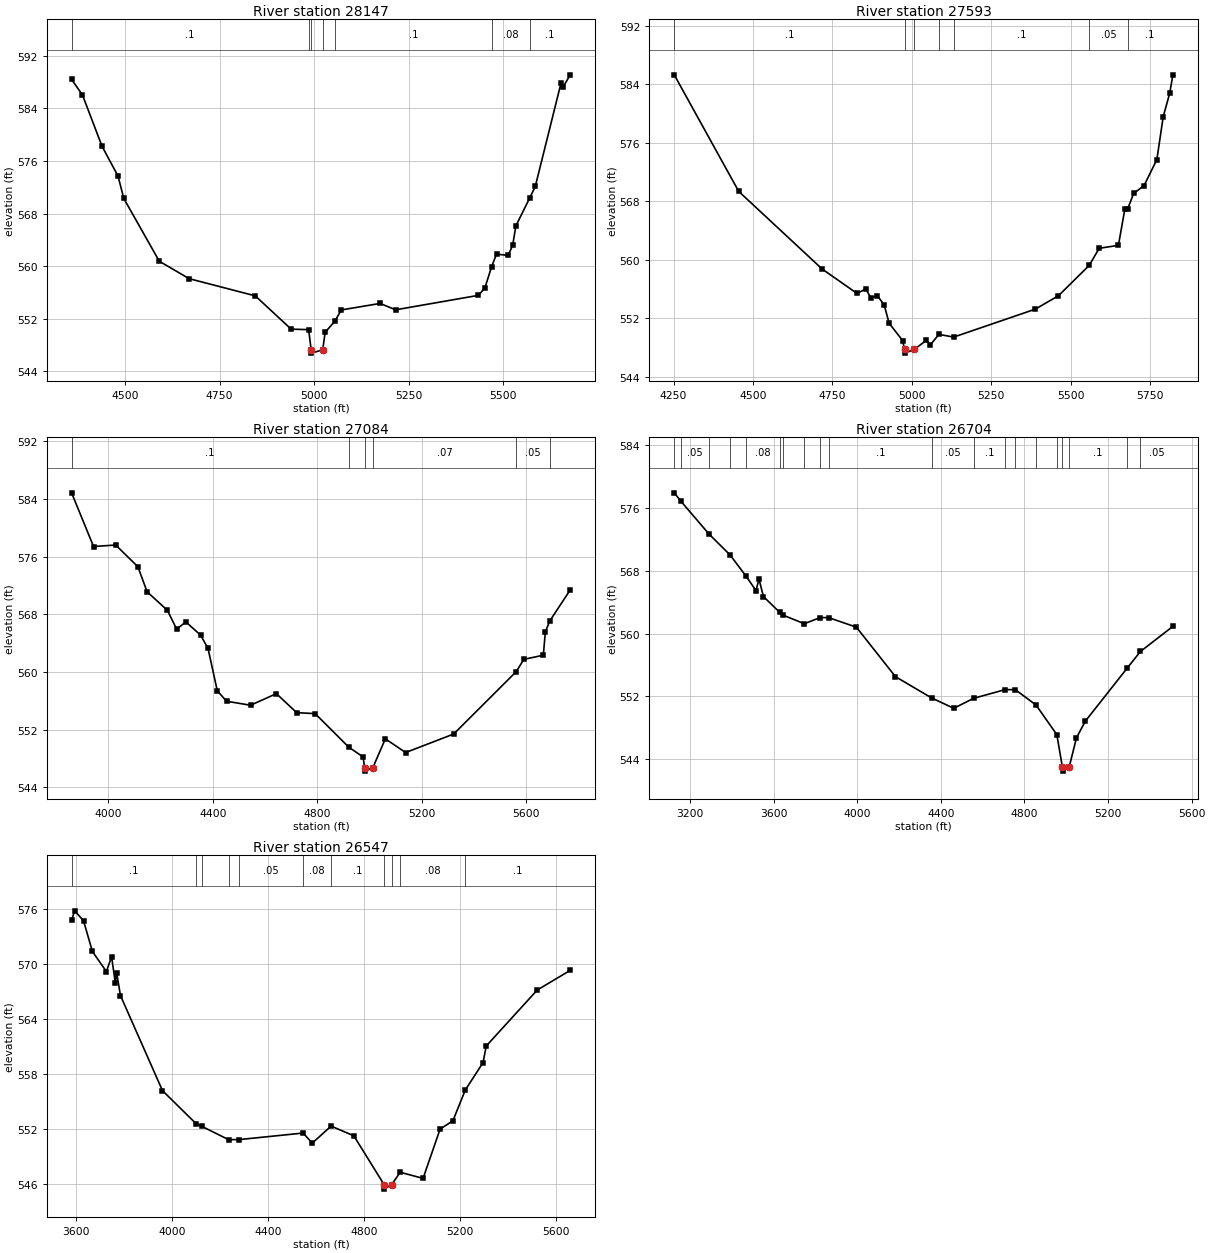
Type RM Length L Ch R = 1,28147,554,554,554
BEGIN DESCRIPTION:
Buckhorn Creek 32.0
END DESCRIPTION:
XS GIS Cut Line= 3
      1967624.97     13509825.04      1967975.00     13509275.00
      1968125.01     13508624.95
#Sta/Elev= 30
  4358.4  588.42  4387.2  586.05  4438.9  578.25  4481.2  573.72  4496.5  570.31
  4590.4  560.76  4669.2  558.11  4844.4  555.49  4939.2  550.43  4985.5  550.35
  4992.2  547.28  4992.7  546.78  5022.7  547.28  5029.2  549.95  5055.0  551.65
  5071.9  553.35  5174.6  554.34  5215.6  553.37  5434.6  555.57  5451.7  556.69
  5469.6  559.94  5482.5  561.84  5513.2  561.65  5525.2  563.16  5533.8  566.14
  5570.1  570.36  5585.1  572.14  5653.5  587.94  5658.6  587.25  5677.5  589.12
#Mann=7,-1,0
  4358.4     0.1       0  4985.5    0.12       0  4992.2    0.07       0
  5022.7    0.12       0  5055.0     0.1       0  5469.6    0.08       0
  5570.1     0.1       0
Bank Sta=4992.2,5022.7
Exp/Cntr=0.3,0.1

Type RM Length L Ch R = 1,27593,509,509,509
BEGIN DESCRIPTION:
Buckhorn Creek 31.0
END DESCRIPTION:
XS GIS Cut Line= 3
      1968074.99     13510125.02      1968475.00     13509475.00
      1968375.00     13508674.97
#Sta/Elev= 30
  4252.1  585.28  4455.0  569.36  4717.8  558.75  4827.5  555.42  4855.0  556.04
  4870.4  554.86  4891.7  555.11  4913.0  553.84  4928.4  551.36  4970.9  548.99
  4976.9  547.77  4977.4  547.27  5007.5  547.77  5045.6  549.02  5058.2  548.40
  5085.2  549.83  5131.6  549.46  5388.2  553.27  5461.3  555.10  5558.0  559.24
  5589.8  561.59  5650.2  561.99  5670.4  566.93  5678.9  566.92  5698.1  569.08
  5730.9  570.15  5771.2  573.70  5791.3  579.58  5811.5  582.74  5821.6  585.26
#Mann=7,-1,0
  4252.1     0.1       0  4976.9    0.07       0  5007.5     0.1       0
  5085.2    0.07       0  5131.6     0.1       0  5558.0    0.05       0
  5678.9     0.1       0
Bank Sta=4976.9,5007.5
Exp/Cntr=0.3,0.1

Type RM Length L Ch R = 1,27084,380,380,380
BEGIN DESCRIPTION:
Mapping XS 9a845340
END DESCRIPTION:
XS GIS Cut Line= 4
      1969644.80     13510154.01      1968616.12     13509120.12
      1968439.04     13508922.20      1968394.77     13508742.51
#Sta/Elev= 30
  3859.1  584.86  3943.1  577.41  4027.9  577.62  4112.8  574.61  4148.2  571.13
  4225.9  568.56  4261.3  565.95  4296.7  566.95  4353.2  565.11  4381.5  563.27
  4416.9  557.40  4452.2  555.95  4544.2  555.39  4643.2  557.00  4720.9  554.36
  4791.6  554.23  4919.9  549.59  4975.5  548.21  4980.6  546.75  4981.1  546.25
  5012.8  546.75  5060.3  550.73  5138.1  548.83  5322.2  551.40  5561.9  560.07
  5590.6  561.76  5665.3  562.33  5672.9  565.54  5689.2  567.04  5768.2  571.39
#Mann=6,-1,0
  3859.1     0.1       0  4919.9    0.07       0  4980.6    0.07       0
  5012.8    0.07       0  5561.9    0.05       0  5689.2     0.1       0
Bank Sta=4980.6,5012.8
Exp/Cntr=0.3,0.1

Type RM Length L Ch R = 1,26704,157,157,157
BEGIN DESCRIPTION:
Buckhorn Creek 30.0
END DESCRIPTION:
XS GIS Cut Line= 4
      1970578.83     13509886.64      1969485.05     13509105.36
      1968946.85     13509005.54      1968465.06     13508897.02
#Sta/Elev= 30
  3124.7  577.89  3155.9  576.84  3291.3  572.64  3392.2  569.98  3468.8  567.27
  3515.6  565.47  3530.3  566.91  3551.2  564.71  3628.6  562.71  3646.3  562.33
  3746.8  561.25  3823.8  562.04  3865.0  562.01  3996.1  560.81  4182.9  554.52
  4356.3  551.81  4461.8  550.50  4557.3  551.77  4707.5  552.87  4756.2  552.87
  4855.6  550.91  4955.0  547.15  4981.7  543.01  4982.2  542.51  5013.9  543.01
  5048.9  546.74  5091.0  548.85  5291.1  555.59  5355.0  557.72  5510.1  560.91
#Mann=20,-1,0
  3124.7    0.08       0  3155.9    0.05       0  3291.3    0.05       0
  3392.2     0.1       0  3468.8    0.08       0  3628.6     0.1       0
  3646.3    0.05       0  3746.8     0.1       0  3823.8    0.08       0
  3865.0     0.1       0  4356.3    0.05       0  4557.3     0.1       0
  4707.5    0.05       0  4756.2    0.08       0  4855.6    0.05       0
  4955.0     0.1       0  4981.7    0.07       0  5013.9     0.1       0
  5291.1    0.08       0  5355.0    0.05       0
Bank Sta=4981.7,5013.9
Exp/Cntr=0.3,0.1

Type RM Length L Ch R = 1,26547,637,637,637
BEGIN DESCRIPTION:
Buckhorn Creek 29.0
END DESCRIPTION:
XS GIS Cut Line= 4
      1970353.06     13509435.20      1969741.12     13509070.64
      1969159.52     13508901.37      1968409.34     13508784.29
#Sta/Elev= 30
  3580.8  574.77  3593.5  575.78  3630.5  574.70  3667.5  571.35  3725.9  569.16
  3747.3  570.79  3762.9  567.95  3768.7  569.00  3784.3  566.55  3959.5  556.18
  4101.1  552.54  4122.7  552.30  4235.0  550.84  4279.2  550.85  4545.1  551.56
  4583.8  550.47  4661.9  552.32  4756.6  551.26  4882.5  545.95  4883.0  545.45
  4914.7  545.95  4949.7  547.29  5045.1  546.62  5116.0  551.99  5169.4  552.90
  5221.0  556.25  5294.9  559.24  5308.3  561.05  5520.8  567.15  5658.1  569.29
#Mann=11,-1,0
  3580.8     0.1       0  4101.1    0.05       0  4122.7     0.1       0
  4235.0    0.08       0  4279.2    0.05       0  4545.1    0.08       0
  4661.9     0.1       0  4882.5    0.07       0  4914.7     0.1       0
  4949.7    0.08       0  5221.0     0.1       0
Bank Sta=4882.5,4914.7
Exp/Cntr=0.3,0.1