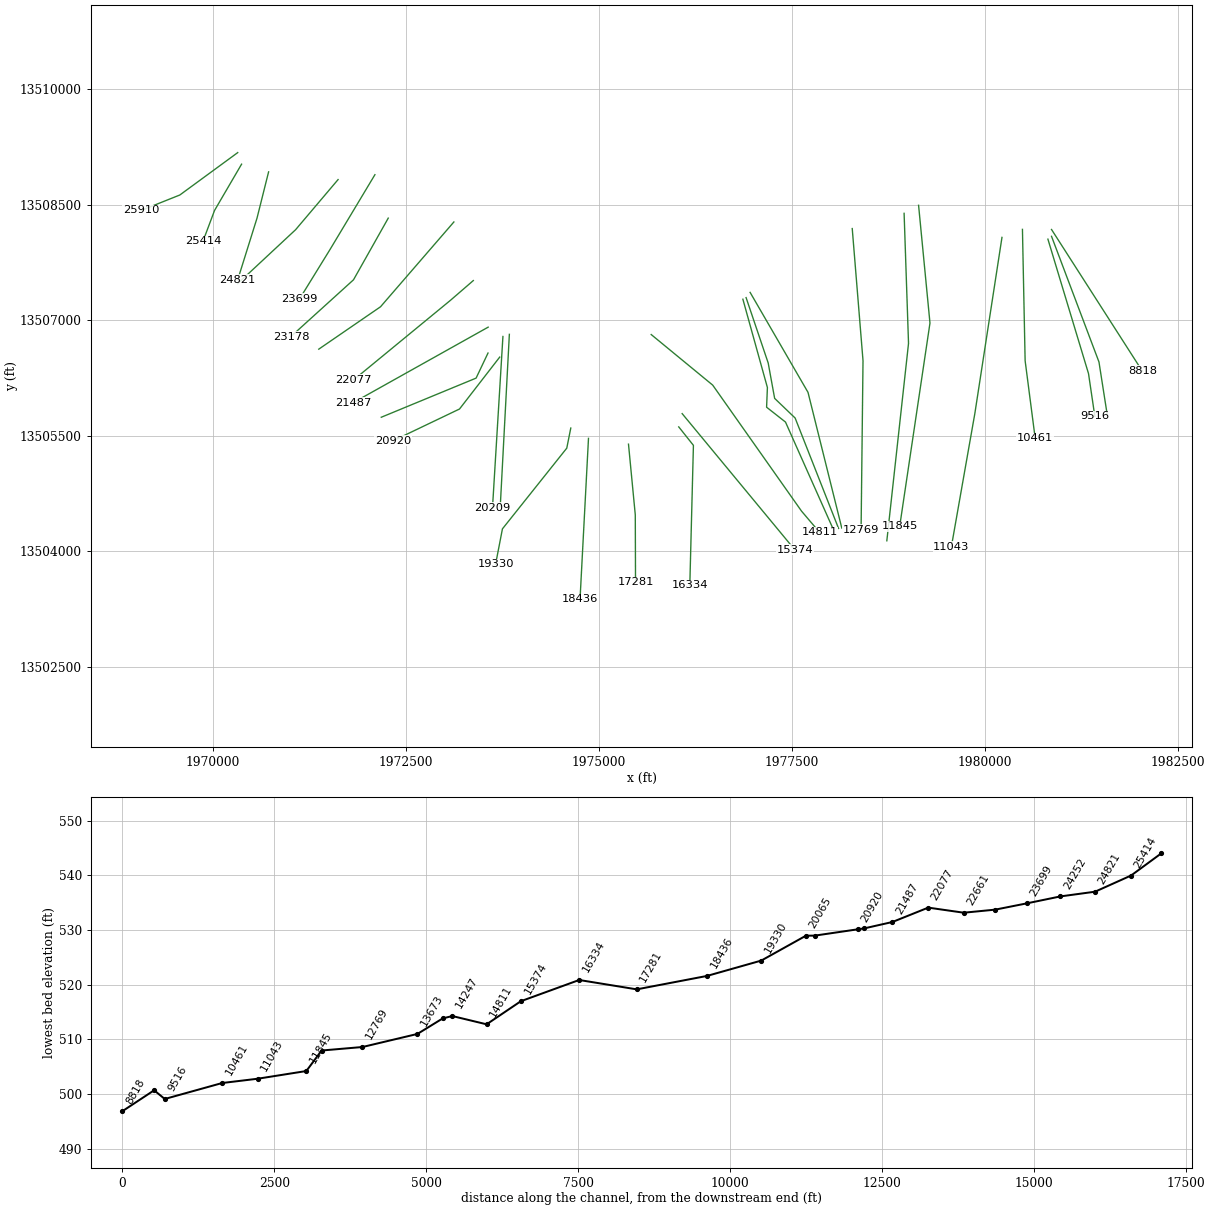
HEC-RAS study Buckhorn Creek.prj: Buckhorn Creek Base Level Engineering

--- Buckhorn Creek.g01 (geometry) --- (continued)

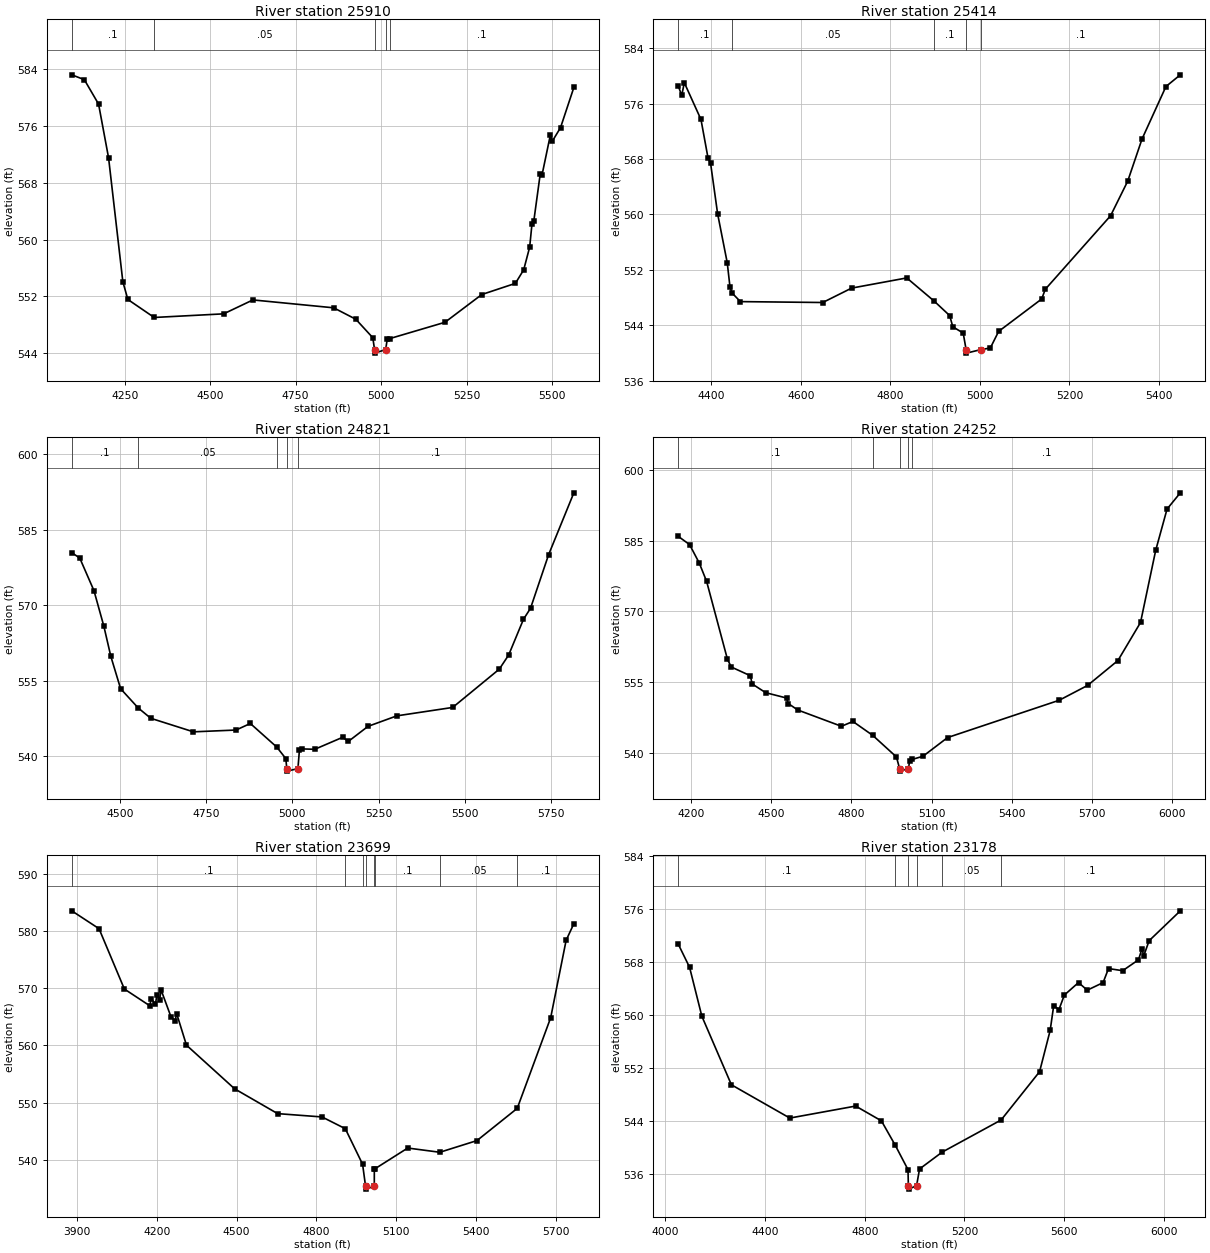
Type RM Length L Ch R = 1,25910,496,496,496
BEGIN DESCRIPTION:
Buckhorn Creek 28.0
END DESCRIPTION:
XS GIS Cut Line= 3
      1970325.02     13509175.02      1969575.00     13508625.00
      1969075.00     13508425.00
#Sta/Elev= 30
  4095.2  583.19  4131.9  582.51  4173.6  579.07  4202.9  571.49  4244.6  554.06
  4259.3  551.56  4336.3  549.03  4539.4  549.54  4625.1  551.50  4861.3  550.39
  4926.1  548.78  4975.7  546.18  4980.9  544.51  4981.4  544.01  5013.3  544.51
  5018.0  545.97  5025.6  546.06  5186.8  548.35  5294.5  552.26  5392.8  553.83
  5417.1  555.74  5434.6  558.94  5441.3  562.18  5446.7  562.61  5465.5  569.25
  5470.9  569.13  5495.1  574.72  5500.5  573.82  5524.8  575.75  5563.8  581.41
#Mann=5,-1,0
  4095.2     0.1       0  4336.3    0.05       0  4980.9    0.03       0
  5013.3    0.05       0  5025.6     0.1       0
Bank Sta=4980.9,5013.3
Exp/Cntr=0.3,0.1

Type RM Length L Ch R = 1,25414,593,593,593
BEGIN DESCRIPTION:
Buckhorn Creek 27.0
END DESCRIPTION:
XS GIS Cut Line= 3
      1970374.98     13509024.97      1970025.00     13508425.00
      1969875.00     13508024.99
#Sta/Elev= 30
  4325.9  578.56  4333.7  577.19  4339.5  579.02  4376.7  573.71  4392.4  568.17
  4398.2  567.37  4413.9  560.09  4435.4  553.02  4441.6  549.48  4446.5  548.63
  4464.8  547.41  4648.8  547.28  4713.3  549.36  4836.5  550.83  4897.6  547.49
  4932.4  545.39  4939.4  543.77  4962.6  542.87  4969.1  540.47  4969.7  539.97
  5001.5  540.47  5023.2  540.71  5041.8  543.11  5138.0  547.79  5146.0  549.19
  5291.9  559.81  5330.2  564.81  5362.2  570.90  5415.6  578.47  5447.7  580.16
#Mann=5,-1,0
  4325.9     0.1       0  4446.5    0.05       0  4897.6     0.1       0
  4969.1    0.07       0  5001.5     0.1       0
Bank Sta=4969.1,5001.5
Exp/Cntr=0.3,0.1

Type RM Length L Ch R = 1,24821,569,569,569
BEGIN DESCRIPTION:
Buckhorn Creek 26.0
END DESCRIPTION:
XS GIS Cut Line= 3
      1970725.00     13508925.00      1970575.00     13508325.00
      1970325.00     13507525.01
#Sta/Elev= 30
  4360.1  580.44  4383.3  579.36  4424.5  572.88  4452.9  565.89  4473.5  559.80
  4501.8  553.39  4552.8  549.57  4589.4  547.51  4713.1  544.82  4836.8  545.18
  4878.1  546.48  4955.0  541.78  4981.2  539.49  4983.8  537.51  4984.4  537.01
  5016.2  537.51  5020.5  541.13  5027.3  541.43  5065.0  541.35  5146.2  543.74
  5162.4  542.91  5219.5  545.91  5303.3  548.00  5465.2  549.67  5600.4  557.28
  5627.6  560.09  5670.6  567.20  5691.0  569.38  5743.4  580.02  5816.7  592.33
#Mann=5,-1,0
  4360.1     0.1       0  4552.8    0.05       0  4955.0     0.1       0
  4983.8    0.07       0  5016.2     0.1       0
Bank Sta=4983.8,5016.2
Exp/Cntr=0.3,0.1

Type RM Length L Ch R = 1,24252,553,553,553
BEGIN DESCRIPTION:
Buckhorn Creek 25.0
END DESCRIPTION:
XS GIS Cut Line= 3
      1971625.01     13508825.01      1971075.00     13508175.00
      1970325.00     13507475.00
#Sta/Elev= 30
  4152.3  585.89  4194.6  584.15  4230.9  580.24  4258.3  576.37  4336.3  559.85
  4350.6  558.21  4422.0  556.36  4428.6  554.63  4479.2  552.77  4557.2  551.64
  4563.8  550.47  4598.9  549.11  4762.6  545.65  4805.5  546.67  4879.9  543.71
  4968.1  539.16  4980.3  536.65  4980.8  536.15  5013.0  536.65  5017.7  538.36
  5027.7  538.64  5067.5  539.30  5159.4  543.26  5577.1  551.17  5683.1  554.31
  5796.4  559.58  5880.9  567.64  5937.6  582.91  5980.1  591.67  6029.7  595.11
#Mann=5,-1,0
  4152.3     0.1       0  4879.9    0.07       0  4980.3    0.07       0
  5013.0    0.07       0  5027.7     0.1       0
Bank Sta=4980.3,5013
Exp/Cntr=0.3,0.1

Type RM Length L Ch R = 1,23699,521,521,521
BEGIN DESCRIPTION:
Buckhorn Creek 24.0
END DESCRIPTION:
XS GIS Cut Line= 3
      1972102.25     13508888.38      1971525.00     13507925.00
      1971125.00     13507275.01
#Sta/Elev= 30
  3880.8  583.50  3983.2  580.38  4078.4  569.84  4173.7  566.92  4179.5  568.16
  4195.1  567.18  4200.9  568.88  4210.6  567.92  4216.5  569.66  4253.4  565.00
  4269.0  564.28  4274.8  565.56  4311.7  560.03  4492.5  552.41  4654.2  548.07
  4821.1  547.49  4908.4  545.44  4973.4  539.23  4984.6  535.38  4985.1  534.88
  5017.4  535.38  5017.5  538.34  5021.5  538.48  5143.0  542.06  5263.6  541.32
  5403.1  543.36  5554.4  548.99  5680.1  564.83  5738.1  578.35  5767.1  581.25
#Mann=8,-1,0
  3880.8     0.1       0  4908.4    0.07       0  4973.4    0.12       0
  4984.6    0.07       0  5017.4    0.12       0  5021.5     0.1       0
  5263.6    0.05       0  5554.4     0.1       0
Bank Sta=4984.6,5017.4
Exp/Cntr=0.3,0.1

Type RM Length L Ch R = 1,23178,517,517,517
BEGIN DESCRIPTION:
Buckhorn Creek 23.0
END DESCRIPTION:
XS GIS Cut Line= 3
      1972274.98     13508324.96      1971825.00     13507525.00
      1971014.15     13506788.86
#Sta/Elev= 30
  4052.4  570.69  4097.9  567.19  4147.0  559.82  4265.6  549.47  4499.8  544.45
  4763.7  546.26  4867.0  544.03  4922.6  540.34  4973.6  536.67  4975.1  534.23
  4975.7  533.73  5007.9  534.23  5019.9  536.77  5110.5  539.31  5346.9  544.16
  5501.1  551.44  5543.6  557.67  5557.8  561.42  5578.8  560.81  5600.4  563.00
  5657.2  564.89  5692.3  563.74  5755.8  564.88  5777.5  567.00  5834.2  566.68
  5897.7  568.32  5911.9  570.00  5918.7  568.91  5940.3  571.20  6065.4  575.71
#Mann=6,-1,0
  4052.4     0.1       0  4922.6    0.12       0  4975.1    0.07       0
  5007.9    0.12       0  5110.5    0.05       0  5346.9     0.1       0
Bank Sta=4975.1,5007.9
Exp/Cntr=0.3,0.1

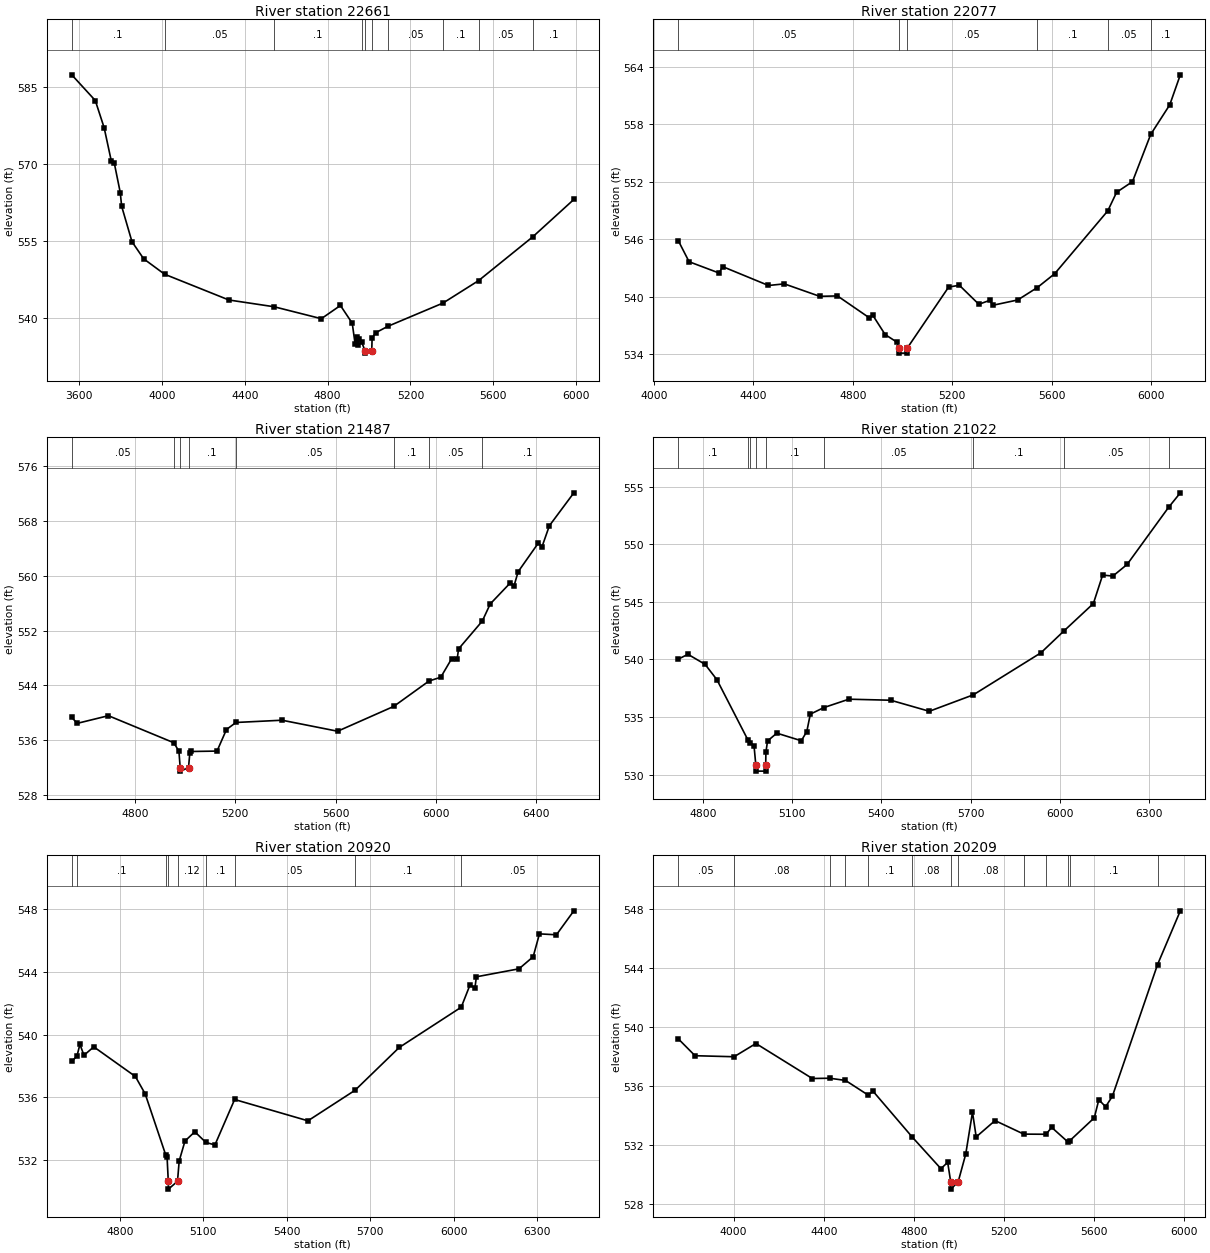
Type RM Length L Ch R = 1,22661,584,584,584
BEGIN DESCRIPTION:
Buckhorn Creek 22.0
END DESCRIPTION:
XS GIS Cut Line= 3
      1973125.02     13508275.02      1972175.00     13507175.00
      1971375.00     13506625.00
#Sta/Elev= 30
  3564.5  587.32  3678.1  582.32  3720.8  577.03  3755.9  570.46  3770.2  570.07
  3798.7  564.40  3805.3  561.76  3855.2  554.85  3911.7  551.52  4012.8  548.52
  4323.1  543.51  4541.8  542.19  4769.5  539.87  4861.7  542.44  4918.7  539.00
  4933.0  534.86  4939.6  536.22  4947.2  534.71  4953.8  536.01  4964.1  535.33
  4980.1  533.67  4980.7  533.17  5013.0  533.67  5014.7  536.10  5031.5  537.13
  5091.4  538.40  5356.9  542.91  5528.9  547.28  5790.2  555.79  5988.8  563.07
#Mann=10,-1,0
  3564.5     0.1       0  4012.8    0.05       0  4541.8     0.1       0
  4964.1    0.07       0  4980.1    0.07       0  5013.0    0.07       0
  5091.4    0.05       0  5356.9     0.1       0  5528.9    0.05       0
  5790.2     0.1       0
Bank Sta=4980.1,5013
Exp/Cntr=0.3,0.1

Type RM Length L Ch R = 1,22077,590,590,590
BEGIN DESCRIPTION:
Buckhorn Creek 21.0
END DESCRIPTION:
XS GIS Cut Line= 3
      1973377.01     13507515.08      1973083.14     13507260.75
      1971824.98     13506224.98
#Sta/Elev= 30
  4098.1  545.85  4141.7  543.64  4262.4  542.46  4276.6  543.13  4460.9  541.16
  4524.5  541.33  4666.6  540.03  4738.3  540.07  4866.0  537.79  4880.3  538.05
  4929.8  536.04  4979.3  535.21  4985.0  534.60  4985.6  534.10  5017.5  534.10
  5018.1  534.60  5185.2  541.00  5228.3  541.18  5306.5  539.20  5349.5  539.60
  5363.8  539.10  5462.8  539.65  5541.8  540.95  5611.4  542.39  5824.8  548.95
  5860.3  550.89  5924.1  552.00  5997.4  556.93  6074.0  560.02  6116.4  563.15
#Mann=6,-1,0
  4098.1    0.05       0  4985.0    0.03       0  5018.1    0.05       0
  5541.8     0.1       0  5824.8    0.05       0  5997.4     0.1       0
Bank Sta=4985,5018.1
Exp/Cntr=0.3,0.1

Type RM Length L Ch R = 1,21487,465,465,465
BEGIN DESCRIPTION:
Mapping XS 0de99b0b
END DESCRIPTION:
XS GIS Cut Line= 2
      1973569.12     13506910.41      1971824.44     13505932.61
#Sta/Elev= 30
  4548.8  539.32  4570.4  538.45  4694.8  539.57  4955.1  535.62  4975.6  534.39
  4980.7  531.97  4981.3  531.47  5013.8  531.97  5018.9  534.05  5024.7  534.34
  5127.4  534.40  5165.0  537.55  5202.8  538.58  5386.4  538.91  5607.8  537.30
  5831.4  540.93  5971.9  544.64  6018.7  545.19  6062.1  547.90  6083.8  547.79
  6089.6  549.33  6184.1  553.40  6215.7  555.90  6296.0  558.99  6310.9  558.59
  6326.9  560.61  6407.9  564.83  6422.1  564.27  6451.3  567.33  6548.8  572.14
#Mann=8,-1,0
  4548.8    0.05       0  4955.1     0.1       0  4980.7    0.07       0
  5013.8     0.1       0  5202.8    0.05       0  5831.4     0.1       0
  5971.9    0.05       0  6184.1     0.1       0
Bank Sta=4980.7,5013.8
Exp/Cntr=0.3,0.1

Type RM Length L Ch R = 1,21022,102,102,102
BEGIN DESCRIPTION:
Buckhorn Creek 20.0
END DESCRIPTION:
XS GIS Cut Line= 3
      1973567.24     13506574.58      1973413.00     13506249.46
      1972184.69     13505741.64
#Sta/Elev= 30
  4716.5  540.03  4749.2  540.45  4806.8  539.58  4846.7  538.24  4951.3  532.99
  4959.5  532.78  4971.4  532.52  4977.6  530.80  4978.2  530.30  5010.2  530.30
  5010.7  530.80  5011.4  531.93  5016.9  532.92  5048.1  533.60  5130.5  532.94
  5149.0  533.74  5160.8  535.25  5206.2  535.82  5290.6  536.55  5431.3  536.46
  5561.1  535.50  5709.3  536.93  5936.6  540.58  6013.6  542.47  6113.0  544.86
  6144.1  547.33  6178.8  547.25  6226.6  548.26  6365.8  553.21  6405.5  554.48
#Mann=9,-1,0
  4716.5     0.1       0  4951.3    0.12       0  4959.5     0.1       0
  4977.6    0.07       0  5010.7     0.1       0  5206.2    0.05       0
  5709.3     0.1       0  6013.6    0.05       0  6365.8     0.1       0
Bank Sta=4977.6,5010.7
Exp/Cntr=0.3,0.1

Type RM Length L Ch R = 1,20920,711,711,711
BEGIN DESCRIPTION:
Mapping XS b5010c7a
END DESCRIPTION:
XS GIS Cut Line= 3
      1973718.78     13506522.04      1973197.96     13505848.44
      1972338.48     13505436.65
#Sta/Elev= 30
  4627.4  538.29  4646.0  538.63  4656.7  539.38  4671.2  538.68  4706.5  539.22
  4855.9  537.33  4891.2  536.22  4964.9  532.33  4970.0  532.16  4974.3  530.64
  4974.8  530.14  5007.4  530.64  5013.5  531.94  5034.3  533.21  5069.6  533.80
  5109.4  533.12  5141.9  532.96  5212.7  535.86  5476.2  534.50  5645.6  536.45
  5804.3  539.18  6027.2  541.75  6059.1  543.19  6076.2  542.96  6081.7  543.69
  6234.8  544.20  6285.7  544.97  6308.3  546.43  6369.2  546.37  6431.9  547.90
#Mann=9,-1,0
  4627.4    0.08       0  4646.0     0.1       0  4964.9    0.12       0
  4974.3    0.07       0  5007.4    0.12       0  5109.4     0.1       0
  5212.7    0.05       0  5645.6     0.1       0  6027.2    0.05       0
Bank Sta=4974.3,5007.4
Exp/Cntr=0.3,0.1

Type RM Length L Ch R = 1,20209,144,144,144
BEGIN DESCRIPTION:
Mapping XS 28221d7d
END DESCRIPTION:
XS GIS Cut Line= 2
      1973760.46     13506789.41      1973625.04     13504563.73
#Sta/Elev= 30
  3753.8  539.20  3828.4  538.05  4001.8  537.98  4098.8  538.88  4349.3  536.50
  4426.2  536.52  4496.6  536.37  4595.6  535.39  4619.8  535.62  4793.6  532.51
  4920.4  530.37  4950.4  530.80  4963.9  529.48  4964.5  528.98  4997.1  529.48
  5030.6  531.36  5060.6  534.21  5077.1  532.53  5160.8  533.64  5288.4  532.72
  5387.4  532.71  5412.1  533.18  5486.4  532.16  5493.4  532.28  5601.6  533.83
  5621.7  535.06  5651.7  534.58  5681.8  535.29  5882.3  544.24  5983.6  547.90
#Mann=13,-1,0
  3753.8    0.05       0  4001.8    0.08       0  4426.2    0.12       0
  4496.6    0.07       0  4595.6     0.1       0  4793.6    0.08       0
  4963.9    0.04       0  4997.1    0.08       0  5288.4    0.08       0
  5387.4    0.05       0  5486.4    0.08       0  5493.4     0.1       0
  5882.3    0.08       0
Bank Sta=4963.9,4997.1
Exp/Cntr=0.3,0.1

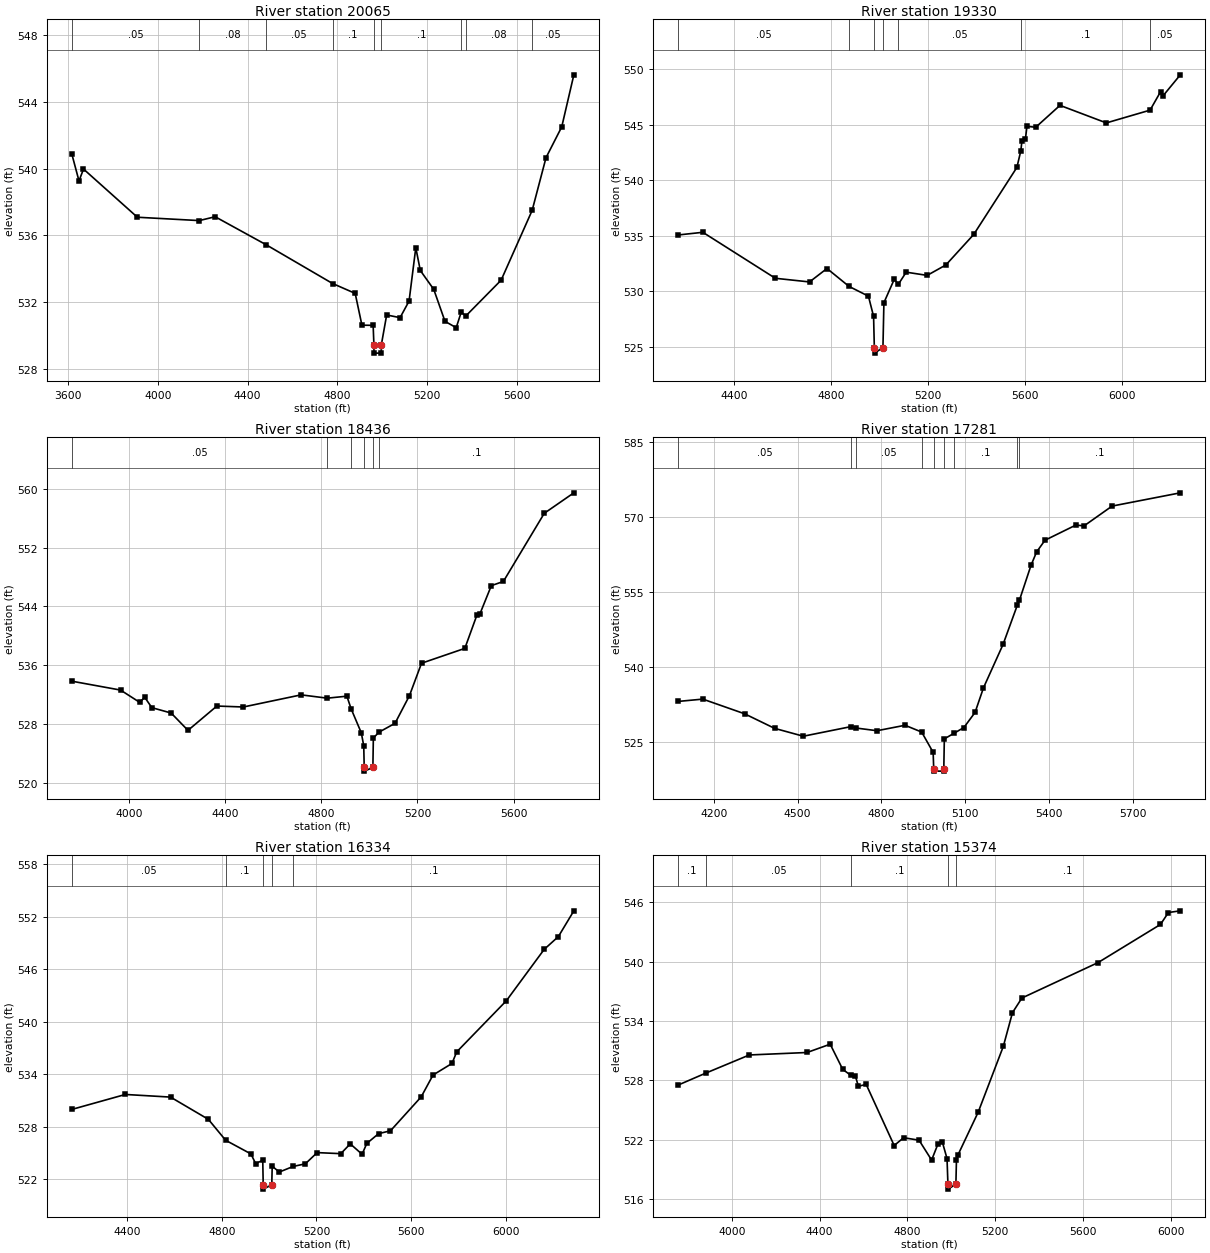
Type RM Length L Ch R = 1,20065,735,735,735
BEGIN DESCRIPTION:
Mapping XS aeae99cb
END DESCRIPTION:
XS GIS Cut Line= 2
      1973843.79     13506817.20      1973725.74     13504581.11
#Sta/Elev= 30
  3615.5  540.88  3647.7  539.26  3667.8  539.97  3908.1  537.09  4184.0  536.89
  4255.0  537.12  4481.9  535.45  4778.7  533.13  4879.5  532.54  4909.5  530.64
  4959.6  530.63  4963.0  529.47  4963.6  528.97  4995.6  528.97  4996.2  529.47
  5019.9  531.25  5079.7  531.09  5119.8  532.08  5149.8  535.27  5169.9  533.91
  5229.9  532.78  5280.0  530.87  5330.1  530.49  5352.6  531.43  5372.1  531.18
  5530.4  533.33  5668.8  537.50  5730.6  540.65  5800.7  542.49  5854.7  545.60
#Mann=9,-1,0
  3615.5    0.05       0  4184.0    0.08       0  4481.9    0.05       0
  4778.7     0.1       0  4963.0    0.07       0  4996.2     0.1       0
  5352.6    0.05       0  5372.1    0.08       0  5668.8    0.05       0
Bank Sta=4963,4996.2
Exp/Cntr=0.3,0.1

Type RM Length L Ch R = 1,19330,894,894,894
BEGIN DESCRIPTION:
Mapping XS 77f70c84
END DESCRIPTION:
XS GIS Cut Line= 4
      1974639.46     13505601.44      1974587.48     13505340.61
      1973754.14     13504293.73      1973665.60     13503835.42
#Sta/Elev= 30
  4170.3  535.06  4271.8  535.30  4570.8  531.16  4711.8  530.83  4783.8  532.04
  4874.6  530.43  4954.7  529.55  4976.0  527.73  4979.1  524.92  4979.9  524.42
  5014.6  524.92  5018.6  528.96  5060.9  531.05  5078.5  530.63  5110.5  531.71
  5197.0  531.42  5274.2  532.36  5389.2  535.11  5567.0  541.14  5583.4  542.65
  5587.8  543.52  5602.2  543.70  5608.6  544.84  5644.9  544.76  5744.8  546.73
  5936.0  545.15  6116.4  546.30  6160.0  547.97  6170.3  547.60  6241.1  549.48
#Mann=7,-1,0
  4170.3    0.05       0  4874.6     0.1       0  4979.1    0.07       0
  5014.6     0.1       0  5078.5    0.05       0  5583.4     0.1       0
  6116.4    0.05       0
Bank Sta=4979.1,5014.6
Exp/Cntr=0.3,0.1

Type RM Length L Ch R = 1,18436,1155,1155,1155
BEGIN DESCRIPTION:
Buckhorn Creek 19.0
END DESCRIPTION:
XS GIS Cut Line= 2
      1974868.87     13505467.69      1974759.35     13503382.26
#Sta/Elev= 30
  3762.0  533.84  3965.0  532.63  4045.1  530.95  4065.1  531.66  4095.1  530.24
  4175.3  529.51  4245.4  527.15  4365.5  530.46  4475.7  530.33  4716.0  531.98
  4824.7  531.53  4906.3  531.80  4923.6  530.11  4966.3  526.81  4976.4  525.06
  4978.4  522.11  4979.2  521.61  5014.4  522.11  5016.4  526.12  5040.5  526.92
  5106.5  528.11  5166.6  531.88  5216.7  536.28  5396.9  538.30  5447.0  542.82
  5459.3  542.96  5507.1  546.83  5557.2  547.40  5727.4  556.67  5850.3  559.45
#Mann=6,-1,0
  3762.0    0.05       0  4824.7    0.07       0  4923.6    0.16       0
  4978.4    0.07       0  5014.4    0.16       0  5040.5     0.1       0
Bank Sta=4978.4,5014.4
Exp/Cntr=0.3,0.1

Type RM Length L Ch R = 1,17281,947,947,947
BEGIN DESCRIPTION:
Buckhorn Creek 18.0
END DESCRIPTION:
XS GIS Cut Line= 3
      1975387.01     13505392.52      1975475.00     13504475.00
      1975478.10     13503601.04
#Sta/Elev= 30
  4073.2  533.10  4161.1  533.56  4310.4  530.63  4418.0  527.71  4520.6  526.14
  4691.1  528.06  4707.6  527.79  4784.0  527.24  4884.4  528.33  4943.9  526.97
  4984.9  522.91  4986.9  519.66  4987.7  519.16  5022.1  519.16  5023.0  519.66
  5024.9  525.61  5059.6  526.73  5094.9  527.88  5134.9  530.91  5164.9  535.82
  5234.9  544.49  5286.0  552.35  5293.3  553.30  5334.9  560.31  5354.9  562.99
  5384.9  565.33  5494.9  568.35  5524.9  568.21  5624.9  572.16  5868.9  574.81
#Mann=9,-1,0
  4073.2    0.05       0  4691.1     0.1       0  4707.6    0.05       0
  4943.9    0.07       0  4986.9    0.07       0  5023.0    0.07       0
  5059.6     0.1       0  5286.0    0.16       0  5293.3     0.1       0
Bank Sta=4986.9,5023
Exp/Cntr=0.3,0.1

Type RM Length L Ch R = 1,16334,960,960,960
BEGIN DESCRIPTION:
Mapping XS 48affaa1
END DESCRIPTION:
XS GIS Cut Line= 3
      1976038.15     13505616.42      1976228.10     13505377.06
      1976181.23     13503559.64
#Sta/Elev= 30
  4164.9  529.97  4391.6  531.68  4582.6  531.38  4742.6  528.84  4815.7  526.45
  4922.7  524.89  4942.7  523.78  4972.7  524.17  4974.6  521.37  4975.5  520.87
  5010.8  521.37  5012.7  523.49  5042.7  522.82  5101.3  523.46  5152.8  523.76
  5202.8  525.04  5302.8  524.92  5342.8  526.04  5392.8  524.85  5412.8  526.09
  5462.9  527.21  5512.9  527.53  5642.9  531.41  5692.9  533.90  5773.0  535.22
  5793.0  536.54  6003.0  542.38  6163.1  548.25  6223.1  549.71  6288.5  552.65
#Mann=5,-1,0
  4164.9    0.05       0  4815.7     0.1       0  4974.6    0.07       0
  5010.8     0.1       0  5101.3     0.1       0
Bank Sta=4974.6,5010.8
Exp/Cntr=0.3,0.1

Type RM Length L Ch R = 1,15374,563,563,563
BEGIN DESCRIPTION:
Mapping XS 62ba9f58
END DESCRIPTION:
XS GIS Cut Line= 2
      1976082.29     13505788.50      1977540.29     13504023.27
#Sta/Elev= 30
  3755.2  527.52  3882.4  528.74  4079.4  530.56  4342.6  530.81  4448.1  531.65
  4505.4  529.10  4542.2  528.50  4562.8  528.43  4576.8  527.40  4612.3  527.58
  4739.9  521.40  4782.9  522.19  4853.3  521.94  4910.6  519.93  4939.3  521.54
  4960.1  521.71  4980.9  520.08  4985.0  517.49  4985.8  516.99  5021.3  517.49
  5023.9  519.94  5030.8  520.45  5122.9  524.77  5237.6  531.43  5279.3  534.84
  5322.3  536.32  5670.1  539.91  5954.1  543.76  5990.6  544.97  6044.7  545.14
#Mann=5,-1,0
  3755.2     0.1       0  3882.4    0.05       0  4542.2     0.1       0
  4985.0    0.07       0  5021.3     0.1       0
Bank Sta=4985,5021.3
Exp/Cntr=0.3,0.1

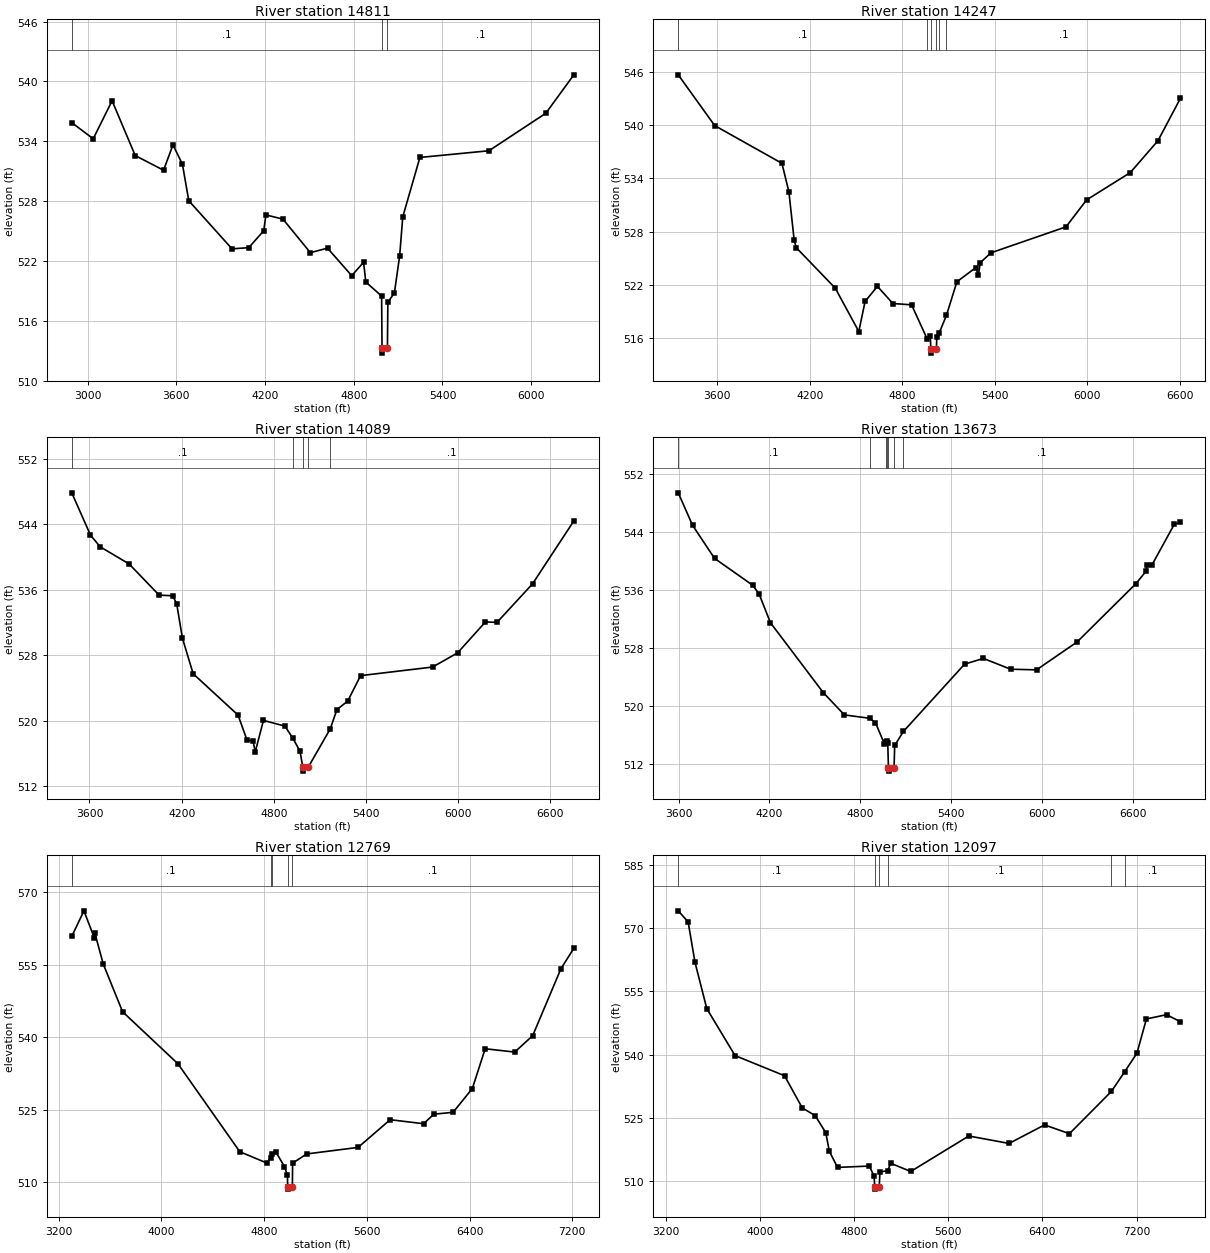
Type RM Length L Ch R = 1,14811,564,564,564
BEGIN DESCRIPTION:
Mapping XS ddd8b679
END DESCRIPTION:
XS GIS Cut Line= 4
      1975681.19     13506814.60      1976478.10     13506158.31
      1977629.14     13504522.90      1977863.55     13504246.82
#Sta/Elev= 30
  2893.6  535.87  3038.5  534.25  3166.2  538.06  3322.6  532.57  3514.1  531.10
  3577.9  533.64  3641.8  531.69  3684.8  528.04  3977.1  523.22  4090.4  523.34
  4191.4  525.04  4206.2  526.62  4321.3  526.20  4506.7  522.84  4622.6  523.29
  4786.4  520.53  4866.5  521.88  4881.3  519.90  4988.4  518.49  4991.2  513.27
  4992.1  512.77  5027.6  513.27  5030.6  517.87  5074.7  518.80  5110.4  522.52
  5131.3  526.42  5247.2  532.38  5714.0  533.05  6098.6  536.81  6288.0  540.66
#Mann=3,-1,0
  2893.6     0.1       0  4991.2    0.07       0  5027.6     0.1       0
Bank Sta=4991.2,5027.6
Exp/Cntr=0.3,0.1

Type RM Length L Ch R = 1,14247,158,158,158
BEGIN DESCRIPTION:
Mapping XS b41ef966
END DESCRIPTION:
XS GIS Cut Line= 5
      1976868.72     13507272.91      1977186.43     13506127.06
      1977176.02     13505871.86      1977420.81     13505679.15
      1978029.96     13504309.87
#Sta/Elev= 30
  3347.5  545.69  3584.0  539.96  4019.9  535.70  4065.0  532.46  4099.2  527.01
  4113.2  526.17  4365.1  521.62  4518.0  516.72  4558.7  520.11  4638.7  521.82
  4738.8  519.88  4860.2  519.73  4961.2  515.88  4981.6  516.21  4984.7  514.78
  4985.6  514.28  5021.1  514.78  5023.7  516.15  5039.2  516.56  5086.1  518.54
  5154.0  522.34  5275.7  523.92  5293.5  523.09  5305.1  524.48  5374.2  525.60
  5861.0  528.53  5994.6  531.57  6278.1  534.66  6457.2  538.25  6602.2  543.02
#Mann=6,-1,0
  3347.5     0.1       0  4961.2    0.12       0  4984.7    0.07       0
  5021.1    0.12       0  5039.2    0.07       0  5086.1     0.1       0
Bank Sta=4984.7,5021.1
Exp/Cntr=0.3,0.1

Type RM Length L Ch R = 1,14089,416,416,416
BEGIN DESCRIPTION:
Mapping XS 121e329d
END DESCRIPTION:
XS GIS Cut Line= 5
      1976910.40     13507293.71      1977196.85     13506444.77
      1977280.18     13505986.44      1977545.81     13505731.23
      1978108.11     13504299.45
#Sta/Elev= 30
  3484.8  547.83  3606.7  542.66  3669.7  541.24  3858.5  539.14  4053.3  535.34
  4141.7  535.26  4167.9  534.29  4204.7  530.11  4275.0  525.74  4567.3  520.69
  4625.8  517.63  4665.1  517.54  4679.1  516.19  4732.5  520.04  4872.2  519.35
  4924.9  517.84  4971.3  516.25  4988.3  514.35  4989.1  513.85  5024.7  514.35
  5167.1  519.00  5210.9  521.36  5280.9  522.40  5365.0  525.51  5834.0  526.56
  5996.5  528.29  6177.8  532.07  6253.0  532.01  6484.4  536.72  6753.2  544.40
#Mann=5,-1,0
  3484.8     0.1       0  4924.9    0.07       0  4988.3    0.07       0
  5024.7    0.07       0  5167.1     0.1       0
Bank Sta=4988.3,5024.7
Exp/Cntr=0.3,0.1

Type RM Length L Ch R = 1,13673,904,904,904
BEGIN DESCRIPTION:
Buckhorn Creek 13.0
END DESCRIPTION:
XS GIS Cut Line= 3
      1976962.46     13507361.46      1977712.48     13506064.56
      1978149.97     13504304.17
#Sta/Elev= 30
  3598.2  549.43  3692.7  544.95  3837.7  540.38  4088.9  536.68  4131.9  535.45
  4206.4  531.50  4555.4  521.84  4694.6  518.77  4860.0  518.31  4899.5  517.69
  4957.3  514.82  4971.8  515.08  4973.6  515.11  4980.3  514.92  4984.9  511.51
  4985.8  511.01  5022.0  511.51  5026.1  514.55  5083.7  516.49  5487.5  525.78
  5611.1  526.57  5791.2  525.08  5961.7  524.99  6229.4  528.84  6618.0  536.90
  6682.8  538.57  6693.1  539.53  6724.0  539.50  6871.2  545.11  6910.3  545.35
#Mann=7,-1,0
  3598.2     0.1       0  4860.0    0.07       0  4971.8     0.1       0
  4973.6    0.07       0  4984.9    0.07       0  5022.0    0.07       0
  5083.7     0.1       0
Bank Sta=4984.9,5022
Exp/Cntr=0.3,0.1

Type RM Length L Ch R = 1,12769,672,672,672
BEGIN DESCRIPTION:
Buckhorn Creek 12.0
END DESCRIPTION:
XS GIS Cut Line= 3
      1978285.39     13508189.55      1978425.00     13506475.00
      1978399.99     13504284.37
#Sta/Elev= 30
  3301.8  560.91  3396.7  566.19  3476.8  560.63  3481.9  561.55  3547.2  555.17
  3697.7  545.31  4129.1  534.54  4610.7  516.36  4821.4  514.02  4850.1  515.07
  4862.8  515.80  4891.6  516.31  4958.6  513.29  4981.9  511.48  4983.4  509.12
  4984.3  508.62  5020.5  509.12  5022.0  513.99  5132.0  515.90  5532.1  517.25
  5782.1  522.98  6042.1  522.15  6122.1  524.12  6272.1  524.51  6422.1  529.43
  6522.1  537.66  6752.1  536.97  6892.1  540.36  7112.2  554.21  7212.8  558.44
#Mann=5,-1,0
  3301.8     0.1       0  4850.1    0.07       0  4862.8     0.1       0
  4983.4    0.07       0  5020.5     0.1       0
Bank Sta=4983.4,5020.5
Exp/Cntr=0.3,0.1

Type RM Length L Ch R = 1,12097,252,252,252
BEGIN DESCRIPTION:
Buckhorn Creek 11.0
END DESCRIPTION:
XS GIS Cut Line= 3
      1978957.27     13508387.43      1979014.56     13506699.98
      1978733.45     13504138.79
#Sta/Elev= 30
  3306.1  574.19  3390.1  571.55  3448.6  561.92  3548.7  550.92  3788.8  539.75
  4209.1  534.96  4359.1  527.33  4469.2  525.46  4559.3  521.43  4589.3  517.01
  4659.3  513.15  4929.5  513.47  4969.5  511.08  4975.8  508.48  4976.8  507.98
  5013.2  508.48  5019.7  512.10  5085.5  512.35  5110.2  514.14  5281.2  512.18
  5774.4  520.62  6116.2  518.85  6418.0  523.26  6629.3  521.17  6985.8  531.23
  7097.9  535.88  7202.7  540.33  7283.2  548.47  7454.2  549.48  7571.1  547.81
#Mann=6,-1,0
  3306.1     0.1       0  4975.8    0.07       0  5013.2     0.1       0
  5085.5     0.1       0  6985.8    0.05       0  7097.9     0.1       0
Bank Sta=4975.8,5013.2
Exp/Cntr=0.3,0.1

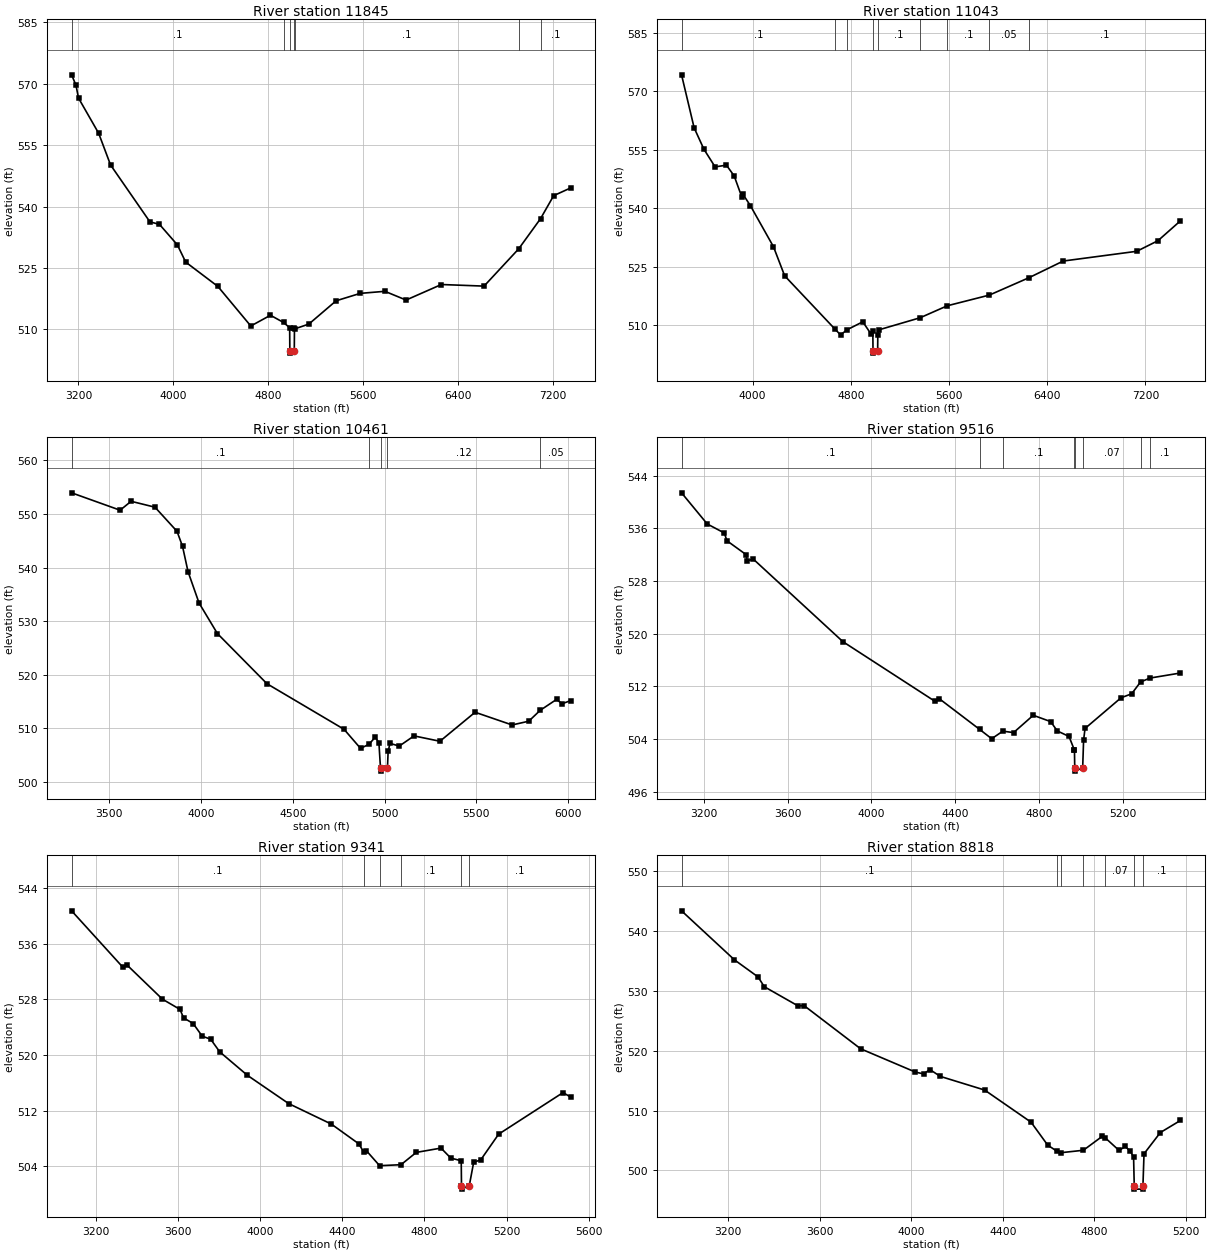
Type RM Length L Ch R = 1,11845,802,802,802
BEGIN DESCRIPTION:
Buckhorn Creek 10.0
END DESCRIPTION:
XS GIS Cut Line= 3
      1979144.77     13508491.62      1979292.34     13506963.87
      1978899.83     13504324.45
#Sta/Elev= 30
  3142.3  572.13  3179.1  569.58  3200.4  566.46  3370.0  557.88  3470.4  550.14
  3802.0  536.26  3882.3  535.65  4033.4  530.64  4103.4  526.44  4374.6  520.50
  4651.9  510.85  4817.6  513.47  4927.6  511.71  4979.3  510.43  4980.8  504.73
  4981.8  504.23  5018.2  504.73  5019.8  510.34  5027.8  510.20  5141.1  511.32
  5370.7  517.00  5573.8  518.81  5781.9  519.31  5960.0  517.18  6257.5  520.97
  6617.1  520.58  6908.5  529.66  7093.2  537.05  7203.5  542.65  7345.6  544.52
#Mann=7,-1,0
  3142.3     0.1       0  4927.6    0.12       0  4980.8    0.07       0
  5018.2    0.12       0  5027.8     0.1       0  6908.5    0.05       0
  7093.2     0.1       0
Bank Sta=4980.8,5018.2
Exp/Cntr=0.3,0.1

Type RM Length L Ch R = 1,11043,582,582,582
BEGIN DESCRIPTION:
Buckhorn Creek 9.0
END DESCRIPTION:
XS GIS Cut Line= 3
      1980225.00     13508075.00      1979873.93     13505792.00
      1979570.11     13504064.55
#Sta/Elev= 30
  3421.2  574.20  3523.7  560.61  3603.3  555.12  3694.4  550.59  3786.8  551.03
  3850.0  548.26  3913.3  542.75  3918.3  543.71  3981.6  540.66  4169.9  530.11
  4261.0  522.65  4671.4  508.96  4716.2  507.51  4771.6  508.85  4897.4  510.85
  4965.7  507.67  4979.3  508.46  4980.7  503.32  4981.7  502.82  5018.4  503.32
  5019.8  507.54  5029.0  508.80  5364.2  511.89  5586.1  514.97  5928.6  517.71
  6252.1  522.18  6530.1  526.44  7129.2  528.94  7301.8  531.66  7485.0  536.76
#Mann=9,-1,0
  3421.2     0.1       0  4671.4    0.07       0  4771.6     0.1       0
  4980.7    0.07       0  5018.4     0.1       0  5364.2    0.05       0
  5586.1     0.1       0  5928.6    0.05       0  6252.1     0.1       0
Bank Sta=4980.7,5018.4
Exp/Cntr=0.3,0.1

Type RM Length L Ch R = 1,10461,945,945,945
BEGIN DESCRIPTION:
Buckhorn Creek 8.0
END DESCRIPTION:
XS GIS Cut Line= 3
      1980490.25     13508179.18      1980525.00     13506475.00
      1980655.17     13505469.32
#Sta/Elev= 30
  3295.0  553.94  3559.2  550.70  3619.2  552.36  3749.3  551.26  3869.3  546.76
  3899.3  543.97  3929.3  539.25  3989.3  533.40  4089.3  527.70  4359.4  518.34
  4779.5  509.84  4869.5  506.28  4915.5  507.05  4949.5  508.37  4969.5  507.33
  4978.2  502.54  4979.1  502.04  5015.9  502.54  5019.7  505.72  5029.8  507.22
  5080.2  506.71  5160.9  508.61  5302.0  507.61  5493.6  513.02  5695.3  510.65
  5786.0  511.35  5847.9  513.37  5937.3  515.41  5967.5  514.60  6013.6  515.19
#Mann=5,-1,0
  3295.0     0.1       0  4915.5    0.12       0  4978.2    0.07       0
  5015.9    0.12       0  5847.9    0.05       0
Bank Sta=4978.2,5015.9
Exp/Cntr=0.3,0.1

Type RM Length L Ch R = 1,9516,175,175,175
BEGIN DESCRIPTION:
Buckhorn Creek 7.0
END DESCRIPTION:
XS GIS Cut Line= 3
      1980820.13     13508052.37      1981346.16     13506307.62
      1981427.76     13505754.42
#Sta/Elev= 30
  3093.7  541.38  3216.3  536.65  3297.9  535.28  3310.3  534.10  3402.1  531.99
  3407.3  531.03  3435.0  531.35  3863.8  518.78  4301.5  509.76  4323.4  510.13
  4516.4  505.46  4574.1  504.04  4627.3  505.19  4678.5  504.97  4772.5  507.60
  4855.5  506.64  4887.4  505.22  4943.1  504.39  4968.3  502.37  4969.2  502.28
  4970.5  499.62  4971.5  499.12  5008.4  499.62  5012.8  503.83  5019.7  505.60
  5191.6  510.26  5242.1  510.86  5284.5  512.65  5329.2  513.25  5475.2  514.02
#Mann=8,-1,0
  3093.7     0.1       0  4516.4    0.07       0  4627.3     0.1       0
  4968.3    0.07       0  4970.5    0.07       0  5008.4    0.07       0
  5284.5    0.05       0  5329.2     0.1       0
Bank Sta=4970.5,5008.4
Exp/Cntr=0.3,0.1

Type RM Length L Ch R = 1,9341,523,523,523
BEGIN DESCRIPTION:
Buckhorn Creek 6.0
END DESCRIPTION:
XS GIS Cut Line= 3
      1980867.00     13508088.83      1981481.57     13506458.66
      1981587.65     13505778.96
#Sta/Elev= 30
  3081.6  540.72  3331.5  532.60  3352.9  532.89  3523.9  528.02  3609.4  526.55
  3627.0  525.33  3673.5  524.52  3717.7  522.70  3759.0  522.26  3802.9  520.45
  3937.9  517.07  4138.7  513.01  4346.8  510.06  4479.7  507.24  4504.6  506.05
  4517.8  506.22  4581.7  504.08  4685.9  504.22  4760.4  505.99  4880.8  506.61
  4928.7  505.17  4979.3  504.79  4980.6  501.21  4981.6  500.71  5018.5  501.21
  5040.0  504.58  5074.2  504.91  5161.5  508.61  5475.2  514.59  5511.7  513.95
#Mann=6,-1,0
  3081.6     0.1       0  4504.6    0.07       0  4581.7    0.12       0
  4685.9     0.1       0  4980.6    0.07       0  5018.5     0.1       0
Bank Sta=4980.6,5018.5
Exp/Cntr=0.3,0.1

Type RM Length L Ch R = 1,8818,486,486,486
BEGIN DESCRIPTION:
Buckhorn Creek 5.0
END DESCRIPTION:
XS GIS Cut Line= 3
      1980866.99     13508177.40      1982008.98     13506393.43
      1982043.36     13506341.34
#Sta/Elev= 30
  2996.2  543.36  3227.5  535.17  3330.6  532.32  3357.7  530.69  3503.1  527.53
  3533.4  527.48  3778.8  520.32  4018.1  516.43  4054.4  516.12  4081.5  516.85
  4127.0  515.71  4320.8  513.43  4523.8  508.06  4596.5  504.23  4637.6  503.19
  4655.5  502.97  4752.4  503.37  4835.8  505.72  4847.3  505.47  4908.5  503.34
  4935.6  504.00  4958.2  503.18  4971.9  502.22  4974.8  497.38  4975.8  496.88
  5011.8  496.88  5012.7  497.38  5017.5  502.78  5088.8  506.33  5176.8  508.35
#Mann=7,-1,0
  2996.2     0.1       0  4637.6    0.07       0  4655.5     0.1       0
  4752.4    0.12       0  4847.3    0.07       0  4974.8    0.07       0
  5012.7     0.1       0
Bank Sta=4974.8,5012.7
Exp/Cntr=0.3,0.1