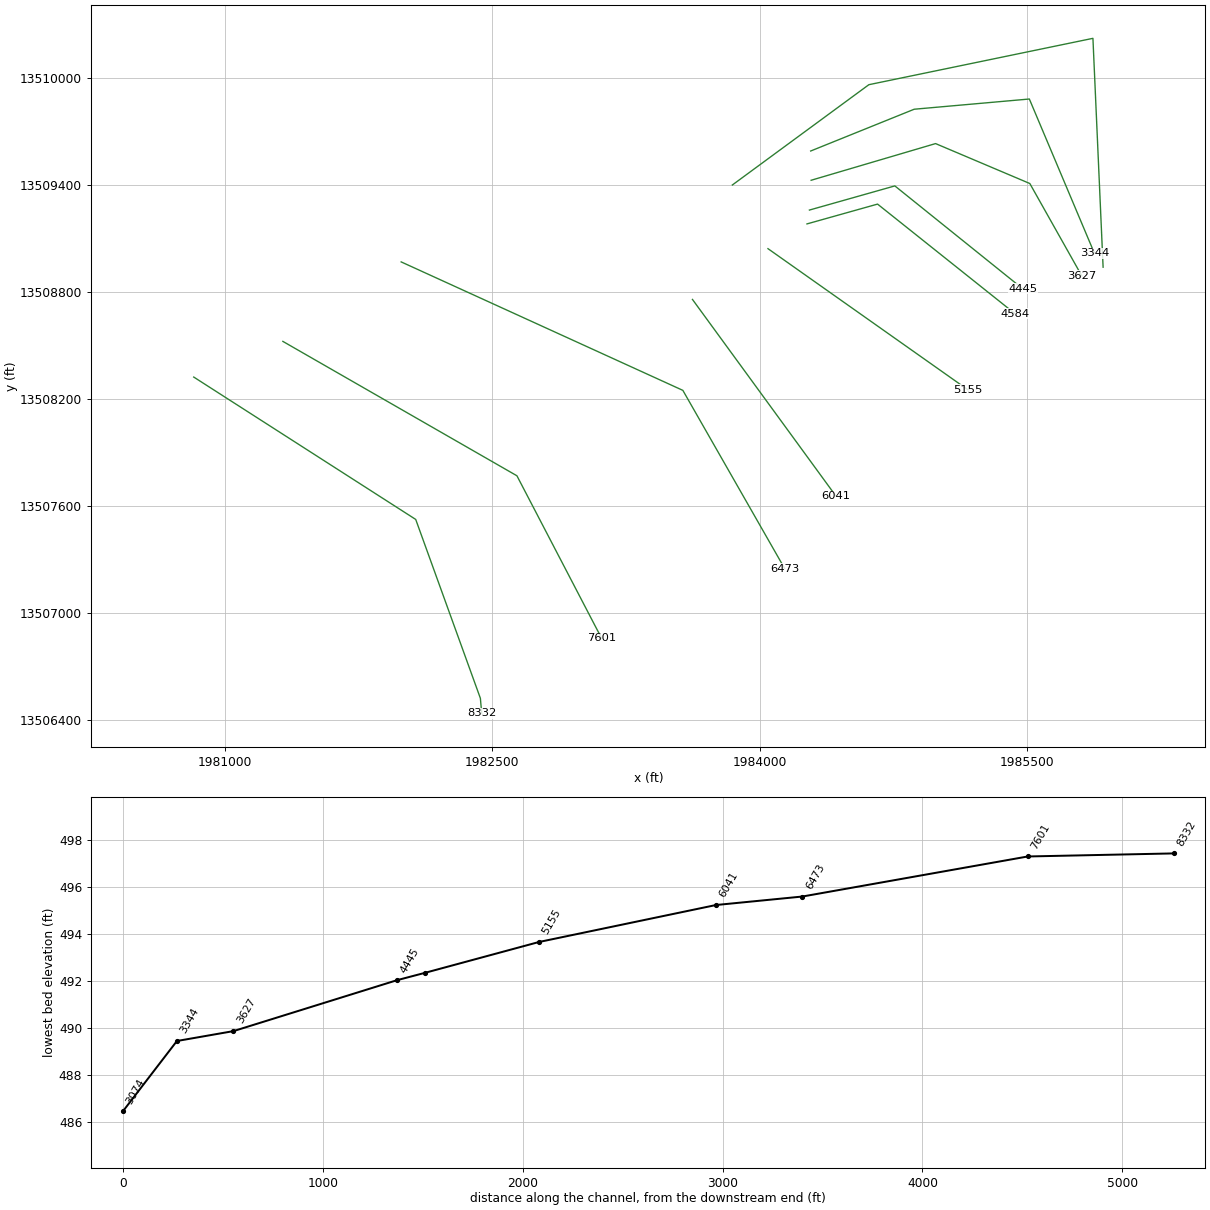
HEC-RAS study Buckhorn Creek.prj: Buckhorn Creek Base Level Engineering

--- Buckhorn Creek.g01 (geometry) --- (continued)

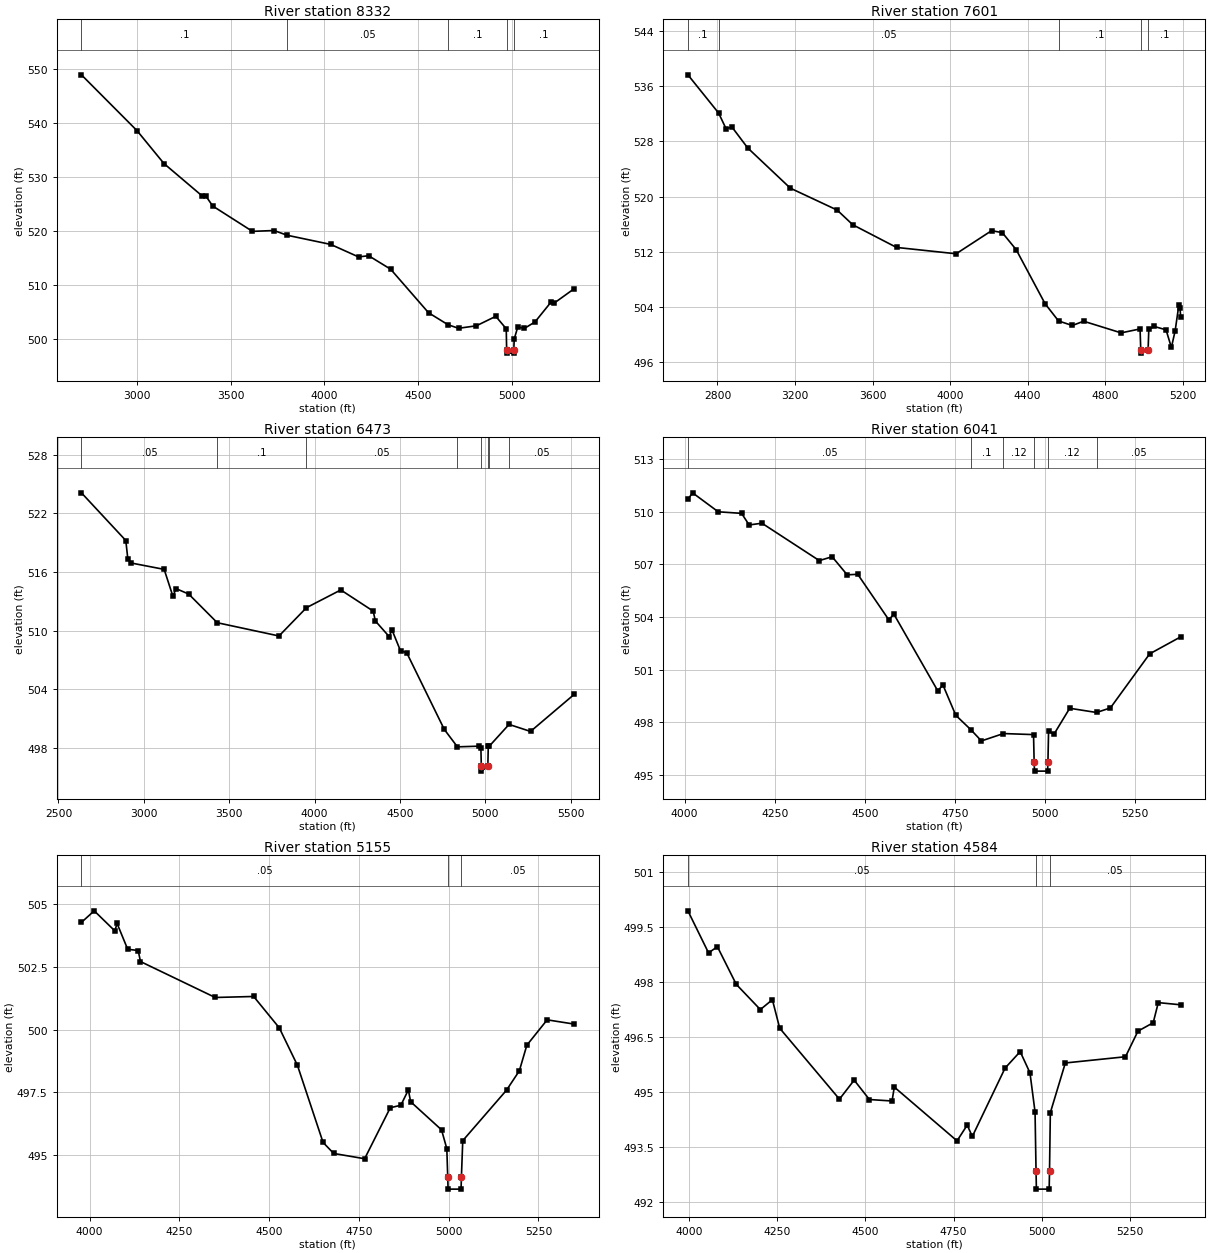
Type RM Length L Ch R = 1,8332,731,731,731
BEGIN DESCRIPTION:
Buckhorn Creek 4.0
END DESCRIPTION:
XS GIS Cut Line= 4
      1980824.98     13508325.01      1982070.11     13507526.37
      1982432.78     13506523.19      1982440.27     13506438.59
#Sta/Elev= 30
  2703.1  548.84  3000.1  538.51  3143.5  532.45  3346.4  526.49  3368.4  526.38
  3404.1  524.59  3616.0  519.91  3730.9  520.07  3801.6  519.19  4033.7  517.50
  4182.3  515.19  4236.2  515.41  4353.6  512.92  4556.0  504.87  4660.2  502.65
  4716.1  502.00  4811.2  502.46  4914.8  504.21  4970.7  501.91  4972.9  497.91
  4973.9  497.41  5009.9  497.41  5010.9  497.91  5013.2  500.01  5032.1  502.23
  5068.1  501.99  5124.1  503.17  5210.7  506.88  5225.9  506.64  5334.0  509.33
#Mann=5,-1,0
  2703.1     0.1       0  3801.6    0.05       0  4660.2     0.1       0
  4972.9    0.07       0  5010.9     0.1       0
Bank Sta=4972.9,5010.9
Exp/Cntr=0.3,0.1

Type RM Length L Ch R = 1,7601,1128,1128,1128
BEGIN DESCRIPTION:
Buckhorn Creek 3.0
END DESCRIPTION:
XS GIS Cut Line= 4
      1981324.97     13508525.02      1982637.82     13507771.16
      1983080.22     13506921.90      1983113.61     13506858.99
#Sta/Elev= 30
  2647.5  537.67  2805.8  532.13  2843.8  529.88  2875.4  530.07  2956.0  527.06
  3176.0  521.22  3417.5  518.04  3498.1  515.91  3723.8  512.62  4031.3  511.70
  4214.2  515.05  4269.3  514.77  4341.2  512.29  4490.2  504.45  4559.6  501.95
  4630.6  501.29  4689.1  501.91  4882.4  500.22  4980.2  500.79  4983.7  497.78
  4984.7  497.28  5021.7  497.78  5025.3  500.74  5053.5  501.15  5114.2  500.66
  5141.8  498.10  5161.2  500.52  5180.1  504.22  5185.8  503.87  5190.2  502.47
#Mann=5,-1,0
  2647.5     0.1       0  2805.8    0.05       0  4559.6     0.1       0
  4983.7    0.07       0  5021.7     0.1       0
Bank Sta=4983.7,5021.7
Exp/Cntr=0.3,0.1

Type RM Length L Ch R = 1,6473,432,432,432
BEGIN DESCRIPTION:
Buckhorn Creek 2.0
END DESCRIPTION:
XS GIS Cut Line= 3
      1981988.52     13508970.81      1983568.38     13508250.33
      1984139.34     13507251.15
#Sta/Elev= 30
  2634.6  524.12  2894.5  519.23  2906.3  517.35  2923.9  516.93  3119.2  516.27
  3170.8  513.49  3188.3  514.30  3262.9  513.74  3430.2  510.80  3791.8  509.44
  3952.7  512.34  4153.9  514.16  4343.7  511.99  4356.3  510.98  4437.6  509.37
  4453.4  510.08  4503.8  507.91  4539.8  507.73  4760.1  499.86  4837.1  498.07
  4964.5  498.14  4974.6  497.92  4977.1  496.08  4978.1  495.58  5015.3  496.08
  5017.8  498.14  5024.8  498.16  5139.5  500.37  5265.4  499.65  5521.8  503.46
#Mann=8,-1,0
  2634.6    0.05       0  3430.2     0.1       0  3952.7    0.05       0
  4837.1    0.07       0  4977.1    0.07       0  5015.3    0.07       0
  5024.8     0.1       0  5139.5    0.05       0
Bank Sta=4977.1,5015.3
Exp/Cntr=0.3,0.1

Type RM Length L Ch R = 1,6041,886,886,886
BEGIN DESCRIPTION:
Mapping XS 45f7dd33
END DESCRIPTION:
XS GIS Cut Line= 2
      1983622.25     13508760.37      1984427.81     13507656.19
#Sta/Elev= 30
  4009.2  510.70  4022.2  511.07  4093.3  509.99  4158.1  509.90  4179.0  509.24
  4214.5  509.34  4373.6  507.21  4409.2  507.43  4450.9  506.40  4480.2  506.43
  4566.0  503.85  4580.7  504.15  4701.9  499.80  4716.6  500.12  4752.1  498.40
  4793.8  497.58  4823.2  496.94  4884.2  497.36  4967.7  497.30  4969.4  495.72
  4970.4  495.22  5006.6  495.22  5007.6  495.72  5009.4  497.50  5024.0  497.31
  5068.0  498.80  5142.4  498.56  5180.9  498.82  5289.8  501.90  5376.0  502.87
#Mann=6,-1,0
  4009.2    0.05       0  4793.8     0.1       0  4884.2    0.12       0
  4969.4    0.07       0  5007.6    0.12       0  5142.4    0.05       0
Bank Sta=4969.4,5007.6
Exp/Cntr=0.3,0.1

Type RM Length L Ch R = 1,5155,571,571,571
BEGIN DESCRIPTION:
Mapping XS 9154333d
END DESCRIPTION:
XS GIS Cut Line= 2
      1984045.89     13509045.05      1985167.42     13508253.38
#Sta/Elev= 30
  3977.2  504.27  4012.8  504.73  4070.3  503.93  4076.4  504.23  4106.0  503.20
  4135.2  503.15  4141.7  502.71  4349.8  501.28  4456.9  501.32  4528.3  500.07
  4578.8  498.58  4650.2  495.51  4679.8  495.07  4766.0  494.86  4837.4  496.89
  4866.9  496.99  4887.8  497.60  4894.1  497.13  4980.2  496.01  4994.9  495.26
  4997.4  494.15  4998.4  493.65  5034.6  493.65  5035.6  494.15  5039.3  495.58
  5161.2  497.59  5196.9  498.36  5217.8  499.38  5274.4  500.39  5350.0  500.22
#Mann=3,-1,0
  3977.2    0.05       0  4997.4    0.03       0  5035.6    0.05       0
Bank Sta=4997.4,5035.6
Exp/Cntr=0.3,0.1

Type RM Length L Ch R = 1,4584,139,139,139
BEGIN DESCRIPTION:
Mapping XS 9a6c0276
END DESCRIPTION:
XS GIS Cut Line= 3
      1984264.59     13509183.94      1984660.46     13509295.06
      1985430.66     13508680.99
#Sta/Elev= 30
  3997.6  499.95  4056.1  498.80  4081.1  498.97  4134.6  497.94  4202.8  497.25
  4236.9  497.52  4257.7  496.74  4426.9  494.80  4468.6  495.32  4511.8  494.79
  4575.9  494.75  4582.3  495.13  4760.0  493.66  4788.8  494.09  4803.3  493.78
  4896.1  495.65  4938.9  496.10  4966.6  495.52  4981.0  494.45  4983.8  492.84
  4984.8  492.34  5021.0  492.34  5022.0  492.84  5024.3  494.43  5066.8  495.79
  5237.2  495.96  5272.5  496.66  5315.7  496.89  5330.1  497.44  5393.8  497.38
#Mann=3,-1,0
  3997.6    0.05       0  4983.8    0.04       0  5022.0    0.05       0
Bank Sta=4983.8,5022
Exp/Cntr=0.3,0.1

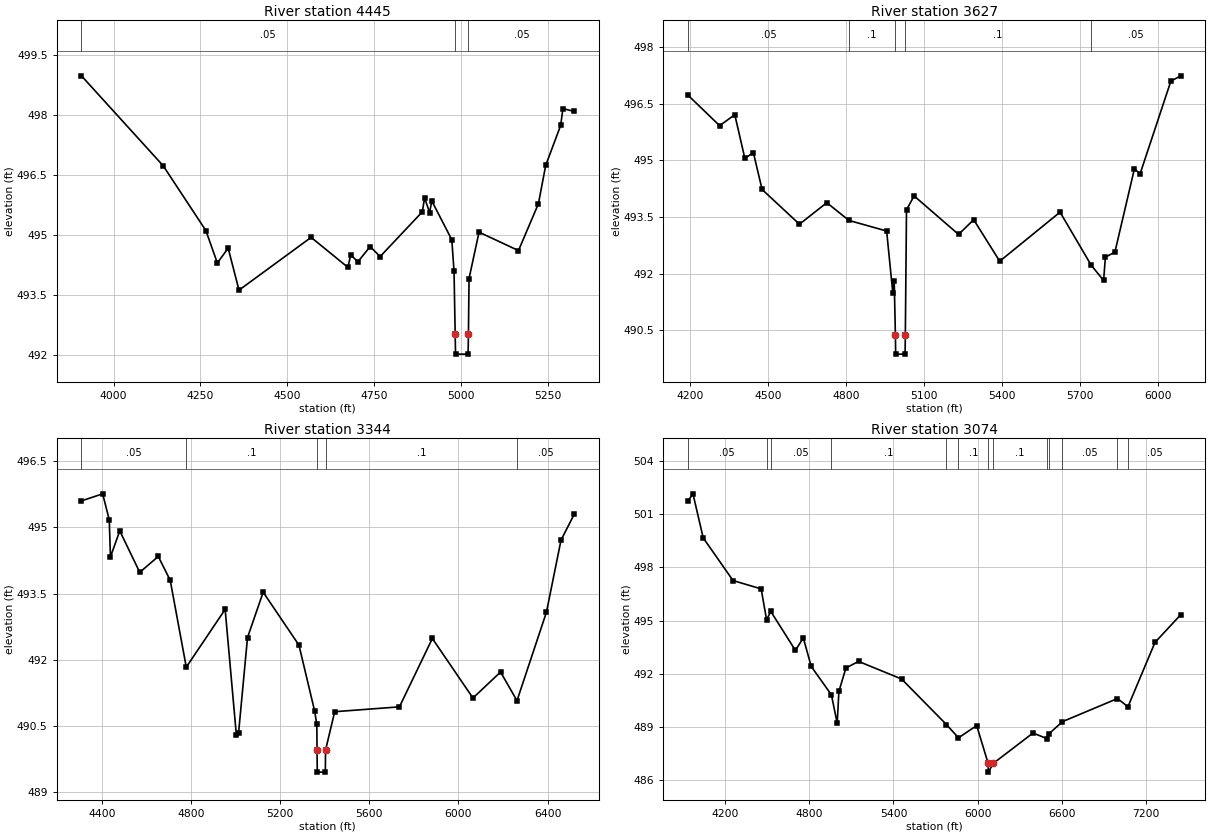
Type RM Length L Ch R = 1,4445,818,818,818
BEGIN DESCRIPTION:
Mapping XS 2c2a78fc
END DESCRIPTION:
XS GIS Cut Line= 3
      1984278.35     13509261.64      1984757.51     13509397.06
      1985475.61     13508819.46
#Sta/Elev= 30
  3907.6  498.99  4143.1  496.74  4266.0  495.12  4299.0  494.31  4330.2  494.68
  4361.4  493.63  4569.1  494.95  4675.1  494.20  4683.1  494.51  4703.9  494.34
  4739.1  494.72  4767.9  494.47  4889.5  495.59  4895.9  495.94  4910.3  495.57
  4916.7  495.86  4974.3  494.89  4980.7  494.10  4984.0  492.53  4985.0  492.03
  5021.2  492.03  5022.2  492.53  5023.9  493.92  5052.7  495.08  5166.3  494.62
  5223.7  495.79  5244.7  496.75  5287.8  497.75  5294.3  498.17  5327.1  498.10
#Mann=3,-1,0
  3907.6    0.05       0  4984.0    0.04       0  5022.2    0.05       0
Bank Sta=4984,5022.2
Exp/Cntr=0.3,0.1

Type RM Length L Ch R = 1,3627,283,283,283
BEGIN DESCRIPTION:
Mapping XS 80662030
END DESCRIPTION:
XS GIS Cut Line= 4
      1984287.94     13509428.73      1984985.85     13509634.46
      1985514.50     13509410.50      1985806.16     13508892.27
#Sta/Elev= 30
  4191.0  496.73  4313.0  495.92  4371.4  496.21  4409.9  495.06  4443.1  495.20
  4476.5  494.23  4620.2  493.31  4725.4  493.88  4810.8  493.41  4955.7  493.13
  4979.4  491.49  4984.8  491.81  4989.4  490.37  4990.4  489.87  5026.6  489.87
  5027.6  490.37  5032.1  493.69  5061.3  494.06  5232.4  493.04  5290.6  493.43
  5390.8  492.33  5622.9  493.63  5742.3  492.23  5790.5  491.82  5797.4  492.44
  5833.9  492.57  5909.1  494.78  5930.7  494.64  6049.3  497.10  6087.4  497.24
#Mann=5,-1,0
  4191.0    0.05       0  4810.8     0.1       0  4989.4    0.07       0
  5027.6     0.1       0  5742.3    0.05       0
Bank Sta=4989.4,5027.6
Exp/Cntr=0.3,0.1

Type RM Length L Ch R = 1,3344,270,270,270
BEGIN DESCRIPTION:
Mapping XS 4769280c
END DESCRIPTION:
XS GIS Cut Line= 4
      1984285.36     13509592.81      1984866.06     13509827.17
      1985511.89     13509884.46      1985876.44     13509019.96
#Sta/Elev= 30
  4307.3  495.60  4402.6  495.76  4432.2  495.17  4437.6  494.33  4479.4  494.92
  4569.1  493.98  4652.3  494.34  4705.9  493.80  4778.0  491.83  4952.5  493.14
  5002.7  490.30  5012.8  490.34  5052.9  492.50  5123.2  493.53  5283.8  492.33
  5354.1  490.84  5364.1  490.53  5365.1  489.95  5366.1  489.45  5402.3  489.45
  5403.3  489.95  5444.4  490.82  5735.0  490.93  5882.8  492.48  6065.1  491.13
  6189.0  491.72  6262.8  491.07  6395.2  493.08  6460.4  494.71  6520.1  495.30
#Mann=5,-1,0
  4307.3    0.05       0  4778.0     0.1       0  5365.1    0.07       0
  5403.3     0.1       0  6262.8    0.05       0
Bank Sta=5365.1,5403.3
Exp/Cntr=0.3,0.1

Type RM Length L Ch R = 1,3074,0,0,0
BEGIN DESCRIPTION:
Buckhorn Creek 1.0
END DESCRIPTION:
XS GIS Cut Line= 4
      1983846.03     13509402.25      1984611.68     13509964.76
      1985868.48     13510224.79      1985925.55     13508941.16
#Sta/Elev= 30
  3932.4  501.73  3968.5  502.13  4041.7  499.65  4254.7  497.25  4455.3  496.78
  4494.0  495.05  4524.3  495.51  4699.9  493.32  4756.3  494.02  4812.6  492.42
  4956.8  490.82  4998.2  489.22  5010.3  491.01  5060.5  492.33  5150.7  492.70
  5457.7  491.71  5777.6  489.15  5863.9  488.40  5994.0  489.09  6075.3  486.97
  6076.3  486.47  6113.5  486.97  6395.9  488.67  6494.0  488.36  6507.6  488.61
  6606.2  489.31  6998.8  490.61  7073.8  490.15  7266.8  493.77  7450.8  495.33
#Mann=13,-1,0
  3932.4    0.05       0  4494.0    0.08       0  4524.3    0.05       0
  4956.8     0.1       0  5777.6    0.05       0  5863.9     0.1       0
  6075.3    0.07       0  6113.5     0.1       0  6494.0    0.05       0
  6507.6     0.1       0  6606.2    0.05       0  6998.8     0.1       0
  7073.8    0.05       0
Bank Sta=6075.3,6113.5
Exp/Cntr=0.3,0.1

Chan Stop Cuts=-1