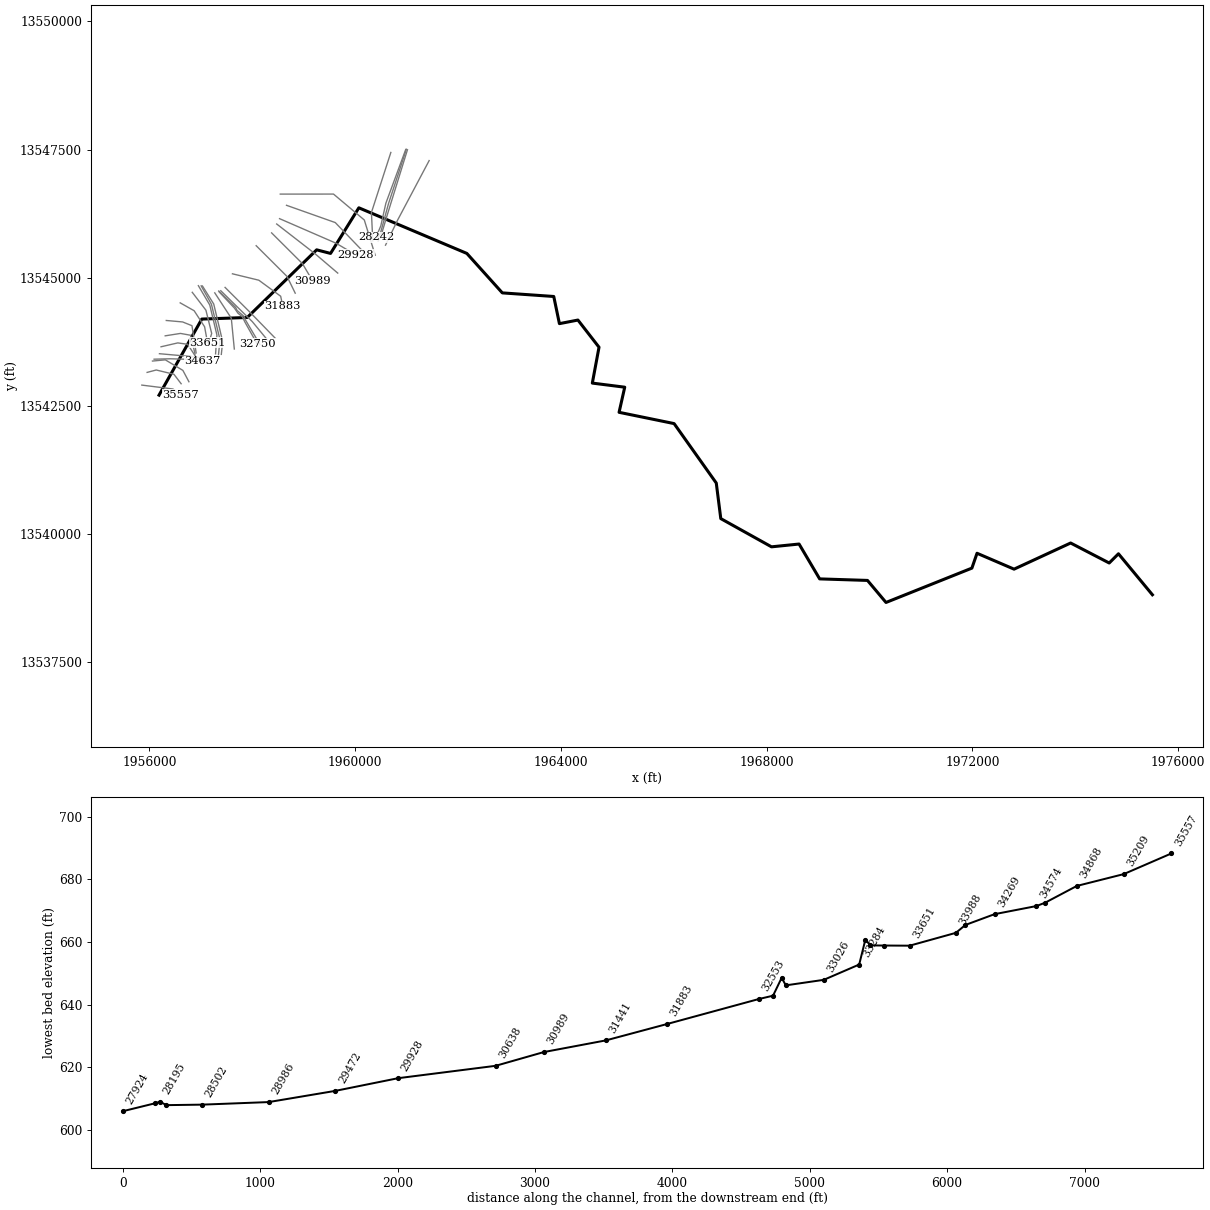
--- Horse Creek.prj (project) ---

Proj Title=Horse Creek Base Level Engineering
Current Plan=p01
Default Exp/Contr=0.3,0.1
English Units
Geom File=g01
Flow File=f01
Plan File=p01
Y Axis Title=Elevation
X Axis Title(PF)=Main Channel Distance
X Axis Title(XS)=Station
BEGIN DESCRIPTION:
Horse Creek
END DESCRIPTION:
DSS Export Rating Curves= 0
DSS Export Rating Curve Sorted= 0
DSS Export Volume Flow Curves= 0
DXF OffsetX= 0
DXF OffsetY= 0
DXF ScaleX= 1
DXF ScaleY= 10

--- Horse Creek.p01 (plan) ---

Plan Title=Multiple Run
Short Identifier=Multiple
Geom File=g01
Flow File=f01
Subcritical Flow
K Sum by GR= 0
Std Step Tol= 0.01
Critical Tol= 0.01
Num of Std Step Trials= 20
Max Error Tol= 0.3
Flow Tol Ratio= 0.001
Split Flow NTrial= 30
Split Flow Tol= 0.02
Split Flow Ratio= 0.02
Log Output Level= 0
Friction Slope Method= 1
Unsteady Friction Slope Method= 2
Unsteady Bridges Friction Slope Method= 1
Parabolic Critical Depth
Global Vel Dist=  1 , 1 , 1
Global Log Level= 0
CheckData=True
Encroach Param= -1, 0, 0, 0
BEGIN DESCRIPTION:
Multiple Run
END DESCRIPTION:

--- Horse Creek.f01 (steady flow) ---

Flow Title=Multiple
Program Version=5.05
Number of Profiles= 7
Profile Names=10-year,25-year,50-year,1pct_min,100-year,1pct_plu,500-year
River Rch & RM=Horse Creek,Reach-1         ,35557
     100     134     161      98     195     390     290
River Rch & RM=Horse Creek,Reach-1         ,28502
     708    1026    1300     816    1629    3249    2583
River Rch & RM=Horse Creek,Reach-1         ,23194
    1539    2299    2970    1894    3780    7541    6170
River Rch & RM=Horse Creek,Reach-1         ,21439
    1446    2156    2781    1773    3538    7059    5777
River Rch & RM=Horse Creek,Reach-1         ,19468
    1339    1990    2564    1635    3262    6509    5342
River Rch & RM=Horse Creek,Reach-1         ,17636
    1339    1990    2564    1635    3262    6509    5342
River Rch & RM=Horse Creek,Reach-1         ,10196
    1304    1931    2481    1578    3149    6283    5132
Boundary for River Rch & Prof#=Horse Creek,Reach-1         , 1
Up Type= 0
Dn Type= 3
Dn Slope=0.0021
Boundary for River Rch & Prof#=Horse Creek,Reach-1         , 2
Up Type= 0
Dn Type= 3
Dn Slope=0.0021
Boundary for River Rch & Prof#=Horse Creek,Reach-1         , 3
Up Type= 0
Dn Type= 3
Dn Slope=0.0021
Boundary for River Rch & Prof#=Horse Creek,Reach-1         , 4
Up Type= 0
Dn Type= 3
Dn Slope=0.0021
Boundary for River Rch & Prof#=Horse Creek,Reach-1         , 5
Up Type= 0
Dn Type= 3
Dn Slope=0.0021
Boundary for River Rch & Prof#=Horse Creek,Reach-1         , 6
Up Type= 0
Dn Type= 3
Dn Slope=0.0021
Boundary for River Rch & Prof#=Horse Creek,Reach-1         , 7
Up Type= 0
Dn Type= 3
Dn Slope=0.0021
DSS Import GetInterval= 0
DSS Import GetPeak= 0
DSS Import FillOption= 0

--- Horse Creek.g01 (geometry) ---

Geom Title=Existing Conditions

River Reach=Horse Creek,Reach-1
Reach XY= 30
      1956185.80     13542709.54      1957017.26     13544193.67
      1957900.80     13544224.54      1959250.80     13545544.54
      1959520.80     13545474.54      1960070.80     13546364.54
      1962170.80     13545474.54      1962860.80     13544704.54
      1963860.80     13544634.54      1963970.80     13544104.54
      1964330.80     13544174.54      1964740.80     13543644.54
      1964610.80     13542944.54      1965240.80     13542864.54
      1965130.80     13542374.54      1966200.80     13542154.54
      1967020.80     13540994.54      1967108.47     13540300.72
      1968094.58     13539750.03      1968630.80     13539804.54
      1969030.80     13539124.54      1969960.80     13539094.54
      1970320.80     13538664.54      1971990.80     13539334.54
      1972090.80     13539624.54      1972810.80     13539314.54
      1973910.80     13539824.54      1974660.80     13539434.54
      1974840.80     13539614.54      1975500.80     13538814.54

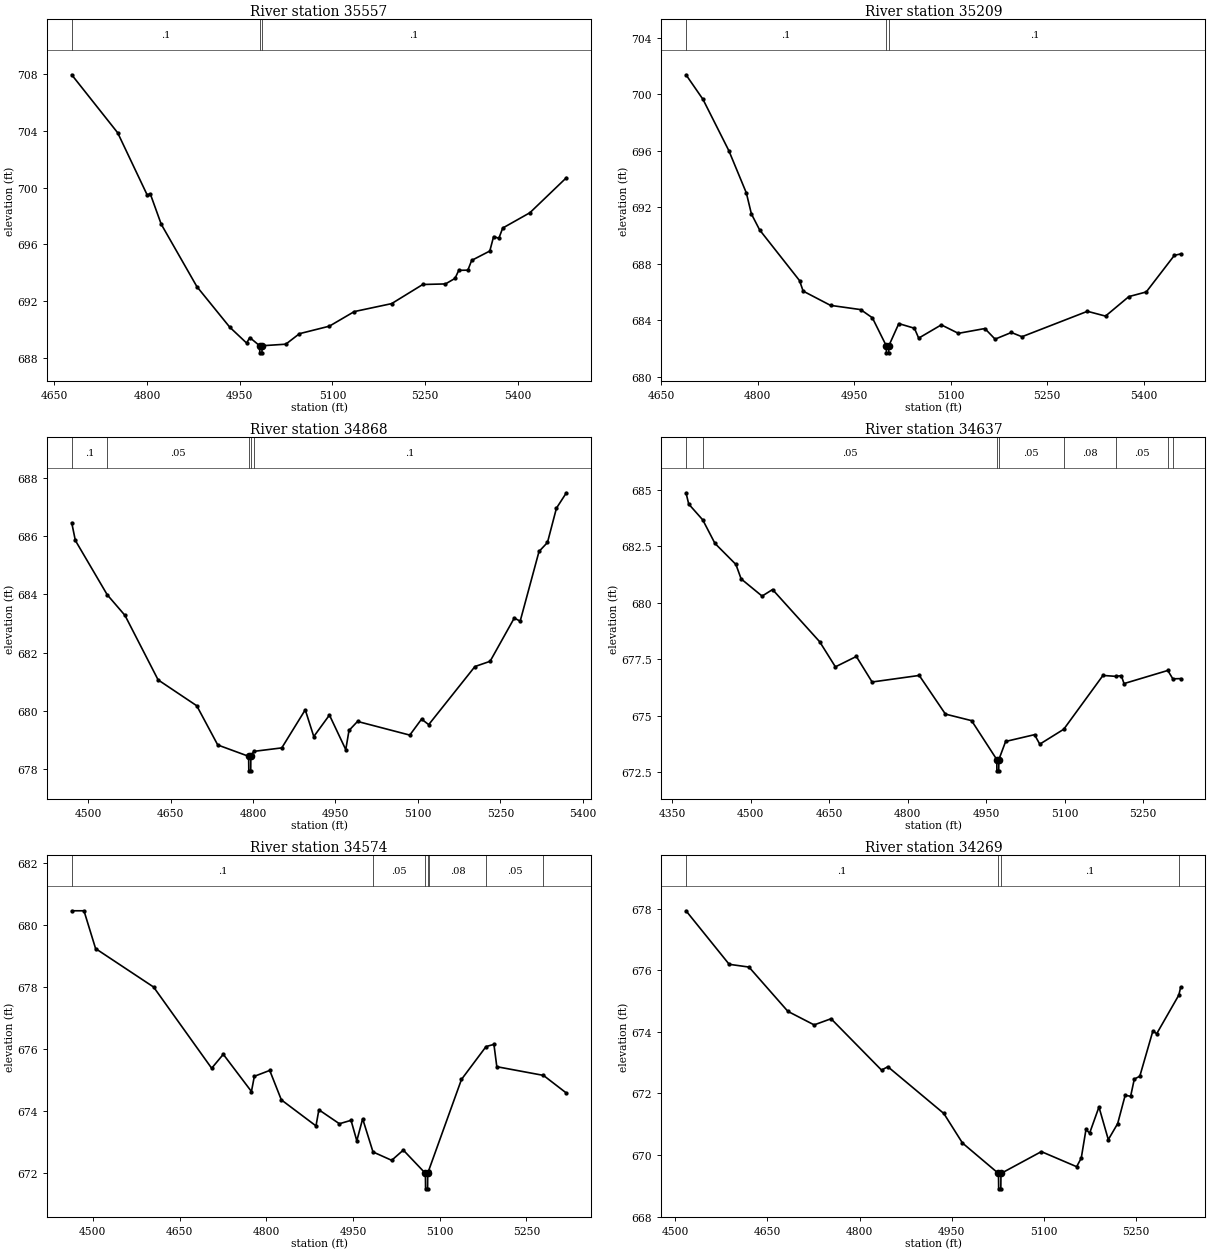
Type RM Length L Ch R = 1,35557,348,348,348
BEGIN DESCRIPTION:
Horse Creek 36.0
END DESCRIPTION:
XS GIS Cut Line= 3
      1955851.20     13542905.51      1956456.64     13542829.55
      1956610.34     13542716.99
#Sta/Elev= 30
  4677.9  707.95  4752.3  703.86  4800.0  699.48  4805.1  699.55  4822.8  697.41
  4880.5  693.01  4933.7  690.15  4961.0  689.03  4966.1  689.42  4982.1  688.84
  4982.3  688.34  4985.8  688.34  4986.1  688.84  5024.4  688.95  5046.5  689.69
  5094.9  690.22  5135.3  691.25  5195.7  691.81  5246.1  693.16  5282.9  693.20
  5298.3  693.59  5304.4  694.16  5319.1  694.17  5325.3  694.86  5354.6  695.52
  5360.8  696.54  5369.3  696.42  5375.5  697.14  5419.5  698.22  5478.6  700.69
#Mann=3,-1,0
  4677.9     0.1       0  4982.1    0.07       0  4986.1     0.1       0
Bank Sta=4982.1,4986.1
Exp/Cntr=0.3,0.1

Type RM Length L Ch R = 1,35209,341,341,341
BEGIN DESCRIPTION:
Mapping XS 868b6979
END DESCRIPTION:
XS GIS Cut Line= 4
      1955954.32     13543153.30      1956131.43     13543200.19
      1956475.18     13543116.85      1956615.80     13542931.98
#Sta/Elev= 30
  4688.4  701.39  4714.8  699.65  4755.0  696.02  4782.2  693.03  4790.1  691.54
  4802.9  690.41  4865.0  686.82  4870.5  686.08  4913.1  685.07  4960.0  684.77
  4978.2  684.19  4999.8  682.21  5000.1  681.71  5003.6  681.71  5003.8  682.21
  5019.3  683.78  5043.6  683.45  5050.2  682.75  5085.4  683.69  5111.9  683.09
  5153.1  683.43  5169.0  682.68  5194.3  683.15  5210.8  682.85  5312.6  684.65
  5340.7  684.31  5377.0  685.69  5404.1  686.02  5447.8  688.61  5457.6  688.71
#Mann=3,-1,0
  4688.4     0.1       0  4999.8    0.07       0  5003.8     0.1       0
Bank Sta=4999.8,5003.8
Exp/Cntr=0.3,0.1

Type RM Length L Ch R = 1,34868,231,231,231
BEGIN DESCRIPTION:
Mapping XS cbc02a52
END DESCRIPTION:
XS GIS Cut Line= 4
      1956058.48     13543374.66      1956308.52     13543398.10
      1956649.66     13543192.38      1956766.86     13542971.00
#Sta/Elev= 30
  4470.1  686.47  4476.7  685.86  4534.7  683.99  4567.0  683.28  4627.3  681.06
  4697.6  680.17  4735.8  678.82  4792.0  678.43  4792.3  677.93  4795.8  677.93
  4796.0  678.43  4801.3  678.60  4852.3  678.72  4895.0  680.03  4910.5  679.11
  4939.0  679.85  4968.7  678.66  4974.6  679.32  4990.1  679.63  5085.2  679.16
  5106.6  679.71  5119.6  679.52  5203.7  681.52  5231.3  681.70  5275.3  683.19
  5286.0  683.08  5320.3  685.48  5335.7  685.79  5352.0  686.97  5370.1  687.50
#Mann=5,-1,0
  4470.1     0.1       0  4534.7    0.05       0  4792.0    0.07       0
  4796.0    0.05       0  4801.3     0.1       0
Bank Sta=4792,4796
Exp/Cntr=0.3,0.1

Type RM Length L Ch R = 1,34637,63,63,63
BEGIN DESCRIPTION:
Mapping XS 975f1454
END DESCRIPTION:
XS GIS Cut Line= 5
      1956089.76     13543411.13      1956404.87     13543418.94
      1956733.77     13543408.97      1956995.93     13543382.22
      1957031.82     13543373.55
#Sta/Elev= 30
  4376.8  684.86  4382.0  684.36  4408.8  683.66  4432.1  682.62  4472.1  681.69
  4482.1  681.05  4522.1  680.29  4542.1  680.58  4632.1  678.27  4662.1  677.16
  4702.1  677.62  4732.2  676.49  4822.2  676.78  4872.2  675.07  4922.2  674.78
  4970.3  673.06  4970.5  672.56  4974.0  672.56  4974.3  673.06  4987.2  673.86
  5042.4  674.16  5052.4  673.74  5098.2  674.40  5173.1  676.78  5197.4  676.74
  5208.1  676.77  5213.3  676.42  5296.9  677.00  5306.5  676.63  5321.5  676.64
#Mann=8,-1,0
  4376.8     0.1       0  4408.8    0.05       0  4970.3    0.04       0
  4974.3    0.05       0  5098.2    0.08       0  5197.4    0.05       0
  5296.9    0.08       0  5306.5     0.1       0
Bank Sta=4970.3,4974.3
Exp/Cntr=0.3,0.1

Type RM Length L Ch R = 1,34574,305,305,305
BEGIN DESCRIPTION:
Mapping XS 16589032
END DESCRIPTION:
XS GIS Cut Line= 3
      1956193.91     13543517.90      1956739.97     13543469.24
      1957045.44     13543436.90
#Sta/Elev= 30
  4463.6  680.47  4484.8  680.47  4504.9  679.25  4605.2  678.01  4705.6  675.39
  4725.7  675.84  4774.4  674.64  4779.4  675.13  4806.0  675.32  4826.1  674.37
  4886.0  673.53  4891.0  674.05  4926.5  673.60  4946.6  673.71  4956.6  673.05
  4966.7  673.76  4984.6  672.69  5016.9  672.42  5037.0  672.75  5075.2  672.00
  5075.5  671.50  5079.0  671.50  5079.2  672.00  5080.9  672.09  5137.6  675.03
  5180.1  676.09  5193.7  676.16  5198.7  675.44  5279.3  675.16  5319.0  674.59
#Mann=7,-1,0
  4463.6     0.1       0  4984.6    0.05       0  5075.2    0.04       0
  5079.2    0.05       0  5080.9    0.08       0  5180.1    0.05       0
  5279.3    0.08       0
Bank Sta=5075.2,5079.2
Exp/Cntr=0.3,0.1

Type RM Length L Ch R = 1,34269,212,212,212
BEGIN DESCRIPTION:
Mapping XS 957b21b0
END DESCRIPTION:
XS GIS Cut Line= 4
      1956225.21     13543653.32      1956550.70     13543728.83
      1956742.83     13543701.33      1956892.47     13543469.08
#Sta/Elev= 30
  4517.8  677.94  4588.0  676.20  4620.2  676.11  4683.5  674.67  4726.2  674.23
  4753.7  674.43  4835.8  672.76  4846.1  672.87  4937.1  671.35  4967.4  670.39
  5026.0  669.40  5026.3  668.90  5029.8  668.90  5030.0  669.40  5095.7  670.11
  5153.1  669.62  5160.6  669.90  5168.3  670.83  5174.2  670.71  5189.4  671.56
  5204.6  670.50  5219.8  671.02  5232.0  671.94  5240.9  671.91  5246.9  672.47
  5255.8  672.56  5277.2  674.04  5283.2  673.94  5319.3  675.20  5322.3  675.46
#Mann=4,-1,0
  4517.8     0.1       0  5026.0    0.07       0  5030.0     0.1       0
  5319.3    0.08       0
Bank Sta=5026,5030
Exp/Cntr=0.3,0.1

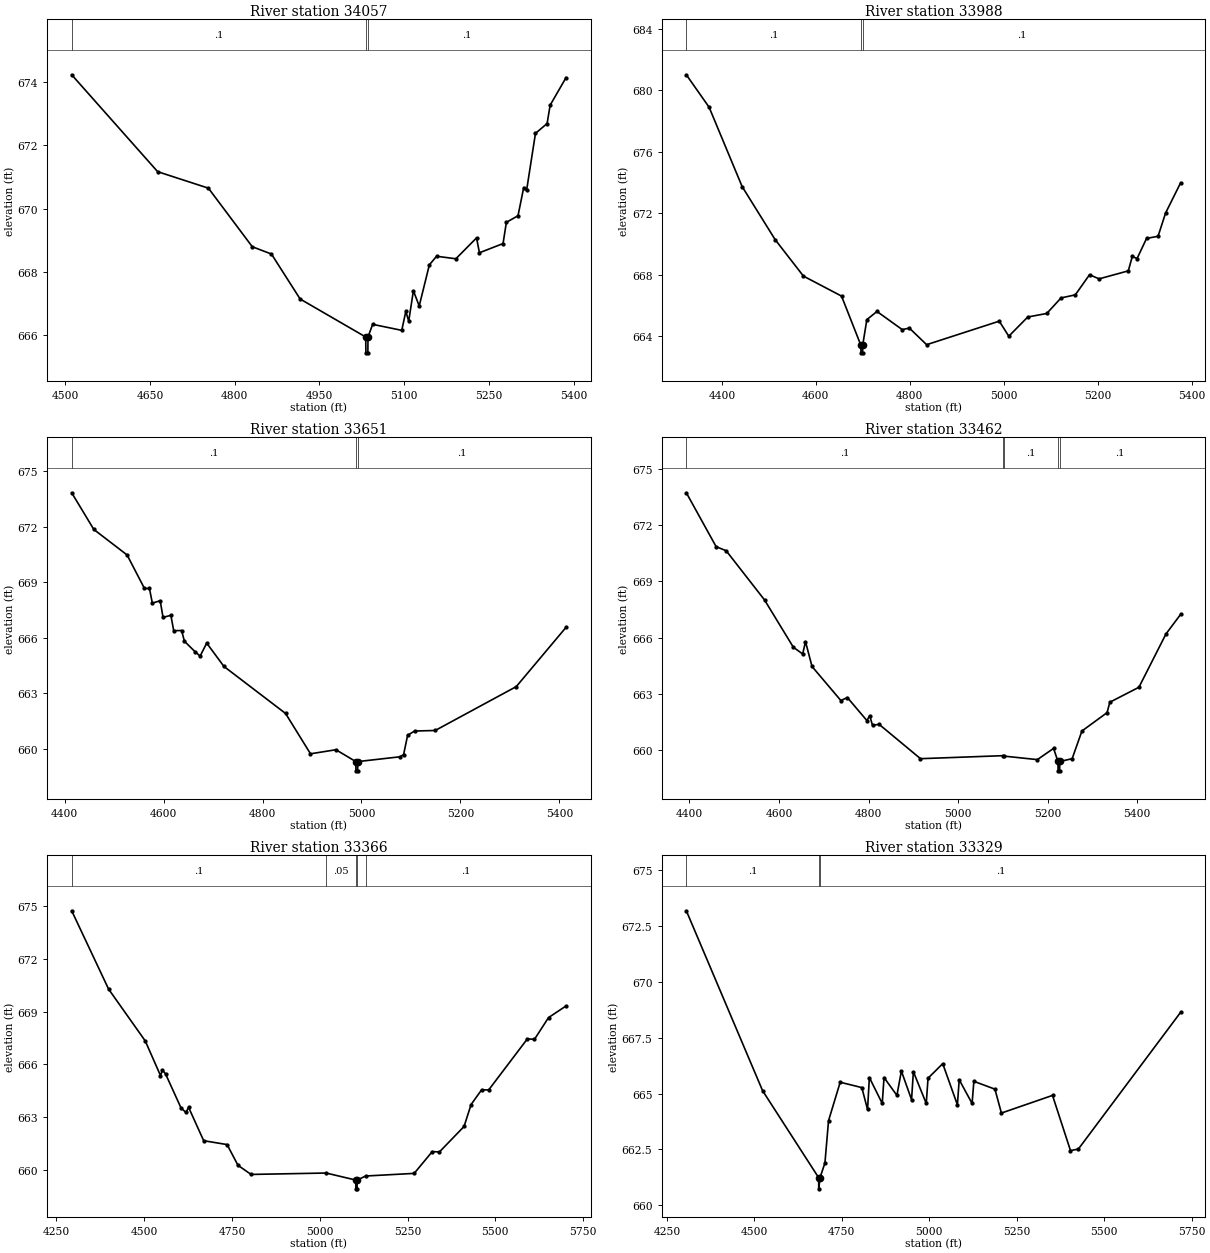
Type RM Length L Ch R = 1,34057,69,69,69
BEGIN DESCRIPTION:
Mapping XS b6ec9747
END DESCRIPTION:
XS GIS Cut Line= 4
      1956305.93     13543866.86      1956602.79     13543913.73
      1956797.52     13543878.41      1956886.56     13543512.43
#Sta/Elev= 30
  4511.4  674.23  4663.6  671.17  4753.4  670.65  4831.1  668.80  4865.0  668.57
  4915.8  667.15  5031.9  665.95  5032.2  665.45  5035.7  665.45  5035.9  665.95
  5044.2  666.35  5095.7  666.16  5102.9  666.76  5108.0  666.45  5116.3  667.41
  5126.6  666.93  5144.6  668.23  5157.4  668.50  5191.5  668.42  5228.1  669.08
  5233.2  668.61  5275.0  668.90  5280.9  669.57  5301.5  669.78  5311.6  670.67
  5316.7  670.58  5332.4  672.38  5353.0  672.69  5358.4  673.27  5386.5  674.14
#Mann=3,-1,0
  4511.4     0.1       0  5031.9    0.07       0  5035.9     0.1       0
Bank Sta=5031.9,5035.9
Exp/Cntr=0.3,0.1

Type RM Length L Ch R = 1,33988,337,337,337
BEGIN DESCRIPTION:
Mapping XS 16d5d0cf
END DESCRIPTION:
XS GIS Cut Line= 4
      1956326.71     13544166.34      1956644.45     13544137.69
      1956826.16     13544064.61      1956907.39     13543533.27
#Sta/Elev= 30
  4324.3  681.01  4372.8  678.90  4443.1  673.74  4513.4  670.29  4573.6  667.92
  4654.7  666.62  4695.8  663.43  4696.1  662.93  4699.6  662.93  4699.8  663.43
  4708.6  665.09  4730.2  665.62  4784.0  664.44  4799.1  664.54  4835.9  663.46
  4990.5  664.99  5010.8  664.01  5051.2  665.26  5091.7  665.49  5122.0  666.50
  5152.4  666.70  5182.7  668.01  5203.0  667.74  5265.2  668.26  5273.8  669.20
  5283.9  669.06  5304.1  670.37  5328.6  670.51  5344.6  672.02  5376.7  673.99
#Mann=3,-1,0
  4324.3     0.1       0  4695.8    0.07       0  4699.8     0.1       0
Bank Sta=4695.8,4699.8
Exp/Cntr=0.3,0.1

Type RM Length L Ch R = 1,33651,189,189,189
BEGIN DESCRIPTION:
Mapping XS f3f06e43
END DESCRIPTION:
XS GIS Cut Line= 4
      1956597.62     13544510.06      1956868.41     13544356.44
      1957071.54     13544043.94      1957128.83     13543734.04
#Sta/Elev= 30
  4414.3  673.84  4459.0  671.86  4526.3  670.48  4561.4  668.67  4571.5  668.67
  4577.3  667.88  4593.2  668.01  4598.9  667.11  4614.8  667.22  4620.5  666.39
  4636.4  666.40  4642.2  665.82  4664.2  665.24  4673.9  665.02  4687.2  665.72
  4722.0  664.46  4846.6  661.92  4897.0  659.74  4948.4  659.96  4988.6  659.32
  4988.8  658.82  4992.3  658.82  4992.6  659.32  5078.2  659.58  5085.2  659.70
  5093.3  660.74  5107.4  660.97  5149.1  661.00  5312.9  663.37  5413.5  666.57
#Mann=3,-1,0
  4414.3     0.1       0  4988.6    0.07       0  4992.6     0.1       0
Bank Sta=4988.6,4992.6
Exp/Cntr=0.3,0.1

Type RM Length L Ch R = 1,33462,96,96,96
BEGIN DESCRIPTION:
Mapping XS e46a0cd1
END DESCRIPTION:
XS GIS Cut Line= 4
      1956831.93     13544715.84      1957097.58     13544366.85
      1957209.56     13543913.73      1957152.26     13543723.62
#Sta/Elev= 30
  4393.0  673.74  4459.5  670.86  4482.0  670.64  4567.6  668.01  4632.0  665.48
  4652.8  665.12  4659.1  665.78  4673.7  664.45  4738.1  662.63  4752.6  662.79
  4796.2  661.56  4802.5  661.82  4808.8  661.30  4823.4  661.36  4915.9  659.52
  5099.2  659.68  5101.5  659.66  5176.9  659.47  5213.1  660.07  5222.9  659.37
  5223.2  658.87  5226.7  658.87  5226.9  659.37  5254.6  659.52  5276.4  661.00
  5332.5  661.98  5338.8  662.54  5403.7  663.34  5464.1  666.19  5496.9  667.24
#Mann=5,-1,0
  4393.0     0.1       0  5099.2    0.05       0  5101.5     0.1       0
  5222.9    0.07       0  5226.9     0.1       0
Bank Sta=5222.9,5226.9
Exp/Cntr=0.3,0.1

Type RM Length L Ch R = 1,33366,37,37,37
BEGIN DESCRIPTION:
Mapping XS 47dfc213
END DESCRIPTION:
XS GIS Cut Line= 4
      1956950.56     13544845.63      1957172.79     13544467.14
      1957311.68     13543880.34      1957285.08     13543515.33
#Sta/Elev= 30
  4293.5  674.74  4398.6  670.28  4503.0  667.33  4546.4  665.36  4552.1  665.67
  4560.9  665.45  4605.0  663.51  4618.9  663.26  4626.4  663.55  4669.4  661.65
  4736.1  661.43  4767.1  660.25  4804.3  659.73  5018.1  659.81  5102.6  659.41
  5102.8  658.91  5106.3  658.91  5106.6  659.41  5130.7  659.64  5269.0  659.79
  5320.4  661.03  5340.8  661.01  5411.0  662.46  5431.0  663.71  5461.1  664.55
  5481.1  664.54  5591.4  667.45  5611.5  667.42  5651.6  668.66  5701.4  669.32
#Mann=5,-1,0
  4293.5     0.1       0  5018.1    0.05       0  5102.6    0.07       0
  5106.6    0.05       0  5130.7     0.1       0
Bank Sta=5102.6,5106.6
Exp/Cntr=0.3,0.1

Type RM Length L Ch R = 1,33329,45,45,45
BEGIN DESCRIPTION:
Horse Creek 32.0
END DESCRIPTION:
XS GIS Cut Line= 4
      1957004.84     13544842.11      1957204.47     13544484.07
      1957371.58     13543789.62      1957342.37     13543502.31
#Sta/Elev= 30
  4305.7  673.18  4523.7  665.13  4683.9  661.24  4684.2  660.74  4687.9  661.24
  4701.9  661.90  4712.2  663.79  4745.5  665.51  4807.3  665.27  4823.7  664.29
  4828.9  665.72  4865.7  664.56  4870.8  665.72  4907.6  664.92  4920.4  666.01
  4949.5  664.73  4954.7  665.98  4991.5  664.56  4996.6  665.69  5038.6  666.34
  5080.5  664.50  5085.7  665.62  5122.5  664.56  5127.6  665.55  5187.8  665.20
  5206.3  664.13  5352.4  664.92  5403.8  662.45  5426.3  662.52  5718.7  668.64
#Mann=3,-1,0
  4305.7     0.1       0  4683.9    0.07       0  4687.9     0.1       0
Bank Sta=4683.9,4687.9
Exp/Cntr=0.3,0.1

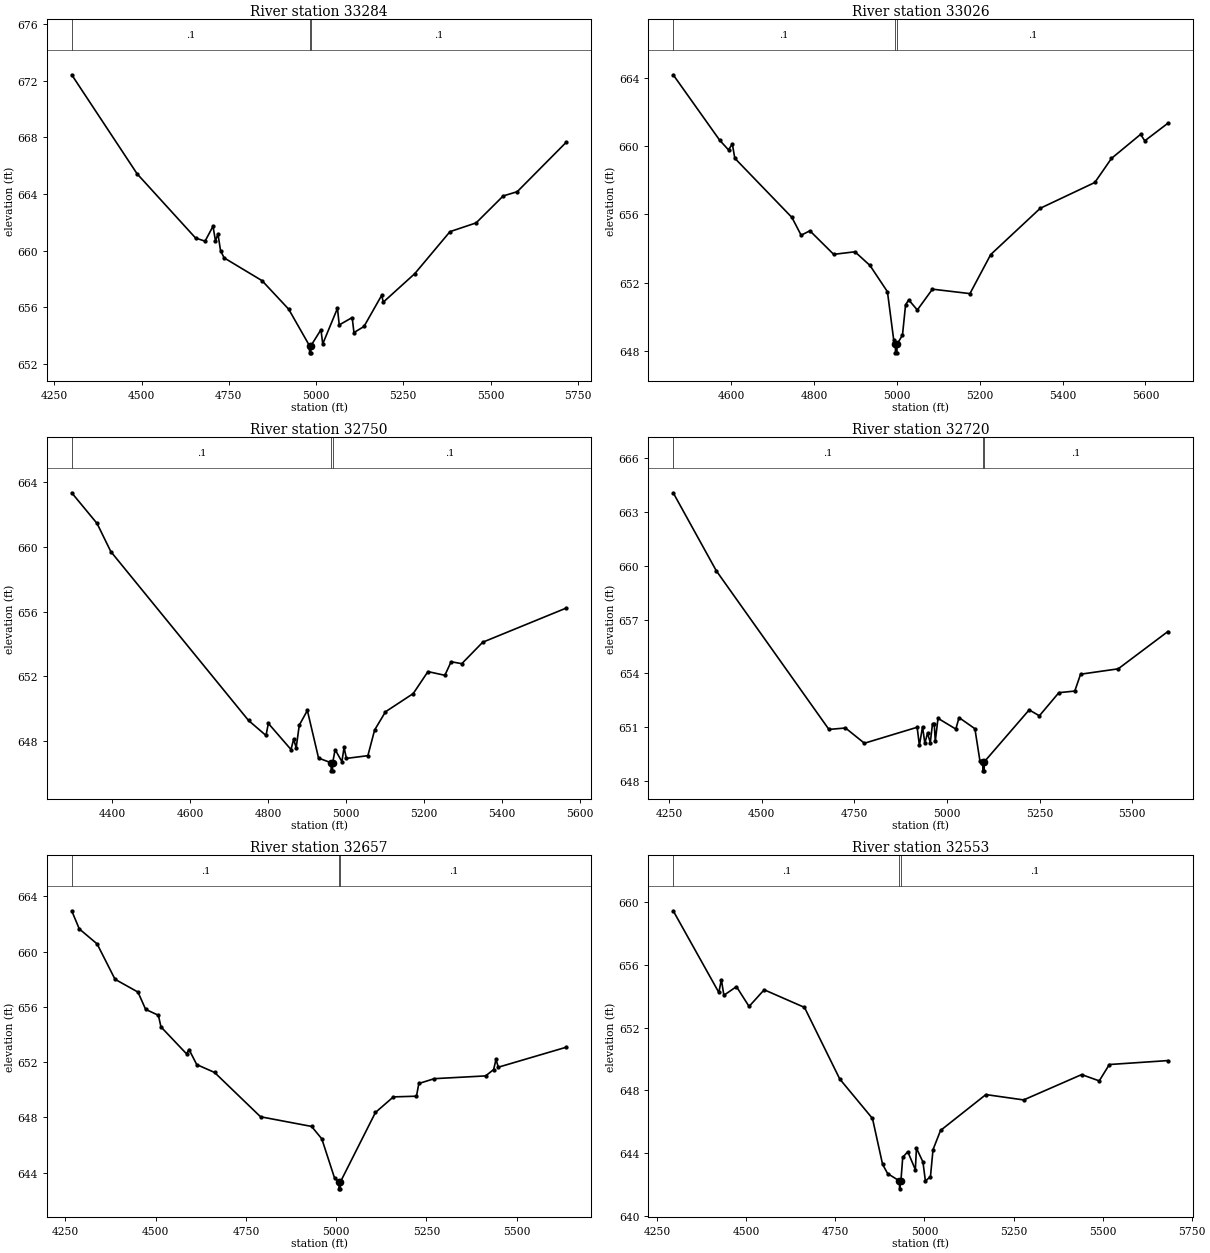
Type RM Length L Ch R = 1,33284,258,258,258
BEGIN DESCRIPTION:
Mapping XS 1d5b6e26
END DESCRIPTION:
XS GIS Cut Line= 5
      1957030.45     13544838.63      1957249.18     13544487.97
      1957367.24     13543991.45      1957422.79     13543751.86
      1957397.06     13543504.89
#Sta/Elev= 30
  4299.6  672.41  4487.1  665.42  4654.7  660.89  4681.8  660.67  4704.6  661.72
  4711.7  660.69  4718.8  661.18  4726.2  660.00  4736.5  659.49  4845.3  657.88
  4921.5  655.87  4981.2  653.29  4981.4  652.79  4984.9  652.79  4985.2  653.29
  5014.0  654.42  5019.1  653.42  5061.3  655.93  5066.4  654.76  5103.5  655.28
  5108.6  654.22  5137.4  654.65  5187.8  656.84  5192.9  656.37  5283.0  658.38
  5383.8  661.34  5458.8  661.96  5536.4  663.86  5576.6  664.16  5717.5  667.66
#Mann=3,-1,0
  4299.6     0.1       0  4981.2    0.07       0  4985.2     0.1       0
Bank Sta=4981.2,4985.2
Exp/Cntr=0.3,0.1

Type RM Length L Ch R = 1,33026,276,276,276
BEGIN DESCRIPTION:
Horse Creek 31.0
END DESCRIPTION:
XS GIS Cut Line= 3
      1957269.46     13544705.38      1957590.76     13544210.63
      1957649.62     13543609.53
#Sta/Elev= 30
  4460.2  664.18  4572.6  660.34  4593.7  659.78  4602.9  660.13  4608.9  659.29
  4746.8  655.82  4769.0  654.78  4790.1  655.04  4847.5  653.66  4898.9  653.81
  4935.1  653.01  4977.3  651.47  4992.4  648.65  4996.4  648.39  4996.7  647.89
  5000.2  647.89  5000.4  648.39  5013.6  648.93  5021.1  650.71  5028.7  650.99
  5049.4  650.40  5085.9  651.62  5176.4  651.36  5226.6  653.65  5346.2  656.36
  5477.8  657.87  5518.0  659.28  5588.3  660.69  5598.4  660.31  5654.1  661.34
#Mann=3,-1,0
  4460.2     0.1       0  4996.4    0.07       0  5000.4     0.1       0
Bank Sta=4996.4,5000.4
Exp/Cntr=0.3,0.1

Type RM Length L Ch R = 1,32750,30,30,30
BEGIN DESCRIPTION:
Mapping XS 6594c7a3
END DESCRIPTION:
XS GIS Cut Line= 6
      1957353.60     13544725.43      1957652.18     13544407.75
      1957719.89     13544308.79      1957808.43     13544235.87
      1957853.57     13544138.65      1958093.11     13543709.90
#Sta/Elev= 30
  4295.7  663.36  4360.7  661.46  4395.9  659.72  4749.3  649.25  4794.1  648.32
  4800.1  649.07  4858.2  647.45  4865.0  648.09  4871.5  647.56  4879.4  648.96
  4900.2  649.87  4928.9  646.92  4961.0  646.63  4961.3  646.13  4964.8  646.13
  4965.0  646.63  4971.4  647.44  4988.8  646.70  4994.3  647.58  5000.3  646.90
  5055.4  647.07  5072.7  648.66  5100.6  649.79  5171.8  650.92  5209.5  652.28
  5252.9  652.05  5268.9  652.89  5296.3  652.77  5350.0  654.10  5564.6  656.22
#Mann=3,-1,0
  4295.7     0.1       0  4961.0    0.07       0  4965.0     0.1       0
Bank Sta=4961,4965
Exp/Cntr=0.3,0.1

Type RM Length L Ch R = 1,32720,63,63,63
BEGIN DESCRIPTION:
Mapping XS 5ce83773
END DESCRIPTION:
XS GIS Cut Line= 6
      1957346.63     13544741.08      1957674.75     13544421.64
      1957702.53     13544362.61      1957839.68     13544244.55
      1957862.25     13544183.79      1958148.72     13543695.92
#Sta/Elev= 30
  4261.2  664.07  4377.5  659.72  4681.5  650.87  4726.2  650.95  4777.3  650.10
  4919.6  650.99  4925.7  649.98  4934.2  651.02  4940.4  650.10  4947.6  650.66
  4955.1  650.14  4961.1  651.19  4965.7  651.19  4968.6  650.21  4975.9  651.49
  5024.0  650.89  5032.7  651.53  5075.5  650.91  5089.1  649.11  5096.7  649.06
  5097.0  648.56  5100.5  648.56  5100.7  649.06  5222.0  651.96  5249.5  651.63
  5302.1  652.92  5345.1  653.01  5360.7  653.95  5462.3  654.25  5596.3  656.33
#Mann=3,-1,0
  4261.2     0.1       0  5096.7    0.07       0  5100.7     0.1       0
Bank Sta=5096.7,5100.7
Exp/Cntr=0.3,0.1

Type RM Length L Ch R = 1,32657,104,104,104
BEGIN DESCRIPTION:
Mapping XS 4bb3c8d3
END DESCRIPTION:
XS GIS Cut Line= 3
      1957386.76     13544746.23      1957998.75     13544144.66
      1958323.80     13543749.40
#Sta/Elev= 30
  4267.6  662.96  4288.5  661.65  4337.9  660.56  4387.5  658.00  4451.1  657.07
  4472.3  655.82  4507.6  655.39  4514.8  654.55  4585.5  652.60  4592.5  652.91
  4613.8  651.82  4663.2  651.25  4790.5  648.04  4931.9  647.34  4960.2  646.44
  4995.5  643.60  5007.7  643.32  5007.9  642.82  5011.4  642.82  5011.7  643.32
  5108.7  648.35  5158.4  649.48  5222.3  649.53  5228.9  650.45  5271.8  650.80
  5413.9  651.00  5436.0  651.46  5442.6  652.19  5449.0  651.63  5637.5  653.08
#Mann=3,-1,0
  4267.6     0.1       0  5007.7    0.07       0  5011.7     0.1       0
Bank Sta=5007.7,5011.7
Exp/Cntr=0.3,0.1

Type RM Length L Ch R = 1,32553,670,670,670
BEGIN DESCRIPTION:
Horse Creek 30.0
END DESCRIPTION:
XS GIS Cut Line= 3
      1957470.12     13544811.30      1957954.47     13544326.95
      1958444.07     13543821.73
#Sta/Elev= 30
  4294.7  659.42  4422.8  654.23  4429.9  655.04  4437.0  654.05  4472.3  654.60
  4507.7  653.34  4550.1  654.40  4663.2  653.28  4762.2  648.73  4854.1  646.22
  4882.4  643.31  4896.6  642.72  4929.9  642.25  4930.2  641.75  4933.9  642.25
  4939.0  643.75  4953.1  644.11  4974.4  642.97  4977.5  644.33  4995.7  643.46
  5002.6  642.25  5016.8  642.52  5024.0  644.24  5045.1  645.46  5172.4  647.74
  5278.4  647.40  5441.2  649.01  5490.6  648.61  5518.9  649.65  5683.2  649.90
#Mann=3,-1,0
  4294.7     0.1       0  4929.9    0.07       0  4933.9     0.1       0
Bank Sta=4929.9,4933.9
Exp/Cntr=0.3,0.1

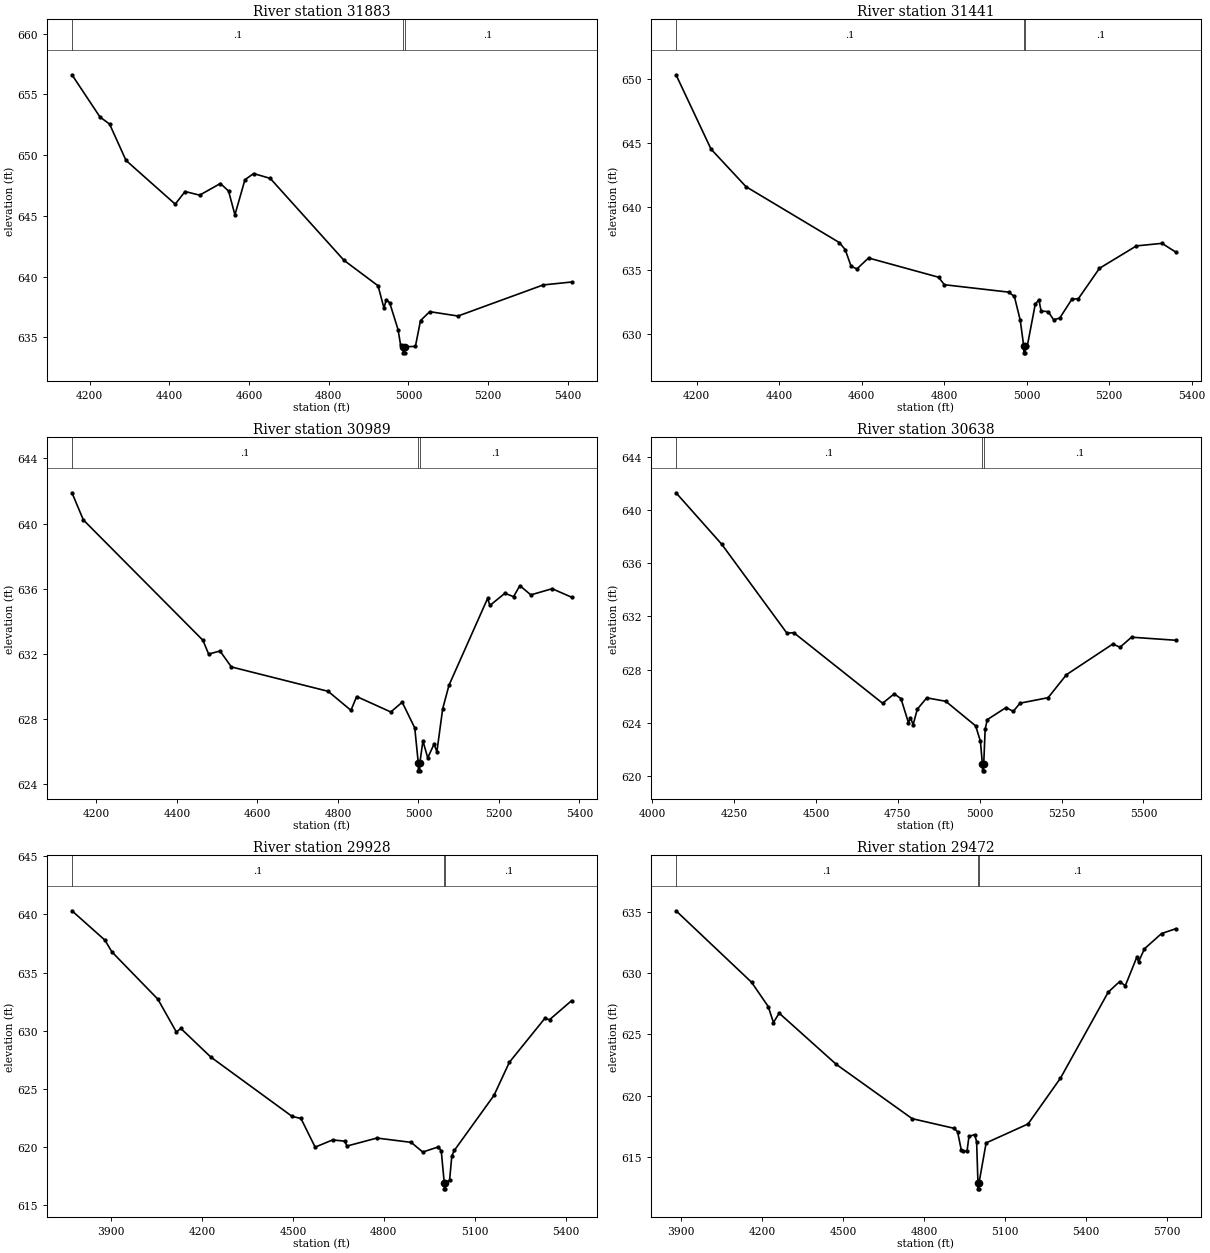
Type RM Length L Ch R = 1,31883,442,442,442
BEGIN DESCRIPTION:
Horse Creek 29.0
END DESCRIPTION:
XS GIS Cut Line= 4
      1957613.29     13545076.96      1958126.35     13544951.95
      1958550.83     13544639.45      1958592.10     13544445.47
#Sta/Elev= 30
  4155.9  656.62  4226.1  653.15  4250.3  652.56  4291.5  649.57  4415.0  645.97
  4439.7  647.01  4476.3  646.71  4528.3  647.67  4548.8  647.05  4564.8  645.09
  4589.9  647.98  4611.7  648.49  4653.4  648.09  4838.3  641.35  4923.9  639.25
  4938.6  637.43  4944.8  638.11  4953.2  637.84  4974.1  635.64  4980.3  634.40
  4986.7  634.23  4986.9  633.73  4990.4  633.73  4990.7  634.23  5017.6  634.26
  5030.4  636.38  5053.5  637.12  5124.5  636.76  5338.3  639.32  5409.4  639.56
#Mann=3,-1,0
  4155.9     0.1       0  4986.7    0.07       0  4990.7     0.1       0
Bank Sta=4986.7,4990.7
Exp/Cntr=0.3,0.1

Type RM Length L Ch R = 1,31441,452,452,452
BEGIN DESCRIPTION:
Horse Creek 28.0
END DESCRIPTION:
XS GIS Cut Line= 3
      1958075.00     13545625.00      1958675.00     13545025.00
      1958833.80     13544699.06
#Sta/Elev= 30
  4149.9  650.37  4234.8  644.53  4319.6  641.58  4545.9  637.19  4560.0  636.64
  4574.2  635.34  4588.3  635.12  4616.6  635.98  4786.3  634.47  4800.4  633.88
  4956.0  633.30  4970.1  632.96  4984.3  631.10  4992.9  629.03  4993.1  628.53
  4996.6  628.53  4996.9  629.03  5001.2  629.03  5020.7  632.34  5029.5  632.70
  5035.0  631.81  5052.0  631.77  5065.2  631.13  5080.1  631.26  5109.7  632.75
  5125.2  632.78  5176.4  635.17  5266.0  636.93  5328.0  637.13  5361.0  636.45
#Mann=3,-1,0
  4149.9     0.1       0  4992.9    0.07       0  4996.9     0.1       0
Bank Sta=4992.9,4996.9
Exp/Cntr=0.3,0.1

Type RM Length L Ch R = 1,30989,351,351,351
BEGIN DESCRIPTION:
Horse Creek 27.0
END DESCRIPTION:
XS GIS Cut Line= 3
      1958374.97     13545875.03      1958975.00     13545275.00
      1959173.23     13544936.32
#Sta/Elev= 30
  4139.3  641.89  4167.6  640.22  4464.6  632.82  4478.8  631.97  4507.0  632.16
  4535.3  631.18  4775.7  629.68  4832.3  628.51  4846.5  629.36  4931.3  628.41
  4959.6  629.01  4990.8  627.43  4999.5  625.29  4999.8  624.79  5003.3  624.79
  5003.5  625.29  5011.1  626.63  5023.0  625.59  5038.7  626.43  5045.8  625.97
  5060.2  628.61  5075.9  630.06  5171.7  635.39  5177.5  634.96  5214.7  635.71
  5236.2  635.50  5251.9  636.18  5279.1  635.61  5332.0  635.99  5380.3  635.47
#Mann=3,-1,0
  4139.3     0.1       0  4999.5    0.07       0  5003.5     0.1       0
Bank Sta=4999.5,5003.5
Exp/Cntr=0.3,0.1

Type RM Length L Ch R = 1,30638,710,710,710
BEGIN DESCRIPTION:
Horse Creek 26.0
END DESCRIPTION:
XS GIS Cut Line= 3
      1958473.60     13546048.72      1959227.04     13545461.93
      1959660.53     13545090.87
#Sta/Elev= 30
  4072.7  641.30  4212.3  637.43  4411.4  630.74  4432.2  630.78  4703.6  625.47
  4738.9  626.18  4759.7  625.82  4782.3  624.02  4788.7  624.36  4796.8  623.87
  4809.6  625.03  4838.4  625.88  4896.3  625.62  4987.7  623.77  5002.2  622.62
  5008.3  620.89  5008.6  620.39  5012.1  620.39  5012.3  620.89  5016.7  623.52
  5023.2  624.24  5080.5  625.15  5102.5  624.86  5123.3  625.48  5208.9  625.89
  5264.9  627.62  5406.7  629.93  5428.5  629.68  5463.6  630.44  5598.3  630.21
#Mann=3,-1,0
  4072.7     0.1       0  5008.3    0.07       0  5012.3     0.1       0
Bank Sta=5008.3,5012.3
Exp/Cntr=0.3,0.1

Type RM Length L Ch R = 1,29928,456,456,456
BEGIN DESCRIPTION:
Horse Creek 25.0
END DESCRIPTION:
XS GIS Cut Line= 3
      1958529.15     13546152.90      1959625.00     13545675.00
      1960015.23     13545444.58
#Sta/Elev= 30
  3770.7  640.30  3879.4  637.78  3902.8  636.76  4054.2  632.71  4115.3  629.89
  4129.9  630.20  4229.0  627.74  4497.1  622.65  4526.4  622.47  4573.2  620.01
  4631.0  620.63  4671.7  620.52  4677.8  620.10  4777.0  620.79  4889.9  620.42
  4928.4  619.59  4979.8  620.03  4989.4  619.68  4999.3  616.93  4999.5  616.43
  5003.0  616.43  5003.3  616.93  5016.9  617.17  5024.3  619.27  5032.6  619.73
  5163.6  624.46  5214.0  627.29  5331.1  631.06  5346.7  630.95  5419.4  632.58
#Mann=3,-1,0
  3770.7     0.1       0  4999.3    0.07       0  5003.3     0.1       0
Bank Sta=4999.3,5003.3
Exp/Cntr=0.3,0.1

Type RM Length L Ch R = 1,29472,486,486,486
BEGIN DESCRIPTION:
Horse Creek 24.0
END DESCRIPTION:
XS GIS Cut Line= 3
      1958664.50     13546413.34      1959612.46     13546076.52
      1960199.23     13545465.44
#Sta/Elev= 30
  3880.6  635.09  4160.9  629.25  4222.6  627.27  4242.0  625.96  4263.2  626.73
  4475.4  622.54  4756.7  618.11  4910.7  617.33  4924.9  617.05  4939.0  615.53
  4946.0  615.44  4960.1  615.47  4967.3  616.66  4988.4  616.81  4995.6  616.23
  5000.6  612.88  5000.8  612.38  5004.3  612.38  5004.6  612.88  5030.9  616.13
  5186.5  617.68  5306.7  621.42  5483.7  628.44  5526.1  629.31  5547.2  628.97
  5589.7  631.29  5596.6  630.93  5618.0  631.98  5681.5  633.23  5733.8  633.62
#Mann=3,-1,0
  3880.6     0.1       0  5000.6    0.07       0  5004.6     0.1       0
Bank Sta=5000.6,5004.6
Exp/Cntr=0.3,0.1

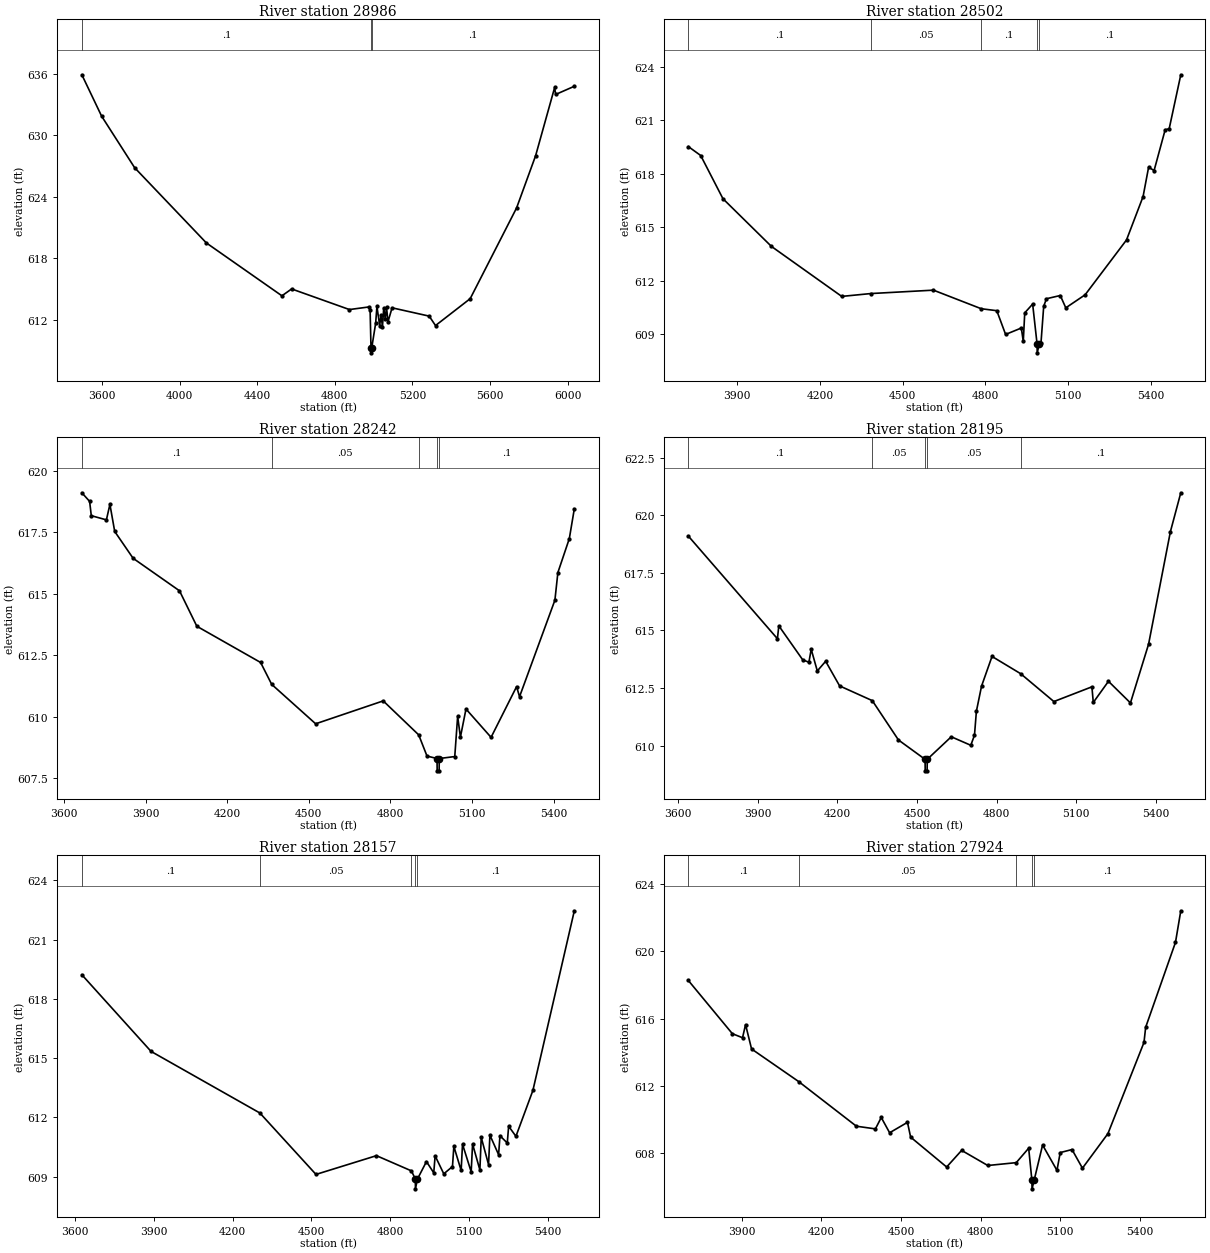
Type RM Length L Ch R = 1,28986,484,484,484
BEGIN DESCRIPTION:
Horse Creek 23.0
END DESCRIPTION:
XS GIS Cut Line= 4
      1958543.05     13546632.07      1959578.22     13546632.49
      1960177.13     13546126.86      1960388.83     13545439.71
#Sta/Elev= 30
  3496.1  635.90  3598.1  631.86  3768.1  626.84  4138.1  619.50  4527.2  614.35
  4577.2  615.02  4875.0  613.01  4973.9  613.26  4981.6  612.99  4986.2  609.29
  4986.4  608.79  4990.2  609.29  5010.2  611.67  5016.8  613.31  5031.0  611.45
  5037.6  612.49  5045.3  611.34  5051.9  613.18  5059.6  612.09  5066.2  613.23
  5073.9  611.82  5094.8  613.18  5286.1  612.37  5318.7  611.45  5497.4  614.07
  5736.6  622.92  5834.6  628.01  5932.7  634.66  5937.9  633.98  6034.1  634.78
#Mann=3,-1,0
  3496.1     0.1       0  4986.2    0.07       0  4990.2     0.1       0
Bank Sta=4986.2,4990.2
Exp/Cntr=0.3,0.1

Type RM Length L Ch R = 1,28502,260,260,260
BEGIN DESCRIPTION:
Horse Creek 22.0
END DESCRIPTION:
XS GIS Cut Line= 3
      1960693.20     13547444.59      1960315.59     13546272.70
      1960342.03     13545718.36
#Sta/Elev= 30
  3722.4  619.52  3767.3  619.02  3848.0  616.60  4023.8  613.93  4278.8  611.13
  4384.7  611.29  4611.5  611.48  4784.8  610.44  4841.2  610.33  4873.2  609.00
  4930.2  609.36  4937.3  608.61  4942.6  610.21  4971.3  610.70  4987.3  608.47
  4987.8  607.97  4995.5  608.47  5001.4  608.50  5011.4  610.58  5021.4  611.00
  5071.5  611.18  5091.5  610.49  5161.6  611.22  5311.7  614.29  5371.8  616.72
  5391.8  618.36  5411.8  618.18  5451.9  620.46  5466.5  620.52  5508.6  623.54
#Mann=5,-1,0
  3722.4     0.1       0  4384.7    0.05       0  4784.8     0.1       0
  4987.3    0.07       0  4995.5     0.1       0
Bank Sta=4987.3,4995.5
Exp/Cntr=0.3,0.1

Type RM Length L Ch R = 1,28242,47,47,47
BEGIN DESCRIPTION:
Mapping XS 0e0edb58
END DESCRIPTION:
XS GIS Cut Line= 4
      1960982.26     13547501.88      1960596.84     13546454.99
      1960497.88     13546012.28      1960404.48     13545789.16
#Sta/Elev= 30
  3665.2  619.10  3693.8  618.75  3699.9  618.17  3755.5  618.00  3768.4  618.63
  3786.0  617.53  3853.7  616.44  4024.3  615.12  4088.1  613.68  4322.6  612.21
  4363.4  611.32  4525.0  609.72  4773.5  610.65  4904.0  609.27  4934.5  608.41
  4971.4  608.31  4971.9  607.81  4979.1  607.81  4979.6  608.31  5036.6  608.39
  5047.2  610.02  5057.4  609.18  5077.9  610.32  5170.1  609.17  5264.0  611.23
  5274.8  610.82  5404.9  614.74  5415.8  615.86  5457.9  617.24  5476.3  618.45
#Mann=5,-1,0
  3665.2     0.1       0  4363.4    0.05       0  4904.0     0.1       0
  4971.4    0.07       0  4979.6     0.1       0
Bank Sta=4971.4,4979.6
Exp/Cntr=0.3,0.1

Type RM Length L Ch R = 1,28195,38,38,38
BEGIN DESCRIPTION:
Mapping XS 4bdde867
END DESCRIPTION:
XS GIS Cut Line= 4
      1960995.28     13547507.10      1960648.92     13546449.78
      1960492.67     13545876.86      1960422.37     13545744.07
#Sta/Elev= 30
  3637.6  619.10  3973.5  614.64  3978.8  615.20  4069.1  613.72  4092.3  613.62
  4100.9  614.18  4123.9  613.24  4155.4  613.66  4208.0  612.59  4331.2  611.95
  4429.9  610.24  4530.2  609.40  4530.7  608.90  4537.9  608.90  4538.4  609.40
  4629.0  610.38  4702.6  610.01  4716.5  610.45  4723.7  611.49  4743.1  612.58
  4782.6  613.87  4890.6  613.12  5015.8  611.91  5159.2  612.55  5164.4  611.87
  5221.6  612.79  5304.5  611.85  5372.8  614.40  5455.1  619.29  5494.3  620.98
#Mann=5,-1,0
  3637.6     0.1       0  4331.2    0.05       0  4530.2    0.07       0
  4538.4    0.05       0  4890.6     0.1       0
Bank Sta=4530.2,4538.4
Exp/Cntr=0.3,0.1

Type RM Length L Ch R = 1,28157,233,233,233
BEGIN DESCRIPTION:
Mapping XS 16658c60
END DESCRIPTION:
XS GIS Cut Line= 4
      1961016.10     13547496.65      1960641.11     13546283.11
      1960497.88     13545806.55      1960445.80     13545712.82
#Sta/Elev= 30
  3626.4  619.22  3889.8  615.34  4304.2  612.22  4517.8  609.11  4748.0  610.06
  4881.1  609.29  4896.0  608.88  4896.5  608.38  4904.2  608.88  4938.4  609.76
  4966.2  609.19  4971.4  610.05  5004.4  609.14  5037.5  609.51  5042.7  610.53
  5070.5  609.31  5075.7  610.64  5108.7  609.24  5114.0  610.65  5141.8  609.34
  5147.0  610.98  5174.8  609.61  5180.0  611.10  5213.1  610.11  5218.3  611.07
  5246.1  610.70  5251.3  611.55  5279.1  611.04  5343.6  613.36  5501.4  622.46
#Mann=5,-1,0
  3626.4     0.1       0  4304.2    0.05       0  4881.1     0.1       0
  4896.0    0.07       0  4904.2     0.1       0
Bank Sta=4896,4904.2
Exp/Cntr=0.3,0.1

Type RM Length L Ch R = 1,27924,621,621,621
BEGIN DESCRIPTION:
Horse Creek 21.0
END DESCRIPTION:
XS GIS Cut Line= 3
      1961437.99     13547285.74      1960825.00     13546125.00
      1960589.51     13545635.68
#Sta/Elev= 30
  3698.4  618.27  3864.3  615.10  3902.7  614.86  3914.1  615.64  3936.7  614.19
  4114.1  612.25  4331.7  609.59  4403.4  609.43  4425.4  610.11  4456.9  609.20
  4524.2  609.82  4536.1  608.94  4671.8  607.16  4728.3  608.15  4826.8  607.25
  4934.1  607.42  4980.9  608.28  4993.1  606.36  4993.6  605.86  5001.3  606.36
  5033.3  608.47  5087.5  606.96  5099.8  608.02  5144.2  608.20  5183.5  607.09
  5279.6  609.15  5415.4  614.58  5421.7  615.48  5534.1  620.54  5554.1  622.42
#Mann=5,-1,0
  3698.4     0.1       0  4114.1    0.05       0  4934.1     0.1       0
  4993.1    0.07       0  5001.3     0.1       0
Bank Sta=4993.1,5001.3
Exp/Cntr=0.3,0.1