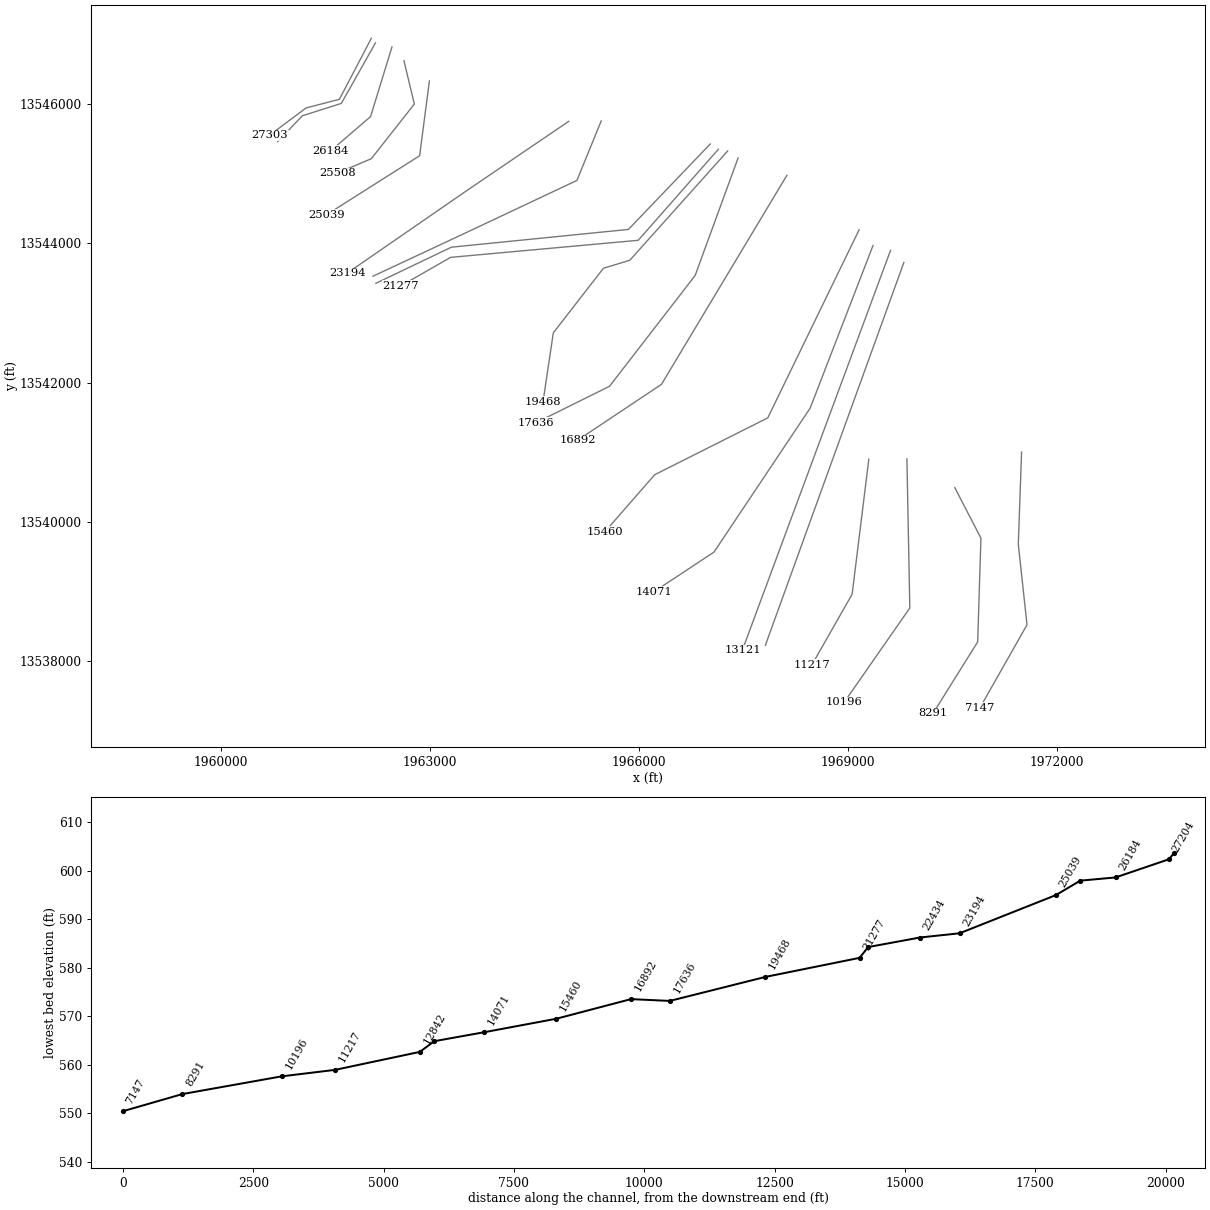
HEC-RAS study Horse Creek.prj: Horse Creek Base Level Engineering

--- Horse Creek.g01 (geometry) --- (continued)

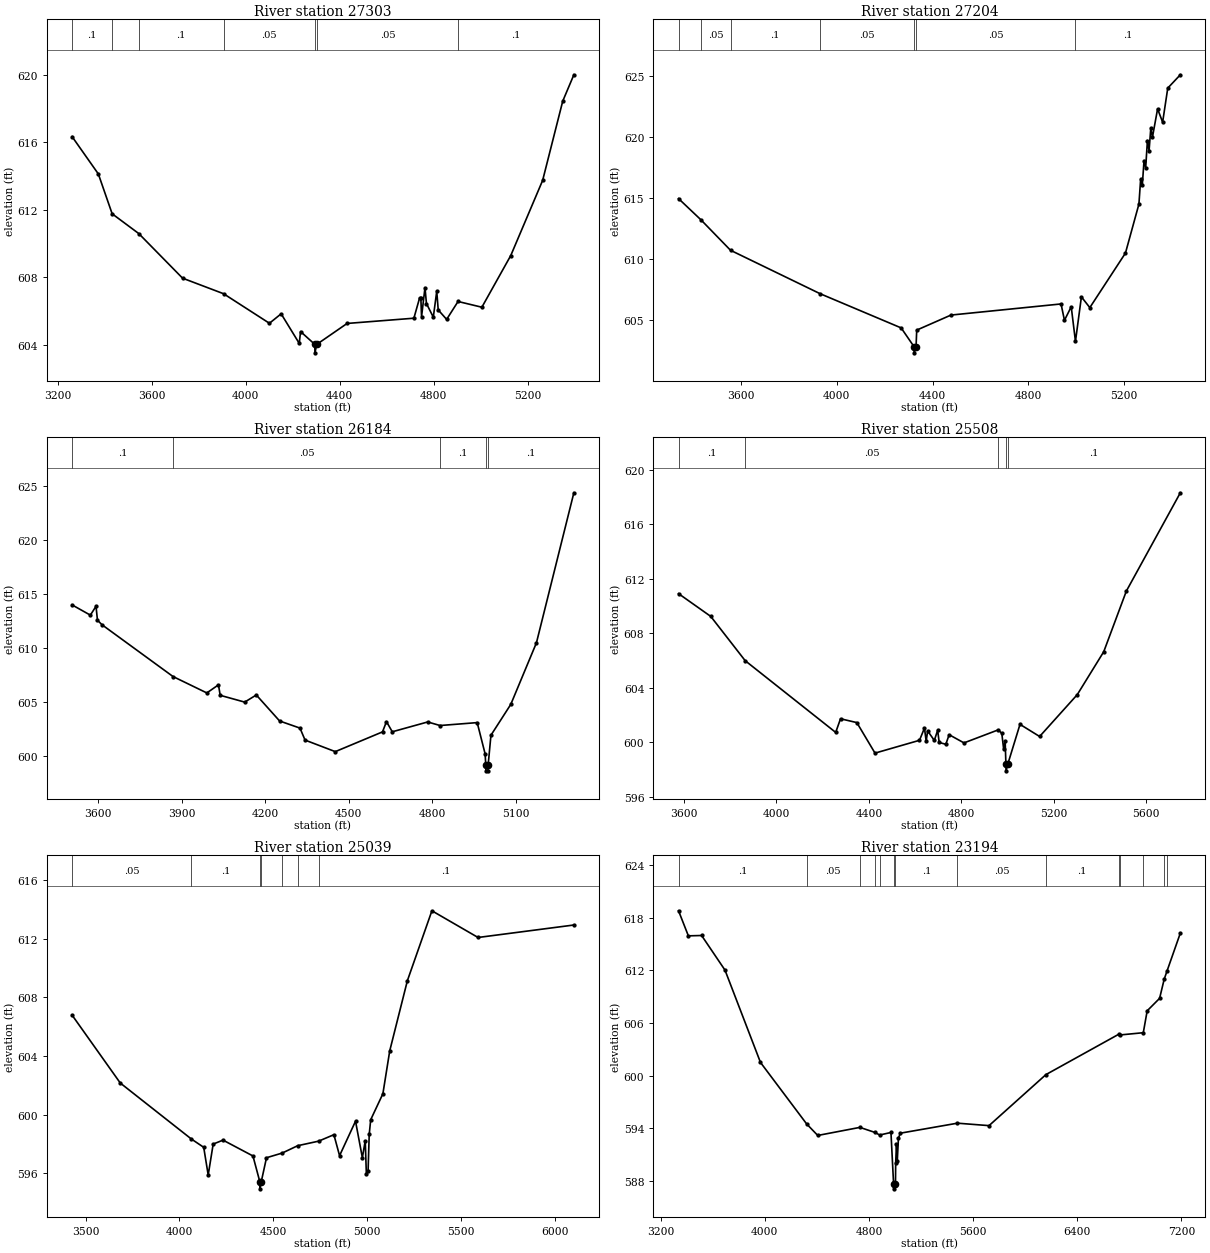
Type RM Length L Ch R = 1,27303,99,99,99
BEGIN DESCRIPTION:
Horse Creek 20.0
END DESCRIPTION:
XS GIS Cut Line= 4
      1962160.42     13546941.67      1961702.10     13546066.68
      1961224.87     13545942.84      1960701.45     13545552.22
#Sta/Elev= 30
  3261.7  616.33  3373.4  614.12  3432.2  611.76  3545.4  610.59  3731.6  607.95
  3905.9  607.03  4101.0  605.28  4150.8  605.84  4227.8  604.09  4233.4  604.79
  4294.0  604.03  4294.5  603.53  4302.2  604.03  4431.3  605.27  4715.3  605.58
  4739.8  606.79  4744.9  606.79  4747.9  605.67  4762.5  607.39  4768.7  606.45
  4797.9  605.64  4812.5  607.18  4818.8  606.07  4854.6  605.51  4903.1  606.57
  5004.4  606.23  5127.3  609.29  5262.9  613.74  5348.3  618.43  5395.6  619.99
#Mann=7,-1,0
  3261.7     0.1       0  3432.2    0.05       0  3545.4     0.1       0
  3905.9    0.05       0  4294.0    0.07       0  4302.2    0.05       0
  4903.1     0.1       0
Bank Sta=4294,4302.2
Exp/Cntr=0.3,0.1

Type RM Length L Ch R = 1,27204,1020,1020,1020
BEGIN DESCRIPTION:
Horse Creek 19.0
END DESCRIPTION:
XS GIS Cut Line= 4
      1962219.44     13546875.67      1961729.87     13546007.65
      1961169.75     13545829.99      1960816.76     13545458.82
#Sta/Elev= 30
  3338.5  614.93  3432.8  613.18  3555.8  610.70  3929.8  607.15  4268.6  604.35
  4322.5  602.81  4323.0  602.31  4330.8  602.81  4333.6  604.17  4476.6  605.40
  4936.6  606.31  4950.8  604.97  4979.1  606.08  4996.8  603.25  5021.6  606.89
  5056.8  606.01  5205.6  610.47  5261.9  614.48  5269.1  616.51  5276.0  616.02
  5283.3  618.04  5290.2  617.46  5297.4  619.68  5304.3  618.85  5311.6  620.71
  5318.5  619.96  5339.9  622.27  5361.0  621.18  5382.4  623.97  5434.9  625.06
#Mann=7,-1,0
  3338.5     0.1       0  3432.8    0.05       0  3555.8     0.1       0
  3929.8    0.05       0  4322.5    0.07       0  4330.8    0.05       0
  4996.8     0.1       0
Bank Sta=4322.5,4330.8
Exp/Cntr=0.3,0.1

Type RM Length L Ch R = 1,26184,676,676,676
BEGIN DESCRIPTION:
Horse Creek 18.0
END DESCRIPTION:
XS GIS Cut Line= 3
      1962456.63     13546817.80      1962149.35     13545817.84
      1961575.02     13545325.02
#Sta/Elev= 30
  3505.8  613.96  3571.5  613.01  3591.8  613.83  3597.1  612.54  3613.3  612.12
  3868.5  607.32  3990.0  605.80  4031.8  606.55  4038.0  605.58  4126.0  604.95
  4167.8  605.61  4251.5  603.20  4324.7  602.54  4342.9  601.43  4451.5  600.36
  4621.2  602.19  4635.4  603.14  4656.3  602.20  4783.6  603.11  4827.9  602.78
  4961.4  603.05  4989.9  600.15  4992.3  599.08  4992.8  598.58  5000.1  598.58
  5000.6  599.08  5010.8  601.88  5082.1  604.74  5174.3  610.45  5308.7  624.35
#Mann=5,-1,0
  3505.8     0.1       0  3868.5    0.05       0  4827.9     0.1       0
  4992.3    0.07       0  5000.6     0.1       0
Bank Sta=4992.3,5000.6
Exp/Cntr=0.3,0.1

Type RM Length L Ch R = 1,25508,469,469,469
BEGIN DESCRIPTION:
Mapping XS b7a650f2
END DESCRIPTION:
XS GIS Cut Line= 4
      1962628.53     13546619.89      1962777.83     13545998.39
      1962159.77     13545213.67      1961670.22     13545005.35
#Sta/Elev= 30
  3576.9  610.92  3716.2  609.25  3865.2  606.00  4256.6  600.74  4277.4  601.74
  4348.0  601.46  4426.6  599.22  4619.0  600.16  4640.5  601.06  4647.9  600.09
  4654.2  600.85  4683.1  600.15  4697.6  600.90  4704.1  600.00  4732.8  599.87
  4747.3  600.57  4811.4  599.97  4960.2  600.93  4975.0  600.66  4983.1  599.49
  4989.4  600.10  4992.7  598.42  4993.2  597.92  5001.0  598.42  5053.6  601.33
  5138.5  600.44  5301.3  603.51  5415.8  606.66  5513.6  611.11  5747.0  618.32
#Mann=5,-1,0
  3576.9     0.1       0  3865.2    0.05       0  4960.2     0.1       0
  4992.7    0.07       0  5001.0     0.1       0
Bank Sta=4992.7,5001
Exp/Cntr=0.3,0.1

Type RM Length L Ch R = 1,25039,1845,1845,1845
BEGIN DESCRIPTION:
Horse Creek 15.0
END DESCRIPTION:
XS GIS Cut Line= 3
      1962993.93     13546330.08      1962853.35     13545256.20
      1961511.30     13544405.49
#Sta/Elev= 30
  3428.4  606.78  3685.2  602.15  4063.2  598.34  4129.4  597.77  4153.3  595.88
  4179.8  597.99  4232.2  598.26  4391.6  597.18  4427.8  595.44  4428.3  594.94
  4436.1  595.44  4463.7  597.06  4547.5  597.38  4629.9  597.88  4741.3  598.19
  4822.6  598.63  4852.8  597.20  4937.8  599.55  4974.2  597.06  4989.5  598.22
  4995.4  595.98  5004.7  596.16  5010.7  598.65  5018.6  599.65  5083.5  601.42
  5120.0  604.35  5214.0  609.13  5344.5  613.89  5590.2  612.07  6100.4  612.92
#Mann=7,-1,0
  3428.4    0.05       0  4063.2     0.1       0  4427.8    0.07       0
  4436.1     0.1       0  4547.5     0.1       0  4629.9    0.05       0
  4741.3     0.1       0
Bank Sta=4427.8,4436.1
Exp/Cntr=0.3,0.1

Type RM Length L Ch R = 1,23194,760,760,760
BEGIN DESCRIPTION:
Horse Creek 14.0
END DESCRIPTION:
XS GIS Cut Line= 3
      1964994.67     13545750.93      1963538.24     13544761.41
      1961815.16     13543572.18
#Sta/Elev= 30
  3336.9  618.80  3412.4  615.94  3514.1  615.98  3693.8  612.03  3966.3  601.50
  4321.2  594.48  4406.3  593.17  4730.1  594.09  4846.5  593.51  4881.9  593.22
  4968.6  593.51  4989.0  587.58  4989.5  587.08  5003.3  587.58  5004.9  590.05
  5011.1  592.19  5017.1  590.24  5026.0  592.87  5041.0  593.43  5479.3  594.57
  5721.8  594.29  6158.8  600.11  6716.6  604.70  6724.9  604.63  6906.8  604.89
  6936.7  607.39  7032.1  608.81  7067.5  611.00  7088.7  611.91  7191.3  616.25
#Mann=14,-1,0
  3336.9     0.1       0  4321.2    0.05       0  4730.1     0.1       0
  4846.5    0.05       0  4881.9     0.1       0  4989.0    0.07       0
  5003.3     0.1       0  5479.3    0.05       0  6158.8     0.1       0
  6716.6    0.12       0  6724.9    0.08       0  6906.8     0.1       0
  7067.5    0.05       0  7088.7     0.1       0
Bank Sta=4989,5003.3
Exp/Cntr=0.3,0.1

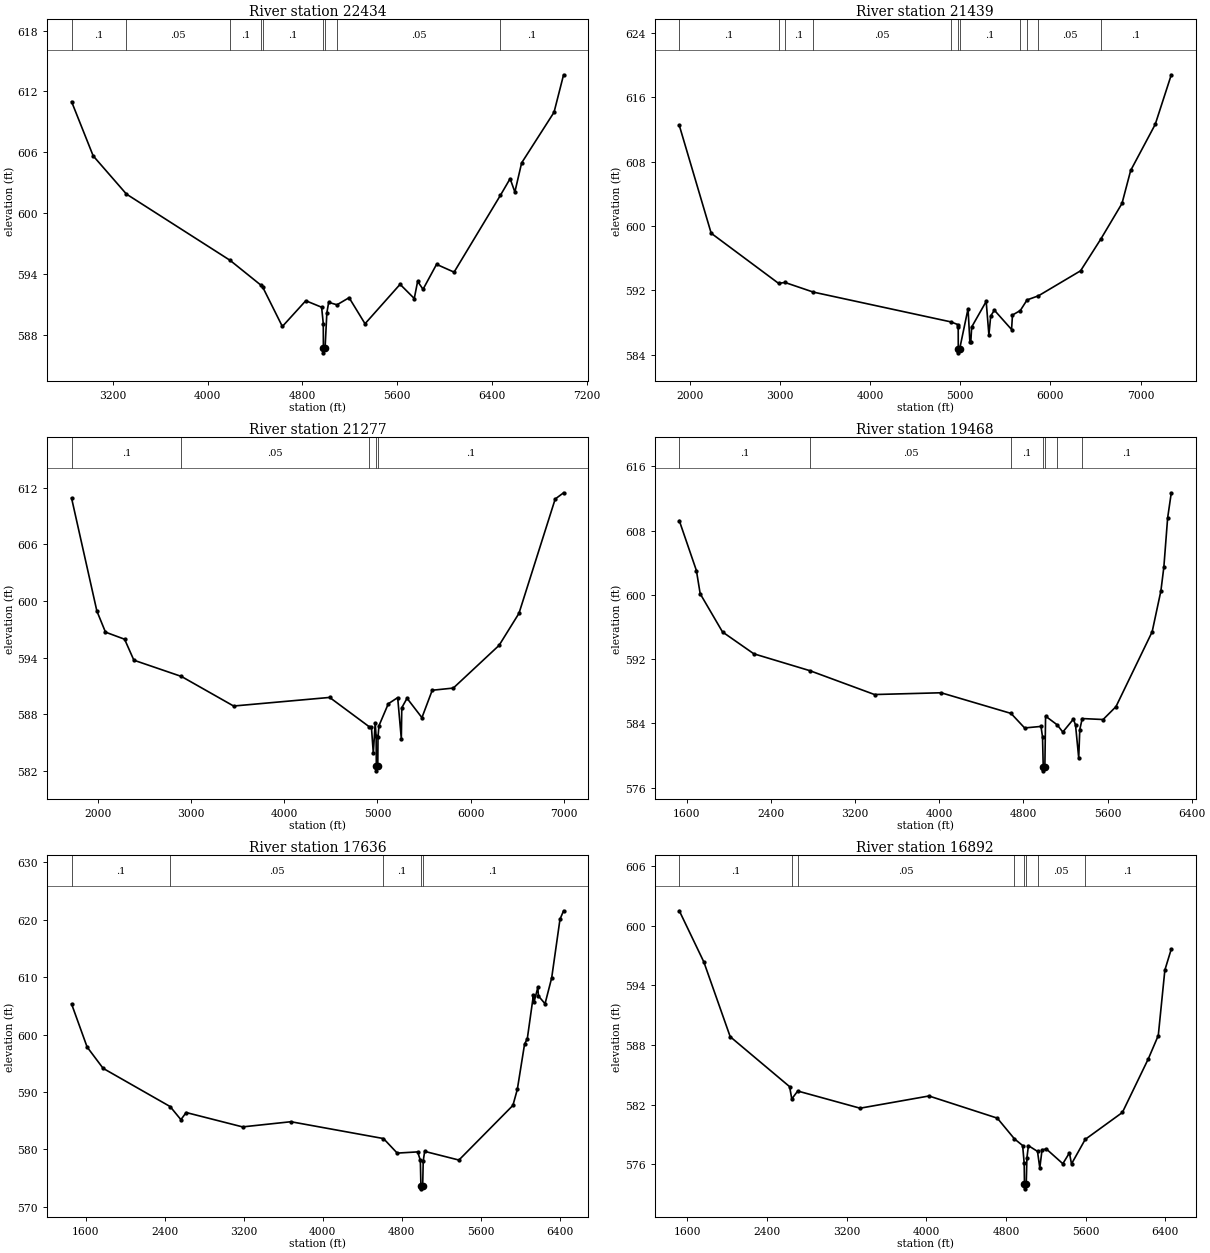
Type RM Length L Ch R = 1,22434,995,995,995
BEGIN DESCRIPTION:
Mapping XS 1c3d2587
END DESCRIPTION:
XS GIS Cut Line= 4
      1965460.11     13545756.19      1965111.16     13544902.04
      1963475.74     13544131.20      1962184.11     13543527.05
#Sta/Elev= 30
  2849.8  610.99  3032.3  605.64  3313.3  601.87  4188.2  595.34  4450.0  592.88
  4464.7  592.69  4630.5  588.81  4828.4  591.35  4962.2  590.71  4976.1  589.10
  4977.2  586.71  4977.7  586.21  4991.5  586.71  5006.4  590.15  5021.7  591.19
  5092.2  590.95  5194.3  591.65  5328.9  589.08  5625.2  592.97  5744.9  591.57
  5773.3  593.26  5819.0  592.48  5933.2  594.94  6081.3  594.17  6472.2  601.74
  6554.6  603.39  6594.8  602.08  6652.1  604.95  6925.6  609.94  7006.4  613.64
#Mann=9,-1,0
  2849.8     0.1       0  3313.3    0.05       0  4188.2     0.1       0
  4450.0    0.05       0  4464.7     0.1       0  4977.2    0.07       0
  4991.5     0.1       0  5092.2    0.05       0  6472.2     0.1       0
Bank Sta=4977.2,4991.5
Exp/Cntr=0.3,0.1

Type RM Length L Ch R = 1,21439,162,162,162
BEGIN DESCRIPTION:
Horse Creek 10.0
END DESCRIPTION:
XS GIS Cut Line= 4
      1967024.98     13545424.98      1965850.74     13544198.91
      1963309.08     13543943.70      1962224.99     13543425.00
#Sta/Elev= 30
  1885.3  612.52  2238.9  599.11  2985.7  592.88  3056.5  592.99  3371.4  591.79
  4895.3  588.09  4972.0  587.76  4977.0  587.43  4978.0  584.74  4978.5  584.24
  4993.5  584.74  5086.2  589.73  5106.3  585.62  5116.4  585.53  5126.4  587.45
  5287.2  590.63  5317.4  586.47  5337.5  588.83  5378.2  589.54  5568.6  587.14
  5578.8  588.94  5665.3  589.50  5740.6  590.82  5866.5  591.33  6333.6  594.44
  6559.3  598.41  6792.6  602.81  6888.8  606.91  7160.9  612.64  7339.2  618.81
#Mann=11,-1,0
  1885.3     0.1       0  2985.7    0.05       0  3056.5     0.1       0
  3371.4    0.05       0  4895.3     0.1       0  4978.0    0.07       0
  4993.5     0.1       0  5665.3    0.05       0  5740.6    0.08       0
  5866.5    0.05       0  6559.3     0.1       0
Bank Sta=4978,4993.5
Exp/Cntr=0.3,0.1

Type RM Length L Ch R = 1,21277,1809,1809,1809
BEGIN DESCRIPTION:
Mapping XS f75e9110
END DESCRIPTION:
XS GIS Cut Line= 4
      1967142.41     13545349.96      1965991.37     13544042.66
      1963298.66     13543797.87      1962579.93     13543386.42
#Sta/Elev= 30
  1721.3  610.88  1992.5  598.93  2084.6  596.70  2289.5  595.95  2389.1  593.73
  2898.7  592.01  3458.2  588.88  4487.7  589.79  4911.3  586.69  4935.5  586.63
  4955.6  583.88  4975.7  587.08  4985.7  585.67  4988.0  582.52  4988.5  582.02
  5003.5  582.52  5005.8  585.58  5015.9  586.79  5116.3  589.12  5216.7  589.77
  5255.8  585.41  5260.8  588.70  5317.1  589.70  5476.7  587.65  5587.2  590.55
  5813.1  590.78  6303.6  595.30  6516.8  598.69  6905.1  610.79  6995.1  611.45
#Mann=5,-1,0
  1721.3     0.1       0  2898.7    0.05       0  4911.3     0.1       0
  4988.0    0.07       0  5003.5     0.1       0
Bank Sta=4988,5003.5
Exp/Cntr=0.3,0.1

Type RM Length L Ch R = 1,19468,1832,1832,1832
BEGIN DESCRIPTION:
Horse Creek 9.0
END DESCRIPTION:
XS GIS Cut Line= 6
      1967275.03     13545325.04      1965991.87     13543891.41
      1965870.71     13543756.03      1965492.24     13543641.45
      1964772.62     13542714.54      1964625.00     13541724.97
#Sta/Elev= 30
  1530.8  609.24  1693.4  603.03  1729.4  600.14  1941.7  595.38  2239.3  592.66
  2771.6  590.56  3386.1  587.59  4018.6  587.81  4682.9  585.24  4812.2  583.43
  4967.8  583.62  4982.3  582.31  4989.0  578.59  4989.5  578.09  5004.5  578.59
  5011.3  584.90  5121.4  583.82  5175.1  582.92  5275.7  584.53  5295.9  583.79
  5326.2  579.70  5336.4  583.23  5359.6  584.60  5557.9  584.48  5680.1  586.08
  6023.9  595.40  6107.0  600.49  6135.1  603.45  6171.2  609.59  6205.9  612.71
#Mann=7,-1,0
  1530.8     0.1       0  2771.6    0.05       0  4682.9     0.1       0
  4989.0    0.07       0  5004.5     0.1       0  5121.4    0.12       0
  5359.6     0.1       0
Bank Sta=4989,5004.5
Exp/Cntr=0.3,0.1

Type RM Length L Ch R = 1,17636,744,744,744
BEGIN DESCRIPTION:
Horse Creek 8.0
END DESCRIPTION:
XS GIS Cut Line= 4
      1967425.01     13545225.03      1966808.21     13543537.28
      1965579.04     13541947.00      1964524.98     13541424.99
#Sta/Elev= 30
  1456.4  605.32  1613.7  597.83  1775.8  594.12  2454.6  587.47  2563.7  585.19
  2616.9  586.43  3188.2  583.93  3677.6  584.83  4615.5  581.90  4754.4  579.37
  4961.7  579.58  4988.9  578.10  4994.5  573.65  4995.0  573.15  5012.3  573.65
  5017.9  578.00  5032.4  579.67  5379.4  578.16  5926.2  587.67  5970.8  590.45
  6044.2  598.32  6072.2  599.30  6133.9  606.85  6139.5  605.60  6178.8  608.21
  6184.4  606.72  6251.7  605.36  6318.9  609.86  6403.1  620.07  6439.5  621.54
#Mann=5,-1,0
  1456.4     0.1       0  2454.6    0.05       0  4615.5     0.1       0
  4994.5    0.07       0  5012.3     0.1       0
Bank Sta=4994.5,5012.3
Exp/Cntr=0.3,0.1

Type RM Length L Ch R = 1,16892,1432,1432,1432
BEGIN DESCRIPTION:
Horse Creek 7.0
END DESCRIPTION:
XS GIS Cut Line= 3
      1968125.00     13544975.00      1966325.00     13541975.00
      1965124.99     13541174.99
#Sta/Elev= 30
  1519.9  601.52  1766.7  596.36  2031.1  588.84  2627.8  583.81  2649.5  582.57
  2709.2  583.37  3335.3  581.64  4027.2  582.87  4713.3  580.64  4885.7  578.55
  4967.9  577.88  4983.5  576.08  4986.1  574.02  4986.6  573.52  5004.1  574.02
  5010.7  576.62  5026.0  577.87  5117.1  577.29  5140.2  575.62  5162.7  577.45
  5206.3  577.53  5371.5  576.05  5437.6  577.14  5458.6  576.03  5596.3  578.50
  5969.4  581.21  6230.8  586.63  6330.0  588.96  6396.1  595.55  6460.7  597.67
#Mann=8,-1,0
  1519.9     0.1       0  2649.5    0.08       0  2709.2    0.05       0
  4885.7     0.1       0  4986.1    0.07       0  5004.1     0.1       0
  5117.1    0.05       0  5596.3     0.1       0
Bank Sta=4986.1,5004.1
Exp/Cntr=0.3,0.1

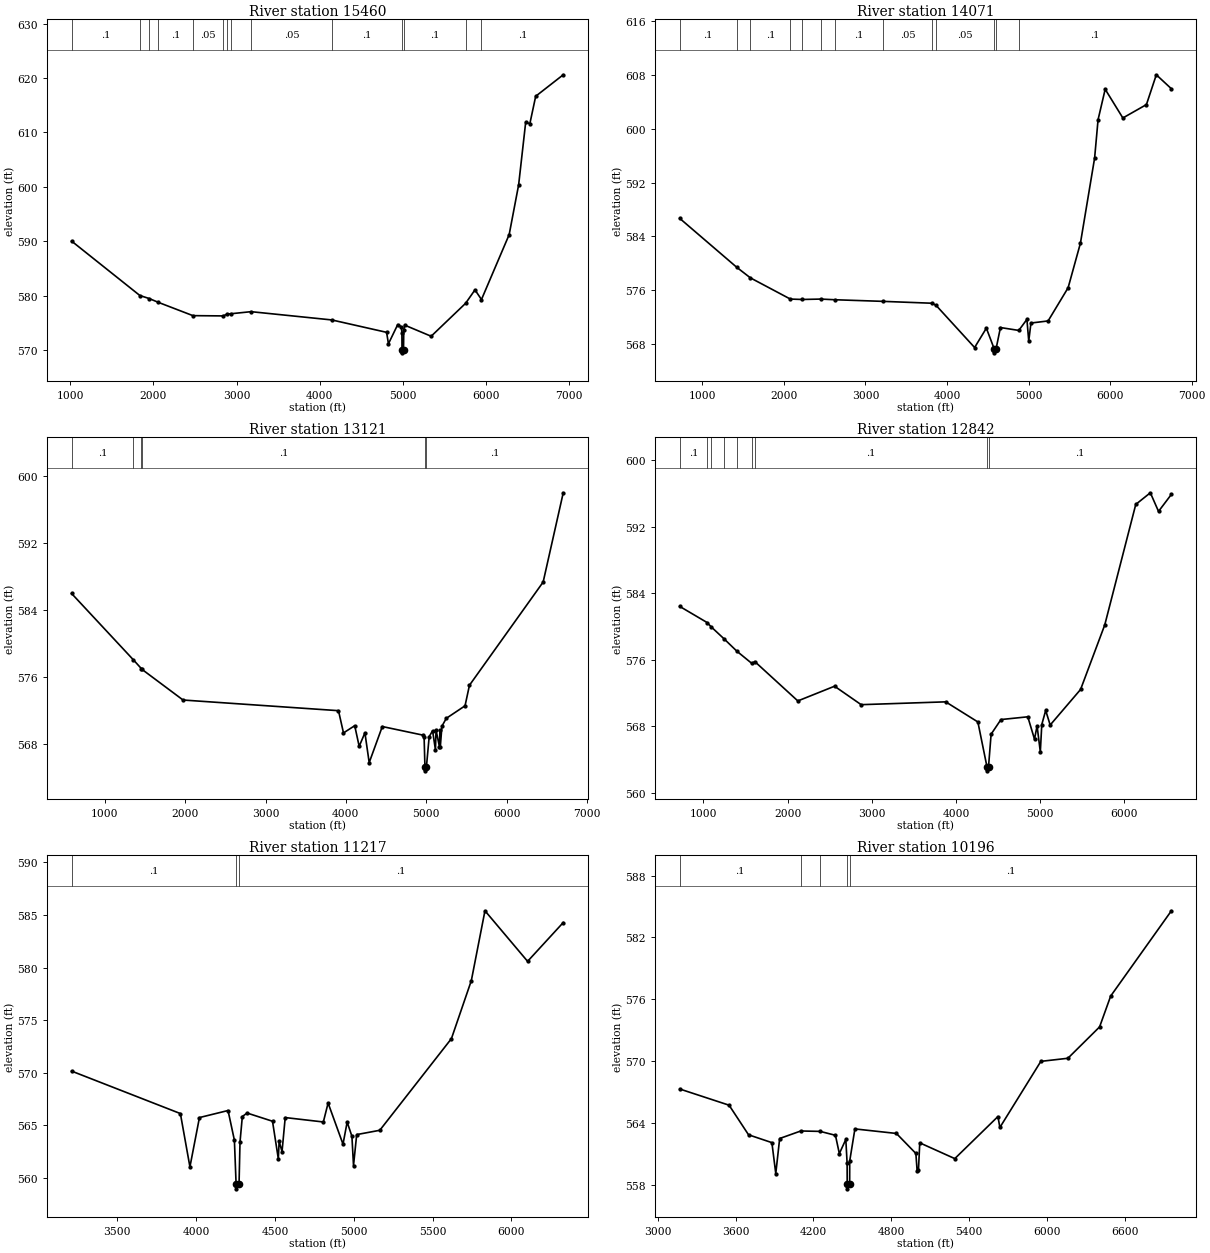
Type RM Length L Ch R = 1,15460,1389,1389,1389
BEGIN DESCRIPTION:
Mapping XS 7ccfb732
END DESCRIPTION:
XS GIS Cut Line= 4
      1969161.94     13544193.53      1967851.18     13541493.88
      1966227.91     13540677.90      1965508.68     13539854.69
#Sta/Elev= 30
  1016.0  590.03  1837.2  580.02  1948.5  579.47  2059.8  578.76  2474.8  576.32
  2838.8  576.27  2885.5  576.60  2932.9  576.67  3174.0  577.05  4144.7  575.53
  4803.4  573.25  4825.7  571.15  4937.3  574.68  4982.0  574.24  4987.6  573.06
  4988.6  569.98  4989.1  569.48  5006.7  569.98  5009.9  573.70  5020.1  574.58
  5339.2  572.53  5753.3  578.59  5866.0  581.06  5944.0  579.28  6277.0  591.22
  6390.9  600.38  6475.4  611.86  6525.7  611.62  6595.9  616.66  6927.0  620.61
#Mann=14,-1,0
  1016.0     0.1       0  1837.2    0.08       0  1948.5    0.05       0
  2059.8     0.1       0  2474.8    0.05       0  2838.8     0.1       0
  2885.5    0.05       0  2932.9     0.1       0  3174.0    0.05       0
  4144.7     0.1       0  4988.6    0.07       0  5006.7     0.1       0
  5753.3    0.05       0  5944.0     0.1       0
Bank Sta=4988.6,5006.7
Exp/Cntr=0.3,0.1

Type RM Length L Ch R = 1,14071,950,950,950
BEGIN DESCRIPTION:
Mapping XS 0782ced8
END DESCRIPTION:
XS GIS Cut Line= 4
      1969361.59     13543967.82      1968458.82     13541632.77
      1967078.61     13539566.79      1966210.52     13538993.86
#Sta/Elev= 30
   723.5  586.67  1423.7  579.39  1590.0  577.83  2079.7  574.68  2223.5  574.62
  2452.8  574.68  2625.8  574.58  3214.4  574.34  3819.8  574.06  3867.6  573.73
  4338.8  567.48  4483.0  570.36  4581.8  567.19  4582.3  566.69  4600.4  567.19
  4655.4  570.45  4880.3  570.02  4980.1  571.66  5002.6  568.44  5029.6  571.12
  5239.9  571.43  5485.2  576.36  5636.3  582.99  5810.2  595.64  5852.4  601.33
  5939.7  605.86  6156.4  601.59  6445.4  603.58  6566.6  608.01  6751.7  605.93
#Mann=13,-1,0
   723.5     0.1       0  1423.7    0.05       0  1590.0     0.1       0
  2079.7    0.05       0  2223.5     0.1       0  2452.8    0.05       0
  2625.8     0.1       0  3214.4    0.05       0  3819.8     0.1       0
  3867.6    0.05       0  4581.8    0.07       0  4600.4    0.05       0
  4880.3     0.1       0
Bank Sta=4581.8,4600.4
Exp/Cntr=0.3,0.1

Type RM Length L Ch R = 1,13121,279,279,279
BEGIN DESCRIPTION:
Mapping XS 6c6886f4
END DESCRIPTION:
XS GIS Cut Line= 2
      1969613.33     13543898.39      1967486.60     13538160.55
#Sta/Elev= 30
   586.1  586.00  1356.3  578.08  1456.3  577.03  1461.6  576.96  1973.8  573.30
  3908.2  572.03  3970.5  569.38  4110.2  570.24  4165.7  567.78  4237.1  569.39
  4290.4  565.84  4453.5  570.14  4962.3  569.11  4973.8  568.89  4984.1  565.36
  4984.6  564.86  5002.9  565.36  5036.9  568.93  5079.3  569.64  5115.0  567.36
  5122.3  569.73  5164.9  567.72  5170.4  569.67  5175.8  567.74  5195.5  570.18
  5250.2  571.12  5483.3  572.61  5538.2  575.06  6455.4  587.36  6705.4  598.00
#Mann=6,-1,0
   586.1     0.1       0  1356.3    0.08       0  1456.3    0.05       0
  1461.6     0.1       0  4984.1    0.07       0  5002.9     0.1       0
Bank Sta=4984.1,5002.9
Exp/Cntr=0.3,0.1

Type RM Length L Ch R = 1,12842,1625,1625,1625
BEGIN DESCRIPTION:
Mapping XS 2e80a77e
END DESCRIPTION:
XS GIS Cut Line= 2
      1969804.30     13543724.79      1967816.46     13538230.01
#Sta/Elev= 30
   718.0  582.43  1043.2  580.49  1089.8  579.99  1240.4  578.57  1398.5  577.03
  1575.1  575.57  1610.6  575.79  2121.5  571.06  2558.0  572.83  2873.9  570.61
  3878.7  570.95  4261.2  568.53  4369.1  563.15  4369.6  562.65  4387.9  563.15
  4418.5  567.06  4535.5  568.82  4854.5  569.15  4934.2  566.46  4964.9  568.06
  5003.4  564.93  5020.8  568.22  5067.2  569.92  5120.4  568.16  5481.9  572.44
  5769.1  580.20  6137.7  594.70  6310.9  596.10  6408.2  593.86  6561.3  595.91
#Mann=9,-1,0
   718.0     0.1       0  1043.2    0.08       0  1089.8     0.1       0
  1240.4    0.08       0  1398.5     0.1       0  1575.1    0.08       0
  1610.6     0.1       0  4369.1    0.07       0  4387.9     0.1       0
Bank Sta=4369.1,4387.9
Exp/Cntr=0.3,0.1

Type RM Length L Ch R = 1,11217,1021,1021,1021
BEGIN DESCRIPTION:
Horse Creek 3.0
END DESCRIPTION:
XS GIS Cut Line= 3
      1969301.18     13540900.18      1969061.61     13538962.72
      1968484.30     13537948.54
#Sta/Elev= 30
  3210.1  570.15  3900.5  566.11  3961.0  561.04  4021.4  565.73  4202.8  566.40
  4243.1  563.58  4253.8  559.45  4254.3  558.95  4272.7  559.45  4278.7  563.40
  4293.5  565.83  4323.7  566.16  4484.9  565.38  4521.8  561.81  4526.9  563.46
  4545.4  562.50  4565.5  565.73  4807.4  565.31  4837.6  567.11  4932.1  563.20
  4958.5  565.30  4988.7  563.95  4998.8  561.17  5019.0  564.11  5165.5  564.52
  5620.0  573.24  5746.3  578.76  5832.7  585.40  6103.2  580.59  6329.3  584.28
#Mann=3,-1,0
  3210.1     0.1       0  4253.8    0.07       0  4272.7     0.1       0
Bank Sta=4253.8,4272.7
Exp/Cntr=0.3,0.1

Type RM Length L Ch R = 1,10196,1905,1905,1905
BEGIN DESCRIPTION:
Horse Creek 2.0
END DESCRIPTION:
XS GIS Cut Line= 3
      1969848.06     13540905.39      1969889.73     13538764.81
      1968947.01     13537410.62
#Sta/Elev= 30
  3168.8  567.30  3549.3  565.73  3699.3  562.86  3879.3  562.10  3909.3  559.10
  3939.3  562.50  4102.3  563.23  4252.1  563.19  4369.4  562.81  4399.4  561.04
  4449.4  562.41  4459.4  560.09  4460.0  558.12  4460.5  557.62  4478.9  558.12
  4479.4  560.32  4519.4  563.43  4839.5  562.99  4989.5  561.05  4999.5  559.31
  5009.5  559.45  5019.5  562.08  5289.6  560.55  5622.3  564.63  5637.2  563.57
  5953.1  569.98  6161.7  570.28  6406.0  573.32  6491.5  576.31  6959.8  584.58
#Mann=5,-1,0
  3168.8     0.1       0  4102.3    0.16       0  4252.1     0.1       0
  4460.0    0.07       0  4478.9     0.1       0
Bank Sta=4460,4478.9
Exp/Cntr=0.3,0.1

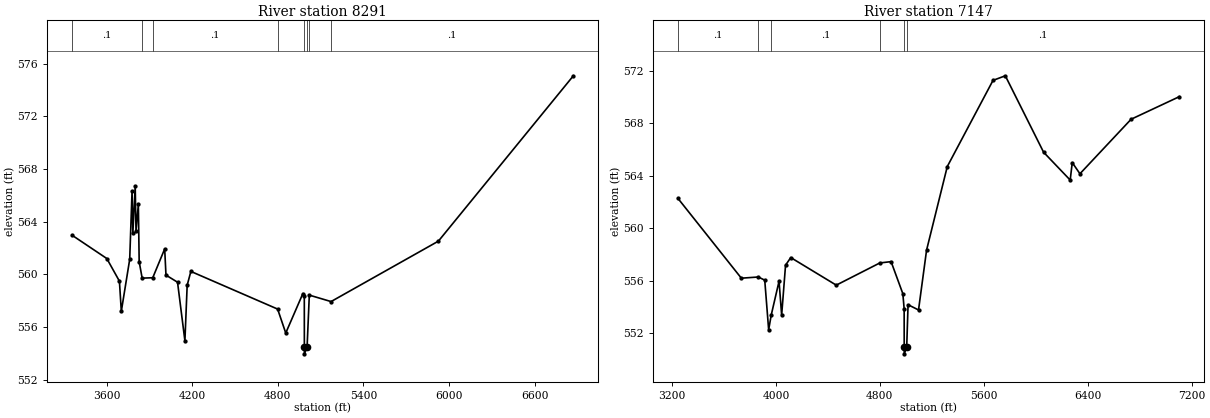
Type RM Length L Ch R = 1,8291,1144,1144,1144
BEGIN DESCRIPTION:
Mapping XS 7c7e0425
END DESCRIPTION:
XS GIS Cut Line= 4
      1970535.55     13540491.83      1970910.56     13539767.85
      1970863.69     13538278.26      1970223.05     13537252.20
#Sta/Elev= 30
  3357.2  562.98  3600.9  561.21  3689.4  559.49  3702.7  557.20  3761.5  561.15
  3778.0  566.33  3783.6  563.15  3800.1  566.69  3805.7  563.30  3822.2  565.34
  3827.9  560.97  3848.8  559.72  3923.1  559.75  4006.8  561.94  4015.8  559.95
  4096.9  559.41  4148.6  554.96  4164.5  559.18  4190.4  560.23  4798.7  557.37
  4855.7  555.55  4975.8  558.55  4985.8  558.37  4986.2  554.47  4986.7  553.97
  5005.3  554.47  5020.9  558.43  5173.4  557.94  5926.1  562.53  6872.5  575.09
#Mann=8,-1,0
  3357.2     0.1       0  3848.8    0.16       0  3923.1     0.1       0
  4798.7    0.12       0  4986.2    0.07       0  5005.3    0.12       0
  5020.9    0.16       0  5173.4     0.1       0
Bank Sta=4986.2,5005.3
Exp/Cntr=0.3,0.1

Type RM Length L Ch R = 1,7147,1081,1081,1081
BEGIN DESCRIPTION:
Mapping XS d068736f
END DESCRIPTION:
XS GIS Cut Line= 4
      1971493.90     13541002.21      1971447.02     13539679.30
      1971572.02     13538523.05      1970894.95     13537330.36
#Sta/Elev= 30
  3246.6  562.26  3734.1  556.19  3864.4  556.28  3914.2  556.04  3944.3  552.26
  3964.0  553.38  4024.3  555.96  4044.3  553.37  4074.3  557.18  4114.4  557.76
  4464.6  555.66  4799.9  557.35  4886.5  557.45  4977.0  555.01  4987.1  553.85
  4987.5  550.93  4988.0  550.43  5006.7  550.93  5017.2  554.17  5097.7  553.77
  5159.7  558.33  5319.0  564.69  5671.0  571.25  5765.6  571.60  6060.2  565.78
  6264.9  563.66  6280.8  564.99  6339.9  564.14  6733.6  568.29  7104.8  570.01
#Mann=6,-1,0
  3246.6     0.1       0  3864.4    0.12       0  3964.0     0.1       0
  4799.9    0.12       0  4987.5    0.07       0  5006.7     0.1       0
Bank Sta=4987.5,5006.7
Exp/Cntr=0.3,0.1