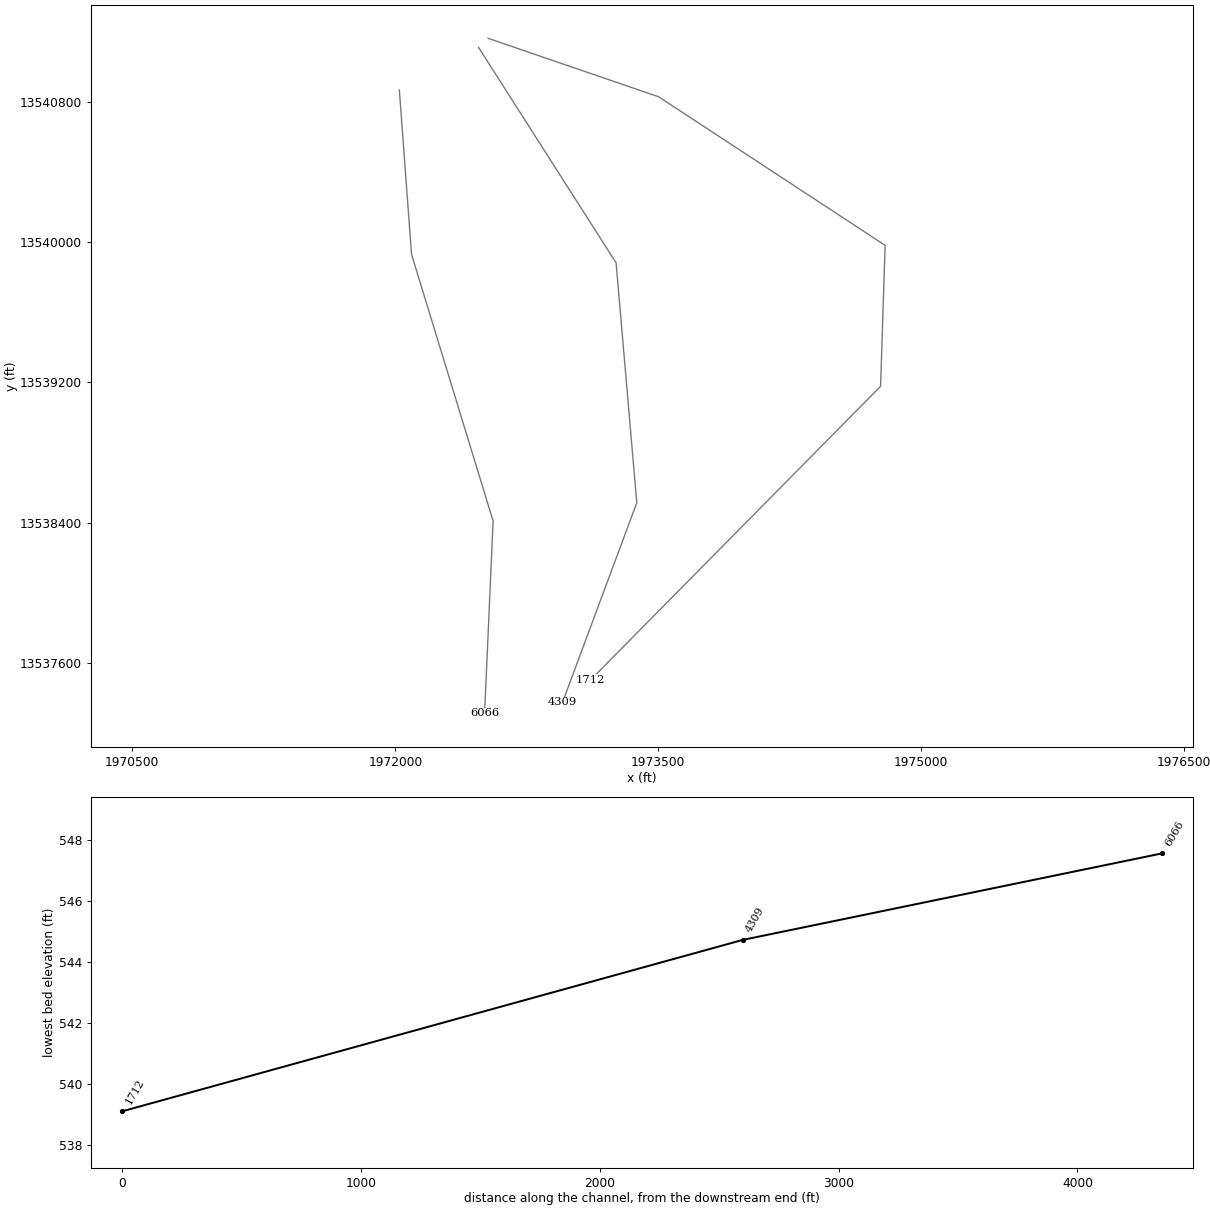
HEC-RAS study Horse Creek.prj: Horse Creek Base Level Engineering

--- Horse Creek.g01 (geometry) --- (continued)

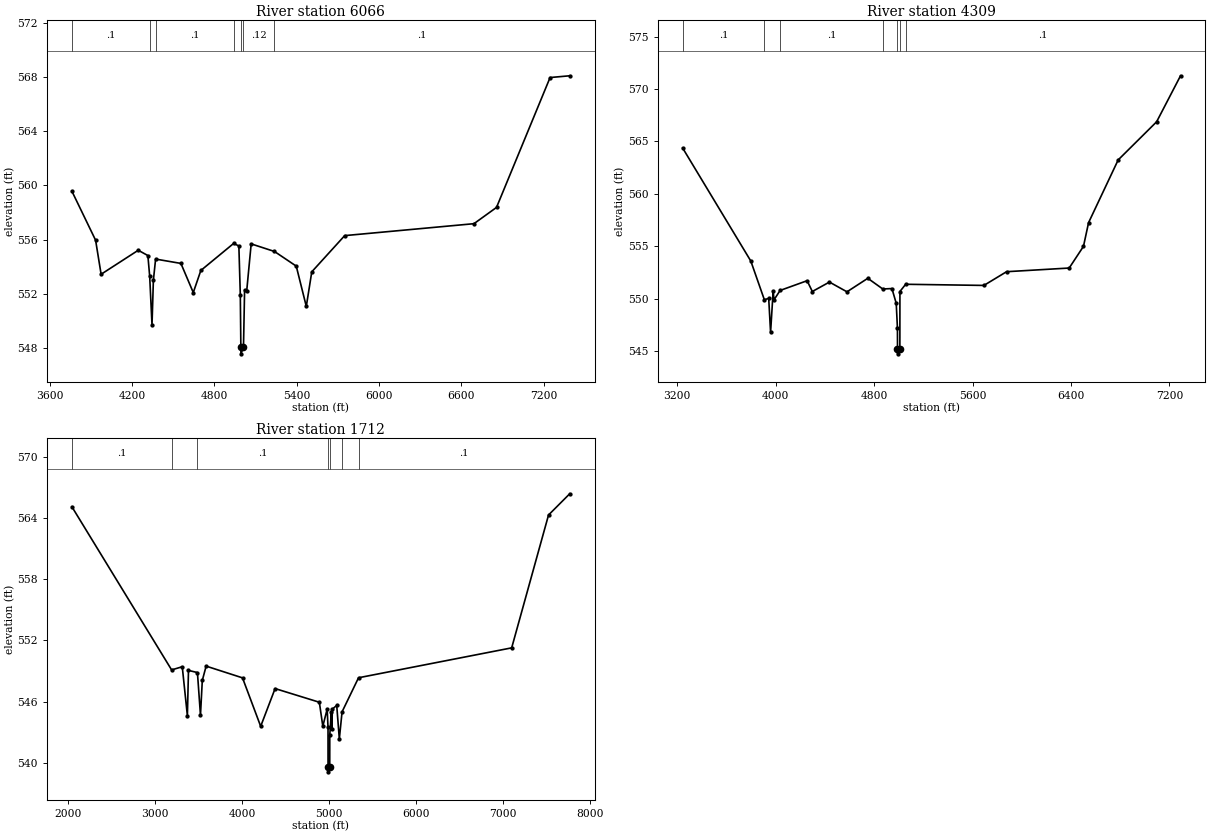
Type RM Length L Ch R = 1,6066,1757,1757,1757
BEGIN DESCRIPTION:
Mapping XS 78b0d906
END DESCRIPTION:
XS GIS Cut Line= 4
      1972023.02     13540867.51      1972092.47     13539929.99
      1972557.74     13538409.15      1972509.13     13537311.94
#Sta/Elev= 30
  3761.4  559.57  3934.4  555.95  3974.5  553.44  4245.2  555.21  4315.4  554.82
  4328.6  553.29  4345.5  549.70  4355.5  552.99  4371.7  554.56  4556.1  554.24
  4646.3  552.09  4701.5  553.72  4940.1  555.71  4978.6  555.53  4989.1  551.94
  4993.1  548.07  4993.6  547.57  5012.3  548.07  5020.4  552.28  5035.5  552.18
  5068.3  555.68  5238.2  555.12  5396.9  554.04  5470.1  551.07  5510.1  553.62
  5750.0  556.29  6692.1  557.17  6856.6  558.37  7247.0  567.95  7390.2  568.08
#Mann=7,-1,0
  3761.4     0.1       0  4328.6    0.12       0  4371.7     0.1       0
  4940.1    0.12       0  4993.1    0.07       0  5012.3    0.12       0
  5238.2     0.1       0
Bank Sta=4993.1,5012.3
Exp/Cntr=0.3,0.1

Type RM Length L Ch R = 1,4309,2597,2597,2597
BEGIN DESCRIPTION:
Mapping XS b44945d0
END DESCRIPTION:
XS GIS Cut Line= 4
      1972474.43     13541110.51      1973259.13     13539881.38
      1973377.19     13538513.32      1972953.58     13537374.45
#Sta/Elev= 30
  3243.8  564.37  3797.5  553.59  3907.5  549.90  3943.1  550.02  3958.3  546.78
  3979.4  550.75  3985.9  549.88  4035.8  550.78  4255.3  551.71  4297.6  550.68
  4436.7  551.58  4579.3  550.65  4748.6  551.94  4870.2  550.92  4944.6  550.96
  4979.5  549.56  4989.5  547.17  4989.9  545.23  4990.4  544.73  5009.1  545.23
  5009.6  550.68  5056.2  551.37  5692.1  551.26  5876.5  552.57  6385.4  552.92
  6501.5  554.99  6542.9  557.25  6783.6  563.24  7096.1  566.88  7290.3  571.27
#Mann=7,-1,0
  3243.8     0.1       0  3907.5    0.12       0  4035.8     0.1       0
  4870.2    0.12       0  4989.9    0.07       0  5009.1    0.12       0
  5056.2     0.1       0
Bank Sta=4989.9,5009.1
Exp/Cntr=0.3,0.1

Type RM Length L Ch R = 1,1712,0,0,0
BEGIN DESCRIPTION:
Horse Creek 1.0
END DESCRIPTION:
XS GIS Cut Line= 5
      1972529.58     13541161.86      1973501.84     13540828.51
      1974793.51     13539981.29      1974767.53     13539177.28
      1973112.95     13537502.12
#Sta/Elev= 30
  2040.5  565.09  3188.8  549.10  3311.3  549.41  3370.3  544.61  3383.0  549.05
  3486.0  548.84  3521.0  544.66  3542.1  548.07  3586.3  549.47  4004.9  548.32
  4214.2  543.57  4380.0  547.27  4889.5  545.93  4929.5  543.58  4979.5  545.26
  4989.5  543.47  4989.8  539.61  4990.3  539.11  5009.3  539.61  5009.5  542.70
  5027.9  545.00  5032.9  543.30  5039.6  545.26  5089.6  545.62  5119.6  542.33
  5151.1  544.99  5340.7  548.33  7103.8  551.26  7528.1  564.28  7772.0  566.36
#Mann=7,-1,0
  2040.5     0.1       0  3188.8    0.12       0  3486.0     0.1       0
  4989.8    0.07       0  5009.3     0.1       0  5151.1    0.12       0
  5340.7     0.1       0
Bank Sta=4989.8,5009.3
Exp/Cntr=0.3,0.1

Chan Stop Cuts=-1