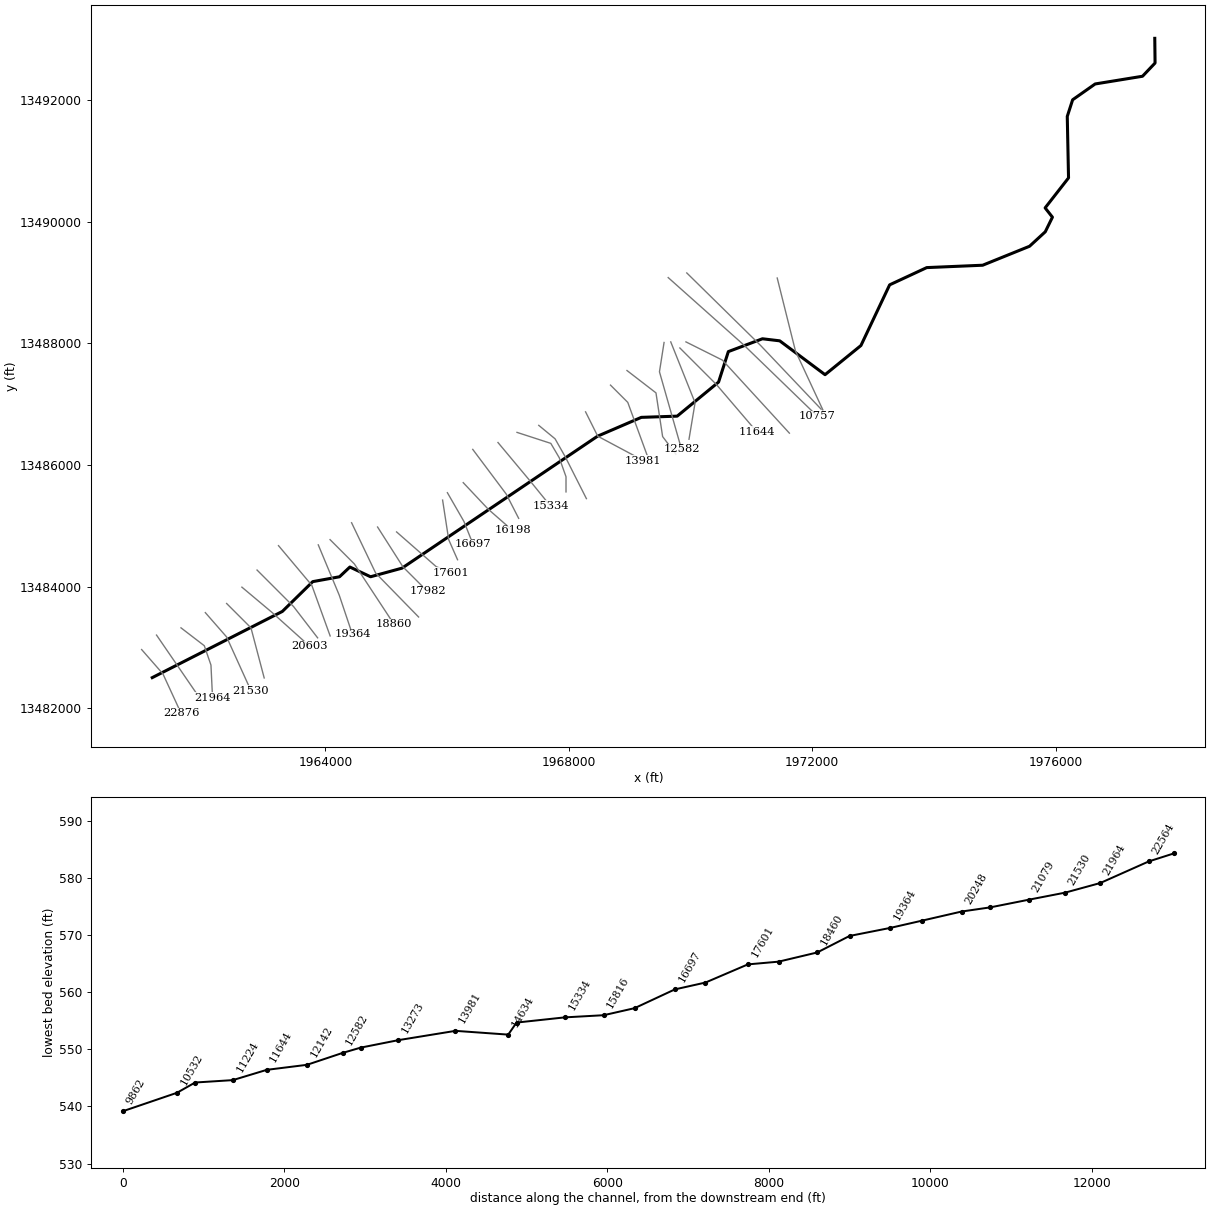
--- UNT 001 in BCW.prj (project) ---

Proj Title=UNT 001 in BCW Base Level Engineering
Current Plan=p01
Default Exp/Contr=0.3,0.1
English Units
Geom File=g01
Flow File=f01
Plan File=p01
Y Axis Title=Elevation
X Axis Title(PF)=Main Channel Distance
X Axis Title(XS)=Station
BEGIN DESCRIPTION:
UNT 001 in BCW
END DESCRIPTION:
DSS File=dss
DSS Export Rating Curves= 0
DSS Export Rating Curve Sorted= 0
DSS Export Volume Flow Curves= 0
DXF OffsetX= 0
DXF OffsetY= 0
DXF ScaleX= 1
DXF ScaleY= 10

--- UNT 001 in BCW.p01 (plan) ---

Plan Title=Multiple Run
Program Version=5.05
Short Identifier=Multiple Run
Geom File=g01
Flow File=f01
Subcritical Flow
K Sum by GR= 0
Std Step Tol= 0.01
Critical Tol= 0.01
Num of Std Step Trials= 20
Max Error Tol= 0.3
Flow Tol Ratio= 0.001
Split Flow NTrial= 30
Split Flow Tol= 0.02
Split Flow Ratio= 0.02
Log Output Level= 0
Friction Slope Method= 1
Unsteady Friction Slope Method= 2
Unsteady Bridges Friction Slope Method= 1
Parabolic Critical Depth
Global Vel Dist= 1 , 1 , 1
Global Log Level= 0
CheckData=True
Encroach Param=-1 ,0,0, 0
BEGIN DESCRIPTION:
Multiple Run
END DESCRIPTION:
Computation Interval=1MIN
Output Interval=1HOUR
Instantaneous Interval=1HOUR
Mapping Interval=1HOUR
Computation Time Step Use Courant=        0
Computation Time Step Use Time Series=    0
Computation Time Step Count To Double=0
Computation Time Step Max Doubling=0
Computation Time Step Max Halving=0
Computation Time Step Residence Courant=0
Run HTab= 0
Run UNet= 0
Run Sediment= 0
Run PostProcess= 0
Run WQNet= 0
Run RASMapper= 0
UNET Theta= 1
UNET Theta Warmup= 1
UNET ZTol= 0.02
UNET ZSATol= 0.02
UNET MxIter= 20
UNET Max Iter WO Improvement= 0
UNET MaxInSteps= 0
UNET DtIC= 0
UNET DtMin= 0
UNET MaxCRTS= 20
UNET WFStab= 2
UNET SFStab= 1
UNET WFX= 1
UNET SFX= 1
UNET 1D Methodology=Finite Difference
UNET DSS MLevel= 4
UNET Pardiso=0
UNET DZMax Abort= 100
UNET Use Existing IB Tables=-1
UNET Froude Reduction=False
UNET Froude Limit= 0.8
UNET Froude Power= 4
UNET D1 Cores= 0
UNET D2 Coriolis=0
UNET D2 Cores= 0
UNET D2 Theta= 1
UNET D2 Theta Warmup= 1
UNET D2 Z Tol= 0.01
UNET D2 Volume Tol= 0.01
UNET D2 Max Iterations= 20
UNET D2 Equation= 0
UNET D2 RampUpFraction=0.1
UNET D2 TimeSlices= 1
UNET D2 BCVolumeCheck=0
UNET D1D2 MaxIter= 0
UNET D1D2 ZTol=0.01
UNET D1D2 QTol=0.1
UNET D1D2 MinQTol=1
DSS File=dss
Write IC File= 0
Write IC File at Fixed DateTime=0
Write IC File at Sim End=0
Echo Input=False
Echo Parameters=False
Echo Output=False
Write Detailed= 0
HDF Write Warmup=0
HDF Write Time Slices=0
HDF Flush=0
HDF Face Node Velocities=0
HDF Compression= 1
HDF Chunk Size= 1
HDF Spatial Parts= 1
HDF Use Max Rows=0
HDF Fixed Rows= 1
Calibration Method= 0
Calibration Iterations= 20
Calibration Max Change=0.05
Calibration Tolerance=0.2
Calibration Maximum=1.5
Calibration Minimum=0.5
Calibration Optimization Method= 1
WQ AD Non Conservative
WQ ULTIMATE=-1
WQ Max Comp Step=1HOUR
WQ Output Interval=15MIN
WQ Output Selected Increments= 0
WQ Output face flow=0
WQ Output face velocity=0
WQ Output face area=0
WQ Output face dispersion=0
WQ Output cell volume=0
WQ Output cell surface area=0
WQ Output cell continuity=0
WQ Output cumulative cell continuity=0
WQ Output face conc=0
WQ Output face dconc_dx=0
WQ Output face courant=0
WQ Output face peclet=0
WQ Output face adv mass=0
WQ Output face disp mass=0
WQ Output cell mass=0
WQ Output cell source sink temp=0
WQ Output nsm pathways=0
WQ Output nsm derived pathways=0
WQ Output MaxMinRange=-1
WQ Daily Max Min Mean=-1
WQ Daily Range=0
WQ Daily Time=0
WQ Create Restart=0
WQ Fixed Restart=0
WQ System Summary=0
WQ Write To DSS=0
WQ Use Fixed Temperature=0
Sorting and Armoring Iterations= 10
XS Update Threshold= 0.02
Bed Roughness Predictor= 0
Hydraulics Update Threshold= 0.02
Energy Slope Method= 1
Volume Change Method= 1
Sediment Retention Method= 0
XS Weighting Method= 0
Number of US Weighted Cross Sections= 1
Number of DS Weighted Cross Sections= 1
Upstream XS Weight=0
Main XS Weight=1
Downstream XS Weight=0
Number of DS XS's Weighted with US Boundary= 1
Upstream Boundary Weight= 1
Weight of XSs Associated with US Boundary= 0
Number of US XS's Weighted with DS Boundary= 1
Downstream Boundary Weight= 0.5
Weight of XSs Associated with DS Boundary= 0.5
Percentile Method= 0
Sediment Output Level= 3
Mass or Volume Output= 0
Output Increment Type= 1
Profile and TS Output Increment= 1
XS Output Flag= 0
XS Output Increment= 10
Write Gradation File= 0
Read Gradation Hotstart= 0
Write HDF5 File= 1
Write Binary Output= 1
Write DSS Sediment File= 0
SV Curve= 0
Specific Gage Flag= 0

--- UNT 001 in BCW.f01 (steady flow) ---

Flow Title=Multiple
Program Version=5.05
Number of Profiles= 7
Profile Names=10-year,25-year,50-year,1pct_min,100-year,1pct_plu,500-year
River Rch & RM=UNT 001 in BCW,Reach-1         ,22876
     150     206     252     155     309     617     473
River Rch & RM=UNT 001 in BCW,Reach-1         ,22564
     159     219     268     165     329     655     502
River Rch & RM=UNT 001 in BCW,Reach-1         ,20248
     224     313     388     241     480     958     747
River Rch & RM=UNT 001 in BCW,Reach-1         ,17076
     343     489     613     384     767    1530    1221
River Rch & RM=UNT 001 in BCW,Reach-1         ,16198
     477     685     864     543    1083    2161    1733
River Rch & RM=UNT 001 in BCW,Reach-1         ,5493
     619     898    1139     719    1434    2862    2317
River Rch & RM=UNT 001 in BCW,Reach-1         ,2362
     641     929    1179     744    1485    2962    2397
Boundary for River Rch & Prof#=UNT 001 in BCW,Reach-1         , 1
Up Type= 0
Dn Type= 3
Dn Slope=0.00467
Boundary for River Rch & Prof#=UNT 001 in BCW,Reach-1         , 2
Up Type= 0
Dn Type= 3
Dn Slope=0.00467
Boundary for River Rch & Prof#=UNT 001 in BCW,Reach-1         , 3
Up Type= 0
Dn Type= 3
Dn Slope=0.00467
Boundary for River Rch & Prof#=UNT 001 in BCW,Reach-1         , 4
Up Type= 0
Dn Type= 3
Dn Slope=0.00467
Boundary for River Rch & Prof#=UNT 001 in BCW,Reach-1         , 5
Up Type= 0
Dn Type= 3
Dn Slope=0.00467
Boundary for River Rch & Prof#=UNT 001 in BCW,Reach-1         , 6
Up Type= 0
Dn Type= 3
Dn Slope=0.00467
Boundary for River Rch & Prof#=UNT 001 in BCW,Reach-1         , 7
Up Type= 0
Dn Type= 3
Dn Slope=0.00467
DSS Import GetInterval= 0
DSS Import GetPeak= 0
DSS Import FillOption= 0

--- UNT 001 in BCW.g01 (geometry) ---

Geom Title=Existing Conditions

River Reach=UNT 001 in BCW,Reach-1
Reach XY= 30
      1961152.54     13482506.64      1963290.80     13483594.54
      1963790.80     13484084.54      1964230.80     13484164.54
      1964400.80     13484324.54      1964740.80     13484164.54
      1965258.06     13484306.25      1968470.80     13486474.54
      1969190.80     13486784.54      1969780.80     13486804.54
      1970461.01     13487364.54      1970621.60     13487865.40
      1971182.36     13488076.34      1971466.22     13488042.49
      1972211.18     13487485.98      1972801.13     13487965.35
      1973273.01     13488962.75      1973882.38     13489246.08
      1974801.91     13489285.14      1975572.75     13489597.12
      1975830.80     13489834.54      1975948.70     13490074.81
      1975828.57     13490227.59      1976213.29     13490720.64
      1976192.45     13491731.06      1976280.80     13492004.54
      1976650.80     13492264.54      1977429.40     13492391.27
      1977635.65     13492608.63      1977630.80     13493014.54

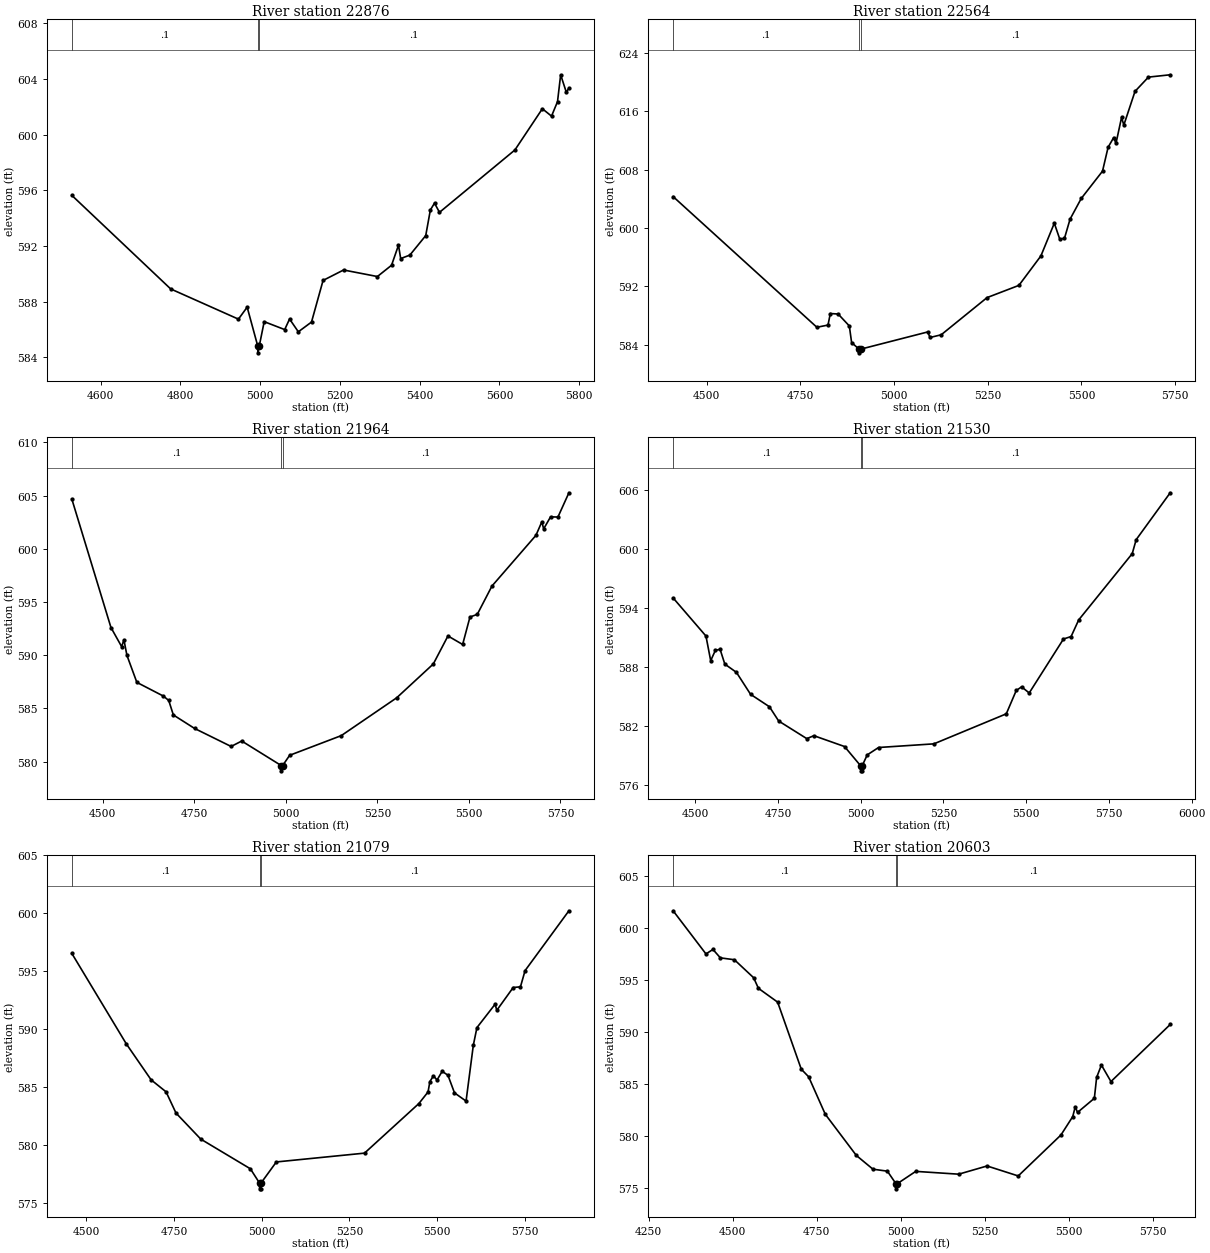
Type RM Length L Ch R = 1,22876,312,312,312
BEGIN DESCRIPTION:
UNT 001 in BCW 43.0
END DESCRIPTION:
XS GIS Cut Line= 3
      1960978.13     13482968.04      1961328.13     13482568.06
      1961627.67     13481919.04
#Sta/Elev= 30
  4527.9  595.64  4775.7  588.92  4945.6  586.75  4967.5  587.61  4993.9  584.83
  4994.2  584.33  4997.9  584.83  5010.2  586.57  5061.6  586.00  5073.8  586.76
  5095.8  585.84  5128.8  586.54  5157.8  589.53  5209.2  590.28  5294.0  589.81
  5329.5  590.62  5346.9  592.06  5352.4  591.10  5375.4  591.35  5415.2  592.75
  5426.8  594.59  5437.2  595.08  5449.7  594.42  5638.8  598.90  5707.6  601.86
  5730.6  601.33  5745.6  602.37  5753.5  604.30  5767.6  603.05  5774.2  603.34
#Mann=3,-1,0
  4527.9     0.1       0  4993.9    0.07       0  4997.9     0.1       0
Bank Sta=4993.9,4997.9
Exp/Cntr=0.3,0.1

Type RM Length L Ch R = 1,22564,600,600,600
BEGIN DESCRIPTION:
Mapping XS fff17b8e
END DESCRIPTION:
XS GIS Cut Line= 2
      1961222.80     13483205.82      1961972.80     13482112.06
#Sta/Elev= 30
  4410.7  604.30  4794.2  586.42  4823.9  586.72  4830.1  588.30  4851.0  588.23
  4880.8  586.60  4886.9  584.33  4906.8  583.42  4907.1  582.92  4910.8  583.42
  5090.0  585.78  5096.1  585.02  5125.9  585.39  5248.3  590.48  5333.2  592.15
  5391.9  596.18  5427.7  600.66  5442.3  598.47  5454.8  598.59  5469.7  601.21
  5499.5  604.04  5556.3  607.78  5571.2  611.05  5586.1  612.38  5592.2  611.58
  5607.1  615.13  5613.2  614.09  5643.0  618.70  5678.8  620.65  5736.9  620.97
#Mann=3,-1,0
  4410.7     0.1       0  4906.8    0.07       0  4910.8     0.1       0
Bank Sta=4906.8,4910.8
Exp/Cntr=0.3,0.1

Type RM Length L Ch R = 1,21964,434,434,434
BEGIN DESCRIPTION:
UNT 001 in BCW 42.0
END DESCRIPTION:
XS GIS Cut Line= 4
      1961625.01     13483324.99      1962008.11     13483030.94
      1962117.48     13482713.23      1962143.52     13482175.00
#Sta/Elev= 30
  4415.5  604.67  4522.4  592.60  4551.5  590.81  4557.8  591.44  4566.0  589.99
  4593.1  587.45  4665.7  586.16  4680.2  585.75  4692.8  584.39  4750.9  583.12
  4850.6  581.43  4879.6  581.94  4987.3  579.64  4987.5  579.14  4991.4  579.64
  5010.5  580.60  5151.6  582.45  5302.8  586.00  5402.9  589.18  5442.9  591.81
  5483.0  591.01  5503.0  593.59  5523.0  593.84  5563.1  596.50  5683.2  601.26
  5699.3  602.53  5704.3  601.87  5723.2  603.00  5743.3  602.98  5773.3  605.26
#Mann=3,-1,0
  4415.5     0.1       0  4987.3    0.07       0  4991.4     0.1       0
Bank Sta=4987.3,4991.4
Exp/Cntr=0.3,0.1

Type RM Length L Ch R = 1,21530,451,451,451
BEGIN DESCRIPTION:
UNT 001 in BCW 41.0
END DESCRIPTION:
XS GIS Cut Line= 3
      1962024.97     13483575.03      1962375.00     13483175.00
      1962775.47     13482291.36
#Sta/Elev= 30
  4433.5  595.02  4532.7  591.15  4547.0  588.65  4561.2  589.70  4575.4  589.80
  4589.7  588.30  4624.8  587.46  4667.5  585.23  4724.4  583.97  4752.4  582.52
  4837.4  580.73  4858.7  581.03  4951.3  579.93  5000.3  577.96  5000.6  577.46
  5004.3  577.46  5004.5  577.96  5019.9  579.08  5054.1  579.83  5221.2  580.20
  5440.0  583.25  5470.1  585.62  5486.2  585.99  5509.3  585.37  5612.8  590.85
  5635.8  591.10  5658.8  592.79  5820.5  599.52  5832.4  600.94  5935.2  605.70
#Mann=3,-1,0
  4433.5     0.1       0  5000.3    0.07       0  5004.5     0.1       0
Bank Sta=5000.3,5004.5
Exp/Cntr=0.3,0.1

Type RM Length L Ch R = 1,21079,476,476,476
BEGIN DESCRIPTION:
UNT 001 in BCW 40.0
END DESCRIPTION:
XS GIS Cut Line= 3
      1962375.02     13483724.98      1962775.00     13483325.00
      1962992.49     13482501.39
#Sta/Elev= 30
  4458.2  596.53  4613.7  588.72  4684.4  585.62  4726.9  584.59  4755.2  582.76
  4825.9  580.51  4967.3  577.95  4993.4  576.72  4993.7  576.22  4997.4  576.22
  4997.7  576.72  5041.4  578.54  5292.8  579.30  5447.9  583.58  5474.0  584.58
  5479.2  585.47  5489.3  585.97  5499.6  585.61  5514.3  586.36  5530.7  586.02
  5549.4  584.50  5582.4  583.79  5603.1  588.61  5613.4  590.13  5665.0  592.14
  5670.2  591.63  5716.8  593.59  5737.5  593.65  5750.7  595.05  5875.7  600.21
#Mann=3,-1,0
  4458.2     0.1       0  4993.4    0.07       0  4997.7     0.1       0
Bank Sta=4993.4,4997.7
Exp/Cntr=0.3,0.1

Type RM Length L Ch R = 1,20603,355,355,355
BEGIN DESCRIPTION:
UNT 001 in BCW 39.0
END DESCRIPTION:
XS GIS Cut Line= 3
      1962626.15     13483993.62      1963125.00     13483575.00
      1963740.84     13483021.87
#Sta/Elev= 30
  4323.1  601.63  4420.8  597.48  4441.6  597.91  4463.7  597.10  4505.4  596.92
  4562.6  595.19  4576.9  594.17  4634.1  592.84  4704.4  586.39  4726.3  585.66
  4775.9  582.05  4868.3  578.09  4917.7  576.77  4960.6  576.58  4985.9  575.38
  4986.2  574.88  4990.3  575.38  5045.0  576.56  5172.8  576.29  5257.2  577.08
  5349.9  576.12  5477.0  580.06  5512.1  581.83  5519.6  582.78  5526.3  582.23
  5576.4  583.59  5583.2  585.60  5597.4  586.79  5625.8  585.20  5802.1  590.69
#Mann=3,-1,0
  4323.1     0.1       0  4985.9    0.07       0  4990.3     0.1       0
Bank Sta=4985.9,4990.3
Exp/Cntr=0.3,0.1

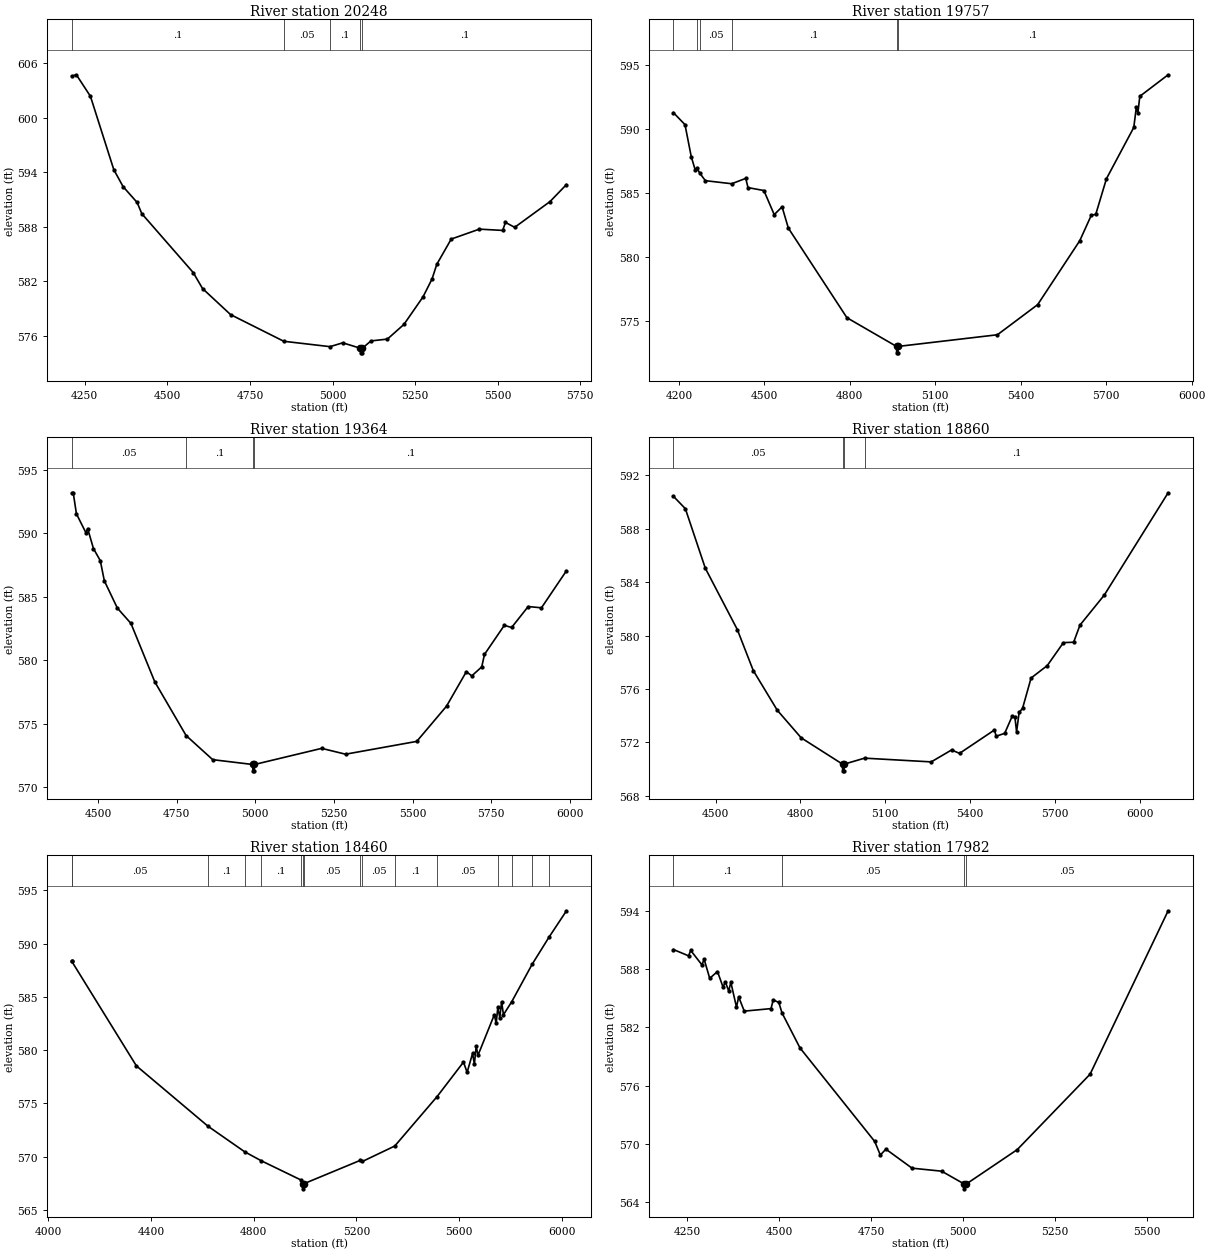
Type RM Length L Ch R = 1,20248,491,491,491
BEGIN DESCRIPTION:
UNT 001 in BCW 38.0
END DESCRIPTION:
XS GIS Cut Line= 3
      1962875.01     13484274.99      1963475.00     13483675.00
      1963870.60     13483160.78
#Sta/Elev= 30
  4210.7  604.56  4224.8  604.70  4267.3  602.34  4338.0  594.28  4366.2  592.41
  4408.7  590.67  4422.8  589.44  4578.4  582.97  4606.7  581.21  4691.5  578.35
  4852.5  575.42  4992.3  574.83  5030.9  575.25  5084.6  574.65  5085.0  574.15
  5089.6  574.15  5090.0  574.65  5116.3  575.46  5166.1  575.66  5216.0  577.27
  5273.7  580.29  5301.1  582.26  5315.6  583.88  5359.2  586.65  5444.3  587.74
  5515.0  587.60  5523.2  588.48  5551.3  587.94  5658.2  590.77  5708.0  592.64
#Mann=5,-1,0
  4210.7     0.1       0  4852.5    0.05       0  4992.3     0.1       0
  5084.6    0.07       0  5090.0     0.1       0
Bank Sta=5084.6,5090
Exp/Cntr=0.3,0.1

Type RM Length L Ch R = 1,19757,393,393,393
BEGIN DESCRIPTION:
UNT 001 in BCW 37.0
END DESCRIPTION:
XS GIS Cut Line= 3
      1963227.70     13484675.94      1963775.00     13484025.00
      1964076.67     13483191.56
#Sta/Elev= 30
  4180.6  591.29  4221.4  590.35  4243.5  587.84  4257.8  586.78  4263.2  586.99
  4272.5  586.59  4292.9  585.98  4385.4  585.74  4434.7  586.16  4442.5  585.44
  4498.4  585.21  4534.6  583.33  4562.2  583.94  4584.2  582.28  4789.8  575.29
  4964.0  573.05  4964.4  572.55  4969.0  572.55  4969.4  573.05  5318.2  573.96
  5459.4  576.31  5607.3  581.30  5647.9  583.29  5663.3  583.35  5701.0  586.14
  5796.8  590.13  5805.9  591.73  5811.2  591.27  5818.0  592.56  5917.4  594.24
#Mann=6,-1,0
  4180.6    0.05       0  4263.2     0.1       0  4272.5    0.05       0
  4385.4     0.1       0  4964.0    0.07       0  4969.4     0.1       0
Bank Sta=4964,4969.4
Exp/Cntr=0.3,0.1

Type RM Length L Ch R = 1,19364,504,504,504
BEGIN DESCRIPTION:
UNT 001 in BCW 36.0
END DESCRIPTION:
XS GIS Cut Line= 3
      1963881.39     13484688.88      1964225.99     13483862.32
      1964441.98     13483219.56
#Sta/Elev= 30
  4416.0  593.18  4420.8  593.18  4431.0  591.52  4461.2  590.03  4466.7  590.36
  4485.1  588.79  4506.9  587.83  4519.7  586.25  4561.1  584.10  4604.4  582.89
  4680.2  578.29  4779.8  574.06  4864.4  572.16  4991.6  571.78  4992.1  571.28
  4996.8  571.28  4997.2  571.78  5211.1  573.05  5286.9  572.59  5513.4  573.60
  5608.0  576.37  5671.1  579.09  5688.5  578.76  5720.1  579.47  5728.8  580.45
  5791.9  582.74  5815.1  582.57  5867.8  584.22  5910.0  584.12  5989.6  587.04
#Mann=4,-1,0
  4416.0    0.05       0  4779.8     0.1       0  4991.6    0.07       0
  4997.2     0.1       0
Bank Sta=4991.6,4997.2
Exp/Cntr=0.3,0.1

Type RM Length L Ch R = 1,18860,400,400,400
BEGIN DESCRIPTION:
UNT 001 in BCW 35.0
END DESCRIPTION:
XS GIS Cut Line= 3
      1964075.00     13484775.00      1964475.00     13484375.00
      1965126.18     13483384.21
#Sta/Elev= 30
  4350.0  590.43  4392.4  589.50  4463.1  585.04  4576.3  580.45  4632.8  577.38
  4717.7  574.41  4802.5  572.34  4948.8  570.37  4949.2  569.87  4953.9  569.87
  4954.4  570.37  5026.8  570.82  5262.7  570.54  5334.5  571.43  5363.1  571.18
  5486.6  572.93  5492.6  572.46  5522.8  572.68  5549.9  573.99  5559.0  573.89
  5564.9  572.79  5573.8  574.24  5586.0  574.55  5616.2  576.82  5673.4  577.75
  5730.6  579.47  5766.8  579.50  5789.2  580.78  5875.3  583.03  6101.3  590.69
#Mann=4,-1,0
  4350.0    0.05       0  4948.8   0.035       0  4954.4    0.05       0
  5026.8     0.1       0
Bank Sta=4948.8,4954.4
Exp/Cntr=0.3,0.1

Type RM Length L Ch R = 1,18460,478,478,478
BEGIN DESCRIPTION:
UNT 001 in BCW 34.0
END DESCRIPTION:
XS GIS Cut Line= 3
      1964429.12     13485052.42      1964825.00     13484225.00
      1965530.35     13483503.28
#Sta/Elev= 30
  4091.6  588.34  4091.9  588.34  4343.3  578.53  4622.2  572.86  4765.0  570.46
  4829.3  569.62  4984.2  567.81  4991.8  567.48  4992.3  566.98  4997.6  567.48
  5215.6  569.66  5223.4  569.55  5349.4  571.00  5514.1  575.64  5617.0  578.88
  5631.1  577.92  5652.3  579.69  5659.4  578.70  5666.4  580.35  5673.6  579.53
  5737.1  583.33  5744.3  582.51  5750.6  584.01  5758.4  583.06  5765.4  584.55
  5772.6  583.33  5804.8  584.55  5884.4  588.07  5950.2  590.62  6018.0  593.09
#Mann=16,-1,0
  4091.6     0.1       0  4091.9    0.05       0  4622.2     0.1       0
  4765.0    0.05       0  4829.3     0.1       0  4984.2    0.05       0
  4991.8    0.03       0  4997.6    0.05       0  5215.6     0.1       0
  5223.4    0.05       0  5349.4     0.1       0  5514.1    0.05       0
  5750.6     0.1       0  5804.8    0.05       0  5884.4     0.1       0
  5950.2    0.05       0
Bank Sta=4991.8,4997.6
Exp/Cntr=0.3,0.1

Type RM Length L Ch R = 1,17982,381,381,381
BEGIN DESCRIPTION:
UNT 001 in BCW 33.0
END DESCRIPTION:
XS GIS Cut Line= 3
      1964856.17     13484982.15      1965275.00     13484325.00
      1965675.03     13483924.97
#Sta/Elev= 30
  4212.6  590.03  4253.8  589.38  4259.8  589.93  4290.2  588.45  4296.2  589.03
  4311.4  587.06  4332.5  587.76  4347.8  586.14  4353.7  586.72  4363.0  585.76
  4368.9  586.64  4384.2  584.09  4390.1  585.15  4405.3  583.68  4478.1  583.94
  4484.0  584.84  4499.3  584.57  4507.9  583.50  4556.8  579.89  4760.0  570.25
  4775.2  568.85  4790.3  569.46  4861.4  567.50  4941.9  567.19  5003.1  565.87
  5003.6  565.37  5009.0  565.87  5147.4  569.41  5345.4  577.18  5557.6  594.02
#Mann=4,-1,0
  4212.6     0.1       0  4507.9    0.05       0  5003.1   0.035       0
  5009.0    0.05       0
Bank Sta=5003.1,5009
Exp/Cntr=0.3,0.1

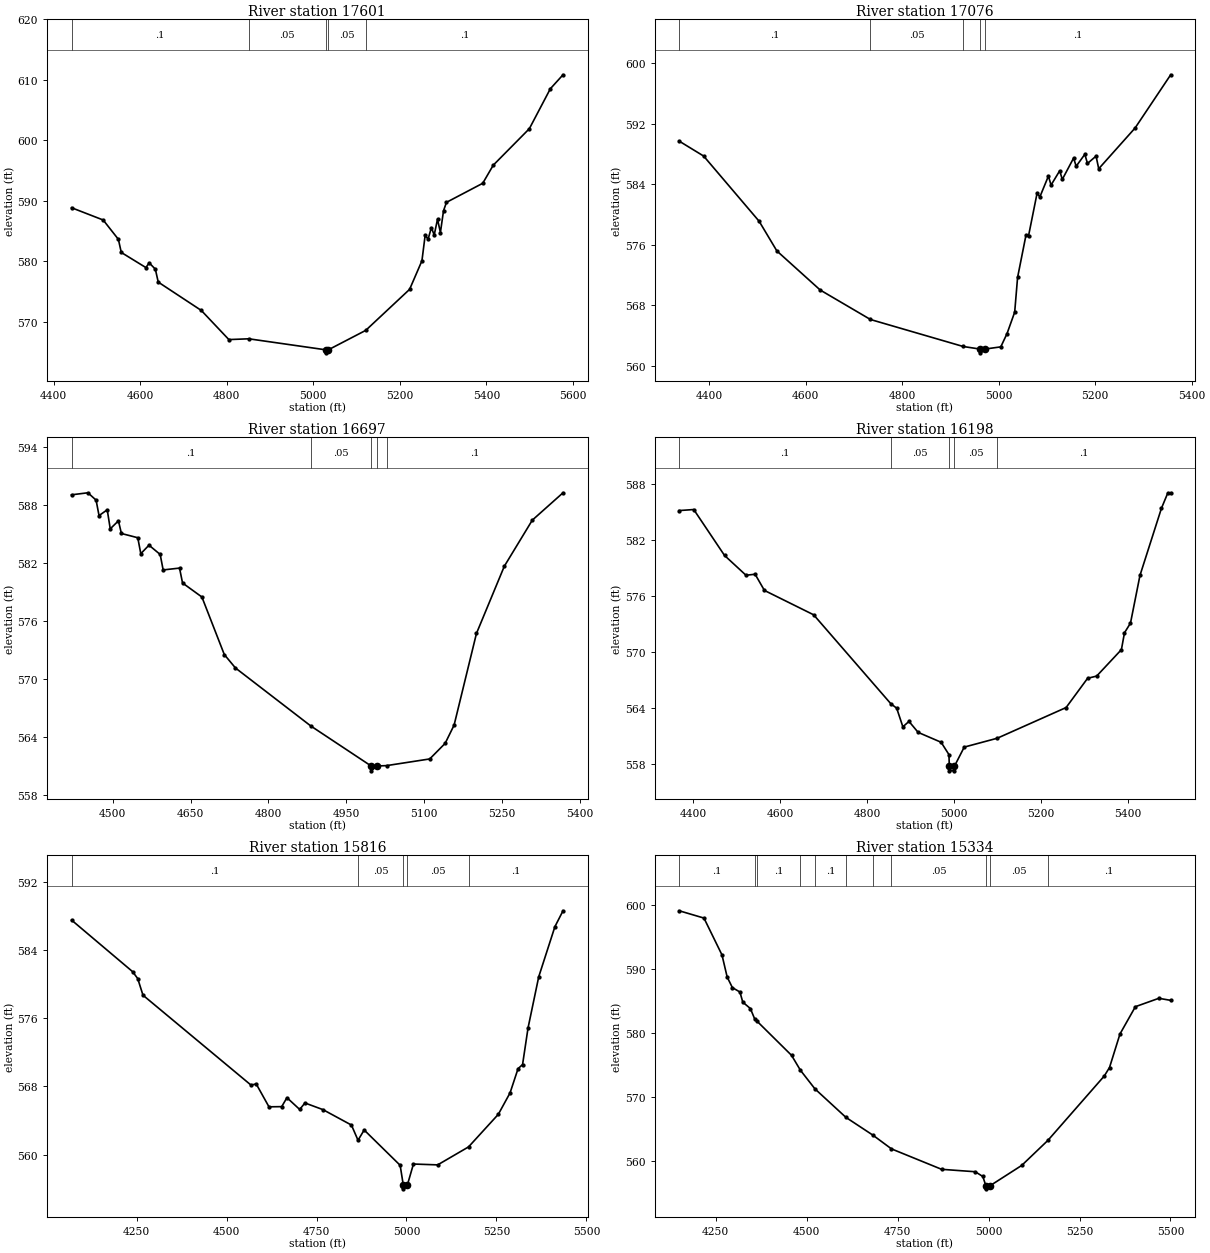
Type RM Length L Ch R = 1,17601,525,525,525
BEGIN DESCRIPTION:
UNT 001 in BCW 32.0
END DESCRIPTION:
XS GIS Cut Line= 3
      1965168.67     13484901.41      1965820.31     13484330.21
      1966070.12     13484230.28
#Sta/Elev= 30
  4441.5  588.87  4514.6  586.84  4549.7  583.65  4556.4  581.48  4613.3  578.98
  4620.9  579.76  4635.1  578.72  4641.8  576.58  4741.4  571.89  4805.0  567.08
  4851.0  567.21  5028.8  565.39  5029.3  564.89  5034.8  565.39  5121.2  568.60
  5222.6  575.38  5251.1  580.10  5258.6  584.34  5265.3  583.67  5272.9  585.58
  5279.5  584.37  5287.1  586.97  5293.8  584.77  5301.0  588.38  5307.8  589.76
  5391.6  592.91  5415.9  595.90  5499.3  601.93  5547.8  608.53  5577.1  610.84
#Mann=5,-1,0
  4441.5     0.1       0  4851.0    0.05       0  5028.8    0.03       0
  5034.8    0.05       0  5121.2     0.1       0
Bank Sta=5028.8,5034.8
Exp/Cntr=0.3,0.1

Type RM Length L Ch R = 1,17076,379,379,379
BEGIN DESCRIPTION:
UNT 001 in BCW 31.0
END DESCRIPTION:
XS GIS Cut Line= 3
      1965925.00     13485425.00      1966025.00     13484775.00
      1966170.65     13484444.52
#Sta/Elev= 30
  4337.6  589.71  4388.2  587.74  4503.3  579.11  4540.0  575.19  4629.8  570.02
  4734.0  566.12  4926.2  562.55  4961.0  562.21  4961.5  561.71  4971.3  562.21
  5004.2  562.50  5017.1  564.25  5033.0  567.09  5039.0  571.68  5056.3  577.24
  5061.8  577.21  5079.6  582.88  5085.1  582.32  5102.9  585.09  5108.4  583.90
  5126.3  585.79  5131.7  584.65  5155.1  587.47  5160.5  586.39  5178.4  587.97
  5183.9  586.76  5201.7  587.73  5207.2  586.06  5282.6  591.45  5356.4  598.49
#Mann=5,-1,0
  4337.6     0.1       0  4734.0    0.05       0  4926.2     0.1       0
  4961.0    0.07       0  4971.3     0.1       0
Bank Sta=4961,4971.3
Exp/Cntr=0.3,0.1

Type RM Length L Ch R = 1,16697,499,499,499
BEGIN DESCRIPTION:
UNT 001 in BCW 30.0
END DESCRIPTION:
XS GIS Cut Line= 3
      1966003.77     13485546.34      1966275.00     13485075.00
      1966424.77     13484700.01
#Sta/Elev= 30
  4420.6  589.06  4452.1  589.27  4467.9  588.51  4473.6  586.91  4489.4  587.51
  4495.2  585.54  4511.0  586.37  4516.7  585.06  4548.3  584.62  4554.1  582.97
  4569.9  583.85  4591.5  582.89  4597.2  581.29  4628.8  581.48  4634.6  579.94
  4671.9  578.49  4715.1  572.54  4736.6  571.15  4881.9  565.15  4998.3  561.01
  4998.8  560.51  5008.6  561.01  5028.0  561.05  5111.2  561.74  5140.9  563.35
  5158.2  565.24  5201.3  574.72  5255.1  581.68  5309.0  586.44  5368.2  589.27
#Mann=5,-1,0
  4420.6     0.1       0  4881.9    0.05       0  4998.3    0.03       0
  5008.6    0.05       0  5028.0     0.1       0
Bank Sta=4998.3,5008.6
Exp/Cntr=0.3,0.1

Type RM Length L Ch R = 1,16198,382,382,382
BEGIN DESCRIPTION:
UNT 001 in BCW 29.0
END DESCRIPTION:
XS GIS Cut Line= 3
      1966264.21     13485711.25      1966675.00     13485275.00
      1967074.98     13484925.02
#Sta/Elev= 30
  4368.0  585.18  4401.4  585.29  4472.2  580.36  4521.6  578.23  4542.6  578.34
  4564.0  576.60  4677.3  573.98  4854.8  564.43  4868.3  563.95  4882.5  561.95
  4896.6  562.53  4917.7  561.35  4970.5  560.29  4988.6  558.96  4989.3  557.72
  4989.8  557.22  5000.7  557.22  5001.2  557.72  5023.7  559.77  5099.5  560.72
  5258.1  564.02  5307.5  567.16  5328.4  567.40  5385.3  570.24  5392.4  572.05
  5406.2  573.09  5428.0  578.21  5477.4  585.42  5491.6  587.02  5498.7  587.09
#Mann=5,-1,0
  4368.0     0.1       0  4854.8    0.05       0  4989.3    0.03       0
  5001.2    0.05       0  5099.5     0.1       0
Bank Sta=4989.3,5001.2
Exp/Cntr=0.3,0.1

Type RM Length L Ch R = 1,15816,482,482,482
BEGIN DESCRIPTION:
UNT 001 in BCW 28.0
END DESCRIPTION:
XS GIS Cut Line= 3
      1966420.42     13486258.17      1966971.21     13485523.04
      1967175.02     13485124.96
#Sta/Elev= 30
  4069.2  587.51  4238.6  581.47  4253.1  580.65  4267.7  578.70  4567.8  568.16
  4582.4  568.29  4617.8  565.61  4653.2  565.63  4667.8  566.68  4703.2  565.30
  4717.8  566.06  4767.8  565.28  4847.0  563.47  4865.3  561.69  4882.4  562.89
  4982.4  558.75  4990.9  556.49  4991.4  555.99  5002.8  556.49  5019.3  558.90
  5086.7  558.80  5172.5  560.91  5255.2  564.73  5287.8  567.24  5310.0  570.08
  5322.6  570.57  5337.8  574.86  5367.5  580.86  5412.5  586.74  5435.0  588.60
#Mann=5,-1,0
  4069.2     0.1       0  4865.3    0.05       0  4990.9   0.035       0
  5002.8    0.05       0  5172.5     0.1       0
Bank Sta=4990.9,5002.8
Exp/Cntr=0.3,0.1

Type RM Length L Ch R = 1,15334,597,597,597
BEGIN DESCRIPTION:
UNT 001 in BCW 27.0
END DESCRIPTION:
XS GIS Cut Line= 3
      1966835.37     13486370.99      1967375.00     13485725.00
      1967696.21     13485329.67
#Sta/Elev= 30
  4149.5  599.04  4217.5  597.90  4267.0  592.15  4281.3  588.69  4295.6  587.04
  4316.4  586.35  4324.2  584.77  4345.1  583.77  4357.5  582.07  4363.1  581.81
  4458.3  576.46  4482.6  574.14  4522.5  571.23  4607.8  566.77  4681.8  564.00
  4733.0  561.85  4870.8  558.66  4963.2  558.28  4984.1  557.54  4992.4  556.11
  4992.9  555.61  5004.4  556.11  5091.1  559.27  5162.9  563.17  5318.1  573.24
  5332.4  574.56  5361.2  579.80  5403.5  584.06  5468.0  585.37  5500.6  585.05
#Mann=11,-1,0
  4149.5     0.1       0  4357.5    0.05       0  4363.1     0.1       0
  4482.6    0.05       0  4522.5     0.1       0  4607.8    0.05       0
  4681.8     0.1       0  4733.0    0.05       0  4992.4   0.035       0
  5004.4    0.05       0  5162.9     0.1       0
Bank Sta=4992.4,5004.4
Exp/Cntr=0.3,0.1

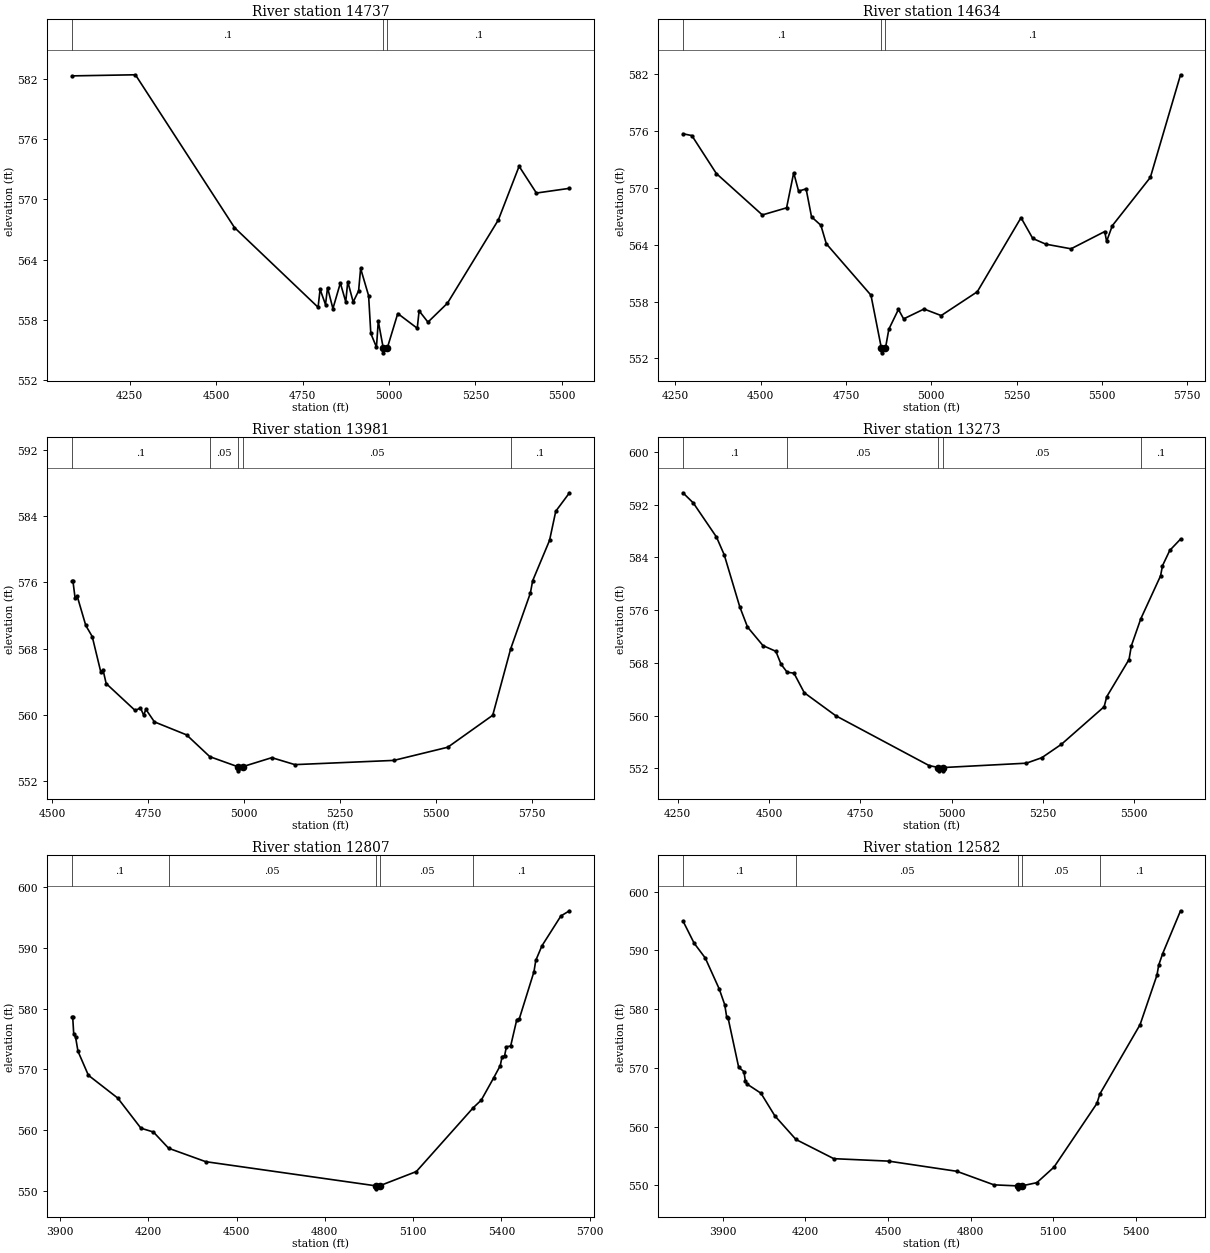
Type RM Length L Ch R = 1,14737,103,103,103
BEGIN DESCRIPTION:
UNT 001 in BCW 26.0
END DESCRIPTION:
XS GIS Cut Line= 5
      1967147.83     13486537.68      1967703.42     13486357.11
      1967842.31     13486121.00      1967953.42     13485808.50
      1967953.42     13485559.30
#Sta/Elev= 30
  4083.0  582.31  4266.8  582.42  4553.2  567.19  4795.0  559.24  4800.8  561.03
  4816.5  559.51  4822.3  561.20  4837.9  559.11  4859.4  561.66  4875.0  559.79
  4880.8  561.80  4896.5  559.77  4912.2  560.88  4918.0  563.11  4941.1  560.40
  4947.5  556.63  4963.8  555.27  4969.1  557.85  4983.3  555.20  4983.8  554.70
  4995.3  555.20  5025.4  558.62  5081.8  557.15  5087.1  558.89  5112.7  557.76
  5169.1  559.65  5316.3  567.95  5376.3  573.30  5426.3  570.63  5522.0  571.10
#Mann=3,-1,0
  4083.0     0.1       0  4983.3    0.07       0  4995.3     0.1       0
Bank Sta=4983.3,4995.3
Exp/Cntr=0.3,0.1

Type RM Length L Ch R = 1,14634,653,653,653
BEGIN DESCRIPTION:
UNT 001 in BCW 25.0
END DESCRIPTION:
XS GIS Cut Line= 4
      1967505.49     13486653.13      1967773.73     13486431.77
      1967940.40     13486137.50      1968288.69     13485448.72
#Sta/Elev= 30
  4272.4  575.69  4298.6  575.50  4370.3  571.50  4505.1  567.13  4576.1  567.88
  4597.0  571.58  4611.3  569.64  4633.3  569.88  4649.2  566.93  4676.6  566.04
  4692.5  564.09  4823.3  558.67  4853.8  553.09  4854.3  552.59  4865.8  553.09
  4875.7  555.08  4903.8  557.17  4919.0  556.17  4978.8  557.21  5029.0  556.52
  5134.8  559.03  5262.9  566.84  5297.3  564.65  5335.4  564.05  5409.4  563.56
  5508.1  565.38  5513.7  564.35  5530.4  566.00  5641.8  571.09  5730.2  581.91
#Mann=3,-1,0
  4272.4     0.1       0  4853.8    0.07       0  4865.8     0.1       0
Bank Sta=4853.8,4865.8
Exp/Cntr=0.3,0.1

Type RM Length L Ch R = 1,13981,708,708,708
BEGIN DESCRIPTION:
UNT 001 in BCW 24.0
END DESCRIPTION:
XS GIS Cut Line= 3
      1968275.00     13486875.00      1968475.00     13486475.00
      1969224.98     13486075.01
#Sta/Elev= 30
  4551.8  576.15  4554.6  576.15  4560.2  574.13  4565.8  574.32  4588.1  570.80
  4604.9  569.46  4627.3  565.17  4632.9  565.47  4641.2  563.79  4716.7  560.54
  4730.7  560.84  4739.1  559.96  4744.7  560.68  4767.0  559.16  4850.9  557.59
  4911.4  554.96  4984.3  553.75  4984.8  553.25  4997.0  553.75  5073.0  554.84
  5133.2  554.00  5391.1  554.51  5531.7  556.10  5648.9  559.96  5695.5  567.95
  5747.0  574.71  5753.0  576.20  5797.0  581.07  5813.2  584.59  5849.0  586.82
#Mann=5,-1,0
  4551.8     0.1       0  4911.4    0.05       0  4984.3    0.03       0
  4997.0    0.05       0  5695.5     0.1       0
Bank Sta=4984.3,4997
Exp/Cntr=0.3,0.1

Type RM Length L Ch R = 1,13273,466,466,466
BEGIN DESCRIPTION:
Mapping XS 0506f0e5
END DESCRIPTION:
XS GIS Cut Line= 3
      1968684.74     13487314.73      1968968.61     13487030.86
      1969298.82     13486128.64
#Sta/Elev= 30
  4264.5  593.78  4292.8  592.25  4356.4  587.07  4377.6  584.38  4420.1  576.50
  4441.3  573.43  4483.7  570.61  4519.0  569.74  4533.2  567.78  4549.9  566.57
  4568.5  566.43  4596.8  563.46  4682.8  559.98  4938.4  552.42  4964.0  552.12
  4964.5  551.62  4976.3  551.62  4976.8  552.12  5204.6  552.78  5246.9  553.61
  5300.5  555.64  5417.6  561.34  5424.7  562.86  5485.7  568.50  5492.1  570.58
  5517.9  574.67  5572.0  581.18  5577.3  582.72  5597.2  585.04  5626.7  586.76
#Mann=5,-1,0
  4264.5     0.1       0  4549.9    0.05       0  4964.0    0.03       0
  4976.8    0.05       0  5517.9     0.1       0
Bank Sta=4964,4976.8
Exp/Cntr=0.3,0.1

Type RM Length L Ch R = 1,12807,225,225,225
BEGIN DESCRIPTION:
Mapping XS fab5f543
END DESCRIPTION:
XS GIS Cut Line= 4
      1968955.58     13487554.30      1969432.15     13487187.11
      1969541.53     13486468.36      1969759.88     13486179.81
#Sta/Elev= 30
  3940.6  578.68  3943.4  578.68  3946.9  575.88  3953.2  575.33  3961.4  572.99
  3996.7  569.04  4096.4  565.28  4175.2  560.31  4217.6  559.68  4269.4  557.00
  4395.3  554.79  4972.6  550.81  4973.1  550.31  4986.0  550.81  5110.8  553.16
  5304.2  563.69  5331.4  564.94  5373.8  568.63  5395.9  570.63  5402.2  572.11
  5410.5  572.23  5416.8  573.73  5431.3  573.87  5452.1  578.22  5460.4  578.32
  5510.4  586.11  5516.6  587.98  5537.5  590.38  5602.0  595.31  5631.1  596.16
#Mann=5,-1,0
  3940.6     0.1       0  4269.4    0.05       0  4972.6    0.03       0
  4986.0    0.05       0  5304.2     0.1       0
Bank Sta=4972.6,4986
Exp/Cntr=0.3,0.1

Type RM Length L Ch R = 1,12582,440,440,440
BEGIN DESCRIPTION:
Mapping XS 9073cba7
END DESCRIPTION:
XS GIS Cut Line= 3
      1969564.97     13488015.26      1969489.44     13487533.46
      1969851.43     13486262.59
#Sta/Elev= 30
  3754.4  595.04  3795.2  591.23  3835.6  588.71  3886.3  583.45  3906.5  580.74
  3913.6  578.64  3918.7  578.47  3957.1  570.10  3976.2  569.35  3981.3  567.82
  3987.5  567.23  4038.1  565.67  4088.7  561.81  4165.4  557.79  4302.9  554.52
  4502.6  554.10  4750.0  552.37  4885.1  550.06  4972.4  549.88  4972.9  549.38
  4985.8  549.88  5041.1  550.43  5103.5  553.08  5259.5  563.93  5270.2  565.54
  5416.4  577.35  5477.8  585.78  5484.1  587.49  5498.6  589.46  5563.5  596.75
#Mann=5,-1,0
  3754.4     0.1       0  4165.4    0.05       0  4972.4    0.03       0
  4985.8    0.05       0  5270.2     0.1       0
Bank Sta=4972.4,4985.8
Exp/Cntr=0.3,0.1

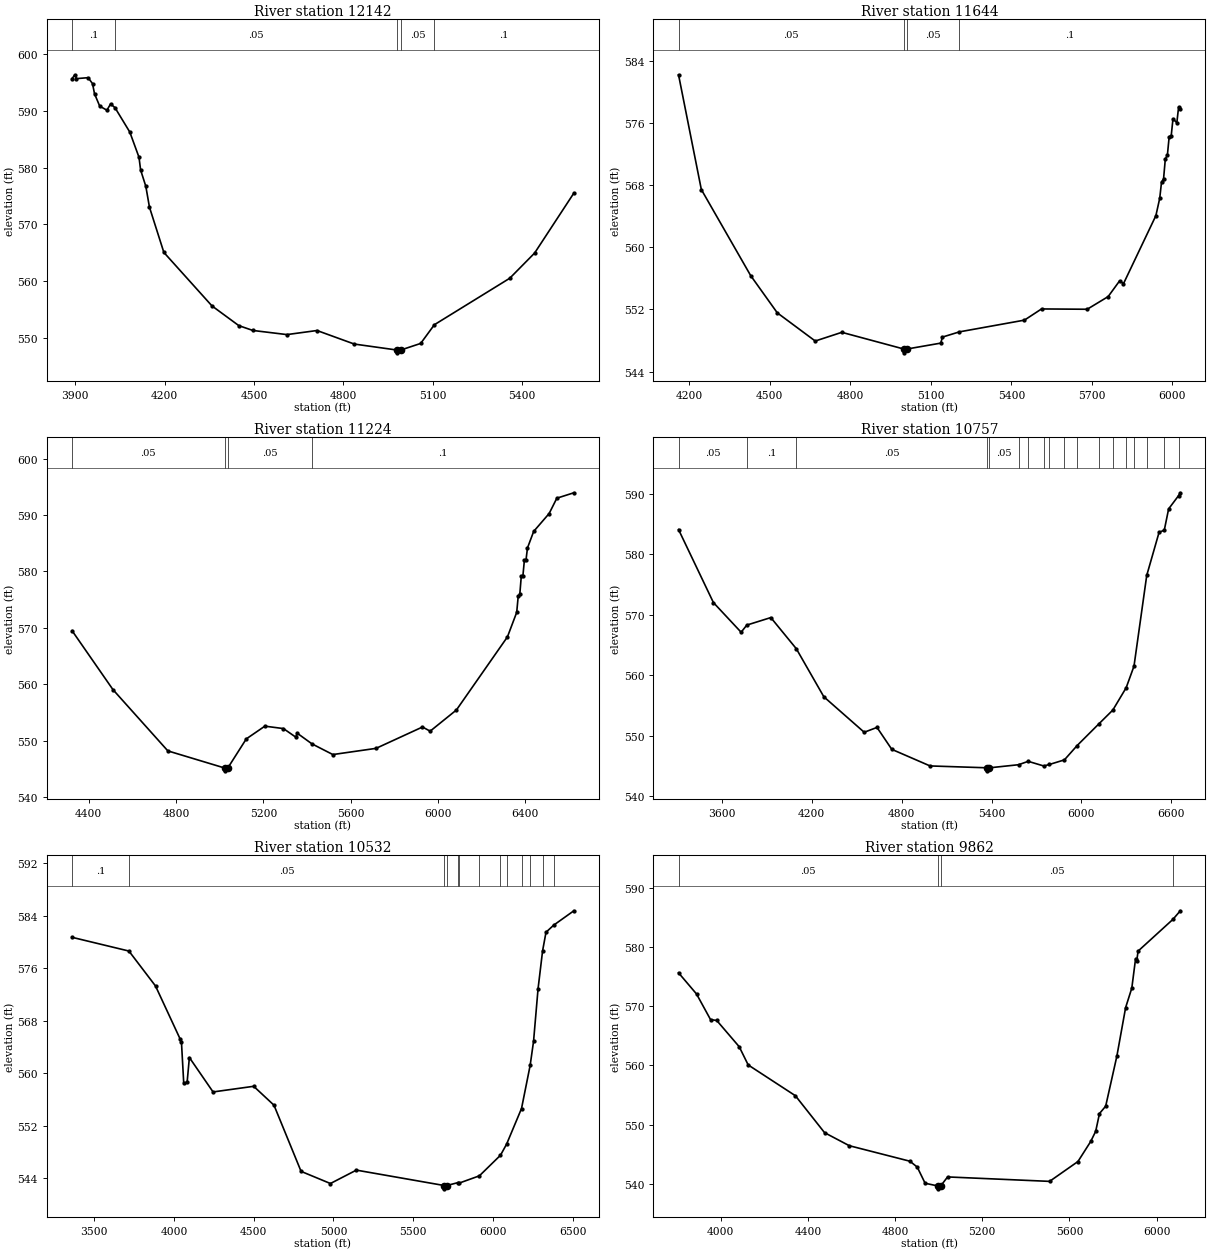
Type RM Length L Ch R = 1,12142,498,498,498
BEGIN DESCRIPTION:
UNT 001 in BCW 20.0
END DESCRIPTION:
XS GIS Cut Line= 3
      1969674.99     13488025.02      1970075.00     13487025.00
      1969975.00     13486425.03
#Sta/Elev= 30
  3889.0  595.70  3898.4  596.37  3903.8  595.69  3942.9  595.86  3957.7  594.81
  3964.4  593.02  3981.9  590.83  4006.1  590.12  4018.3  591.22  4033.1  590.57
  4082.9  586.26  4113.8  581.81  4119.2  579.57  4136.7  576.69  4148.9  573.01
  4197.3  565.02  4358.9  555.58  4449.1  552.10  4496.2  551.25  4610.6  550.52
  4711.6  551.24  4836.8  548.85  4979.6  547.80  4980.1  547.30  4993.1  547.80
  5059.8  548.96  5105.8  552.26  5358.9  560.46  5442.5  564.91  5574.3  575.49
#Mann=5,-1,0
  3889.0     0.1       0  4033.1    0.05       0  4979.6    0.03       0
  4993.1    0.05       0  5105.8     0.1       0
Bank Sta=4979.6,4993.1
Exp/Cntr=0.3,0.1

Type RM Length L Ch R = 1,11644,420,420,420
BEGIN DESCRIPTION:
UNT 001 in BCW 19.0
END DESCRIPTION:
XS GIS Cut Line= 3
      1969824.99     13487925.01      1970425.00     13487325.00
      1971088.01     13486549.54
#Sta/Elev= 30
  4160.6  582.21  4245.5  567.44  4429.3  556.36  4528.3  551.57  4669.7  547.94
  4768.7  549.06  4998.7  546.92  4999.2  546.42  5012.5  546.92  5137.0  547.67
  5143.6  548.45  5206.6  549.12  5448.8  550.63  5512.5  552.07  5682.6  552.03
  5760.6  553.66  5803.4  555.69  5817.7  555.32  5938.4  564.08  5952.7  566.32
  5959.3  568.37  5967.0  568.83  5973.5  571.37  5981.2  571.86  5987.8  574.22
  5995.5  574.38  6002.1  576.55  6016.4  576.03  6022.9  578.04  6029.4  577.82
#Mann=4,-1,0
  4160.6    0.05       0  4998.7    0.03       0  5012.5    0.05       0
  5206.6     0.1       0
Bank Sta=4998.7,5012.5
Exp/Cntr=0.3,0.1

Type RM Length L Ch R = 1,11224,467,467,467
BEGIN DESCRIPTION:
UNT 001 in BCW 18.0
END DESCRIPTION:
XS GIS Cut Line= 3
      1969925.03     13488024.99      1970525.00     13487725.00
      1971625.02     13486524.98
#Sta/Elev= 30
  4323.9  569.49  4511.1  559.04  4762.7  548.16  5023.0  545.12  5023.5  544.62
  5037.2  545.12  5122.0  550.29  5207.1  552.55  5292.2  552.12  5348.3  550.61
  5355.7  551.29  5422.7  549.41  5518.5  547.51  5716.4  548.61  5929.2  552.40
  5964.3  551.66  6084.6  555.42  6318.3  568.39  6360.8  572.75  6367.6  575.58
  6375.0  575.97  6381.8  579.20  6389.2  579.25  6396.0  582.02  6403.4  582.05
  6410.1  584.18  6438.5  587.11  6509.4  590.29  6544.6  593.01  6622.6  593.97
#Mann=4,-1,0
  4323.9    0.05       0  5023.0    0.03       0  5037.2    0.05       0
  5422.7     0.1       0
Bank Sta=5023,5037.2
Exp/Cntr=0.3,0.1

Type RM Length L Ch R = 1,10757,225,225,225
BEGIN DESCRIPTION:
UNT 001 in BCW 17.0
END DESCRIPTION:
XS GIS Cut Line= 3
      1969633.14     13489081.91      1970875.00     13487975.00
      1972084.47     13486804.19
#Sta/Elev= 30
  3312.4  584.05  3545.0  571.99  3729.8  567.09  3767.8  568.27  3927.9  569.51
  4097.9  564.37  4281.6  556.43  4550.8  550.57  4636.1  551.37  4734.8  547.75
  4990.0  545.01  5372.0  544.70  5372.5  544.20  5386.3  544.70  5580.2  545.21
  5644.7  545.77  5748.8  545.00  5785.8  545.25  5886.1  546.01  5971.2  548.38
  6113.7  551.90  6209.2  554.24  6298.0  557.92  6350.3  561.49  6435.3  576.48
  6517.7  583.60  6552.3  583.94  6581.3  587.46  6648.0  589.66  6659.3  590.12
#Mann=18,-1,0
  3312.4    0.05       0  3767.8     0.1       0  4097.9    0.05       0
  5372.0    0.04       0  5386.3    0.05       0  5580.2     0.1       0
  5644.7    0.05       0  5748.8     0.1       0  5785.8    0.05       0
  5886.1     0.1       0  5971.2    0.05       0  6113.7     0.1       0
  6209.2    0.05       0  6298.0     0.1       0  6350.3    0.05       0
  6435.3     0.1       0  6552.3    0.05       0  6648.0     0.1       0
Bank Sta=5372,5386.3
Exp/Cntr=0.3,0.1

Type RM Length L Ch R = 1,10532,670,670,670
BEGIN DESCRIPTION:
UNT 001 in BCW 16.0
END DESCRIPTION:
XS GIS Cut Line= 3
      1969938.69     13489158.30      1971153.94     13487963.88
      1972146.41     13486919.36
#Sta/Elev= 30
  3361.8  580.69  3718.1  578.60  3884.8  573.28  4040.4  565.14  4047.4  564.71
  4061.6  558.51  4082.8  558.61  4097.0  562.39  4245.4  557.15  4500.0  558.01
  4627.3  555.13  4797.0  545.06  4980.9  543.21  5143.6  545.25  5695.1  542.90
  5695.6  542.40  5709.4  542.90  5782.4  543.36  5789.8  543.29  5914.5  544.38
  6046.6  547.51  6085.0  549.20  6178.6  554.63  6232.6  561.18  6254.0  564.86
  6282.3  572.88  6310.7  578.64  6332.0  581.46  6380.2  582.54  6506.6  584.73
#Mann=13,-1,0
  3361.8     0.1       0  3718.1    0.05       0  5695.1    0.03       0
  5709.4    0.05       0  5782.4    0.08       0  5789.8     0.1       0
  5914.5    0.05       0  6046.6    0.08       0  6085.0    0.05       0
  6178.6    0.08       0  6232.6    0.05       0  6310.7    0.08       0
  6380.2    0.05       0
Bank Sta=5695.1,5709.4
Exp/Cntr=0.3,0.1

Type RM Length L Ch R = 1,9862,937,937,937
BEGIN DESCRIPTION:
UNT 001 in BCW 15.0
END DESCRIPTION:
XS GIS Cut Line= 3
      1971425.00     13489075.02      1971725.00     13487875.00
      1972174.38     13486909.18
#Sta/Elev= 30
  3806.5  575.63  3889.0  572.06  3953.4  567.73  3981.7  567.59  4084.8  563.16
  4126.1  560.08  4342.5  554.89  4476.5  548.65  4589.9  546.45  4868.2  543.83
  4901.7  542.84  4937.8  540.11  4995.0  539.67  4995.5  539.17  5009.5  539.67
  5040.9  541.18  5508.9  540.43  5639.0  543.78  5697.5  547.16  5720.4  548.88
  5737.8  551.88  5766.2  553.12  5817.4  561.54  5857.7  569.76  5886.1  573.05
  5903.5  578.04  5909.0  577.70  5914.8  579.29  6074.4  584.64  6108.7  586.10
#Mann=4,-1,0
  3806.5    0.05       0  4995.0    0.03       0  5009.5    0.05       0
  6074.4     0.1       0
Bank Sta=4995,5009.5
Exp/Cntr=0.3,0.1