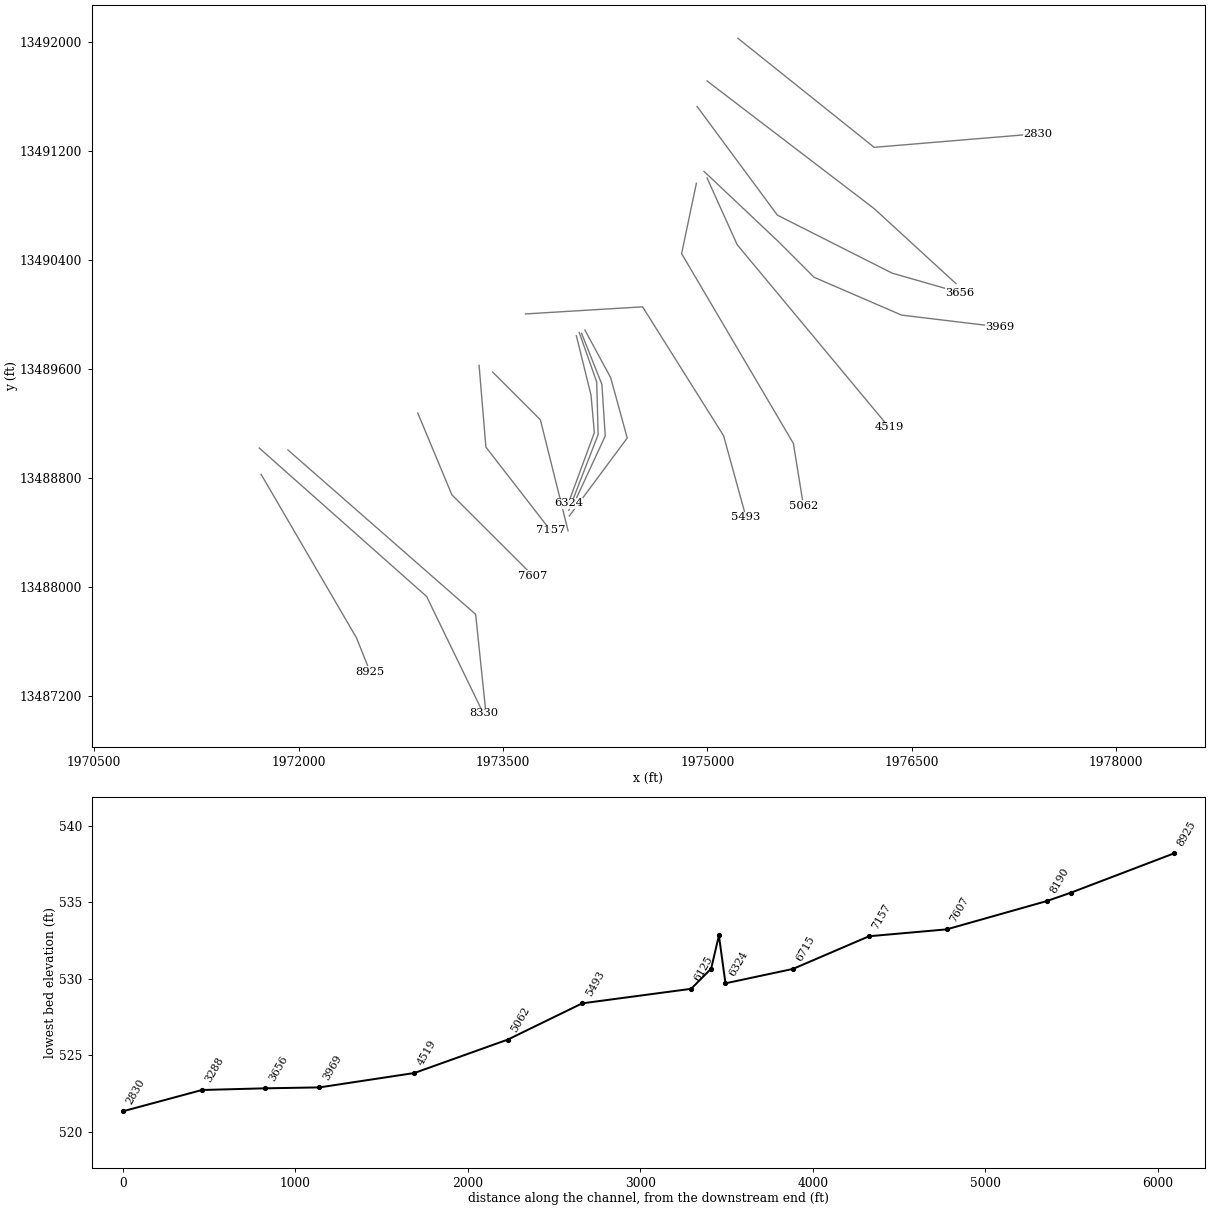
HEC-RAS study UNT 001 in BCW.prj: UNT 001 in BCW Base Level Engineering

--- UNT 001 in BCW.g01 (geometry) --- (continued)

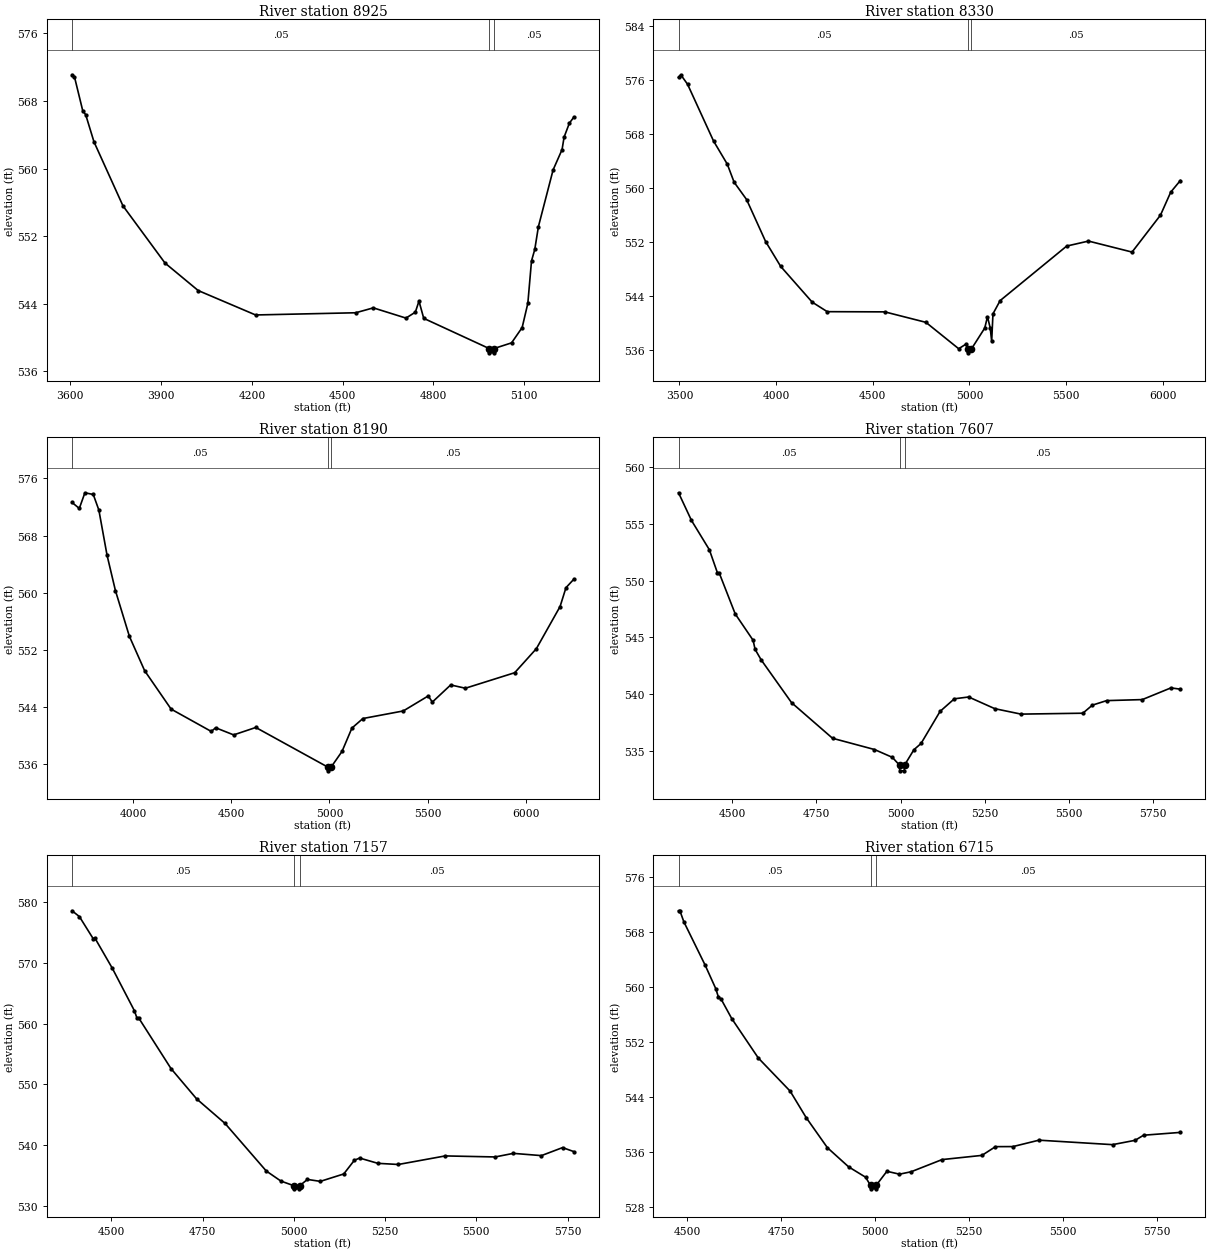
Type RM Length L Ch R = 1,8925,595,595,595
BEGIN DESCRIPTION:
UNT 001 in BCW 14.0
END DESCRIPTION:
XS GIS Cut Line= 3
      1971724.98     13488825.03      1972425.00     13487625.00
      1972524.98     13487375.04
#Sta/Elev= 30
  3605.9  571.09  3613.8  570.85  3641.1  566.85  3651.0  566.36  3678.3  563.16
  3774.2  555.58  3913.1  548.82  4022.7  545.57  4212.5  542.68  4543.3  542.94
  4601.6  543.52  4709.5  542.31  4740.5  543.01  4752.5  544.32  4768.2  542.28
  4985.0  538.70  4985.5  538.20  4999.1  538.20  4999.6  538.70  5058.5  539.38
  5093.5  541.19  5112.3  544.06  5124.4  549.07  5135.2  550.43  5147.3  553.14
  5195.8  559.84  5225.4  562.24  5232.1  563.71  5249.6  565.37  5264.4  566.08
#Mann=3,-1,0
  3605.9    0.05       0  4985.0   0.035       0  4999.6    0.05       0
Bank Sta=4985,4999.6
Exp/Cntr=0.3,0.1

Type RM Length L Ch R = 1,8330,140,140,140
BEGIN DESCRIPTION:
UNT 001 in BCW 13.0
END DESCRIPTION:
XS GIS Cut Line= 3
      1971711.66     13489017.84      1972939.96     13487928.42
      1973356.19     13487070.36
#Sta/Elev= 30
  3495.4  576.44  3506.9  576.84  3542.0  575.44  3676.6  567.02  3747.7  563.59
  3782.9  560.92  3847.3  558.36  3945.9  552.13  4023.7  548.45  4186.8  543.15
  4264.6  541.74  4562.3  541.71  4774.8  540.16  4944.5  536.25  4980.5  536.90
  4994.1  536.14  4994.6  535.64  5008.7  536.14  5079.2  539.31  5093.4  540.99
  5107.6  539.33  5115.1  537.34  5121.8  541.42  5158.9  543.38  5503.1  551.46
  5615.9  552.20  5841.2  550.57  5988.2  556.04  6041.3  559.45  6090.9  561.17
#Mann=3,-1,0
  3495.4    0.05       0  4994.1   0.035       0  5008.7    0.05       0
Bank Sta=4994.1,5008.7
Exp/Cntr=0.3,0.1

Type RM Length L Ch R = 1,8190,583,583,583
BEGIN DESCRIPTION:
UNT 001 in BCW 12.0
END DESCRIPTION:
XS GIS Cut Line= 3
      1971921.77     13489003.92      1973299.77     13487797.35
      1973375.00     13487075.04
#Sta/Elev= 30
  3688.2  572.64  3725.1  571.81  3753.6  574.00  3796.3  573.76  3824.8  571.58
  3866.5  565.26  3909.2  560.31  3980.4  553.91  4058.2  549.10  4193.0  543.73
  4398.0  540.60  4419.8  541.12  4511.9  540.12  4624.8  541.16  4993.3  535.59
  4993.8  535.09  5008.0  535.59  5064.3  537.81  5114.6  541.07  5170.6  542.41
  5376.5  543.47  5503.7  545.57  5524.6  544.71  5618.1  547.11  5693.1  546.65
  5944.4  548.82  6055.0  552.19  6175.7  558.08  6205.8  560.72  6246.0  561.91
#Mann=3,-1,0
  3688.2    0.05       0  4993.3    0.03       0  5008.0    0.05       0
Bank Sta=4993.3,5008
Exp/Cntr=0.3,0.1

Type RM Length L Ch R = 1,7607,450,450,450
BEGIN DESCRIPTION:
UNT 001 in BCW 11.0
END DESCRIPTION:
XS GIS Cut Line= 3
      1972874.99     13489275.02      1973125.00     13488675.00
      1973720.29     13488080.55
#Sta/Elev= 30
  4340.3  557.74  4378.8  555.30  4431.9  552.72  4455.7  550.70  4461.1  550.68
  4508.8  547.06  4561.9  544.74  4567.8  543.94  4585.7  543.02  4676.2  539.24
  4798.0  536.10  4922.6  535.11  4975.7  534.42  4997.1  533.73  4997.6  533.23
  5011.4  533.23  5011.9  533.73  5039.8  535.09  5061.0  535.64  5117.6  538.47
  5160.0  539.58  5202.5  539.74  5280.2  538.71  5358.0  538.23  5541.9  538.31
  5570.1  539.02  5612.6  539.42  5718.6  539.51  5803.5  540.54  5831.6  540.43
#Mann=3,-1,0
  4340.3    0.05       0  4997.1    0.03       0  5011.9    0.05       0
Bank Sta=4997.1,5011.9
Exp/Cntr=0.3,0.1

Type RM Length L Ch R = 1,7157,442,442,442
BEGIN DESCRIPTION:
UNT 001 in BCW 10.0
END DESCRIPTION:
XS GIS Cut Line= 3
      1973325.00     13489625.03      1973375.00     13489025.00
      1973848.10     13488414.46
#Sta/Elev= 30
  4392.6  578.56  4412.7  577.60  4450.3  573.98  4455.4  574.04  4503.0  569.08
  4563.2  562.12  4570.7  560.84  4575.8  560.85  4663.6  552.58  4733.8  547.59
  4811.6  543.55  4924.5  535.72  4964.6  534.06  5000.8  533.28  5001.3  532.78
  5015.3  532.78  5015.8  533.28  5037.3  534.33  5072.6  534.01  5136.8  535.23
  5165.8  537.48  5180.3  537.85  5230.1  536.98  5286.2  536.79  5414.8  538.20
  5551.4  538.03  5601.3  538.62  5678.2  538.25  5736.2  539.57  5767.1  538.91
#Mann=3,-1,0
  4392.6    0.05       0  5000.8    0.03       0  5015.8    0.05       0
Bank Sta=5000.8,5015.8
Exp/Cntr=0.3,0.1

Type RM Length L Ch R = 1,6715,391,391,391
BEGIN DESCRIPTION:
UNT 001 in BCW 9.0
END DESCRIPTION:
XS GIS Cut Line= 3
      1973424.98     13489575.02      1973775.00     13489225.00
      1973978.33     13488410.09
#Sta/Elev= 30
  4477.5  571.04  4481.1  571.04  4491.7  569.43  4548.2  563.15  4576.5  559.73
  4583.6  558.50  4590.7  558.21  4619.0  555.38  4689.7  549.65  4774.5  544.83
  4816.9  541.00  4873.5  536.62  4930.1  533.83  4975.1  532.33  4988.2  531.14
  4988.7  530.64  5002.7  530.64  5003.2  531.14  5031.8  533.19  5065.3  532.77
  5096.2  533.12  5178.6  534.89  5284.6  535.50  5320.7  536.77  5367.1  536.78
  5436.3  537.71  5632.1  537.06  5692.1  537.69  5714.6  538.43  5812.4  538.84
#Mann=3,-1,0
  4477.5    0.05       0  4988.2    0.03       0  5003.2    0.05       0
Bank Sta=4988.2,5003.2
Exp/Cntr=0.3,0.1

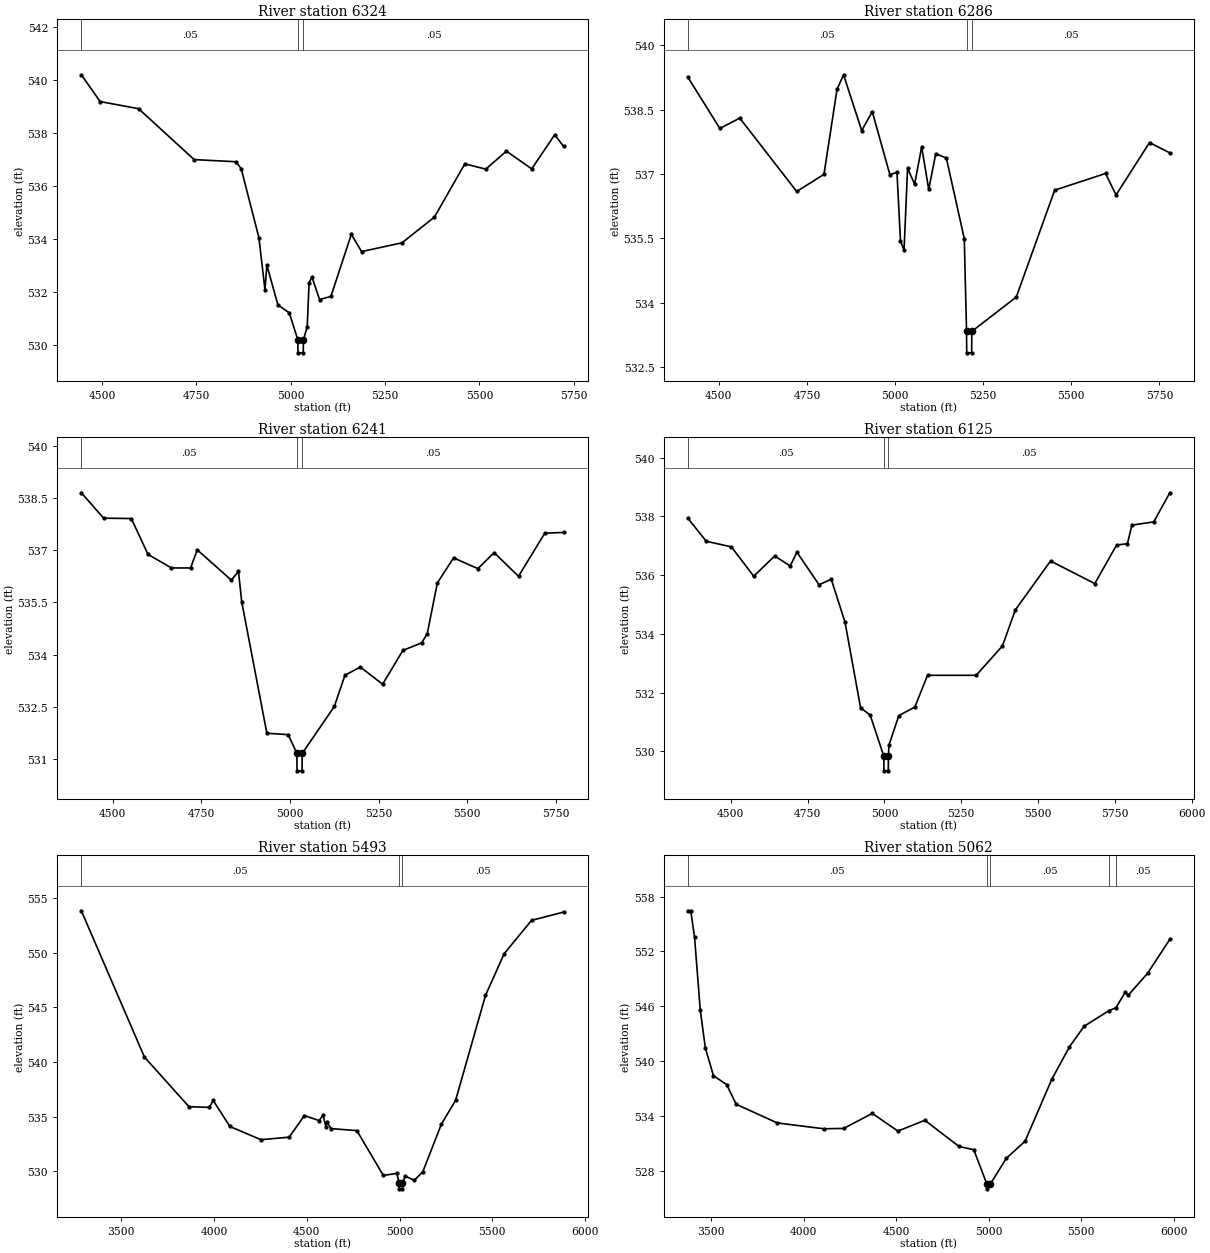
Type RM Length L Ch R = 1,6324,38,38,38
BEGIN DESCRIPTION:
Mapping XS 465266da
END DESCRIPTION:
XS GIS Cut Line= 4
      1974039.11     13489842.34      1974146.73     13489404.89
      1974171.04     13489130.58      1973980.05     13488613.19
#Sta/Elev= 30
  4445.4  540.19  4495.2  539.18  4597.1  538.91  4744.3  536.99  4854.6  536.91
  4868.9  536.65  4915.9  534.04  4931.9  532.08  4936.9  533.01  4966.1  531.51
  4996.2  531.21  5018.8  530.20  5019.3  529.70  5033.3  529.70  5033.8  530.20
  5043.8  530.68  5048.8  532.35  5056.4  532.56  5076.5  531.71  5106.6  531.83
  5160.7  534.17  5187.9  533.52  5294.8  533.85  5380.8  534.82  5461.4  536.83
  5516.9  536.63  5571.6  537.31  5638.6  536.64  5699.5  537.93  5722.8  537.49
#Mann=3,-1,0
  4445.4    0.05       0  5018.8    0.03       0  5033.8    0.05       0
Bank Sta=5018.8,5033.8
Exp/Cntr=0.3,0.1

Type RM Length L Ch R = 1,6286,45,45,45
BEGIN DESCRIPTION:
Mapping XS 0a046c23
END DESCRIPTION:
XS GIS Cut Line= 4
      1974059.93     13489866.70      1974188.40     13489502.11
      1974198.82     13489116.70      1973983.55     13488561.16
#Sta/Elev= 30
  4411.8  539.26  4503.0  538.06  4559.6  538.30  4721.1  536.59  4798.4  536.99
  4835.5  538.97  4854.0  539.31  4905.5  538.01  4935.5  538.45  4985.5  536.98
  5005.5  537.04  5015.5  535.44  5025.6  535.22  5035.6  537.13  5055.6  536.76
  5075.6  537.63  5095.6  536.64  5115.6  537.47  5145.6  537.37  5196.5  535.49
  5202.9  533.33  5203.4  532.83  5217.4  532.83  5217.9  533.33  5344.0  534.13
  5452.9  536.62  5597.2  537.01  5627.1  536.51  5722.0  537.73  5779.7  537.49
#Mann=3,-1,0
  4411.8    0.05       0  5202.9    0.03       0  5217.9    0.05       0
Bank Sta=5202.9,5217.9
Exp/Cntr=0.3,0.1

Type RM Length L Ch R = 1,6241,116,116,116
BEGIN DESCRIPTION:
Mapping XS 3b9b096e
END DESCRIPTION:
XS GIS Cut Line= 4
      1974077.28     13489859.77      1974226.59     13489484.75
      1974250.90     13489106.28      1974007.85     13488581.98
#Sta/Elev= 30
  4411.0  538.65  4473.9  537.92  4552.1  537.91  4599.1  536.88  4665.4  536.49
  4719.3  536.49  4738.2  537.01  4834.4  536.14  4854.5  536.39  4863.6  535.52
  4934.6  531.74  4994.8  531.70  5019.3  531.16  5019.8  530.66  5033.8  530.66
  5034.3  531.16  5125.0  532.51  5155.1  533.41  5198.4  533.64  5261.4  533.15
  5318.5  534.12  5371.7  534.34  5387.2  534.60  5415.8  536.06  5461.5  536.78
  5530.2  536.47  5576.0  536.93  5644.8  536.25  5719.0  537.49  5771.8  537.51
#Mann=3,-1,0
  4411.0    0.05       0  5019.3    0.03       0  5034.3    0.05       0
Bank Sta=5019.3,5034.3
Exp/Cntr=0.3,0.1

Type RM Length L Ch R = 1,6125,632,632,632
BEGIN DESCRIPTION:
UNT 001 in BCW 8.0
END DESCRIPTION:
XS GIS Cut Line= 4
      1974101.58     13489884.09      1974290.83     13489534.23
      1974412.36     13489091.52      1973987.55     13488519.33
#Sta/Elev= 30
  4359.5  537.94  4420.1  537.15  4501.9  536.96  4574.5  535.96  4642.7  536.65
  4693.2  536.31  4715.0  536.78  4787.2  535.67  4826.8  535.86  4871.6  534.40
  4922.4  531.48  4953.5  531.24  4997.8  529.84  4998.3  529.34  5012.4  529.34
  5012.9  529.84  5014.5  530.21  5046.8  531.22  5099.0  531.51  5140.2  532.59
  5298.6  532.59  5384.1  533.59  5425.8  534.81  5540.6  536.48  5684.6  535.71
  5755.5  537.02  5790.9  537.07  5805.5  537.70  5876.5  537.81  5929.0  538.80
#Mann=3,-1,0
  4359.5    0.05       0  4997.8    0.03       0  5012.9    0.05       0
Bank Sta=4997.8,5012.9
Exp/Cntr=0.3,0.1

Type RM Length L Ch R = 1,5493,431,431,431
BEGIN DESCRIPTION:
Mapping XS 528deda1
END DESCRIPTION:
XS GIS Cut Line= 4
      1973665.69     13490002.21      1974525.03     13490054.29
      1975119.65     13489108.11      1975284.46     13488509.61
#Sta/Elev= 30
  3284.5  553.85  3624.4  540.46  3864.9  535.91  3975.1  535.85  3995.1  536.49
  4085.3  534.10  4252.7  532.89  4404.7  533.12  4487.1  535.10  4566.0  534.64
  4587.2  535.13  4602.5  534.09  4608.5  534.53  4629.7  533.91  4769.8  533.72
  4912.3  529.62  4985.4  529.80  4998.0  528.89  4998.5  528.39  5015.0  528.39
  5015.5  528.89  5030.4  529.55  5079.6  529.18  5124.9  529.94  5225.6  534.32
  5302.2  536.50  5463.2  546.10  5563.7  549.92  5711.6  552.97  5883.7  553.73
#Mann=3,-1,0
  3284.5    0.05       0  4998.0    0.03       0  5015.5    0.05       0
Bank Sta=4998,5015.5
Exp/Cntr=0.3,0.1

Type RM Length L Ch R = 1,5062,543,543,543
BEGIN DESCRIPTION:
Mapping XS 585c4bf1
END DESCRIPTION:
XS GIS Cut Line= 4
      1974919.99     13490961.37      1974811.49     13490444.92
      1975631.80     13489051.69      1975705.59     13488595.94
#Sta/Elev= 30
  3373.3  556.44  3390.0  556.42  3410.5  553.53  3441.1  545.63  3468.6  541.44
  3512.6  538.40  3584.2  537.42  3635.3  535.27  3857.3  533.23  4109.5  532.59
  4216.7  532.63  4371.0  534.27  4509.6  532.34  4655.2  533.52  4839.6  530.66
  4919.7  530.30  4990.8  526.52  4991.3  526.02  5008.5  526.52  5095.4  529.36
  5196.9  531.23  5341.3  538.00  5437.0  541.56  5516.0  543.80  5651.7  545.53
  5688.1  545.83  5737.3  547.50  5754.7  547.20  5858.9  549.59  5979.5  553.32
#Mann=5,-1,0
  3373.3    0.05       0  4990.8    0.03       0  5008.5    0.05       0
  5651.7     0.1       0  5688.1    0.05       0
Bank Sta=4990.8,5008.5
Exp/Cntr=0.3,0.1

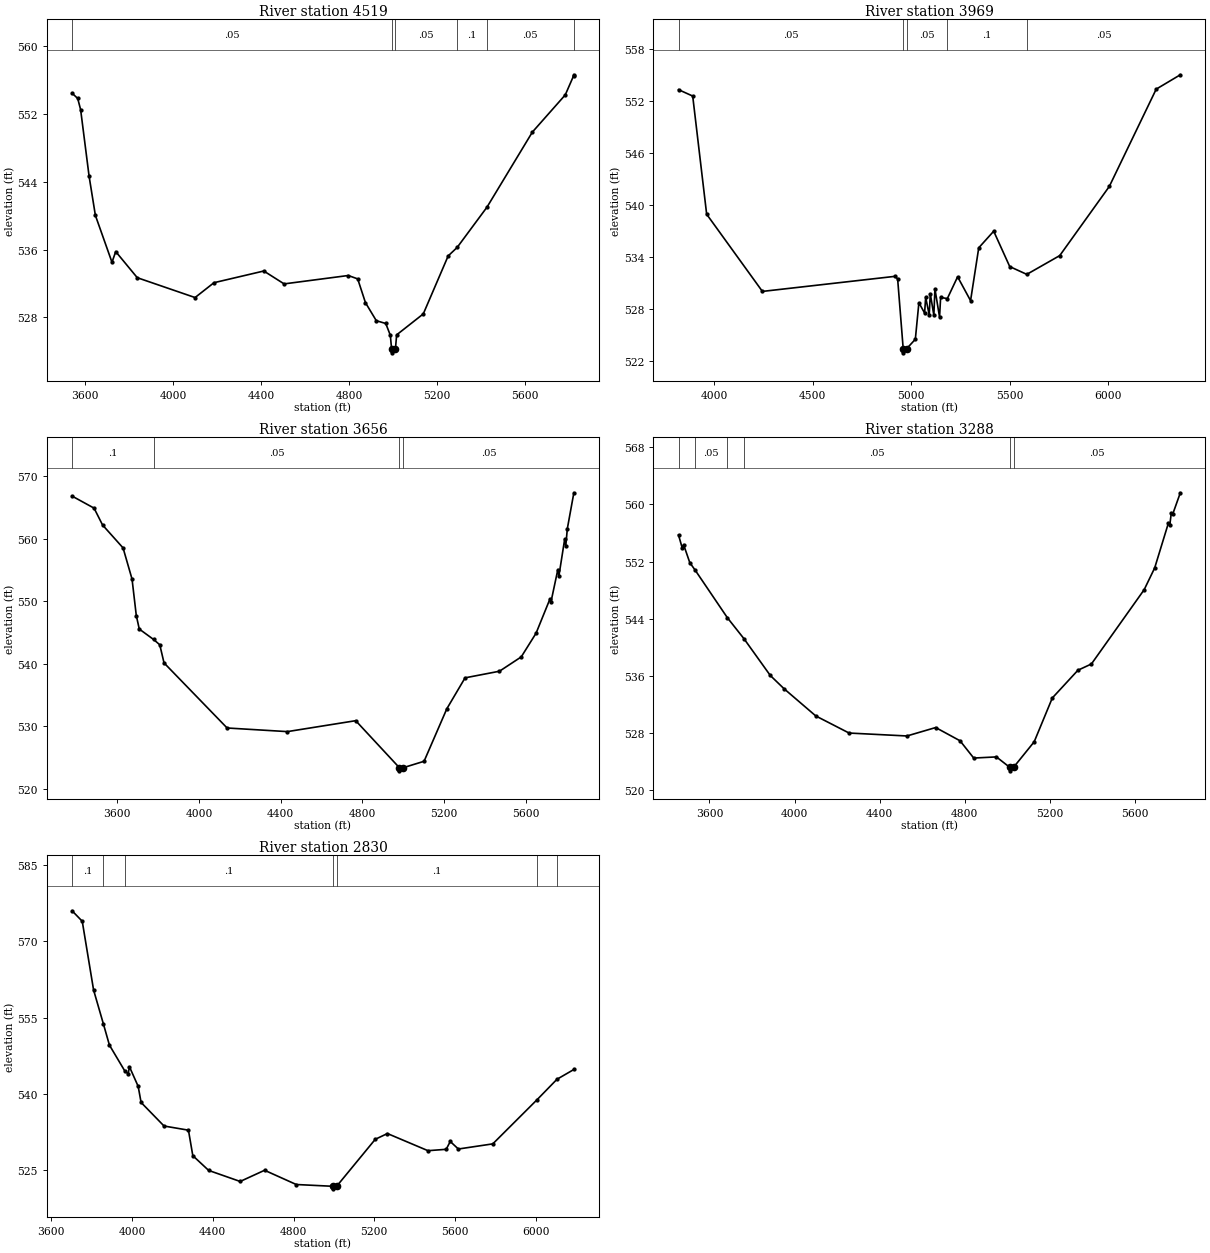
Type RM Length L Ch R = 1,4519,550,550,550
BEGIN DESCRIPTION:
Mapping XS ac1df20b
END DESCRIPTION:
XS GIS Cut Line= 3
      1974998.14     13491000.45      1975219.48     13490510.02
      1976334.45     13489169.45
#Sta/Elev= 30
  3541.1  554.45  3566.7  553.83  3580.0  552.51  3618.5  544.66  3647.1  540.04
  3722.6  534.51  3739.6  535.77  3837.6  532.69  4100.4  530.35  4186.3  532.10
  4412.9  533.48  4505.3  531.96  4797.0  532.95  4839.9  532.55  4875.1  529.75
  4924.5  527.62  4967.5  527.29  4988.3  525.90  4993.8  524.33  4994.3  523.83
  5011.6  524.33  5017.0  525.95  5138.1  528.42  5251.3  535.26  5292.2  536.26
  5427.8  541.01  5634.1  549.86  5783.8  554.25  5821.6  556.50  5822.8  556.62
#Mann=6,-1,0
  3541.1    0.05       0  4993.8    0.03       0  5011.6    0.05       0
  5292.2     0.1       0  5427.8    0.05       0  5821.6     0.1       0
Bank Sta=4993.8,5011.6
Exp/Cntr=0.3,0.1

Type RM Length L Ch R = 1,3969,313,313,313
BEGIN DESCRIPTION:
Mapping XS ea547250
END DESCRIPTION:
XS GIS Cut Line= 5
      1974976.45     13491048.19      1975523.30     13490531.72
      1975783.71     13490271.31      1976426.08     13489993.53
      1977146.54     13489906.73
#Sta/Elev= 30
  3820.1  553.31  3892.0  552.57  3962.8  538.91  4245.6  529.99  4917.7  531.73
  4931.8  531.44  4959.9  523.39  4960.4  522.89  4978.3  523.39  5021.6  524.46
  5039.6  528.68  5068.6  527.49  5074.0  529.31  5092.0  527.27  5097.5  529.71
  5115.5  527.24  5121.0  530.28  5144.5  527.02  5149.9  529.30  5183.9  529.16
  5236.1  531.68  5301.8  528.92  5343.3  535.03  5419.2  536.95  5500.6  532.86
  5587.1  531.96  5754.3  534.13  6005.7  542.12  6243.7  553.37  6366.1  555.03
#Mann=5,-1,0
  3820.1    0.05       0  4959.9    0.03       0  4978.3    0.05       0
  5183.9     0.1       0  5587.1    0.05       0
Bank Sta=4959.9,4978.3
Exp/Cntr=0.3,0.1

Type RM Length L Ch R = 1,3656,368,368,368
BEGIN DESCRIPTION:
UNT 001 in BCW 6.0
END DESCRIPTION:
XS GIS Cut Line= 4
      1974924.99     13491525.02      1975514.62     13490727.04
      1976356.63     13490301.69      1976855.75     13490158.46
#Sta/Elev= 30
  3379.5  566.82  3487.1  564.89  3528.7  562.19  3629.0  558.52  3672.9  553.53
  3693.7  547.69  3708.3  545.53  3778.4  543.86  3808.6  543.01  3829.4  540.11
  4138.0  529.69  4432.7  529.11  4767.1  530.86  4980.8  523.33  4981.3  522.83
  4999.3  523.33  5101.5  524.36  5212.9  532.77  5302.1  537.72  5470.4  538.78
  5576.8  541.07  5649.5  544.87  5716.9  550.31  5722.1  549.83  5755.9  555.05
  5761.1  554.03  5789.6  559.97  5794.8  558.85  5802.3  561.59  5834.3  567.35
#Mann=4,-1,0
  3379.5     0.1       0  3778.4    0.05       0  4980.8    0.03       0
  4999.3    0.05       0
Bank Sta=4980.8,4999.3
Exp/Cntr=0.3,0.1

Type RM Length L Ch R = 1,3288,458,458,458
BEGIN DESCRIPTION:
UNT 001 in BCW 5.0
END DESCRIPTION:
XS GIS Cut Line= 3
      1974998.16     13491712.25      1976225.00     13490775.00
      1976824.98     13490225.02
#Sta/Elev= 30
  3454.7  555.72  3472.2  553.90  3478.5  554.38  3507.6  551.86  3533.3  550.79
  3684.2  544.15  3762.5  541.20  3885.8  536.07  3950.2  534.22  4099.8  530.40
  4256.1  528.01  4527.9  527.60  4663.0  528.78  4777.3  526.93  4841.7  524.51
  4948.3  524.67  5010.6  523.22  5011.1  522.72  5029.1  523.22  5125.9  526.79
  5211.0  532.92  5331.3  536.80  5394.8  537.68  5642.7  548.08  5692.0  551.12
  5756.1  557.36  5762.9  557.11  5770.3  558.85  5777.1  558.68  5812.5  561.64
#Mann=6,-1,0
  3454.7     0.1       0  3533.3    0.05       0  3684.2     0.1       0
  3762.5    0.05       0  5010.6    0.03       0  5029.1    0.05       0
Bank Sta=5010.6,5029.1
Exp/Cntr=0.3,0.1

Type RM Length L Ch R = 1,2830,468,468,468
BEGIN DESCRIPTION:
UNT 001 in BCW 4.0
END DESCRIPTION:
XS GIS Cut Line= 3
      1975224.98     13492025.01      1976225.00     13491225.00
      1977424.99     13491325.00
#Sta/Elev= 30
  3703.5  575.99  3753.9  573.93  3810.0  560.42  3858.2  553.81  3888.4  549.59
  3964.7  544.49  3981.3  543.95  3987.7  545.32  4030.9  541.47  4045.3  538.31
  4158.9  533.68  4279.8  532.86  4301.4  527.85  4379.9  524.95  4535.9  522.78
  4656.8  524.98  4813.7  522.18  4995.0  521.83  4995.5  521.33  5013.5  521.83
  5204.9  531.07  5265.1  532.20  5465.8  528.83  5556.1  529.10  5576.2  530.64
  5616.3  529.16  5786.9  530.17  6007.1  538.89  6104.7  542.87  6188.3  544.79
#Mann=7,-1,0
  3703.5     0.1       0  3858.2    0.05       0  3964.7     0.1       0
  4995.0    0.07       0  5013.5     0.1       0  6007.1    0.05       0
  6104.7     0.1       0
Bank Sta=4995,5013.5
Exp/Cntr=0.3,0.1