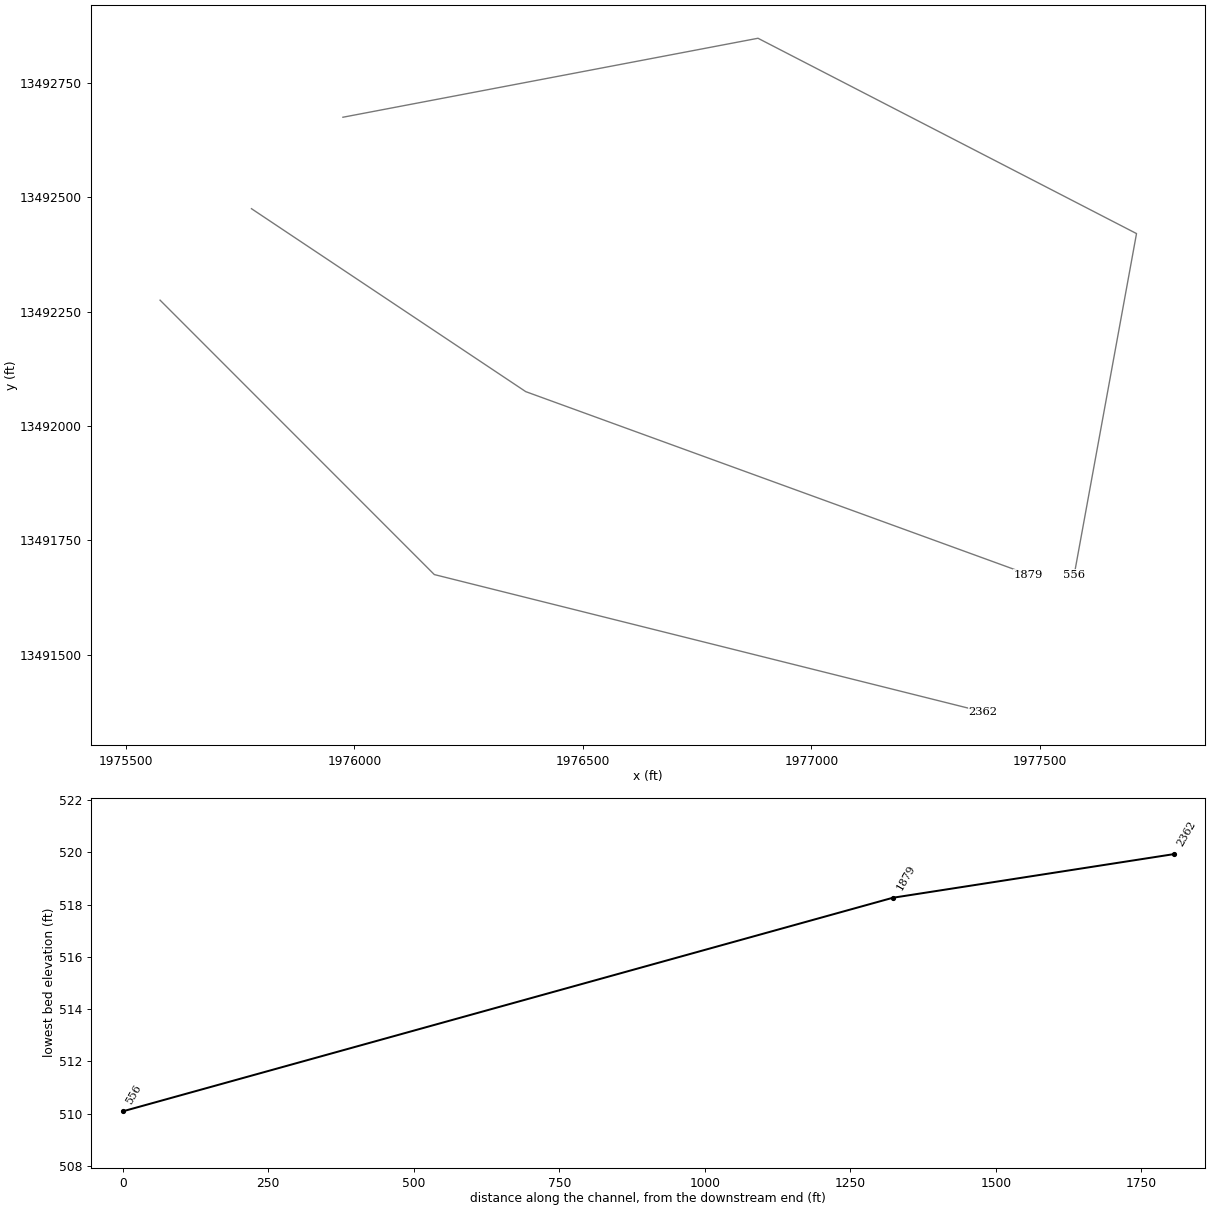
HEC-RAS study UNT 001 in BCW.prj: UNT 001 in BCW Base Level Engineering

--- UNT 001 in BCW.g01 (geometry) --- (continued)

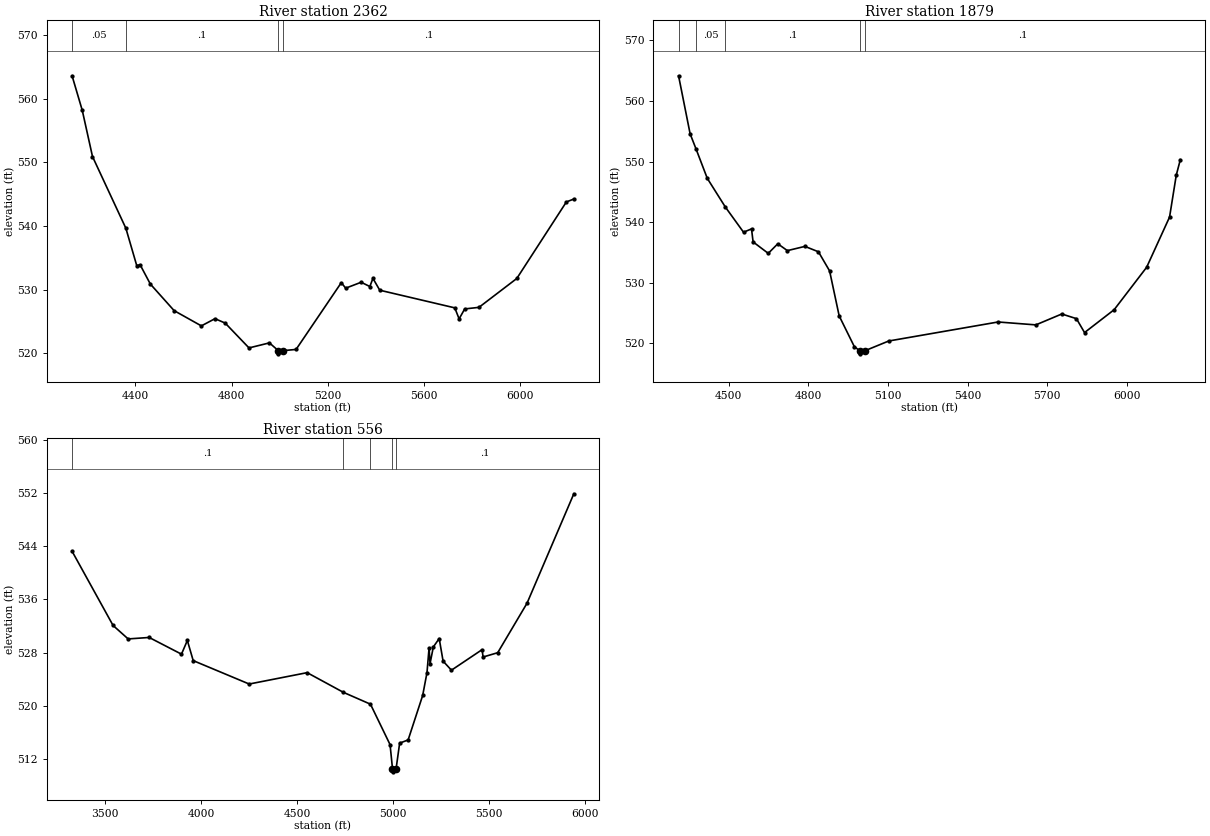
Type RM Length L Ch R = 1,2362,483,483,483
BEGIN DESCRIPTION:
UNT 001 in BCW 3.0
END DESCRIPTION:
XS GIS Cut Line= 3
      1975574.99     13492275.01      1976175.00     13491675.00
      1977375.03     13491374.99
#Sta/Elev= 30
  4136.4  563.59  4178.8  558.16  4221.3  550.91  4360.0  539.65  4405.1  533.80
  4419.3  533.91  4461.7  530.89  4560.7  526.71  4673.8  524.32  4730.4  525.45
  4772.8  524.76  4871.8  520.86  4956.7  521.65  4993.6  520.43  4994.1  519.93
  5012.4  520.43  5067.4  520.62  5255.5  531.11  5273.6  530.24  5338.0  531.17
  5374.1  530.50  5386.9  531.78  5415.3  529.92  5727.1  527.15  5745.1  525.42
  5768.3  526.98  5827.6  527.23  5984.8  531.76  6190.9  543.78  6221.9  544.24
#Mann=4,-1,0
  4136.4    0.05       0  4360.0     0.1       0  4993.6    0.07       0
  5012.4     0.1       0
Bank Sta=4993.6,5012.4
Exp/Cntr=0.3,0.1

Type RM Length L Ch R = 1,1879,1323,1323,1323
BEGIN DESCRIPTION:
UNT 001 in BCW 2.0
END DESCRIPTION:
XS GIS Cut Line= 3
      1975774.97     13492475.02      1976375.00     13492075.00
      1977474.99     13491675.00
#Sta/Elev= 30
  4310.4  564.17  4354.0  554.58  4376.8  552.03  4418.6  547.24  4486.6  542.51
  4555.3  538.34  4585.4  538.89  4591.4  536.74  4648.5  534.85  4684.5  536.43
  4720.6  535.30  4786.7  536.00  4837.7  535.11  4879.8  531.95  4915.9  524.52
  4973.0  519.45  4993.6  518.76  4994.1  518.26  5012.4  518.76  5102.7  520.38
  5515.0  523.52  5657.3  523.04  5755.1  524.84  5810.3  524.07  5840.9  521.77
  5952.6  525.55  6075.0  532.55  6161.4  540.84  6186.7  547.76  6202.0  550.32
#Mann=5,-1,0
  4310.4     0.1       0  4376.8    0.05       0  4486.6     0.1       0
  4993.6    0.07       0  5012.4     0.1       0
Bank Sta=4993.6,5012.4
Exp/Cntr=0.3,0.1

Type RM Length L Ch R = 1,556,0,0,0
BEGIN DESCRIPTION:
UNT 001 in BCW 1.0
END DESCRIPTION:
XS GIS Cut Line= 4
      1975975.02     13492675.00      1976883.11     13492847.70
      1977711.23     13492420.61      1977575.00     13491674.99
#Sta/Elev= 30
  3326.7  543.25  3540.4  532.09  3618.9  530.07  3728.4  530.29  3896.7  527.78
  3927.3  529.84  3957.8  526.81  4249.5  523.29  4551.4  525.00  4740.3  522.04
  4881.3  520.26  4983.4  514.18  4996.0  510.59  4996.5  510.09  5015.0  510.59
  5033.3  514.40  5077.6  514.89  5153.3  521.57  5175.8  525.01  5186.6  528.71
  5191.7  526.36  5208.9  528.87  5239.4  530.13  5259.7  526.73  5303.2  525.37
  5462.9  528.46  5468.0  527.35  5544.3  528.00  5696.8  535.43  5940.8  551.89
#Mann=5,-1,0
  3326.7     0.1       0  4740.3    0.05       0  4881.3     0.1       0
  4996.0    0.07       0  5015.0     0.1       0
Bank Sta=4996,5015
Exp/Cntr=0.3,0.1

Chan Stop Cuts=-1