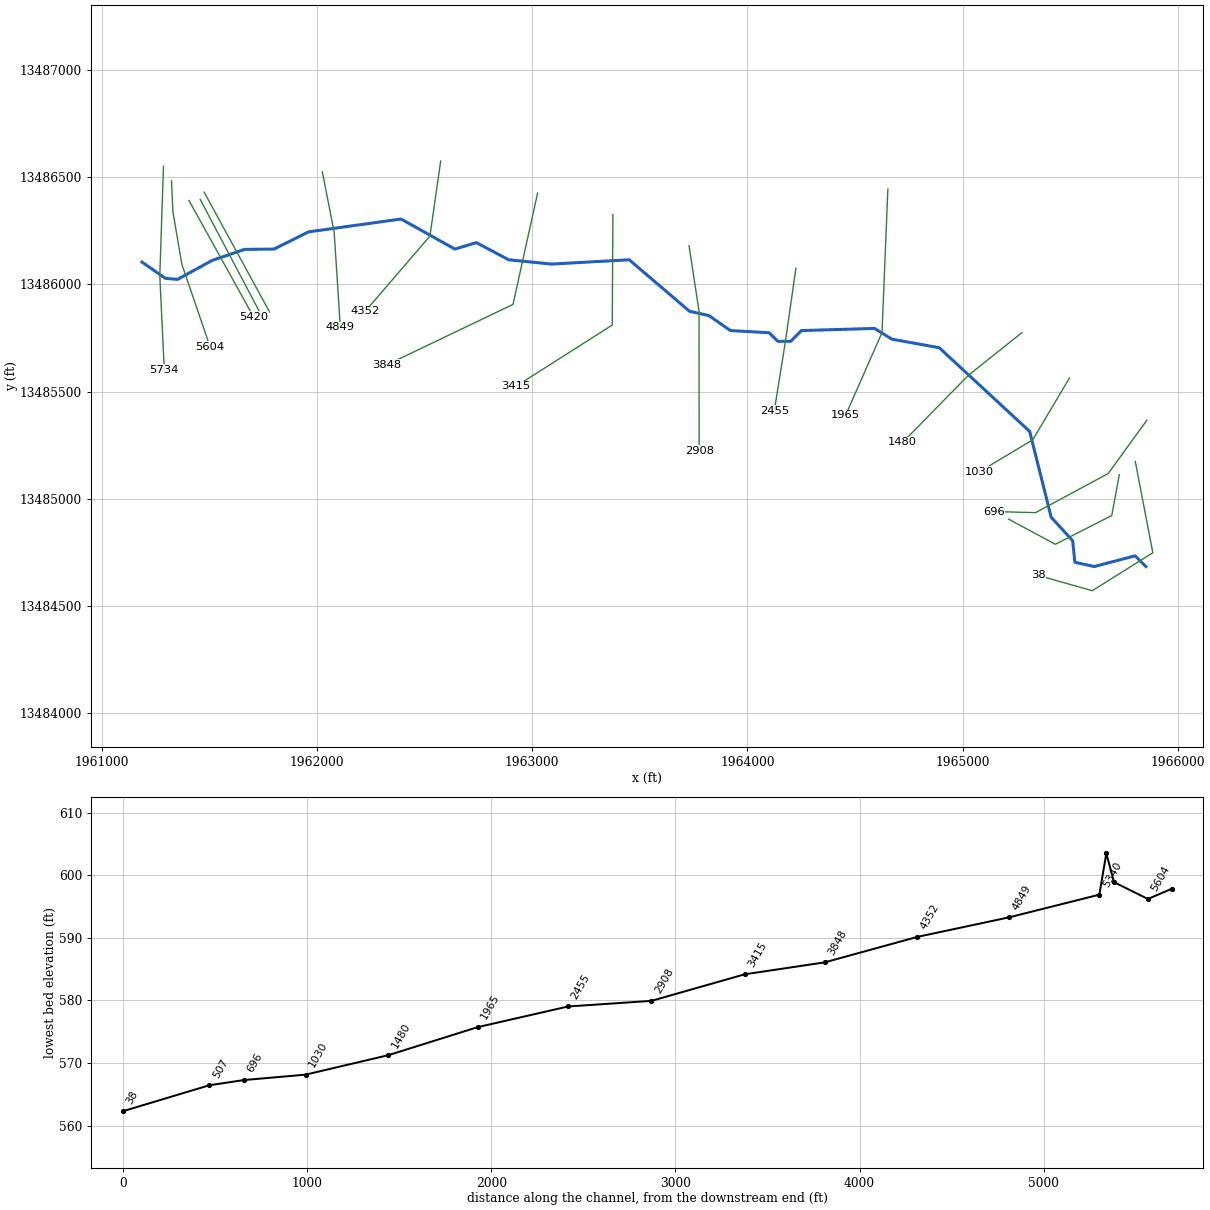
--- UNT 002 in BCW.prj (project) ---

Proj Title=UNT 002 in BCW Base Level Engineering
Current Plan=p01
Default Exp/Contr=0.3,0.1
English Units
Geom File=g01
Flow File=f01
Plan File=p01
BEGIN DESCRIPTION:
UNT 002 in BCW
END DESCRIPTION:

--- UNT 002 in BCW.p01 (plan) ---

Plan Title=Multiple Run
Short Identifier=Multiple
Geom File=g01
Flow File=f01
Subcritical Flow
K Sum by GR= 0
Std Step Tol= 0.01
Critical Tol= 0.01
Num of Std Step Trials= 20
Max Error Tol= 0.3
Flow Tol Ratio= 0.001
Split Flow NTrial= 30
Split Flow Tol= 0.02
Split Flow Ratio= 0.02
Log Output Level= 0
Friction Slope Method= 1
Unsteady Friction Slope Method= 2
Unsteady Bridges Friction Slope Method= 1
Parabolic Critical Depth
Global Vel Dist=  1 , 1 , 1
Global Log Level= 0
CheckData=True
Encroach Param= -1, 0, 0, 0
BEGIN DESCRIPTION:
Multiple Run
END DESCRIPTION:

--- UNT 002 in BCW.f01 (steady flow) ---

Flow Title=Multiple
Number of Profiles=7
Profile Names=10-year,25-year,50-year,1pct_min,100-year,1pct_plu,500-year
River Rch & RM= UNT 002 in BCW,Reach-1,5734
     129     175     212     129     257     512     383
River Rch & RM= UNT 002 in BCW,Reach-1,4352
     189     262     322     198     395     787     605
River Rch & RM= UNT 002 in BCW,Reach-1,38
     343     489     613     384     767    1530    1221
Boundary for River Rch & Prof#=UNT 002 in BCW,Reach-1,1
Up Type=0
Dn Type=3
Dn Slope=0.005
Boundary for River Rch & Prof#=UNT 002 in BCW,Reach-1,2
Up Type=0
Dn Type=3
Dn Slope=0.005
Boundary for River Rch & Prof#=UNT 002 in BCW,Reach-1,3
Up Type=0
Dn Type=3
Dn Slope=0.005
Boundary for River Rch & Prof#=UNT 002 in BCW,Reach-1,4
Up Type=0
Dn Type=3
Dn Slope=0.005
Boundary for River Rch & Prof#=UNT 002 in BCW,Reach-1,5
Up Type=0
Dn Type=3
Dn Slope=0.005
Boundary for River Rch & Prof#=UNT 002 in BCW,Reach-1,6
Up Type=0
Dn Type=3
Dn Slope=0.005
Boundary for River Rch & Prof#=UNT 002 in BCW,Reach-1,7
Up Type=0
Dn Type=3
Dn Slope=0.005

--- UNT 002 in BCW.g01 (geometry) ---

Geom Title=Existing Conditions

River Reach=UNT 002 in BCW,Reach-1
Reach XY= 30
      1961187.27     13486103.99      1961295.99     13486028.07
      1961352.24     13486023.21      1961514.48     13486111.93
      1961663.96     13486162.97      1961800.80     13486164.54
      1961960.80     13486244.54      1962390.80     13486304.54
      1962640.80     13486164.54      1962740.80     13486194.54
      1962890.80     13486114.54      1963090.80     13486094.54
      1963450.80     13486114.54      1963730.80     13485874.54
      1963820.80     13485854.54      1963920.80     13485784.54
      1964100.80     13485774.54      1964140.80     13485734.54
      1964200.80     13485734.54      1964250.80     13485784.54
      1964590.80     13485794.54      1964670.80     13485744.54
      1964890.80     13485704.54      1965310.80     13485314.54
      1965410.80     13484914.54      1965510.80     13484804.54
      1965520.80     13484704.54      1965610.80     13484684.54
      1965800.80     13484734.54      1965850.80     13484684.54

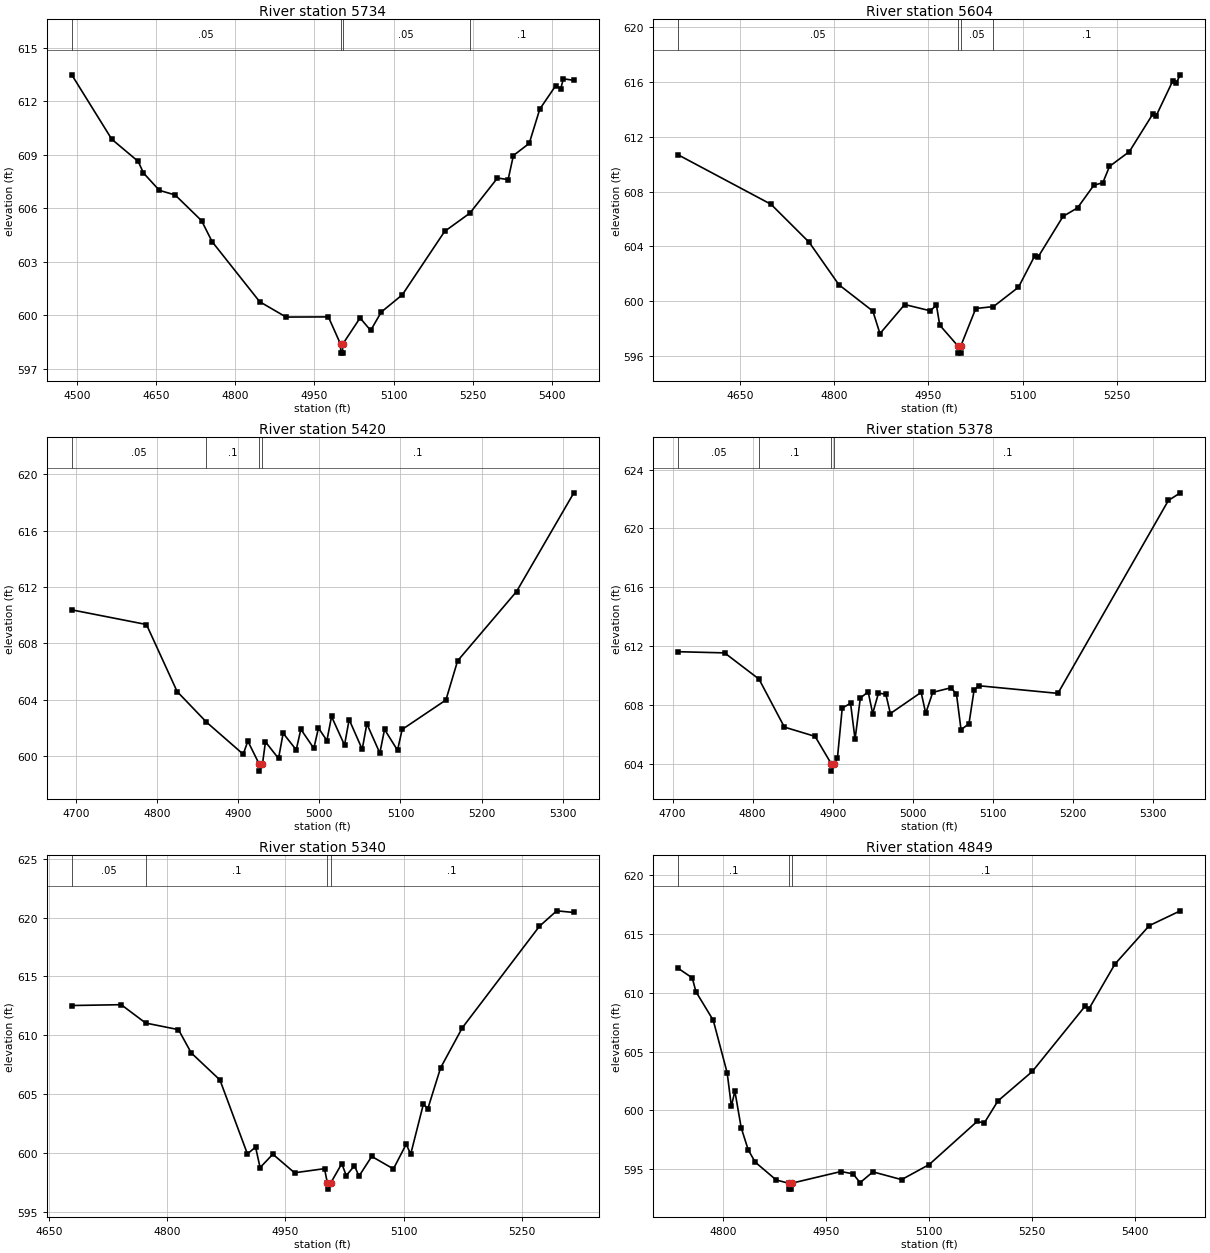
Type RM Length L Ch R = 1,5734,130,130,130
BEGIN DESCRIPTION:
UNT 002 in BCW 11.0
END DESCRIPTION:
XS GIS Cut Line= 3
      1961287.32     13486550.71      1961270.12     13486039.86
      1961290.96     13485600.59
#Sta/Elev= 30
  4490.3  613.47  4566.1  609.86  4616.1  608.62  4626.1  607.97  4656.1  607.00
  4686.1  606.74  4736.1  605.30  4756.2  604.12  4846.2  600.76  4896.2  599.90
  4976.3  599.91  4999.4  598.38  4999.6  597.88  5003.1  597.88  5003.4  598.38
  5036.3  599.85  5056.4  599.15  5076.4  600.18  5116.4  601.15  5196.5  604.70
  5244.2  605.72  5296.6  607.69  5316.7  607.60  5326.7  608.95  5356.7  609.63
  5376.7  611.55  5406.8  612.86  5416.4  612.70  5421.4  613.25  5441.2  613.16
#Mann=4,-1,0
  4490.3    0.05       0  4999.4   0.035       0  5003.4    0.05       0
  5244.2     0.1       0
Bank Sta=4999.4,5003.4
Exp/Cntr=0.3,0.1

Type RM Length L Ch R = 1,5604,184,184,184
BEGIN DESCRIPTION:
Mapping XS 61972e47
END DESCRIPTION:
XS GIS Cut Line= 4
      1961324.55     13486482.51      1961330.80     13486339.81
      1961372.55     13486093.68      1961503.92     13485708.23
#Sta/Elev= 30
  4551.4  610.67  4699.2  607.07  4760.0  604.30  4807.3  601.21  4861.4  599.29
  4872.7  597.65  4912.1  599.77  4953.1  599.31  4962.6  599.74  4967.9  598.27
  4997.3  596.73  4997.5  596.23  5001.0  596.23  5001.3  596.73  5025.3  599.48
  5053.5  599.62  5093.3  601.03  5119.4  603.33  5124.7  603.24  5164.3  606.19
  5187.4  606.81  5213.4  608.46  5227.7  608.64  5238.3  609.83  5270.0  610.91
  5307.5  613.66  5312.7  613.52  5338.8  616.03  5344.1  615.87  5351.1  616.50
#Mann=4,-1,0
  4551.4    0.05       0  4997.3   0.035       0  5001.3    0.05       0
  5053.5     0.1       0
Bank Sta=4997.3,5001.3
Exp/Cntr=0.3,0.1

Type RM Length L Ch R = 1,5420,42,42,42
BEGIN DESCRIPTION:
Mapping XS 7e610716
END DESCRIPTION:
XS GIS Cut Line= 2
      1961405.69     13486390.95      1961704.95     13485849.67
#Sta/Elev= 30
  4695.1  610.37  4787.1  609.33  4824.9  604.57  4861.0  602.40  4906.3  600.12
  4912.0  601.05  4926.0  599.42  4926.3  598.92  4930.0  599.42  4933.7  601.00
  4949.8  599.82  4955.5  601.61  4971.6  600.43  4977.3  601.89  4993.3  600.54
  4999.0  601.98  5009.4  601.09  5015.1  602.80  5031.1  600.77  5036.8  602.58
  5052.9  600.47  5058.6  602.28  5074.6  600.20  5080.4  601.88  5096.4  600.40
  5102.1  601.88  5156.0  603.97  5170.4  606.75  5243.0  611.67  5313.6  618.68
#Mann=4,-1,0
  4695.1    0.05       0  4861.0     0.1       0  4926.0    0.07       0
  4930.0     0.1       0
Bank Sta=4926,4930
Exp/Cntr=0.3,0.1

Type RM Length L Ch R = 1,5378,38,38,38
BEGIN DESCRIPTION:
Mapping XS 7e7ea979
END DESCRIPTION:
XS GIS Cut Line= 2
      1961457.74     13486396.21      1961749.41     13485841.52
#Sta/Elev= 30
  4707.1  611.63  4765.0  611.55  4807.9  609.77  4839.6  606.51  4877.9  605.88
  4898.1  604.02  4898.4  603.52  4902.1  604.02  4905.8  604.40  4911.8  607.80
  4922.2  608.13  4927.8  605.68  4934.4  608.49  4944.2  608.90  4949.8  607.43
  4957.0  608.81  4966.2  608.75  4971.9  607.43  5010.3  608.87  5016.0  607.45
  5024.8  608.87  5047.4  609.18  5054.4  608.76  5060.1  606.33  5070.0  606.74
  5076.4  609.03  5082.1  609.32  5181.0  608.80  5318.9  621.90  5333.8  622.42
#Mann=4,-1,0
  4707.1    0.05       0  4807.9     0.1       0  4898.1    0.07       0
  4902.1     0.1       0
Bank Sta=4898.1,4902.1
Exp/Cntr=0.3,0.1

Type RM Length L Ch R = 1,5340,491,491,491
BEGIN DESCRIPTION:
Mapping XS ee92ae67
END DESCRIPTION:
XS GIS Cut Line= 2
      1961475.98     13486430.05      1961780.32     13485870.79
#Sta/Elev= 30
  4679.0  612.53  4741.7  612.60  4772.7  611.04  4814.3  610.48  4830.5  608.50
  4866.9  606.20  4901.7  599.92  4912.1  600.49  4917.8  598.75  4934.0  599.89
  4961.5  598.31  4999.5  598.66  5003.2  597.42  5003.5  596.92  5007.2  597.42
  5021.4  599.09  5027.1  598.07  5037.5  598.91  5043.2  598.02  5059.4  599.70
  5086.9  598.64  5103.1  600.74  5108.8  599.89  5124.9  604.15  5130.6  603.77
  5146.7  607.23  5174.3  610.64  5272.1  619.27  5294.0  620.58  5315.7  620.44
#Mann=4,-1,0
  4679.0    0.05       0  4772.7     0.1       0  5003.2    0.07       0
  5007.2     0.1       0
Bank Sta=5003.2,5007.2
Exp/Cntr=0.3,0.1

Type RM Length L Ch R = 1,4849,497,497,497
BEGIN DESCRIPTION:
UNT 002 in BCW 10.0
END DESCRIPTION:
XS GIS Cut Line= 3
      1962025.00     13486525.02      1962080.16     13486242.53
      1962108.80     13485799.88
#Sta/Elev= 30
  4734.6  612.09  4755.0  611.28  4760.4  610.10  4785.6  607.67  4805.9  603.19
  4812.0  600.35  4817.1  601.64  4826.3  598.52  4836.5  596.64  4846.7  595.59
  4877.3  594.07  4895.6  593.79  4895.9  593.29  4899.4  593.29  4899.6  593.79
  4971.7  594.79  4989.3  594.59  4999.5  593.84  5018.2  594.76  5060.0  594.10
  5100.1  595.38  5170.1  599.06  5180.3  598.91  5200.3  600.80  5250.4  603.31
  5327.7  608.90  5332.7  608.62  5370.7  612.45  5420.8  615.73  5466.0  616.99
#Mann=3,-1,0
  4734.6     0.1       0  4895.6    0.07       0  4899.6     0.1       0
Bank Sta=4895.6,4899.6
Exp/Cntr=0.3,0.1

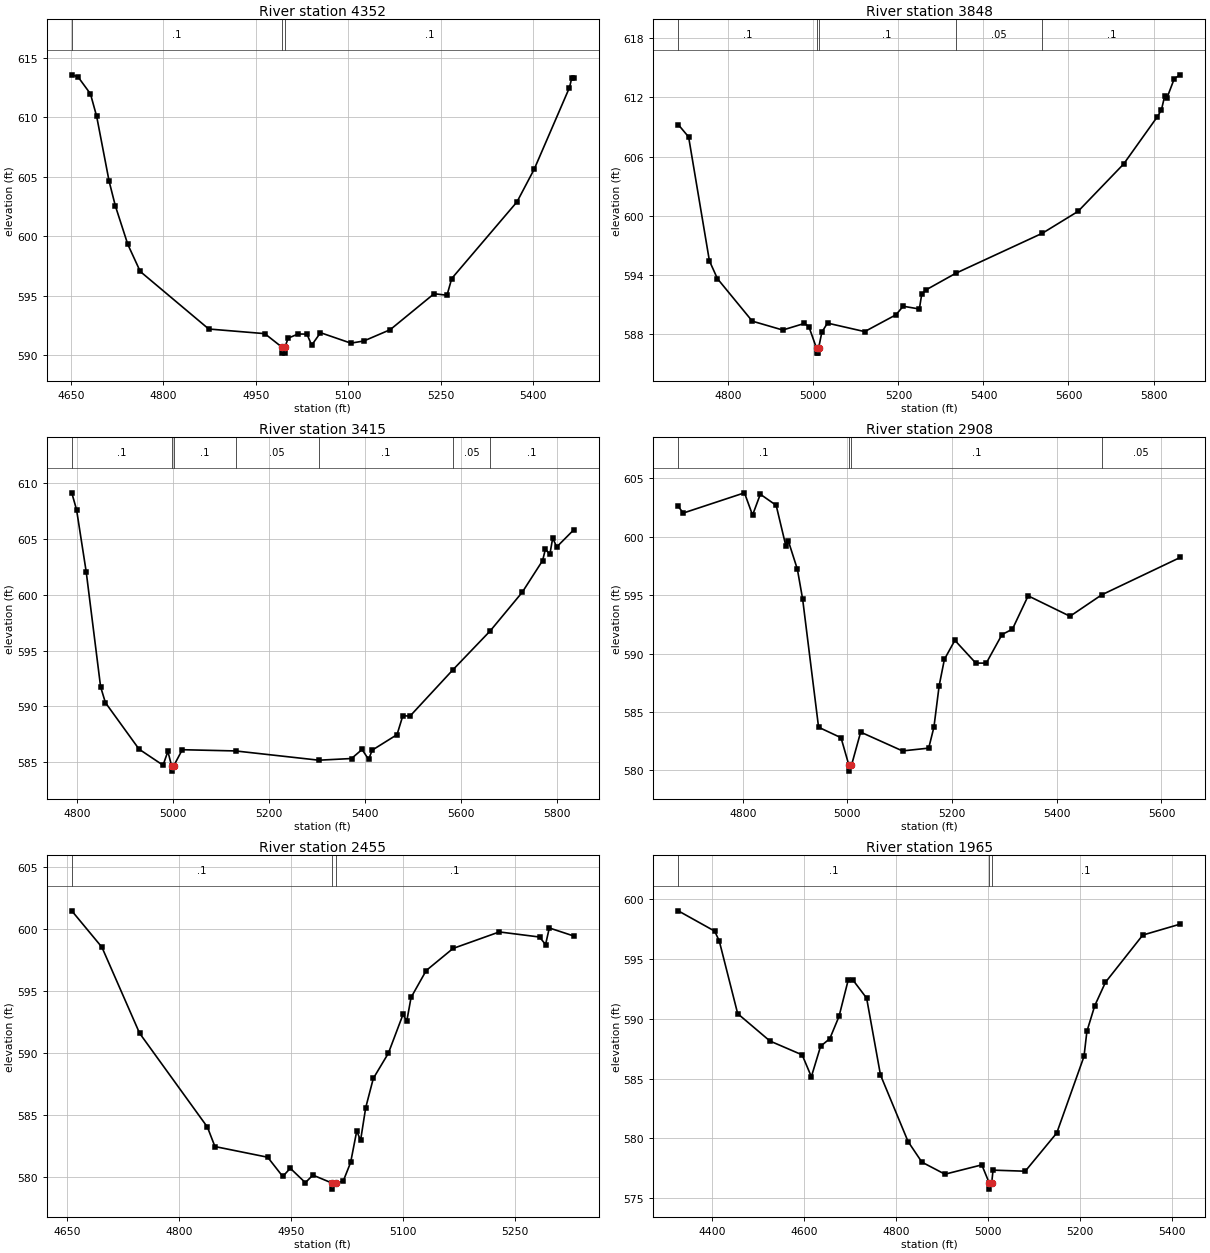
Type RM Length L Ch R = 1,4352,504,504,504
BEGIN DESCRIPTION:
UNT 002 in BCW 9.0
END DESCRIPTION:
XS GIS Cut Line= 3
      1962574.99     13486574.96      1962525.00     13486225.00
      1962225.00     13485875.00
#Sta/Elev= 30
  4651.2  613.59  4661.3  613.42  4681.5  611.99  4691.6  610.09  4711.8  604.63
  4721.9  602.56  4742.1  599.32  4762.3  597.04  4873.4  592.20  4964.3  591.81
  4992.2  590.67  4992.6  590.17  4996.7  590.17  4997.0  590.67  5002.2  591.43
  5018.4  591.78  5032.7  591.77  5040.4  590.84  5054.7  591.89  5104.0  591.01
  5124.9  591.19  5167.7  592.14  5239.0  595.17  5259.9  595.04  5267.6  596.45
  5373.5  602.90  5401.5  605.66  5458.6  612.52  5462.4  613.34  5465.7  613.34
#Mann=3,-1,0
  4651.2     0.1       0  4992.2    0.07       0  4997.0     0.1       0
Bank Sta=4992.2,4997
Exp/Cntr=0.3,0.1

Type RM Length L Ch R = 1,3848,433,433,433
BEGIN DESCRIPTION:
UNT 002 in BCW 8.0
END DESCRIPTION:
XS GIS Cut Line= 3
      1963025.00     13486425.00      1962910.88     13485906.59
      1962324.97     13485624.99
#Sta/Elev= 30
  4682.1  609.24  4706.5  607.99  4755.4  595.44  4774.3  593.63  4856.2  589.33
  4927.9  588.43  4979.0  589.10  4989.4  588.77  5007.3  586.59  5007.7  586.09
  5011.9  586.09  5012.2  586.59  5020.0  588.23  5033.2  589.13  5120.6  588.27
  5194.1  589.97  5211.2  590.84  5249.2  590.56  5254.8  592.06  5263.8  592.47
  5334.9  594.18  5538.8  598.24  5622.5  600.45  5729.8  605.25  5809.1  610.04
  5818.6  610.73  5826.2  612.13  5831.8  611.96  5848.9  613.90  5863.0  614.28
#Mann=5,-1,0
  4682.1     0.1       0  5007.3    0.07       0  5012.2     0.1       0
  5334.9    0.05       0  5538.8     0.1       0
Bank Sta=5007.3,5012.2
Exp/Cntr=0.3,0.1

Type RM Length L Ch R = 1,3415,507,507,507
BEGIN DESCRIPTION:
UNT 002 in BCW 7.0
END DESCRIPTION:
XS GIS Cut Line= 3
      1963375.00     13486325.03      1963371.82     13485810.24
      1962925.01     13485525.01
#Sta/Elev= 30
  4789.5  609.14  4799.5  607.62  4819.5  602.07  4849.5  591.75  4859.5  590.33
  4929.5  586.16  4979.5  584.72  4989.5  585.96  4997.1  584.69  4997.4  584.19
  5002.0  584.69  5019.5  586.11  5130.3  586.00  5303.7  585.17  5371.7  585.32
  5393.6  586.13  5407.3  585.24  5414.7  586.07  5466.4  587.46  5478.5  589.16
  5493.4  589.12  5582.4  593.26  5660.3  596.76  5726.9  600.22  5769.3  603.06
  5775.2  604.08  5784.5  603.63  5790.4  605.08  5798.8  604.29  5834.4  605.83
#Mann=7,-1,0
  4789.5     0.1       0  4997.1    0.07       0  5002.0     0.1       0
  5130.3    0.05       0  5303.7     0.1       0  5582.4    0.05       0
  5660.3     0.1       0
Bank Sta=4997.1,5002
Exp/Cntr=0.3,0.1

Type RM Length L Ch R = 1,2908,453,453,453
BEGIN DESCRIPTION:
UNT 002 in BCW 6.0
END DESCRIPTION:
XS GIS Cut Line= 3
      1963728.59     13486180.02      1963775.00     13485875.00
      1963775.47     13485224.33
#Sta/Elev= 30
  4676.8  602.60  4686.5  602.04  4803.3  603.77  4818.8  601.86  4833.6  603.65
  4863.9  602.70  4882.4  599.22  4887.4  599.61  4904.4  597.23  4914.5  594.66
  4944.9  583.70  4987.8  582.80  5002.9  580.44  5003.2  579.94  5007.8  580.44
  5025.3  583.28  5105.3  581.67  5155.3  581.91  5165.3  583.71  5175.3  587.26
  5185.3  589.51  5205.3  591.14  5245.3  589.19  5265.3  589.19  5295.3  591.63
  5315.3  592.10  5345.3  594.95  5425.3  593.20  5485.6  595.03  5636.0  598.24
#Mann=4,-1,0
  4676.8     0.1       0  5002.9    0.07       0  5007.8     0.1       0
  5485.6    0.05       0
Bank Sta=5002.9,5007.8
Exp/Cntr=0.3,0.1

Type RM Length L Ch R = 1,2455,490,490,490
BEGIN DESCRIPTION:
UNT 002 in BCW 5.0
END DESCRIPTION:
XS GIS Cut Line= 3
      1964225.00     13486074.98      1964175.00     13485725.00
      1964124.48     13485409.55
#Sta/Elev= 30
  4656.1  601.46  4696.5  598.53  4747.0  591.60  4837.9  584.04  4848.0  582.47
  4918.7  581.61  4938.9  580.06  4949.0  580.72  4969.2  579.56  4979.3  580.17
  5004.5  579.54  5004.9  579.04  5009.7  579.54  5019.8  579.66  5029.9  581.19
  5038.1  583.73  5043.2  582.96  5050.1  585.60  5060.3  587.96  5080.5  589.99
  5100.1  593.11  5105.2  592.59  5110.9  594.48  5131.2  596.65  5167.2  598.43
  5229.2  599.76  5283.1  599.35  5291.2  598.74  5296.2  600.08  5329.1  599.43
#Mann=3,-1,0
  4656.1     0.1       0  5004.5    0.07       0  5009.7     0.1       0
Bank Sta=5004.5,5009.7
Exp/Cntr=0.3,0.1

Type RM Length L Ch R = 1,1965,485,485,485
BEGIN DESCRIPTION:
UNT 002 in BCW 4.0
END DESCRIPTION:
XS GIS Cut Line= 3
      1964652.20     13486444.11      1964625.00     13485775.00
      1964455.50     13485389.15
#Sta/Elev= 30
  4326.8  599.04  4406.0  597.34  4416.0  596.51  4456.0  590.43  4526.1  588.14
  4596.1  586.98  4616.1  585.15  4636.2  587.70  4656.2  588.34  4676.2  590.20
  4696.2  593.25  4706.2  593.26  4736.2  591.73  4766.3  585.30  4826.3  579.72
  4856.3  578.00  4906.4  576.99  4986.5  577.77  5002.8  576.24  5003.2  575.74
  5008.0  576.24  5010.9  577.33  5080.9  577.24  5149.4  580.44  5208.6  586.85
  5214.9  588.95  5232.0  591.10  5255.3  593.06  5336.3  597.01  5417.9  597.93
#Mann=3,-1,0
  4326.8     0.1       0  5002.8    0.07       0  5008.0     0.1       0
Bank Sta=5002.8,5008
Exp/Cntr=0.3,0.1

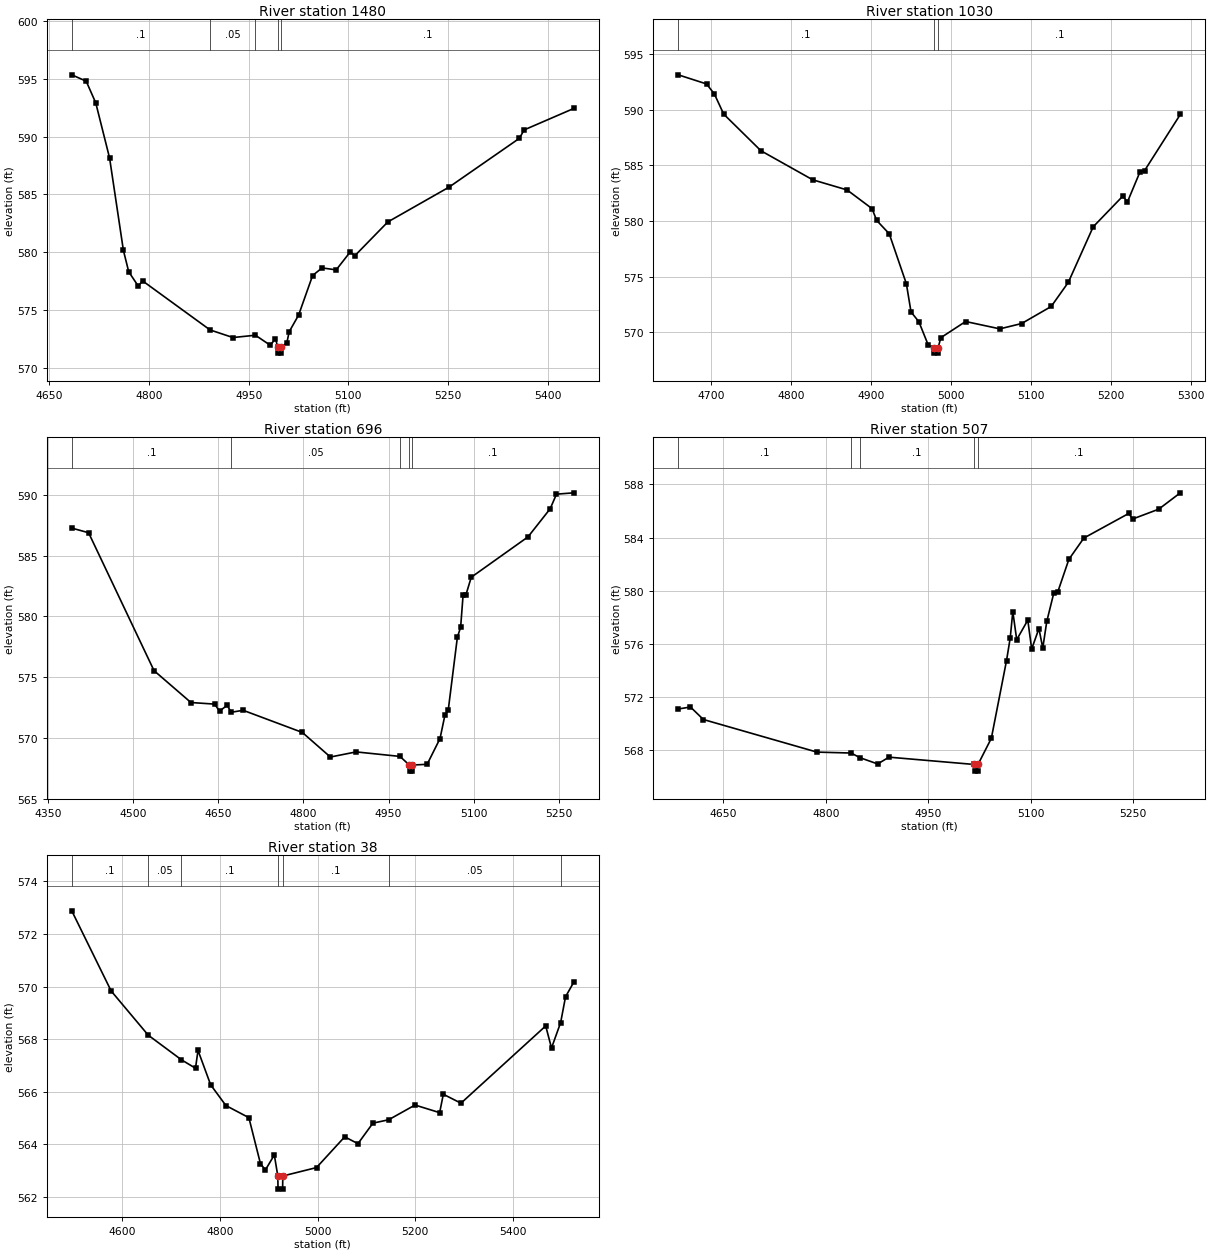
Type RM Length L Ch R = 1,1480,450,450,450
BEGIN DESCRIPTION:
UNT 002 in BCW 3.0
END DESCRIPTION:
XS GIS Cut Line= 3
      1965275.03     13485775.03      1965025.00     13485575.00
      1964720.78     13485263.37
#Sta/Elev= 30
  4683.6  595.36  4705.3  594.81  4719.7  592.93  4740.5  588.16  4761.3  580.16
  4769.3  578.31  4783.7  577.06  4790.1  577.52  4891.7  573.27  4926.2  572.61
  4960.0  572.81  4982.2  571.95  4990.2  572.49  4993.9  571.76  4994.3  571.26
  4998.8  571.26  4999.2  571.76  5007.3  572.16  5010.9  573.12  5025.0  574.55
  5046.1  577.98  5060.3  578.64  5081.6  578.47  5102.7  580.02  5109.9  579.71
  5159.3  582.62  5251.3  585.63  5357.3  589.86  5364.5  590.59  5439.3  592.45
#Mann=5,-1,0
  4683.6     0.1       0  4891.7    0.05       0  4960.0     0.1       0
  4993.9    0.07       0  4999.2     0.1       0
Bank Sta=4993.9,4999.2
Exp/Cntr=0.3,0.1

Type RM Length L Ch R = 1,1030,334,334,334
BEGIN DESCRIPTION:
UNT 002 in BCW 2.0
END DESCRIPTION:
XS GIS Cut Line= 3
      1965495.95     13485563.92      1965325.00     13485275.00
      1965075.04     13485125.02
#Sta/Elev= 30
  4659.4  593.14  4694.8  592.32  4704.6  591.41  4716.2  589.61  4762.7  586.32
  4827.4  583.71  4870.3  582.80  4901.5  581.12  4907.3  580.06  4923.0  578.86
  4944.4  574.37  4950.2  571.84  4960.0  570.96  4971.9  568.83  4978.8  568.64
  4979.2  568.14  4983.7  568.14  4984.2  568.64  4987.3  569.52  5018.4  570.98
  5061.2  570.32  5088.4  570.80  5125.3  572.33  5146.7  574.50  5177.8  579.49
  5214.7  582.24  5220.6  581.73  5236.1  584.40  5241.9  584.53  5286.6  589.58
#Mann=3,-1,0
  4659.4     0.1       0  4978.8    0.07       0  4984.2     0.1       0
Bank Sta=4978.8,4984.2
Exp/Cntr=0.3,0.1

Type RM Length L Ch R = 1,696,189,189,189
BEGIN DESCRIPTION:
Mapping XS c262739a
END DESCRIPTION:
XS GIS Cut Line= 4
      1965855.34     13485366.81      1965675.64     13485118.09
      1965338.40     13484935.80      1965144.37     13484941.01
#Sta/Elev= 30
  4392.1  587.26  4421.7  586.88  4537.0  575.54  4602.0  572.92  4643.8  572.79
  4652.3  572.21  4665.7  572.69  4673.0  572.12  4694.0  572.28  4798.2  570.46
  4847.6  568.44  4892.9  568.86  4970.1  568.49  4986.7  567.78  4987.2  567.28
  4991.7  567.28  4992.1  567.78  5018.0  567.84  5040.7  569.96  5049.4  571.90
  5055.1  572.27  5071.3  578.30  5077.0  579.11  5081.4  581.80  5086.5  581.80
  5095.7  583.22  5195.7  586.54  5234.7  588.85  5245.8  590.05  5276.4  590.16
#Mann=5,-1,0
  4392.1     0.1       0  4673.0    0.05       0  4970.1     0.1       0
  4986.7    0.07       0  4992.1     0.1       0
Bank Sta=4986.7,4992.1
Exp/Cntr=0.3,0.1

Type RM Length L Ch R = 1,507,469,469,469
BEGIN DESCRIPTION:
Mapping XS 42bc587f
END DESCRIPTION:
XS GIS Cut Line= 4
      1965727.35     13485112.56      1965692.19     13484922.45
      1965430.47     13484788.33      1965213.05     13484905.50
#Sta/Elev= 30
  4584.3  571.11  4602.2  571.26  4621.1  570.32  4787.2  567.87  4837.2  567.80
  4850.1  567.45  4876.0  566.98  4892.6  567.49  5017.4  566.94  5017.9  566.44
  5022.4  566.44  5022.8  566.94  5042.3  568.91  5064.5  574.75  5069.9  576.45
  5073.7  578.43  5079.4  576.32  5095.6  577.79  5101.3  575.62  5111.9  577.16
  5117.5  575.69  5123.4  577.70  5133.8  579.86  5139.4  579.90  5155.7  582.36
  5177.6  583.96  5243.3  585.81  5248.9  585.39  5287.1  586.13  5318.7  587.36
#Mann=5,-1,0
  4584.3     0.1       0  4837.2    0.05       0  4850.1     0.1       0
  5017.4    0.07       0  5022.8     0.1       0
Bank Sta=5017.4,5022.8
Exp/Cntr=0.3,0.1

Type RM Length L Ch R = 1,38,0,0,0
BEGIN DESCRIPTION:
UNT 002 in BCW 1.0
END DESCRIPTION:
XS GIS Cut Line= 4
      1965801.57     13485174.18      1965882.95     13484748.84
      1965601.91     13484571.97      1965349.56     13484643.45
#Sta/Elev= 30
  4497.0  572.88  4577.6  569.83  4653.4  568.15  4721.5  567.21  4750.2  566.89
  4755.3  567.57  4781.2  566.26  4812.4  565.47  4859.4  565.01  4883.1  563.26
  4893.2  563.02  4911.5  563.59  4918.6  562.79  4919.1  562.29  4928.4  562.29
  4928.9  562.79  4997.8  563.11  5055.5  564.28  5082.6  564.02  5113.2  564.80
  5145.5  564.93  5199.4  565.49  5249.8  565.20  5257.3  565.90  5293.4  565.56
  5466.8  568.50  5478.7  567.66  5497.4  568.63  5507.4  569.61  5524.4  570.17
#Mann=7,-1,0
  4497.0     0.1       0  4653.4    0.05       0  4721.5     0.1       0
  4918.6    0.07       0  4928.9     0.1       0  5145.5    0.05       0
  5497.4     0.1       0
Bank Sta=4918.6,4928.9
Exp/Cntr=0.3,0.1

Chan Stop Cuts=-1