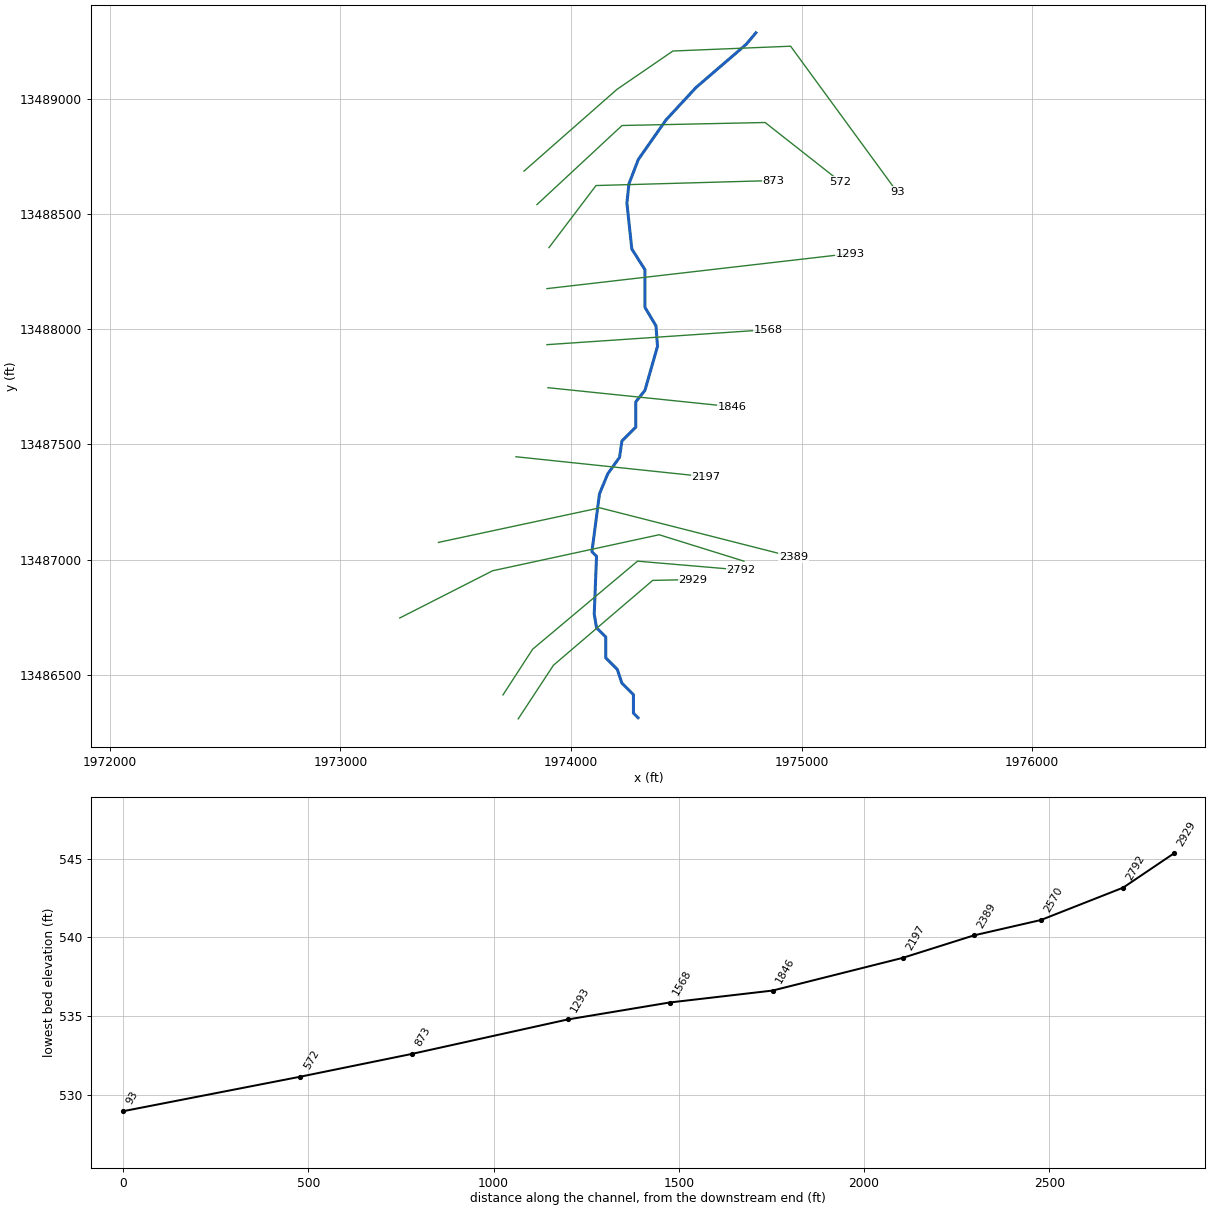
--- UNT 003 in BCW.prj (project) ---

Proj Title=UNT 003 in BCW Base Level Engineering
Current Plan=p01
Default Exp/Contr=0.3,0.1
English Units
Geom File=g01
Flow File=f01
Plan File=p01
BEGIN DESCRIPTION:
UNT 003 in BCW
END DESCRIPTION:

--- UNT 003 in BCW.p01 (plan) ---

Plan Title=Multiple Run
Short Identifier=Multiple
Geom File=g01
Flow File=f01
Subcritical Flow
K Sum by GR= 0
Std Step Tol= 0.01
Critical Tol= 0.01
Num of Std Step Trials= 20
Max Error Tol= 0.3
Flow Tol Ratio= 0.001
Split Flow NTrial= 30
Split Flow Tol= 0.02
Split Flow Ratio= 0.02
Log Output Level= 0
Friction Slope Method= 1
Unsteady Friction Slope Method= 2
Unsteady Bridges Friction Slope Method= 1
Parabolic Critical Depth
Global Vel Dist=  1 , 1 , 1
Global Log Level= 0
CheckData=True
Encroach Param= -1, 0, 0, 0
BEGIN DESCRIPTION:
Multiple Run
END DESCRIPTION:

--- UNT 003 in BCW.f01 (steady flow) ---

Flow Title=Multiple
Number of Profiles=7
Profile Names=10-year,25-year,50-year,1pct_min,100-year,1pct_plu,500-year
River Rch & RM= UNT 003 in BCW,Reach-1,2929
     160     219     267     163     326     651     492
River Rch & RM= UNT 003 in BCW,Reach-1,2389
     252     354     440     273     545    1087     846
Boundary for River Rch & Prof#=UNT 003 in BCW,Reach-1,1
Up Type=0
Dn Type=3
Dn Slope=0.005
Boundary for River Rch & Prof#=UNT 003 in BCW,Reach-1,2
Up Type=0
Dn Type=3
Dn Slope=0.005
Boundary for River Rch & Prof#=UNT 003 in BCW,Reach-1,3
Up Type=0
Dn Type=3
Dn Slope=0.005
Boundary for River Rch & Prof#=UNT 003 in BCW,Reach-1,4
Up Type=0
Dn Type=3
Dn Slope=0.005
Boundary for River Rch & Prof#=UNT 003 in BCW,Reach-1,5
Up Type=0
Dn Type=3
Dn Slope=0.005
Boundary for River Rch & Prof#=UNT 003 in BCW,Reach-1,6
Up Type=0
Dn Type=3
Dn Slope=0.005
Boundary for River Rch & Prof#=UNT 003 in BCW,Reach-1,7
Up Type=0
Dn Type=3
Dn Slope=0.005

--- UNT 003 in BCW.g01 (geometry) ---

Geom Title=Existing Conditions

River Reach=UNT 003 in BCW,Reach-1
Reach XY= 30
      1974290.80     13486314.54      1974270.80     13486334.54
      1974270.80     13486414.54      1974220.80     13486464.54
      1974200.80     13486524.54      1974150.80     13486574.54
      1974150.80     13486664.54      1974110.80     13486704.54
      1974100.80     13486764.54      1974110.80     13487014.54
      1974090.80     13487034.54      1974123.55     13487285.45
      1974159.57     13487372.69      1974210.80     13487444.54
      1974220.80     13487514.54      1974280.80     13487574.54
      1974280.80     13487684.54      1974320.80     13487734.54
      1974375.29     13487925.32      1974368.52     13488014.38
      1974320.80     13488094.54      1974320.80     13488257.61
      1974263.83     13488347.72      1974242.47     13488546.67
      1974251.33     13488630.01      1974291.95     13488735.74
      1974412.27     13488907.61      1974541.95     13489047.72
      1974759.73     13489235.14      1974801.91     13489285.14

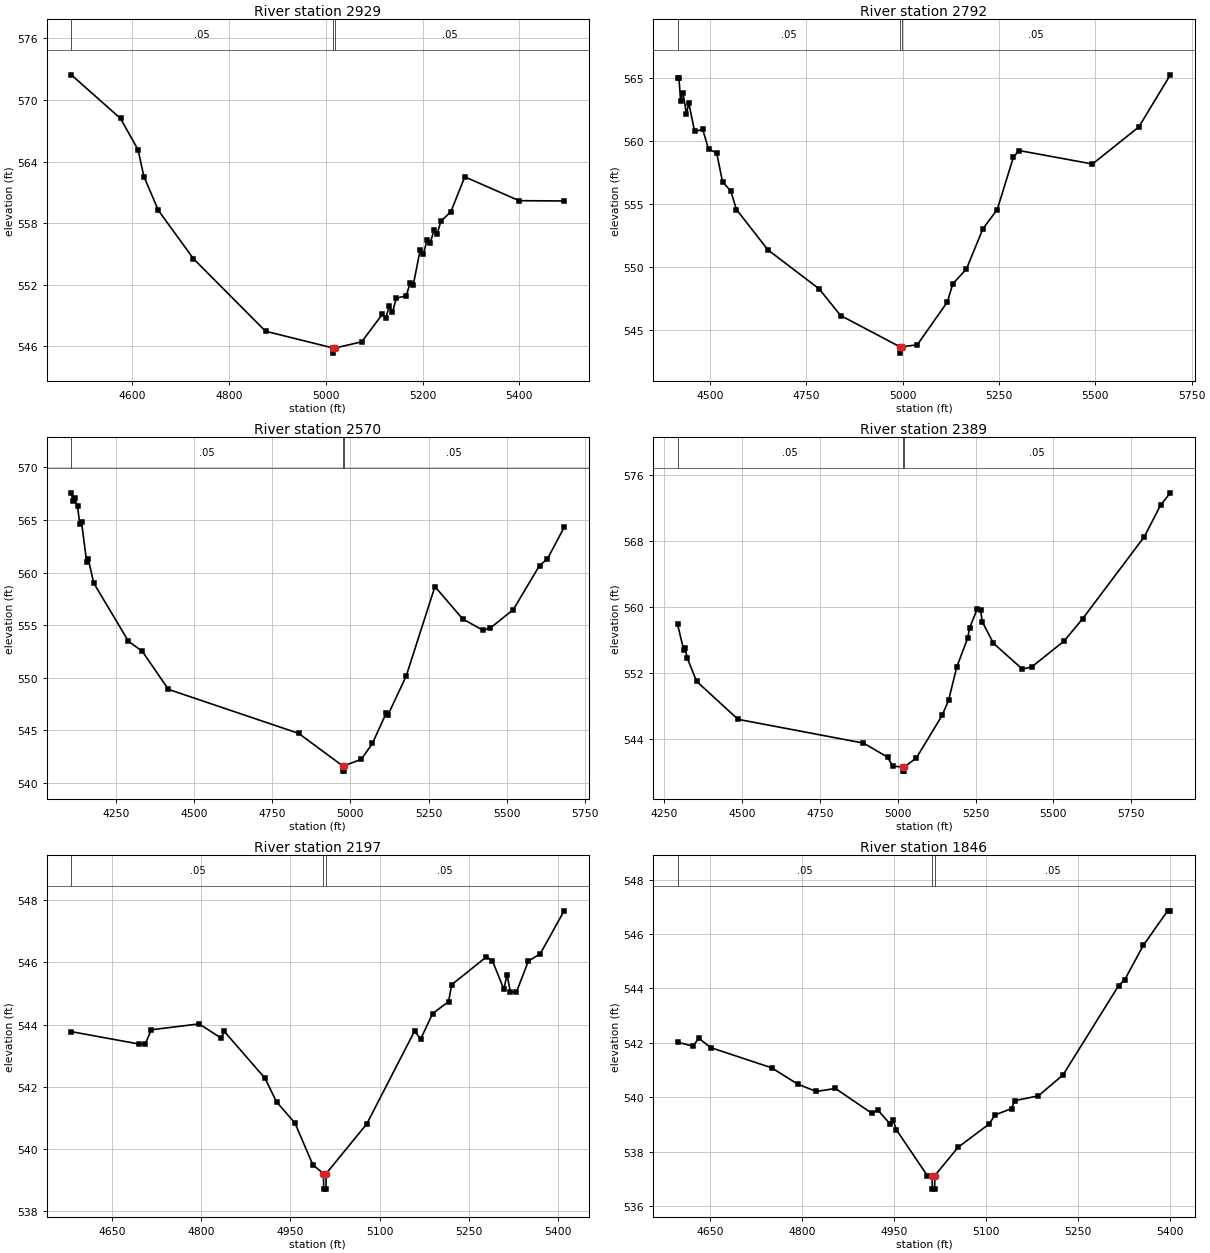
Type RM Length L Ch R = 1,2929,137,137,137
BEGIN DESCRIPTION:
UNT 003 in BCW 2.0
END DESCRIPTION:
XS GIS Cut Line= 4
      1973771.11     13486309.60      1973923.89     13486542.25
      1974354.45     13486910.30      1974528.06     13486913.77
#Sta/Elev= 30
  4474.0  572.44  4575.7  568.19  4611.9  565.15  4624.0  562.54  4654.0  559.24
  4726.4  554.54  4875.4  547.48  5015.0  545.85  5015.2  545.35  5019.0  545.85
  5074.1  546.45  5116.9  549.14  5123.5  548.75  5131.2  549.92  5137.7  549.32
  5145.4  550.69  5166.3  550.94  5174.0  552.18  5180.6  551.97  5194.8  555.36
  5201.4  554.97  5209.1  556.34  5215.7  556.07  5223.4  557.30  5230.0  556.96
  5237.7  558.18  5258.5  559.13  5287.1  562.51  5399.3  560.19  5492.4  560.16
#Mann=3,-1,0
  4474.0    0.05       0  5015.0   0.035       0  5019.0    0.05       0
Bank Sta=5015,5019
Exp/Cntr=0.3,0.1

Type RM Length L Ch R = 1,2792,222,222,222
BEGIN DESCRIPTION:
UNT 003 in BCW 3.0
END DESCRIPTION:
XS GIS Cut Line= 4
      1973705.17     13486413.81      1973833.61     13486611.69
      1974288.47     13486993.64      1974736.38     13486955.44
#Sta/Elev= 30
  4415.2  564.98  4418.9  564.98  4423.3  563.17  4429.3  563.81  4438.5  562.12
  4444.4  563.01  4459.6  560.75  4480.7  560.90  4495.8  559.33  4516.9  559.05
  4532.1  556.74  4553.2  556.04  4568.3  554.55  4650.1  551.35  4782.7  548.27
  4838.7  546.15  4992.8  543.67  4993.0  543.17  4996.8  543.67  5037.7  543.83
  5115.7  547.22  5130.0  548.67  5165.2  549.83  5208.1  553.03  5245.1  554.54
  5287.3  558.71  5301.8  559.23  5492.5  558.16  5612.9  561.10  5694.6  565.23
#Mann=3,-1,0
  4415.2    0.05       0  4992.8   0.035       0  4996.8    0.05       0
Bank Sta=4992.8,4996.8
Exp/Cntr=0.3,0.1

Type RM Length L Ch R = 1,2570,181,181,181
BEGIN DESCRIPTION:
UNT 003 in BCW 4.0
END DESCRIPTION:
XS GIS Cut Line= 4
      1973257.26     13486747.13      1973660.00     13486951.97
      1974382.22     13487108.22      1974750.14     13486993.68
#Sta/Elev= 30
  4107.4  567.59  4112.1  566.84  4117.7  567.14  4127.3  566.31  4134.3  564.64
  4140.0  564.81  4156.6  561.00  4162.2  561.26  4178.8  559.02  4290.1  553.47
  4334.6  552.50  4418.0  548.89  4834.6  544.70  4975.1  541.61  4975.4  541.11
  4978.9  541.11  4979.1  541.61  5035.0  542.24  5070.5  543.75  5114.6  546.65
  5119.7  546.43  5178.2  550.14  5270.3  558.67  5359.1  555.59  5424.1  554.51
  5447.7  554.73  5521.0  556.48  5604.8  560.67  5629.8  561.29  5683.5  564.30
#Mann=3,-1,0
  4107.4    0.05       0  4975.1   0.035       0  4979.1    0.05       0
Bank Sta=4975.1,4979.1
Exp/Cntr=0.3,0.1

Type RM Length L Ch R = 1,2389,192,192,192
BEGIN DESCRIPTION:
UNT 003 in BCW 1.0
END DESCRIPTION:
XS GIS Cut Line= 3
      1973424.97     13487074.99      1974125.00     13487225.00
      1974965.57     13487010.99
#Sta/Elev= 30
  4292.5  557.93  4312.1  554.84  4317.2  555.04  4323.2  553.87  4353.9  551.00
  4486.8  546.40  4890.0  543.52  4967.5  541.82  4983.7  540.74  5016.5  540.63
  5016.8  540.13  5020.6  540.13  5021.0  540.63  5060.0  541.73  5142.6  546.87
  5163.2  548.68  5189.9  552.76  5225.1  556.25  5230.8  557.47  5256.1  559.80
  5266.4  559.57  5271.7  558.20  5307.5  555.60  5400.5  552.48  5430.2  552.73
  5534.7  555.88  5593.8  558.56  5792.7  568.52  5844.4  572.32  5875.8  573.81
#Mann=3,-1,0
  4292.5    0.05       0  5016.5   0.035       0  5021.0    0.05       0
Bank Sta=5016.5,5021
Exp/Cntr=0.3,0.1

Type RM Length L Ch R = 1,2197,351,351,351
BEGIN DESCRIPTION:
Mapping XS f2976a67
END DESCRIPTION:
XS GIS Cut Line= 2
      1973761.35     13487446.55      1974584.80     13487359.87
#Sta/Elev= 30
  4581.8  543.77  4696.1  543.37  4706.1  543.38  4716.2  543.83  4796.6  544.02
  4833.6  543.56  4838.7  543.78  4907.2  542.27  4926.6  541.51  4957.5  540.83
  4987.7  539.48  5005.5  539.20  5005.8  538.70  5009.7  538.70  5010.0  539.20
  5078.2  540.80  5158.6  543.79  5168.7  543.53  5188.8  544.35  5215.7  544.74
  5220.8  545.28  5279.3  546.18  5289.3  546.05  5308.7  545.13  5313.8  545.61
  5319.5  545.05  5329.6  545.04  5349.7  546.04  5369.8  546.28  5409.8  547.66
#Mann=3,-1,0
  4581.8    0.05       0  5005.5   0.035       0  5010.0    0.05       0
Bank Sta=5005.5,5010
Exp/Cntr=0.3,0.1

Type RM Length L Ch R = 1,1846,278,278,278
BEGIN DESCRIPTION:
Mapping XS 391db6f5
END DESCRIPTION:
XS GIS Cut Line= 2
      1973900.25     13487746.03      1974698.80     13487663.57
#Sta/Elev= 30
  4597.2  542.02  4622.1  541.88  4632.1  542.16  4651.6  541.82  4750.5  541.08
  4793.0  540.48  4823.1  540.21  4854.5  540.32  4913.6  539.41  4923.7  539.52
  4943.4  539.02  4948.4  539.15  4953.8  538.80  5004.1  537.12  5011.9  537.12
  5012.2  536.62  5016.1  536.62  5016.4  537.12  5054.4  538.16  5104.6  539.01
  5114.7  539.35  5141.3  539.58  5146.3  539.87  5185.1  540.05  5225.3  540.82
  5315.8  544.10  5325.8  544.32  5356.0  545.58  5395.6  546.85  5400.0  546.85
#Mann=3,-1,0
  4597.2    0.05       0  5011.9   0.035       0  5016.4    0.05       0
Bank Sta=5011.9,5016.4
Exp/Cntr=0.3,0.1

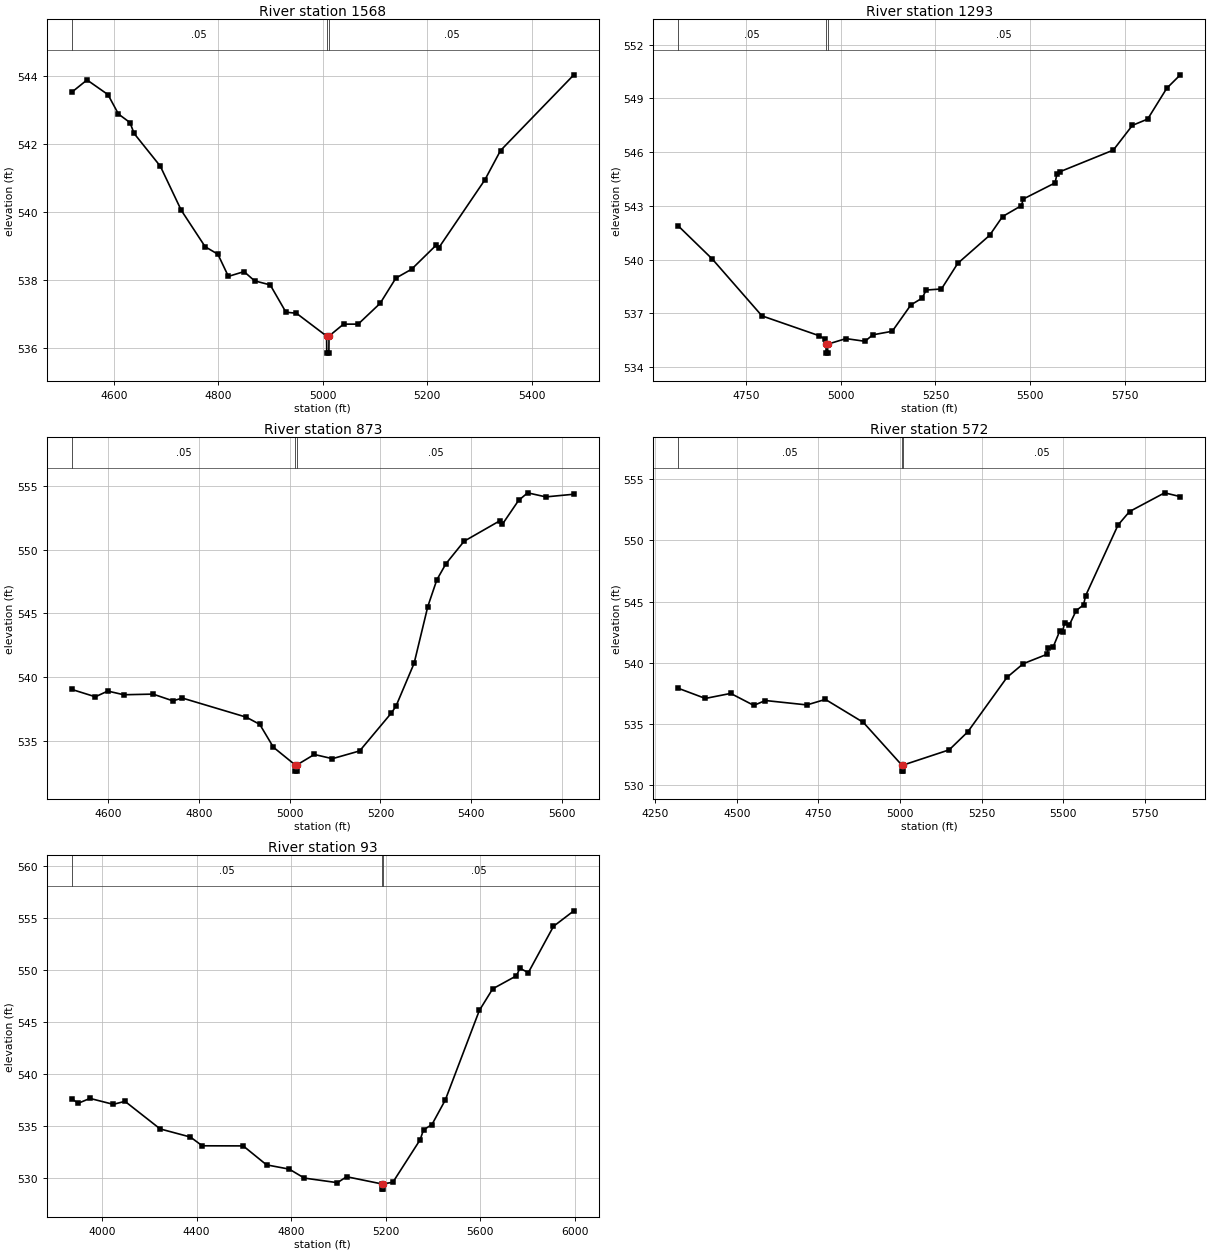
Type RM Length L Ch R = 1,1568,275,275,275
BEGIN DESCRIPTION:
Mapping XS 6009bb00
END DESCRIPTION:
XS GIS Cut Line= 2
      1973895.84     13487932.67      1974855.03     13487997.77
#Sta/Elev= 30
  4519.2  543.51  4548.4  543.87  4588.5  543.44  4608.6  542.87  4630.6  542.62
  4638.6  542.30  4688.8  541.34  4728.8  540.05  4774.6  538.98  4799.0  538.76
  4819.1  538.11  4849.1  538.25  4869.2  537.98  4899.2  537.86  4929.3  537.06
  4949.3  537.03  5007.1  536.36  5007.5  535.86  5011.5  535.86  5011.8  536.36
  5039.6  536.71  5067.6  536.71  5109.7  537.32  5139.8  538.06  5169.9  538.32
  5216.6  539.02  5221.6  538.94  5310.2  540.94  5340.2  541.80  5480.6  544.02
#Mann=3,-1,0
  4519.2    0.05       0  5007.1    0.03       0  5011.8    0.05       0
Bank Sta=5007.1,5011.8
Exp/Cntr=0.3,0.1

Type RM Length L Ch R = 1,1293,420,420,420
BEGIN DESCRIPTION:
Mapping XS c32479da
END DESCRIPTION:
XS GIS Cut Line= 2
      1973895.82     13488175.72      1975210.48     13488327.58
#Sta/Elev= 30
  4572.2  541.88  4662.0  540.03  4792.8  536.86  4943.8  535.75  4958.5  535.56
  4961.6  535.28  4962.0  534.78  4966.0  534.78  4966.3  535.28  5014.3  535.59
  5064.6  535.44  5084.8  535.80  5136.3  536.00  5185.4  537.47  5215.1  537.85
  5225.7  538.30  5266.0  538.36  5309.0  539.79  5392.8  541.35  5427.0  542.40
  5476.7  543.01  5481.7  543.38  5565.5  544.28  5570.6  544.79  5578.0  544.90
  5719.0  546.11  5769.3  547.49  5809.5  547.84  5859.9  549.56  5895.6  550.31
#Mann=3,-1,0
  4572.2    0.05       0  4961.6    0.03       0  4966.3    0.05       0
Bank Sta=4961.6,4966.3
Exp/Cntr=0.3,0.1

Type RM Length L Ch R = 1,873,301,301,301
BEGIN DESCRIPTION:
Mapping XS 0f85f3c8
END DESCRIPTION:
XS GIS Cut Line= 3
      1973904.53     13488353.65      1974108.54     13488622.77
      1974876.72     13488644.47
#Sta/Elev= 30
  4519.8  539.02  4571.7  538.44  4599.1  538.89  4634.4  538.60  4698.9  538.65
  4742.6  538.12  4763.4  538.34  4904.0  536.84  4934.0  536.27  4964.0  534.47
  5011.6  533.09  5012.0  532.59  5016.1  532.59  5016.4  533.09  5054.1  533.90
  5094.1  533.57  5154.1  534.18  5224.1  537.17  5234.1  537.70  5274.1  541.08
  5304.2  545.54  5324.2  547.65  5344.2  548.91  5384.2  550.68  5463.4  552.30
  5468.4  552.01  5504.2  553.89  5524.2  554.49  5564.3  554.17  5626.0  554.38
#Mann=3,-1,0
  4519.8    0.05       0  5011.6    0.03       0  5016.4    0.05       0
Bank Sta=5011.6,5016.4
Exp/Cntr=0.3,0.1

Type RM Length L Ch R = 1,572,479,479,479
BEGIN DESCRIPTION:
Mapping XS 58dd52e1
END DESCRIPTION:
XS GIS Cut Line= 4
      1973852.48     13488540.33      1974221.39     13488883.19
      1974842.05     13488896.21      1975167.57     13488640.13
#Sta/Elev= 30
  4320.6  537.91  4403.7  537.08  4481.4  537.49  4552.2  536.51  4587.4  536.91
  4714.9  536.55  4771.6  537.00  4887.9  535.12  5005.5  531.64  5005.8  531.14
  5009.9  531.14  5010.3  531.64  5151.0  532.88  5207.9  534.35  5328.0  538.80
  5378.0  539.92  5450.0  540.68  5455.1  541.20  5469.6  541.29  5490.4  542.63
  5498.5  542.54  5504.8  543.28  5519.3  543.09  5540.1  544.26  5562.6  544.72
  5569.0  545.47  5668.4  551.25  5703.6  552.35  5811.1  553.88  5859.2  553.57
#Mann=3,-1,0
  4320.6    0.05       0  5005.5    0.03       0  5010.3    0.05       0
Bank Sta=5005.5,5010.3
Exp/Cntr=0.3,0.1

Type RM Length L Ch R = 1,93,0,0,0
BEGIN DESCRIPTION:
UNT 003 in BCW 5.0
END DESCRIPTION:
XS GIS Cut Line= 5
      1973796.30     13488685.49      1974199.06     13489039.64
      1974442.12     13489206.31      1974952.54     13489227.14
      1975414.36     13488595.18
#Sta/Elev= 30
  3872.1  537.62  3898.9  537.18  3949.1  537.65  4047.8  537.08  4097.2  537.37
  4246.1  534.72  4374.2  533.94  4424.2  533.10  4597.5  533.09  4696.3  531.27
  4792.4  530.86  4856.1  530.00  4996.3  529.56  5035.1  530.13  5184.0  529.44
  5184.4  528.94  5188.5  528.94  5188.8  529.44  5230.9  529.60  5346.0  533.67
  5360.6  534.63  5396.2  535.14  5452.6  537.49  5596.9  546.10  5653.3  548.17
  5753.7  549.42  5768.4  550.15  5803.9  549.72  5910.5  554.17  5996.7  555.66
#Mann=3,-1,0
  3872.1    0.05       0  5184.0    0.03       0  5188.8    0.05       0
Bank Sta=5184,5188.8
Exp/Cntr=0.3,0.1

Chan Stop Cuts=-1