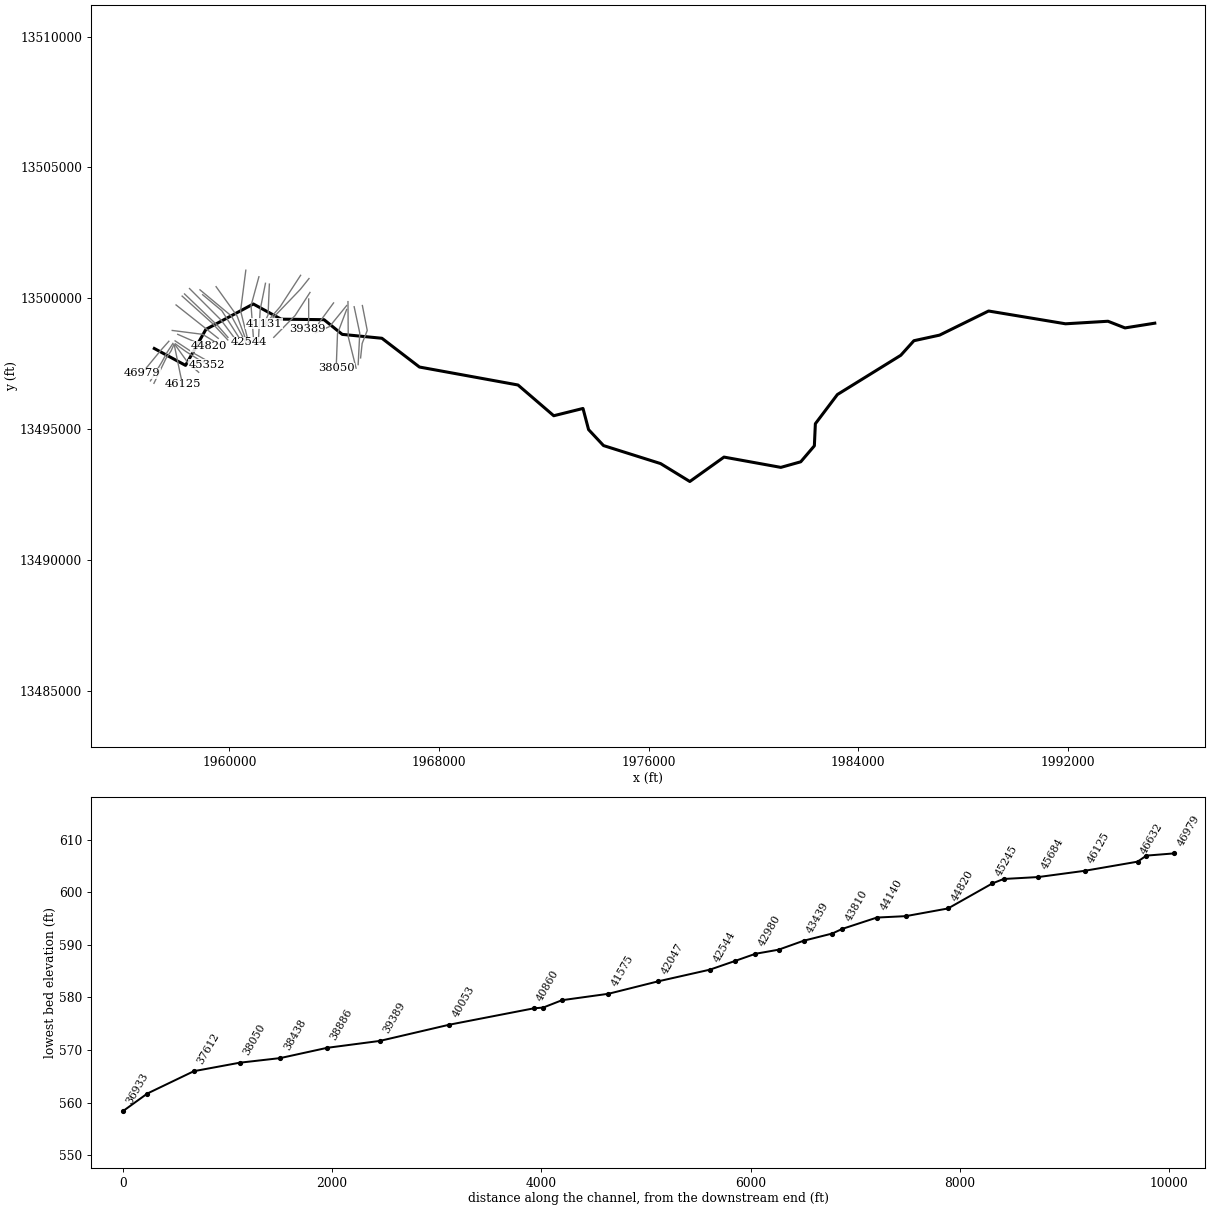
--- UNT 004 in BCW.prj (project) ---

Proj Title=UNT 004 in BCW Base Level Engineering
Current Plan=p01
Default Exp/Contr=0.3,0.1
English Units
Geom File=g01
Flow File=f01
Plan File=p01
Y Axis Title=Elevation
X Axis Title(PF)=Main Channel Distance
X Axis Title(XS)=Station
BEGIN DESCRIPTION:
UNT 004 in BCW
END DESCRIPTION:
DSS Export Rating Curves= 0
DSS Export Rating Curve Sorted= 0
DSS Export Volume Flow Curves= 0
DXF OffsetX= 0
DXF OffsetY= 0
DXF ScaleX= 1
DXF ScaleY= 10

--- UNT 004 in BCW.p01 (plan) ---

Plan Title=Multiple Run
Short Identifier=Multiple
Geom File=g01
Flow File=f01
Subcritical Flow
K Sum by GR= 0
Std Step Tol= 0.01
Critical Tol= 0.01
Num of Std Step Trials= 20
Max Error Tol= 0.3
Flow Tol Ratio= 0.001
Split Flow NTrial= 30
Split Flow Tol= 0.02
Split Flow Ratio= 0.02
Log Output Level= 0
Friction Slope Method= 1
Unsteady Friction Slope Method= 2
Unsteady Bridges Friction Slope Method= 1
Parabolic Critical Depth
Global Vel Dist=  1 , 1 , 1
Global Log Level= 0
CheckData=True
Encroach Param= -1, 0, 0, 0
BEGIN DESCRIPTION:
Multiple Run
END DESCRIPTION:

--- UNT 004 in BCW.f01 (steady flow) ---

Flow Title=Multiple
Program Version=5.05
Number of Profiles= 7
Profile Names=10-year,25-year,50-year,1pct_min,100-year,1pct_plu,500-year
River Rch & RM=UNT 004 in BCW,Reach-1         ,46979
     155     214     262     161     322     642     494
River Rch & RM=UNT 004 in BCW,Reach-1         ,46716
     167     231     283     174     346     691     529
River Rch & RM=UNT 004 in BCW,Reach-1         ,41575
     261     368     459     286     571    1139     898
River Rch & RM=UNT 004 in BCW,Reach-1         ,40053
     261     368     459     286     571    1139     898
River Rch & RM=UNT 004 in BCW,Reach-1         ,38886
     302     429     538     337     671    1340    1067
River Rch & RM=UNT 004 in BCW,Reach-1         ,38050
     475     688     873     552    1102    2198    1788
River Rch & RM=UNT 004 in BCW,Reach-1         ,36933
     475     688     873     552    1102    2198    1788
River Rch & RM=UNT 004 in BCW,Reach-1         ,32255
     526     763     970     614    1224    2443    1990
River Rch & RM=UNT 004 in BCW,Reach-1         ,27035
     561     817    1038     658    1312    2618    2135
River Rch & RM=UNT 004 in BCW,Reach-1         ,26083
     681     997    1273     809    1613    3219    2641
River Rch & RM=UNT 004 in BCW,Reach-1         ,21406
    1168    1740    2249    1444    2882    5750    4818
River Rch & RM=UNT 004 in BCW,Reach-1         ,16836
    1201    1787    2308    1481    2956    5897    4933
River Rch & RM=UNT 004 in BCW,Reach-1         ,12766
    1285    1914    2474    1588    3169    6322    5290
River Rch & RM=UNT 004 in BCW,Reach-1         ,11673
    1285    1914    2474    1588    3169    6322    5290
River Rch & RM=UNT 004 in BCW,Reach-1         ,7369
    1313    1955    2526    1620    3233    6450    5389
River Rch & RM=UNT 004 in BCW,Reach-1         ,4283
    1328    1975    2550    1635    3262    6509    5431
Boundary for River Rch & Prof#=UNT 004 in BCW,Reach-1         , 1
Up Type= 0
Dn Type= 3
Dn Slope=0.00101
Boundary for River Rch & Prof#=UNT 004 in BCW,Reach-1         , 2
Up Type= 0
Dn Type= 3
Dn Slope=0.00101
Boundary for River Rch & Prof#=UNT 004 in BCW,Reach-1         , 3
Up Type= 0
Dn Type= 3
Dn Slope=0.00101
Boundary for River Rch & Prof#=UNT 004 in BCW,Reach-1         , 4
Up Type= 0
Dn Type= 3
Dn Slope=0.00101
Boundary for River Rch & Prof#=UNT 004 in BCW,Reach-1         , 5
Up Type= 0
Dn Type= 3
Dn Slope=0.00101
Boundary for River Rch & Prof#=UNT 004 in BCW,Reach-1         , 6
Up Type= 0
Dn Type= 3
Dn Slope=0.00101
Boundary for River Rch & Prof#=UNT 004 in BCW,Reach-1         , 7
Up Type= 0
Dn Type= 3
Dn Slope=0.00101
DSS Import GetInterval= 0
DSS Import GetPeak= 0
DSS Import FillOption= 0

--- UNT 004 in BCW.g01 (geometry) ---

Geom Title=Existing Conditions

River Reach=UNT 004 in BCW,Reach-1
Reach XY= 30
      1957131.30     13498084.04      1958324.67     13497438.10
      1959100.80     13498814.54      1960910.80     13499784.54
      1961970.80     13499204.54      1963610.80     13499184.54
      1964305.21     13498623.40      1965820.80     13498474.54
      1967253.41     13497375.50      1971016.12     13496689.22
      1972380.80     13495514.54      1973497.55     13495792.62
      1973710.80     13494984.54      1974280.80     13494374.54
      1976459.57     13493686.65      1977575.89     13493001.76
      1978880.80     13493934.54      1981050.87     13493541.29
      1981811.19     13493754.93      1982330.80     13494364.54
      1982369.11     13495209.61      1983210.04     13496324.54
      1985630.76     13497824.50      1986131.47     13498381.07
      1987110.80     13498594.54      1988982.68     13499515.97
      1991919.50     13499027.51      1993540.80     13499124.54
      1994189.98     13498870.04      1995327.00     13499050.90

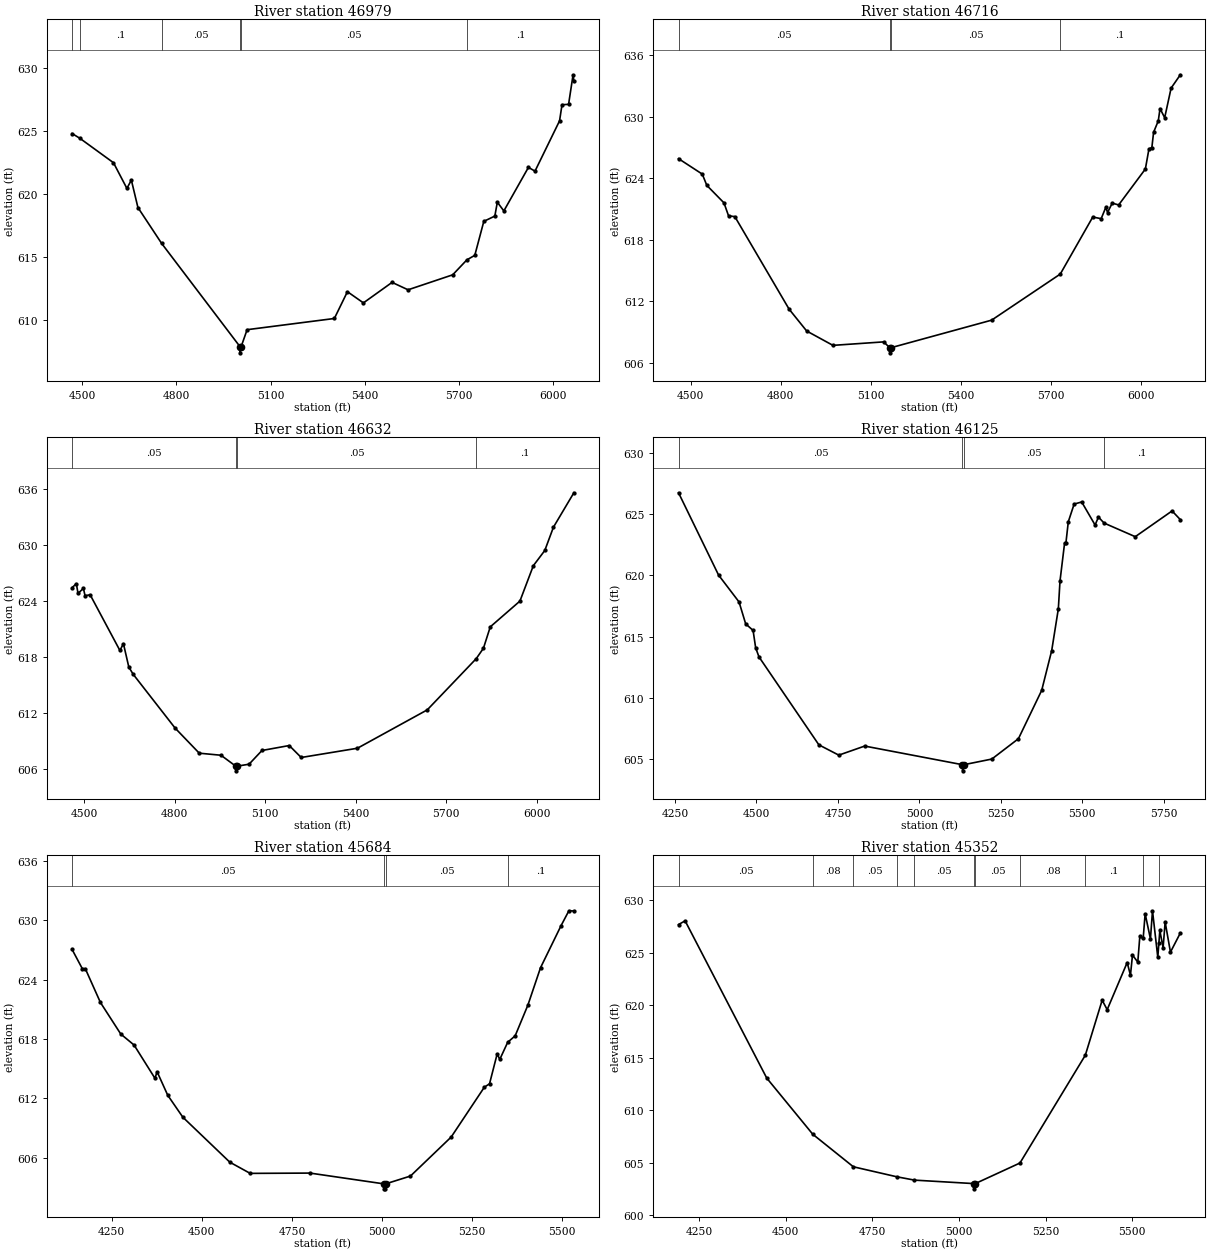
Type RM Length L Ch R = 1,46979,263,263,263
BEGIN DESCRIPTION:
UNT 004 in BCW 80.0
END DESCRIPTION:
XS GIS Cut Line= 3
      1957686.22     13498360.05      1957378.07     13498012.84
      1956658.81     13497137.59
#Sta/Elev= 30
  4467.8  624.80  4492.7  624.42  4599.6  622.48  4642.3  620.44  4656.5  621.10
  4677.4  618.92  4752.5  616.08  5002.0  607.87  5002.3  607.37  5006.1  607.87
  5024.9  609.21  5302.6  610.10  5344.2  612.23  5395.1  611.34  5486.3  612.97
  5537.2  612.38  5679.2  613.57  5724.4  614.76  5749.6  615.12  5778.3  617.82
  5813.4  618.24  5821.3  619.34  5842.1  618.65  5920.3  622.11  5941.2  621.81
  6019.4  625.81  6027.2  627.09  6048.1  627.12  6062.4  629.47  6064.9  628.98
#Mann=6,-1,0
  4467.8    0.05       0  4492.7     0.1       0  4752.5    0.05       0
  5002.0   0.035       0  5006.1    0.05       0  5724.4     0.1       0
Bank Sta=5002,5006.1
Exp/Cntr=0.3,0.1

Type RM Length L Ch R = 1,46716,84,84,84
BEGIN DESCRIPTION:
Mapping XS 8e66b1ad
END DESCRIPTION:
XS GIS Cut Line= 4
      1957842.47     13498277.58      1957625.47     13497947.74
      1957412.79     13497557.11      1956983.12     13496845.34
#Sta/Elev= 30
  4459.3  625.91  4538.4  624.40  4553.5  623.30  4610.7  621.59  4625.8  620.33
  4646.8  620.25  4827.6  611.21  4886.1  609.08  4973.5  607.68  5142.5  608.02
  5162.6  607.45  5162.9  606.95  5166.7  607.45  5501.8  610.14  5730.5  614.64
  5838.7  620.21  5866.7  620.05  5882.2  621.16  5888.0  620.65  5903.5  621.57
  5924.9  621.39  6013.9  624.90  6025.8  626.86  6035.5  626.99  6041.3  628.49
  6056.9  629.60  6062.7  630.80  6078.2  629.91  6099.6  632.80  6130.3  634.10
#Mann=4,-1,0
  4459.3    0.05       0  5162.6   0.035       0  5166.7    0.05       0
  5730.5     0.1       0
Bank Sta=5162.6,5166.7
Exp/Cntr=0.3,0.1

Type RM Length L Ch R = 1,46632,507,507,507
BEGIN DESCRIPTION:
Mapping XS df563784
END DESCRIPTION:
XS GIS Cut Line= 4
      1957877.20     13498229.84      1957773.04     13497995.48
      1957577.72     13497704.68      1957117.64     13496754.14
#Sta/Elev= 30
  4460.2  625.42  4474.4  625.84  4479.9  624.80  4497.7  625.34  4503.2  624.57
  4520.2  624.65  4618.7  618.69  4630.4  619.42  4648.2  616.92  4662.5  616.15
  4801.6  610.38  4881.7  607.69  4953.7  607.47  5002.7  606.30  5002.9  605.80
  5006.8  606.30  5046.7  606.51  5089.5  607.98  5179.9  608.51  5219.5  607.23
  5405.8  608.22  5637.2  612.33  5799.6  617.82  5823.4  618.93  5846.0  621.22
  5944.3  623.98  5988.7  627.77  6026.7  629.40  6055.4  631.90  6123.0  635.58
#Mann=4,-1,0
  4460.2    0.05       0  5002.7   0.035       0  5006.8    0.05       0
  5799.6     0.1       0
Bank Sta=5002.7,5006.8
Exp/Cntr=0.3,0.1

Type RM Length L Ch R = 1,46125,441,441,441
BEGIN DESCRIPTION:
UNT 004 in BCW 79.0
END DESCRIPTION:
XS GIS Cut Line= 3
      1957894.56     13498216.86      1958133.63     13497052.25
      1958214.07     13496710.39
#Sta/Elev= 30
  4260.8  626.73  4383.7  620.02  4446.5  617.83  4466.9  616.04  4489.6  615.51
  4497.5  614.09  4507.7  613.35  4691.5  606.18  4752.7  605.34  4832.1  606.08
  5132.3  604.56  5132.6  604.06  5136.5  604.56  5222.3  605.02  5304.0  606.68
  5375.4  610.62  5406.1  613.86  5426.5  617.27  5431.6  619.54  5445.7  622.63
  5449.7  622.63  5457.1  624.37  5475.0  625.81  5498.2  625.98  5539.3  624.10
  5549.6  624.75  5566.9  624.26  5662.6  623.15  5775.6  625.25  5800.9  624.54
#Mann=4,-1,0
  4260.8    0.05       0  5132.3   0.035       0  5136.5    0.05       0
  5566.9     0.1       0
Bank Sta=5132.3,5136.5
Exp/Cntr=0.3,0.1

Type RM Length L Ch R = 1,45684,332,332,332
BEGIN DESCRIPTION:
UNT 004 in BCW 78.0
END DESCRIPTION:
XS GIS Cut Line= 3
      1957925.02     13498224.98      1958425.00     13497525.00
      1958824.99     13497175.01
#Sta/Elev= 30
  4140.3  627.04  4168.5  625.11  4177.1  625.09  4218.9  621.69  4275.4  618.50
  4312.3  617.39  4370.1  614.04  4376.2  614.69  4405.7  612.32  4447.5  610.11
  4577.8  605.57  4634.3  604.44  4800.2  604.47  5005.5  603.38  5005.8  602.88
  5009.5  602.88  5009.8  603.38  5078.8  604.17  5191.8  608.11  5283.8  613.14
  5298.1  613.48  5319.4  616.51  5326.5  615.94  5348.5  617.67  5369.2  618.32
  5404.4  621.41  5439.5  625.19  5496.4  629.43  5518.2  630.94  5532.0  630.92
#Mann=4,-1,0
  4140.3    0.05       0  5005.5   0.035       0  5009.8    0.05       0
  5348.5     0.1       0
Bank Sta=5005.5,5009.8
Exp/Cntr=0.3,0.1

Type RM Length L Ch R = 1,45352,107,107,107
BEGIN DESCRIPTION:
Mapping XS ce040553
END DESCRIPTION:
XS GIS Cut Line= 3
      1957929.31     13498264.56      1958328.59     13497973.78
      1959135.91     13497465.95
#Sta/Elev= 30
  4191.0  627.69  4210.0  628.04  4445.5  613.06  4578.3  607.71  4695.4  604.61
  4820.5  603.66  4871.7  603.34  5042.8  603.01  5043.1  602.51  5047.1  603.01
  5176.0  604.97  5364.6  615.24  5413.2  620.48  5427.7  619.58  5485.4  624.07
  5494.8  622.86  5500.7  624.78  5516.0  624.11  5521.9  626.59  5531.5  626.36
  5537.2  628.72  5552.5  626.32  5558.4  629.00  5573.7  624.57  5576.9  625.96
  5579.6  627.13  5589.0  625.47  5594.9  627.93  5610.2  625.06  5638.7  626.88
#Mann=11,-1,0
  4191.0    0.05       0  4578.3    0.08       0  4695.4    0.05       0
  4820.5    0.08       0  4871.7    0.05       0  5042.8    0.04       0
  5047.1    0.05       0  5176.0    0.08       0  5364.6     0.1       0
  5531.5    0.08       0  5576.9     0.1       0
Bank Sta=5042.8,5047.1
Exp/Cntr=0.3,0.1

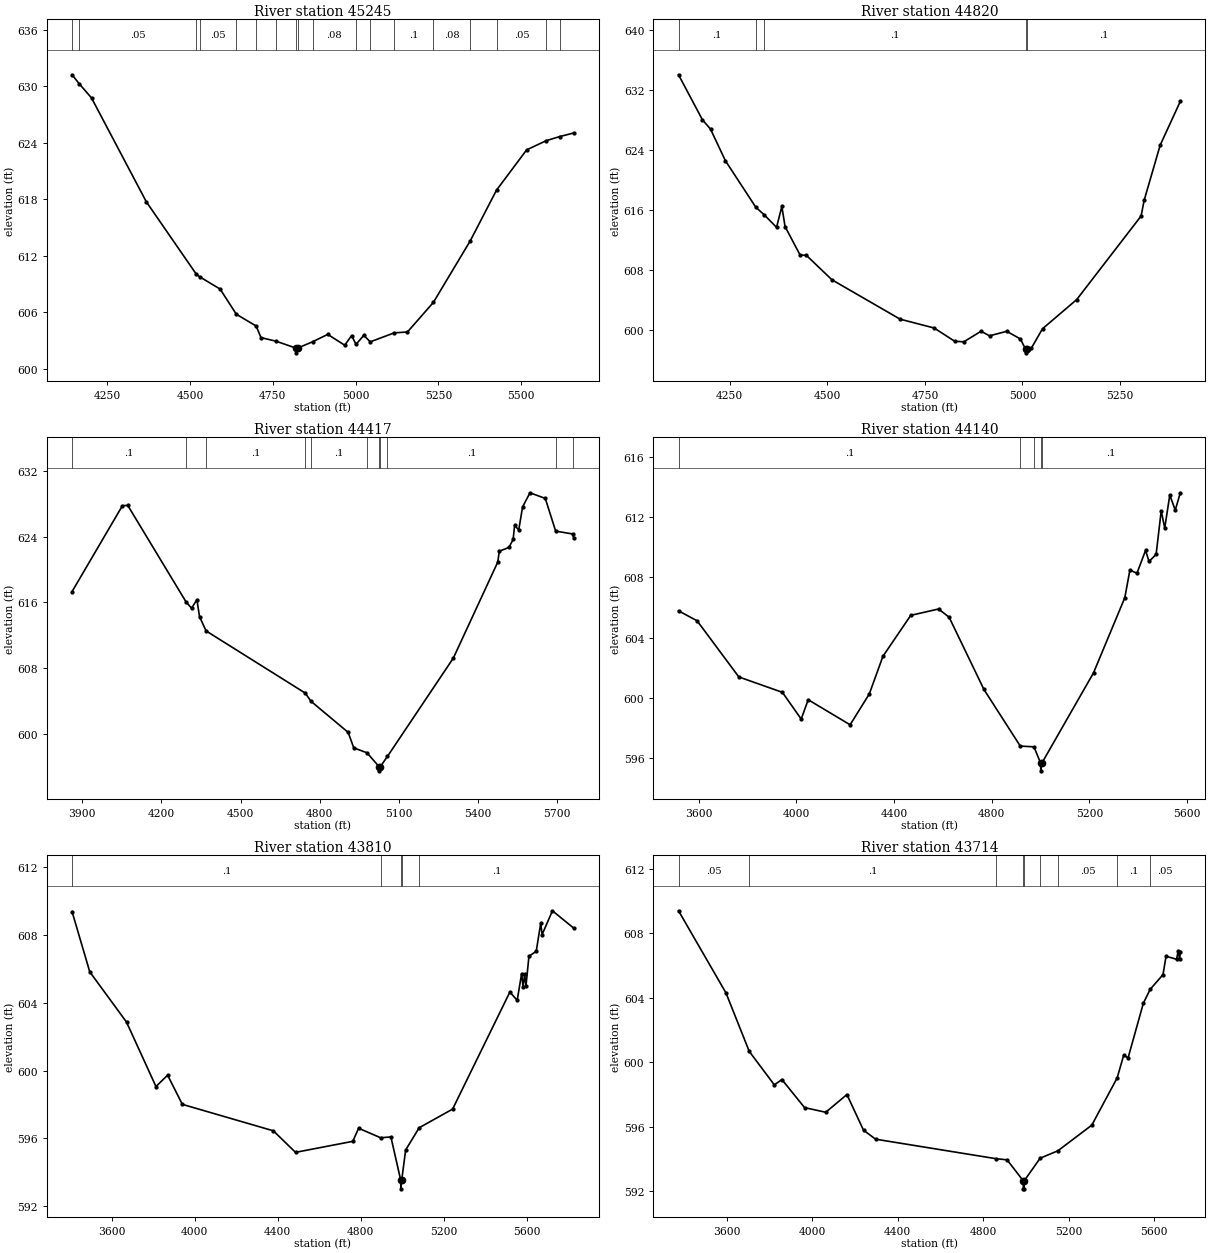
Type RM Length L Ch R = 1,45245,425,425,425
BEGIN DESCRIPTION:
UNT 004 in BCW 77.0
END DESCRIPTION:
XS GIS Cut Line= 3
      1957924.98     13498375.01      1958649.77     13497895.66
      1959212.98     13497579.39
#Sta/Elev= 30
  4144.2  631.23  4166.4  630.25  4202.9  628.77  4368.4  617.73  4519.8  610.01
  4529.4  609.76  4591.1  608.46  4640.2  605.78  4700.0  604.53  4714.5  603.30
  4760.6  602.91  4820.6  602.18  4820.9  601.68  4825.0  602.18  4870.5  602.86
  4916.1  603.64  4967.3  602.49  4988.3  603.52  5001.4  602.57  5024.8  603.54
  5044.4  602.85  5116.7  603.80  5156.8  603.90  5235.0  607.04  5346.3  613.58
  5425.6  618.97  5516.5  623.25  5575.9  624.23  5616.2  624.66  5659.1  625.05
#Mann=18,-1,0
  4144.2     0.1       0  4166.4    0.05       0  4519.8     0.1       0
  4529.4    0.05       0  4640.2     0.1       0  4700.0    0.08       0
  4760.6     0.1       0  4820.6    0.07       0  4825.0     0.1       0
  4870.5    0.08       0  5001.4     0.1       0  5044.4    0.08       0
  5116.7     0.1       0  5235.0    0.08       0  5346.3     0.1       0
  5425.6    0.05       0  5575.9     0.1       0  5616.2    0.05       0
Bank Sta=4820.6,4825
Exp/Cntr=0.3,0.1

Type RM Length L Ch R = 1,44820,403,403,403
BEGIN DESCRIPTION:
UNT 004 in BCW 76.0
END DESCRIPTION:
XS GIS Cut Line= 3
      1958024.97     13498625.01      1958825.00     13498275.00
      1959225.05     13498174.99
#Sta/Elev= 30
  4118.8  633.98  4180.0  627.98  4200.7  626.74  4238.9  622.52  4316.8  616.32
  4338.9  615.28  4369.9  613.64  4383.5  616.42  4391.7  613.75  4430.3  609.94
  4446.3  609.91  4511.8  606.65  4686.4  601.40  4773.7  600.22  4826.4  598.45
  4849.8  598.38  4893.8  599.79  4915.6  599.18  4959.7  599.78  4994.6  598.76
  5007.9  597.41  5008.2  596.91  5012.3  597.41  5023.0  597.56  5051.3  600.12
  5138.9  604.01  5303.9  615.15  5311.6  617.22  5352.8  624.60  5404.4  630.44
#Mann=5,-1,0
  4118.8     0.1       0  4316.8    0.05       0  4338.9     0.1       0
  5007.9    0.07       0  5012.3     0.1       0
Bank Sta=5007.9,5012.3
Exp/Cntr=0.3,0.1

Type RM Length L Ch R = 1,44417,277,277,277
BEGIN DESCRIPTION:
UNT 004 in BCW 75.0
END DESCRIPTION:
XS GIS Cut Line= 3
      1957815.58     13498773.26      1958975.00     13498625.00
      1959601.00     13498242.64
#Sta/Elev= 30
  3861.3  617.30  4052.3  627.77  4072.4  627.80  4293.6  616.03  4314.4  615.27
  4334.5  616.31  4344.6  614.23  4369.5  612.50  4745.2  604.93  4767.4  603.92
  4908.0  600.14  4929.3  598.25  4979.4  597.65  5025.4  595.95  5025.7  595.45
  5029.8  595.95  5057.0  597.21  5306.9  609.20  5475.3  620.90  5481.1  622.22
  5517.9  622.68  5533.4  623.66  5539.2  625.37  5554.7  624.80  5569.2  627.60
  5597.3  629.34  5655.4  628.65  5694.7  624.67  5758.8  624.32  5763.7  623.78
#Mann=11,-1,0
  3861.3     0.1       0  4293.6    0.05       0  4369.5     0.1       0
  4745.2    0.05       0  4767.4     0.1       0  4979.4    0.05       0
  5025.4   0.035       0  5029.8    0.05       0  5057.0     0.1       0
  5694.7    0.05       0  5758.8     0.1       0
Bank Sta=5025.4,5029.8
Exp/Cntr=0.3,0.1

Type RM Length L Ch R = 1,44140,330,330,330
BEGIN DESCRIPTION:
Mapping XS be0fbef4
END DESCRIPTION:
XS GIS Cut Line= 2
      1957961.54     13499748.04      1959571.32     13498471.32
#Sta/Elev= 30
  3517.5  605.78  3593.5  605.12  3764.4  601.40  3942.8  600.38  4019.7  598.61
  4048.5  599.89  4220.0  598.23  4298.5  600.27  4354.5  602.77  4468.3  605.48
  4582.1  605.90  4625.3  605.36  4768.0  600.57  4916.8  596.82  4972.9  596.77
  5000.3  595.68  5000.6  595.18  5004.7  595.68  5216.6  601.67  5344.8  606.65
  5365.6  608.48  5394.5  608.27  5429.7  609.78  5444.1  609.05  5473.0  609.52
  5493.8  612.40  5508.2  611.26  5529.0  613.45  5551.3  612.45  5572.1  613.60
#Mann=5,-1,0
  3517.5     0.1       0  4916.8    0.05       0  4972.9     0.1       0
  5000.3    0.07       0  5004.7     0.1       0
Bank Sta=5000.3,5004.7
Exp/Cntr=0.3,0.1

Type RM Length L Ch R = 1,43810,96,96,96
BEGIN DESCRIPTION:
UNT 004 in BCW 74.0
END DESCRIPTION:
XS GIS Cut Line= 3
      1958194.16     13500084.86      1959340.00     13499053.60
      1959937.25     13498411.22
#Sta/Elev= 30
  3409.0  609.37  3494.3  605.82  3671.4  602.86  3813.4  599.06  3869.5  599.73
  3940.5  598.01  4379.2  596.45  4486.1  595.18  4761.9  595.83  4790.3  596.60
  4896.6  596.04  4945.8  596.09  4993.3  593.53  4993.6  593.03  4997.8  593.53
  5016.9  595.32  5082.0  596.63  5243.3  597.73  5519.3  604.63  5554.5  604.14
  5576.0  605.72  5582.8  604.90  5590.2  605.68  5597.0  605.01  5611.2  606.74
  5646.3  607.03  5667.9  608.68  5674.7  608.02  5724.5  609.42  5827.7  608.39
#Mann=5,-1,0
  3409.0     0.1       0  4896.6    0.05       0  4993.3   0.035       0
  4997.8    0.05       0  5082.0     0.1       0
Bank Sta=4993.3,4997.8
Exp/Cntr=0.3,0.1

Type RM Length L Ch R = 1,43714,275,275,275
BEGIN DESCRIPTION:
Mapping XS 060063e2
END DESCRIPTION:
XS GIS Cut Line= 3
      1958284.44     13500168.19      1959569.17     13498939.02
      1959943.51     13498509.22
#Sta/Elev= 30
  3374.6  609.40  3596.7  604.30  3705.4  600.68  3822.8  598.60  3858.3  598.93
  3964.3  597.19  4063.4  596.90  4162.5  598.00  4240.1  595.79  4296.7  595.23
  4860.3  594.02  4911.9  593.95  4987.7  592.65  4988.0  592.15  4991.8  592.15
  4992.2  592.65  5066.6  594.05  5149.6  594.51  5308.3  596.10  5427.0  599.03
  5457.4  600.43  5478.3  600.28  5549.5  603.66  5581.2  604.52  5641.6  605.44
  5655.8  606.58  5705.2  606.39  5712.8  606.93  5719.4  606.38  5722.6  606.87
#Mann=9,-1,0
  3374.6    0.05       0  3705.4     0.1       0  4860.3    0.05       0
  4987.7   0.035       0  4992.2    0.05       0  5066.6     0.1       0
  5149.6    0.05       0  5427.0     0.1       0  5581.2    0.05       0
Bank Sta=4987.7,4992.2
Exp/Cntr=0.3,0.1

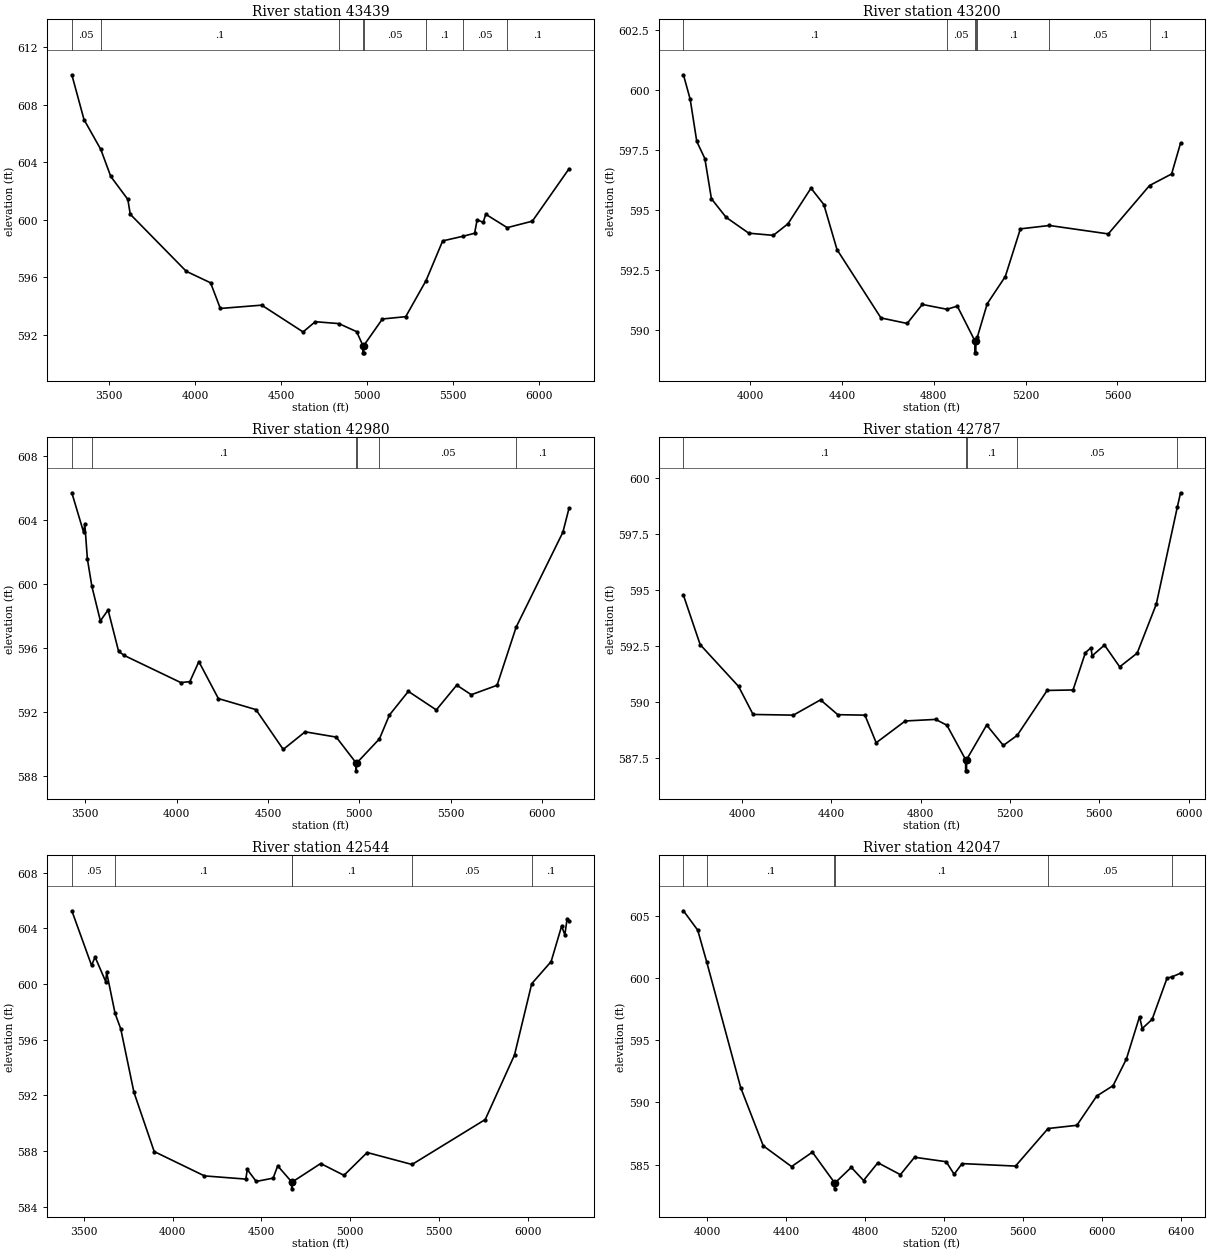
Type RM Length L Ch R = 1,43439,239,239,239
BEGIN DESCRIPTION:
UNT 004 in BCW 73.0
END DESCRIPTION:
XS GIS Cut Line= 3
      1958475.01     13500374.99      1959675.00     13499175.00
      1960388.49     13498221.17
#Sta/Elev= 30
  3284.2  610.07  3354.9  606.96  3452.4  604.89  3510.5  603.01  3609.5  601.42
  3623.6  600.39  3948.9  596.43  4090.3  595.63  4146.9  593.85  4387.3  594.08
  4627.7  592.22  4698.4  592.93  4835.6  592.80  4938.8  592.24  4975.5  591.27
  4975.8  590.77  4979.7  590.77  4980.0  591.27  5088.6  593.12  5224.0  593.28
  5342.3  595.79  5438.7  598.54  5559.6  598.87  5624.2  599.07  5638.8  600.00
  5674.2  599.83  5688.8  600.39  5813.7  599.46  5959.7  599.91  6172.4  603.54
#Mann=8,-1,0
  3284.2    0.05       0  3452.4     0.1       0  4835.6    0.05       0
  4975.5   0.035       0  4980.0    0.05       0  5342.3     0.1       0
  5559.6    0.05       0  5813.7     0.1       0
Bank Sta=4975.5,4980
Exp/Cntr=0.3,0.1

Type RM Length L Ch R = 1,43200,220,220,220
BEGIN DESCRIPTION:
Mapping XS 4cfbfa5f
END DESCRIPTION:
XS GIS Cut Line= 3
      1958976.73     13500138.37      1959708.49     13499529.01
      1960361.05     13498507.28
#Sta/Elev= 30
  3710.2  600.62  3739.7  599.60  3768.3  597.85  3803.5  597.14  3832.1  595.47
  3895.9  594.70  3994.8  594.04  4101.6  593.95  4165.4  594.43  4265.6  595.91
  4321.6  595.23  4378.9  593.36  4570.2  590.52  4684.4  590.29  4750.3  591.08
  4857.6  590.88  4902.7  591.01  4979.1  589.57  4979.4  589.07  4983.3  589.07
  4983.6  589.57  4989.8  589.72  5033.0  591.11  5111.7  592.24  5177.4  594.22
  5303.9  594.36  5560.0  594.01  5739.8  596.02  5835.8  596.50  5874.8  597.78
#Mann=7,-1,0
  3710.2     0.1       0  4857.6    0.05       0  4979.1    0.07       0
  4983.6    0.05       0  4989.8     0.1       0  5303.9    0.05       0
  5739.8     0.1       0
Bank Sta=4979.1,4983.6
Exp/Cntr=0.3,0.1

Type RM Length L Ch R = 1,42980,193,193,193
BEGIN DESCRIPTION:
UNT 004 in BCW 72.0
END DESCRIPTION:
XS GIS Cut Line= 3
      1958874.96     13500325.03      1960075.00     13499325.00
      1960628.06     13498304.53
#Sta/Elev= 30
  3426.0  605.69  3490.5  603.22  3497.0  603.73  3511.3  601.54  3535.7  599.84
  3582.3  597.68  3624.6  598.36  3681.8  595.79  3710.5  595.53  4022.9  593.82
  4072.3  593.88  4121.8  595.13  4228.6  592.82  4434.2  592.13  4583.9  589.64
  4703.7  590.74  4874.2  590.41  4982.6  588.80  4982.9  588.30  4987.1  588.80
  5110.8  590.30  5165.4  591.79  5269.1  593.27  5422.2  592.11  5534.1  593.66
  5613.7  593.06  5755.0  593.65  5859.6  597.29  6115.4  603.22  6148.8  604.71
#Mann=6,-1,0
  3426.0    0.05       0  3535.7     0.1       0  4982.6    0.07       0
  4987.1     0.1       0  5110.8    0.05       0  5859.6     0.1       0
Bank Sta=4982.6,4987.1
Exp/Cntr=0.3,0.1

Type RM Length L Ch R = 1,42787,243,243,243
BEGIN DESCRIPTION:
Mapping XS abad7512
END DESCRIPTION:
XS GIS Cut Line= 3
      1959489.73     13500445.70      1960291.83     13499325.88
      1960588.52     13498529.50
#Sta/Elev= 30
  3737.0  594.77  3812.0  592.57  3984.0  590.71  4049.1  589.46  4229.6  589.43
  4351.2  590.11  4428.6  589.45  4550.2  589.43  4600.6  588.20  4730.8  589.17
  4867.1  589.24  4917.5  588.98  5001.2  587.45  5001.5  586.95  5005.4  586.95
  5005.7  587.45  5095.6  588.99  5170.3  588.08  5232.5  588.53  5366.6  590.53
  5482.6  590.55  5537.9  592.21  5562.9  592.43  5568.2  592.07  5623.5  592.55
  5691.6  591.58  5769.9  592.19  5855.5  594.37  5949.5  598.68  5964.3  599.33
#Mann=5,-1,0
  3737.0     0.1       0  5001.2    0.07       0  5005.7     0.1       0
  5232.5    0.05       0  5949.5     0.1       0
Bank Sta=5001.2,5005.7
Exp/Cntr=0.3,0.1

Type RM Length L Ch R = 1,42544,497,497,497
BEGIN DESCRIPTION:
UNT 004 in BCW 71.0
END DESCRIPTION:
XS GIS Cut Line= 3
      1960625.00     13501074.99      1960425.00     13499525.00
      1960725.01     13498324.97
#Sta/Elev= 30
  3432.0  605.26  3542.9  601.34  3563.1  601.93  3622.9  600.17  3628.0  600.84
  3675.6  597.88  3707.4  596.78  3781.7  592.22  3895.8  587.96  4178.8  586.21
  4411.9  585.98  4420.1  586.67  4470.5  585.81  4565.7  586.05  4591.5  586.93
  4669.9  585.78  4670.2  585.28  4674.4  585.78  4833.5  587.10  4964.6  586.25
  5095.3  587.89  5348.0  587.03  5760.2  590.26  5925.1  594.90  6022.1  600.02
  6131.3  601.61  6190.5  604.16  6208.6  603.53  6221.5  604.70  6231.8  604.50
#Mann=6,-1,0
  3432.0    0.05       0  3675.6     0.1       0  4669.9    0.07       0
  4674.4     0.1       0  5348.0    0.05       0  6022.1     0.1       0
Bank Sta=4669.9,4674.4
Exp/Cntr=0.3,0.1

Type RM Length L Ch R = 1,42047,472,472,472
BEGIN DESCRIPTION:
UNT 004 in BCW 70.0
END DESCRIPTION:
XS GIS Cut Line= 3
      1961124.99     13500824.98      1960825.00     13499725.00
      1960924.95     13498351.38
#Sta/Elev= 30
  3880.1  605.41  3952.6  603.85  3998.6  601.26  4170.3  591.18  4284.3  586.51
  4427.7  584.84  4533.1  586.00  4644.9  583.55  4645.2  583.05  4649.4  583.55
  4730.0  584.78  4792.2  583.72  4864.8  585.15  4978.8  584.19  5050.3  585.59
  5210.8  585.23  5250.9  584.22  5291.0  585.08  5561.7  584.88  5726.6  587.90
  5872.5  588.16  5972.8  590.51  6055.9  591.35  6123.2  593.49  6189.9  596.90
  6203.4  595.94  6253.5  596.68  6329.0  599.99  6354.5  600.10  6397.5  600.39
#Mann=6,-1,0
  3880.1    0.05       0  3998.6     0.1       0  4644.9    0.07       0
  4649.4     0.1       0  5726.6    0.05       0  6354.5     0.1       0
Bank Sta=4644.9,4649.4
Exp/Cntr=0.3,0.1

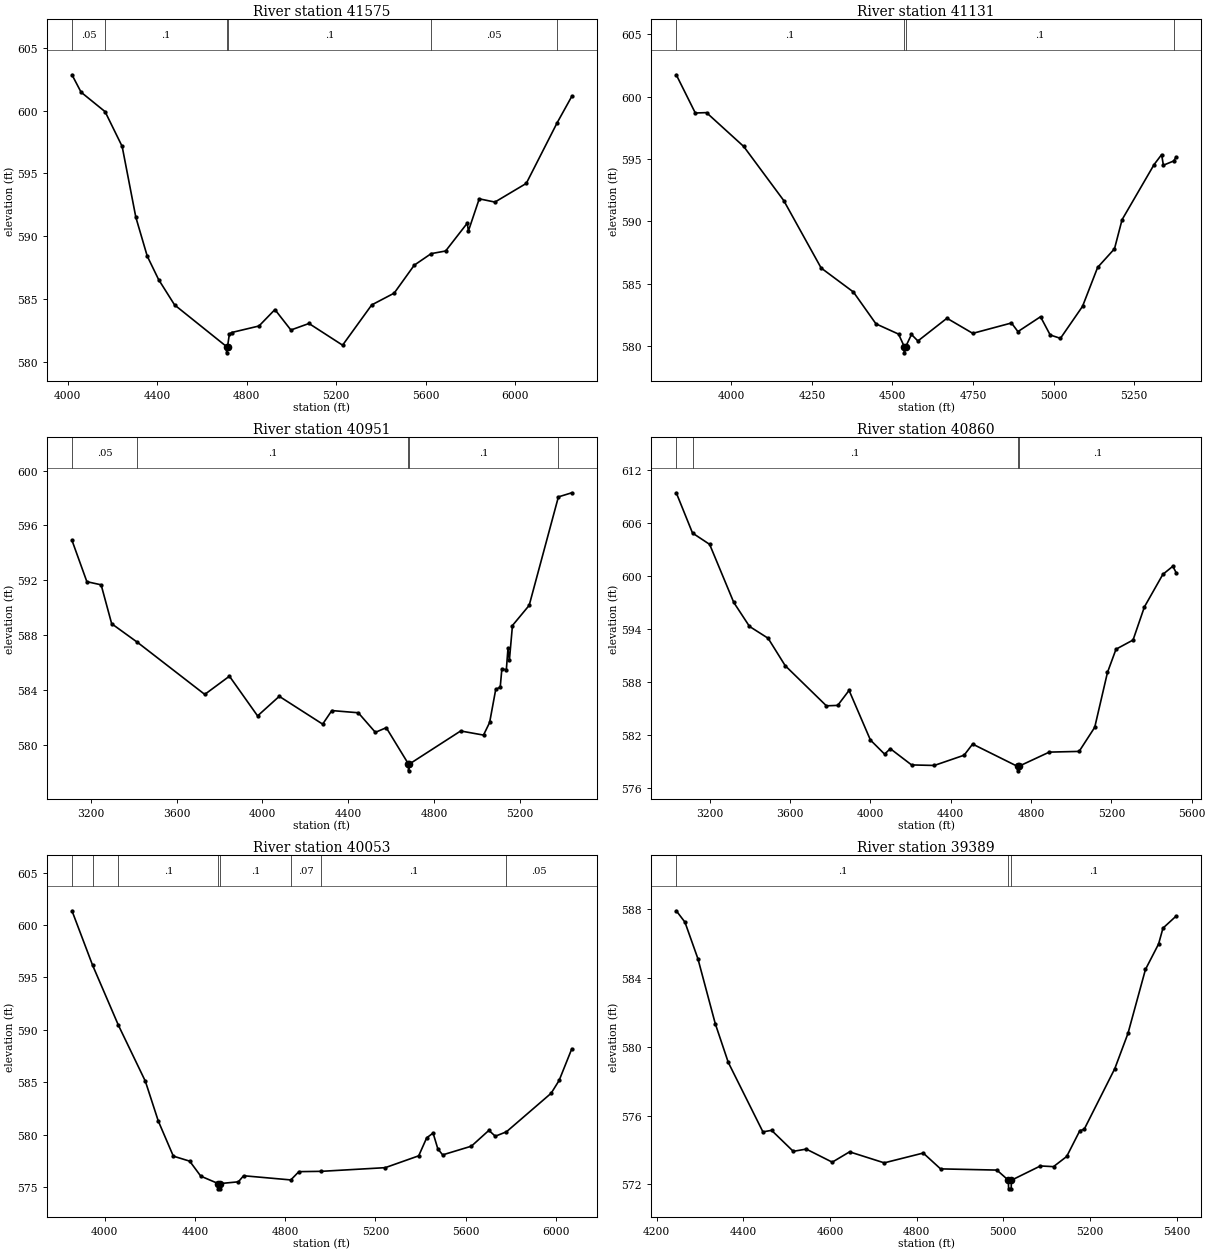
Type RM Length L Ch R = 1,41575,444,444,444
BEGIN DESCRIPTION:
UNT 004 in BCW 69.0
END DESCRIPTION:
XS GIS Cut Line= 3
      1961375.00     13500575.02      1961175.00     13499575.00
      1961102.03     13498361.82
#Sta/Elev= 30
  4018.7  602.87  4059.5  601.48  4166.8  599.93  4243.1  597.16  4304.3  591.51
  4355.3  588.41  4406.2  586.54  4477.6  584.52  4709.9  581.20  4710.2  580.70
  4714.4  581.20  4722.4  582.17  4732.6  582.32  4855.0  582.84  4926.3  584.15
  4997.7  582.52  5078.6  583.04  5228.9  581.31  5359.1  584.52  5459.6  585.46
  5549.4  587.69  5625.1  588.61  5689.7  588.82  5786.5  591.04  5791.5  590.41
  5840.0  592.98  5910.1  592.72  6050.4  594.21  6188.3  599.04  6253.9  601.15
#Mann=6,-1,0
  4018.7    0.05       0  4166.8     0.1       0  4709.9    0.07       0
  4714.4     0.1       0  5625.1    0.05       0  6188.3     0.1       0
Bank Sta=4709.9,4714.4
Exp/Cntr=0.3,0.1

Type RM Length L Ch R = 1,41131,180,180,180
BEGIN DESCRIPTION:
UNT 004 in BCW 68.0
END DESCRIPTION:
XS GIS Cut Line= 3
      1961523.90     13500544.07      1961475.00     13499375.00
      1961323.40     13499025.89
#Sta/Elev= 30
  3829.4  601.74  3888.5  598.68  3923.2  598.71  4038.7  596.00  4162.9  591.67
  4278.9  586.27  4379.0  584.35  4449.0  581.80  4519.1  580.98  4536.7  579.98
  4537.1  579.48  4541.4  579.98  4559.1  580.95  4579.1  580.43  4669.2  582.25
  4749.3  581.04  4869.4  581.87  4889.4  581.18  4959.5  582.37  4989.5  580.91
  5021.3  580.64  5089.8  583.20  5136.7  586.32  5189.0  587.81  5212.5  590.14
  5311.8  594.55  5335.2  595.35  5340.7  594.50  5372.8  594.84  5380.1  595.16
#Mann=4,-1,0
  3829.4     0.1       0  4536.7    0.07       0  4541.4     0.1       0
  5372.8    0.05       0
Bank Sta=4536.7,4541.4
Exp/Cntr=0.3,0.1

Type RM Length L Ch R = 1,40951,91,91,91
BEGIN DESCRIPTION:
Mapping XS aa74d868
END DESCRIPTION:
XS GIS Cut Line= 3
      1962716.61     13500880.03      1961935.36     13499679.51
      1961349.77     13499000.22
#Sta/Elev= 30
  3112.2  594.91  3181.6  591.89  3248.1  591.66  3297.2  588.82  3417.5  587.46
  3731.0  583.66  3846.0  584.99  3977.2  582.09  4078.2  583.52  4280.4  581.49
  4323.2  582.48  4446.4  582.32  4526.1  580.89  4576.8  581.23  4680.2  578.58
  4680.5  578.08  4684.9  578.58  4923.5  580.99  5030.0  580.69  5058.5  581.61
  5087.0  584.03  5107.9  584.19  5115.5  585.52  5136.4  585.46  5144.0  587.02
  5150.6  586.16  5164.9  588.69  5242.8  590.16  5379.0  598.08  5441.4  598.38
#Mann=5,-1,0
  3112.2    0.05       0  3417.5     0.1       0  4680.2    0.07       0
  4684.9     0.1       0  5379.0    0.05       0
Bank Sta=4680.2,4684.9
Exp/Cntr=0.3,0.1

Type RM Length L Ch R = 1,40860,807,807,807
BEGIN DESCRIPTION:
UNT 004 in BCW 67.0
END DESCRIPTION:
XS GIS Cut Line= 3
      1963036.95     13500755.92      1962708.80     13500346.18
      1961349.71     13498927.20
#Sta/Elev= 30
  3032.7  609.41  3113.7  604.85  3198.9  603.57  3319.0  597.00  3397.4  594.28
  3490.2  592.94  3575.2  589.84  3780.6  585.29  3836.9  585.34  3893.5  587.04
  3999.8  581.42  4070.5  579.82  4098.8  580.44  4204.8  578.60  4318.0  578.54
  4466.5  579.70  4508.9  580.96  4733.0  578.43  4733.4  577.93  4737.7  578.43
  4890.7  580.05  5039.5  580.13  5117.2  582.86  5180.7  589.07  5223.2  591.70
  5308.1  592.74  5364.7  596.49  5456.5  600.17  5506.2  601.09  5522.5  600.38
#Mann=4,-1,0
  3032.7    0.05       0  3113.7     0.1       0  4733.0    0.07       0
  4737.7     0.1       0
Bank Sta=4733,4737.7
Exp/Cntr=0.3,0.1

Type RM Length L Ch R = 1,40053,664,664,664
BEGIN DESCRIPTION:
UNT 004 in BCW 66.0
END DESCRIPTION:
XS GIS Cut Line= 3
      1963075.02     13500225.03      1962506.54     13499342.70
      1961690.85     13498509.65
#Sta/Elev= 30
  3855.0  601.35  3946.3  596.16  4061.0  590.42  4180.2  585.09  4237.6  581.29
  4304.3  577.94  4376.9  577.46  4426.0  576.03  4503.4  575.32  4503.9  574.82
  4509.9  574.82  4510.4  575.32  4592.6  575.49  4615.8  576.07  4825.0  575.67
  4860.8  576.46  4959.8  576.49  5243.5  576.84  5391.9  577.97  5427.4  579.69
  5455.7  580.14  5476.8  578.63  5498.1  578.06  5625.4  578.89  5703.1  580.40
  5731.4  579.84  5780.7  580.26  5979.0  583.94  6014.3  585.16  6070.5  588.18
#Mann=8,-1,0
  3855.0     0.1       0  3946.3    0.05       0  4061.0     0.1       0
  4503.4    0.07       0  4510.4     0.1       0  4825.0    0.07       0
  4959.8     0.1       0  5780.7    0.05       0
Bank Sta=4503.4,4510.4
Exp/Cntr=0.3,0.1

Type RM Length L Ch R = 1,39389,503,503,503
BEGIN DESCRIPTION:
UNT 004 in BCW 65.0
END DESCRIPTION:
XS GIS Cut Line= 3
      1963025.00     13499975.04      1963025.00     13499175.00
      1962975.00     13498824.99
#Sta/Elev= 30
  4245.3  587.90  4265.3  587.24  4295.3  585.11  4335.3  581.34  4365.3  579.09
  4445.3  575.05  4465.3  575.14  4515.3  573.92  4545.3  574.05  4605.3  573.29
  4645.3  573.89  4725.3  573.25  4815.3  573.82  4855.3  572.90  4985.3  572.83
  5011.8  572.24  5012.3  571.74  5018.3  571.74  5018.8  572.24  5085.7  573.07
  5116.0  573.03  5146.4  573.62  5176.7  575.12  5186.8  575.20  5257.5  578.73
  5287.8  580.77  5328.2  584.49  5358.5  585.97  5368.6  586.89  5398.9  587.59
#Mann=3,-1,0
  4245.3     0.1       0  5011.8    0.07       0  5018.8     0.1       0
Bank Sta=5011.8,5018.8
Exp/Cntr=0.3,0.1

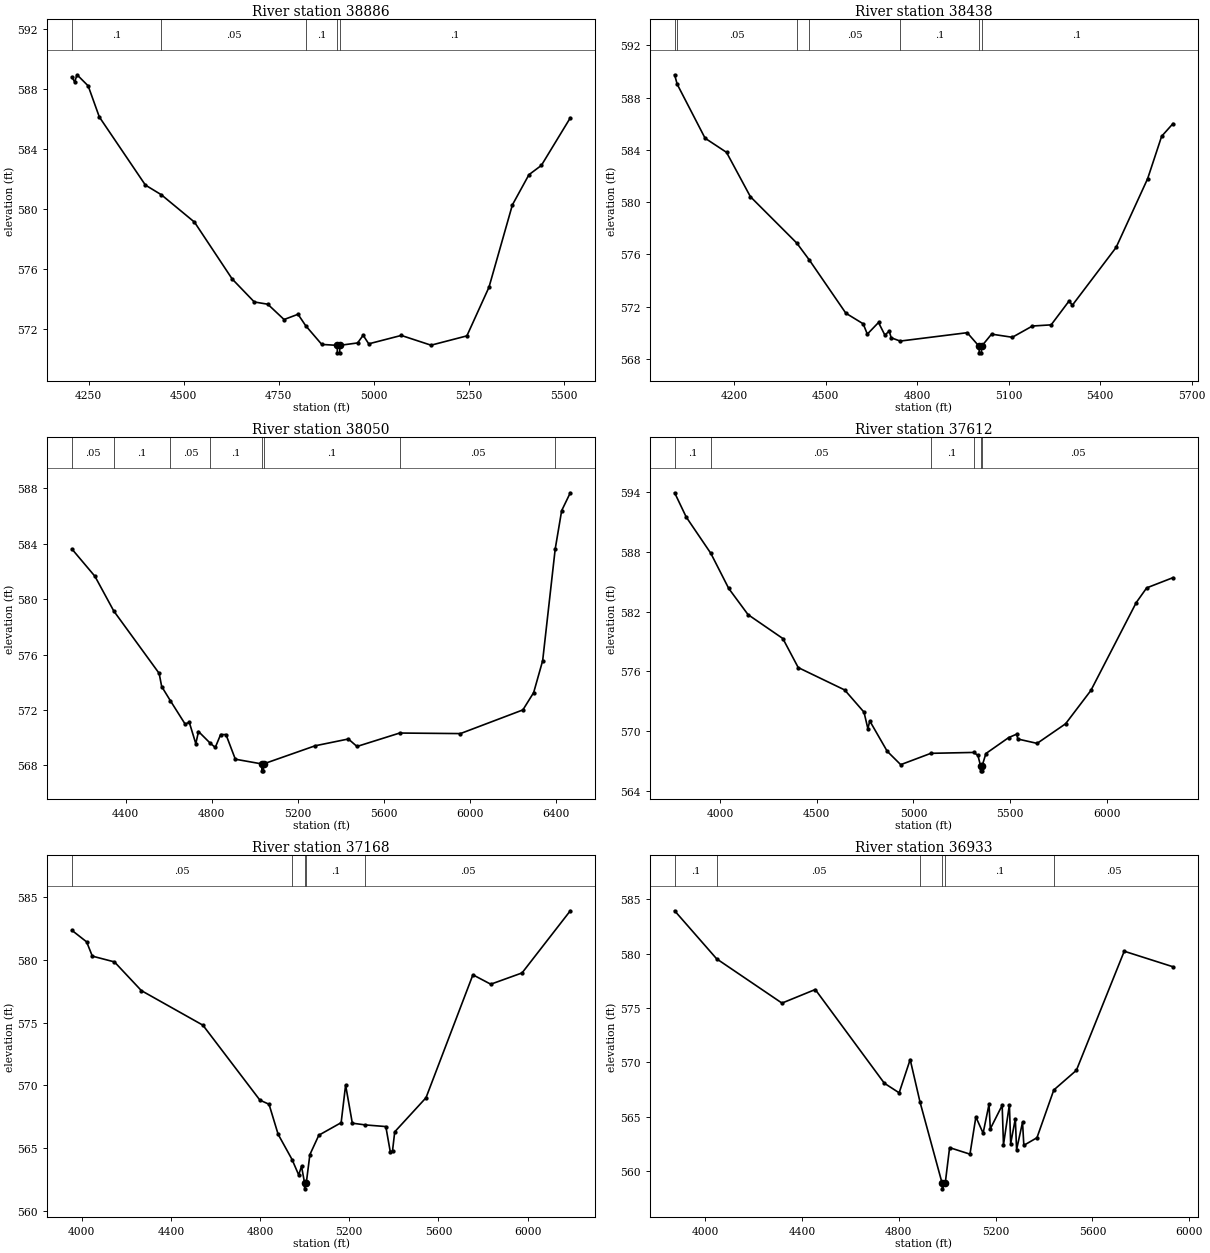
Type RM Length L Ch R = 1,38886,448,448,448
BEGIN DESCRIPTION:
UNT 004 in BCW 64.0
END DESCRIPTION:
XS GIS Cut Line= 3
      1963974.99     13499824.98      1963425.00     13499075.00
      1963275.01     13498725.02
#Sta/Elev= 30
  4205.8  588.82  4213.1  588.48  4219.3  588.96  4248.6  588.22  4277.9  586.15
  4399.1  581.61  4441.3  580.96  4528.2  579.14  4627.4  575.35  4685.5  573.82
  4721.0  573.67  4763.8  572.65  4800.5  573.00  4820.6  572.24  4863.0  570.99
  4903.5  570.93  4904.0  570.43  4910.0  570.43  4910.5  570.93  4957.2  571.09
  4971.8  571.60  4986.5  571.03  5072.1  571.59  5150.3  570.94  5244.6  571.56
  5302.7  574.80  5364.3  580.29  5407.8  582.30  5440.5  582.92  5516.6  586.09
#Mann=5,-1,0
  4205.8     0.1       0  4441.3    0.05       0  4820.6     0.1       0
  4903.5    0.07       0  4910.5     0.1       0
Bank Sta=4903.5,4910.5
Exp/Cntr=0.3,0.1

Type RM Length L Ch R = 1,38438,388,388,388
BEGIN DESCRIPTION:
UNT 004 in BCW 63.0
END DESCRIPTION:
XS GIS Cut Line= 3
      1964475.01     13499725.01      1963825.00     13498925.00
      1963275.04     13498675.02
#Sta/Elev= 30
  4004.0  589.74  4012.3  589.02  4103.9  584.89  4174.2  583.81  4252.5  580.42
  4404.8  576.87  4445.5  575.59  4565.7  571.51  4622.5  570.70  4636.1  569.91
  4672.8  570.80  4693.6  569.84  4708.0  570.14  4714.4  569.63  4743.9  569.38
  4963.7  570.02  5002.7  568.98  5003.2  568.48  5010.3  568.48  5010.8  568.98
  5043.6  569.91  5111.7  569.67  5177.6  570.53  5239.1  570.62  5298.4  572.46
  5308.3  572.11  5452.2  576.54  5555.5  581.79  5601.6  585.04  5638.9  586.01
#Mann=7,-1,0
  4004.0     0.1       0  4012.3    0.05       0  4404.8     0.1       0
  4445.5    0.05       0  4743.9     0.1       0  5002.7    0.07       0
  5010.8     0.1       0
Bank Sta=5002.7,5010.8
Exp/Cntr=0.3,0.1

Type RM Length L Ch R = 1,38050,438,438,438
BEGIN DESCRIPTION:
UNT 004 in BCW 62.0
END DESCRIPTION:
XS GIS Cut Line= 3
      1964474.98     13499574.95      1964125.47     13498651.73
      1964075.00     13497324.96
#Sta/Elev= 30
  4151.0  583.62  4257.9  581.65  4345.6  579.14  4556.2  574.64  4568.0  573.69
  4608.9  572.65  4676.8  570.98  4696.3  571.10  4726.5  569.56  4739.0  570.44
  4794.6  569.58  4817.0  569.29  4841.8  570.22  4866.6  570.22  4910.1  568.44
  5032.8  568.10  5033.3  567.60  5040.5  567.60  5041.0  568.10  5281.0  569.41
  5435.1  569.90  5475.1  569.36  5673.5  570.33  5955.5  570.29  6245.7  572.00
  6295.7  573.25  6337.5  575.55  6395.8  583.62  6425.8  586.39  6465.9  587.68
#Mann=8,-1,0
  4151.0    0.05       0  4345.6     0.1       0  4608.9    0.05       0
  4794.6     0.1       0  5032.8    0.07       0  5041.0     0.1       0
  5673.5    0.05       0  6395.8     0.1       0
Bank Sta=5032.8,5041
Exp/Cntr=0.3,0.1

Type RM Length L Ch R = 1,37612,444,444,444
BEGIN DESCRIPTION:
UNT 004 in BCW 61.0
END DESCRIPTION:
XS GIS Cut Line= 3
      1964525.00     13499874.96      1964535.42     13498532.64
      1964835.42     13497332.63
#Sta/Elev= 30
  3764.1  593.94  3824.1  591.50  3951.5  587.85  4044.1  584.32  4144.1  581.69
  4324.1  579.29  4403.7  576.37  4644.1  574.12  4744.1  571.89  4764.1  570.24
  4774.1  571.00  4864.1  567.96  4934.1  566.61  5090.1  567.75  5312.0  567.84
  5333.7  567.54  5347.3  566.49  5347.8  565.99  5355.0  565.99  5355.5  566.49
  5375.0  567.73  5493.5  569.34  5534.7  569.68  5539.9  569.19  5640.0  568.75
  5787.3  570.72  5918.3  574.07  6153.2  582.91  6207.0  584.38  6343.4  585.41
#Mann=6,-1,0
  3764.1     0.1       0  3951.5    0.05       0  5090.1     0.1       0
  5312.0    0.05       0  5347.3    0.03       0  5355.5    0.05       0
Bank Sta=5347.3,5355.5
Exp/Cntr=0.3,0.1

Type RM Length L Ch R = 1,37168,235,235,235
BEGIN DESCRIPTION:
UNT 004 in BCW 60.0
END DESCRIPTION:
XS GIS Cut Line= 3
      1964760.88     13499679.51      1964975.00     13498675.00
      1964913.72     13497468.83
#Sta/Elev= 30
  3956.3  582.38  4022.3  581.46  4047.9  580.32  4147.0  579.86  4267.7  577.57
  4543.7  574.81  4799.3  568.83  4840.2  568.50  4881.1  566.10  4943.5  564.09
  4973.2  562.86  4985.9  563.55  4999.3  562.25  4999.8  561.75  5007.5  562.25
  5023.4  564.48  5063.5  566.03  5163.6  567.03  5183.6  570.03  5213.7  566.99
  5272.4  566.85  5363.9  566.72  5383.9  564.71  5393.9  564.78  5403.9  566.30
  5544.1  569.02  5754.4  578.83  5834.5  578.08  5974.7  578.98  6191.1  583.94
#Mann=5,-1,0
  3956.3    0.05       0  4943.5     0.1       0  4999.3    0.07       0
  5007.5     0.1       0  5272.4    0.05       0
Bank Sta=4999.3,5007.5
Exp/Cntr=0.3,0.1

Type RM Length L Ch R = 1,36933,38,38,38
BEGIN DESCRIPTION:
UNT 004 in BCW 59.0
END DESCRIPTION:
XS GIS Cut Line= 4
      1965075.00     13499725.00      1965260.88     13498773.26
      1965066.44     13498276.73      1965007.41     13497724.65
#Sta/Elev= 30
  3874.7  583.95  4048.3  579.53  4318.0  575.46  4455.5  576.71  4740.8  568.09
  4801.9  567.21  4847.4  570.27  4888.3  566.34  4979.5  558.88  4980.0  558.38
  4992.1  558.88  5010.2  562.17  5094.3  561.57  5118.7  564.99  5148.6  563.50
  5173.0  566.15  5178.4  563.90  5227.3  566.06  5232.7  562.43  5257.1  566.11
  5262.5  562.54  5281.6  564.83  5286.9  561.99  5311.4  564.50  5316.8  562.38
  5371.0  563.08  5440.5  567.47  5533.8  569.28  5731.4  580.23  5932.9  578.80
#Mann=6,-1,0
  3874.7     0.1       0  4048.3    0.05       0  4888.3     0.1       0
  4979.5    0.07       0  4992.1     0.1       0  5440.5    0.05       0
Bank Sta=4979.5,4992.1
Exp/Cntr=0.3,0.1