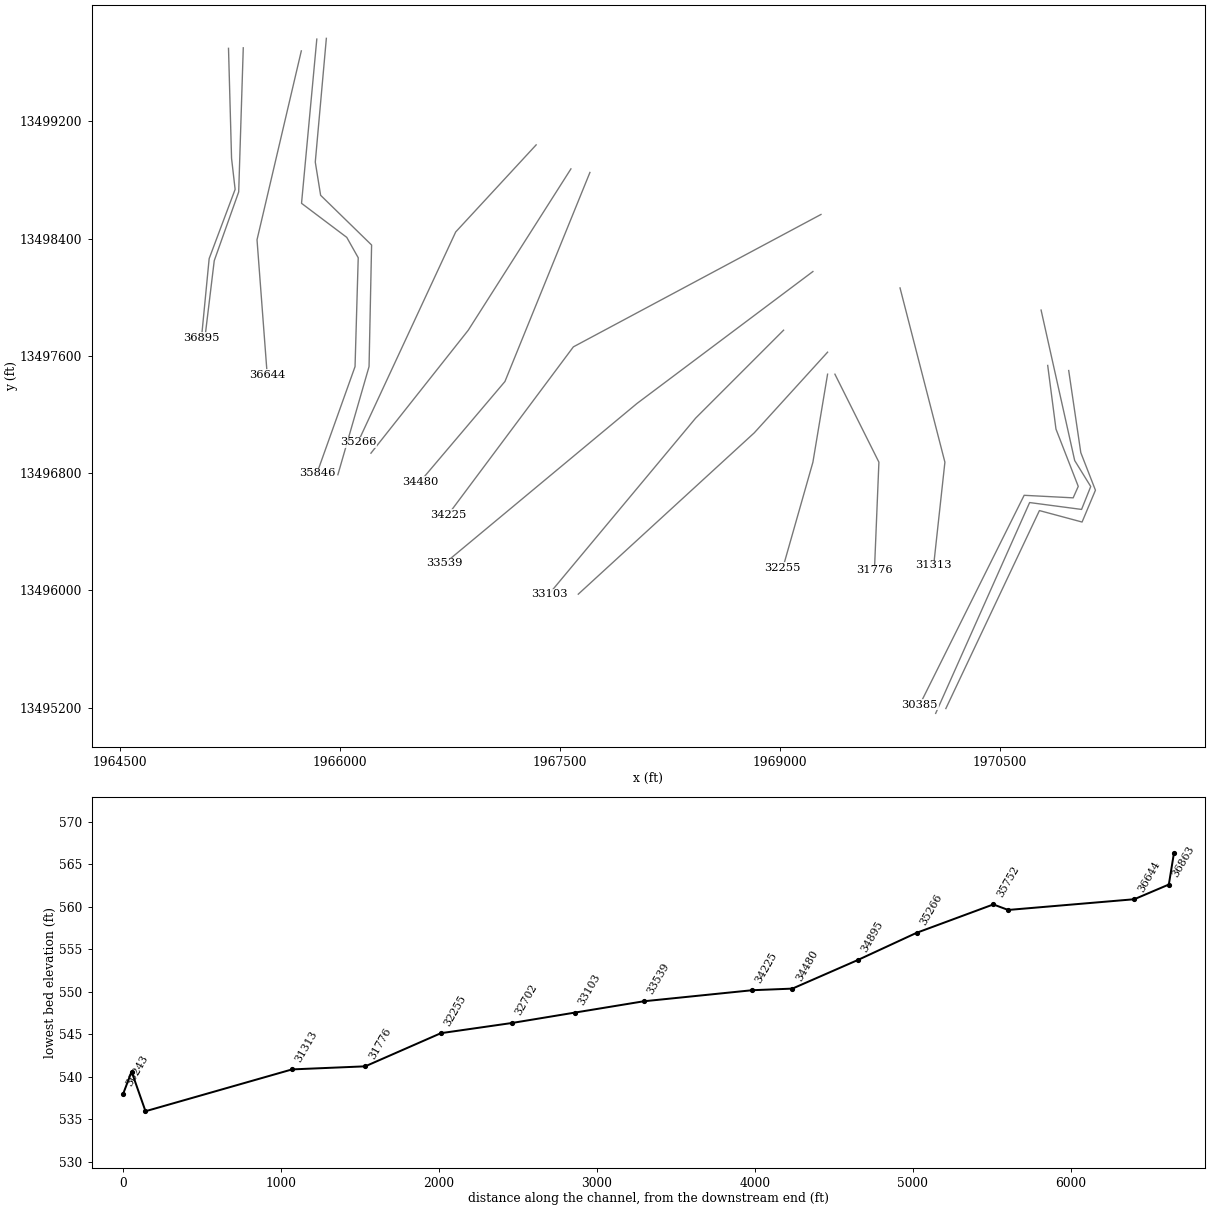
HEC-RAS study UNT 004 in BCW.prj: UNT 004 in BCW Base Level Engineering

--- UNT 004 in BCW.g01 (geometry) --- (continued)

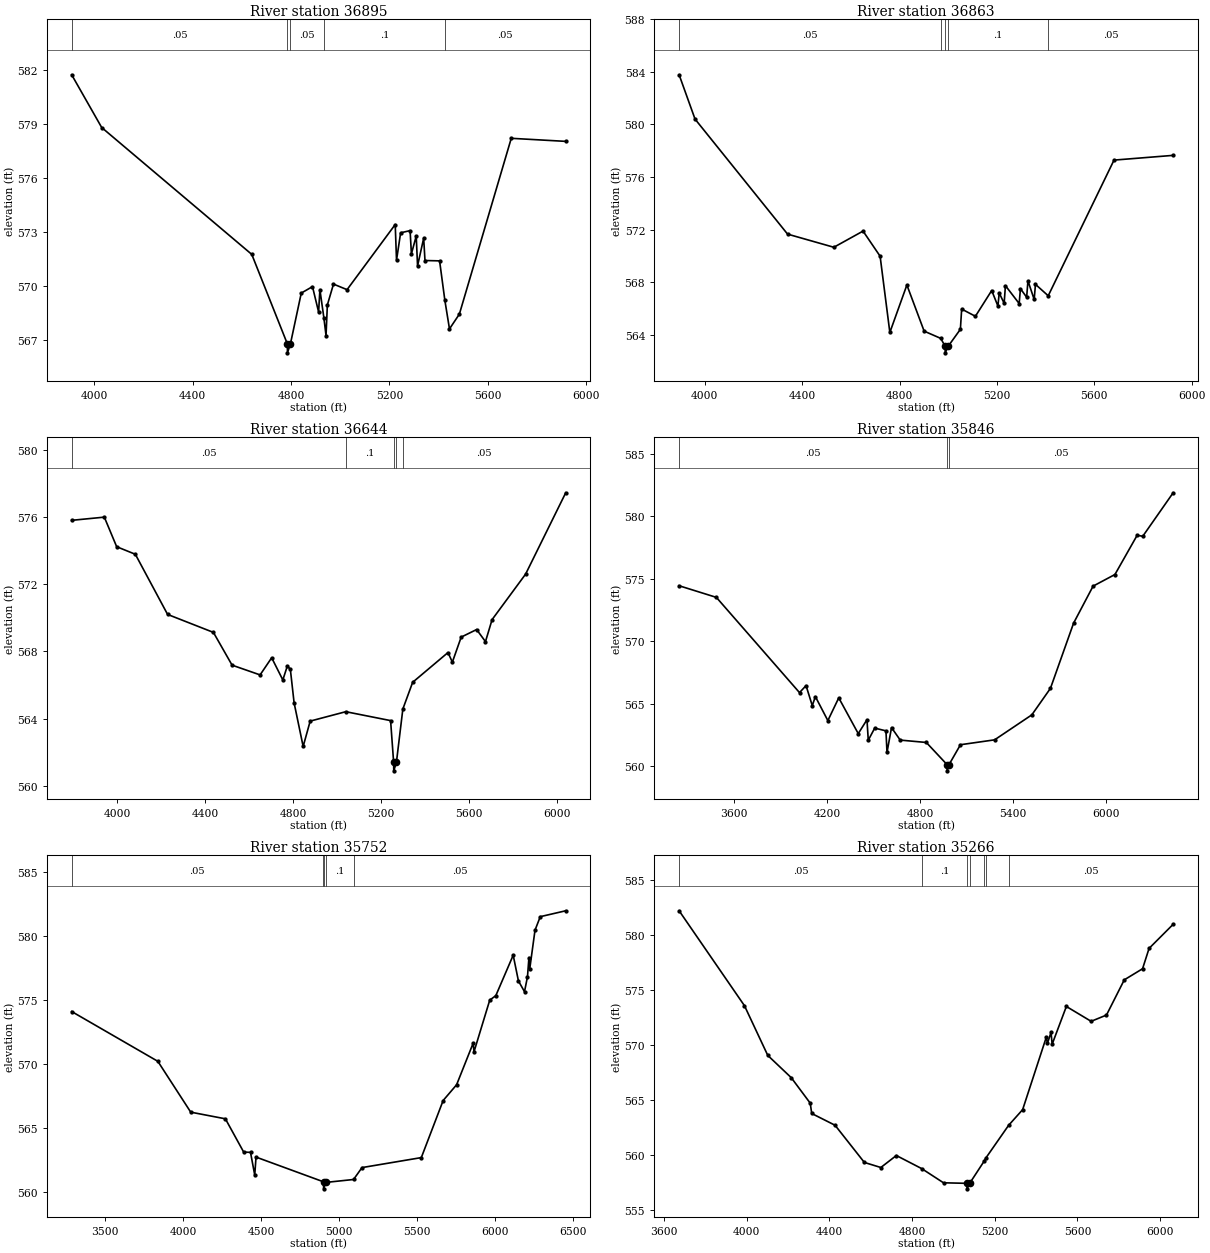
Type RM Length L Ch R = 1,36895,32,32,32
BEGIN DESCRIPTION:
Mapping XS 6e1979c2
END DESCRIPTION:
XS GIS Cut Line= 5
      1965240.05     13499696.91      1965260.88     13498946.87
      1965285.19     13498735.07      1965108.11     13498262.84
      1965056.02     13497724.62
#Sta/Elev= 30
  3908.3  581.73  4030.3  578.80  4640.5  571.75  4785.1  566.78  4785.6  566.28
  4797.7  566.78  4841.7  569.60  4887.3  569.96  4912.2  568.55  4917.5  569.79
  4933.8  568.21  4942.4  567.24  4947.8  568.94  4972.7  570.10  5027.9  569.79
  5223.7  573.41  5229.0  571.43  5245.7  572.95  5284.2  573.07  5289.5  571.78
  5309.1  572.77  5314.5  571.11  5339.4  572.65  5344.7  571.41  5404.1  571.39
  5425.5  569.20  5444.3  567.61  5484.5  568.43  5695.5  578.20  5916.9  578.03
#Mann=5,-1,0
  3908.3    0.05       0  4785.1    0.07       0  4797.7    0.05       0
  4933.8     0.1       0  5425.5    0.05       0
Bank Sta=4785.1,4797.7
Exp/Cntr=0.3,0.1

Type RM Length L Ch R = 1,36863,219,219,219
BEGIN DESCRIPTION:
UNT 004 in BCW 58.0
END DESCRIPTION:
XS GIS Cut Line= 4
      1965340.75     13499700.35      1965309.50     13498717.70
      1965142.83     13498248.95      1965076.85     13497703.77
#Sta/Elev= 30
  3894.2  583.77  3959.6  580.40  4339.8  571.65  4529.9  570.65  4649.9  571.88
  4720.0  569.97  4760.0  564.17  4830.0  567.78  4900.9  564.27  4969.1  563.72
  4987.1  563.12  4987.6  562.62  4999.7  563.12  5049.8  564.41  5055.1  565.95
  5111.5  565.40  5178.5  567.36  5204.0  566.18  5209.4  567.17  5229.6  566.39
  5234.9  567.73  5291.3  566.37  5296.6  567.50  5322.1  566.85  5327.4  568.10
  5353.0  566.68  5358.3  567.83  5410.7  566.96  5681.0  577.28  5924.0  577.64
#Mann=5,-1,0
  3894.2    0.05       0  4969.1     0.1       0  4987.1    0.07       0
  4999.7     0.1       0  5410.7    0.05       0
Bank Sta=4987.1,4999.7
Exp/Cntr=0.3,0.1

Type RM Length L Ch R = 1,36644,798,798,798
BEGIN DESCRIPTION:
Mapping XS 34bc4644
END DESCRIPTION:
XS GIS Cut Line= 3
      1965736.58     13499679.53      1965434.50     13498391.32
      1965503.94     13497471.19
#Sta/Elev= 30
  3793.8  575.80  3942.2  575.99  3998.3  574.23  4083.2  573.78  4229.8  570.20
  4438.1  569.13  4523.0  567.18  4650.3  566.60  4703.0  567.62  4753.7  566.30
  4774.2  567.13  4787.9  566.93  4805.0  564.93  4846.1  562.34  4878.0  563.85
  5039.9  564.41  5243.6  563.88  5257.4  561.39  5257.9  560.89  5270.0  561.39
  5299.3  564.57  5343.9  566.16  5504.4  567.93  5524.4  567.36  5564.5  568.85
  5634.7  569.30  5674.9  568.58  5704.9  569.89  5857.4  572.60  6039.7  577.44
#Mann=5,-1,0
  3793.8    0.05       0  5039.9     0.1       0  5257.4    0.03       0
  5270.0     0.1       0  5299.3    0.05       0
Bank Sta=5257.4,5270
Exp/Cntr=0.3,0.1

Type RM Length L Ch R = 1,35846,94,94,94
BEGIN DESCRIPTION:
UNT 004 in BCW 57.0
END DESCRIPTION:
XS GIS Cut Line= 6
      1965842.18     13499759.95      1965738.01     13498640.12
      1966046.47     13498407.81      1966124.60     13498268.92
      1966102.90     13497526.73      1965842.90     13496798.75
#Sta/Elev= 30
  3246.7  574.44  3486.9  573.51  4023.0  565.89  4065.2  566.45  4105.3  564.85
  4125.4  565.57  4205.8  563.65  4276.1  565.47  4401.8  562.61  4458.1  563.72
  4466.4  562.08  4508.0  563.05  4580.4  562.83  4587.2  561.10  4616.3  563.09
  4672.5  562.09  4840.8  561.90  4974.3  560.13  4974.8  559.63  4987.3  560.13
  5060.9  561.72  5281.0  562.11  5521.1  564.11  5641.1  566.23  5790.4  571.45
  5916.1  574.41  6057.0  575.34  6200.3  578.48  6236.4  578.40  6432.4  581.88
#Mann=3,-1,0
  3246.7    0.05       0  4974.3    0.04       0  4987.3    0.05       0
Bank Sta=4974.3,4987.3
Exp/Cntr=0.3,0.1

Type RM Length L Ch R = 1,35752,486,486,486
BEGIN DESCRIPTION:
UNT 004 in BCW 56.0
END DESCRIPTION:
XS GIS Cut Line= 6
      1965907.27     13499765.07      1965831.76     13498921.37
      1965868.22     13498694.81      1966215.75     13498355.73
      1966198.38     13497526.73      1965985.87     13496789.45
#Sta/Elev= 30
  3284.8  574.13  3837.1  570.24  4047.9  566.27  4270.0  565.75  4387.3  563.15
  4431.0  563.13  4458.1  561.36  4466.4  562.76  4894.1  560.85  4899.1  560.78
  4899.6  560.28  4912.2  560.78  5091.4  561.01  5145.7  561.94  5525.8  562.72
  5665.8  567.18  5752.0  568.41  5858.2  571.66  5863.4  570.98  5964.4  575.02
  6003.3  575.37  6114.7  578.53  6148.3  576.52  6187.2  575.68  6206.3  576.85
  6215.7  578.35  6220.9  577.47  6254.5  580.48  6288.2  581.54  6451.4  582.00
#Mann=5,-1,0
  3284.8    0.05       0  4894.1     0.1       0  4899.1    0.07       0
  4912.2     0.1       0  5091.4    0.05       0
Bank Sta=4899.1,4912.2
Exp/Cntr=0.3,0.1

Type RM Length L Ch R = 1,35266,371,371,371
BEGIN DESCRIPTION:
Mapping XS ed718778
END DESCRIPTION:
XS GIS Cut Line= 3
      1967337.81     13499038.53      1966789.22     13498444.81
      1966122.55     13497010.77
#Sta/Elev= 30
  3673.5  582.22  3989.6  573.59  4102.4  569.07  4215.8  567.05  4307.7  564.73
  4315.0  563.79  4427.9  562.72  4569.6  559.34  4649.3  558.88  4724.3  559.97
  4846.9  558.78  4952.4  557.49  5065.8  557.44  5066.3  556.94  5079.0  557.44
  5149.8  559.48  5156.8  559.73  5267.2  562.71  5335.2  564.14  5449.6  570.72
  5455.1  570.17  5472.5  571.16  5478.0  570.09  5546.7  573.52  5666.6  572.17
  5740.8  572.74  5826.8  575.94  5915.3  576.95  5946.8  578.80  6063.3  580.99
#Mann=7,-1,0
  3673.5    0.05       0  4846.9     0.1       0  5065.8    0.07       0
  5079.0     0.1       0  5149.8    0.05       0  5156.8     0.1       0
  5267.2    0.05       0
Bank Sta=5065.8,5079
Exp/Cntr=0.3,0.1

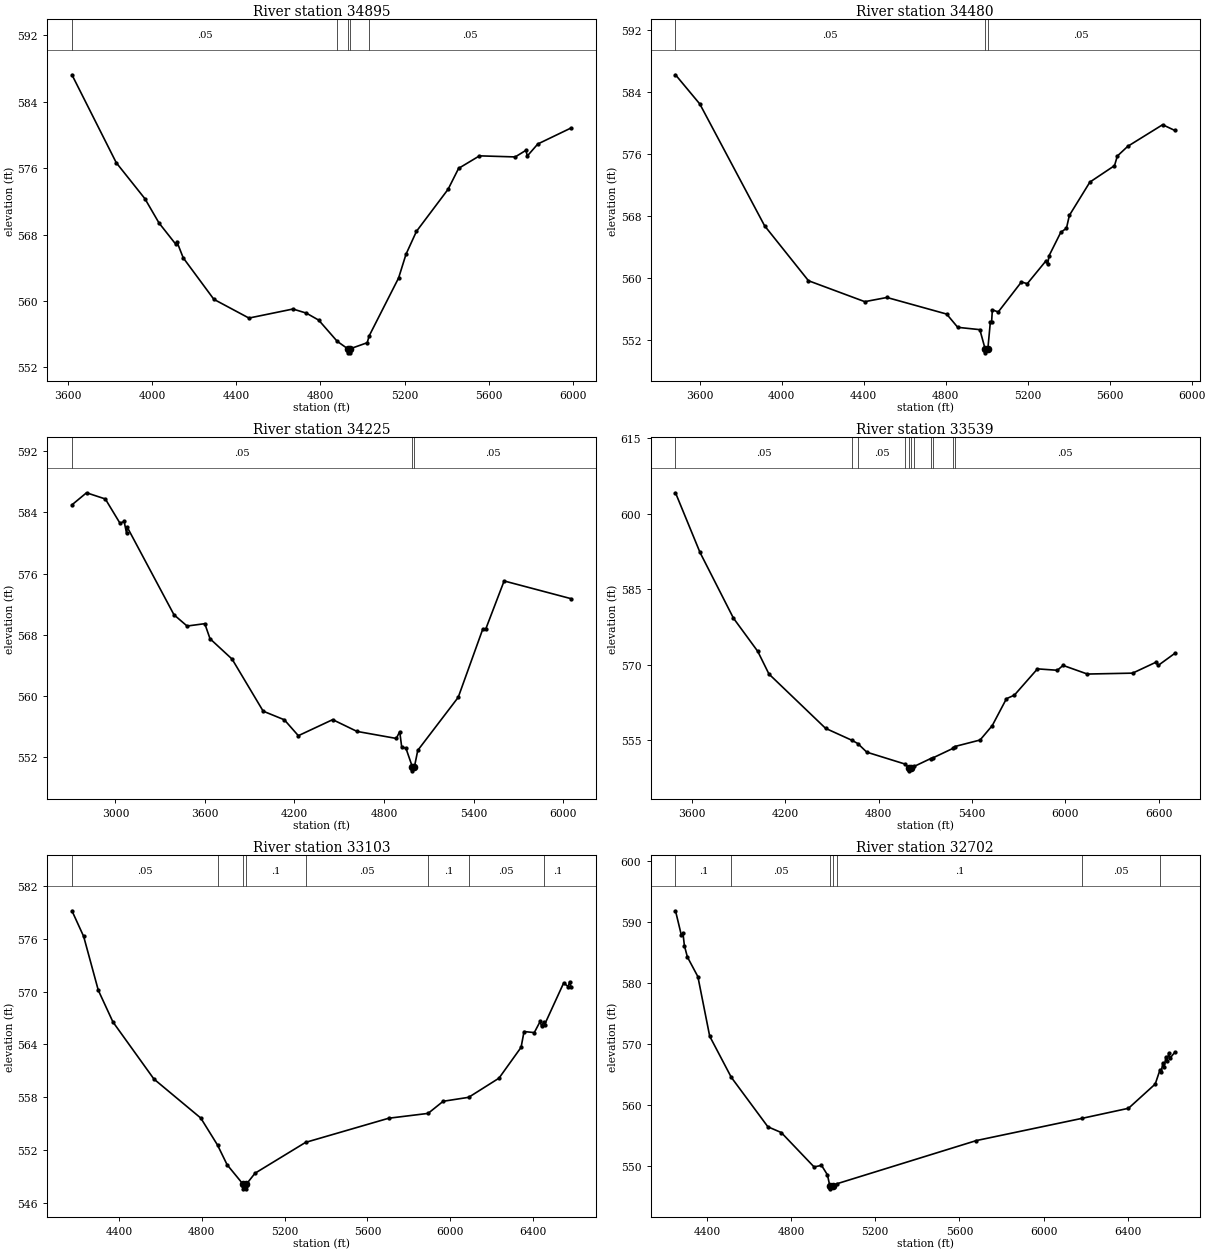
Type RM Length L Ch R = 1,34895,415,415,415
BEGIN DESCRIPTION:
UNT 004 in BCW 55.0
END DESCRIPTION:
XS GIS Cut Line= 3
      1967574.99     13498874.99      1966875.00     13497775.00
      1966211.39     13496936.44
#Sta/Elev= 30
  3618.6  587.26  3829.4  576.66  3965.7  572.32  4032.6  569.40  4111.3  566.87
  4117.3  567.16  4147.7  565.20  4293.4  560.20  4460.2  557.94  4669.3  559.03
  4732.8  558.54  4792.0  557.69  4879.8  555.14  4929.4  554.25  4929.9  553.75
  4942.1  553.75  4942.6  554.25  5022.6  554.97  5031.5  555.78  5171.7  562.77
  5206.9  565.63  5256.6  568.39  5407.0  573.46  5457.0  575.98  5556.3  577.49
  5726.2  577.36  5776.8  578.15  5783.9  577.48  5833.6  578.92  5991.8  580.85
#Mann=5,-1,0
  3618.6    0.05       0  4879.8     0.1       0  4929.4    0.07       0
  4942.6     0.1       0  5031.5    0.05       0
Bank Sta=4929.4,4942.6
Exp/Cntr=0.3,0.1

Type RM Length L Ch R = 1,34480,255,255,255
BEGIN DESCRIPTION:
UNT 004 in BCW 54.0
END DESCRIPTION:
XS GIS Cut Line= 3
      1967704.47     13498850.53      1967125.00     13497425.00
      1966545.61     13496741.15
#Sta/Elev= 30
  3481.9  586.24  3600.6  582.47  3916.5  566.77  4130.6  559.68  4405.4  556.98
  4513.4  557.52  4804.8  555.38  4858.8  553.67  4966.7  553.37  4992.5  550.88
  4993.0  550.38  5005.7  550.88  5018.0  554.36  5024.0  554.36  5027.8  555.93
  5056.4  555.65  5169.5  559.52  5198.1  559.30  5290.4  562.28  5297.0  561.78
  5304.7  562.92  5361.5  565.92  5389.2  566.45  5403.5  568.11  5503.5  572.40
  5623.6  574.52  5637.5  575.76  5688.1  577.01  5858.4  579.80  5917.0  579.07
#Mann=3,-1,0
  3481.9    0.05       0  4992.5    0.03       0  5005.7    0.05       0
Bank Sta=4992.5,5005.7
Exp/Cntr=0.3,0.1

Type RM Length L Ch R = 1,34225,686,686,686
BEGIN DESCRIPTION:
UNT 004 in BCW 53.0
END DESCRIPTION:
XS GIS Cut Line= 3
      1969279.95     13498564.04      1967591.61     13497661.28
      1966736.59     13496515.47
#Sta/Elev= 30
  2708.9  585.00  2806.6  586.58  2932.6  585.77  3031.0  582.59  3058.6  582.83
  3074.9  581.28  3080.5  582.04  3392.7  570.61  3480.4  569.14  3599.0  569.45
  3634.0  567.48  3782.0  564.81  3990.1  558.00  4132.0  556.87  4225.8  554.79
  4455.8  556.89  4618.7  555.35  4882.0  554.43  4905.0  555.32  4918.2  553.32
  4946.6  553.15  4990.0  550.69  4990.5  550.19  5003.3  550.69  5025.9  552.87
  5296.9  559.81  5461.6  568.75  5482.4  568.80  5604.5  575.04  6053.1  572.72
#Mann=3,-1,0
  2708.9    0.05       0  4990.0    0.03       0  5003.3    0.05       0
Bank Sta=4990,5003.3
Exp/Cntr=0.3,0.1

Type RM Length L Ch R = 1,33539,436,436,436
BEGIN DESCRIPTION:
UNT 004 in BCW 52.0
END DESCRIPTION:
XS GIS Cut Line= 3
      1969224.99     13498174.99      1968025.00     13497275.00
      1966714.86     13496185.57
#Sta/Elev= 30
  3496.7  604.19  3654.0  592.33  3868.6  579.26  4024.8  572.65  4096.7  568.14
  4460.2  557.34  4628.7  554.97  4666.7  554.32  4724.8  552.60  4971.9  550.22
  4997.1  549.39  4997.6  548.89  5010.6  549.39  5028.1  549.76  5133.8  551.32
  5152.7  551.52  5277.3  553.35  5288.5  553.72  5451.7  555.02  5529.8  557.88
  5621.0  563.24  5671.8  563.94  5820.2  569.17  5947.8  568.89  5984.2  569.86
  6140.5  568.14  6430.8  568.32  6580.5  570.49  6594.9  569.85  6700.6  572.23
#Mann=11,-1,0
  3496.7    0.05       0  4628.7     0.1       0  4666.7    0.05       0
  4971.9     0.1       0  4997.1    0.07       0  5010.6     0.1       0
  5028.1    0.07       0  5133.8     0.1       0  5152.7    0.05       0
  5277.3     0.1       0  5288.5    0.05       0
Bank Sta=4997.1,5010.6
Exp/Cntr=0.3,0.1

Type RM Length L Ch R = 1,33103,401,401,401
BEGIN DESCRIPTION:
UNT 004 in BCW 51.0
END DESCRIPTION:
XS GIS Cut Line= 3
      1969024.99     13497774.99      1968425.00     13497175.00
      1967424.98     13495974.98
#Sta/Elev= 30
  4172.8  579.22  4229.4  576.30  4300.1  570.17  4370.8  566.56  4568.8  560.06
  4795.0  555.62  4875.8  552.55  4922.3  550.30  5000.2  548.06  5000.7  547.56
  5013.7  547.56  5014.2  548.06  5057.1  549.34  5301.3  552.85  5702.8  555.60
  5892.8  556.15  5965.7  557.53  6088.6  557.98  6235.2  560.16  6341.9  563.67
  6356.2  565.47  6405.7  565.35  6434.3  566.63  6440.8  566.06  6450.7  566.54
  6455.2  566.25  6547.6  571.00  6569.7  570.58  6576.2  571.15  6583.4  570.51
#Mann=8,-1,0
  4172.8    0.05       0  4875.8     0.1       0  5000.2    0.07       0
  5014.2     0.1       0  5301.3    0.05       0  5892.8     0.1       0
  6088.6    0.05       0  6450.7     0.1       0
Bank Sta=5000.2,5014.2
Exp/Cntr=0.3,0.1

Type RM Length L Ch R = 1,32702,447,447,447
BEGIN DESCRIPTION:
UNT 004 in BCW 50.0
END DESCRIPTION:
XS GIS Cut Line= 3
      1969325.01     13497625.01      1968825.00     13497075.00
      1967625.00     13495975.00
#Sta/Elev= 30
  4250.9  591.86  4279.0  587.83  4286.4  588.18  4293.1  586.17  4307.3  584.30
  4357.3  581.07  4413.4  571.32  4515.8  564.60  4689.8  556.49  4753.3  555.55
  4909.4  549.91  4944.5  550.18  4972.9  548.61  4983.8  546.83  4984.3  546.33
  4997.8  546.83  5017.5  547.16  5680.8  554.24  6181.9  557.87  6402.9  559.52
  6529.9  563.49  6553.0  565.86  6558.3  565.45  6565.7  566.91  6572.5  566.22
  6579.9  567.85  6586.6  567.32  6594.0  568.56  6600.8  567.75  6622.1  568.66
#Mann=7,-1,0
  4250.9     0.1       0  4515.8    0.05       0  4983.8    0.03       0
  4997.8    0.05       0  5017.5     0.1       0  6181.9    0.05       0
  6553.0     0.1       0
Bank Sta=4983.8,4997.8
Exp/Cntr=0.3,0.1

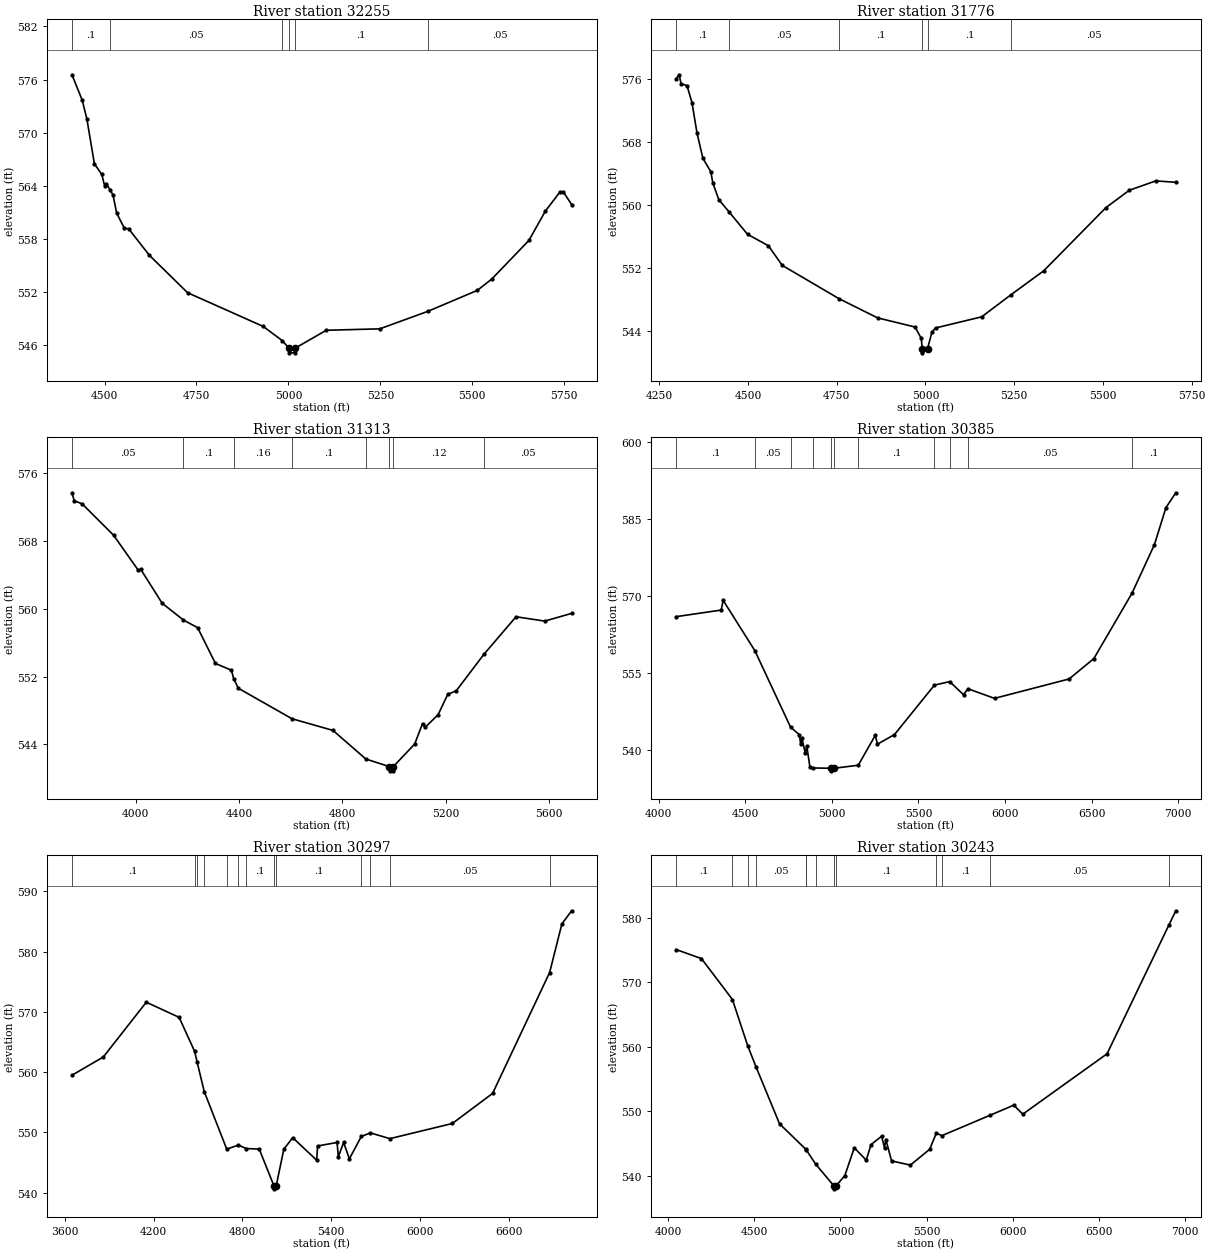
Type RM Length L Ch R = 1,32255,479,479,479
BEGIN DESCRIPTION:
UNT 004 in BCW 49.0
END DESCRIPTION:
XS GIS Cut Line= 3
      1969325.01     13497475.03      1969225.00     13496875.00
      1969019.77     13496153.32
#Sta/Elev= 30
  4411.5  576.54  4439.4  573.67  4452.1  571.54  4472.4  566.50  4492.6  565.28
  4500.2  564.02  4505.3  564.25  4515.8  563.48  4523.0  562.98  4533.2  560.90
  4553.5  559.25  4566.1  559.12  4621.9  556.16  4725.8  551.93  4931.1  548.13
  4983.3  546.52  5002.2  545.64  5002.7  545.14  5016.6  545.14  5017.1  545.64
  5103.0  547.69  5248.5  547.85  5378.7  549.82  5513.5  552.19  5552.6  553.46
  5654.0  557.84  5698.5  561.14  5737.5  563.26  5747.6  563.30  5770.1  561.89
#Mann=6,-1,0
  4411.5     0.1       0  4515.8    0.05       0  4983.3     0.1       0
  5002.2    0.07       0  5017.1     0.1       0  5378.7    0.05       0
Bank Sta=5002.2,5017.1
Exp/Cntr=0.3,0.1

Type RM Length L Ch R = 1,31776,463,463,463
BEGIN DESCRIPTION:
UNT 004 in BCW 48.0
END DESCRIPTION:
XS GIS Cut Line= 3
      1969375.01     13497474.97      1969675.00     13496875.00
      1969644.63     13496138.52
#Sta/Elev= 30
  4297.5  576.07  4305.9  576.59  4311.4  575.47  4328.2  575.20  4342.2  573.05
  4356.2  569.21  4372.9  565.98  4395.3  564.26  4400.9  562.83  4417.7  560.72
  4445.9  559.20  4498.7  556.31  4557.4  554.86  4596.5  552.36  4755.8  548.14
  4864.9  545.69  4970.8  544.52  4988.3  543.07  4990.9  541.74  4991.4  541.24
  5005.8  541.74  5018.3  543.90  5028.3  544.40  5158.5  545.82  5241.4  548.64
  5333.0  551.66  5508.7  559.71  5574.4  561.91  5648.9  563.10  5705.4  562.92
#Mann=6,-1,0
  4297.5     0.1       0  4445.9    0.05       0  4755.8     0.1       0
  4990.9    0.07       0  5005.8     0.1       0  5241.4    0.05       0
Bank Sta=4990.9,5005.8
Exp/Cntr=0.3,0.1

Type RM Length L Ch R = 1,31313,928,928,928
BEGIN DESCRIPTION:
UNT 004 in BCW 47.0
END DESCRIPTION:
XS GIS Cut Line= 3
      1969819.05     13498063.16      1970125.00     13496875.00
      1970048.21     13496170.79
#Sta/Elev= 30
  3752.5  573.69  3761.2  572.75  3791.6  572.39  3913.7  568.68  4008.8  564.57
  4019.1  564.65  4101.7  560.66  4184.0  558.68  4239.3  557.77  4308.2  553.55
  4370.2  552.75  4378.6  551.77  4397.0  550.62  4604.5  547.03  4763.3  545.65
  4891.0  542.27  4982.0  541.38  4982.5  540.88  4996.5  540.88  4997.0  541.38
  5080.0  544.05  5110.2  546.46  5121.5  546.05  5170.5  547.50  5207.9  549.90
  5241.0  550.33  5347.4  554.61  5472.3  559.06  5583.5  558.55  5687.8  559.46
#Mann=8,-1,0
  3752.5    0.05       0  4184.0     0.1       0  4378.6    0.16       0
  4604.5     0.1       0  4891.0    0.12       0  4982.0    0.07       0
  4997.0    0.12       0  5347.4    0.05       0
Bank Sta=4982,4997
Exp/Cntr=0.3,0.1

Type RM Length L Ch R = 1,30385,88,88,88
BEGIN DESCRIPTION:
Mapping XS 92b32f0c
END DESCRIPTION:
XS GIS Cut Line= 6
      1970825.99     13497534.56      1970882.41     13497100.52
      1971034.32     13496709.89      1970999.60     13496631.77
      1970665.40     13496649.13      1969953.61     13495221.21
#Sta/Elev= 30
  4100.5  566.02  4360.8  567.30  4372.3  569.19  4555.2  559.39  4761.7  544.46
  4812.7  542.99  4819.7  541.11  4826.8  542.35  4846.8  539.36  4854.9  540.85
  4872.8  536.78  4892.1  536.52  4996.8  536.46  4997.3  535.96  5012.2  536.46
  5152.4  537.05  5251.0  542.89  5263.2  541.15  5361.5  543.03  5592.6  552.68
  5680.4  553.35  5760.4  550.81  5786.3  551.96  5939.4  550.09  6370.2  553.87
  6513.1  557.84  6733.8  570.61  6862.6  580.03  6929.8  587.29  6986.6  590.17
#Mann=11,-1,0
  4100.5     0.1       0  4555.2    0.05       0  4761.7     0.1       0
  4892.1    0.05       0  4996.8   0.033       0  5012.2    0.05       0
  5152.4     0.1       0  5592.6    0.05       0  5680.4     0.1       0
  5786.3    0.05       0  6733.8     0.1       0
Bank Sta=4996.8,5012.2
Exp/Cntr=0.3,0.1

Type RM Length L Ch R = 1,30297,54,54,54
BEGIN DESCRIPTION:
Mapping XS a7c0a74e
END DESCRIPTION:
XS GIS Cut Line= 6
      1970780.86     13497912.12      1971010.02     13496886.11
      1971119.39     13496709.02      1971056.89     13496552.77
      1970702.72     13496599.65      1970062.09     13495162.12
#Sta/Elev= 30
  3647.5  559.48  3859.7  562.51  4150.0  571.60  4372.0  569.09  4476.8  563.44
  4493.4  561.71  4541.9  556.76  4694.1  547.21  4772.4  547.88  4826.1  547.31
  4913.8  547.22  5013.0  541.12  5013.5  540.62  5028.4  541.12  5080.0  547.20
  5140.0  549.11  5302.5  545.37  5307.9  547.73  5440.0  548.32  5448.7  545.94
  5484.2  548.32  5523.2  545.60  5604.1  549.32  5665.7  549.91  5796.9  548.95
  6219.5  551.47  6491.5  556.46  6877.3  576.53  6960.2  584.61  7026.2  586.78
#Mann=13,-1,0
  3647.5     0.1       0  4476.8    0.05       0  4493.4     0.1       0
  4541.9    0.05       0  4694.1     0.1       0  4772.4    0.05       0
  4826.1     0.1       0  5013.0    0.07       0  5028.4     0.1       0
  5604.1    0.05       0  5665.7     0.1       0  5796.9    0.05       0
  6877.3     0.1       0
Bank Sta=5013,5028.4
Exp/Cntr=0.3,0.1

Type RM Length L Ch R = 1,30243,138,138,138
BEGIN DESCRIPTION:
Mapping XS c52bd68a
END DESCRIPTION:
XS GIS Cut Line= 6
      1970969.21     13497499.84      1971051.68     13496939.93
      1971151.51     13496683.85      1971060.36     13496466.84
      1970769.56     13496544.96      1970131.52     13495195.09
#Sta/Elev= 30
  4046.4  575.06  4193.5  573.66  4373.0  567.32  4462.1  560.13  4510.4  556.85
  4646.3  548.06  4799.9  544.08  4800.6  544.05  4855.9  541.81  4960.5  538.48
  4961.0  537.98  4975.9  538.48  5025.1  540.03  5080.1  544.34  5149.4  542.42
  5177.1  544.83  5238.4  546.13  5255.6  544.36  5263.3  545.62  5296.3  542.31
  5405.6  541.66  5517.5  544.11  5556.3  546.62  5588.3  546.22  5869.4  549.40
  6005.5  550.95  6057.6  549.55  6546.7  558.91  6906.6  578.93  6945.6  581.07
#Mann=13,-1,0
  4046.4     0.1       0  4373.0    0.05       0  4462.1     0.1       0
  4510.4    0.05       0  4799.9     0.1       0  4800.6    0.05       0
  4855.9     0.1       0  4960.5    0.07       0  4975.9     0.1       0
  5556.3    0.05       0  5588.3     0.1       0  5869.4    0.05       0
  6906.6     0.1       0
Bank Sta=4960.5,4975.9
Exp/Cntr=0.3,0.1