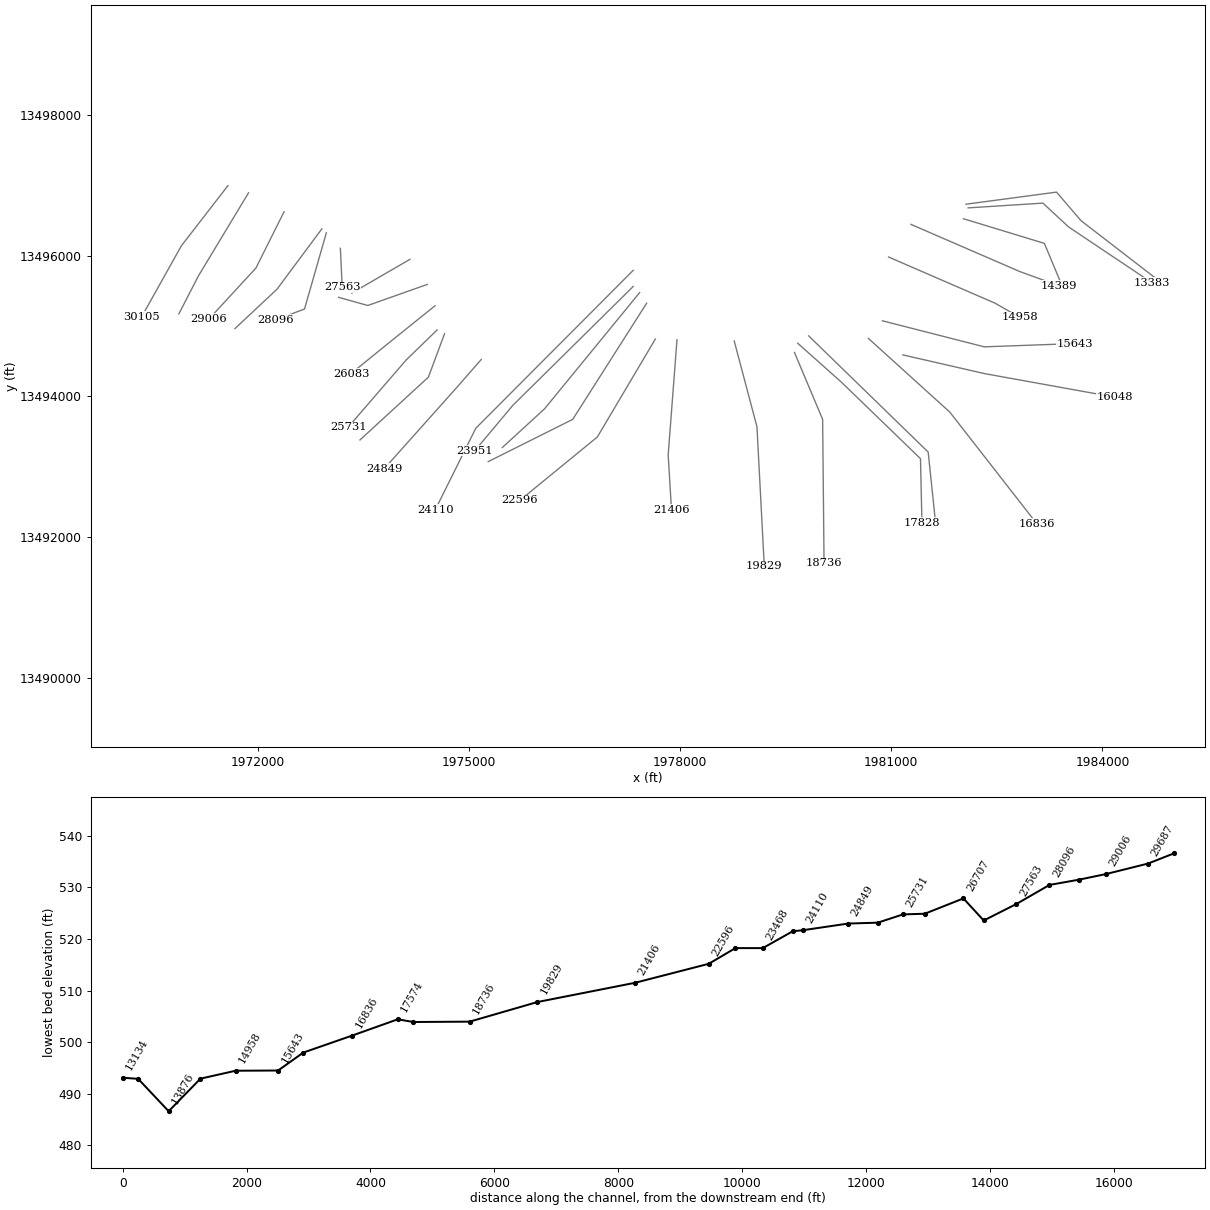
HEC-RAS study UNT 004 in BCW.prj: UNT 004 in BCW Base Level Engineering

--- UNT 004 in BCW.g01 (geometry) --- (continued)

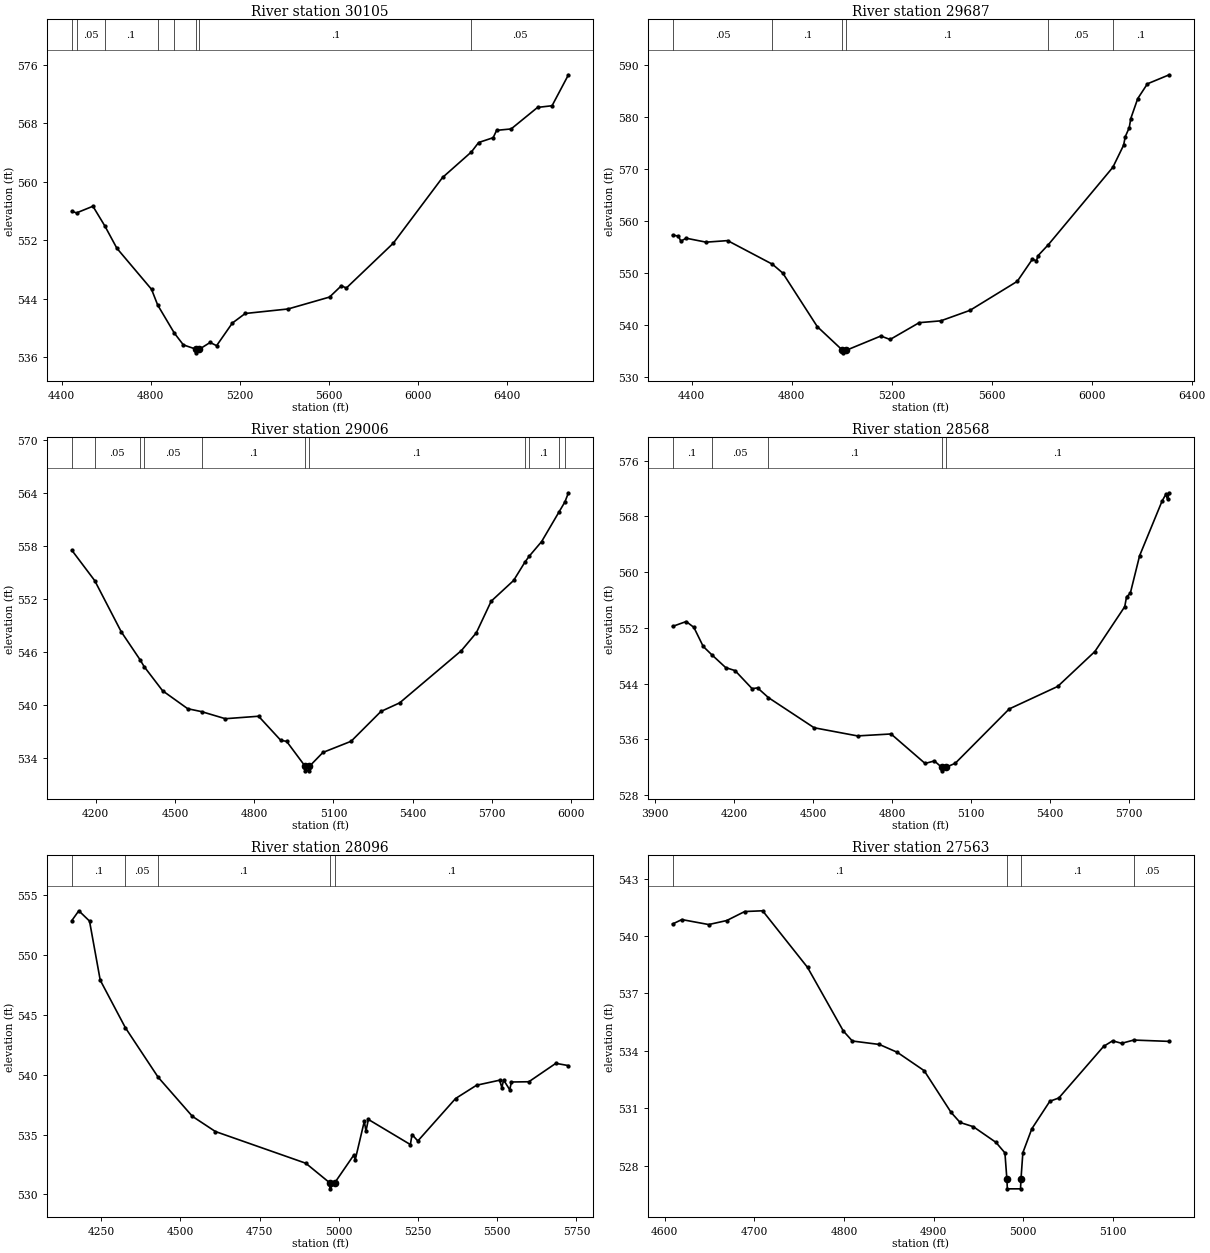
Type RM Length L Ch R = 1,30105,418,418,418
BEGIN DESCRIPTION:
Mapping XS 4e8478f7
END DESCRIPTION:
XS GIS Cut Line= 3
      1971577.75     13496995.51      1970916.27     13496141.32
      1970353.75     13495136.07
#Sta/Elev= 30
  4445.5  555.97  4466.6  555.75  4540.4  556.66  4593.6  553.98  4648.2  550.90
  4803.9  545.28  4831.6  543.12  4906.4  539.28  4946.9  537.67  5003.5  537.08
  5004.0  536.58  5018.9  537.08  5067.3  538.00  5096.3  537.56  5167.1  540.66
  5224.9  541.97  5417.7  542.59  5603.9  544.22  5657.5  545.78  5679.2  545.45
  5890.5  551.60  6111.9  560.60  6241.6  564.10  6274.1  565.39  6339.2  566.05
  6355.1  567.06  6420.2  567.25  6539.0  570.20  6604.1  570.43  6677.8  574.67
#Mann=8,-1,0
  4445.5     0.1       0  4466.6    0.05       0  4593.6     0.1       0
  4831.6    0.05       0  4906.4     0.1       0  5003.5    0.07       0
  5018.9     0.1       0  6241.6    0.05       0
Bank Sta=5003.5,5018.9
Exp/Cntr=0.3,0.1

Type RM Length L Ch R = 1,29687,681,681,681
BEGIN DESCRIPTION:
Mapping XS 87e8294d
END DESCRIPTION:
XS GIS Cut Line= 3
      1971869.91     13496893.39      1971155.85     13495709.02
      1970879.89     13495172.72
#Sta/Elev= 30
  4324.0  557.29  4347.2  557.08  4356.9  556.12  4378.3  556.68  4457.9  555.92
  4544.0  556.22  4723.2  551.67  4764.6  549.97  4902.5  539.66  5003.4  535.11
  5003.9  534.61  5018.8  535.11  5156.8  537.85  5193.7  537.18  5310.2  540.42
  5396.4  540.77  5513.2  542.79  5702.4  548.38  5762.8  552.64  5779.0  552.33
  5785.0  553.30  5827.2  555.47  6084.6  570.34  6127.6  574.59  6134.1  576.22
  6150.1  577.96  6156.3  579.73  6184.1  583.57  6222.8  586.41  6310.1  588.15
#Mann=6,-1,0
  4324.0    0.05       0  4723.2     0.1       0  5003.4    0.07       0
  5018.8     0.1       0  5827.2    0.05       0  6084.6     0.1       0
Bank Sta=5003.4,5018.8
Exp/Cntr=0.3,0.1

Type RM Length L Ch R = 1,29006,438,438,438
BEGIN DESCRIPTION:
UNT 004 in BCW 42.0
END DESCRIPTION:
XS GIS Cut Line= 3
      1972374.98     13496624.96      1971975.00     13495825.00
      1971307.05     13495099.82
#Sta/Elev= 30
  4109.6  557.50  4196.4  554.06  4296.8  548.28  4367.8  545.13  4383.4  544.35
  4453.3  541.62  4548.4  539.59  4600.9  539.26  4690.9  538.46  4816.7  538.74
  4900.6  536.02  4922.9  535.90  4993.4  533.07  4993.9  532.57  5008.4  532.57
  5008.9  533.07  5060.4  534.65  5167.0  535.91  5279.9  539.28  5350.8  540.25
  5584.4  546.15  5641.1  548.17  5697.4  551.74  5782.3  554.08  5824.6  556.13
  5840.7  556.80  5888.4  558.48  5954.3  561.83  5976.4  562.95  5989.9  563.99
#Mann=11,-1,0
  4109.6     0.1       0  4196.4    0.05       0  4367.8     0.1       0
  4383.4    0.05       0  4600.9     0.1       0  4993.4    0.07       0
  5008.9     0.1       0  5824.6    0.05       0  5840.7     0.1       0
  5954.3    0.05       0  5976.4     0.1       0
Bank Sta=4993.4,5008.9
Exp/Cntr=0.3,0.1

Type RM Length L Ch R = 1,28568,472,472,472
BEGIN DESCRIPTION:
UNT 004 in BCW 41.0
END DESCRIPTION:
XS GIS Cut Line= 3
      1972911.08     13496380.93      1972275.00     13495525.00
      1971676.71     13494964.25
#Sta/Elev= 30
  3966.0  552.20  4017.6  552.90  4046.8  552.06  4082.2  549.33  4114.1  548.16
  4167.7  546.29  4203.2  545.86  4267.9  543.27  4288.7  543.38  4330.1  541.98
  4503.6  537.66  4668.4  536.49  4795.7  536.77  4925.0  532.54  4960.4  532.90
  4988.1  531.98  4988.6  531.48  5003.7  531.98  5039.5  532.56  5244.6  540.36
  5428.8  543.59  5570.0  548.60  5683.3  555.03  5690.3  556.45  5704.3  556.93
  5739.9  562.35  5824.9  570.16  5839.1  571.13  5845.9  570.44  5852.4  571.37
#Mann=5,-1,0
  3966.0     0.1       0  4114.1    0.05       0  4330.1     0.1       0
  4988.1    0.07       0  5003.7     0.1       0
Bank Sta=4988.1,5003.7
Exp/Cntr=0.3,0.1

Type RM Length L Ch R = 1,28096,533,533,533
BEGIN DESCRIPTION:
UNT 004 in BCW 40.0
END DESCRIPTION:
XS GIS Cut Line= 3
      1972975.01     13496325.05      1972664.96     13495242.56
      1972251.73     13495086.30
#Sta/Elev= 30
  4156.9  552.89  4179.0  553.71  4212.8  552.85  4246.6  547.91  4325.9  543.94
  4429.4  539.80  4537.5  536.53  4610.2  535.26  4895.5  532.61  4971.2  530.97
  4971.7  530.47  4986.8  530.97  5046.5  533.27  5051.7  532.91  5080.3  536.12
  5085.5  535.30  5093.1  536.27  5225.7  534.17  5230.9  535.01  5249.2  534.47
  5368.4  538.02  5434.7  539.13  5507.4  539.55  5514.5  538.93  5519.9  539.57
  5539.4  538.75  5544.7  539.40  5599.7  539.42  5684.9  540.96  5724.7  540.77
#Mann=5,-1,0
  4156.9     0.1       0  4325.9    0.05       0  4429.4     0.1       0
  4971.2    0.07       0  4986.8     0.1       0
Bank Sta=4971.2,4986.8
Exp/Cntr=0.3,0.1

Type RM Length L Ch R = 1,27563,528,528,528
BEGIN DESCRIPTION:
Mapping XS 43a1cd3c
END DESCRIPTION:
XS GIS Cut Line= 2
      1973174.25     13496105.31      1973200.29     13495551.92
#Sta/Elev= 30
  4608.8  540.63  4619.1  540.86  4649.1  540.60  4669.2  540.81  4689.2  541.28
  4709.2  541.32  4759.3  538.36  4799.3  535.03  4809.3  534.51  4839.4  534.33
  4859.4  533.92  4889.4  532.96  4919.4  530.78  4929.5  530.25  4944.2  530.03
  4969.5  529.21  4979.5  528.66  4981.7  527.28  4982.2  526.78  4996.9  526.78
  4997.4  527.28  4999.5  528.67  5009.5  529.92  5029.6  531.36  5039.6  531.53
  5089.6  534.23  5099.6  534.52  5109.7  534.39  5123.2  534.56  5162.8  534.49
#Mann=4,-1,0
  4608.8     0.1       0  4981.7    0.07       0  4997.4     0.1       0
  5123.2    0.05       0
Bank Sta=4981.7,4997.4
Exp/Cntr=0.3,0.1

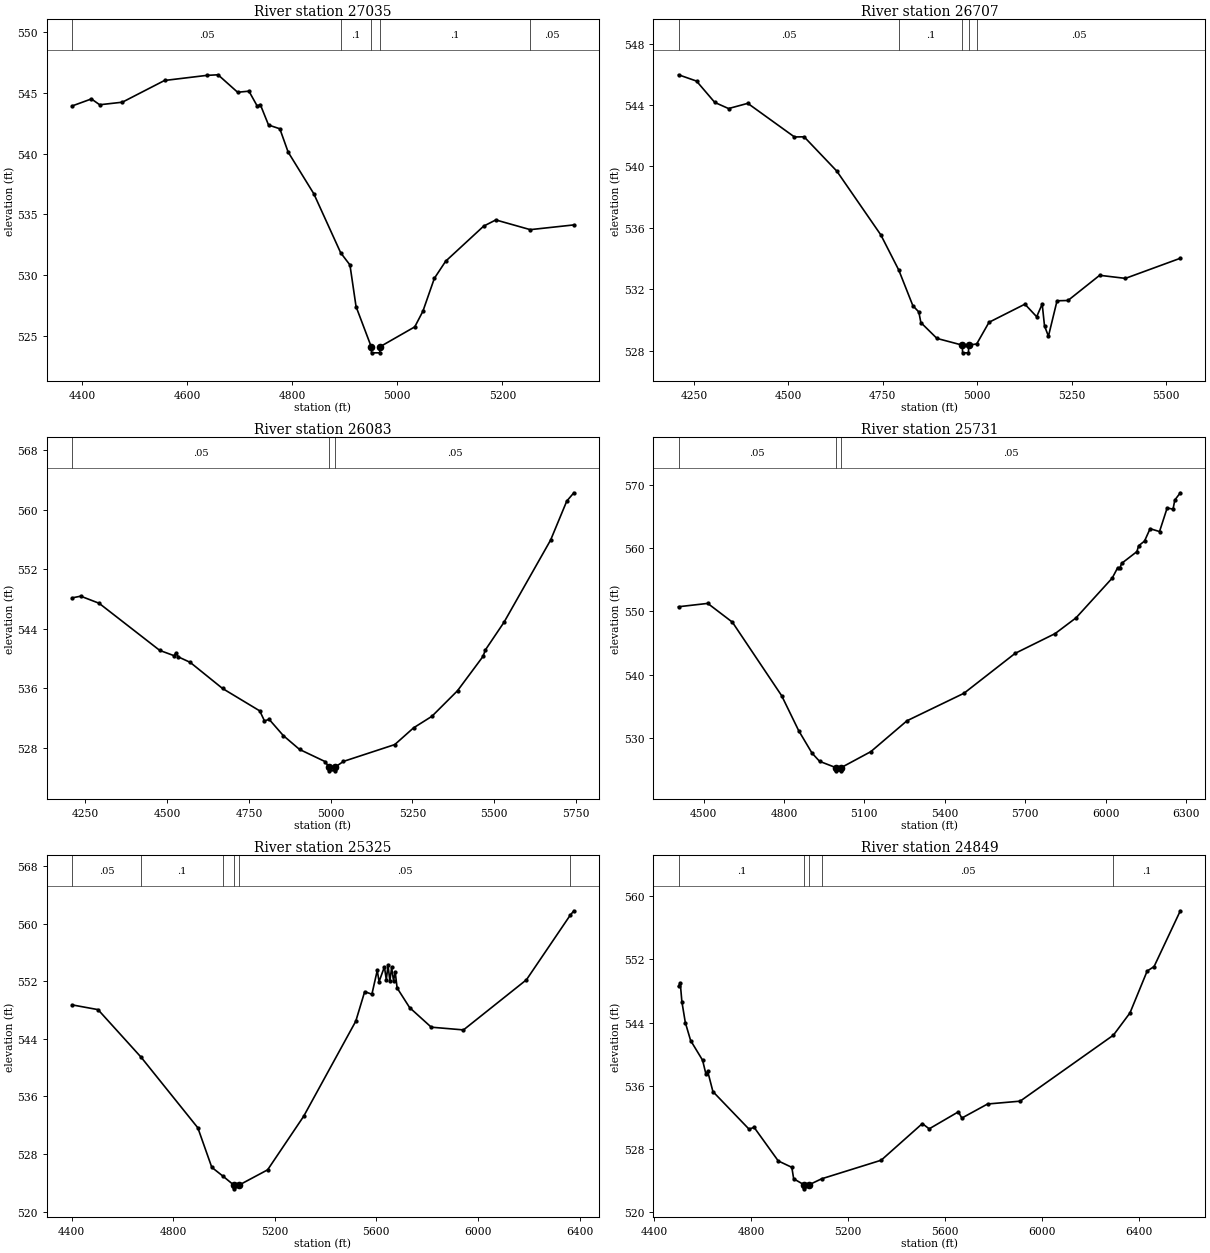
Type RM Length L Ch R = 1,27035,328,328,328
BEGIN DESCRIPTION:
UNT 004 in BCW 39.0
END DESCRIPTION:
XS GIS Cut Line= 2
      1974162.42     13495948.07      1973336.56     13495469.11
#Sta/Elev= 30
  4381.4  543.92  4418.2  544.50  4433.9  544.02  4477.0  544.23  4557.3  546.02
  4637.6  546.44  4659.1  546.49  4696.4  545.05  4717.9  545.14  4733.7  543.91
  4739.5  544.04  4755.2  542.35  4776.7  542.04  4792.5  540.12  4841.3  536.69
  4892.5  531.82  4910.1  530.82  4921.7  527.39  4950.6  524.08  4951.1  523.58
  4966.7  523.58  4967.2  524.08  5033.4  525.72  5048.9  527.01  5070.7  529.72
  5092.2  531.13  5164.5  534.02  5187.6  534.53  5253.1  533.73  5336.1  534.12
#Mann=5,-1,0
  4381.4    0.05       0  4892.5     0.1       0  4950.6    0.07       0
  4967.2     0.1       0  5253.1    0.05       0
Bank Sta=4950.6,4967.2
Exp/Cntr=0.3,0.1

Type RM Length L Ch R = 1,26707,624,624,624
BEGIN DESCRIPTION:
UNT 004 in BCW 38.0
END DESCRIPTION:
XS GIS Cut Line= 3
      1974409.88     13495592.20      1973563.49     13495292.70
      1973148.77     13495408.90
#Sta/Elev= 30
  4209.1  545.97  4256.7  545.56  4305.0  544.17  4341.6  543.77  4392.4  544.11
  4516.0  541.92  4541.6  541.93  4628.0  539.70  4744.7  535.54  4792.2  533.25
  4829.5  530.93  4845.3  530.52  4850.7  529.83  4893.2  528.80  4960.6  528.36
  4961.1  527.86  4976.7  527.86  4977.2  528.36  4998.5  528.44  5031.1  529.85
  5126.1  531.03  5157.3  530.21  5171.9  531.04  5178.0  529.62  5188.4  528.94
  5211.2  531.25  5240.2  531.27  5324.0  532.91  5392.2  532.71  5537.6  534.02
#Mann=5,-1,0
  4209.1    0.05       0  4792.2     0.1       0  4960.6   0.035       0
  4977.2     0.1       0  4998.5    0.05       0
Bank Sta=4960.6,4977.2
Exp/Cntr=0.3,0.1

Type RM Length L Ch R = 1,26083,352,352,352
BEGIN DESCRIPTION:
UNT 004 in BCW 37.0
END DESCRIPTION:
XS GIS Cut Line= 3
      1974518.36     13495288.37      1973854.29     13494754.51
      1973324.99     13494324.99
#Sta/Elev= 30
  4209.5  548.14  4235.9  548.37  4292.0  547.42  4477.5  541.08  4520.7  540.38
  4527.1  540.72  4534.6  540.20  4570.3  539.48  4669.5  535.96  4783.1  532.95
  4797.5  531.61  4811.9  531.81  4855.1  529.63  4904.7  527.77  4983.1  526.13
  4994.5  525.39  4995.0  524.89  5012.8  524.89  5013.3  525.39  5039.1  526.16
  5195.8  528.42  5253.3  530.67  5309.3  532.22  5387.6  535.66  5465.5  540.27
  5472.7  541.14  5529.8  544.87  5672.1  555.91  5721.6  561.16  5743.2  562.27
#Mann=3,-1,0
  4209.5    0.05       0  4994.5   0.035       0  5013.3    0.05       0
Bank Sta=4994.5,5013.3
Exp/Cntr=0.3,0.1

Type RM Length L Ch R = 1,25731,406,406,406
BEGIN DESCRIPTION:
UNT 004 in BCW 36.0
END DESCRIPTION:
XS GIS Cut Line= 3
      1974548.70     13494945.45      1974110.36     13494520.13
      1973285.73     13493565.30
#Sta/Elev= 30
  4406.8  550.75  4515.8  551.28  4607.7  548.31  4791.6  536.66  4855.3  531.11
  4904.7  527.58  4933.0  526.27  4994.4  525.26  4994.9  524.76  5012.7  524.76
  5013.2  525.26  5124.3  527.80  5259.2  532.69  5472.0  537.05  5662.9  543.37
  5812.1  546.50  5890.0  548.99  6024.9  555.28  6045.8  556.96  6053.4  556.83
  6060.0  557.61  6117.1  559.48  6123.7  560.41  6145.6  561.15  6166.4  563.11
  6201.6  562.66  6230.1  566.40  6252.0  566.20  6258.6  567.65  6279.2  568.80
#Mann=3,-1,0
  4406.8    0.05       0  4994.4   0.035       0  5013.2    0.05       0
Bank Sta=4994.4,5013.2
Exp/Cntr=0.3,0.1

Type RM Length L Ch R = 1,25325,476,476,476
BEGIN DESCRIPTION:
UNT 004 in BCW 35.0
END DESCRIPTION:
XS GIS Cut Line= 3
      1974653.76     13494890.78      1974425.00     13494275.00
      1973453.24     13493382.97
#Sta/Elev= 30
  4401.7  548.73  4503.9  548.07  4673.7  541.45  4897.0  531.64  4951.9  526.15
  4997.4  524.88  5039.4  523.66  5039.9  523.16  5058.2  523.66  5171.7  525.80
  5313.6  533.24  5518.9  546.46  5554.0  550.57  5582.4  550.21  5603.4  553.51
  5610.7  551.97  5631.7  554.01  5639.1  552.23  5645.9  554.24  5653.3  552.04
  5660.1  553.94  5667.5  552.10  5674.3  553.26  5681.7  551.08  5731.0  548.35
  5816.1  545.63  5943.1  545.25  6191.0  552.22  6362.9  561.17  6377.7  561.81
#Mann=6,-1,0
  4401.7    0.05       0  4673.7     0.1       0  4997.4    0.05       0
  5039.4   0.035       0  5058.2    0.05       0  6362.9     0.1       0
Bank Sta=5039.4,5058.2
Exp/Cntr=0.3,0.1

Type RM Length L Ch R = 1,24849,739,739,739
BEGIN DESCRIPTION:
UNT 004 in BCW 34.0
END DESCRIPTION:
XS GIS Cut Line= 3
      1975175.01     13494525.02      1974825.00     13494125.00
      1973799.80     13492976.95
#Sta/Elev= 30
  4500.6  548.61  4507.7  549.03  4514.4  546.66  4528.6  544.02  4550.5  541.75
  4599.8  539.26  4614.0  537.46  4620.7  537.88  4642.5  535.29  4791.5  530.54
  4812.4  530.77  4912.1  526.52  4968.1  525.71  4975.7  524.26  5019.4  523.49
  5019.9  522.99  5038.3  523.49  5091.1  524.26  5336.8  526.61  5506.6  531.24
  5535.0  530.58  5655.4  532.73  5669.6  531.94  5775.8  533.72  5910.3  534.08
  6295.2  542.43  6363.5  545.24  6434.5  550.54  6462.9  551.10  6571.3  558.16
#Mann=5,-1,0
  4500.6     0.1       0  5019.4    0.07       0  5038.3     0.1       0
  5091.1    0.05       0  6295.2     0.1       0
Bank Sta=5019.4,5038.3
Exp/Cntr=0.3,0.1

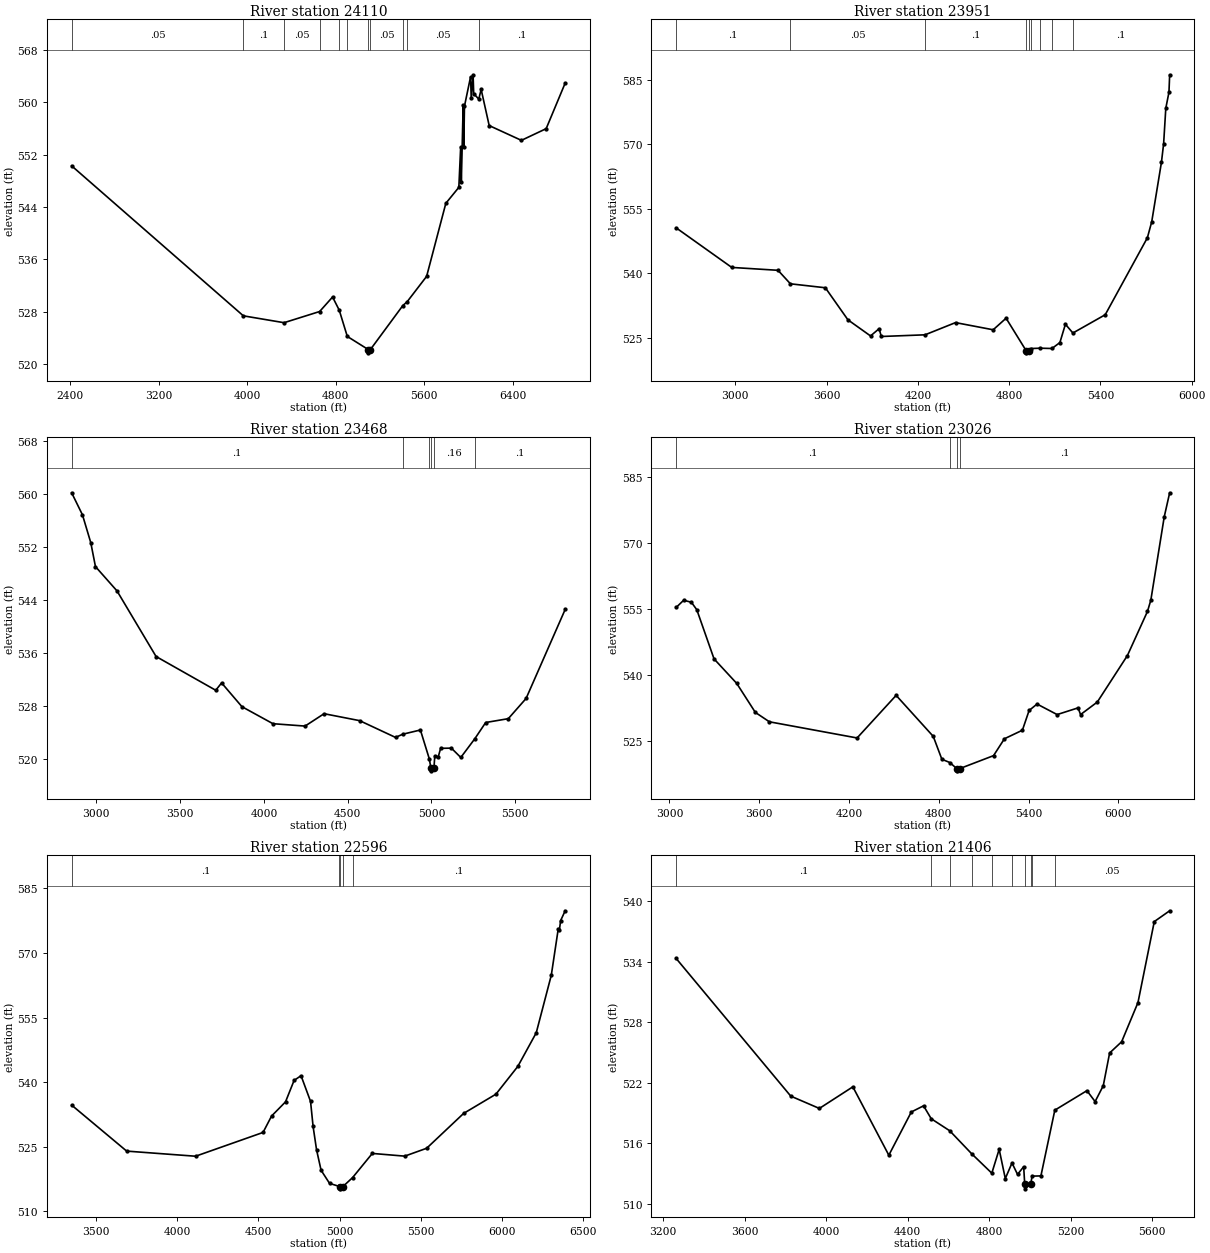
Type RM Length L Ch R = 1,24110,159,159,159
BEGIN DESCRIPTION:
UNT 004 in BCW 33.0
END DESCRIPTION:
XS GIS Cut Line= 3
      1977334.15     13495792.01      1975098.06     13493548.98
      1974521.84     13492389.60
#Sta/Elev= 30
  2411.4  550.29  3963.7  527.35  4331.6  526.30  4653.4  528.01  4770.4  530.23
  4830.8  528.21  4903.5  524.20  5093.3  522.19  5093.8  521.69  5112.2  522.19
  5405.9  528.93  5443.5  529.48  5620.7  533.39  5794.3  544.56  5911.9  547.00
  5928.7  553.22  5934.3  547.79  5951.1  559.56  5956.7  553.23  5962.7  559.41
  6018.3  563.93  6023.9  560.62  6040.7  564.22  6046.3  561.32  6092.4  560.50
  6113.5  561.99  6186.3  556.45  6477.5  554.19  6701.5  555.98  6873.3  562.95
#Mann=11,-1,0
  2411.4    0.05       0  3963.7     0.1       0  4331.6    0.05       0
  4653.4     0.1       0  4830.8    0.08       0  4903.5    0.05       0
  5093.3    0.04       0  5112.2    0.05       0  5405.9    0.08       0
  5443.5    0.05       0  6092.4     0.1       0
Bank Sta=5093.3,5112.2
Exp/Cntr=0.3,0.1

Type RM Length L Ch R = 1,23951,483,483,483
BEGIN DESCRIPTION:
UNT 004 in BCW 32.0
END DESCRIPTION:
XS GIS Cut Line= 3
      1977334.14     13495562.84      1975625.00     13493875.00
      1975084.34     13493229.74
#Sta/Elev= 30
  2611.5  550.55  2977.0  541.35  3281.1  540.68  3362.6  537.54  3592.3  536.62
  3740.8  529.16  3889.2  525.42  3945.8  527.11  3959.9  525.29  4247.4  525.68
  4447.9  528.52  4695.4  526.85  4780.2  529.54  4912.1  521.99  4912.6  521.49
  4931.1  521.99  4941.6  522.49  5004.3  522.57  5081.8  522.50  5133.9  523.88
  5170.1  528.14  5219.4  526.10  5431.9  530.35  5709.0  548.25  5737.6  551.99
  5801.4  565.80  5815.7  570.09  5830.0  578.35  5850.8  582.08  5855.4  586.14
#Mann=9,-1,0
  2611.5     0.1       0  3362.6    0.05       0  4247.4     0.1       0
  4912.1    0.04       0  4931.1     0.1       0  4941.6    0.05       0
  5004.3    0.16       0  5081.8    0.05       0  5219.4     0.1       0
Bank Sta=4912.1,4931.1
Exp/Cntr=0.3,0.1

Type RM Length L Ch R = 1,23468,442,442,442
BEGIN DESCRIPTION:
UNT 004 in BCW 31.0
END DESCRIPTION:
XS GIS Cut Line= 3
      1977425.01     13495475.01      1976075.00     13493825.00
      1975474.97     13493274.97
#Sta/Elev= 30
  2852.6  560.23  2917.2  556.89  2966.7  552.70  2994.7  549.08  3123.2  545.41
  3356.5  535.50  3712.6  530.40  3747.7  531.51  3869.0  527.92  4054.2  525.35
  4245.9  524.99  4359.3  526.86  4571.8  525.81  4785.7  523.28  4828.8  523.76
  4934.3  524.40  4987.6  520.03  4996.3  518.73  4996.8  518.23  5015.3  518.73
  5020.0  520.40  5040.9  520.35  5055.1  521.63  5119.2  521.66  5175.4  520.25
  5259.2  523.08  5324.0  525.53  5459.0  526.11  5565.1  529.16  5798.5  542.61
#Mann=6,-1,0
  2852.6     0.1       0  4828.8    0.07       0  4987.6    0.16       0
  4996.3    0.07       0  5015.3    0.16       0  5259.2     0.1       0
Bank Sta=4996.3,5015.3
Exp/Cntr=0.3,0.1

Type RM Length L Ch R = 1,23026,430,430,430
BEGIN DESCRIPTION:
UNT 004 in BCW 30.0
END DESCRIPTION:
XS GIS Cut Line= 3
      1977525.01     13495325.01      1976475.00     13493675.00
      1975275.01     13493075.01
#Sta/Elev= 30
  3044.7  555.31  3094.7  556.94  3146.3  556.50  3182.7  554.80  3297.9  543.64
  3449.4  538.08  3573.9  531.49  3667.8  529.36  4253.7  525.69  4514.5  535.36
  4762.6  526.05  4820.1  520.86  4873.6  520.11  4919.7  518.73  4920.2  518.23
  4939.0  518.73  5165.4  521.68  5238.1  525.51  5358.2  527.45  5403.0  531.93
  5456.1  533.39  5590.2  531.00  5730.0  532.52  5746.8  531.00  5858.6  533.84
  6059.8  544.40  6194.0  554.43  6216.3  556.97  6305.8  575.87  6342.1  581.34
#Mann=4,-1,0
  3044.7     0.1       0  4873.6    0.12       0  4919.7    0.07       0
  4939.0     0.1       0
Bank Sta=4919.7,4939
Exp/Cntr=0.3,0.1

Type RM Length L Ch R = 1,22596,1190,1190,1190
BEGIN DESCRIPTION:
UNT 004 in BCW 29.0
END DESCRIPTION:
XS GIS Cut Line= 3
      1977648.73     13494816.44      1976825.00     13493425.00
      1975724.96     13492524.97
#Sta/Elev= 30
  3350.7  534.65  3689.4  523.96  4113.7  522.77  4529.0  528.30  4581.6  532.12
  4667.4  535.41  4720.1  540.39  4762.9  541.49  4821.4  535.51  4837.1  529.69
  4858.5  524.24  4886.3  519.51  4938.4  516.46  4998.4  515.75  5000.4  515.69
  5000.9  515.19  5019.7  515.69  5079.9  517.79  5201.7  523.42  5401.2  522.79
  5536.2  524.62  5763.7  532.72  5962.6  537.19  6097.5  543.65  6210.9  551.46
  6303.5  564.83  6346.6  575.67  6353.1  575.26  6361.0  577.54  6389.0  579.82
#Mann=5,-1,0
  3350.7     0.1       0  4998.4    0.16       0  5000.4    0.07       0
  5019.7    0.16       0  5079.9     0.1       0
Bank Sta=5000.4,5019.7
Exp/Cntr=0.3,0.1

Type RM Length L Ch R = 1,21406,1577,1577,1577
BEGIN DESCRIPTION:
UNT 004 in BCW 28.0
END DESCRIPTION:
XS GIS Cut Line= 3
      1977956.02     13494805.99      1977831.02     13493170.61
      1977877.88     13492389.67
#Sta/Elev= 30
  3263.6  534.32  3826.2  520.69  3966.6  519.47  4131.0  521.61  4307.6  514.84
  4418.0  519.12  4478.1  519.73  4515.7  518.45  4606.5  517.26  4713.9  514.99
  4813.1  513.06  4849.2  515.42  4879.3  512.53  4912.2  514.07  4939.4  512.94
  4969.5  513.70  4974.5  512.01  4975.0  511.51  5004.5  512.01  5010.8  512.77
  5054.1  512.79  5122.4  519.30  5280.0  521.23  5320.1  520.15  5360.2  521.72
  5391.4  524.96  5450.3  526.07  5530.5  529.95  5610.6  537.97  5686.1  539.04
#Mann=10,-1,0
  3263.6     0.1       0  4515.7    0.16       0  4606.5     0.1       0
  4713.9    0.07       0  4813.1    0.12       0  4912.2    0.16       0
  4974.5    0.07       0  5004.5    0.16       0  5010.8     0.1       0
  5122.4    0.05       0
Bank Sta=4974.5,5004.5
Exp/Cntr=0.3,0.1

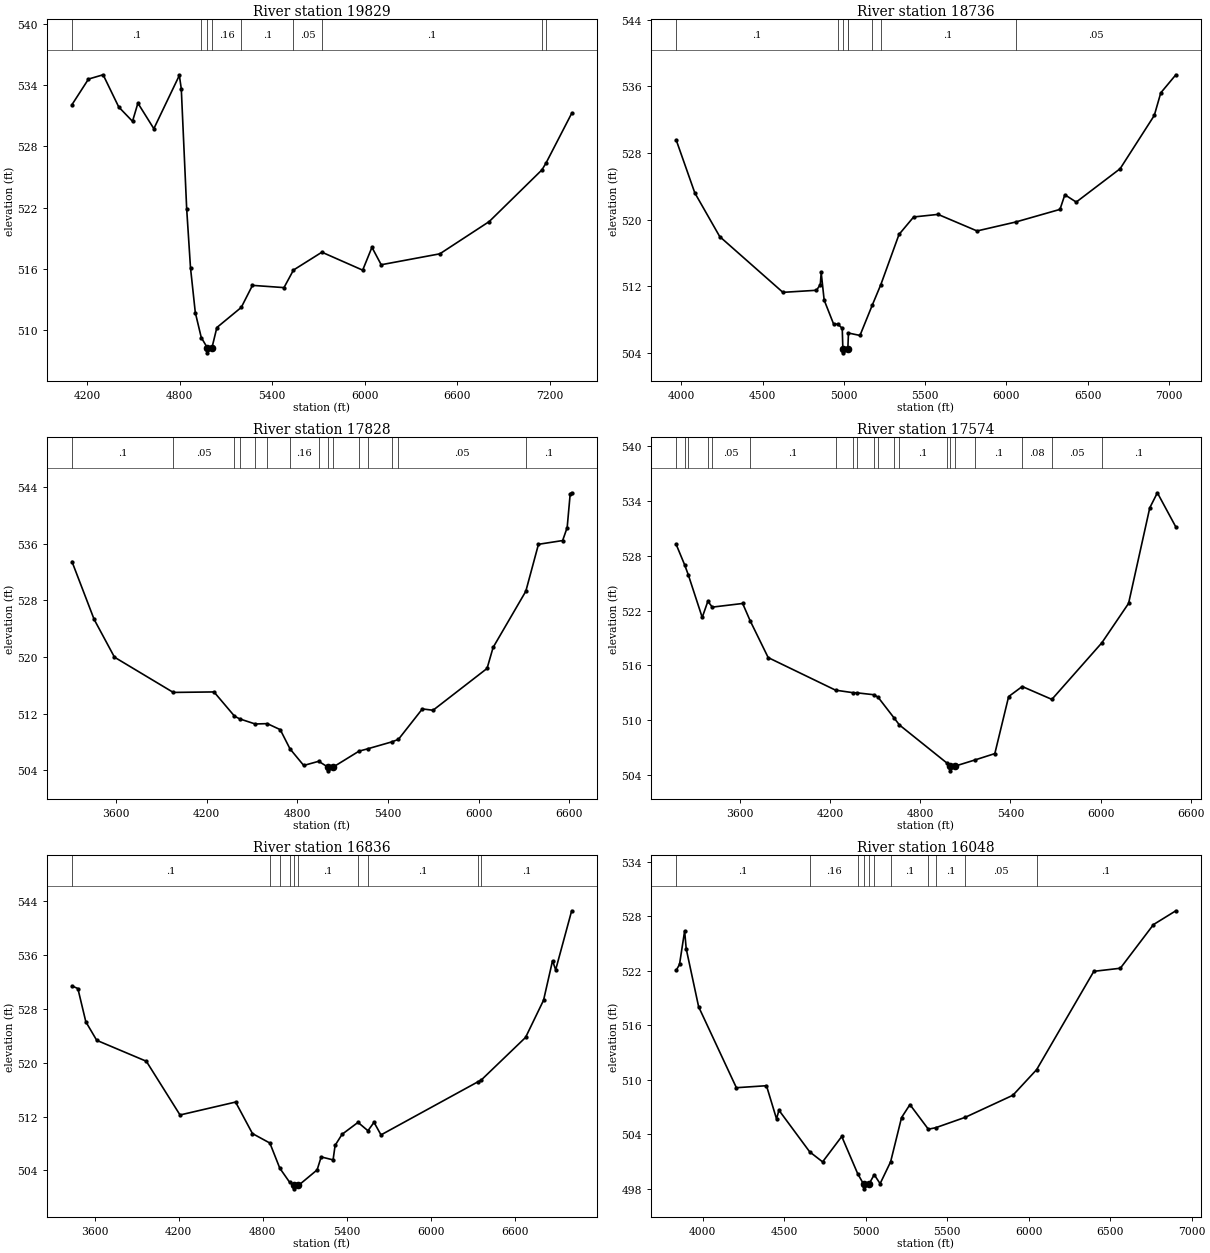
Type RM Length L Ch R = 1,19829,1093,1093,1093
BEGIN DESCRIPTION:
UNT 004 in BCW 27.0
END DESCRIPTION:
XS GIS Cut Line= 3
      1978769.06     13494788.59      1979091.98     13493569.81
      1979196.15     13491590.68
#Sta/Elev= 30
  4100.8  532.09  4208.0  534.60  4303.0  535.02  4404.5  531.86  4493.7  530.46
  4528.7  532.24  4632.1  529.74  4797.6  534.96  4810.2  533.65  4845.2  521.89
  4870.0  516.11  4901.1  511.73  4939.8  509.28  4979.1  508.28  4979.6  507.78
  5009.3  508.28  5041.1  510.26  5199.4  512.23  5272.1  514.39  5476.6  514.17
  5538.2  515.89  5722.6  517.64  5987.3  515.88  6047.4  518.12  6107.5  516.41
  6488.0  517.48  6808.4  520.64  7150.3  525.70  7177.3  526.38  7343.5  531.24
#Mann=9,-1,0
  4100.8     0.1       0  4939.8    0.16       0  4979.1    0.07       0
  5009.3    0.16       0  5199.4     0.1       0  5538.2    0.05       0
  5722.6     0.1       0  7150.3    0.05       0  7177.3     0.1       0
Bank Sta=4979.1,5009.3
Exp/Cntr=0.3,0.1

Type RM Length L Ch R = 1,18736,908,908,908
BEGIN DESCRIPTION:
UNT 004 in BCW 26.0
END DESCRIPTION:
XS GIS Cut Line= 3
      1979625.02     13494624.96      1980025.00     13493675.00
      1980045.11     13491632.34
#Sta/Elev= 30
  3968.8  529.58  4083.7  523.20  4237.0  517.95  4625.5  511.25  4831.7  511.50
  4855.4  512.17  4860.9  513.64  4879.2  510.32  4937.5  507.43  4963.7  507.43
  4990.4  506.92  4994.2  504.48  4994.7  503.98  5024.9  504.48  5028.7  506.36
  5099.5  506.07  5176.3  509.77  5228.0  512.19  5339.6  518.21  5429.6  520.31
  5579.6  520.62  5819.6  518.63  6056.6  519.70  6329.6  521.22  6359.6  522.98
  6429.6  522.10  6699.6  526.11  6909.6  532.51  6949.6  535.23  7042.3  537.40
#Mann=8,-1,0
  3968.8     0.1       0  4963.7    0.16       0  4994.2    0.07       0
  5024.9    0.16       0  5028.7     0.1       0  5176.3    0.16       0
  5228.0     0.1       0  6056.6    0.05       0
Bank Sta=4994.2,5024.9
Exp/Cntr=0.3,0.1

Type RM Length L Ch R = 1,17828,254,254,254
BEGIN DESCRIPTION:
Mapping XS dabf614d
END DESCRIPTION:
XS GIS Cut Line= 4
      1979670.11     13494757.30      1980295.11     13494200.02
      1981414.90     13493116.68      1981435.73     13492205.25
#Sta/Elev= 30
  3308.0  533.48  3454.7  525.31  3589.3  519.97  3978.5  514.99  4247.8  515.06
  4383.6  511.64  4418.2  511.25  4521.0  510.53  4600.8  510.58  4686.4  509.73
  4751.1  507.01  4841.8  504.67  4941.1  505.26  5003.4  504.41  5003.9  503.91
  5034.2  504.41  5207.6  506.69  5264.7  507.02  5422.8  507.99  5468.2  508.35
  5626.9  512.66  5697.6  512.47  6055.2  518.38  6095.2  521.35  6311.5  529.28
  6395.3  535.92  6555.3  536.45  6585.3  538.29  6605.3  543.04  6615.1  543.20
#Mann=15,-1,0
  3308.0     0.1       0  3978.5    0.05       0  4383.6    0.16       0
  4418.2    0.05       0  4521.0    0.16       0  4600.8    0.05       0
  4751.1    0.16       0  4941.1    0.05       0  5003.4    0.04       0
  5034.2    0.05       0  5207.6    0.16       0  5264.7    0.05       0
  5422.8     0.1       0  5468.2    0.05       0  6311.5     0.1       0
Bank Sta=5003.4,5034.2
Exp/Cntr=0.3,0.1

Type RM Length L Ch R = 1,17574,738,738,738
BEGIN DESCRIPTION:
Mapping XS 050acc4f
END DESCRIPTION:
XS GIS Cut Line= 3
      1979826.36     13494861.48      1981524.27     13493210.43
      1981623.24     13492262.49
#Sta/Elev= 30
  3177.9  529.25  3234.5  527.00  3259.1  525.89  3351.3  521.24  3388.7  523.01
  3418.1  522.37  3620.0  522.77  3670.0  520.87  3789.7  516.84  4237.5  513.27
  4355.1  512.99  4378.9  512.98  4492.1  512.77  4520.4  512.49  4629.1  510.17
  4661.8  509.46  4976.5  505.30  4997.7  504.93  4998.2  504.43  5028.5  504.93
  5165.6  505.63  5296.1  506.32  5387.9  512.57  5478.2  513.67  5675.2  512.26
  6007.4  518.46  6185.1  522.78  6325.9  533.25  6376.5  534.90  6499.3  531.15
#Mann=20,-1,0
  3177.9    0.05       0  3234.5     0.1       0  3259.1    0.08       0
  3388.7     0.1       0  3418.1    0.05       0  3670.0     0.1       0
  4237.5     0.1       0  4355.1    0.08       0  4378.9     0.1       0
  4492.1    0.05       0  4520.4     0.1       0  4629.1    0.08       0
  4661.8     0.1       0  4976.5    0.05       0  4997.7    0.04       0
  5028.5    0.05       0  5165.6     0.1       0  5478.2    0.08       0
  5675.2    0.05       0  6007.4     0.1       0
Bank Sta=4997.7,5028.5
Exp/Cntr=0.3,0.1

Type RM Length L Ch R = 1,16836,788,788,788
BEGIN DESCRIPTION:
UNT 004 in BCW 22.0
END DESCRIPTION:
XS GIS Cut Line= 3
      1980675.01     13494825.00      1981831.57     13493778.14
      1983065.93     13492194.83
#Sta/Elev= 30
  3438.0  531.41  3480.2  531.02  3537.0  526.08  3614.7  523.33  3968.9  520.22
  4209.5  512.24  4606.2  514.16  4726.5  509.48  4850.9  508.07  4921.7  504.34
  4992.9  502.22  5023.2  501.77  5023.7  501.27  5054.7  501.77  5188.2  504.08
  5217.2  506.01  5302.2  505.57  5316.7  507.73  5366.4  509.37  5480.1  511.14
  5551.2  509.90  5594.4  511.15  5644.2  509.28  6337.3  517.18  6358.4  517.40
  6676.4  523.76  6804.8  529.28  6869.0  535.15  6891.3  533.80  7005.6  542.57
#Mann=10,-1,0
  3438.0     0.1       0  4850.9    0.07       0  4921.7    0.12       0
  4992.9     0.1       0  5023.2    0.07       0  5054.7     0.1       0
  5480.1    0.08       0  5551.2     0.1       0  6337.3    0.05       0
  6358.4     0.1       0
Bank Sta=5023.2,5054.7
Exp/Cntr=0.3,0.1

Type RM Length L Ch R = 1,16048,405,405,405
BEGIN DESCRIPTION:
UNT 004 in BCW 21.0
END DESCRIPTION:
XS GIS Cut Line= 3
      1981164.86     13494590.65      1982325.00     13494325.00
      1984170.07     13493991.69
#Sta/Elev= 30
  3838.0  522.04  3858.7  522.70  3890.1  526.39  3899.7  524.43  3976.0  518.03
  4207.5  509.12  4392.1  509.34  4453.7  505.69  4468.6  506.64  4657.4  502.05
  4736.4  500.95  4853.8  503.75  4951.8  499.64  4988.3  498.48  4988.8  497.98
  5019.9  498.48  5053.1  499.54  5089.1  498.55  5153.6  500.96  5220.6  505.83
  5272.0  507.26  5384.9  504.55  5429.5  504.71  5611.3  505.86  5903.6  508.29
  6049.2  511.11  6400.0  521.94  6562.6  522.28  6765.8  527.09  6903.1  528.61
#Mann=11,-1,0
  3838.0     0.1       0  4657.4    0.16       0  4951.8    0.07       0
  4988.3    0.07       0  5019.9    0.07       0  5053.1    0.16       0
  5153.6     0.1       0  5384.9    0.05       0  5429.5     0.1       0
  5611.3    0.05       0  6049.2     0.1       0
Bank Sta=4988.3,5019.9
Exp/Cntr=0.3,0.1

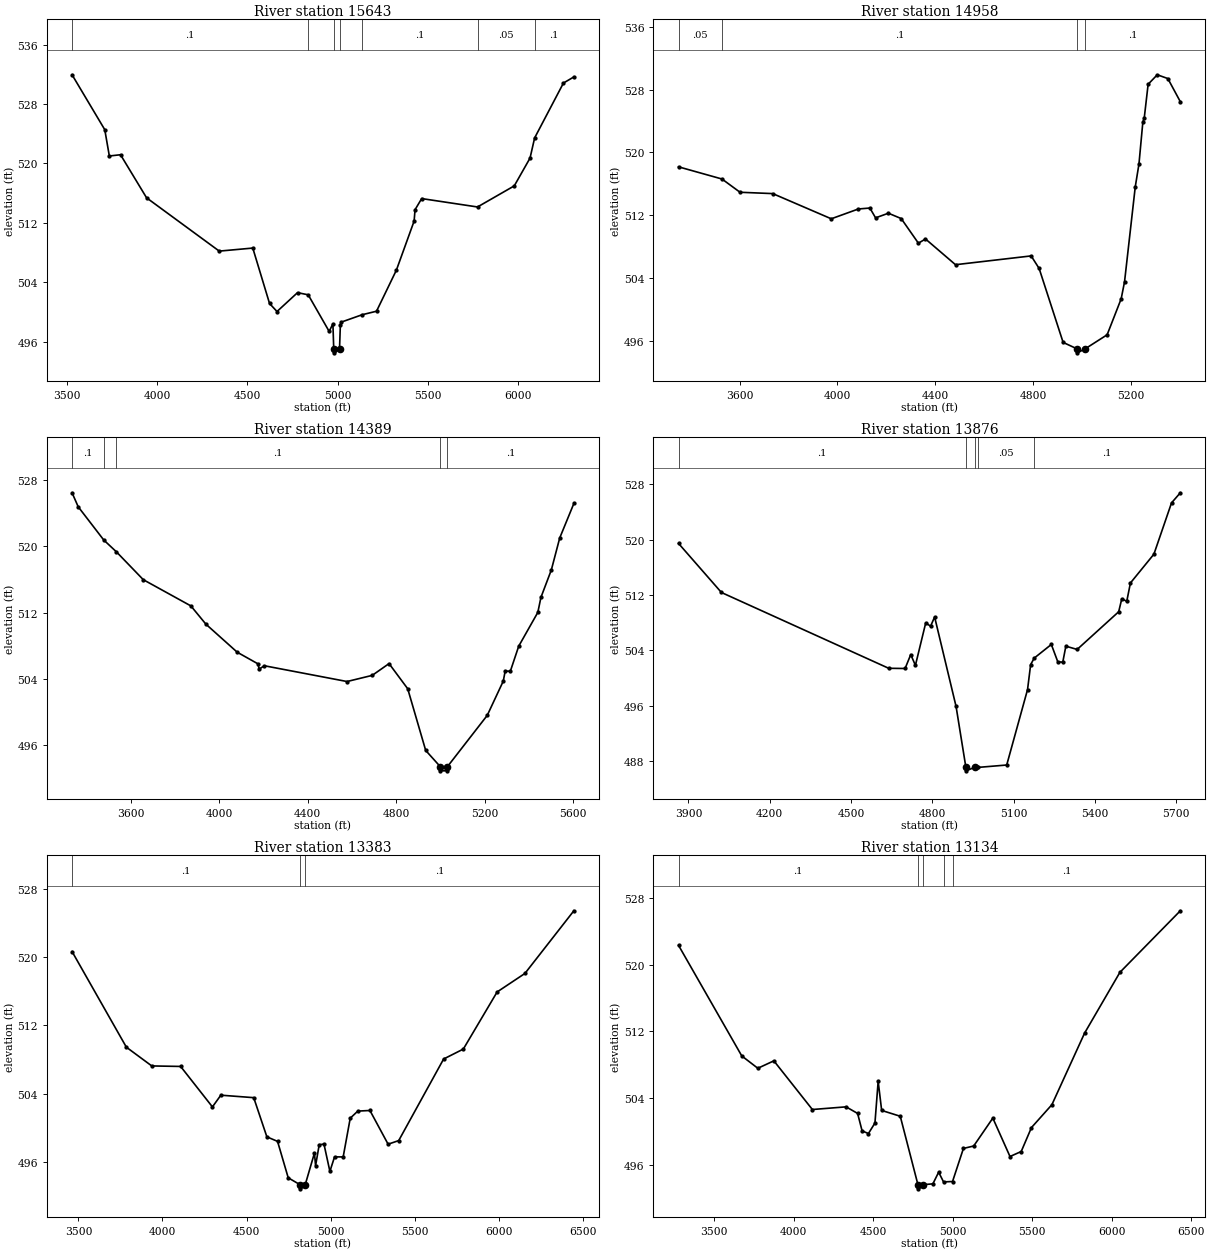
Type RM Length L Ch R = 1,15643,685,685,685
BEGIN DESCRIPTION:
UNT 004 in BCW 20.0
END DESCRIPTION:
XS GIS Cut Line= 3
      1980874.97     13495075.01      1982321.15     13494705.23
      1983607.59     13494752.10
#Sta/Elev= 30
  3528.3  531.93  3709.5  524.54  3734.8  521.00  3796.7  521.17  3941.2  515.37
  4343.7  508.20  4529.5  508.61  4622.4  501.15  4663.7  500.07  4777.3  502.61
  4836.5  502.32  4952.7  497.39  4973.4  498.42  4978.0  495.01  4978.5  494.51
  5010.0  495.01  5014.7  498.29  5020.4  498.65  5135.6  499.64  5215.0  500.11
  5325.1  505.64  5423.4  512.25  5428.4  513.77  5465.2  515.27  5774.5  514.14
  5978.2  516.98  6065.5  520.72  6090.9  523.43  6250.6  530.82  6308.3  531.64
#Mann=7,-1,0
  3528.3     0.1       0  4836.5    0.16       0  4978.0    0.07       0
  5010.0    0.16       0  5135.6     0.1       0  5774.5    0.05       0
  6090.9     0.1       0
Bank Sta=4978,5010
Exp/Cntr=0.3,0.1

Type RM Length L Ch R = 1,14958,569,569,569
BEGIN DESCRIPTION:
UNT 004 in BCW 19.0
END DESCRIPTION:
XS GIS Cut Line= 3
      1980961.78     13495981.26      1982475.00     13495325.00
      1982824.99     13495125.01
#Sta/Elev= 30
  3349.9  518.17  3527.5  516.62  3601.5  514.93  3735.2  514.76  3974.7  511.55
  4085.5  512.80  4132.5  512.92  4155.9  511.67  4208.3  512.26  4260.7  511.58
  4331.1  508.44  4360.0  508.98  4482.8  505.70  4792.2  506.82  4824.9  505.22
  4923.0  495.80  4980.6  494.97  4981.1  494.47  5012.6  494.97  5103.0  496.77
  5160.5  501.36  5174.2  503.52  5218.1  515.63  5233.2  518.53  5249.1  523.88
  5254.8  524.38  5270.7  528.69  5308.1  529.90  5351.3  529.42  5402.4  526.47
#Mann=4,-1,0
  3349.9    0.05       0  3527.5     0.1       0  4980.6    0.07       0
  5012.6     0.1       0
Bank Sta=4980.6,5012.6
Exp/Cntr=0.3,0.1

Type RM Length L Ch R = 1,14389,513,513,513
BEGIN DESCRIPTION:
UNT 004 in BCW 18.0
END DESCRIPTION:
XS GIS Cut Line= 3
      1981279.48     13496444.81      1982825.00     13495775.00
      1983375.04     13495574.99
#Sta/Elev= 30
  3333.7  526.43  3361.5  524.74  3477.0  520.74  3533.7  519.33  3655.8  515.96
  3871.1  512.80  3939.1  510.60  4080.8  507.22  4174.6  505.82  4180.0  505.19
  4203.5  505.59  4577.4  503.69  4691.2  504.43  4767.5  505.85  4851.9  502.82
  4933.2  495.39  4999.3  493.43  4999.8  492.93  5030.9  492.93  5031.4  493.43
  5211.6  499.61  5284.1  503.74  5292.8  504.95  5316.1  504.93  5354.0  507.95
  5440.4  512.02  5454.4  513.82  5501.6  517.14  5539.5  520.99  5603.4  525.14
#Mann=5,-1,0
  3333.7     0.1       0  3477.0    0.05       0  3533.7     0.1       0
  4999.3    0.07       0  5031.4     0.1       0
Bank Sta=4999.3,5031.4
Exp/Cntr=0.3,0.1

Type RM Length L Ch R = 1,13876,493,493,493
BEGIN DESCRIPTION:
UNT 004 in BCW 17.0
END DESCRIPTION:
XS GIS Cut Line= 3
      1982025.00     13496525.00      1983175.00     13496175.00
      1983425.01     13495574.98
#Sta/Elev= 30
  3863.5  519.44  4021.8  512.36  4639.2  501.42  4699.7  501.39  4720.6  503.40
  4737.8  501.84  4775.9  507.98  4793.8  507.49  4808.7  508.83  4887.9  495.91
  4924.1  487.12  4924.6  486.62  4956.2  487.12  4969.8  487.12  5074.8  487.46
  5151.7  498.35  5163.1  501.95  5176.3  502.89  5239.5  504.86  5263.3  502.36
  5281.7  502.30  5293.1  504.61  5334.8  504.14  5488.1  509.58  5499.5  511.45
  5517.9  511.09  5531.4  513.73  5618.1  517.89  5683.1  525.29  5715.6  526.75
#Mann=5,-1,0
  3863.5     0.1       0  4924.1   0.033       0  4956.2     0.1       0
  4969.8    0.05       0  5176.3     0.1       0
Bank Sta=4924.1,4956.2
Exp/Cntr=0.3,0.1

Type RM Length L Ch R = 1,13383,249,249,249
BEGIN DESCRIPTION:
Mapping XS bc6ef9d0
END DESCRIPTION:
XS GIS Cut Line= 4
      1982091.98     13496679.18      1983154.48     13496746.89
      1983519.07     13496408.35      1984700.65     13495617.15
#Sta/Elev= 30
  3462.2  520.64  3785.2  509.46  3936.2  507.27  4107.8  507.21  4296.9  502.48
  4347.0  503.85  4542.5  503.56  4620.7  498.98  4684.2  498.45  4747.7  494.19
  4816.6  493.40  4817.1  492.90  4849.0  493.40  4903.6  497.08  4910.4  495.61
  4932.0  498.06  4960.3  498.13  4995.5  494.94  5023.2  496.64  5074.5  496.63
  5116.5  501.16  5161.5  501.99  5233.6  502.06  5341.7  498.12  5404.7  498.54
  5671.9  508.08  5789.0  509.24  5990.1  515.92  6155.2  518.08  6446.4  525.41
#Mann=3,-1,0
  3462.2     0.1       0  4816.6    0.07       0  4849.0     0.1       0
Bank Sta=4816.6,4849
Exp/Cntr=0.3,0.1

Type RM Length L Ch R = 1,13134,368,368,368
BEGIN DESCRIPTION:
UNT 004 in BCW 16.0
END DESCRIPTION:
XS GIS Cut Line= 4
      1982060.77     13496731.27      1983347.19     13496903.14
      1983696.15     13496496.89      1984743.03     13495689.59
#Sta/Elev= 30
  3275.1  522.33  3672.8  509.06  3773.7  507.58  3874.6  508.47  4116.7  502.63
  4328.6  502.95  4401.2  502.16  4429.5  500.06  4469.3  499.75  4510.2  501.01
  4530.4  506.02  4552.4  502.52  4669.4  501.82  4780.5  493.61  4781.0  493.11
  4812.9  493.61  4874.6  493.71  4910.8  495.11  4941.5  493.94  4998.1  493.99
  5066.6  497.96  5131.1  498.25  5251.5  501.60  5359.4  496.99  5430.0  497.59
  5494.3  500.46  5623.0  503.21  5828.5  511.80  6050.5  519.09  6430.5  526.48
#Mann=5,-1,0
  3275.1     0.1       0  4780.5    0.07       0  4812.9     0.1       0
  4941.5    0.12       0  4998.1     0.1       0
Bank Sta=4780.5,4812.9
Exp/Cntr=0.3,0.1