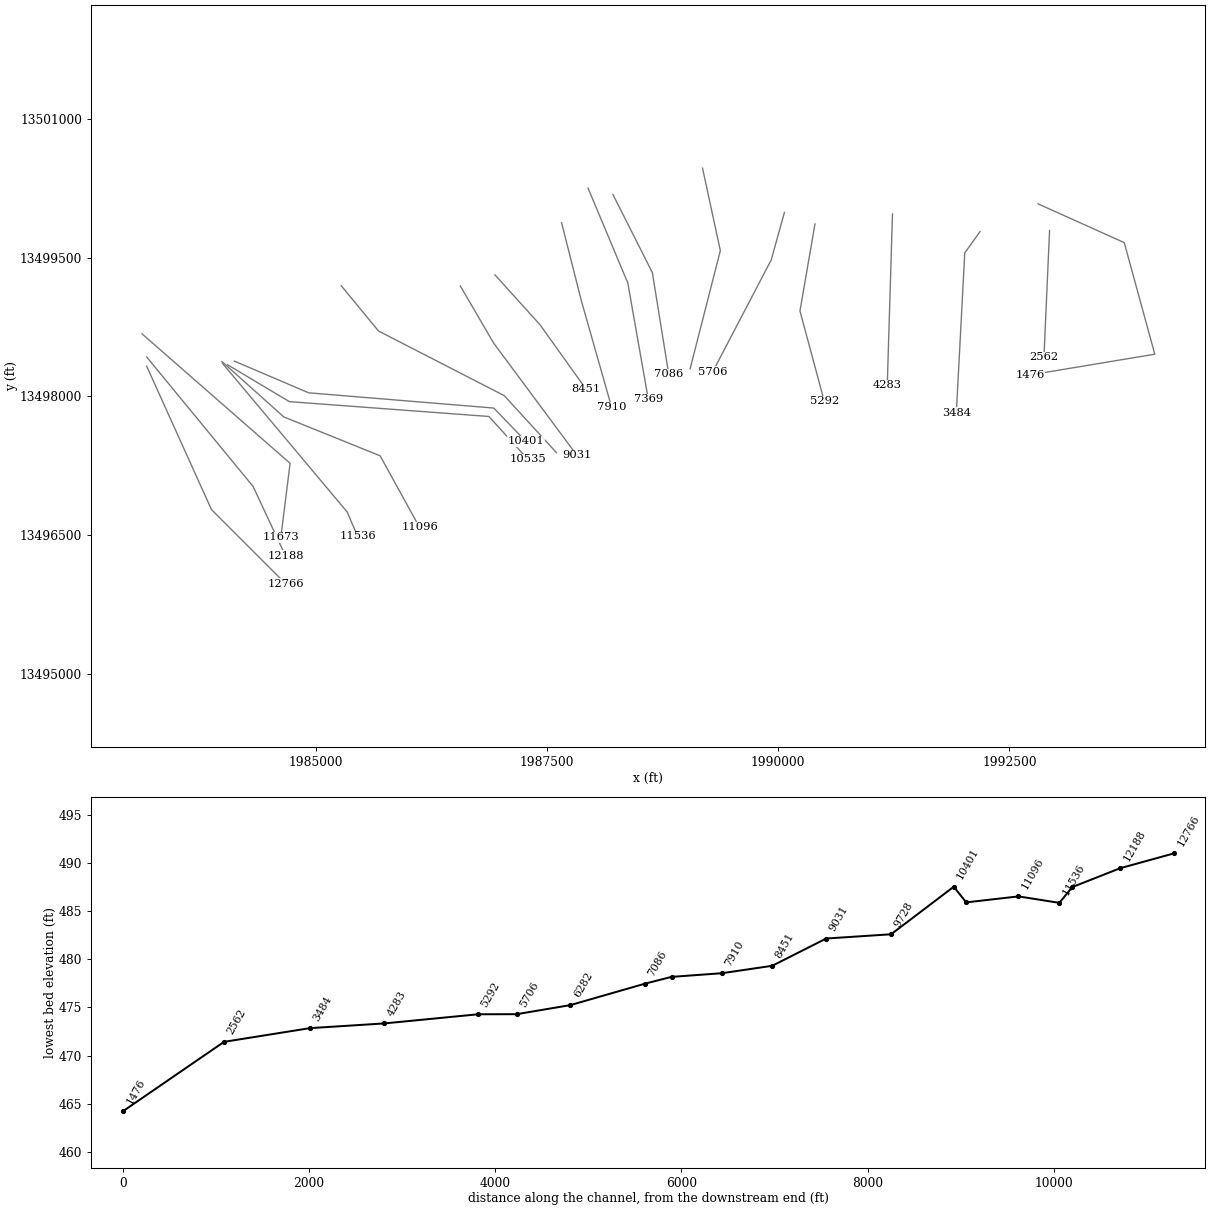
HEC-RAS study UNT 004 in BCW.prj: UNT 004 in BCW Base Level Engineering

--- UNT 004 in BCW.g01 (geometry) --- (continued)

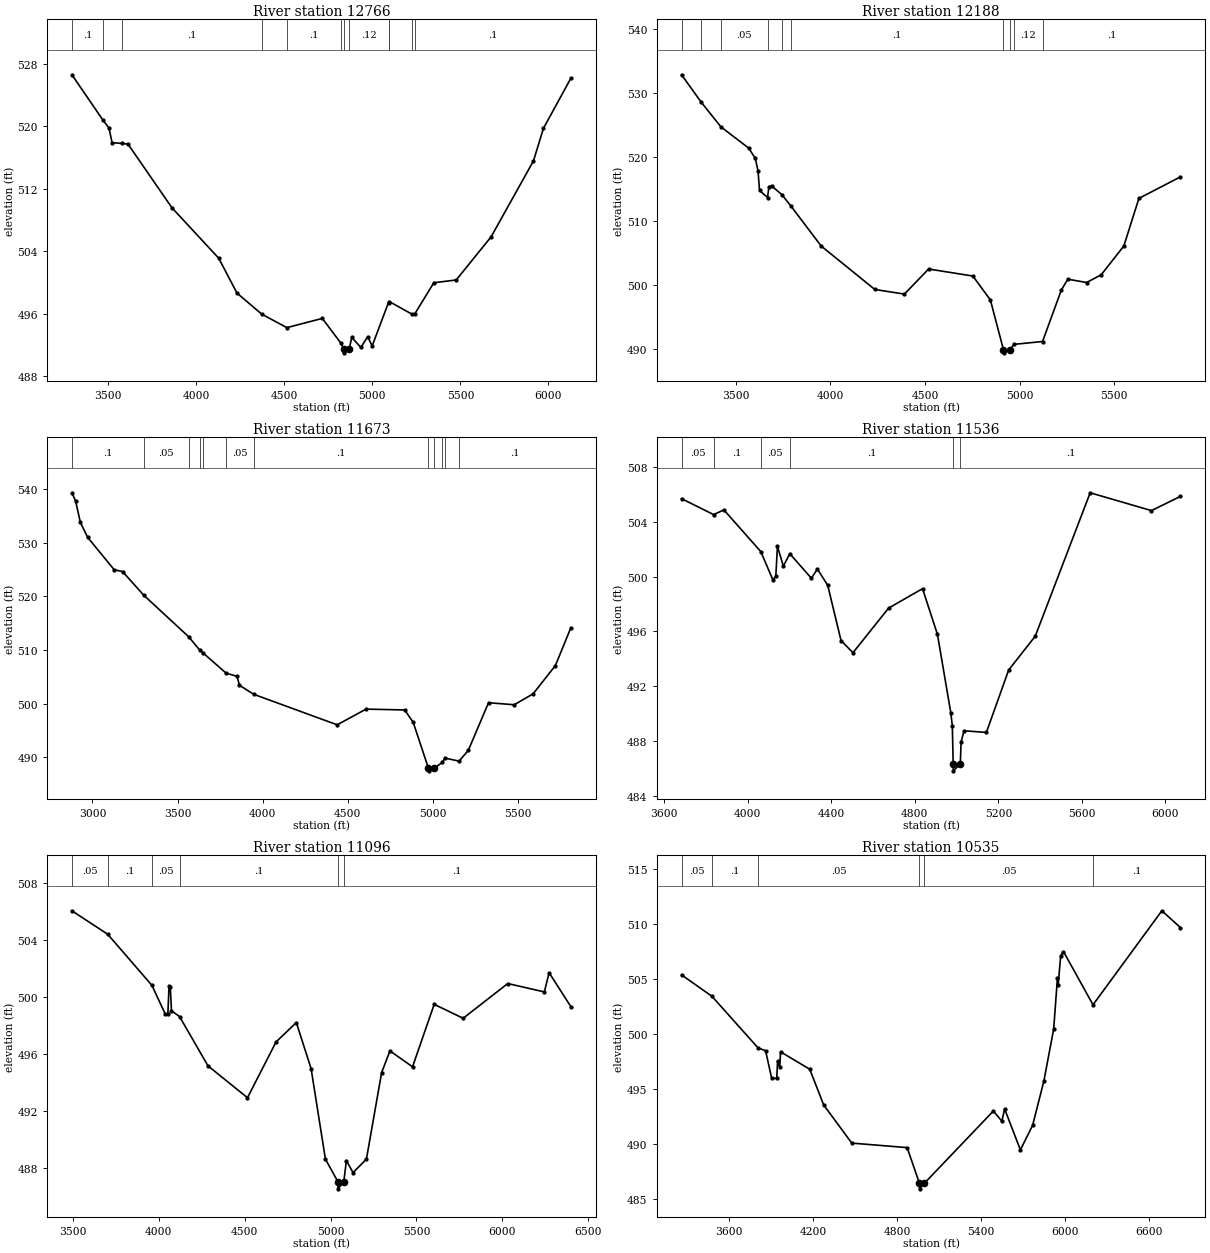
Type RM Length L Ch R = 1,12766,578,578,578
BEGIN DESCRIPTION:
UNT 004 in BCW 15.0
END DESCRIPTION:
XS GIS Cut Line= 3
      1983174.98     13498325.03      1983875.00     13496775.00
      1984674.97     13495975.03
#Sta/Elev= 30
  3294.8  526.60  3470.3  520.81  3505.1  519.79  3522.7  517.90  3577.0  517.81
  3613.0  517.72  3862.9  509.55  4128.2  503.09  4231.6  498.63  4372.7  495.92
  4515.0  494.20  4716.0  495.38  4821.8  492.21  4836.7  491.47  4837.3  490.97
  4869.1  491.47  4883.3  492.96  4935.0  491.66  4973.6  493.04  4999.1  491.85
  5091.9  497.42  5096.2  497.54  5225.6  495.92  5239.7  495.91  5349.1  499.95
  5476.4  500.31  5674.4  505.84  5914.8  515.57  5971.4  519.74  6126.9  526.15
#Mann=12,-1,0
  3294.8     0.1       0  3470.3    0.08       0  3577.0     0.1       0
  4372.7    0.12       0  4515.0     0.1       0  4821.8    0.12       0
  4836.7    0.07       0  4869.1    0.12       0  5091.9     0.1       0
  5096.2    0.07       0  5225.6    0.12       0  5239.7     0.1       0
Bank Sta=4836.7,4869.1
Exp/Cntr=0.3,0.1

Type RM Length L Ch R = 1,12188,515,515,515
BEGIN DESCRIPTION:
UNT 004 in BCW 14.0
END DESCRIPTION:
XS GIS Cut Line= 3
      1983175.02     13498424.98      1984325.00     13497025.00
      1984675.00     13496274.99
#Sta/Elev= 30
  3212.1  532.88  3316.3  528.59  3420.4  524.74  3567.3  521.42  3602.4  519.80
  3616.8  517.84  3624.6  514.80  3667.2  513.70  3674.2  515.40  3688.5  515.51
  3742.5  514.16  3791.5  512.34  3950.4  506.13  4234.6  499.33  4391.0  498.61
  4519.1  502.53  4753.3  501.43  4845.9  497.69  4914.9  489.93  4915.6  489.43
  4949.0  489.93  4972.0  490.76  5121.9  491.20  5220.9  499.22  5255.6  500.94
  5354.9  500.42  5432.1  501.62  5552.0  506.13  5631.6  513.56  5851.5  516.93
#Mann=10,-1,0
  3212.1    0.05       0  3316.3     0.1       0  3420.4    0.05       0
  3667.2     0.1       0  3742.5    0.05       0  3791.5     0.1       0
  4914.9    0.07       0  4949.0     0.1       0  4972.0    0.12       0
  5121.9     0.1       0
Bank Sta=4914.9,4949
Exp/Cntr=0.3,0.1

Type RM Length L Ch R = 1,11673,137,137,137
BEGIN DESCRIPTION:
UNT 004 in BCW 13.0
END DESCRIPTION:
XS GIS Cut Line= 3
      1983124.99     13498675.01      1984725.00     13497275.00
      1984625.00     13496474.97
#Sta/Elev= 30
  2879.1  539.31  2900.5  537.81  2928.9  533.77  2971.7  530.99  3127.3  524.97
  3176.7  524.62  3301.3  520.21  3565.2  512.47  3632.1  509.91  3647.8  509.51
  3785.0  505.69  3849.6  505.08  3863.8  503.42  3947.5  501.74  4438.0  496.05
  4607.9  498.98  4834.8  498.82  4885.1  496.50  4974.3  487.97  4975.0  487.47
  5008.4  487.97  5056.0  489.03  5071.1  489.86  5154.8  489.27  5209.2  491.32
  5327.6  500.17  5478.8  499.79  5589.7  501.83  5720.7  507.10  5811.4  514.15
#Mann=12,-1,0
  2879.1     0.1       0  3301.3    0.05       0  3565.2     0.1       0
  3632.1    0.05       0  3647.8     0.1       0  3785.0    0.05       0
  3947.5     0.1       0  4974.3    0.07       0  5008.4     0.1       0
  5056.0    0.07       0  5071.1    0.12       0  5154.8     0.1       0
Bank Sta=4974.3,5008.4
Exp/Cntr=0.3,0.1

Type RM Length L Ch R = 1,11536,440,440,440
BEGIN DESCRIPTION:
Mapping XS c784e2fa
END DESCRIPTION:
XS GIS Cut Line= 3
      1983992.38     13498358.62      1985342.19     13496748.39
      1985455.06     13496483.59
#Sta/Elev= 30
  3683.1  505.68  3836.5  504.52  3885.9  504.86  4062.7  501.82  4120.1  499.77
  4134.4  500.02  4142.2  502.20  4170.6  500.76  4201.3  501.67  4304.8  499.88
  4333.5  500.55  4382.9  499.37  4446.7  495.34  4503.9  494.45  4674.3  497.70
  4837.0  499.12  4908.5  495.78  4972.3  490.08  4979.7  489.11  4983.8  486.34
  4984.5  485.84  5017.9  486.34  5021.7  487.96  5036.0  488.76  5142.7  488.64
  5249.4  493.19  5376.9  495.66  5639.7  506.11  5933.2  504.81  6072.1  505.85
#Mann=6,-1,0
  3683.1    0.05       0  3836.5     0.1       0  4062.7    0.05       0
  4201.3     0.1       0  4983.8    0.07       0  5017.9     0.1       0
Bank Sta=4983.8,5017.9
Exp/Cntr=0.3,0.1

Type RM Length L Ch R = 1,11096,561,561,561
BEGIN DESCRIPTION:
Mapping XS d99f88d9
END DESCRIPTION:
XS GIS Cut Line= 4
      1983988.01     13498376.01      1984656.43     13497777.04
      1985698.10     13497356.03      1986123.46     13496583.43
#Sta/Elev= 30
  3495.1  506.04  3703.4  504.39  3960.7  500.80  4039.2  498.76  4053.4  498.80
  4060.1  500.73  4067.6  500.66  4074.3  499.02  4121.4  498.61  4286.6  495.15
  4516.6  492.91  4683.0  496.83  4800.9  498.19  4886.8  494.95  4970.0  488.60
  5042.7  487.01  5043.4  486.51  5076.9  487.01  5092.2  488.49  5130.9  487.65
  5208.7  488.60  5297.3  494.68  5345.5  496.20  5477.0  495.08  5603.0  499.47
  5771.5  498.49  6031.0  500.93  6244.0  500.34  6271.5  501.69  6398.1  499.31
#Mann=6,-1,0
  3495.1    0.05       0  3703.4     0.1       0  3960.7    0.05       0
  4121.4     0.1       0  5042.7    0.07       0  5076.9     0.1       0
Bank Sta=5042.7,5076.9
Exp/Cntr=0.3,0.1

Type RM Length L Ch R = 1,10535,134,134,134
BEGIN DESCRIPTION:
Mapping XS 6dbd7420
END DESCRIPTION:
XS GIS Cut Line= 4
      1984048.83     13498341.25      1984717.19     13497941.97
      1986874.31     13497781.38      1987295.34     13497316.95
#Sta/Elev= 30
  3259.2  505.35  3476.7  503.40  3806.3  498.71  3860.4  498.45  3903.2  495.97
  3940.1  495.93  3946.0  497.51  3961.5  496.94  3967.4  498.35  4175.9  496.77
  4276.2  493.51  4476.8  490.05  4872.6  489.64  4960.9  486.39  4961.6  485.89
  4995.4  486.39  5489.6  492.97  5550.3  492.04  5569.8  493.16  5682.8  489.43
  5770.3  491.67  5850.6  495.69  5920.8  500.42  5947.9  505.09  5952.9  504.41
  5970.9  507.09  5990.9  507.47  6202.2  502.63  6694.6  511.18  6827.7  509.65
#Mann=6,-1,0
  3259.2    0.05       0  3476.7     0.1       0  3806.3    0.05       0
  4960.9    0.04       0  4995.4    0.05       0  6202.2     0.1       0
Bank Sta=4960.9,4995.4
Exp/Cntr=0.3,0.1

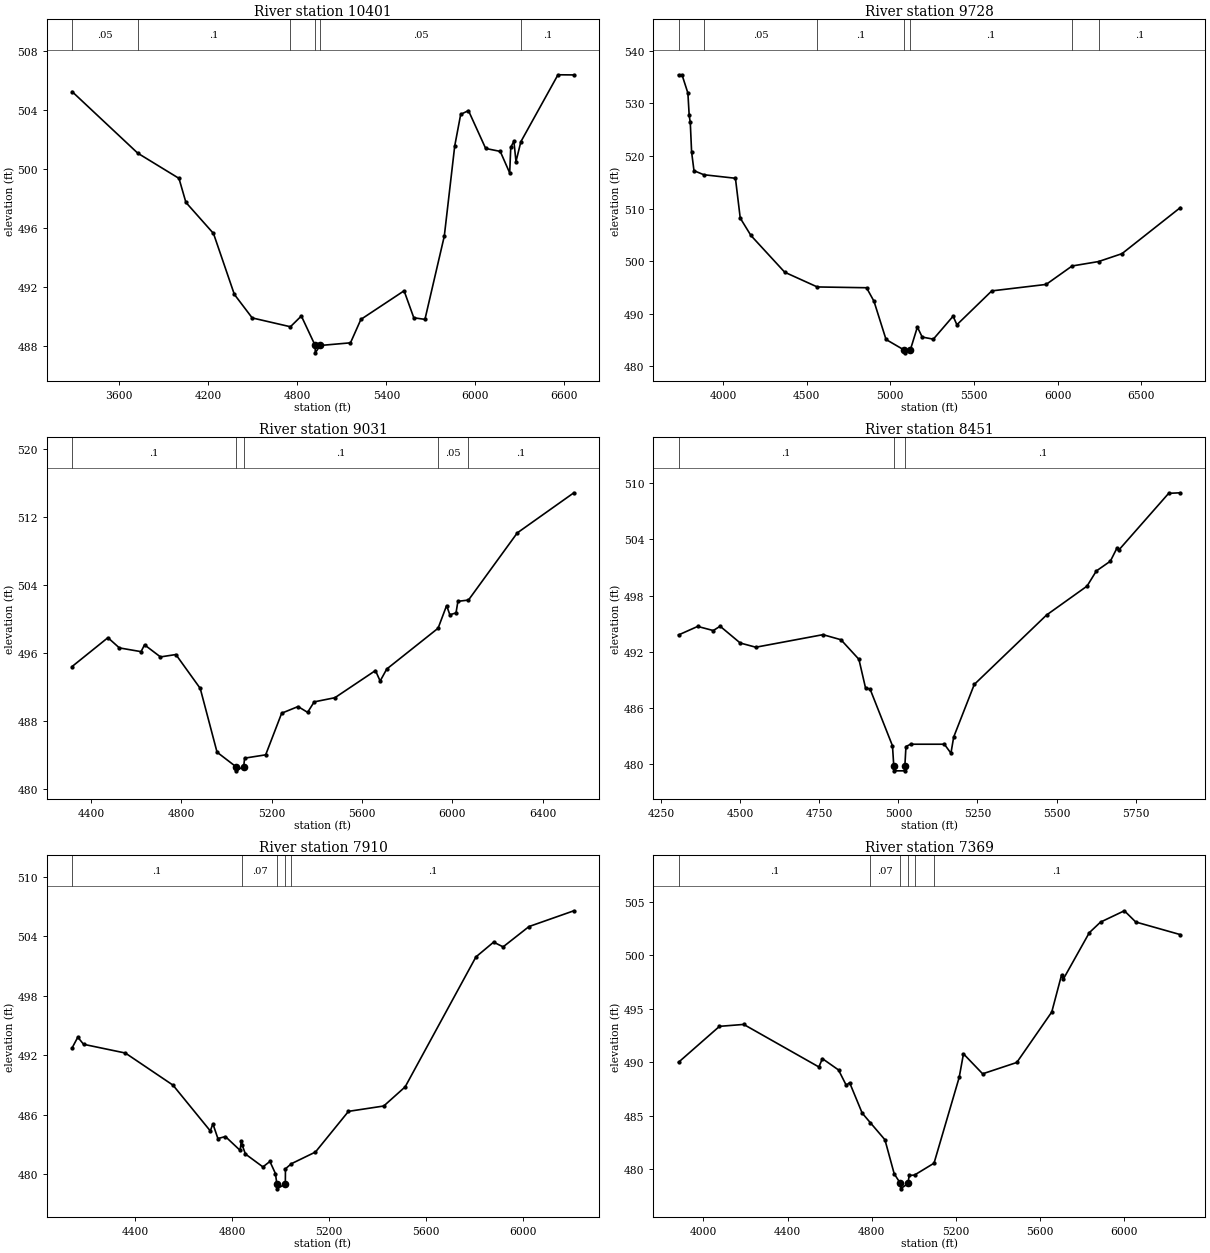
Type RM Length L Ch R = 1,10401,673,673,673
BEGIN DESCRIPTION:
Mapping XS de5d6345
END DESCRIPTION:
XS GIS Cut Line= 4
      1984122.56     13498380.34      1984925.53     13498037.45
      1986926.39     13497872.52      1987273.61     13497512.29
#Sta/Elev= 30
  3282.0  505.24  3724.6  501.06  4002.3  499.35  4049.0  497.72  4234.9  495.61
  4375.3  491.48  4495.7  489.88  4753.2  489.28  4826.9  490.01  4920.0  488.01
  4920.7  487.51  4954.5  488.01  5158.0  488.19  5228.2  489.78  5519.2  491.72
  5584.6  489.89  5659.7  489.78  5790.1  495.43  5860.4  501.55  5900.5  503.69
  5952.8  503.95  6068.9  501.38  6167.1  501.18  6230.7  499.72  6237.9  501.45
  6259.0  501.88  6273.1  500.49  6306.1  501.84  6556.1  506.38  6663.1  506.37
#Mann=6,-1,0
  3282.0    0.05       0  3724.6     0.1       0  4753.2    0.05       0
  4920.0    0.04       0  4954.5    0.05       0  6306.1     0.1       0
Bank Sta=4920,4954.5
Exp/Cntr=0.3,0.1

Type RM Length L Ch R = 1,9728,697,697,697
BEGIN DESCRIPTION:
Mapping XS 119d6ce1
END DESCRIPTION:
XS GIS Cut Line= 4
      1985277.09     13499196.30      1985680.73     13498705.86
      1987039.24     13498007.07      1987603.50     13497390.73
#Sta/Elev= 30
  3734.6  535.46  3755.3  535.46  3790.5  531.98  3798.3  527.73  3804.8  526.39
  3812.7  520.78  3826.9  517.22  3885.7  516.45  4074.6  515.78  4103.3  508.21
  4167.1  504.90  4369.2  497.91  4563.7  495.11  4858.0  494.96  4902.4  492.40
  4974.5  485.12  5084.7  483.08  5085.4  482.58  5119.2  483.08  5161.8  487.48
  5190.7  485.58  5257.2  485.18  5375.4  489.55  5397.9  487.92  5606.4  494.36
  5931.2  495.59  6086.6  499.10  6244.5  499.94  6384.4  501.44  6733.1  510.20
#Mann=7,-1,0
  3734.6     0.1       0  3885.7    0.05       0  4563.7     0.1       0
  5084.7    0.07       0  5119.2     0.1       0  6086.6    0.05       0
  6244.5     0.1       0
Bank Sta=5084.7,5119.2
Exp/Cntr=0.3,0.1

Type RM Length L Ch R = 1,9031,580,580,580
BEGIN DESCRIPTION:
UNT 004 in BCW 8.0
END DESCRIPTION:
XS GIS Cut Line= 3
      1986565.14     13499192.20      1986925.00     13498575.00
      1987823.15     13497363.82
#Sta/Elev= 30
  4315.7  494.39  4474.5  497.78  4525.2  496.58  4621.2  496.14  4636.6  496.94
  4707.2  495.52  4775.5  495.80  4883.3  491.82  4957.8  484.33  5040.8  482.64
  5041.6  482.14  5075.7  482.64  5079.9  483.63  5173.1  484.02  5244.0  488.91
  5316.5  489.69  5358.8  489.01  5388.0  490.24  5479.8  490.73  5659.3  493.92
  5680.1  492.69  5709.4  494.10  5936.7  498.89  5974.4  501.55  5988.8  500.47
  6016.1  500.69  6024.5  502.05  6071.3  502.20  6287.5  510.09  6538.0  514.80
#Mann=5,-1,0
  4315.7     0.1       0  5040.8    0.07       0  5075.7     0.1       0
  5936.7    0.05       0  6071.3     0.1       0
Bank Sta=5040.8,5075.7
Exp/Cntr=0.3,0.1

Type RM Length L Ch R = 1,8451,541,541,541
BEGIN DESCRIPTION:
UNT 004 in BCW 7.0
END DESCRIPTION:
XS GIS Cut Line= 3
      1986938.40     13499313.75      1987425.00     13498775.00
      1987925.00     13498075.00
#Sta/Elev= 30
  4305.0  493.81  4365.5  494.72  4414.8  494.28  4436.5  494.74  4500.0  492.95
  4549.3  492.50  4761.6  493.84  4818.4  493.30  4875.2  491.21  4896.2  488.14
  4910.3  488.05  4981.3  481.98  4985.4  479.81  4986.2  479.31  5019.7  479.31
  5020.4  479.81  5023.9  481.90  5038.3  482.15  5145.3  482.15  5166.1  481.19
  5174.8  482.92  5239.9  488.53  5468.5  495.94  5596.3  499.02  5625.8  500.64
  5670.0  501.68  5690.9  503.08  5697.0  502.88  5854.3  508.92  5891.2  508.98
#Mann=3,-1,0
  4305.0     0.1       0  4985.4    0.07       0  5020.4     0.1       0
Bank Sta=4985.4,5020.4
Exp/Cntr=0.3,0.1

Type RM Length L Ch R = 1,7910,541,541,541
BEGIN DESCRIPTION:
UNT 004 in BCW 6.0
END DESCRIPTION:
XS GIS Cut Line= 3
      1987658.88     13499878.01      1987875.00     13499025.00
      1988200.24     13497880.89
#Sta/Elev= 30
  4139.4  492.74  4163.1  493.83  4186.8  493.11  4359.1  492.23  4555.7  488.99
  4709.4  484.38  4720.2  485.09  4740.8  483.61  4771.8  483.81  4832.3  482.42
  4837.5  483.36  4841.7  482.91  4854.3  482.05  4926.5  480.75  4955.3  481.30
  4978.1  480.08  4983.9  479.04  4984.7  478.54  5018.9  479.04  5019.4  480.56
  5043.7  481.07  5143.1  482.25  5279.3  486.35  5424.8  486.89  5513.1  488.82
  5805.0  501.92  5877.9  503.41  5917.0  502.93  6023.8  504.98  6208.8  506.57
#Mann=5,-1,0
  4139.4     0.1       0  4841.7    0.07       0  4983.9    0.07       0
  5018.9    0.07       0  5043.7     0.1       0
Bank Sta=4983.9,5018.9
Exp/Cntr=0.3,0.1

Type RM Length L Ch R = 1,7369,283,283,283
BEGIN DESCRIPTION:
UNT 004 in BCW 5.0
END DESCRIPTION:
XS GIS Cut Line= 3
      1987945.34     13500251.25      1988375.00     13499225.00
      1988596.32     13497968.30
#Sta/Elev= 30
  3881.2  490.00  4076.1  493.36  4191.5  493.54  4549.3  489.56  4566.0  490.34
  4642.8  489.28  4679.4  487.85  4695.6  488.09  4755.3  485.25  4793.6  484.36
  4863.7  482.75  4907.8  479.57  4937.6  478.66  4938.4  478.16  4973.2  478.66
  4979.2  479.41  5004.5  479.45  5097.4  480.56  5217.1  488.58  5237.5  490.79
  5328.8  488.92  5491.3  489.98  5657.8  494.70  5704.5  498.17  5712.0  497.75
  5836.5  502.12  5889.9  503.11  6003.4  504.17  6057.6  503.12  6269.8  501.94
#Mann=6,-1,0
  3881.2     0.1       0  4793.6    0.07       0  4937.6    0.07       0
  4973.2    0.07       0  5004.5    0.12       0  5097.4     0.1       0
Bank Sta=4937.6,4973.2
Exp/Cntr=0.3,0.1

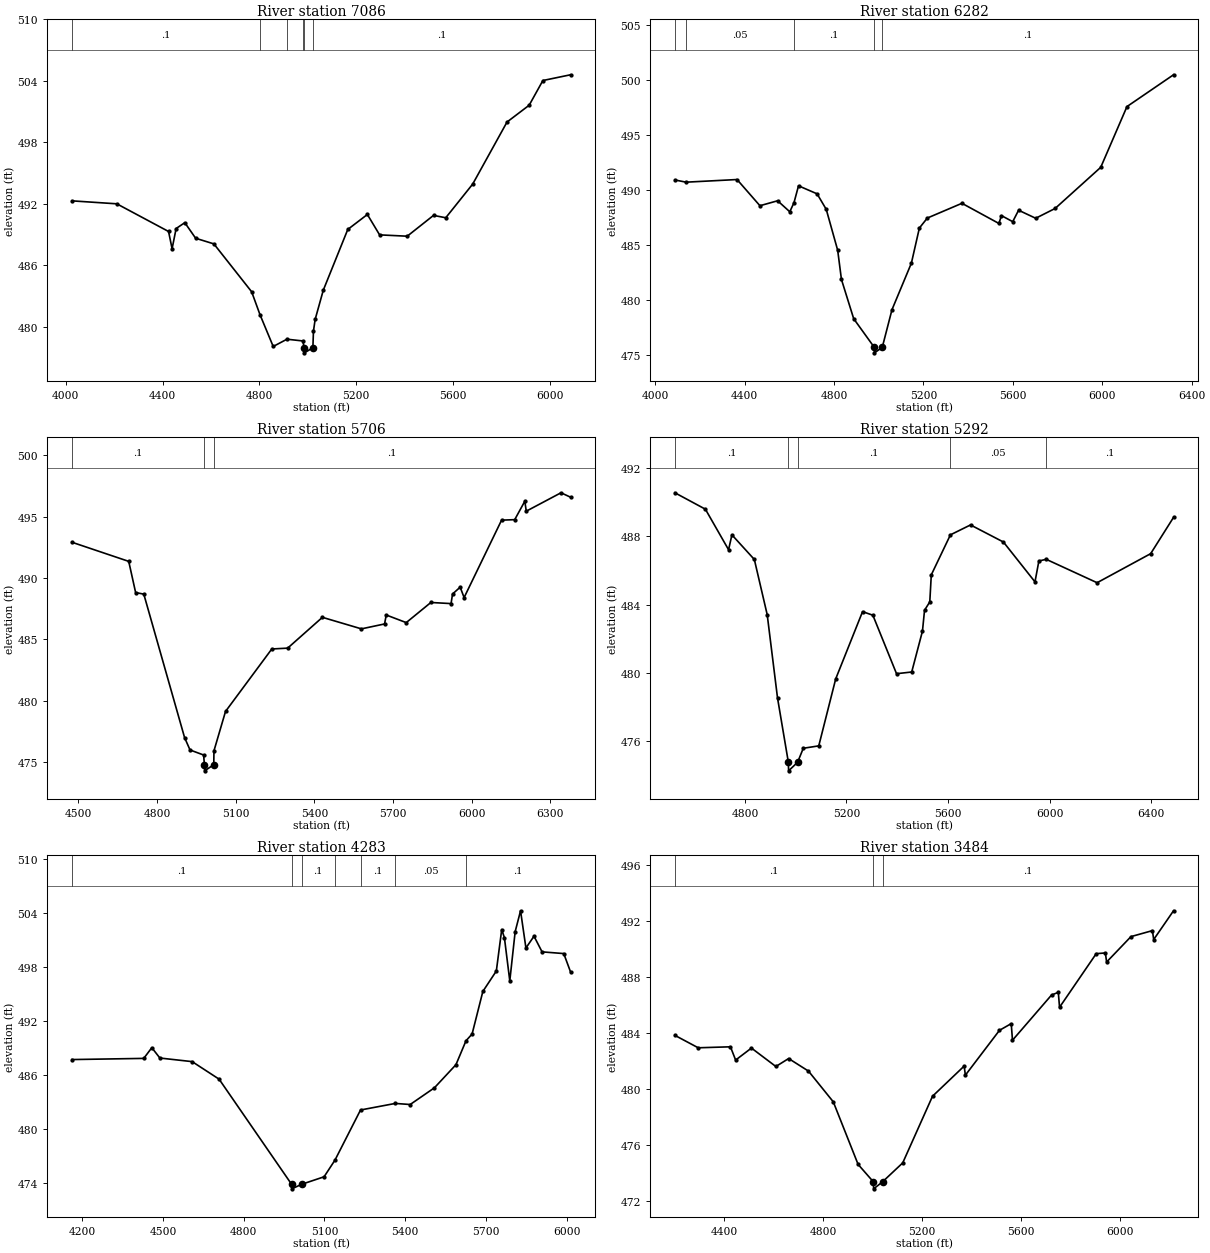
Type RM Length L Ch R = 1,7086,804,804,804
BEGIN DESCRIPTION:
UNT 004 in BCW 4.0
END DESCRIPTION:
XS GIS Cut Line= 3
      1988214.45     13500181.79      1988640.01     13499338.18
      1988817.97     13498235.73
#Sta/Elev= 30
  4025.1  492.29  4210.7  492.00  4424.7  489.30  4439.3  487.62  4456.0  489.59
  4491.9  490.16  4536.7  488.64  4612.1  488.09  4768.2  483.42  4802.8  481.18
  4857.4  478.08  4914.2  478.79  4979.5  478.62  4985.8  477.96  4986.6  477.46
  5021.4  477.96  5023.8  479.58  5030.8  480.72  5064.4  483.57  5165.7  489.50
  5246.7  490.96  5297.3  488.97  5411.5  488.84  5520.2  490.87  5570.8  490.64
  5682.3  493.93  5824.1  499.98  5915.7  501.62  5972.4  504.03  6086.7  504.59
#Mann=6,-1,0
  4025.1     0.1       0  4802.8    0.07       0  4914.2    0.12       0
  4979.5     0.1       0  4985.8    0.07       0  5021.4     0.1       0
Bank Sta=4985.8,5021.4
Exp/Cntr=0.3,0.1

Type RM Length L Ch R = 1,6282,576,576,576
BEGIN DESCRIPTION:
UNT 004 in BCW 3.0
END DESCRIPTION:
XS GIS Cut Line= 3
      1989182.54     13500466.70      1989375.00     13499575.00
      1989048.44     13498298.24
#Sta/Elev= 30
  4088.5  490.94  4138.6  490.74  4366.5  490.98  4468.8  488.60  4548.0  489.05
  4602.4  488.05  4621.2  488.88  4641.4  490.41  4724.5  489.68  4765.4  488.27
  4816.6  484.55  4833.4  481.90  4888.2  478.33  4980.3  475.73  4981.1  475.23
  5016.0  475.73  5059.4  479.15  5146.2  483.38  5181.9  486.57  5217.5  487.48
  5372.3  488.82  5537.5  486.99  5549.2  487.70  5599.4  487.15  5625.7  488.19
  5702.2  487.46  5789.0  488.35  5993.1  492.09  6110.4  497.61  6318.6  500.50
#Mann=5,-1,0
  4088.5     0.1       0  4138.6    0.05       0  4621.2     0.1       0
  4980.3    0.07       0  5016.0     0.1       0
Bank Sta=4980.3,5016
Exp/Cntr=0.3,0.1

Type RM Length L Ch R = 1,5706,414,414,414
BEGIN DESCRIPTION:
UNT 004 in BCW 2.0
END DESCRIPTION:
XS GIS Cut Line= 3
      1990067.97     13499989.23      1989925.00     13499475.00
      1989291.05     13498261.78
#Sta/Elev= 30
  4475.0  492.92  4691.8  491.36  4718.1  488.82  4749.3  488.69  4904.9  477.00
  4925.7  475.99  4977.6  475.58  4980.5  474.79  4981.3  474.29  5016.3  474.79
  5017.0  475.92  5061.1  479.13  5237.7  484.22  5298.3  484.29  5430.8  486.80
  5579.7  485.86  5668.0  486.26  5674.4  486.99  5750.7  486.37  5844.7  488.01
  5921.7  487.92  5927.4  488.70  5956.5  489.26  5971.5  488.41  6114.5  494.72
  6164.6  494.76  6203.1  496.26  6208.7  495.45  6341.2  496.95  6377.6  496.59
#Mann=3,-1,0
  4475.0     0.1       0  4980.5    0.07       0  5016.3     0.1       0
Bank Sta=4980.5,5016.3
Exp/Cntr=0.3,0.1

Type RM Length L Ch R = 1,5292,1009,1009,1009
BEGIN DESCRIPTION:
Mapping XS 45774c94
END DESCRIPTION:
XS GIS Cut Line= 3
      1990397.82     13499863.32      1990235.52     13498922.40
      1990497.95     13497948.13
#Sta/Elev= 30
  4524.3  490.54  4644.4  489.58  4735.7  487.21  4748.9  488.08  4837.2  486.64
  4887.9  483.41  4928.5  478.54  4971.2  474.78  4972.1  474.28  5007.5  474.78
  5030.0  475.60  5090.9  475.74  5157.7  479.66  5263.4  483.59  5304.0  483.38
  5397.2  479.96  5457.0  480.06  5499.3  482.45  5507.5  483.67  5528.2  484.16
  5534.1  485.74  5609.4  488.08  5688.6  488.66  5818.2  487.66  5942.5  485.33
  5957.8  486.55  5986.6  486.65  6187.1  485.28  6398.1  486.98  6488.1  489.10
#Mann=5,-1,0
  4524.3     0.1       0  4971.2    0.07       0  5007.5     0.1       0
  5609.4    0.05       0  5986.6     0.1       0
Bank Sta=4971.2,5007.5
Exp/Cntr=0.3,0.1

Type RM Length L Ch R = 1,4283,799,799,799
BEGIN DESCRIPTION:
Mapping XS c6f6e06f
END DESCRIPTION:
XS GIS Cut Line= 2
      1991235.50     13499971.83      1991179.10     13498119.29
#Sta/Elev= 30
  4161.5  487.71  4428.5  487.84  4458.5  489.03  4488.5  487.88  4608.5  487.48
  4708.6  485.53  4978.2  473.83  4979.1  473.33  5014.9  473.83  5098.8  474.67
  5139.4  476.53  5234.3  482.10  5363.5  482.83  5418.9  482.71  5509.0  484.57
  5589.0  487.14  5626.3  489.80  5649.0  490.55  5689.0  495.29  5739.1  497.56
  5759.1  502.17  5769.1  501.27  5789.1  496.46  5809.1  501.94  5829.1  504.26
  5849.1  500.12  5879.1  501.43  5909.1  499.69  5989.7  499.50  6014.9  497.46
#Mann=7,-1,0
  4161.5     0.1       0  4978.2    0.07       0  5014.9     0.1       0
  5139.4    0.07       0  5234.3     0.1       0  5363.5    0.05       0
  5626.3     0.1       0
Bank Sta=4978.2,5014.9
Exp/Cntr=0.3,0.1

Type RM Length L Ch R = 1,3484,922,922,922
BEGIN DESCRIPTION:
Mapping XS cfc462db
END DESCRIPTION:
XS GIS Cut Line= 3
      1992181.69     13499780.90      1992016.75     13499550.86
      1991925.60     13497823.42
#Sta/Elev= 30
  4201.3  483.83  4295.4  482.94  4425.6  483.01  4446.5  482.06  4510.3  482.92
  4608.9  481.60  4660.5  482.17  4740.6  481.27  4840.7  479.07  4940.9  474.59
  5002.6  473.34  5003.5  472.84  5039.4  473.34  5121.1  474.70  5241.3  479.47
  5369.0  481.63  5374.0  480.98  5511.6  484.19  5559.1  484.67  5564.1  483.48
  5721.9  486.72  5749.1  486.91  5754.1  485.84  5902.2  489.68  5939.1  489.73
  5944.1  489.08  6042.4  490.90  6129.1  491.33  6134.1  490.69  6214.2  492.75
#Mann=3,-1,0
  4201.3     0.1       0  5002.6    0.07       0  5039.4     0.1       0
Bank Sta=5002.6,5039.4
Exp/Cntr=0.3,0.1

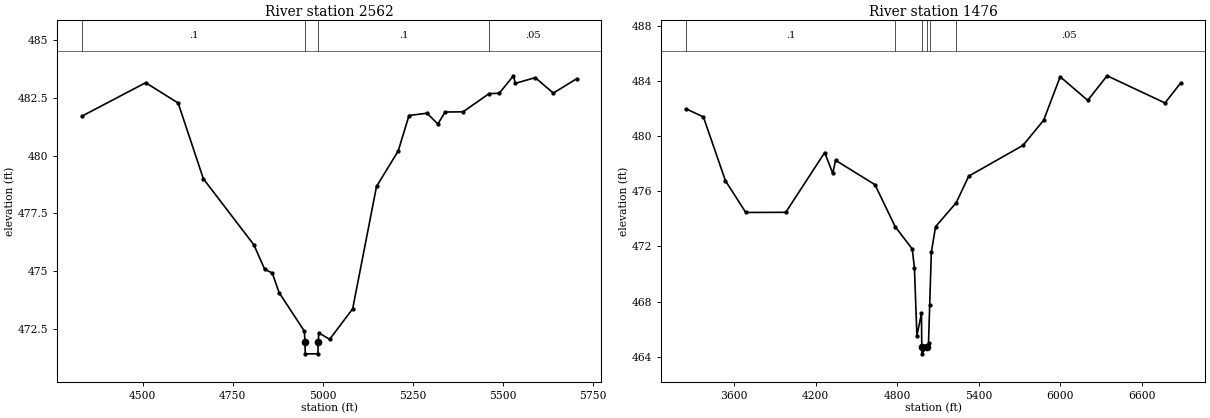
Type RM Length L Ch R = 1,2562,1086,1086,1086
BEGIN DESCRIPTION:
Mapping XS 3b1ff324
END DESCRIPTION:
XS GIS Cut Line= 2
      1992933.21     13499791.90      1992872.44     13498420.34
#Sta/Elev= 30
  4331.5  481.71  4508.6  483.16  4598.7  482.28  4668.7  479.00  4808.9  476.14
  4838.9  475.08  4859.9  474.92  4878.9  474.07  4949.0  472.40  4950.6  471.92
  4951.5  471.42  4986.5  471.42  4987.4  471.92  4989.0  472.33  5019.1  472.05
  5083.0  473.37  5149.2  478.67  5209.3  480.20  5239.3  481.74  5289.3  481.84
  5319.4  481.37  5339.4  481.89  5389.4  481.90  5461.8  482.69  5489.5  482.70
  5529.1  483.46  5534.1  483.13  5589.6  483.38  5639.7  482.71  5704.4  483.33
#Mann=4,-1,0
  4331.5     0.1       0  4950.6    0.07       0  4987.4     0.1       0
  5461.8    0.05       0
Bank Sta=4950.6,4987.4
Exp/Cntr=0.3,0.1

Type RM Length L Ch R = 1,1476,0,0,0
BEGIN DESCRIPTION:
UNT 004 in BCW 1.0
END DESCRIPTION:
XS GIS Cut Line= 4
      1992808.71     13500081.09      1993740.50     13499661.69
      1994070.36     13498455.09      1992720.23     13498230.40
#Sta/Elev= 30
  3244.7  481.97  3373.4  481.38  3535.5  476.76  3685.3  474.46  3979.6  474.47
  4266.2  478.80  4325.3  477.29  4346.0  478.24  4636.3  476.47  4784.9  473.43
  4910.2  471.82  4926.6  470.45  4944.7  465.52  4978.4  467.15  4980.6  464.72
  4981.5  464.22  5017.6  464.72  5030.2  465.00  5039.0  467.76  5051.0  471.58
  5082.1  473.43  5234.3  475.17  5326.1  477.09  5725.6  479.32  5877.6  481.14
  5999.3  484.29  6202.0  482.58  6344.7  484.36  6770.8  482.39  6886.1  483.84
#Mann=6,-1,0
  3244.7     0.1       0  4784.9    0.16       0  4980.6    0.07       0
  5017.6    0.16       0  5039.0     0.1       0  5234.3    0.05       0
Bank Sta=4980.6,5017.6
Exp/Cntr=0.3,0.1

Chan Stop Cuts=-1