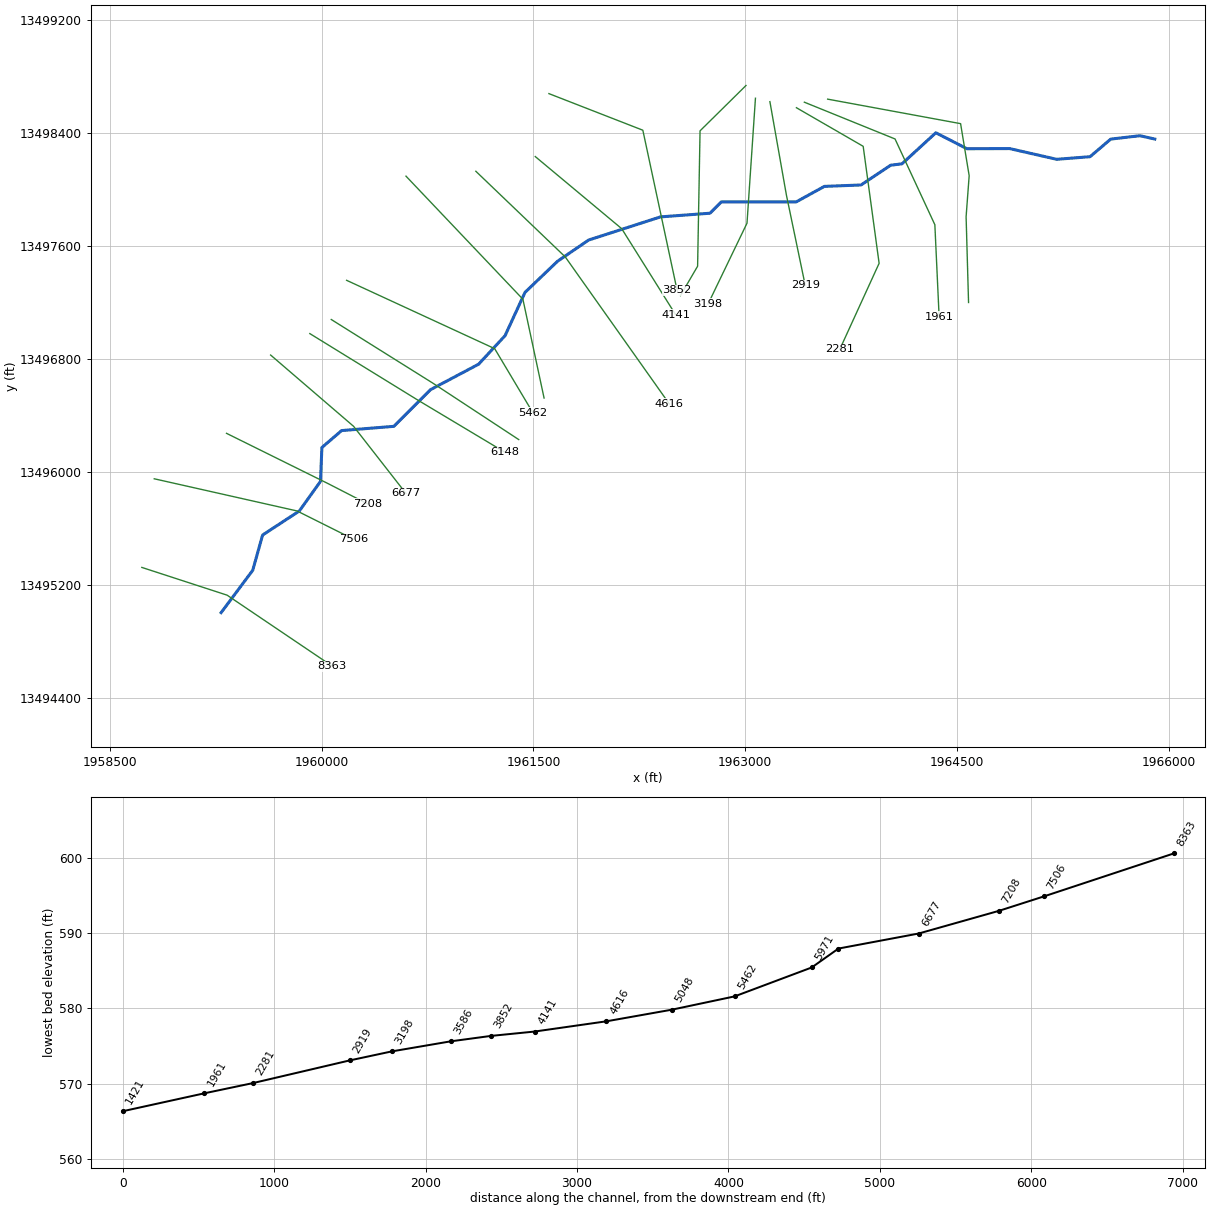
--- UNT 005 in BCW.prj (project) ---

Proj Title=UNT 005 in BCW Base Level Engineering
Current Plan=p01
Default Exp/Contr=0.3,0.1
English Units
Geom File=g01
Flow File=f01
Plan File=p01
BEGIN DESCRIPTION:
UNT 005 in BCW
END DESCRIPTION:

--- UNT 005 in BCW.p01 (plan) ---

Plan Title=Multiple Run
Short Identifier=Multiple
Geom File=g01
Flow File=f01
Subcritical Flow
K Sum by GR= 0
Std Step Tol= 0.01
Critical Tol= 0.01
Num of Std Step Trials= 20
Max Error Tol= 0.3
Flow Tol Ratio= 0.001
Split Flow NTrial= 30
Split Flow Tol= 0.02
Split Flow Ratio= 0.02
Log Output Level= 0
Friction Slope Method= 1
Unsteady Friction Slope Method= 2
Unsteady Bridges Friction Slope Method= 1
Parabolic Critical Depth
Global Vel Dist=  1 , 1 , 1
Global Log Level= 0
CheckData=True
Encroach Param= -1, 0, 0, 0
BEGIN DESCRIPTION:
Multiple Run
END DESCRIPTION:

--- UNT 005 in BCW.f01 (steady flow) ---

Flow Title=Multiple
Number of Profiles=7
Profile Names=10-year,25-year,50-year,1pct_min,100-year,1pct_plu,500-year
River Rch & RM= UNT 005 in BCW,Reach-1,8363
     153     210     258     158     316     630     482
River Rch & RM= UNT 005 in BCW,Reach-1,7506
     175     241     297     183     364     727     559
River Rch & RM= UNT 005 in BCW,Reach-1,4616
     221     309     382     237     472     942     734
Boundary for River Rch & Prof#=UNT 005 in BCW,Reach-1,1
Up Type=0
Dn Type=3
Dn Slope=0.005
Boundary for River Rch & Prof#=UNT 005 in BCW,Reach-1,2
Up Type=0
Dn Type=3
Dn Slope=0.005
Boundary for River Rch & Prof#=UNT 005 in BCW,Reach-1,3
Up Type=0
Dn Type=3
Dn Slope=0.005
Boundary for River Rch & Prof#=UNT 005 in BCW,Reach-1,4
Up Type=0
Dn Type=3
Dn Slope=0.005
Boundary for River Rch & Prof#=UNT 005 in BCW,Reach-1,5
Up Type=0
Dn Type=3
Dn Slope=0.005
Boundary for River Rch & Prof#=UNT 005 in BCW,Reach-1,6
Up Type=0
Dn Type=3
Dn Slope=0.005
Boundary for River Rch & Prof#=UNT 005 in BCW,Reach-1,7
Up Type=0
Dn Type=3
Dn Slope=0.005

--- UNT 005 in BCW.g01 (geometry) ---

Geom Title=Existing Conditions

River Reach=UNT 005 in BCW,Reach-1
Reach XY= 30
      1959286.78     13495004.54      1959510.80     13495304.54
      1959580.80     13495554.54      1959840.80     13495724.54
      1959990.80     13495934.54      1960000.80     13496174.54
      1960140.80     13496294.54      1960510.80     13496324.54
      1960770.80     13496584.54      1961110.80     13496764.54
      1961298.58     13496966.97      1961439.86     13497273.60
      1961670.80     13497494.54      1961890.80     13497644.54
      1962399.83     13497808.51      1962750.80     13497834.54
      1962830.80     13497914.54      1963360.80     13497914.54
      1963560.80     13498024.54      1963820.80     13498034.54
      1964030.80     13498174.54      1964110.80     13498184.54
      1964350.80     13498404.54      1964571.05     13498291.37
      1964873.78     13498292.45      1965206.90     13498216.50
      1965443.44     13498234.95      1965589.93     13498359.73
      1965797.18     13498383.60      1965901.85     13498359.87

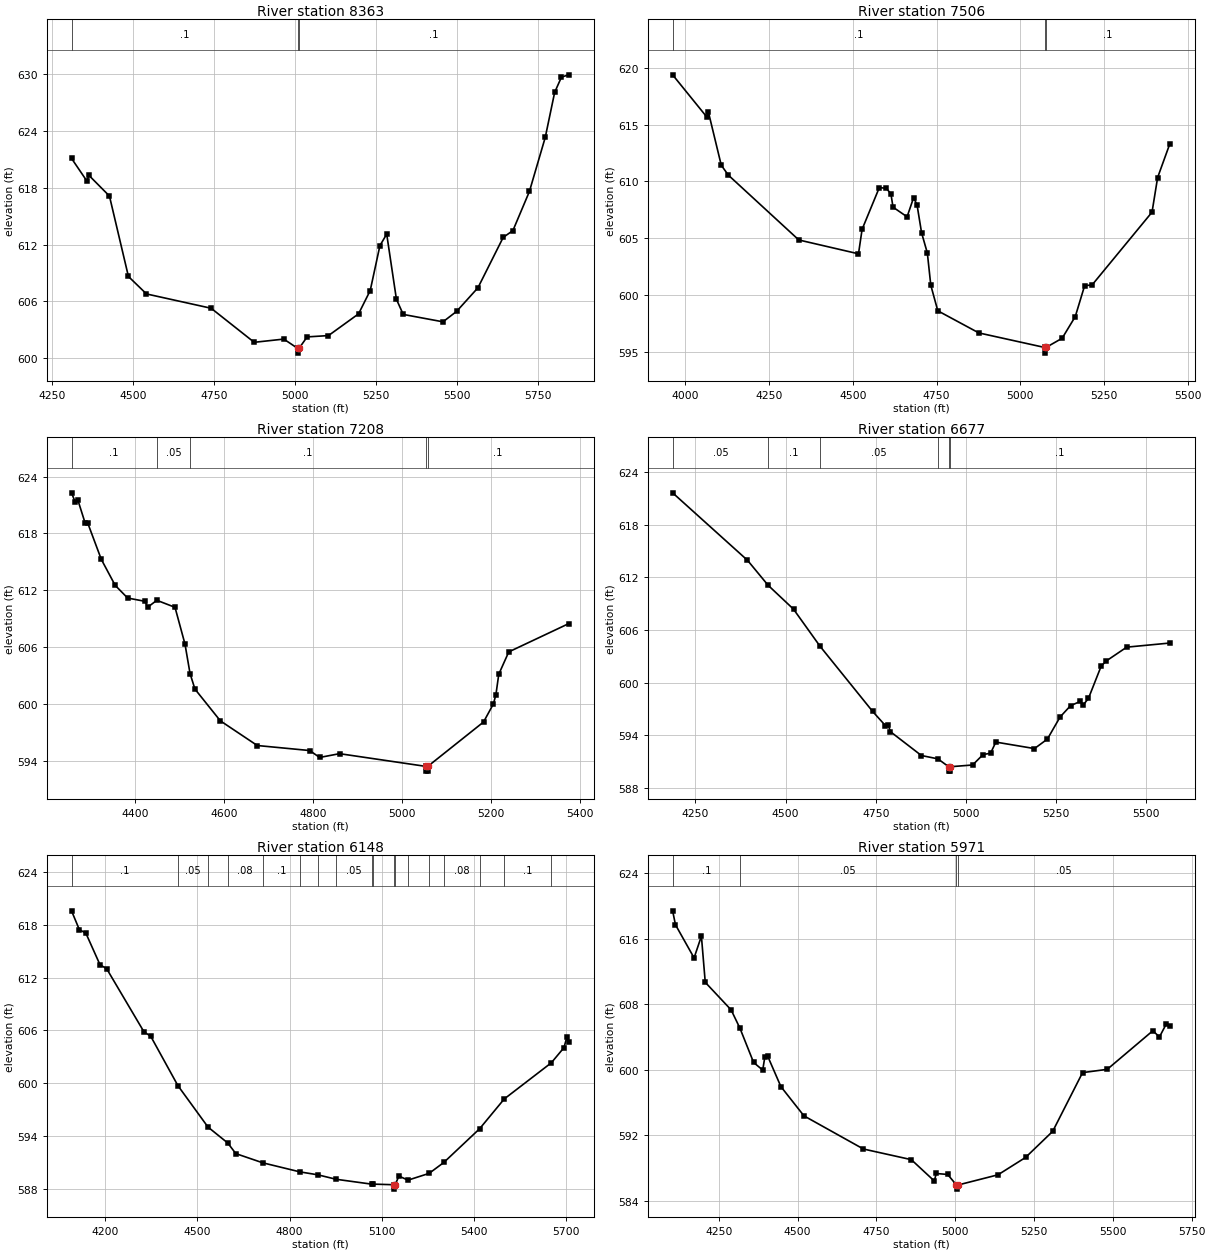
Type RM Length L Ch R = 1,8363,857,857,857
BEGIN DESCRIPTION:
UNT 005 in BCW 12.0
END DESCRIPTION:
XS GIS Cut Line= 3
      1958724.95     13495325.01      1959329.46     13495128.29
      1960074.98     13494625.02
#Sta/Elev= 30
  4310.2  621.08  4358.1  618.67  4363.4  619.31  4427.3  617.11  4485.9  608.63
  4541.6  606.79  4741.3  605.28  4874.3  601.69  4965.7  602.03  5008.6  601.05
  5008.9  600.55  5012.6  601.05  5037.7  602.26  5103.6  602.40  5196.5  604.69
  5232.5  607.15  5262.4  611.88  5283.4  613.10  5313.4  606.23  5334.4  604.63
  5457.2  603.85  5499.2  604.95  5565.1  607.44  5643.1  612.75  5673.1  613.47
  5724.0  617.59  5773.0  623.30  5802.0  628.04  5823.0  629.65  5845.4  629.89
#Mann=3,-1,0
  4310.2     0.1       0  5008.6    0.07       0  5012.6     0.1       0
Bank Sta=5008.6,5012.6
Exp/Cntr=0.3,0.1

Type RM Length L Ch R = 1,7506,298,298,298
BEGIN DESCRIPTION:
UNT 005 in BCW 11.0
END DESCRIPTION:
XS GIS Cut Line= 3
      1958812.99     13495952.94      1959825.00     13495725.00
      1960225.02     13495524.99
#Sta/Elev= 30
  3961.6  619.38  4063.5  615.67  4068.7  616.07  4106.8  611.42  4127.7  610.55
  4338.4  604.83  4516.6  603.61  4527.4  605.77  4578.7  609.44  4599.2  609.39
  4613.4  608.90  4619.7  607.72  4661.7  606.87  4681.2  608.56  4691.5  607.91
  4705.0  605.46  4722.2  603.68  4732.5  600.84  4753.4  598.59  4876.0  596.64
  5072.3  595.36  5072.6  594.86  5076.5  595.36  5124.7  596.17  5163.9  598.08
  5191.8  600.80  5214.2  600.87  5393.1  607.28  5409.8  610.33  5446.2  613.30
#Mann=3,-1,0
  3961.6     0.1       0  5072.3    0.07       0  5076.5     0.1       0
Bank Sta=5072.3,5076.5
Exp/Cntr=0.3,0.1

Type RM Length L Ch R = 1,7208,531,531,531
BEGIN DESCRIPTION:
UNT 005 in BCW 10.0
END DESCRIPTION:
XS GIS Cut Line= 3
      1959325.03     13496274.99      1960045.61     13495918.23
      1960324.98     13495775.01
#Sta/Elev= 30
  4257.1  622.28  4265.5  621.29  4271.1  621.56  4287.9  619.06  4293.5  619.10
  4324.0  615.27  4355.2  612.53  4383.2  611.19  4422.5  610.84  4428.1  610.21
  4448.9  610.95  4489.8  610.21  4512.2  606.34  4523.6  603.23  4534.6  601.59
  4591.8  598.24  4674.8  595.64  4792.7  595.11  4815.0  594.38  4859.8  594.78
  5053.9  593.44  5054.2  592.94  5057.9  592.94  5058.2  593.44  5183.6  598.12
  5205.8  600.03  5211.4  601.00  5217.8  603.15  5240.3  605.51  5375.1  608.49
#Mann=5,-1,0
  4257.1     0.1       0  4448.9    0.05       0  4523.6     0.1       0
  5053.9    0.07       0  5058.2     0.1       0
Bank Sta=5053.9,5058.2
Exp/Cntr=0.3,0.1

Type RM Length L Ch R = 1,6677,529,529,529
BEGIN DESCRIPTION:
UNT 005 in BCW 9.0
END DESCRIPTION:
XS GIS Cut Line= 3
      1959637.59     13496829.71      1960225.00     13496325.00
      1960596.37     13495849.36
#Sta/Elev= 30
  4186.9  621.65  4394.4  613.96  4451.6  611.11  4521.9  608.39  4595.5  604.16
  4741.3  596.73  4776.8  595.11  4784.1  595.19  4790.7  594.42  4876.3  591.71
  4922.0  591.33  4952.0  590.43  4952.3  589.93  4956.1  589.93  4956.4  590.43
  5018.3  590.63  5047.3  591.82  5068.1  591.97  5082.6  593.24  5189.7  592.50
  5225.5  593.58  5260.7  596.10  5289.7  597.39  5316.8  597.88  5324.9  597.47
  5339.4  598.23  5374.7  601.91  5389.2  602.50  5445.3  604.06  5564.8  604.53
#Mann=6,-1,0
  4186.9    0.05       0  4451.6     0.1       0  4595.5    0.05       0
  4922.0     0.1       0  4952.0    0.07       0  4956.4     0.1       0
Bank Sta=4952,4956.4
Exp/Cntr=0.3,0.1

Type RM Length L Ch R = 1,6148,177,177,177
BEGIN DESCRIPTION:
UNT 005 in BCW 8.0
END DESCRIPTION:
XS GIS Cut Line= 3
      1959915.43     13496981.58      1960683.63     13496508.50
      1961299.62     13496139.77
#Sta/Elev= 30
  4089.7  619.60  4115.2  617.46  4136.4  617.06  4182.7  613.45  4203.9  613.03
  4325.8  605.83  4347.6  605.34  4436.4  599.71  4534.4  595.00  4598.7  593.19
  4625.1  591.98  4713.2  590.93  4834.2  589.90  4892.1  589.57  4952.0  589.06
  5069.1  588.50  5072.4  588.51  5139.7  588.44  5140.0  587.94  5144.2  588.44
  5156.6  589.43  5185.9  588.96  5254.8  589.73  5302.7  590.97  5419.5  594.81
  5499.8  598.20  5653.1  602.31  5694.2  604.03  5704.0  605.24  5709.8  604.70
#Mann=18,-1,0
  4089.7     0.1       0  4436.4    0.05       0  4534.4     0.1       0
  4598.7    0.08       0  4713.2     0.1       0  4834.2    0.08       0
  4892.1     0.1       0  4952.0    0.05       0  5069.1    0.08       0
  5072.4     0.1       0  5139.7    0.04       0  5144.2     0.1       0
  5185.9    0.08       0  5254.8     0.1       0  5302.7    0.08       0
  5419.5    0.05       0  5499.8     0.1       0  5653.1    0.08       0
Bank Sta=5139.7,5144.2
Exp/Cntr=0.3,0.1

Type RM Length L Ch R = 1,5971,509,509,509
BEGIN DESCRIPTION:
UNT 005 in BCW 7.0
END DESCRIPTION:
XS GIS Cut Line= 3
      1960067.33     13497081.41      1960787.79     13496630.03
      1961395.45     13496230.71
#Sta/Elev= 30
  4103.4  619.42  4112.4  617.72  4171.5  613.67  4194.7  616.33  4206.9  610.69
  4289.0  607.32  4317.1  605.07  4360.3  600.90  4389.2  599.97  4395.7  601.51
  4404.5  601.71  4446.9  597.95  4520.0  594.38  4708.6  590.33  4860.6  589.03
  4933.7  586.42  4939.6  587.34  4976.0  587.22  5003.9  585.93  5004.2  585.43
  5008.4  585.93  5135.7  587.18  5223.1  589.30  5309.2  592.49  5403.9  599.66
  5482.2  600.06  5626.8  604.77  5647.9  604.02  5669.0  605.57  5680.7  605.30
#Mann=4,-1,0
  4103.4     0.1       0  4317.1    0.05       0  5003.9   0.035       0
  5008.4    0.05       0
Bank Sta=5003.9,5008.4
Exp/Cntr=0.3,0.1

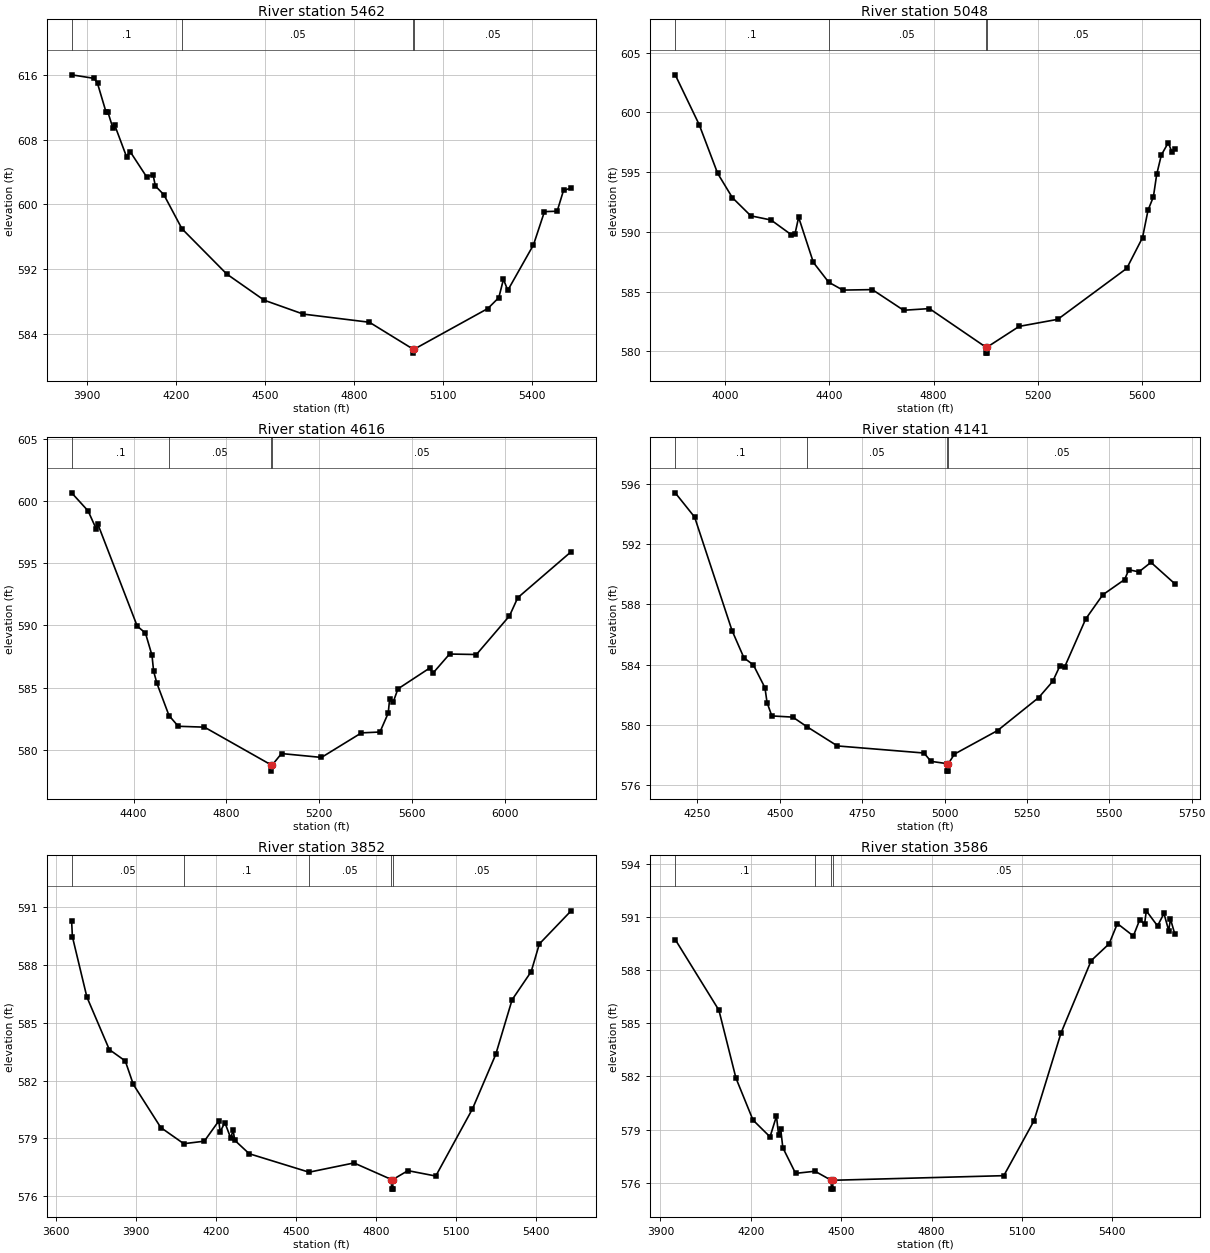
Type RM Length L Ch R = 1,5462,414,414,414
BEGIN DESCRIPTION:
UNT 005 in BCW 6.0
END DESCRIPTION:
XS GIS Cut Line= 3
      1960175.82     13497359.19      1961225.00     13496875.00
      1961495.27     13496421.67
#Sta/Elev= 30
  3847.3  616.04  3923.5  615.60  3934.5  614.98  3963.4  611.41  3968.9  611.50
  3986.3  609.45  3991.8  609.88  4032.2  605.92  4044.6  606.53  4099.7  603.43
  4121.7  603.67  4129.5  602.28  4158.0  601.21  4219.1  596.99  4370.0  591.39
  4496.2  588.15  4627.9  586.43  4850.9  585.42  4997.8  582.10  4998.1  581.60
  5002.3  582.10  5250.0  587.12  5287.0  588.47  5302.6  590.74  5317.2  589.37
  5403.8  595.00  5440.8  599.11  5483.6  599.16  5505.0  601.73  5530.6  602.03
#Mann=4,-1,0
  3847.3     0.1       0  4219.1    0.05       0  4997.8   0.035       0
  5002.3    0.05       0
Bank Sta=4997.8,5002.3
Exp/Cntr=0.3,0.1

Type RM Length L Ch R = 1,5048,432,432,432
BEGIN DESCRIPTION:
UNT 005 in BCW 5.0
END DESCRIPTION:
XS GIS Cut Line= 3
      1960596.79     13498097.08      1961425.00     13497225.00
      1961575.00     13496524.98
#Sta/Elev= 30
  3807.4  603.15  3899.6  598.97  3970.3  594.90  4027.0  592.86  4097.7  591.34
  4175.4  590.99  4253.1  589.76  4267.3  589.81  4281.4  591.22  4338.0  587.44
  4396.9  585.78  4451.3  585.12  4564.5  585.16  4684.7  583.43  4783.8  583.57
  5000.7  580.34  5001.0  579.84  5005.0  579.84  5005.3  580.34  5128.6  582.08
  5276.8  582.67  5541.9  586.94  5602.4  589.51  5623.7  591.82  5644.2  592.93
  5656.9  594.81  5674.8  596.44  5701.3  597.46  5715.8  596.66  5726.0  596.91
#Mann=4,-1,0
  3807.4     0.1       0  4396.9    0.05       0  5000.7   0.035       0
  5005.3    0.05       0
Bank Sta=5000.7,5005.3
Exp/Cntr=0.3,0.1

Type RM Length L Ch R = 1,4616,475,475,475
BEGIN DESCRIPTION:
UNT 005 in BCW 4.0
END DESCRIPTION:
XS GIS Cut Line= 3
      1961091.62     13498131.76      1961725.00     13497525.00
      1962463.13     13496482.47
#Sta/Elev= 30
  4132.6  600.64  4203.5  599.19  4238.7  597.74  4246.0  598.11  4415.5  589.94
  4451.0  589.38  4479.3  587.59  4486.2  586.32  4500.4  585.35  4552.6  582.76
  4592.5  581.90  4705.5  581.83  4993.3  578.80  4993.7  578.30  4998.1  578.80
  5038.0  579.71  5210.3  579.40  5382.6  581.37  5462.6  581.44  5498.3  582.96
  5504.4  584.11  5519.2  583.82  5540.1  584.90  5676.7  586.57  5691.5  586.17
  5762.9  587.70  5878.6  587.66  6021.3  590.76  6057.0  592.22  6287.1  595.91
#Mann=4,-1,0
  4132.6     0.1       0  4552.6    0.05       0  4993.3   0.035       0
  4998.1    0.05       0
Bank Sta=4993.3,4998.1
Exp/Cntr=0.3,0.1

Type RM Length L Ch R = 1,4141,289,289,289
BEGIN DESCRIPTION:
UNT 005 in BCW 3.0
END DESCRIPTION:
XS GIS Cut Line= 3
      1961512.63     13498235.92      1962125.00     13497725.00
      1962506.52     13497116.18
#Sta/Elev= 30
  4182.5  595.39  4241.4  593.78  4354.9  586.26  4391.1  584.45  4419.7  583.98
  4454.8  582.47  4461.3  581.48  4475.7  580.60  4539.4  580.52  4581.9  579.89
  4674.8  578.61  4937.7  578.14  4958.5  577.59  5006.2  577.44  5006.6  576.94
  5011.2  576.94  5011.6  577.44  5030.1  578.07  5160.9  579.63  5285.9  581.82
  5328.3  582.89  5349.5  583.89  5364.8  583.86  5428.5  587.03  5480.3  588.63
  5546.5  589.64  5559.3  590.29  5589.9  590.15  5626.5  590.78  5698.5  589.37
#Mann=4,-1,0
  4182.5     0.1       0  4581.9    0.05       0  5006.2   0.035       0
  5011.6    0.05       0
Bank Sta=5006.2,5011.6
Exp/Cntr=0.3,0.1

Type RM Length L Ch R = 1,3852,266,266,266
BEGIN DESCRIPTION:
Mapping XS 7a233a86
END DESCRIPTION:
XS GIS Cut Line= 3
      1961609.38     13498681.81      1962274.77     13498422.57
      1962517.53     13497288.57
#Sta/Elev= 30
  3658.4  590.28  3661.2  589.48  3715.6  586.34  3799.8  583.61  3859.6  583.02
  3889.8  581.80  3992.8  579.56  4079.2  578.72  4156.0  578.85  4210.4  579.90
  4215.7  579.34  4233.2  579.82  4254.7  579.03  4264.7  579.41  4270.1  578.90
  4324.5  578.20  4549.2  577.24  4717.7  577.72  4858.1  576.86  4858.6  576.36
  4863.2  576.36  4863.6  576.86  4920.1  577.32  5024.5  577.04  5162.2  580.53
  5249.5  583.36  5310.9  586.20  5382.4  587.66  5413.1  589.10  5532.2  590.82
#Mann=5,-1,0
  3658.4    0.05       0  4079.2     0.1       0  4549.2    0.05       0
  4858.1   0.035       0  4863.6    0.05       0
Bank Sta=4858.1,4863.6
Exp/Cntr=0.3,0.1

Type RM Length L Ch R = 1,3586,388,388,388
BEGIN DESCRIPTION:
Mapping XS 8359631f
END DESCRIPTION:
XS GIS Cut Line= 4
      1963005.66     13498739.39      1962680.16     13498418.23
      1962662.79     13497459.02      1962541.28     13497250.71
#Sta/Elev= 30
  3948.9  589.73  4093.9  585.74  4150.4  581.91  4207.0  579.54  4263.6  578.59
  4284.9  579.76  4291.9  578.70  4299.0  579.03  4306.0  577.98  4348.4  576.53
  4412.8  576.65  4466.7  576.14  4467.1  575.64  4471.7  575.64  4472.2  576.14
  5039.5  576.40  5139.5  579.49  5229.5  584.46  5329.6  588.54  5389.2  589.49
  5416.5  590.63  5469.5  589.93  5491.0  590.86  5506.7  590.59  5512.5  591.35
  5549.7  590.50  5571.2  591.20  5586.9  590.23  5592.7  590.89  5606.7  590.06
#Mann=4,-1,0
  3948.9     0.1       0  4412.8    0.05       0  4466.7   0.035       0
  4472.2    0.05       0
Bank Sta=4466.7,4472.2
Exp/Cntr=0.3,0.1

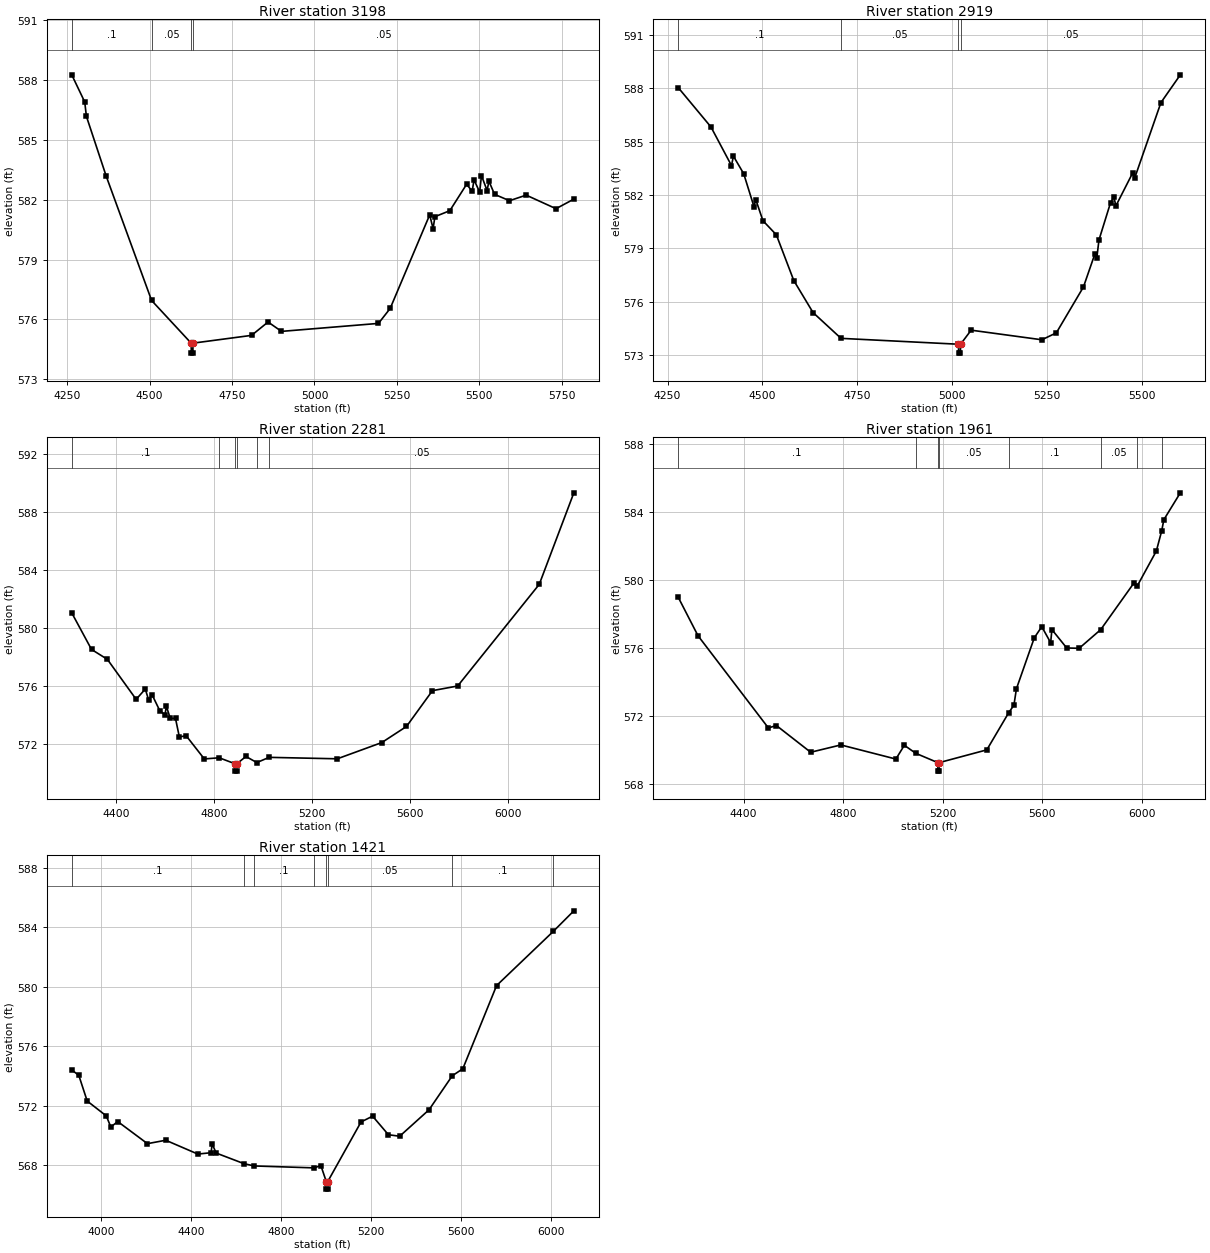
Type RM Length L Ch R = 1,3198,279,279,279
BEGIN DESCRIPTION:
Mapping XS 16a5dfcd
END DESCRIPTION:
XS GIS Cut Line= 3
      1963072.64     13498649.26      1963012.75     13497763.85
      1962736.70     13497190.92
#Sta/Elev= 30
  4263.6  588.26  4302.9  586.90  4308.0  586.18  4368.1  583.18  4505.8  576.95
  4625.9  574.81  4626.4  574.31  4631.0  574.31  4631.4  574.81  4809.1  575.20
  4859.2  575.87  4899.9  575.40  5194.2  575.80  5229.7  576.55  5349.6  581.24
  5359.9  580.55  5365.5  581.15  5410.7  581.45  5461.5  582.77  5478.6  582.43
  5484.1  583.00  5501.2  582.38  5506.7  583.21  5523.8  582.46  5529.3  582.93
  5546.4  582.27  5591.7  581.95  5642.4  582.23  5732.9  581.55  5787.0  582.03
#Mann=4,-1,0
  4263.6     0.1       0  4505.8    0.05       0  4625.9   0.035       0
  4631.4    0.05       0
Bank Sta=4625.9,4631.4
Exp/Cntr=0.3,0.1

Type RM Length L Ch R = 1,2919,638,638,638
BEGIN DESCRIPTION:
UNT 005 in BCW 2.0
END DESCRIPTION:
XS GIS Cut Line= 3
      1963174.99     13498625.03      1963292.13     13497962.50
      1963425.00     13497325.01
#Sta/Elev= 30
  4278.2  588.03  4364.5  585.82  4418.6  583.65  4423.7  584.18  4450.9  583.19
  4477.8  581.35  4482.8  581.73  4501.6  580.55  4536.9  579.76  4582.9  577.19
  4633.7  575.39  4707.5  573.94  5017.2  573.61  5017.7  573.11  5022.3  573.11
  5022.7  573.61  5050.6  574.40  5237.1  573.86  5275.3  574.25  5346.8  576.83
  5377.0  578.69  5382.1  578.48  5387.7  579.47  5418.3  581.57  5427.1  581.89
  5432.2  581.38  5477.1  583.26  5482.2  582.97  5551.1  587.19  5602.2  588.75
#Mann=4,-1,0
  4278.2     0.1       0  4707.5    0.05       0  5017.2   0.035       0
  5022.7    0.05       0
Bank Sta=5017.2,5022.7
Exp/Cntr=0.3,0.1

Type RM Length L Ch R = 1,2281,320,320,320
BEGIN DESCRIPTION:
Mapping XS 701086cd
END DESCRIPTION:
XS GIS Cut Line= 4
      1963362.86     13498581.98      1963835.97     13498308.54
      1963948.82     13497479.54      1963671.04     13496871.91
#Sta/Elev= 30
  4217.4  581.02  4298.1  578.50  4362.7  577.82  4480.4  575.06  4517.8  575.77
  4531.7  575.00  4545.1  575.39  4576.6  574.29  4598.1  573.99  4603.9  574.58
  4619.7  573.75  4641.2  573.74  4657.0  572.46  4684.3  572.56  4758.9  570.95
  4819.7  571.03  4885.7  570.61  4886.2  570.11  4890.9  570.11  4891.3  570.61
  4928.9  571.12  4973.5  570.70  5023.6  571.06  5302.3  570.96  5484.0  572.08
  5584.9  573.19  5690.9  575.66  5794.0  575.98  6127.3  582.99  6268.6  589.30
#Mann=6,-1,0
  4217.4     0.1       0  4819.7    0.05       0  4885.7    0.07       0
  4891.3    0.05       0  4973.5     0.1       0  5023.6    0.05       0
Bank Sta=4885.7,4891.3
Exp/Cntr=0.3,0.1

Type RM Length L Ch R = 1,1961,540,540,540
BEGIN DESCRIPTION:
Mapping XS d580fd70
END DESCRIPTION:
XS GIS Cut Line= 4
      1963419.32     13498621.03      1964061.66     13498360.62
      1964343.78     13497752.98      1964374.11     13497098.84
#Sta/Elev= 30
  4137.3  578.98  4216.7  576.72  4499.5  571.30  4531.9  571.44  4669.6  569.87
  4790.9  570.30  5012.0  569.47  5046.1  570.28  5091.6  569.81  5180.5  569.26
  5180.9  568.76  5185.6  568.76  5186.1  569.26  5377.5  570.01  5465.3  572.19
  5486.5  572.64  5496.5  573.60  5568.4  576.60  5598.4  577.25  5634.1  576.31
  5639.1  577.08  5698.6  576.00  5748.6  575.98  5835.4  577.08  5968.8  579.82
  5981.9  579.64  6058.9  581.70  6080.5  582.89  6089.0  583.54  6155.2  585.12
#Mann=8,-1,0
  4137.3     0.1       0  5091.6    0.05       0  5180.5    0.07       0
  5186.1    0.05       0  5465.3     0.1       0  5835.4    0.05       0
  5981.9     0.1       0  6080.5    0.05       0
Bank Sta=5180.5,5186.1
Exp/Cntr=0.3,0.1

Type RM Length L Ch R = 1,1421,0,0,0
BEGIN DESCRIPTION:
UNT 005 in BCW 1.0
END DESCRIPTION:
XS GIS Cut Line= 5
      1963584.28     13498642.73      1964526.07     13498469.13
      1964586.84     13498100.20      1964565.14     13497809.40
      1964582.50     13497201.81
#Sta/Elev= 30
  3869.0  574.40  3900.2  574.04  3937.5  572.31  4022.3  571.31  4042.6  570.56
  4073.1  570.93  4205.3  569.44  4286.6  569.67  4429.0  568.74  4487.9  568.83
  4493.0  569.43  4510.3  568.81  4634.9  568.09  4679.6  567.94  4946.2  567.81
  4975.8  567.97  5000.1  566.88  5000.6  566.38  5005.6  566.38  5006.1  566.88
  5154.3  570.90  5205.8  571.29  5276.0  570.04  5326.1  569.94  5456.5  571.72
  5559.8  574.01  5606.6  574.48  5756.7  580.08  6008.2  583.72  6100.0  585.11
#Mann=8,-1,0
  3869.0     0.1       0  4634.9    0.05       0  4679.6     0.1       0
  4946.2    0.05       0  5000.1   0.035       0  5006.1    0.05       0
  5559.8     0.1       0  6008.2    0.05       0
Bank Sta=5000.1,5006.1
Exp/Cntr=0.3,0.1

Chan Stop Cuts=-1