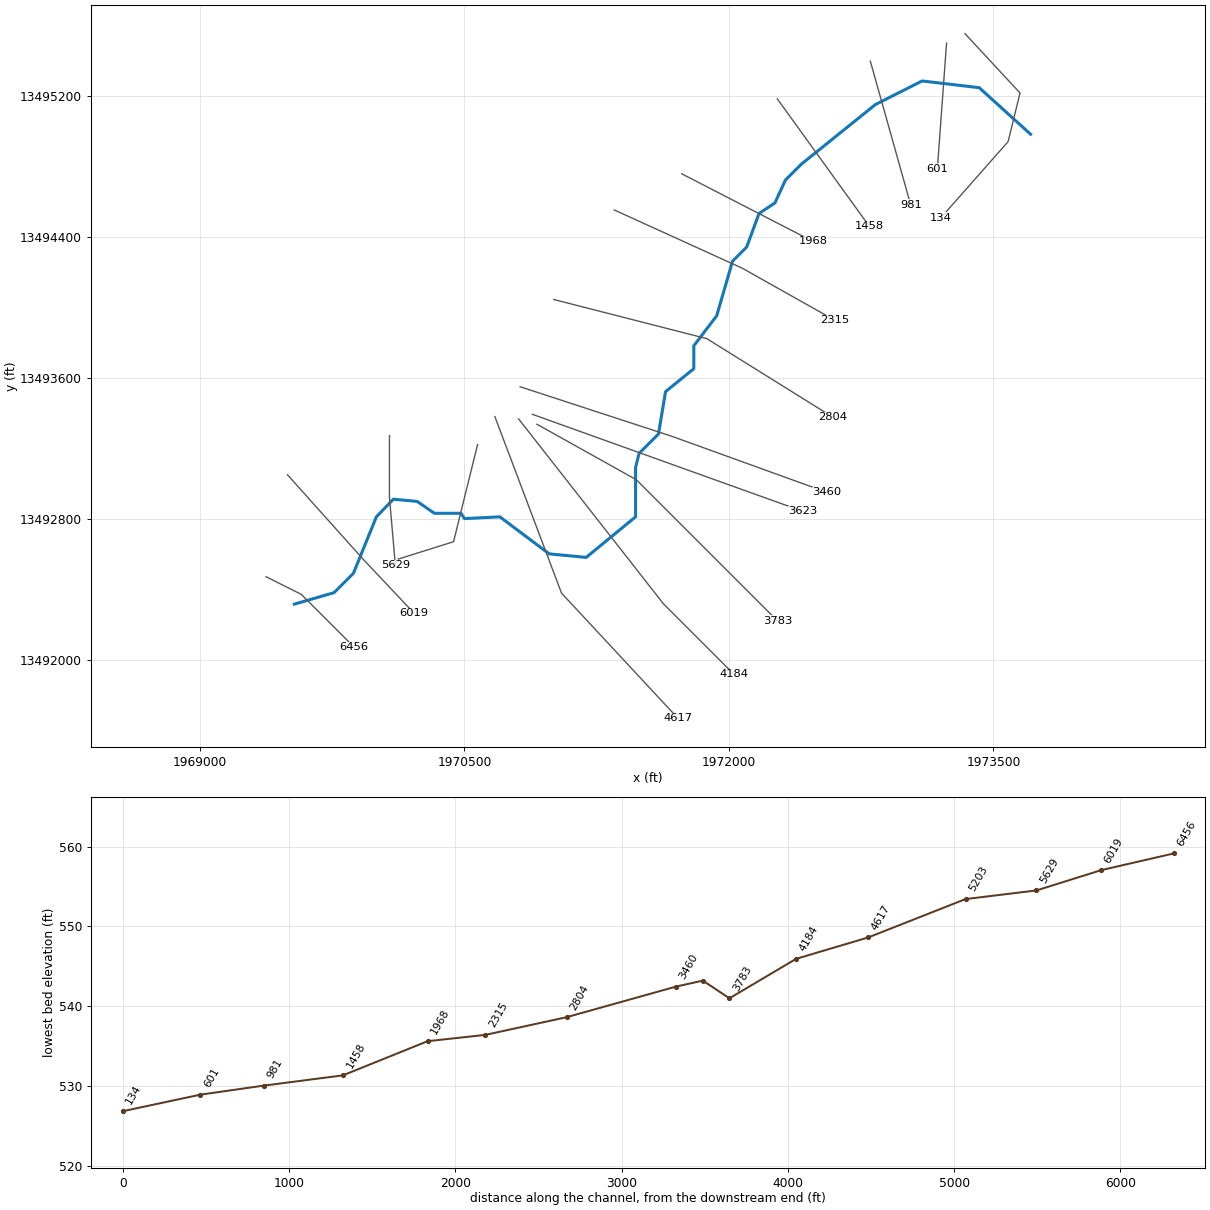
--- UNT 007 in BCW.prj (project) ---

Proj Title=UNT 007 in BCW Base Level Engineering
Current Plan=p01
Default Exp/Contr=0.3,0.1
English Units
Geom File=g01
Flow File=f01
Plan File=p01
BEGIN DESCRIPTION:
UNT 007 in BCW
END DESCRIPTION:

--- UNT 007 in BCW.p01 (plan) ---

Plan Title=Multiple Run
Short Identifier=Multiple
Geom File=g01
Flow File=f01
Subcritical Flow
K Sum by GR= 0
Std Step Tol= 0.01
Critical Tol= 0.01
Num of Std Step Trials= 20
Max Error Tol= 0.3
Flow Tol Ratio= 0.001
Split Flow NTrial= 30
Split Flow Tol= 0.02
Split Flow Ratio= 0.02
Log Output Level= 0
Friction Slope Method= 1
Unsteady Friction Slope Method= 2
Unsteady Bridges Friction Slope Method= 1
Parabolic Critical Depth
Global Vel Dist=  1 , 1 , 1
Global Log Level= 0
CheckData=True
Encroach Param= -1, 0, 0, 0
BEGIN DESCRIPTION:
Multiple Run
END DESCRIPTION:

--- UNT 007 in BCW.f01 (steady flow) ---

Flow Title=Multiple
Number of Profiles=7
Profile Names=10-year,25-year,50-year,1pct_min,100-year,1pct_plu,500-year
River Rch & RM= UNT 007 in BCW,Reach-1,6456
     153     210     257     158     315     628     480
River Rch & RM= UNT 007 in BCW,Reach-1,5629
     162     223     273     168     335     669     512
River Rch & RM= UNT 007 in BCW,Reach-1,4184
     215     300     371     229     457     913     707
Boundary for River Rch & Prof#=UNT 007 in BCW,Reach-1,1
Up Type=0
Dn Type=3
Dn Slope=0.005
Boundary for River Rch & Prof#=UNT 007 in BCW,Reach-1,2
Up Type=0
Dn Type=3
Dn Slope=0.005
Boundary for River Rch & Prof#=UNT 007 in BCW,Reach-1,3
Up Type=0
Dn Type=3
Dn Slope=0.005
Boundary for River Rch & Prof#=UNT 007 in BCW,Reach-1,4
Up Type=0
Dn Type=3
Dn Slope=0.005
Boundary for River Rch & Prof#=UNT 007 in BCW,Reach-1,5
Up Type=0
Dn Type=3
Dn Slope=0.005
Boundary for River Rch & Prof#=UNT 007 in BCW,Reach-1,6
Up Type=0
Dn Type=3
Dn Slope=0.005
Boundary for River Rch & Prof#=UNT 007 in BCW,Reach-1,7
Up Type=0
Dn Type=3
Dn Slope=0.005

--- UNT 007 in BCW.g01 (geometry) ---

Geom Title=Existing Conditions

River Reach=UNT 007 in BCW,Reach-1
Reach XY= 30
      1969535.80     13492319.54      1969760.80     13492384.54
      1969870.80     13492494.54      1970000.80     13492814.54
      1970097.42     13492914.52      1970232.14     13492902.02
      1970330.06     13492834.54      1970480.80     13492834.54
      1970500.80     13492804.54      1970700.80     13492814.54
      1970980.80     13492604.54      1971190.80     13492584.54
      1971470.80     13492814.54      1971470.80     13493094.54
      1971490.80     13493174.54      1971600.80     13493284.54
      1971640.80     13493524.54      1971800.80     13493654.54
      1971800.80     13493784.54      1971930.80     13493954.54
      1972020.80     13494264.54      1972100.80     13494344.54
      1972170.80     13494534.54      1972260.80     13494594.54
      1972320.80     13494724.54      1972410.80     13494814.54
      1972831.10     13495152.80      1973095.86     13495286.48
      1973419.64     13495248.29      1973710.80     13494984.54

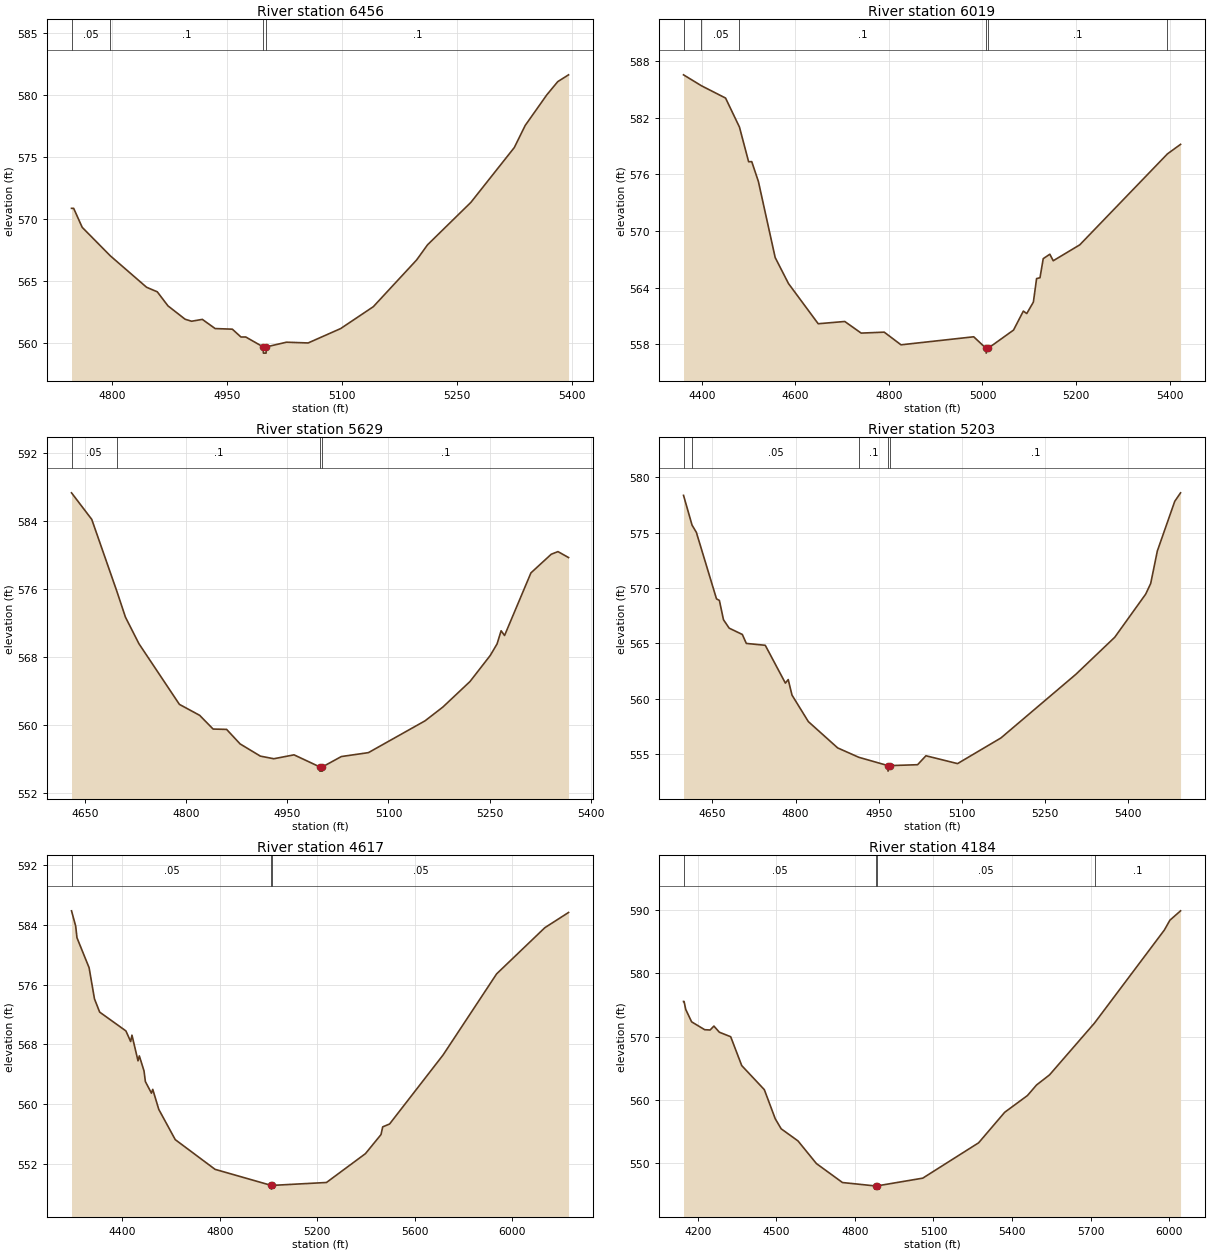
Type RM Length L Ch R = 1,6456,437,437,437
BEGIN DESCRIPTION:
UNT 007 in BCW 11.0
END DESCRIPTION:
XS GIS Cut Line= 3
      1969375.04     13492474.98      1969575.00     13492375.00
      1969874.98     13492075.02
#Sta/Elev= 30
  4747.5  570.84  4750.3  570.84  4761.4  569.31  4798.1  567.01  4845.3  564.48
  4859.3  564.11  4873.2  562.98  4895.6  561.90  4904.0  561.74  4918.0  561.89
  4934.7  561.15  4957.1  561.10  4968.3  560.47  4974.6  560.47  4997.3  559.67
  4997.6  559.17  5001.1  559.17  5001.3  559.67  5027.6  560.05  5055.9  559.99
  5098.3  561.15  5140.8  562.91  5197.3  566.68  5211.5  567.90  5268.0  571.32
  5324.6  575.74  5338.8  577.52  5367.0  579.99  5381.2  581.05  5395.3  581.60
#Mann=4,-1,0
  4747.5    0.05       0  4798.1     0.1       0  4997.3    0.07       0
  5001.3     0.1       0
Bank Sta=4997.3,5001.3
Exp/Cntr=0.3,0.1

Type RM Length L Ch R = 1,6019,390,390,390
BEGIN DESCRIPTION:
UNT 007 in BCW 10.0
END DESCRIPTION:
XS GIS Cut Line= 3
      1969496.64     13493053.13      1969925.00     13492575.00
      1970213.81     13492268.75
#Sta/Elev= 30
  4360.7  586.53  4399.1  585.37  4450.6  584.07  4480.3  581.00  4499.9  577.33
  4506.6  577.34  4520.8  575.24  4556.7  567.19  4585.1  564.44  4648.7  560.18
  4705.5  560.42  4740.6  559.19  4789.9  559.29  4825.8  557.95  4981.3  558.80
  5007.7  557.57  5008.0  557.07  5011.7  557.57  5066.4  559.51  5087.4  561.52
  5094.7  561.26  5108.9  562.48  5115.7  564.96  5123.0  565.05  5129.9  567.07
  5144.0  567.54  5151.3  566.85  5208.0  568.53  5395.5  578.16  5423.6  579.17
#Mann=6,-1,0
  4360.7     0.1       0  4399.1    0.05       0  4480.3     0.1       0
  5007.7    0.07       0  5011.7     0.1       0  5395.5    0.05       0
Bank Sta=5007.7,5011.7
Exp/Cntr=0.3,0.1

Type RM Length L Ch R = 1,5629,426,426,426
BEGIN DESCRIPTION:
UNT 007 in BCW 9.0
END DESCRIPTION:
XS GIS Cut Line= 3
      1970075.00     13493275.00      1970075.00     13492925.00
      1970108.58     13492539.36
#Sta/Elev= 30
  4630.0  587.33  4660.0  584.20  4697.5  575.66  4710.0  572.67  4730.0  569.54
  4790.0  562.39  4820.0  561.10  4840.0  559.48  4860.0  559.44  4880.0  557.73
  4910.0  556.29  4930.0  555.98  4960.0  556.44  4998.1  555.02  4998.3  554.52
  5001.8  554.52  5002.1  555.02  5030.2  556.24  5070.3  556.70  5154.3  560.45
  5180.8  562.08  5220.9  565.08  5251.0  568.16  5261.1  569.52  5267.1  571.07
  5272.2  570.51  5311.3  577.89  5341.4  580.09  5351.4  580.40  5367.1  579.70
#Mann=4,-1,0
  4630.0    0.05       0  4697.5     0.1       0  4998.1    0.07       0
  5002.1     0.1       0
Bank Sta=4998.1,5002.1
Exp/Cntr=0.3,0.1

Type RM Length L Ch R = 1,5203,586,586,586
BEGIN DESCRIPTION:
UNT 007 in BCW 8.0
END DESCRIPTION:
XS GIS Cut Line= 3
      1970574.99     13493224.96      1970438.49     13492673.35
      1970125.01     13492575.00
#Sta/Elev= 30
  4597.8  578.38  4613.2  575.69  4621.0  575.03  4657.3  569.02  4662.5  568.88
  4669.9  567.13  4680.2  566.37  4703.9  565.80  4711.1  564.99  4745.3  564.82
  4781.6  561.40  4786.7  561.72  4793.5  560.32  4823.0  557.92  4875.9  555.54
  4914.1  554.69  4966.6  553.94  4966.8  553.44  4970.7  553.94  5020.1  554.02
  5035.2  554.83  5092.2  554.12  5170.5  556.44  5305.8  562.20  5375.9  565.55
  5431.7  569.45  5440.7  570.41  5452.7  573.35  5484.1  577.84  5494.6  578.61
#Mann=5,-1,0
  4597.8     0.1       0  4613.2    0.05       0  4914.1     0.1       0
  4966.6    0.07       0  4970.7     0.1       0
Bank Sta=4966.6,4970.7
Exp/Cntr=0.3,0.1

Type RM Length L Ch R = 1,4617,433,433,433
BEGIN DESCRIPTION:
UNT 007 in BCW 7.0
END DESCRIPTION:
XS GIS Cut Line= 3
      1970672.86     13493383.00      1971050.87     13492381.94
      1971710.08     13491673.03
#Sta/Elev= 30
  4191.9  585.91  4209.0  583.86  4214.3  582.30  4264.0  578.29  4286.0  574.12
  4307.3  572.34  4414.9  569.82  4434.4  568.40  4439.8  569.25  4464.6  565.81
  4470.0  566.47  4489.1  564.47  4494.8  563.03  4519.6  561.48  4525.0  561.99
  4549.8  559.30  4617.3  555.25  4780.6  551.27  5010.8  549.12  5011.0  548.62
  5014.9  549.12  5237.3  549.51  5397.0  553.37  5461.0  555.93  5467.9  556.96
  5496.2  557.35  5715.6  566.60  5935.0  577.46  6132.8  583.65  6230.0  585.69
#Mann=3,-1,0
  4191.9    0.05       0  5010.8   0.035       0  5014.9    0.05       0
Bank Sta=5010.8,5014.9
Exp/Cntr=0.3,0.1

Type RM Length L Ch R = 1,4184,401,401,401
BEGIN DESCRIPTION:
UNT 007 in BCW 6.0
END DESCRIPTION:
XS GIS Cut Line= 3
      1970807.44     13493369.93      1971628.82     13492321.35
      1972028.84     13491921.33
#Sta/Elev= 30
  4145.8  575.54  4147.9  575.54  4154.2  574.29  4176.7  572.33  4226.5  571.09
  4247.3  571.04  4261.8  571.66  4282.6  570.69  4325.9  569.98  4368.0  565.43
  4454.3  561.63  4495.9  557.05  4518.5  555.46  4582.7  553.55  4653.2  549.97
  4752.7  546.98  4878.8  546.44  4879.1  545.94  4883.0  545.94  4883.3  546.44
  5059.2  547.67  5272.6  553.25  5372.0  558.06  5458.8  560.70  5493.7  562.37
  5543.2  563.96  5715.0  572.14  5981.6  586.81  6002.8  588.36  6043.5  589.84
#Mann=4,-1,0
  4145.8    0.05       0  4878.8   0.035       0  4883.3    0.05       0
  5715.0     0.1       0
Bank Sta=4878.8,4883.3
Exp/Cntr=0.3,0.1

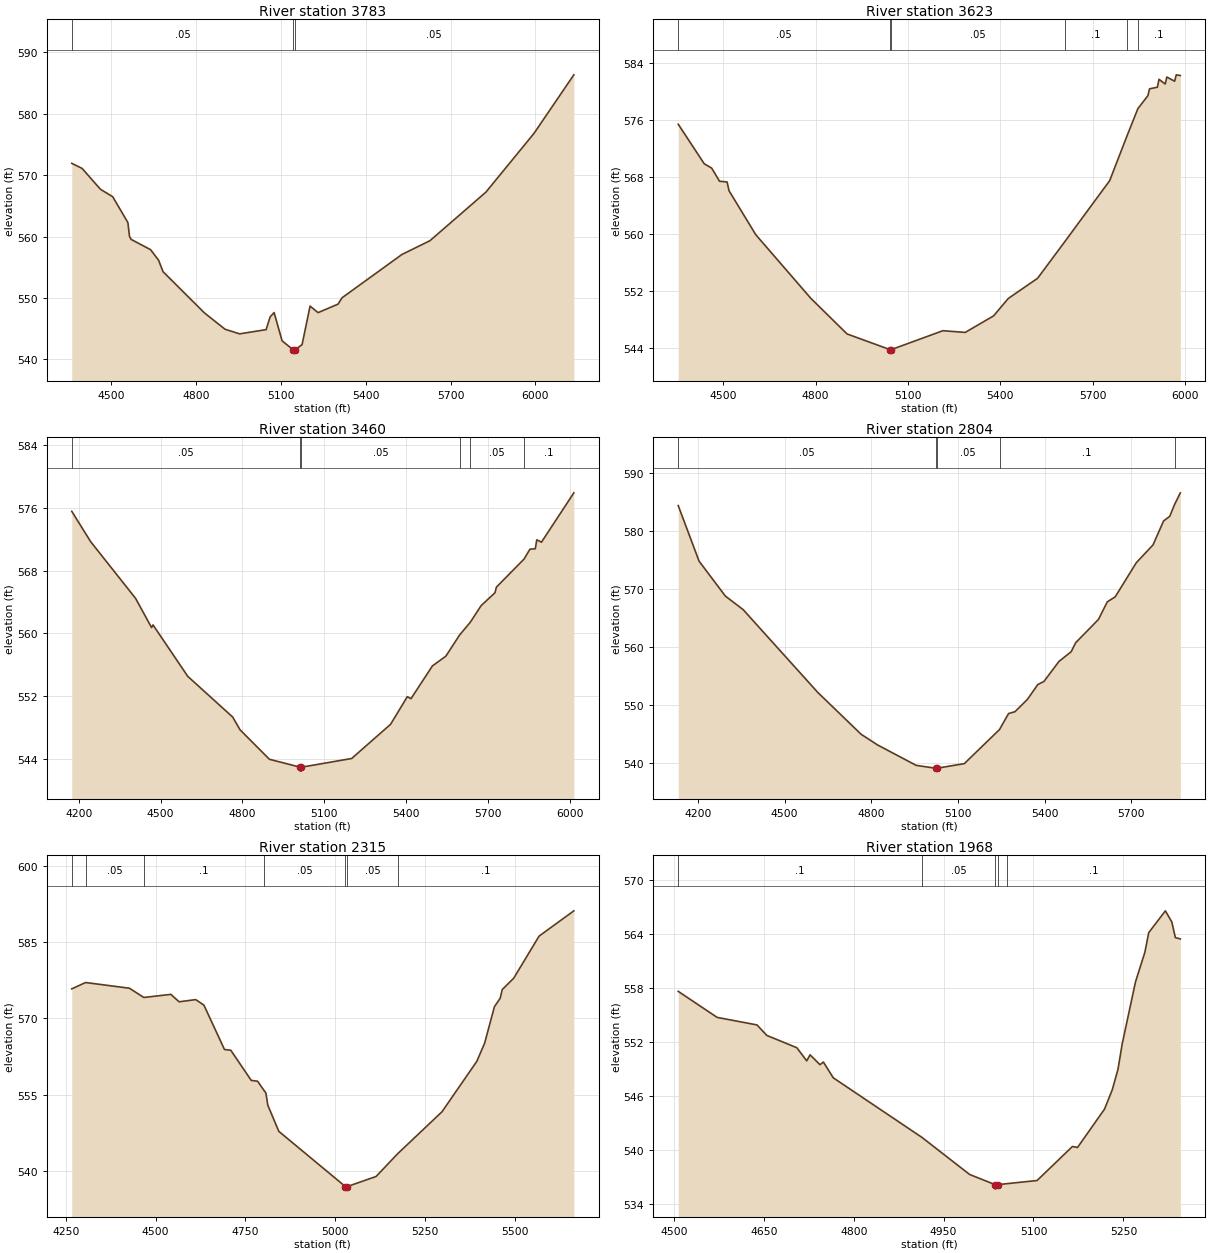
Type RM Length L Ch R = 1,3783,160,160,160
BEGIN DESCRIPTION:
UNT 007 in BCW 5.0
END DESCRIPTION:
XS GIS Cut Line= 3
      1970911.56     13493339.59      1971475.00     13493025.00
      1972275.01     13492224.99
#Sta/Elev= 30
  4359.5  571.93  4395.9  571.11  4461.0  567.70  4504.4  566.49  4558.1  562.27
  4563.8  560.04  4569.6  559.53  4638.3  557.86  4666.6  556.15  4682.6  554.26
  4828.9  547.55  4901.7  544.89  4953.4  544.13  5047.2  544.82  5061.4  546.89
  5075.5  547.60  5103.8  543.00  5143.9  541.49  5144.2  540.99  5148.5  541.49
  5174.5  542.38  5202.8  548.66  5231.1  547.59  5301.8  548.98  5315.9  550.01
  5528.1  557.08  5627.1  559.32  5825.1  567.24  5994.8  576.79  6136.2  586.36
#Mann=3,-1,0
  4359.5    0.05       0  5143.9   0.035       0  5148.5    0.05       0
Bank Sta=5143.9,5148.5
Exp/Cntr=0.3,0.1

Type RM Length L Ch R = 1,3623,163,163,163
BEGIN DESCRIPTION:
Mapping XS 1be8ba91
END DESCRIPTION:
XS GIS Cut Line= 2
      1970885.55     13493396.00      1972421.03     13492845.14
#Sta/Elev= 30
  4353.6  575.37  4438.0  569.82  4462.4  569.20  4487.8  567.36  4512.4  567.26
  4518.6  566.03  4605.5  559.85  4784.6  550.90  4902.3  545.90  5041.3  543.71
  5041.6  543.21  5045.9  543.71  5213.6  546.36  5286.0  546.12  5378.2  548.44
  5426.0  550.89  5521.3  553.73  5610.3  558.91  5755.4  567.44  5813.2  573.89
  5847.1  577.56  5879.6  579.38  5884.9  580.34  5910.4  580.57  5915.7  581.68
  5935.8  581.02  5941.1  582.00  5966.5  581.41  5971.8  582.31  5984.9  582.21
#Mann=6,-1,0
  4353.6    0.05       0  5041.3   0.035       0  5045.9    0.05       0
  5610.3     0.1       0  5813.2    0.05       0  5847.1     0.1       0
Bank Sta=5041.3,5045.9
Exp/Cntr=0.3,0.1

Type RM Length L Ch R = 1,3460,656,656,656
BEGIN DESCRIPTION:
UNT 007 in BCW 4.0
END DESCRIPTION:
XS GIS Cut Line= 3
      1970816.10     13493552.25      1971679.81     13493270.13
      1972556.50     13492953.31
#Sta/Elev= 30
  4174.5  575.57  4243.9  571.70  4408.6  564.47  4467.1  560.75  4472.4  561.09
  4599.9  554.53  4764.6  549.34  4791.2  547.73  4899.2  543.96  5012.1  542.95
  5012.4  542.45  5016.4  542.45  5016.7  542.95  5200.7  544.06  5343.4  548.42
  5404.7  551.94  5418.3  551.69  5496.7  555.86  5545.9  557.10  5596.8  559.82
  5634.8  561.39  5675.4  563.55  5726.1  565.19  5731.4  565.91  5832.9  569.49
  5854.2  570.74  5874.0  570.80  5879.4  571.94  5896.7  571.64  6015.3  577.93
#Mann=6,-1,0
  4174.5    0.05       0  5012.1   0.035       0  5016.7    0.05       0
  5596.8     0.1       0  5634.8    0.05       0  5832.9     0.1       0
Bank Sta=5012.1,5016.7
Exp/Cntr=0.3,0.1

Type RM Length L Ch R = 1,2804,489,489,489
BEGIN DESCRIPTION:
UNT 007 in BCW 3.0
END DESCRIPTION:
XS GIS Cut Line= 3
      1971007.02     13494047.06      1971875.00     13493825.00
      1972589.57     13493379.70
#Sta/Elev= 30
  4131.8  584.33  4203.9  574.77  4294.9  568.76  4356.8  566.41  4614.8  552.17
  4765.0  544.96  4821.3  543.14  4955.5  539.61  5022.8  539.12  5023.1  538.62
  5027.6  539.12  5122.0  539.91  5243.9  545.78  5275.2  548.53  5297.4  548.85
  5339.8  550.93  5376.4  553.52  5397.7  554.06  5449.6  557.50  5492.1  559.19
  5507.4  560.72  5586.5  564.74  5616.9  567.76  5644.3  568.62  5717.4  574.50
  5775.3  577.57  5811.8  581.69  5833.1  582.48  5849.6  584.49  5869.7  586.53
#Mann=5,-1,0
  4131.8    0.05       0  5022.8   0.035       0  5027.6    0.05       0
  5243.9     0.1       0  5849.6    0.05       0
Bank Sta=5022.8,5027.6
Exp/Cntr=0.3,0.1

Type RM Length L Ch R = 1,2315,347,347,347
BEGIN DESCRIPTION:
UNT 007 in BCW 2.0
END DESCRIPTION:
XS GIS Cut Line= 3
      1971349.97     13494554.85      1972075.00     13494225.00
      1972599.81     13493929.93
#Sta/Elev= 30
  4266.7  575.78  4305.2  577.03  4427.4  575.91  4467.4  574.09  4542.7  574.70
  4565.8  573.24  4611.9  573.67  4634.8  572.59  4692.1  563.86  4709.6  563.72
  4766.7  557.78  4784.3  557.62  4802.9  555.75  4807.4  555.32  4812.9  552.89
  4843.5  547.76  5029.0  536.90  5029.3  536.40  5033.8  536.90  5114.5  538.89
  5174.5  543.36  5298.1  551.62  5395.0  561.53  5416.7  565.08  5444.1  572.28
  5460.1  573.94  5465.8  575.64  5497.7  577.87  5568.4  586.15  5665.3  591.13
#Mann=7,-1,0
  4266.7     0.1       0  4305.2    0.05       0  4467.4     0.1       0
  4802.9    0.05       0  5029.0   0.035       0  5033.8    0.05       0
  5174.5     0.1       0
Bank Sta=5029,5033.8
Exp/Cntr=0.3,0.1

Type RM Length L Ch R = 1,1968,510,510,510
BEGIN DESCRIPTION:
Mapping XS 9b63d329
END DESCRIPTION:
XS GIS Cut Line= 2
      1971732.71     13494759.90      1972477.49     13494376.23
#Sta/Elev= 30
  4507.2  557.64  4572.1  554.74  4638.6  553.90  4655.1  552.73  4705.1  551.36
  4721.6  549.90  4727.2  550.57  4743.8  549.47  4749.4  549.77  4765.9  548.01
  4913.7  541.38  4993.5  537.24  5036.0  536.11  5036.4  535.61  5040.9  536.11
  5056.0  536.22  5106.0  536.57  5165.0  540.36  5173.5  540.25  5218.5  544.52
  5231.5  546.68  5241.0  548.96  5248.0  551.77  5270.2  558.69  5285.9  562.00
  5292.3  564.18  5320.1  566.61  5330.9  565.36  5336.7  563.63  5345.0  563.48
#Mann=5,-1,0
  4507.2     0.1       0  4913.7    0.05       0  5036.0   0.035       0
  5040.9    0.05       0  5056.0     0.1       0
Bank Sta=5036,5040.9
Exp/Cntr=0.3,0.1

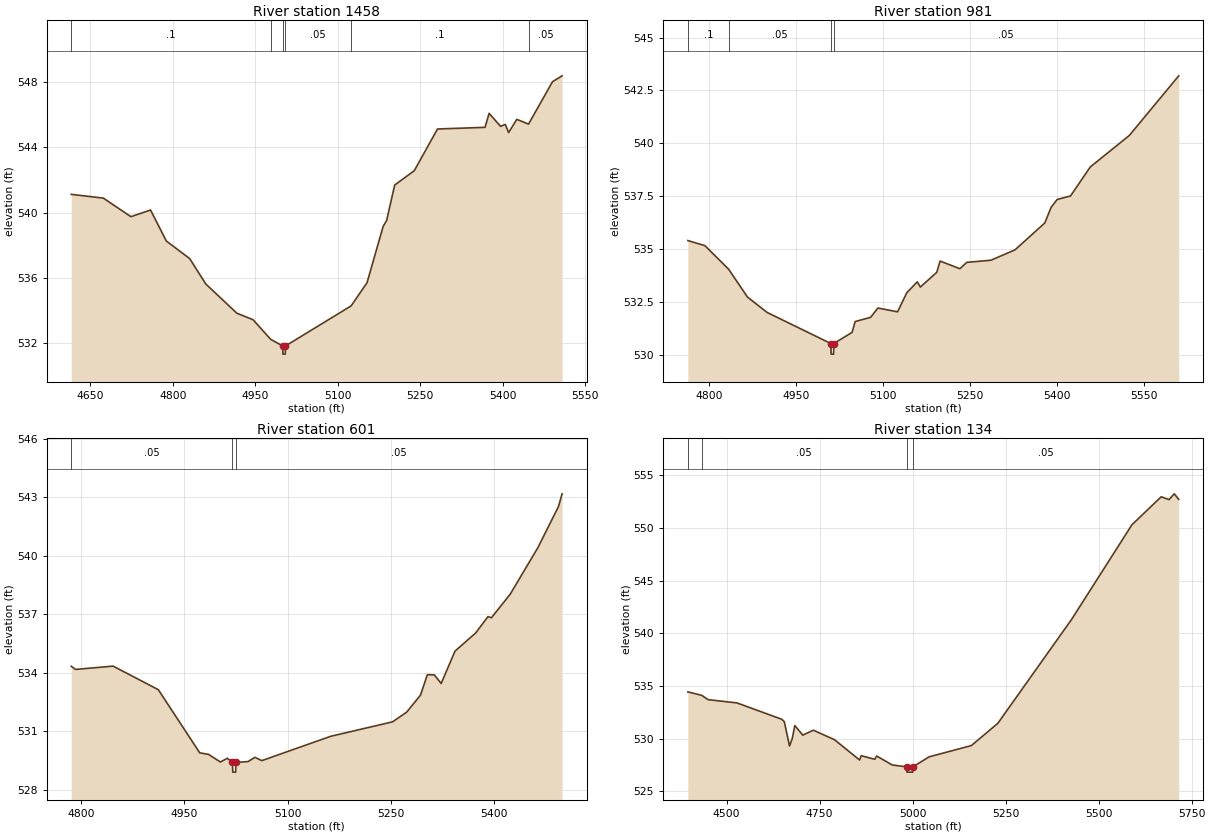
Type RM Length L Ch R = 1,1458,477,477,477
BEGIN DESCRIPTION:
Mapping XS 7191a3ba
END DESCRIPTION:
XS GIS Cut Line= 2
      1972274.33     13495185.29      1972796.92     13494461.29
#Sta/Elev= 30
  4615.2  541.12  4673.6  540.89  4723.9  539.75  4759.5  540.16  4788.2  538.26
  4830.7  537.18  4860.1  535.62  4916.5  533.83  4946.0  533.43  4978.0  532.23
  4999.9  531.82  5000.3  531.32  5004.5  531.32  5004.9  531.82  5124.4  534.28
  5153.3  535.70  5182.7  539.16  5188.9  539.51  5203.6  541.69  5239.2  542.57
  5281.5  545.13  5367.9  545.23  5375.4  546.09  5396.2  545.29  5404.8  545.41
  5410.9  544.91  5425.7  545.72  5447.1  545.43  5490.7  548.03  5508.1  548.39
#Mann=6,-1,0
  4615.2     0.1       0  4978.0    0.05       0  4999.9   0.035       0
  5004.9    0.05       0  5124.4     0.1       0  5447.1    0.05       0
Bank Sta=4999.9,5004.9
Exp/Cntr=0.3,0.1

Type RM Length L Ch R = 1,981,380,380,380
BEGIN DESCRIPTION:
Mapping XS 98e699ac
END DESCRIPTION:
XS GIS Cut Line= 2
      1972802.12     13495398.80      1973031.27     13494582.87
#Sta/Elev= 30
  4763.1  535.40  4792.6  535.16  4833.7  534.04  4866.0  532.73  4900.0  532.00
  5010.1  530.53  5010.5  530.03  5014.7  530.03  5015.1  530.53  5046.7  531.06
  5051.9  531.57  5078.7  531.77  5091.2  532.21  5125.2  532.03  5141.0  532.93
  5159.3  533.45  5164.5  533.20  5192.9  533.90  5198.6  534.43  5232.7  534.07
  5244.8  534.37  5286.4  534.47  5327.9  534.96  5379.3  536.23  5390.3  536.97
  5400.6  537.34  5423.8  537.51  5457.9  538.88  5525.3  540.37  5610.6  543.19
#Mann=4,-1,0
  4763.1     0.1       0  4833.7    0.05       0  5010.1   0.035       0
  5015.1    0.05       0
Bank Sta=5010.1,5015.1
Exp/Cntr=0.3,0.1

Type RM Length L Ch R = 1,601,467,467,467
BEGIN DESCRIPTION:
Mapping XS 2e39c8c0
END DESCRIPTION:
XS GIS Cut Line= 2
      1973234.41     13495501.27      1973182.35     13494789.77
#Sta/Elev= 30
  4785.6  534.33  4791.9  534.17  4846.5  534.34  4912.2  533.13  4972.4  529.89
  4985.2  529.81  5002.4  529.42  5012.5  529.61  5020.0  529.40  5020.4  528.90
  5024.6  528.90  5025.0  529.40  5042.6  529.44  5052.6  529.66  5062.6  529.49
  5162.9  530.74  5252.6  531.48  5273.2  531.98  5293.2  532.85  5303.2  533.90
  5313.3  533.89  5323.3  533.45  5343.4  535.11  5373.4  536.04  5391.3  536.88
  5396.3  536.82  5423.6  538.03  5463.7  540.41  5493.8  542.53  5499.0  543.18
#Mann=3,-1,0
  4785.6    0.05       0  5020.0   0.035       0  5025.0    0.05       0
Bank Sta=5020,5025
Exp/Cntr=0.3,0.1

Type RM Length L Ch R = 1,134,0,0,0
BEGIN DESCRIPTION:
UNT 007 in BCW 1.0
END DESCRIPTION:
XS GIS Cut Line= 4
      1973338.54     13495555.09      1973651.07     13495218.26
      1973583.36     13494942.22      1973202.40     13494510.62
#Sta/Elev= 30
  4395.9  534.44  4433.1  534.11  4450.3  533.70  4528.0  533.39  4648.2  531.84
  4655.2  531.61  4669.2  529.30  4676.5  530.00  4683.4  531.24  4704.9  530.33
  4733.2  530.80  4789.9  529.90  4857.6  527.97  4861.9  528.38  4898.3  528.04
  4903.5  528.35  4945.1  527.50  4984.3  527.32  4984.8  526.82  5000.4  526.82
  5000.9  527.32  5044.1  528.27  5157.9  529.34  5229.0  531.45  5427.2  541.31
  5589.5  550.30  5668.2  552.96  5689.1  552.69  5703.3  553.24  5715.3  552.72
#Mann=4,-1,0
  4395.9     0.1       0  4433.1    0.05       0  4984.3   0.035       0
  5000.9    0.05       0
Bank Sta=4984.3,5000.9
Exp/Cntr=0.3,0.1

Chan Stop Cuts=-1