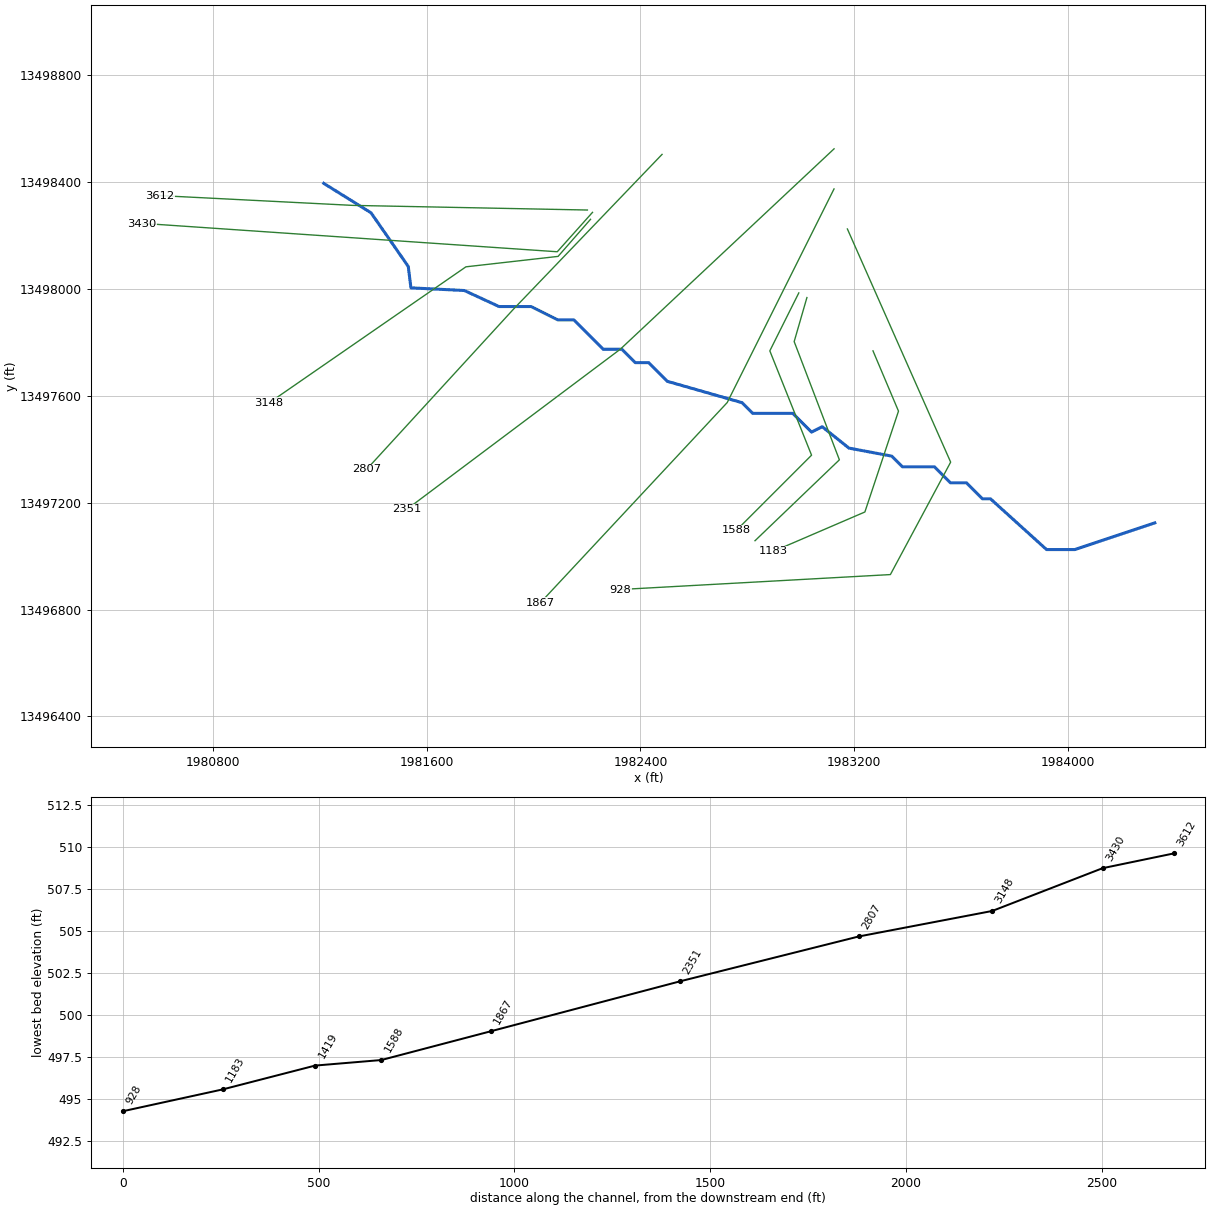
--- UNT 008 in BCW.prj (project) ---

Proj Title=UNT 008 in BCW Base Level Engineering
Current Plan=p01
Default Exp/Contr=0.3,0.1
English Units
Geom File=g01
Flow File=f01
Plan File=p01
BEGIN DESCRIPTION:
UNT 008 in BCW
END DESCRIPTION:

--- UNT 008 in BCW.p01 (plan) ---

Plan Title=Multiple Run
Short Identifier=Multiple
Geom File=g01
Flow File=f01
Subcritical Flow
K Sum by GR= 0
Std Step Tol= 0.01
Critical Tol= 0.01
Num of Std Step Trials= 20
Max Error Tol= 0.3
Flow Tol Ratio= 0.001
Split Flow NTrial= 30
Split Flow Tol= 0.02
Split Flow Ratio= 0.02
Log Output Level= 0
Friction Slope Method= 1
Unsteady Friction Slope Method= 2
Unsteady Bridges Friction Slope Method= 1
Parabolic Critical Depth
Global Vel Dist=  1 , 1 , 1
Global Log Level= 0
CheckData=True
Encroach Param= -1, 0, 0, 0
BEGIN DESCRIPTION:
Multiple Run
END DESCRIPTION:

--- UNT 008 in BCW.f01 (steady flow) ---

Flow Title=Multiple
Number of Profiles=7
Profile Names=10-year,25-year,50-year,1pct_min,100-year,1pct_plu,500-year
River Rch & RM= UNT 008 in BCW,Reach-1,3612
     154     211     257     157     313     624     470
River Rch & RM= UNT 008 in BCW,Reach-1,3148
     232     325     401     248     495     987     762
Boundary for River Rch & Prof#=UNT 008 in BCW,Reach-1,1
Up Type=0
Dn Type=3
Dn Slope=0.005
Boundary for River Rch & Prof#=UNT 008 in BCW,Reach-1,2
Up Type=0
Dn Type=3
Dn Slope=0.005
Boundary for River Rch & Prof#=UNT 008 in BCW,Reach-1,3
Up Type=0
Dn Type=3
Dn Slope=0.005
Boundary for River Rch & Prof#=UNT 008 in BCW,Reach-1,4
Up Type=0
Dn Type=3
Dn Slope=0.005
Boundary for River Rch & Prof#=UNT 008 in BCW,Reach-1,5
Up Type=0
Dn Type=3
Dn Slope=0.005
Boundary for River Rch & Prof#=UNT 008 in BCW,Reach-1,6
Up Type=0
Dn Type=3
Dn Slope=0.005
Boundary for River Rch & Prof#=UNT 008 in BCW,Reach-1,7
Up Type=0
Dn Type=3
Dn Slope=0.005

--- UNT 008 in BCW.g01 (geometry) ---

Geom Title=Existing Conditions

River Reach=UNT 008 in BCW,Reach-1
Reach XY= 30
      1981214.36     13498395.70      1981391.33     13498285.56
      1981530.80     13498084.54      1981540.80     13498004.54
      1981740.80     13497994.54      1981870.80     13497934.54
      1981990.80     13497934.54      1982090.80     13497884.54
      1982150.80     13497884.54      1982260.80     13497774.54
      1982330.80     13497774.54      1982380.80     13497724.54
      1982430.80     13497724.54      1982500.80     13497654.54
      1982780.80     13497574.54      1982820.80     13497534.54
      1982970.80     13497534.54      1983040.80     13497464.54
      1983080.80     13497484.54      1983180.80     13497404.54
      1983340.80     13497374.54      1983380.80     13497334.54
      1983500.80     13497334.54      1983560.80     13497274.54
      1983620.80     13497274.54      1983680.80     13497214.54
      1983710.80     13497214.54      1983920.80     13497024.54
      1984026.44     13497024.54      1984325.92     13497124.54

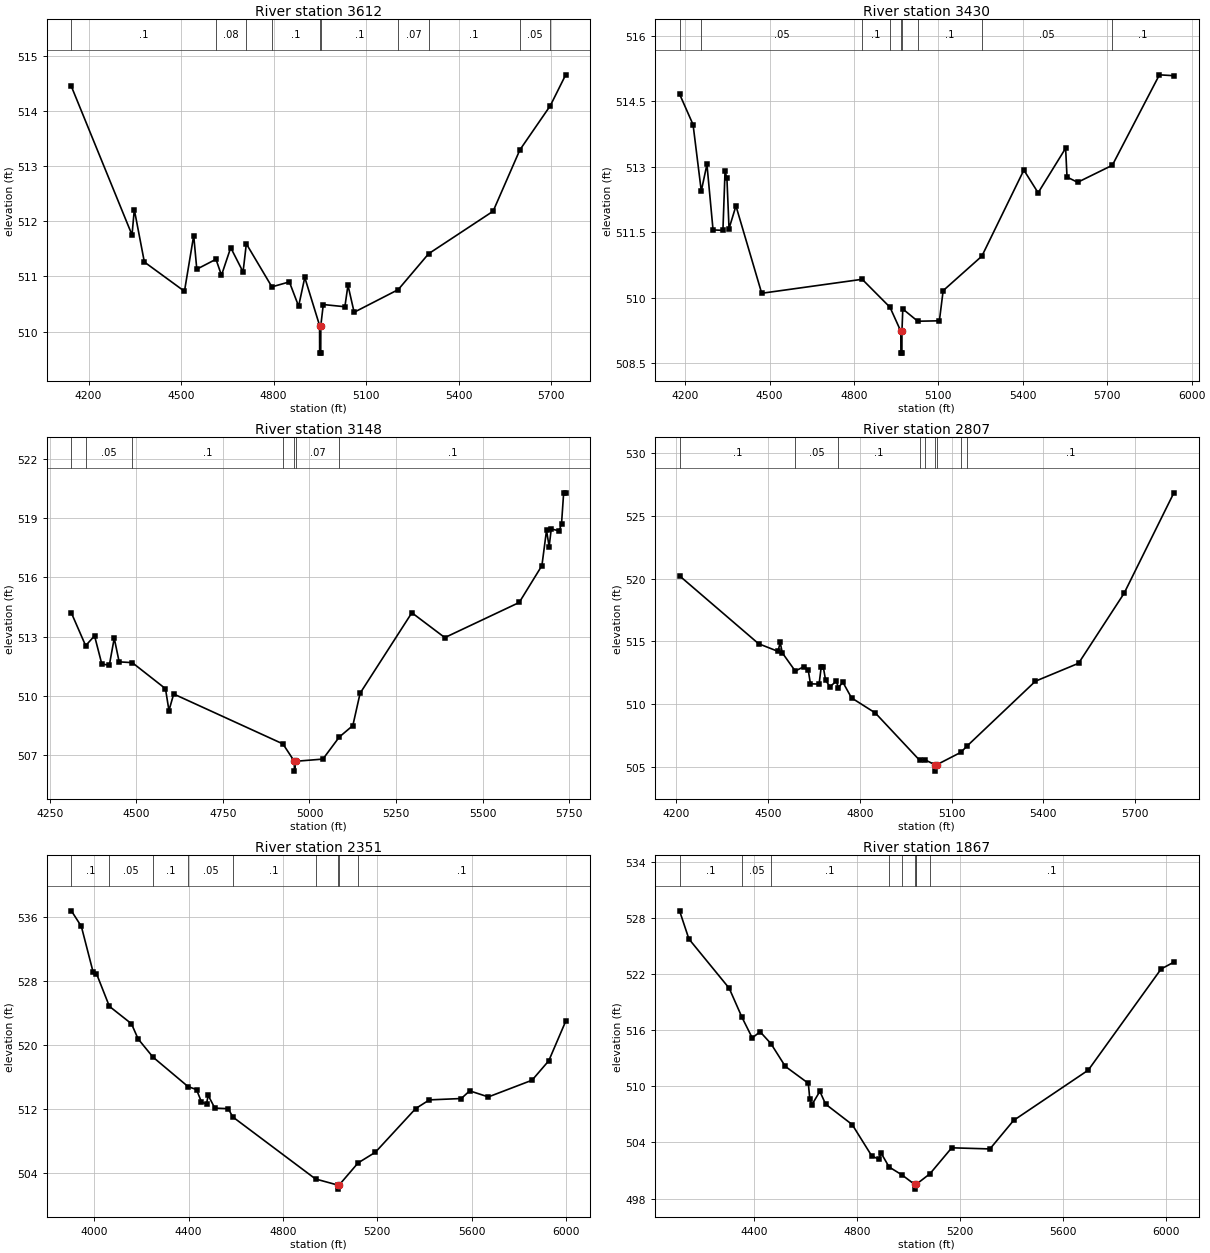
Type RM Length L Ch R = 1,3612,182,182,182
BEGIN DESCRIPTION:
Mapping XS f6a721e2
END DESCRIPTION:
XS GIS Cut Line= 3
      1982201.51     13498295.92      1981323.09     13498313.28
      1980600.02     13498350.00
#Sta/Elev= 30
  4144.3  514.44  4340.9  511.75  4348.3  512.21  4380.9  511.26  4510.9  510.73
  4540.9  511.74  4550.9  511.13  4613.1  511.31  4630.9  511.02  4660.9  511.52
  4700.9  511.08  4711.5  511.59  4794.4  510.81  4851.0  510.90  4881.0  510.46
  4901.0  510.98  4949.0  510.11  4949.2  509.61  4952.7  509.61  4953.0  510.11
  4961.0  510.49  5031.0  510.45  5041.0  510.84  5061.0  510.35  5203.9  510.76
  5302.5  511.41  5511.6  512.18  5598.3  513.29  5696.9  514.09  5746.9  514.65
#Mann=10,-1,0
  4144.3     0.1       0  4613.1    0.08       0  4711.5    0.05       0
  4794.4     0.1       0  4949.0    0.07       0  4953.0     0.1       0
  5203.9    0.07       0  5302.5     0.1       0  5598.3    0.05       0
  5696.9    0.08       0
Bank Sta=4949,4953
Exp/Cntr=0.3,0.1

Type RM Length L Ch R = 1,3430,282,282,282
BEGIN DESCRIPTION:
Mapping XS 8e470f36
END DESCRIPTION:
XS GIS Cut Line= 4
      1982220.65     13498287.23      1982088.71     13498139.67
      1980592.19     13498242.10      1980533.58     13498243.84
#Sta/Elev= 30
  4180.2  514.66  4228.2  513.96  4257.4  512.44  4277.5  513.05  4299.2  511.55
  4334.3  511.54  4341.8  512.89  4348.5  512.73  4356.0  511.58  4380.6  512.10
  4472.1  510.10  4829.2  510.42  4928.0  509.78  4966.5  509.23  4966.8  508.73
  4970.3  508.73  4970.5  509.23  4973.5  509.74  5026.7  509.46  5103.5  509.47
  5116.9  510.16  5254.5  510.95  5403.7  512.92  5454.4  512.40  5552.1  513.42
  5557.1  512.76  5594.7  512.64  5718.1  513.03  5885.4  515.10  5936.8  515.08
#Mann=9,-1,0
  4180.2     0.1       0  4257.4    0.05       0  4829.2     0.1       0
  4928.0    0.12       0  4966.5    0.07       0  4970.5    0.12       0
  5026.7     0.1       0  5254.5    0.05       0  5718.1     0.1       0
Bank Sta=4966.5,4970.5
Exp/Cntr=0.3,0.1

Type RM Length L Ch R = 1,3148,341,341,341
BEGIN DESCRIPTION:
Mapping XS 56a139e7
END DESCRIPTION:
XS GIS Cut Line= 4
      1982213.26     13498261.18      1982091.75     13498122.31
      1981746.70     13498083.25      1981009.45     13497573.67
#Sta/Elev= 30
  4312.2  514.20  4353.4  512.54  4379.1  513.04  4400.1  511.61  4421.8  511.55
  4436.0  512.92  4450.2  511.72  4488.1  511.68  4584.0  510.36  4594.1  509.25
  4607.7  510.09  4923.3  507.56  4956.2  506.68  4956.5  506.18  4960.5  506.68
  5038.8  506.79  5086.2  507.91  5125.3  508.49  5146.3  510.13  5295.8  514.21
  5391.0  512.95  5605.9  514.73  5671.5  516.60  5684.8  518.39  5692.4  517.56
  5698.5  518.46  5721.3  518.36  5728.2  518.73  5734.3  520.29  5740.2  520.26
#Mann=7,-1,0
  4312.2     0.1       0  4353.4    0.05       0  4488.1     0.1       0
  4923.3    0.07       0  4956.2    0.07       0  4960.5    0.07       0
  5086.2     0.1       0
Bank Sta=4956.2,4960.5
Exp/Cntr=0.3,0.1

Type RM Length L Ch R = 1,2807,456,456,456
BEGIN DESCRIPTION:
UNT 008 in BCW 4.0
END DESCRIPTION:
XS GIS Cut Line= 3
      1982481.04     13498504.22      1981925.00     13497925.00
      1981374.97     13497324.97
#Sta/Elev= 30
  4210.3  520.23  4468.7  514.82  4532.2  514.21  4539.5  514.92  4546.4  514.09
  4588.7  512.64  4617.1  512.99  4631.3  512.70  4638.5  511.62  4666.7  511.60
  4673.7  512.97  4680.7  512.93  4687.9  511.92  4702.0  511.39  4723.1  511.83
  4729.7  511.31  4744.5  511.75  4772.8  510.50  4850.5  509.30  4996.2  505.51
  5011.6  505.58  5046.5  505.16  5046.8  504.66  5050.9  505.16  5130.5  506.16
  5149.4  506.63  5374.3  511.83  5515.5  513.26  5664.4  518.84  5827.2  526.85
#Mann=9,-1,0
  4210.3     0.1       0  4588.7    0.05       0  4729.7     0.1       0
  4996.2    0.12       0  5011.6    0.07       0  5046.5    0.07       0
  5050.9    0.07       0  5130.5    0.12       0  5149.4     0.1       0
Bank Sta=5046.5,5050.9
Exp/Cntr=0.3,0.1

Type RM Length L Ch R = 1,2351,484,484,484
BEGIN DESCRIPTION:
UNT 008 in BCW 3.0
END DESCRIPTION:
XS GIS Cut Line= 3
      1983125.03     13498525.03      1982325.00     13497775.00
      1981525.02     13497175.02
#Sta/Elev= 30
  3902.6  536.79  3944.9  534.84  3994.7  529.14  4008.9  528.95  4063.7  524.85
  4157.4  522.67  4185.7  520.77  4248.6  518.50  4397.5  514.81  4433.3  514.44
  4454.4  512.88  4475.8  512.64  4482.7  513.72  4511.0  512.12  4567.7  512.05
  4587.4  511.01  4938.1  503.26  5033.5  502.49  5033.8  501.99  5037.9  502.49
  5118.7  505.27  5191.9  506.60  5362.8  512.06  5421.1  513.15  5556.5  513.32
  5591.9  514.28  5671.1  513.52  5856.5  515.61  5927.4  518.04  5999.2  522.98
#Mann=9,-1,0
  3902.6     0.1       0  4063.7    0.05       0  4248.6     0.1       0
  4397.5    0.05       0  4587.4     0.1       0  4938.1    0.07       0
  5033.5    0.07       0  5037.9    0.07       0  5118.7     0.1       0
Bank Sta=5033.5,5037.9
Exp/Cntr=0.3,0.1

Type RM Length L Ch R = 1,1867,279,279,279
BEGIN DESCRIPTION:
UNT 008 in BCW 2.0
END DESCRIPTION:
XS GIS Cut Line= 3
      1983124.98     13498374.96      1982725.00     13497575.00
      1982024.99     13496824.99
#Sta/Elev= 30
  4109.6  528.78  4145.9  525.77  4302.4  520.50  4352.4  517.37  4391.9  515.19
  4422.6  515.84  4464.4  514.58  4520.4  512.14  4609.9  510.33  4615.5  508.63
  4623.8  508.04  4654.6  509.47  4677.0  508.10  4780.4  505.91  4855.8  502.58
  4883.8  502.19  4892.2  502.88  4923.6  501.38  4974.7  500.51  5023.0  499.51
  5023.3  499.01  5027.5  499.51  5029.4  499.53  5082.5  500.66  5166.9  503.43
  5315.4  503.31  5407.3  506.36  5697.4  511.74  5980.3  522.56  6029.9  523.29
#Mann=9,-1,0
  4109.6     0.1       0  4352.4    0.05       0  4464.4     0.1       0
  4923.6    0.07       0  4974.7    0.12       0  5023.0    0.07       0
  5027.5    0.12       0  5029.4    0.07       0  5082.5     0.1       0
Bank Sta=5023,5027.5
Exp/Cntr=0.3,0.1

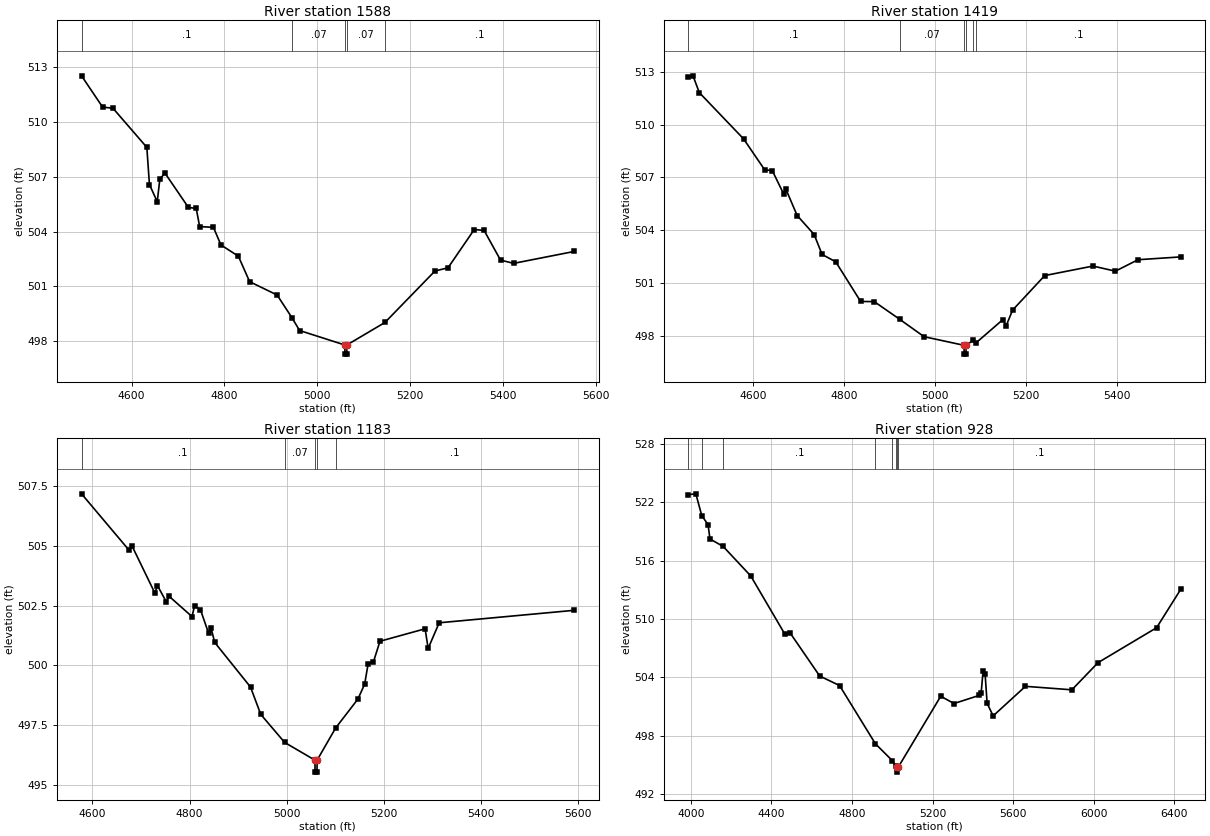
Type RM Length L Ch R = 1,1588,169,169,169
BEGIN DESCRIPTION:
Mapping XS cb14935e
END DESCRIPTION:
XS GIS Cut Line= 4
      1982993.08     13497985.60      1982884.58     13497768.60
      1983040.83     13497377.98      1982759.34     13497096.49
#Sta/Elev= 30
  4492.0  512.51  4537.4  510.80  4559.7  510.74  4632.7  508.60  4638.3  506.57
  4655.1  505.63  4660.7  506.85  4671.6  507.20  4722.2  505.32  4739.2  505.26
  4746.5  504.27  4776.2  504.23  4792.3  503.27  4830.0  502.65  4854.2  501.26
  4913.5  500.53  4945.7  499.28  4961.9  498.59  5059.3  497.80  5059.6  497.30
  5063.5  497.30  5063.8  497.80  5145.8  499.03  5253.5  501.84  5281.8  502.02
  5338.3  504.11  5359.5  504.06  5394.9  502.44  5423.2  502.26  5553.4  502.91
#Mann=5,-1,0
  4492.0     0.1       0  4945.7    0.07       0  5059.3    0.07       0
  5063.8    0.07       0  5145.8     0.1       0
Bank Sta=5059.3,5063.8
Exp/Cntr=0.3,0.1

Type RM Length L Ch R = 1,1419,236,236,236
BEGIN DESCRIPTION:
Mapping XS e1c0fd08
END DESCRIPTION:
XS GIS Cut Line= 4
      1983023.46     13497968.21      1982975.73     13497803.33
      1983145.00     13497360.62      1982829.09     13497057.69
#Sta/Elev= 30
  4457.9  512.70  4468.4  512.77  4482.1  511.82  4579.6  509.19  4626.1  507.43
  4642.7  507.39  4667.4  506.08  4672.7  506.33  4697.4  504.84  4734.8  503.76
  4752.2  502.63  4782.3  502.21  4837.0  499.96  4867.1  499.95  4922.8  498.95
  4976.6  497.96  5064.5  497.47  5064.8  496.97  5068.7  496.97  5069.0  497.47
  5085.0  497.76  5090.4  497.60  5149.9  498.93  5157.1  498.58  5171.3  499.47
  5242.0  501.43  5348.0  501.97  5397.4  501.68  5447.1  502.33  5541.2  502.49
#Mann=6,-1,0
  4457.9     0.1       0  4922.8    0.07       0  5064.5    0.07       0
  5069.0    0.07       0  5085.0    0.12       0  5090.4     0.1       0
Bank Sta=5064.5,5069
Exp/Cntr=0.3,0.1

Type RM Length L Ch R = 1,1183,255,255,255
BEGIN DESCRIPTION:
Mapping XS 30667ad4
END DESCRIPTION:
XS GIS Cut Line= 4
      1983270.88     13497768.57      1983366.35     13497542.91
      1983240.48     13497165.31      1982898.83     13497018.27
#Sta/Elev= 30
  4577.5  507.16  4675.8  504.80  4681.2  505.00  4728.6  503.02  4734.0  503.33
  4752.3  502.65  4757.7  502.89  4805.1  502.04  4810.5  502.49  4822.5  502.33
  4839.4  501.34  4844.6  501.55  4851.9  500.96  4925.7  499.10  4946.8  497.96
  4996.0  496.79  5058.4  496.05  5058.8  495.55  5062.7  495.55  5063.0  496.05
  5101.1  497.39  5147.1  498.60  5160.9  499.22  5168.2  500.08  5178.7  500.13
  5192.5  501.01  5285.5  501.53  5291.8  500.71  5314.5  501.78  5592.5  502.30
#Mann=5,-1,0
  4577.5     0.1       0  4996.0    0.07       0  5058.4    0.07       0
  5063.0    0.07       0  5101.1     0.1       0
Bank Sta=5058.4,5063
Exp/Cntr=0.3,0.1

Type RM Length L Ch R = 1,928,0,0,0
BEGIN DESCRIPTION:
UNT 008 in BCW 1.0
END DESCRIPTION:
XS GIS Cut Line= 4
      1983174.99     13498225.03      1983561.66     13497351.94
      1983335.97     13496930.93      1982324.99     13496875.00
#Sta/Elev= 30
  3987.3  522.81  4025.0  522.89  4054.4  520.65  4085.8  519.71  4094.8  518.25
  4160.8  517.47  4297.5  514.44  4466.0  508.48  4494.7  508.52  4639.9  504.14
  4738.5  503.16  4916.3  497.17  5000.5  495.43  5016.5  494.88  5024.8  494.75
  5025.1  494.25  5029.4  494.75  5240.7  502.06  5306.5  501.31  5430.9  502.14
  5441.3  502.38  5450.9  504.66  5460.9  504.38  5470.9  501.33  5501.0  500.04
  5661.2  503.08  5891.6  502.72  6021.8  505.52  6312.2  509.11  6432.4  513.07
#Mann=8,-1,0
  3987.3     0.1       0  4054.4    0.08       0  4160.8     0.1       0
  4916.3    0.12       0  5000.5    0.07       0  5016.5     0.1       0
  5024.8    0.07       0  5029.4     0.1       0
Bank Sta=5024.8,5029.4
Exp/Cntr=0.3,0.1

Chan Stop Cuts=-1