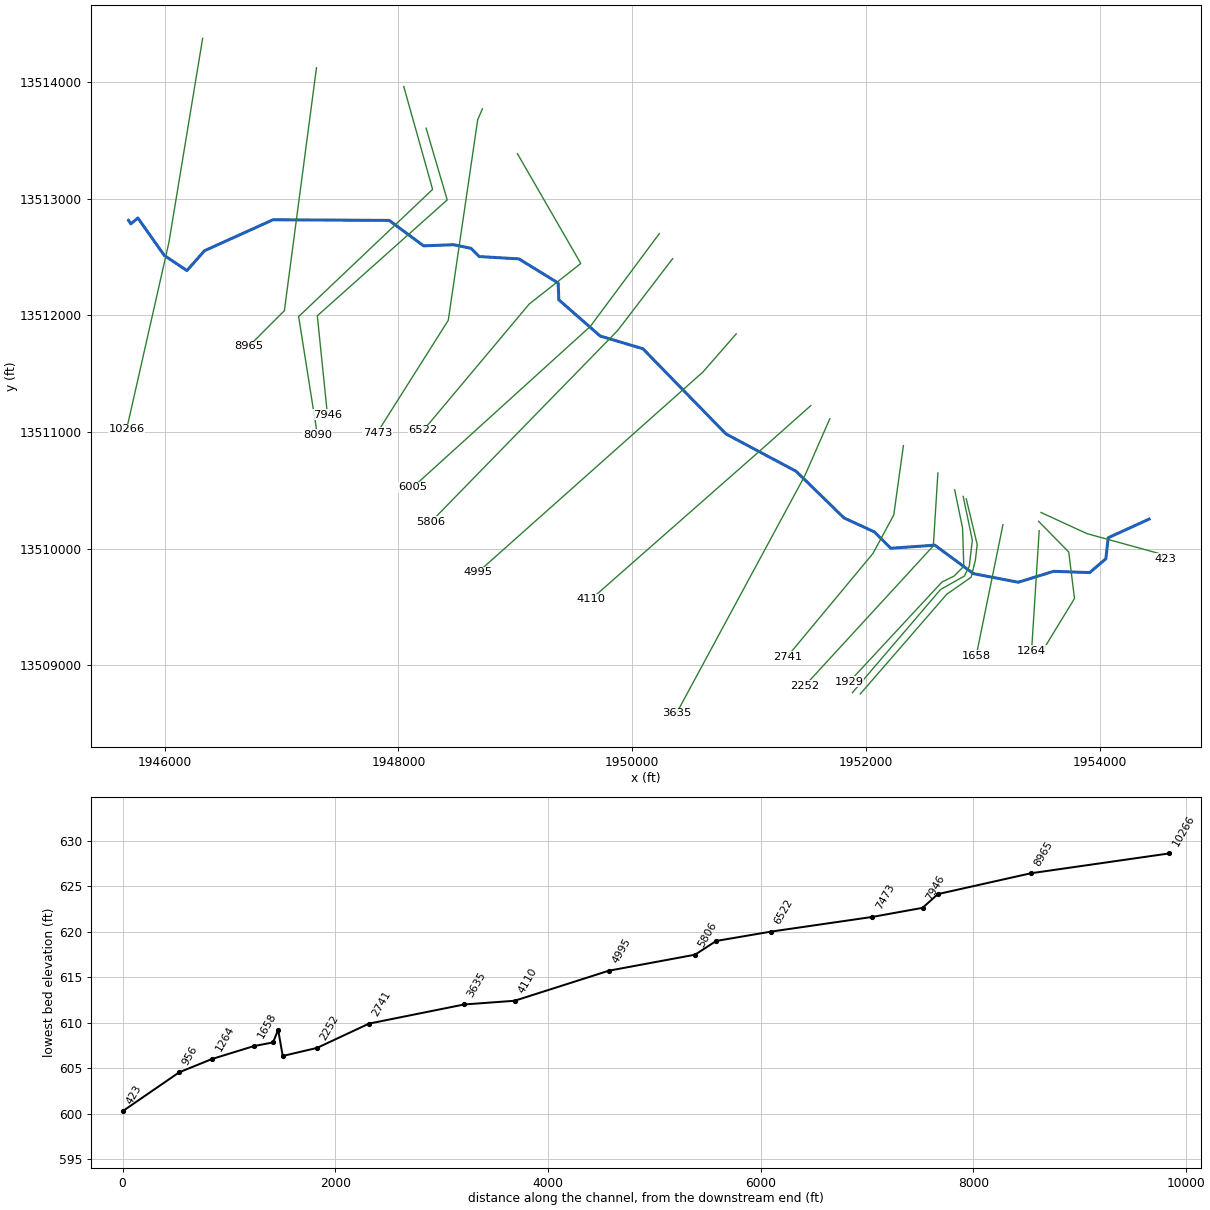
--- UNT 011 in BCW.prj (project) ---

Proj Title=UNT 011 in BCW Base Level Engineering
Current Plan=p01
Default Exp/Contr=0.3,0.1
English Units
Geom File=g01
Flow File=f01
Plan File=p01
Y Axis Title=Elevation
X Axis Title(PF)=Main Channel Distance
X Axis Title(XS)=Station
BEGIN DESCRIPTION:
UNT 011 in BCW
END DESCRIPTION:
DSS Export Rating Curves= 0
DSS Export Rating Curve Sorted= 0
DSS Export Volume Flow Curves= 0
DXF OffsetX= 0
DXF OffsetY= 0
DXF ScaleX= 1
DXF ScaleY= 10

--- UNT 011 in BCW.p01 (plan) ---

Plan Title=Multiple Run
Short Identifier=Multiple
Geom File=g01
Flow File=f01
Subcritical Flow
K Sum by GR= 0
Std Step Tol= 0.01
Critical Tol= 0.01
Num of Std Step Trials= 20
Max Error Tol= 0.3
Flow Tol Ratio= 0.001
Split Flow NTrial= 30
Split Flow Tol= 0.02
Split Flow Ratio= 0.02
Log Output Level= 0
Friction Slope Method= 1
Unsteady Friction Slope Method= 2
Unsteady Bridges Friction Slope Method= 1
Parabolic Critical Depth
Global Vel Dist=  1 , 1 , 1
Global Log Level= 0
CheckData=True
Encroach Param= -1, 0, 0, 0
BEGIN DESCRIPTION:
Multiple Run
END DESCRIPTION:

--- UNT 011 in BCW.f01 (steady flow) ---

Flow Title=Multiple
Number of Profiles=7
Profile Names=10-year,25-year,50-year,1pct_min,100-year,1pct_plu,500-year
River Rch & RM= UNT 011 in BCW,Reach-1,10266
      79     103     121      72     143     286     202
River Rch & RM= UNT 011 in BCW,Reach-1,8965
     143     193     233     140     280     558     412
River Rch & RM= UNT 011 in BCW,Reach-1,4995
     197     269     327     199     398     793     597
River Rch & RM= UNT 011 in BCW,Reach-1,4110
     222     305     373     228     455     908     689
River Rch & RM= UNT 011 in BCW,Reach-1,2741
     247     341     418     256     511    1020     778
River Rch & RM= UNT 011 in BCW,Reach-1,423
     444     637     803     504    1007    2008    1612
Boundary for River Rch & Prof#=UNT 011 in BCW,Reach-1,1
Up Type=0
Dn Type=3
Dn Slope=0.005
Boundary for River Rch & Prof#=UNT 011 in BCW,Reach-1,2
Up Type=0
Dn Type=3
Dn Slope=0.005
Boundary for River Rch & Prof#=UNT 011 in BCW,Reach-1,3
Up Type=0
Dn Type=3
Dn Slope=0.005
Boundary for River Rch & Prof#=UNT 011 in BCW,Reach-1,4
Up Type=0
Dn Type=3
Dn Slope=0.005
Boundary for River Rch & Prof#=UNT 011 in BCW,Reach-1,5
Up Type=0
Dn Type=3
Dn Slope=0.005
Boundary for River Rch & Prof#=UNT 011 in BCW,Reach-1,6
Up Type=0
Dn Type=3
Dn Slope=0.005
Boundary for River Rch & Prof#=UNT 011 in BCW,Reach-1,7
Up Type=0
Dn Type=3
Dn Slope=0.005

--- UNT 011 in BCW.g01 (geometry) ---

Geom Title=Existing Conditions
Program Version=5.05

River Reach=UNT 011 in BCW  ,Reach-1
Reach XY= 30
       1945690.8     13512814.54       1945710.8     13512784.54
      1945771.21     13512834.94       1945996.9     13512514.41
       1946190.8     13512384.54       1946340.8     13512554.54
      1946926.84     13512819.94       1947920.8     13512814.54
      1948214.81     13512596.41      1948470.89     13512606.18
      1948620.08     13512575.25       1948690.8     13512504.54
       1949030.8     13512484.54      1949365.85     13512277.83
      1949371.93     13512133.74      1949724.94     13511823.73
       1950090.8     13511714.54       1950800.8     13510984.54
       1951400.8     13510664.54       1951810.8     13510264.54
       1952070.8     13510144.54       1952210.8     13510004.54
      1952588.09      13510030.8      1952917.95     13509786.88
      1953301.63     13509713.09      1953603.72     13509806.84
      1953912.28     13509796.02       1954050.8     13509914.54
       1954070.8     13510094.54       1954420.8     13510254.54

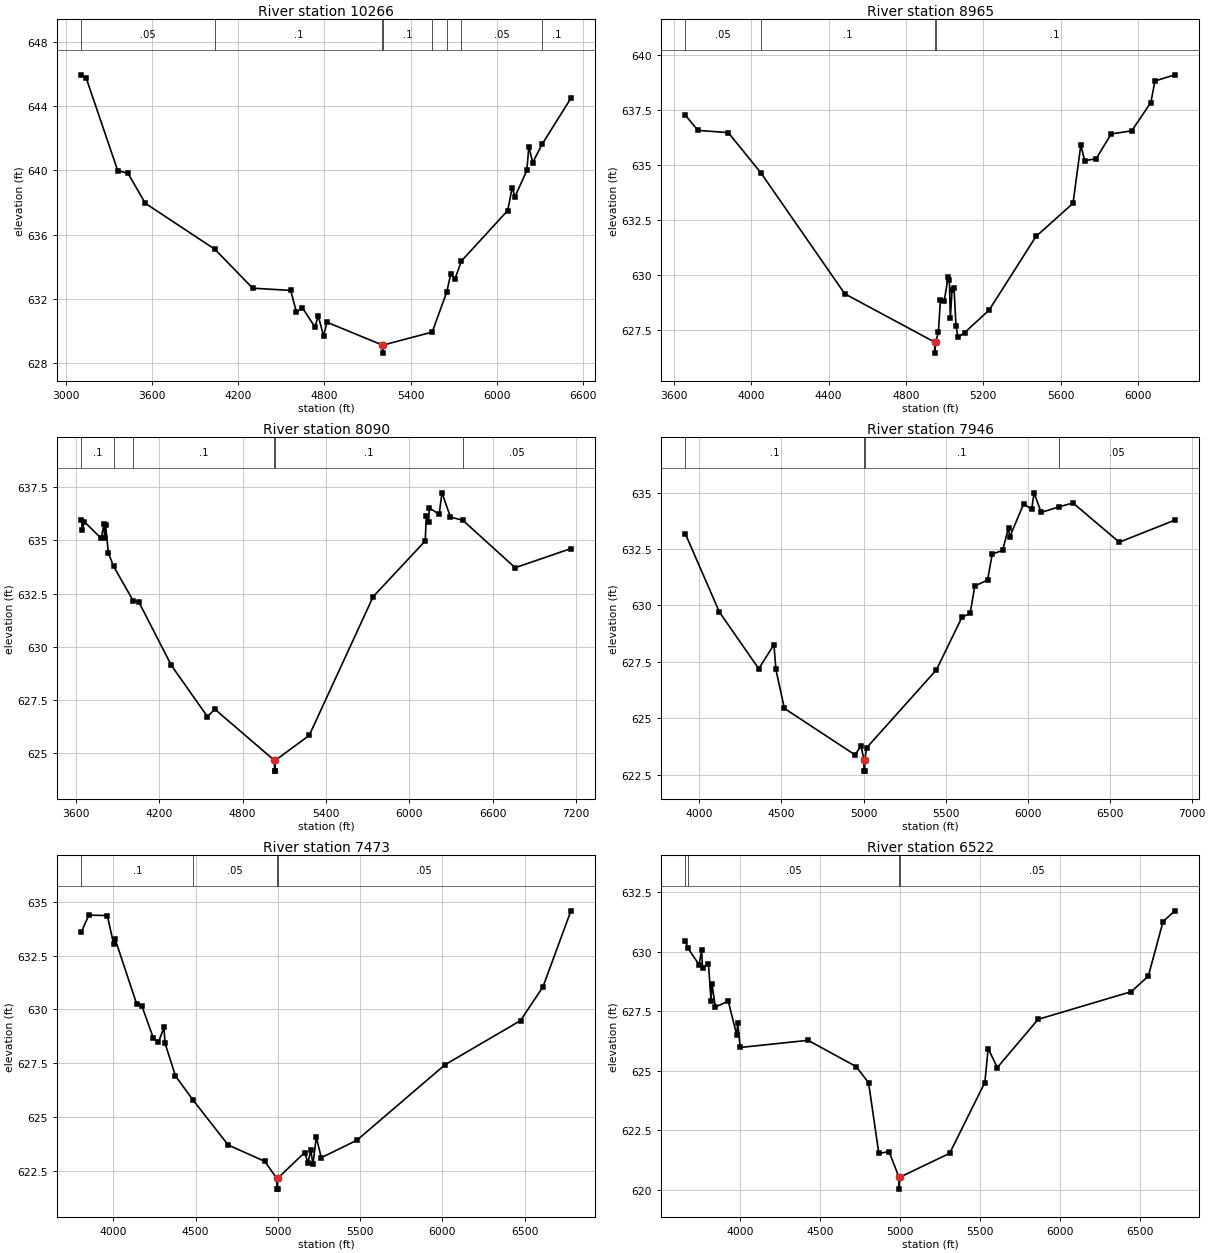
Type RM Length L Ch R = 1 ,10266   ,1301,1301,1301
BEGIN DESCRIPTION:
UNT 011 in BCW 14.0
END DESCRIPTION:
XS GIS Cut Line= 3
        1946325.     13514374.98      1946036.69      13512626.8
        1945675.     13511025.02
#Sta/Elev= 30
  3104.9  645.94    3138  645.75  3358.3  639.98  3429.2  639.82  3550.8  637.95
  4035.6  635.09  4299.5  632.67  4564.3  632.53  4604.9  631.17  4645.4  631.46
  4732.5  630.27  4756.9  630.93  4793.6  629.72  4817.7  630.55  5204.6  629.13
  5204.8  628.63  5208.6  629.13  5551.4  629.94  5653.3  632.45  5681.1  633.58
  5708.9  633.22  5755.1  634.36    6078   637.5  6108.7  638.92  6128.5  638.36
  6211.3  639.99  6225.2  641.47  6252.3  640.48  6317.6  641.62  6518.8  644.49
#Mann= 8 ,-1 , 0
  3104.9     .05       0  4035.6      .1       0  5204.6     .07       0
  5208.6      .1       0  5551.4     .05       0  5653.3     .08       0
  5755.1     .05       0  6317.6      .1       0
Bank Sta=5204.6,5208.6
XS Rating Curve= 0 ,0
Exp/Cntr=0.3,0.1

Type RM Length L Ch R = 1 ,8965    ,875,875,875
BEGIN DESCRIPTION:
UNT 011 in BCW 13.0
END DESCRIPTION:
XS GIS Cut Line= 3
      1947298.71     13514122.65      1947024.11     13512040.87
      1946719.43     13511735.19
#Sta/Elev= 30
    3659  637.29  3723.9  636.59  3881.1  636.49  4048.9  634.67  4483.7  629.15
  4948.6  626.95  4948.9  626.45  4953.3  626.95  4967.9   627.4    4978  628.85
  4998.1  628.83  5018.3  629.92  5024.5  629.79  5029.5  628.06  5038.5  629.34
  5048.6  629.43  5058.7  627.69  5068.8  627.17    5103  627.38  5230.1  628.41
  5472.2  631.76  5663.9  633.27  5704.2  635.92  5724.4  635.21  5783.5   635.3
  5861.3  636.43  5967.4  636.57  6066.4  637.86  6087.6  638.84  6190.4  639.12
#Mann= 4 ,-1 , 0
    3659     .05       0  4048.9      .1       0  4948.6     .07       0
  4953.3      .1       0
Bank Sta=4948.6,4953.3
XS Rating Curve= 0 ,0
Exp/Cntr=0.3,0.1

Type RM Length L Ch R = 1 ,8090    ,144,144,144
BEGIN DESCRIPTION:
Mapping XS ada7049d
END DESCRIPTION:
XS GIS Cut Line= 4
      1948045.24     13513962.04      1948292.04     13513080.39
      1947146.21     13511990.11      1947306.03     13510978.76
#Sta/Elev= 30
  3640.9  635.98  3648.2  635.47  3661.2  635.89  3783.2   635.1  3802.9  635.76
  3808.1   635.1  3814.4  635.74  3835.1  634.41    3872  633.79  4014.3  632.16
  4053.2  632.12    4288  629.13  4547.7  626.72  4600.6  627.07  5029.8  624.66
  5030.1  624.16  5034.2  624.16  5034.6  624.66  5279.7  625.84  5739.5  632.36
  6114.2  634.98  6121.4  636.15  6138.1  635.85  6143.3  636.53  6214.1  636.23
  6234.4  637.24  6295.4   636.1  6384.3  635.95  6760.8  633.72    7162  634.62
#Mann= 6 ,-1 , 0
  3640.9      .1       0    3872     .05       0  4014.3      .1       0
  5029.8     .07       0  5034.6      .1       0  6384.3     .05       0
Bank Sta=5029.8,5034.6
XS Rating Curve= 0 ,0
Exp/Cntr=0.3,0.1

Type RM Length L Ch R = 1 ,7946    ,473,473,473
BEGIN DESCRIPTION:
Mapping XS 910e6a7b
END DESCRIPTION:
XS GIS Cut Line= 4
      1948236.49     13513604.67      1948417.04     13512990.11
      1947305.93     13511997.05      1947392.55      13511148.2
#Sta/Elev= 30
  3913.6  633.18  4121.7   629.7  4361.4  627.19  4454.1  628.26  4465.7  627.16
  4517.8  625.43  4948.5  623.37  4984.4  623.77  5002.9  623.15  5003.2  622.65
  5007.4  622.65  5007.8  623.15  5019.5  623.69  5444.2  627.14  5600.5  629.48
  5649.8  629.64  5678.3  630.86    5756  631.12  5784.4  632.27    5848  632.44
  5883.9  633.45  5890.6  633.02  5975.9   634.5  6025.2  634.26  6039.4  634.99
    6083  634.12  6191.7  634.37    6277  634.54  6559.1   632.8  6897.6  633.78
#Mann= 4 ,-1 , 0
  3913.6      .1       0  5002.9     .07       0  5007.8      .1       0
  6191.7     .05       0
Bank Sta=5002.9,5007.8
XS Rating Curve= 0 ,0
Exp/Cntr=0.3,0.1

Type RM Length L Ch R = 1 ,7473    ,951,951,951
BEGIN DESCRIPTION:
Mapping XS 621d21db
END DESCRIPTION:
XS GIS Cut Line= 4
      1948717.97     13513771.03      1948677.75     13513677.15
      1948426.02      13511958.4      1947819.21     13510996.18
#Sta/Elev= 30
  3805.3   633.6  3850.4  634.38  3963.1  634.36  4000.6  633.06  4010.7  633.26
  4142.1  630.24  4172.7  630.17  4243.1  628.66  4273.4  628.47  4307.4  629.16
  4313.9  628.43  4377.3  626.91  4486.1  625.77  4697.9   623.7  4920.3  622.94
  4993.6  622.15  4993.9  621.65  4998.1  621.65  4998.5  622.15  5162.8  623.35
    5183  622.88  5200.6  623.45  5213.4   622.8  5233.6  624.07  5263.9  623.11
  5480.1  623.92  6016.5  627.43  6475.4  629.48    6612  631.05  6782.1  634.58
#Mann= 4 ,-1 , 0
  3805.3      .1       0  4486.1     .05       0  4993.6    .035       0
  4998.5     .05       0
Bank Sta=4993.6,4998.5
XS Rating Curve= 0 ,0
Exp/Cntr=0.3,0.1

Type RM Length L Ch R = 1 ,6522    ,517,517,517
BEGIN DESCRIPTION:
Mapping XS 15b20b91
END DESCRIPTION:
XS GIS Cut Line= 4
      1949017.76      13513385.9       1949559.4     13512444.97
      1949118.43     13512097.75      1948212.16     13511014.39
#Sta/Elev= 30
  3655.5  630.46  3671.6  630.15  3741.6  629.45  3757.4  630.06  3763.2  629.33
  3800.5  629.47  3816.3  627.94  3822.1  628.65  3843.7  627.68  3924.1  627.92
  3977.3  626.49    3983  627.01  3998.8  625.98  4422.8  626.28  4723.1  625.18
  4800.9   624.5    4865  621.54  4929.2  621.61  4990.7  620.54  4991.1  620.04
  4995.9  620.54  5307.5  621.54  5527.5  624.51  5548.3  625.93  5605.6  625.14
  5860.6  627.16  6442.3  628.32    6549  628.97  6641.4  631.26  6714.9  631.71
#Mann= 4 ,-1 , 0
  3655.5      .1       0  3671.6     .05       0  4990.7    .035       0
  4995.9     .05       0
Bank Sta=4990.7,4995.9
XS Rating Curve= 0 ,0
Exp/Cntr=0.3,0.1

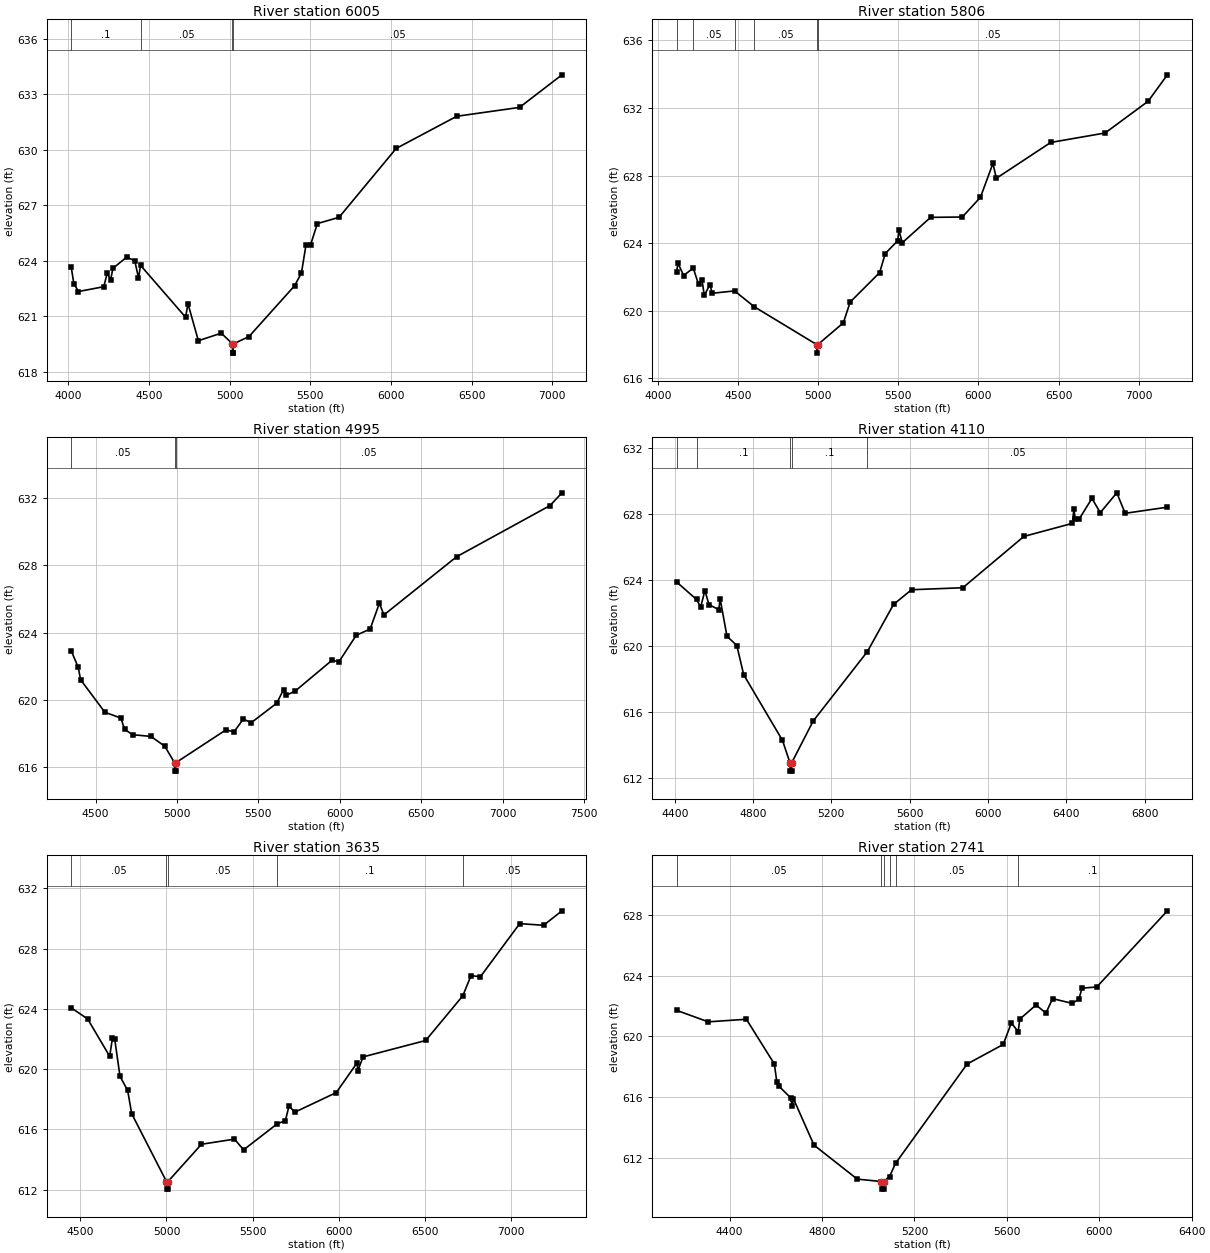
Type RM Length L Ch R = 1 ,6005    ,199,199,199
BEGIN DESCRIPTION:
UNT 011 in BCW 8.0
END DESCRIPTION:
XS GIS Cut Line= 3
      1950231.34     13512701.32       1949641.3     13511906.32
       1948122.2     13510526.12
#Sta/Elev= 30
  4017.3  623.66  4033.9  622.76  4062.5  622.34  4219.5   622.6  4240.4  623.33
  4261.8  622.98  4275.8  623.59  4361.4   624.2  4411.5     624  4434.5  623.08
  4447.5  623.75  4726.5  620.95  4741.1  621.68  4805.8  619.68  4947.7  620.09
    5017  619.51  5017.5  619.01  5021.9  619.01  5022.3  619.51    5119   619.9
  5402.1  622.65  5444.7  623.34  5473.1  624.87  5501.5  624.87  5543.4  626.01
  5677.9  626.35  6031.9  630.07  6407.5  631.81  6796.9  632.29  7059.8  634.05
#Mann= 4 ,-1 , 0
  4017.3      .1       0  4447.5     .05       0    5017    .035       0
  5022.3     .05       0
Bank Sta=5017,5022.3
XS Rating Curve= 0 ,0
Exp/Cntr=0.3,0.1

Type RM Length L Ch R = 1 ,5806    ,811,811,811
BEGIN DESCRIPTION:
UNT 011 in BCW 7.0
END DESCRIPTION:
XS GIS Cut Line= 3
      1950345.22     13512486.73      1949875.67      13511871.6
       1948279.2     13510231.74
#Sta/Elev= 30
  4116.2  622.32  4124.7  622.82  4160.1  622.09  4220.1  622.53  4253.6  621.56
  4274.4  621.85  4288.9  620.92  4324.3  621.55  4338.8  621.04  4477.9  621.18
  4601.5  620.24  4991.6     618    4992   617.5  4996.9     618  5156.8  619.29
  5199.3  620.52  5383.2  622.26  5418.5  623.39  5496.3  624.15  5503.3  624.78
  5524.6  624.03  5701.4  625.53  5899.4  625.55  6012.6  626.72  6090.3  628.72
  6111.6  627.84  6450.9  629.96  6790.4  630.52  7059.2   632.4  7178.7  633.96
#Mann= 6 ,-1 , 0
  4116.2     .08       0  4220.1     .05       0  4477.9     .08       0
  4601.5     .05       0  4991.6     .03       0  4996.9     .05       0
Bank Sta=4991.6,4996.9
XS Rating Curve= 0 ,0
Exp/Cntr=0.3,0.1

Type RM Length L Ch R = 1 ,4995    ,885,885,885
BEGIN DESCRIPTION:
UNT 011 in BCW 6.0
END DESCRIPTION:
XS GIS Cut Line= 3
      1950889.02     13511842.11      1950604.84     13511515.69
      1948678.86     13509797.93
#Sta/Elev= 30
  4350.4  622.92  4393.8  621.92    4408  621.19  4557.1  619.25  4655.8   618.9
  4677.7  618.24    4727  617.91    4840  617.81  4925.3  617.22  4985.2  616.24
  4985.7  615.74    4992  615.74  4992.5  616.24  5300.7   618.2    5350  618.08
  5406.9  618.84  5456.2  618.63  5612.5  619.79  5654.4   620.6  5668.6  620.25
  5725.4  620.51    5952  622.35  5994.6  622.26  6100.8  623.84  6186.1  624.21
  6242.9  625.75  6270.5  625.05    6717  628.52  7290.5  631.57  7363.9  632.33
#Mann= 3 ,-1 , 0
  4350.4     .05       0  4985.2    .035       0  4992.5     .05       0
Bank Sta=4985.2,4992.5
XS Rating Curve= 0 ,0
Exp/Cntr=0.3,0.1

Type RM Length L Ch R = 1 ,4110    ,475,475,475
BEGIN DESCRIPTION:
UNT 011 in BCW 5.0
END DESCRIPTION:
XS GIS Cut Line= 3
      1951526.85     13511227.08        1951075.       13510825.
      1949648.23     13509567.77
#Sta/Elev= 30
  4409.5   623.9  4511.2  622.84  4532.5  622.38    4554  623.38  4574.9  622.53
  4625.1  622.22  4631.8  622.88  4666.9  620.61  4717.1  620.05  4752.2  618.28
  4950.4   614.3  4988.8  612.94  4989.3  612.44  4996.7  612.44  4997.2  612.94
  5106.8  615.47  5383.9  619.68  5517.6  622.54  5609.6  623.43  5871.5  623.55
  6183.6  626.66  6431.2  627.45  6438.8  628.33  6445.4   627.7  6467.1  627.74
  6530.8  628.96  6573.5   628.1  6657.9   629.3  6700.6  628.06    6916  628.43
#Mann= 5 ,-1 , 0
  4409.5     .05       0  4511.2      .1       0  4988.8     .07       0
  4997.2      .1       0  5383.9     .05       0
Bank Sta=4988.8,4997.2
XS Rating Curve= 0 ,0
Exp/Cntr=0.3,0.1

Type RM Length L Ch R = 1 ,3635    ,894,894,894
BEGIN DESCRIPTION:
UNT 011 in BCW 4.0
END DESCRIPTION:
XS GIS Cut Line= 3
      1951689.64     13511114.29        1951475.       13510625.
      1950377.76     13508589.27
#Sta/Elev= 30
  4447.5  624.07  4542.9  623.33  4670.6  620.85    4687  622.07  4699.4  622.03
  4730.6  619.52    4775  618.58  4798.4  617.04  5000.3  612.53  5000.8  612.03
  5008.2  612.03  5008.7  612.53  5203.2  615.01  5394.6  615.35  5447.6  614.64
  5644.2  616.38  5689.8  616.57  5711.7  617.58  5742.9  617.13    5985  618.44
  6105.1   620.4  6110.8   619.9  6140.5  620.81    6504   621.9  6719.3  624.87
  6766.9  626.21  6821.2  626.13  7049.3  629.66  7187.8  629.55  7294.4  630.51
#Mann= 5 ,-1 , 0
  4447.5     .05       0  5000.3    .035       0  5008.7     .05       0
  5644.2      .1       0  6719.3     .05       0
Bank Sta=5000.3,5008.7
XS Rating Curve= 0 ,0
Exp/Cntr=0.3,0.1

Type RM Length L Ch R = 1 ,2741    ,489,489,489
BEGIN DESCRIPTION:
UNT 011 in BCW 3.0
END DESCRIPTION:
XS GIS Cut Line= 4
      1952318.96     13510884.25      1952236.49     13510289.59
      1952058.54     13509959.73      1951325.01     13509075.02
#Sta/Elev= 30
  4170.3  621.72  4307.1  620.96  4472.4  621.13  4593.6  618.18  4604.1     617
  4613.8  616.71  4664.2  615.95  4670.8  615.39  4675.8   615.9  4765.2  612.83
  4952.4  610.59  5057.2  610.43  5057.7  609.93    5066  609.93  5066.5  610.43
  5092.2  610.76  5118.1  611.63    5428  618.18  5584.3  619.47  5619.5  620.89
    5649  620.31  5655.9  621.14  5726.3  622.07  5769.2  621.54  5797.9  622.49
  5882.5  622.18  5911.2  622.44  5925.5  623.18  5989.3  623.26  6294.7  628.28
#Mann= 6 ,-1 , 0
  4170.3     .05       0  5057.2     .03       0  5066.5     .05       0
  5092.2      .1       0  5118.1     .05       0    5649      .1       0
Bank Sta=5057.2,5066.5
XS Rating Curve= 0 ,0
Exp/Cntr=0.3,0.1

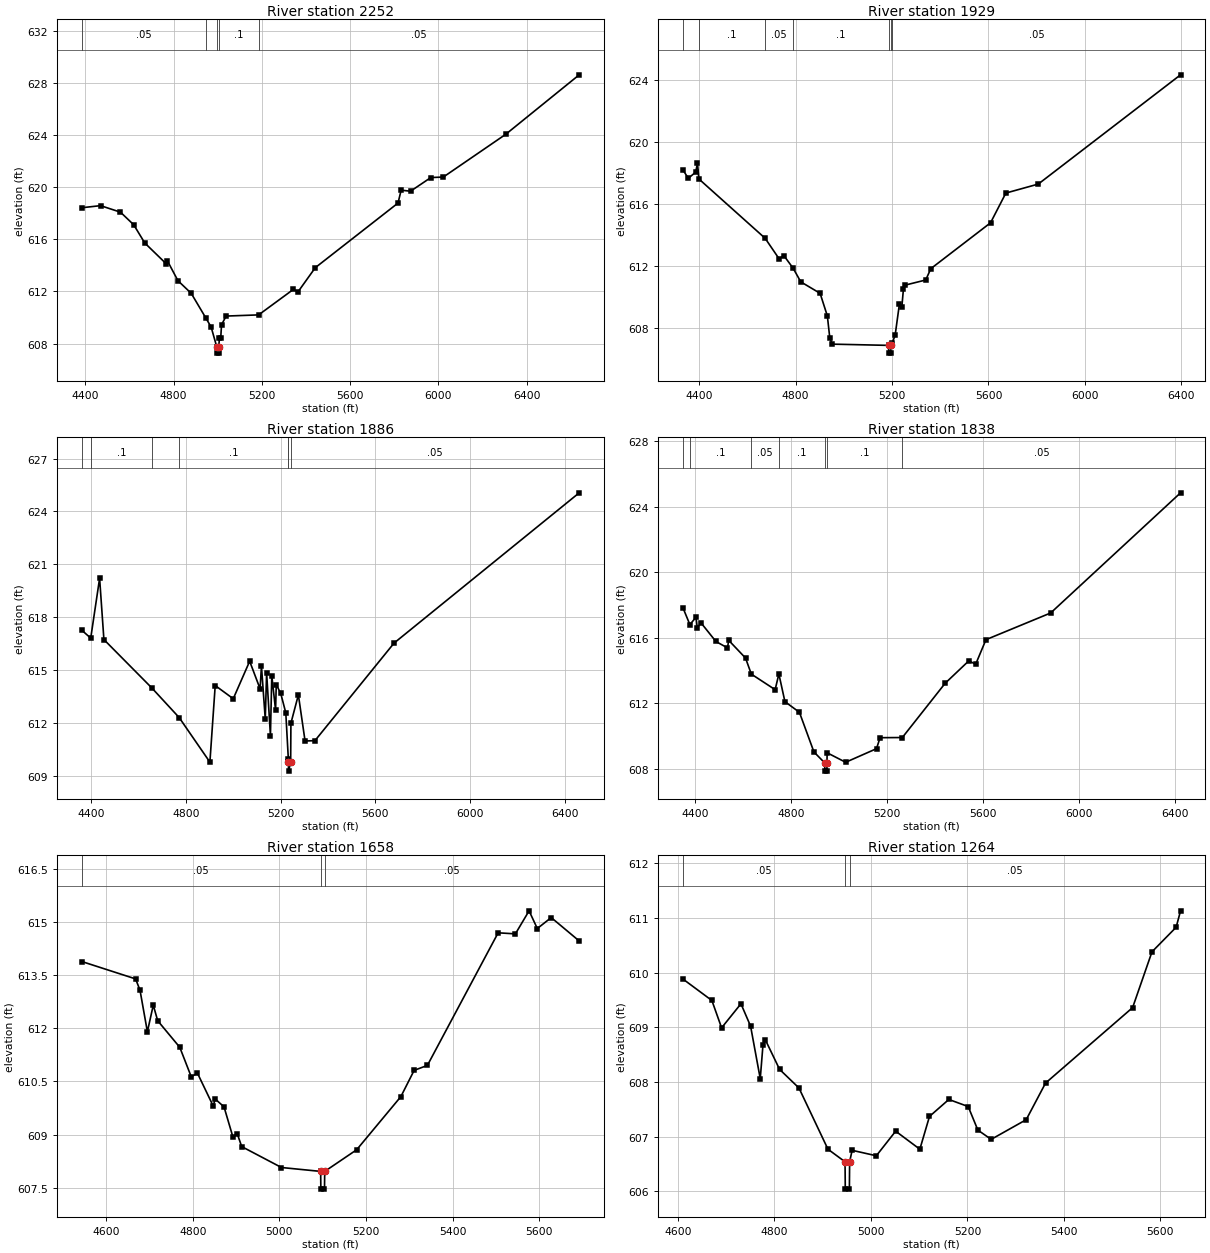
Type RM Length L Ch R = 1 ,2252    ,323,323,323
BEGIN DESCRIPTION:
UNT 011 in BCW 2.0
END DESCRIPTION:
XS GIS Cut Line= 3
       1952614.1     13510649.84        1952575.       13510025.
      1951475.03     13508825.04
#Sta/Elev= 30
  4384.2  618.44  4469.2   618.6  4559.4   618.1  4619.5  617.13  4669.6  615.73
  4767.4  614.12  4772.4  614.35  4819.9  612.83    4880  611.86  4945.3  609.99
  4970.2  609.27  4995.5  607.76    4996  607.26  5004.4  607.26  5004.9  607.76
  5007.8   608.4  5013.7   608.4  5017.4  609.44  5038.3  610.11  5185.5   610.2
  5342.9  612.16  5363.9  611.97  5442.2  613.83  5817.1   618.8  5831.3  619.79
  5873.8  619.71  5965.7  620.76  6022.5   620.8  6305.5  624.09  6638.1  628.66
#Mann= 5 ,-1 , 0
  4384.2     .05       0  4945.3      .1       0  4995.5     .07       0
  5004.9      .1       0  5185.5     .05       0
Bank Sta=4995.5,5004.9
XS Rating Curve= 0 ,0
Exp/Cntr=0.3,0.1

Type RM Length L Ch R = 1 ,1929    ,43,43,43
BEGIN DESCRIPTION:
Mapping XS a891d527
END DESCRIPTION:
XS GIS Cut Line= 6
      1952757.48     13510505.89      1952825.18      13510177.8
      1952835.59     13509849.68      1952752.26     13509766.34
      1952648.09     13509714.26      1951856.45     13508860.12
#Sta/Elev= 30
    4334  618.18  4355.3  617.65    4386  618.05  4393.5  618.63  4399.3  617.61
  4674.1  613.78  4731.8  612.46  4751.8  612.66  4790.1  611.85  4821.8  610.97
  4901.9  610.23    4932  608.77    4942  607.36  4952.1  606.95  5185.9  606.87
  5186.4  606.37  5194.8  606.37  5195.3  606.87  5200.8  607.03  5212.9  607.51
  5230.7  609.53  5240.7  609.33  5247.5  610.52  5254.8  610.76  5339.9  611.09
  5360.9  611.82  5608.6  614.78  5672.1   616.7  5806.5  617.28  6396.4  624.33
#Mann= 7 ,-1 , 0
    4334     .05       0  4399.3      .1       0  4674.1     .05       0
  4790.1      .1       0  5185.9     .07       0  5195.3      .1       0
  5200.8     .05       0
Bank Sta=5185.9,5195.3
XS Rating Curve= 0 ,0
Exp/Cntr=0.3,0.1

Type RM Length L Ch R = 1 ,1886    ,48,48,48
BEGIN DESCRIPTION:
Mapping XS 690824c9
END DESCRIPTION:
XS GIS Cut Line= 6
      1952830.39     13510448.61      1952908.51     13510073.64
      1952882.47     13509849.68       1952840.8     13509766.34
      1952637.68     13509651.76       1951882.5     13508766.37
#Sta/Elev= 30
  4361.1  617.26  4398.8  616.81  4436.3  620.21  4454.4  616.73  4657.5  613.97
    4772   612.3  4901.6  609.77    4924  614.12  5000.1  613.37  5069.4   615.5
  5113.4  613.93  5119.1  615.23  5135.2  612.21  5140.9  614.85    5157  611.28
  5162.7  614.68  5178.7  612.73  5181.6  614.17  5200.3  613.68  5221.8  612.57
  5232.5  609.96  5232.9  609.76  5233.4  609.26  5242.3  609.76  5243.4  611.98
  5274.9  613.59  5303.1  610.97  5344.8  610.99  5678.6  616.53  6459.7  625.06
#Mann= 7 ,-1 , 0
  4361.1     .05       0  4398.8      .1       0  4657.5     .05       0
    4772      .1       0  5232.5     .05       0  5232.9     .07       0
  5242.3     .05       0
Bank Sta=5232.9,5242.3
XS Rating Curve= 0 ,0
Exp/Cntr=0.3,0.1

Type RM Length L Ch R = 1 ,1838    ,180,180,180
BEGIN DESCRIPTION:
Mapping XS 2be6e25d
END DESCRIPTION:
XS GIS Cut Line= 6
      1952856.42     13510427.82      1952950.18     13510037.18
      1952934.55     13509901.76      1952898.09     13509755.93
      1952689.76     13509610.09       1951950.2     13508755.96
#Sta/Elev= 30
  4351.2   617.8  4379.3   616.8  4404.9  617.25    4410  616.62  4426.1   616.9
  4487.8  615.77    4536  615.38  4541.1  615.84  4611.2  614.76  4635.3  613.78
  4734.6  612.83  4750.1  613.79  4775.3   612.1  4835.7  611.45  4896.2  609.03
  4941.2  608.36  4941.7  607.86  4950.1  607.86  4950.6  608.36  4951.1  608.98
  5028.4   608.4  5156.9  609.23  5171.7   609.9  5264.5  609.91  5442.9  613.22
  5541.6  614.59  5570.1  614.38  5612.9  615.88  5882.6  617.51  6423.7  624.84
#Mann= 7 ,-1 , 0
  4351.2     .05       0  4379.3      .1       0  4635.3     .05       0
  4750.1      .1       0  4941.2     .07       0  4950.6      .1       0
  5264.5     .05       0
Bank Sta=4941.2,4950.6
XS Rating Curve= 0 ,0
Exp/Cntr=0.3,0.1

Type RM Length L Ch R = 1 ,1658    ,394,394,394
BEGIN DESCRIPTION:
Mapping XS bf29f756
END DESCRIPTION:
XS GIS Cut Line= 2
      1953170.58     13510206.66      1952941.42     13509081.66
#Sta/Elev= 30
  4543.8  613.88    4668  613.39  4678.2  613.07  4695.2   611.9  4708.8  612.65
    4719  612.21    4770  611.46  4796.4  610.63  4810.8  610.73  4846.9  609.81
    4852     610  4872.1  609.78  4892.4  608.94  4902.7  609.02  4912.9  608.66
  5004.7  608.07  5095.1  607.96  5095.6  607.46    5104  607.46  5104.5  607.96
  5178.2  608.57  5280.3  610.07  5310.9  610.81  5341.5  610.95  5504.8  614.69
  5544.6  614.66  5576.2  615.31  5595.2  614.81  5627.3  615.12  5691.9  614.46
#Mann= 3 ,-1 , 0
  4543.8     .05       0  5095.1    .035       0  5104.5     .05       0
Bank Sta=5095.1,5104.5
XS Rating Curve= 0 ,0
Exp/Cntr=0.3,0.1

Type RM Length L Ch R = 1 ,1264    ,308,308,308
BEGIN DESCRIPTION:
Mapping XS 48a02970
END DESCRIPTION:
XS GIS Cut Line= 2
      1953480.48     13510154.53      1953415.37     13509125.89
#Sta/Elev= 30
    4611  609.88  4670.6  609.49  4690.7  608.99  4730.8  609.43  4750.8  609.02
  4770.8  608.06  4776.4  608.67  4781.4  608.77  4810.9  608.23    4851  607.89
  4911.1  606.77  4946.5  606.54    4947  606.04  4955.5  606.04    4956  606.54
  4961.2  606.75  5011.3  606.65  5051.4   607.1  5101.5  606.77  5121.5  607.37
  5161.6  607.68  5201.7  607.55  5221.7  607.12  5249.3  606.95  5321.9  607.31
    5362  607.98  5542.4  609.36  5582.5  610.38  5632.6  610.83  5641.7  611.13
#Mann= 3 ,-1 , 0
    4611     .05       0  4946.5    .035       0    4956     .05       0
Bank Sta=4946.5,4956
XS Rating Curve= 0 ,0
Exp/Cntr=0.3,0.1

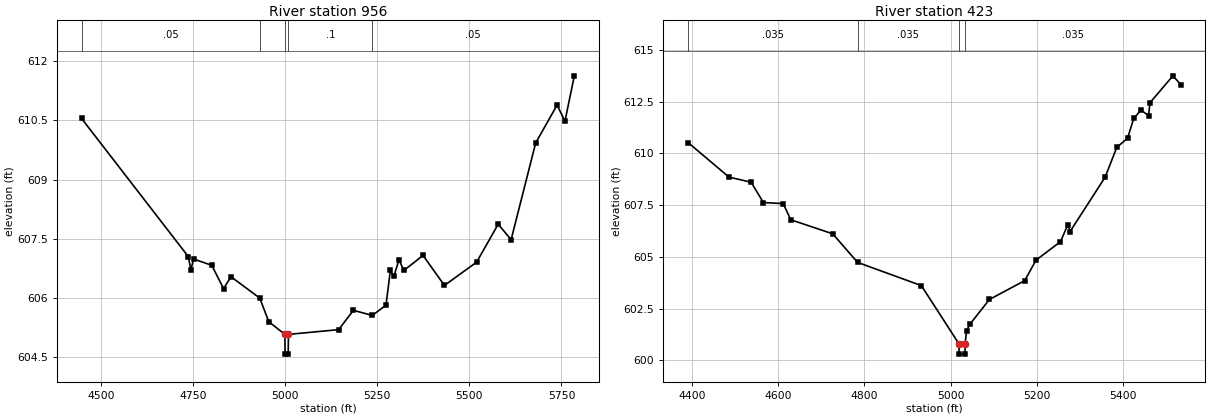
Type RM Length L Ch R = 1 ,956     ,533,533,533
BEGIN DESCRIPTION:
Mapping XS 872e3abc
END DESCRIPTION:
XS GIS Cut Line= 4
      1953475.26     13510235.31      1953733.08     13509972.28
      1953782.56     13509573.84      1953486.65     13509088.45
#Sta/Elev= 30
  4446.6  610.55  4736.6  607.05  4743.6  606.71  4750.7  606.99  4800.2  606.83
  4832.3  606.24  4852.5  606.54  4930.5     606  4955.2   605.4  4998.9  605.08
  4999.4  604.58  5007.9  604.58  5008.4  605.08  5144.7   605.2    5185  605.69
  5236.1  605.56  5273.4  605.82  5285.3   606.7  5294.7  606.55  5308.8  606.97
  5321.9   606.7  5374.1  607.08  5432.2  606.32  5519.6  606.91  5578.1  607.87
  5613.3  607.48    5680  609.93  5738.1  610.89  5759.5  610.48  5784.9  611.63
#Mann= 5 ,-1 , 0
  4446.6     .05       0  4930.5     .05       0  4998.9    .035       0
  5008.4      .1       0  5236.1     .05       0
Bank Sta=4998.9,5008.4
XS Rating Curve= 0 ,0
Exp/Cntr=0.3,0.1

Type RM Length L Ch R = 1 ,423     ,0,0,0
BEGIN DESCRIPTION:
UNT 011 in BCW 1.0
END DESCRIPTION:
XS GIS Cut Line= 4
      1953496.13     13510310.81      1953888.46     13510130.27
      1954506.52     13509959.26      1954558.58      13509912.4
#Sta/Elev= 30
  4390.9  610.52  4485.9  608.85  4537.3   608.6  4565.8  607.62  4611.7  607.57
  4629.2  606.79  4726.6  606.11  4784.3  604.73  4932.2  603.61  5019.4   600.8
  5019.9   600.3  5033.4   600.3  5033.9   600.8  5037.1  601.44  5045.5  601.76
  5090.2  602.94    5172  603.85  5198.3  604.84    5255  605.73  5272.2  606.56
  5277.3  606.22  5358.7  608.85  5385.5  610.28  5410.6  610.73    5425  611.68
  5441.7  612.09  5459.3  611.82  5462.7  612.44  5515.8  613.74  5534.1  613.32
#Mann= 4 ,-1 , 0
  4390.9    .035       0  4784.3    .035       0  5019.4    .035       0
  5033.9    .035       0
Bank Sta=5019.4,5033.9
XS Rating Curve= 0 ,0
Exp/Cntr=0.3,0.1
LCMann Table=0

Chan Stop Cuts=-1
Use User Specified Reach Order=0
Composite Channel Slope=5