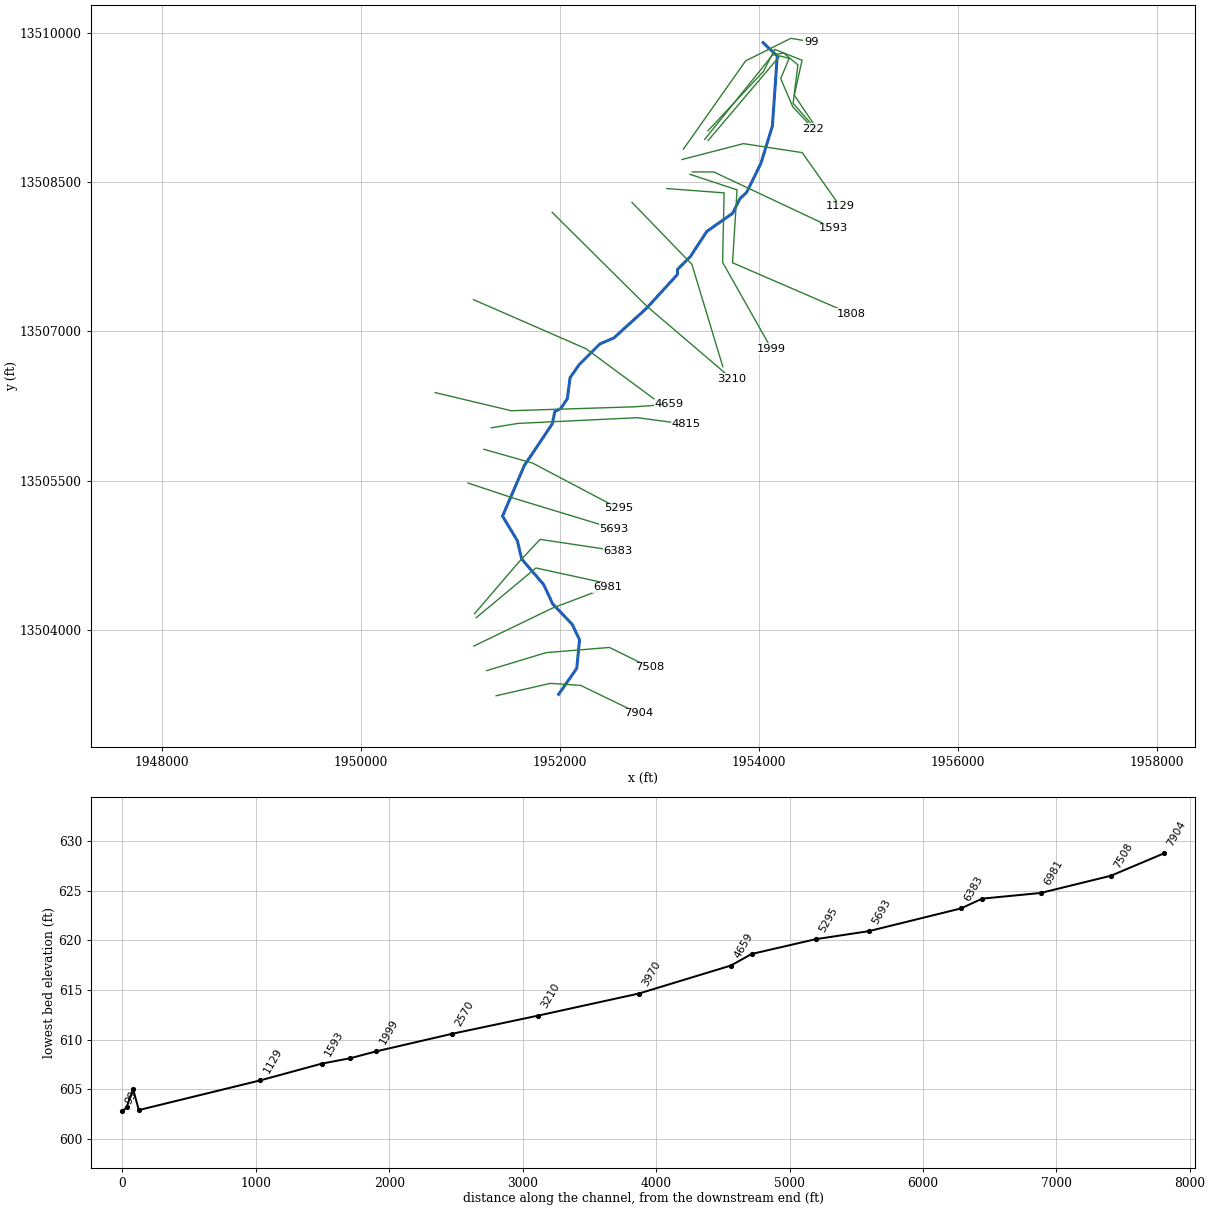
--- UNT 012 in BCW.prj (project) ---

Proj Title=UNT 012 in BCW Base Level Engineering
Current Plan=p01
Default Exp/Contr=0.3,0.1
English Units
Geom File=g01
Flow File=f01
Plan File=p01
Y Axis Title=Elevation
X Axis Title(PF)=Main Channel Distance
X Axis Title(XS)=Station
BEGIN DESCRIPTION:
UNT 012 in BCW
END DESCRIPTION:
DSS Export Rating Curves= 0
DSS Export Rating Curve Sorted= 0
DSS Export Volume Flow Curves= 0
DXF OffsetX= 0
DXF OffsetY= 0
DXF ScaleX= 1
DXF ScaleY= 10

--- UNT 012 in BCW.p01 (plan) ---

Plan Title=Multiple Run
Short Identifier=Multiple
Geom File=g01
Flow File=f01
Subcritical Flow
K Sum by GR= 0
Std Step Tol= 0.01
Critical Tol= 0.01
Num of Std Step Trials= 20
Max Error Tol= 0.3
Flow Tol Ratio= 0.001
Split Flow NTrial= 30
Split Flow Tol= 0.02
Split Flow Ratio= 0.02
Log Output Level= 0
Friction Slope Method= 1
Unsteady Friction Slope Method= 2
Unsteady Bridges Friction Slope Method= 1
Parabolic Critical Depth
Global Vel Dist=  1 , 1 , 1
Global Log Level= 0
CheckData=True
Encroach Param= -1, 0, 0, 0
BEGIN DESCRIPTION:
Multiple Run
END DESCRIPTION:

--- UNT 012 in BCW.f01 (steady flow) ---

Flow Title=Multiple
Program Version=5.05
Number of Profiles= 7
Profile Names=10-year,25-year,50-year,1pct_min,100-year,1pct_plu,500-year
River Rch & RM=UNT 012 in BCW,Reach-1         ,7904
     127     172     208     126     251     502     374
River Rch & RM=UNT 012 in BCW,Reach-1         ,7508
     134     182     220     134     266     532     397
River Rch & RM=UNT 012 in BCW,Reach-1         ,5693
     199     275     338     207     414     826     633
River Rch & RM=UNT 012 in BCW,Reach-1         ,3210
     228     317     391     241     480     958     738
Boundary for River Rch & Prof#=UNT 012 in BCW,Reach-1         , 1
Up Type= 0
Dn Type= 3
Dn Slope=0.005
Boundary for River Rch & Prof#=UNT 012 in BCW,Reach-1         , 2
Up Type= 0
Dn Type= 3
Dn Slope=0.005
Boundary for River Rch & Prof#=UNT 012 in BCW,Reach-1         , 3
Up Type= 0
Dn Type= 3
Dn Slope=0.005
Boundary for River Rch & Prof#=UNT 012 in BCW,Reach-1         , 4
Up Type= 0
Dn Type= 3
Dn Slope=0.005
Boundary for River Rch & Prof#=UNT 012 in BCW,Reach-1         , 5
Up Type= 0
Dn Type= 3
Dn Slope=0.005
Boundary for River Rch & Prof#=UNT 012 in BCW,Reach-1         , 6
Up Type= 0
Dn Type= 3
Dn Slope=0.005
Boundary for River Rch & Prof#=UNT 012 in BCW,Reach-1         , 7
Up Type= 0
Dn Type= 3
Dn Slope=0.005
DSS Import GetInterval= 0
DSS Import GetPeak= 0
DSS Import FillOption= 0

--- UNT 012 in BCW.g01 (geometry) ---

Geom Title=Existing Conditions
Program Version=5.05

River Reach=UNT 012 in BCW  ,Reach-1
Reach XY= 30
      1951985.35     13503349.09      1952167.99     13503611.36
      1952195.77     13503898.16       1952120.8     13504054.54
       1951925.5     13504259.84      1951835.36     13504453.03
      1951614.52     13504709.97       1951570.8     13504894.54
      1951422.03     13505142.21      1951640.69      13505651.5
      1951921.94     13506070.77      1951947.11     13506193.16
      1952007.01     13506225.28      1952072.98     13506323.37
       1952100.8     13506534.54       1952190.8     13506664.54
       1952400.8     13506874.54       1952540.8     13506934.54
       1952870.8     13507234.54       1953180.8     13507574.54
       1953180.8     13507624.54       1953310.8     13507754.54
      1953475.38     13508006.29      1953733.76     13508187.49
      1953806.63     13508333.37      1953876.77     13508400.73
      1954019.47     13508691.92      1954134.49     13509066.27
      1954183.32     13509771.57       1954040.8     13509904.54

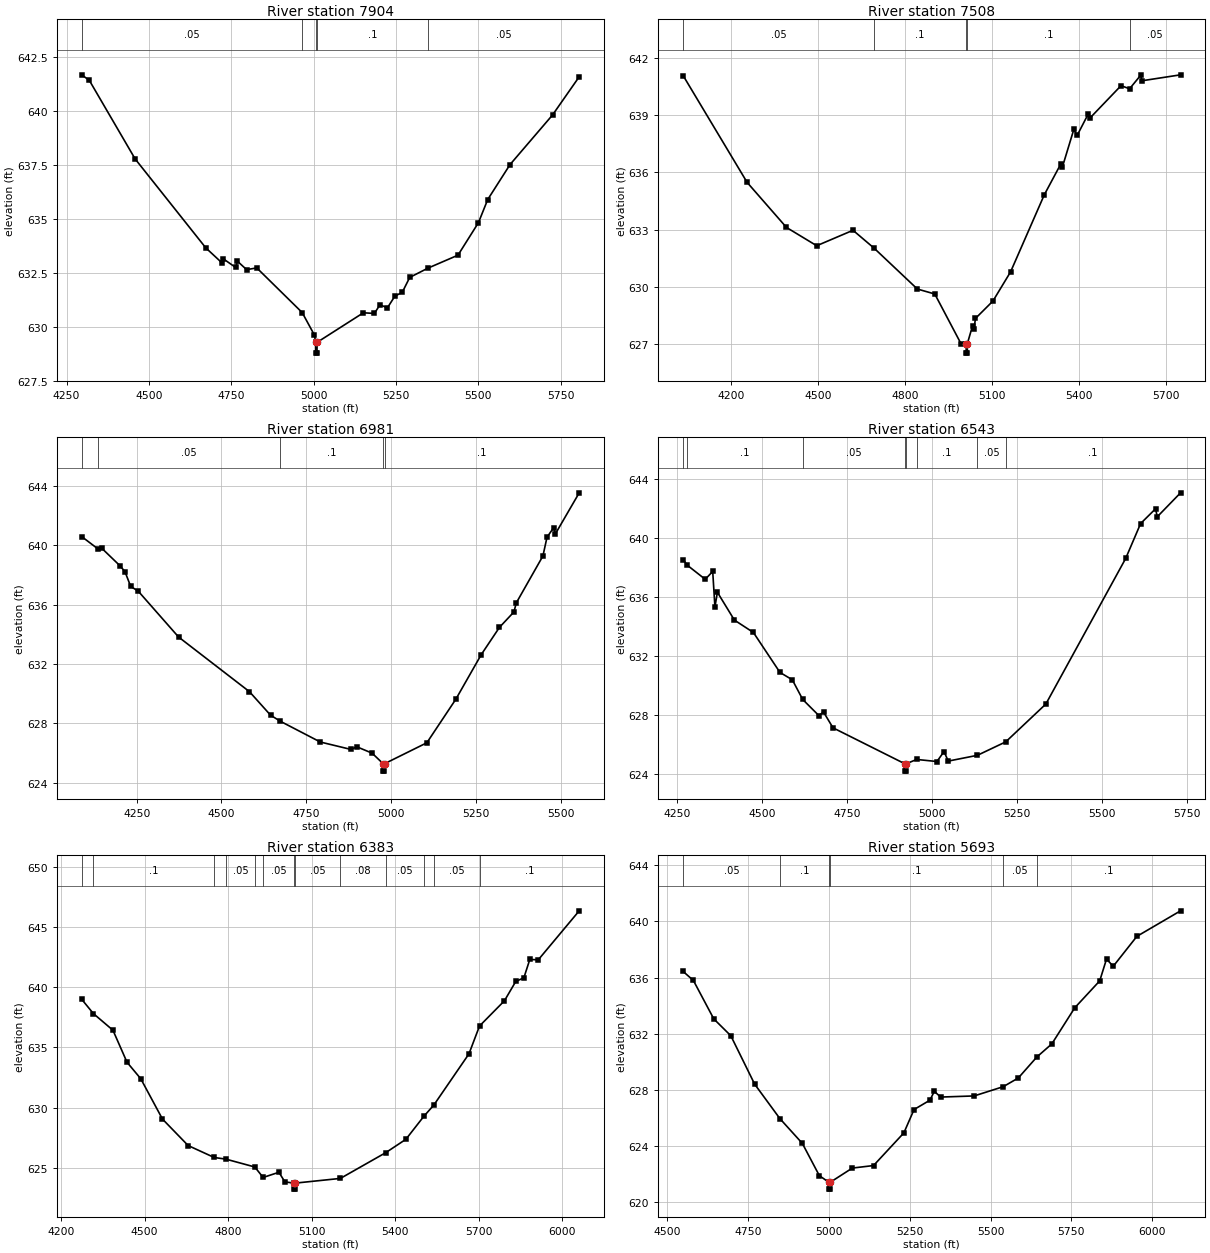
Type RM Length L Ch R = 1 ,7904    ,396,396,396
BEGIN DESCRIPTION:
UNT 012 in BCW 15.0
END DESCRIPTION:
XS GIS Cut Line= 4
      1951357.24     13503334.92      1951902.34     13503459.92
       1952207.9     13503439.08      1952787.77     13503157.83
#Sta/Elev= 30
  4296.4  641.67  4319.4  641.41  4458.4  637.77  4672.8  633.65  4720.8  632.97
    4726  633.14  4763.7  632.74  4768.9  633.03  4796.8  632.64  4827.6  632.72
  4965.5  630.65  5002.5  629.61  5006.7  629.27  5006.9  628.77  5010.4  628.77
  5010.7  629.27  5151.2  630.64  5184.6  630.61  5201.6  631.01  5224.2  630.87
  5246.8  631.41  5269.3  631.59  5291.9  632.28  5347.3  632.71  5438.4  633.31
  5500.6  634.82  5528.7  635.89  5596.4  637.51  5725.5  639.81  5806.4  641.58
#Mann= 5 ,-1 , 0
  4296.4     .05       0  4965.5      .1       0  5006.7     .07       0
  5010.7      .1       0  5347.3     .05       0
Bank Sta=5006.7,5010.7
XS Rating Curve= 0 ,0
Exp/Cntr=0.3,0.1

Type RM Length L Ch R = 1 ,7508    ,527,527,527
BEGIN DESCRIPTION:
Mapping XS 6b1e6550
END DESCRIPTION:
XS GIS Cut Line= 4
      1951263.48     13503588.39      1951860.68     13503768.94
      1952496.09     13503821.03      1952905.47     13503619.81
#Sta/Elev= 30
  4034.2  641.07  4255.2  635.47    4391  633.11  4495.5  632.15  4620.8  632.96
  4693.8  632.02    4843  629.88  4903.2  629.62  4993.5  627.02  5011.5  627.02
  5011.8  626.52  5015.4  626.52  5015.7  627.02  5033.5  627.95  5038.5  627.79
  5043.7  628.34  5103.9  629.25  5164.9  630.78  5281.3  634.82  5338.4  636.44
  5343.9  636.28  5383.3  638.25  5394.7  637.93  5433.8  639.08  5439.4  638.85
  5546.2  640.54  5575.9  640.38  5613.7  641.08  5619.2   640.8  5751.8  641.11
#Mann= 5 ,-1 , 0
  4034.2     .05       0  4693.8      .1       0  5011.5     .07       0
  5015.7      .1       0  5575.9     .05       0
Bank Sta=5011.5,5015.7
XS Rating Curve= 0 ,0
Exp/Cntr=0.3,0.1

Type RM Length L Ch R = 1 ,6981    ,438,438,438
BEGIN DESCRIPTION:
UNT 012 in BCW 14.0
END DESCRIPTION:
XS GIS Cut Line= 3
      1951134.19     13503835.35       1951919.8     13504215.13
      1952474.97     13504424.99
#Sta/Elev= 30
  4088.3  640.57  4136.1  639.74  4147.6  639.78  4200.3  638.62  4215.4  638.22
  4232.4  637.22    4255  636.89  4373.6  633.81  4582.5  630.13  4644.6  628.55
  4673.3  628.14  4791.4  626.74  4881.8  626.24  4898.8  626.42    4944  625.99
  4976.5  625.28  4976.7  624.78  4980.4  624.78  4980.7  625.28  5105.4  626.69
    5191  629.63  5265.8  632.63  5319.3  634.46    5362   635.5    5369  636.11
  5447.5  639.27  5459.5  640.53    5479  641.17  5484.3  640.76  5554.4  643.52
#Mann= 5 ,-1 , 0
  4088.3      .1       0  4136.1     .05       0  4673.3      .1       0
  4976.5     .07       0  4980.7      .1       0
Bank Sta=4976.5,4980.7
XS Rating Curve= 0 ,0
Exp/Cntr=0.3,0.1

Type RM Length L Ch R = 1 ,6543    ,160,160,160
BEGIN DESCRIPTION:
UNT 012 in BCW 13.0
END DESCRIPTION:
XS GIS Cut Line= 3
      1951157.46     13504120.57      1951757.47     13504620.57
      1952425.05     13504474.99
#Sta/Elev= 30
  4267.3  638.52  4279.6  638.14  4332.3  637.19  4354.4  637.72  4360.9  635.32
  4368.2  636.31  4418.2  634.43  4474.2  633.59  4552.3  630.89  4588.7  630.39
  4619.3  629.06  4666.8  627.97  4680.6  628.21  4708.5  627.14  4919.8  624.71
  4920.1  624.21  4923.8  624.21  4924.1  624.71  4954.8     625  5014.4  624.86
  5035.2  625.53  5047.9  624.89  5133.6  625.28    5217  626.19  5335.1  628.75
  5570.1   638.6    5614  640.96    5658  641.96  5663.1  641.42  5731.6  643.04
#Mann= 8 ,-1 , 0
  4267.3     .05       0  4279.6      .1       0  4619.3     .05       0
  4919.8     .07       0  4924.1     .05       0  4954.8      .1       0
  5133.6     .05       0    5217      .1       0
Bank Sta=4919.8,4924.1
XS Rating Curve= 0 ,0
Exp/Cntr=0.3,0.1

Type RM Length L Ch R = 1 ,6383    ,690,690,690
BEGIN DESCRIPTION:
UNT 012 in BCW 12.0
END DESCRIPTION:
XS GIS Cut Line= 4
      1951140.73     13504160.89      1951575.61     13504668.69
      1951799.57     13504908.27      1952580.41     13504791.15
#Sta/Elev= 30
  4274.6  638.98  4316.4   637.8  4386.5  636.42    4437  633.76  4486.4  632.39
  4564.3  629.04  4656.5  626.84    4750  625.85  4792.3  625.71  4895.8  625.06
  4925.8  624.19  4982.5  624.62  5003.9  623.82    5037  623.72  5037.3  623.22
    5041  623.22  5041.3  623.72  5203.2  624.11  5366.1  626.25  5438.4  627.36
  5502.9  629.27  5538.9  630.21  5664.9  634.46  5702.7  636.77  5792.3  638.87
  5832.8  640.47  5862.1  640.78  5883.3   642.3  5913.7  642.27  6060.7  646.34
#Mann= 13 ,-1 , 0
  4274.6     .05       0  4316.4      .1       0    4750     .08       0
  4792.3     .05       0  4895.8     .08       0  4925.8     .05       0
    5037     .04       0  5041.3     .05       0  5203.2     .08       0
  5366.1     .05       0  5502.9      .1       0  5538.9     .05       0
  5702.7      .1       0
Bank Sta=5037,5041.3
XS Rating Curve= 0 ,0
Exp/Cntr=0.3,0.1

Type RM Length L Ch R = 1 ,5693    ,398,398,398
BEGIN DESCRIPTION:
UNT 012 in BCW 11.0
END DESCRIPTION:
XS GIS Cut Line= 3
      1951074.96     13505475.01        1951525.       13505325.
      1952544.33     13505015.05
#Sta/Elev= 30
  4548.4  636.44  4580.1   635.8  4643.3  633.06    4696  631.86  4769.8  628.41
  4848.1  625.95  4917.4  624.19  4970.1  621.89  4998.8  621.43  4999.3  620.93
  5004.1  620.93  5004.6  621.43  5072.1  622.43  5137.8  622.61  5231.8  624.94
  5263.2   626.6  5312.6  627.27  5325.9   627.9  5345.5  627.49  5449.3  627.57
  5539.4  628.23    5586  628.85  5643.2  630.34  5689.8  631.28  5760.7  633.85
    5838  635.77    5859  637.32  5879.9  636.81    5953  638.94  6088.2  640.76
#Mann= 6 ,-1 , 0
  4548.4     .05       0  4848.1      .1       0  4998.8     .07       0
  5004.6      .1       0  5539.4     .05       0  5643.2      .1       0
Bank Sta=4998.8,5004.6
XS Rating Curve= 0 ,0
Exp/Cntr=0.3,0.1

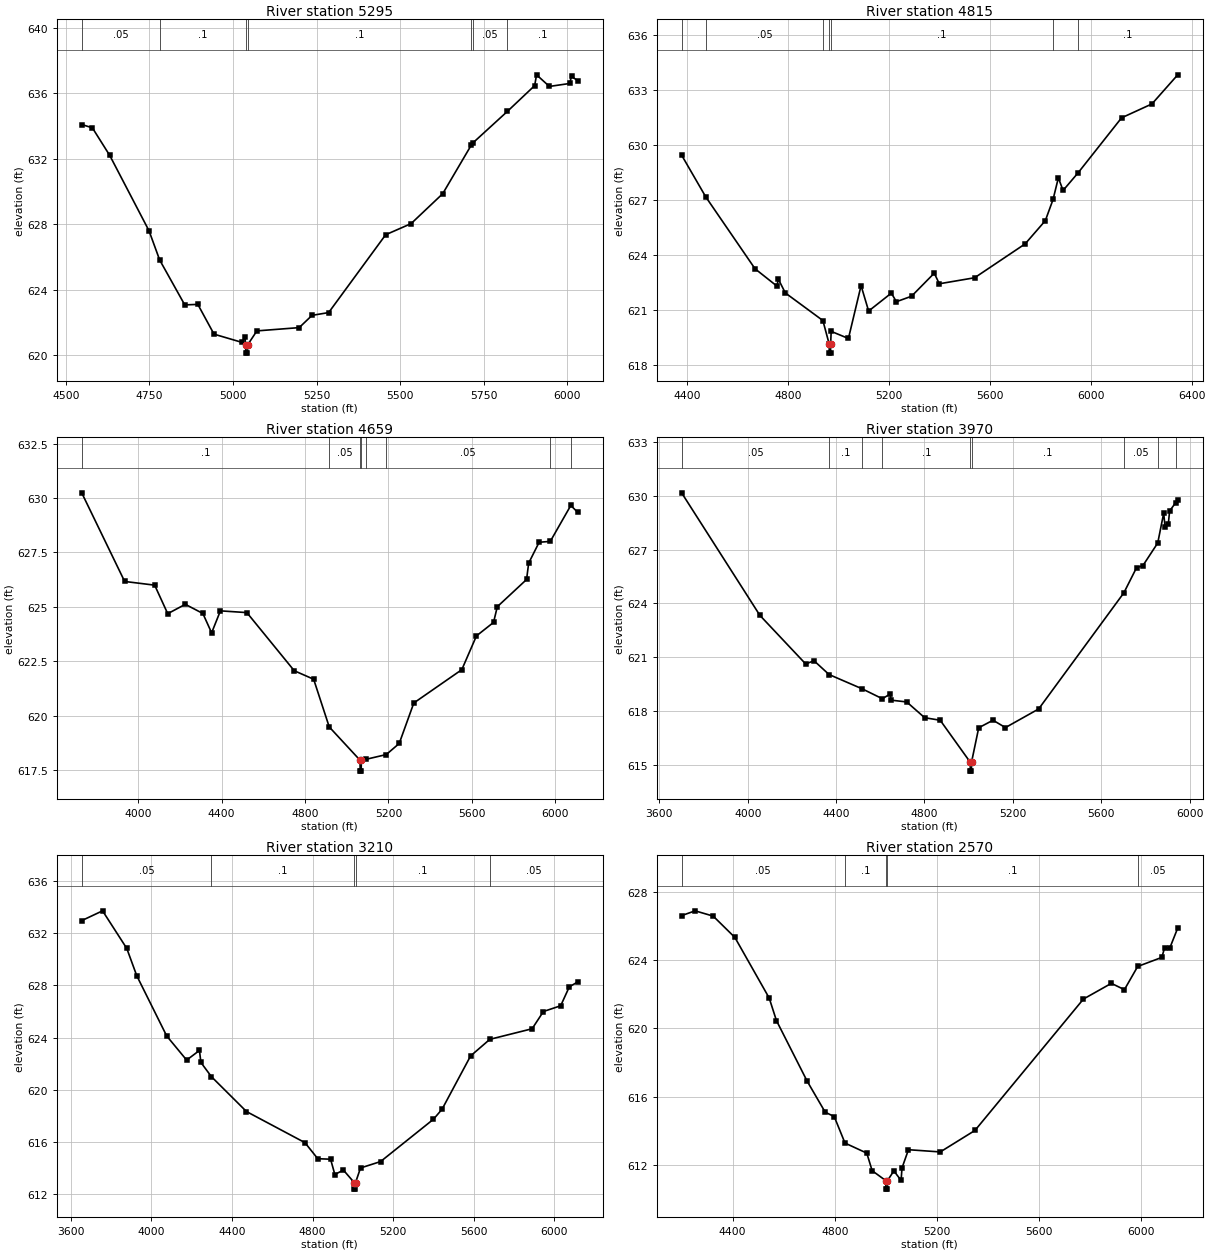
Type RM Length L Ch R = 1 ,5295    ,480,480,480
BEGIN DESCRIPTION:
UNT 012 in BCW 10.0
END DESCRIPTION:
XS GIS Cut Line= 3
      1951234.45     13505814.53        1951725.       13505675.
      1952586.02     13505220.77
#Sta/Elev= 30
  4547.8   634.1  4579.6   633.9  4631.6  632.21  4749.1   627.6  4780.8  625.82
  4855.9  623.07    4895   623.1  4943.4  621.28  5026.6  620.78  5035.7   621.1
    5038  620.62  5038.5  620.12  5043.3  620.12  5043.8  620.62  5071.6  621.48
  5198.1  621.68  5236.5  622.43  5286.2   622.6  5456.7  627.36  5532.7  628.04
  5627.3  629.87  5713.2  632.86  5717.2  632.97    5821  634.91  5902.2  636.48
  5907.9  637.14  5946.3  636.43  6006.7  636.61  6012.4  637.04  6031.3  636.78
#Mann= 7 ,-1 , 0
  4547.8     .05       0  4780.8      .1       0    5038     .07       0
  5043.8      .1       0  5713.2     .08       0  5717.2     .05       0
    5821      .1       0
Bank Sta=5038,5043.8
XS Rating Curve= 0 ,0
Exp/Cntr=0.3,0.1

Type RM Length L Ch R = 1 ,4815    ,156,156,156
BEGIN DESCRIPTION:
Mapping XS e74ed044
END DESCRIPTION:
XS GIS Cut Line= 4
      1951307.41     13506030.67      1951578.22     13506074.94
      1952776.13     13506132.23      1953265.74     13506067.12
#Sta/Elev= 30
  4377.2  629.45  4472.9  627.17  4668.4  623.24  4755.5  622.29  4760.5  622.68
  4788.5  621.92  4937.5  620.41  4962.4  619.13  4962.8  618.63  4967.8  618.63
  4968.3  619.13  4970.3  619.82  5038.8  619.43  5088.9  622.32  5118.9  620.93
    5209  621.91    5229  621.44  5289.1  621.74  5379.2     623  5399.2  622.42
  5539.4  622.75  5739.6   624.6  5819.7  625.87  5850.4  627.03  5871.4  628.21
  5890.1  627.52    5950  628.49  6122.1  631.49  6242.6  632.25  6344.8  633.84
#Mann= 7 ,-1 , 0
  4377.2     .08       0  4472.9     .05       0  4937.5      .1       0
  4962.4     .07       0  4968.3      .1       0  5850.4     .08       0
    5950      .1       0
Bank Sta=4962.4,4968.3
XS Rating Curve= 0 ,0
Exp/Cntr=0.3,0.1

Type RM Length L Ch R = 1 ,4659    ,689,689,689
BEGIN DESCRIPTION:
Mapping XS 349f3ac0
END DESCRIPTION:
XS GIS Cut Line= 4
      1950744.87     13506384.84       1951507.9     13506202.54
      1952744.88      13506241.6      1953100.04     13506267.53
#Sta/Elev= 30
  3729.4  630.24  3935.2  626.17  4079.1     626  4141.7  624.69  4225.9  625.12
  4310.1   624.7  4352.1  623.81  4394.2  624.82    4521  624.74  4748.2  622.07
  4841.2  621.68  4915.9  619.49  5063.7  617.96  5064.1  617.46  5069.1  617.46
  5069.6  617.96  5090.9     618  5189.2  618.22  5251.4  618.73  5321.4  620.59
  5551.5  622.12  5621.6  623.67  5703.6  624.29  5721.6  625.01  5861.9  626.26
  5871.9  627.01  5922.1  627.97  5975.6  628.01  6073.9  629.66  6107.6  629.34
#Mann= 8 ,-1 , 0
  3729.4      .1       0  4915.9     .05       0  5063.7     .04       0
  5069.6     .05       0  5090.9     .08       0  5189.2     .05       0
  5975.6     .08       0  6073.9     .05       0
Bank Sta=5063.7,5069.6
XS Rating Curve= 0 ,0
Exp/Cntr=0.3,0.1

Type RM Length L Ch R = 1 ,3970    ,760,760,760
BEGIN DESCRIPTION:
UNT 012 in BCW 6.0
END DESCRIPTION:
XS GIS Cut Line= 3
      1951130.34     13507319.71      1952263.11     13506824.94
      1953074.99     13506225.01
#Sta/Elev= 30
  3700.9  630.17  4055.3  623.33  4262.5  620.62  4300.2   620.8  4368.3  620.03
  4518.6  619.23  4609.6  618.68  4644.3  618.94  4649.7   618.6  4719.9   618.5
  4801.1  617.62  4871.3  617.48  5007.2  615.14  5007.7  614.64  5012.7  614.64
  5013.2  615.14  5045.7  617.06  5110.4  617.48  5166.7  617.07  5317.1  618.11
  5702.7  624.59    5760  625.99  5788.9  626.11    5856  627.37  5882.9  629.03
  5889.1  628.29  5903.7  628.41  5909.9  629.16  5937.3  629.62  5946.5  629.77
#Mann= 9 ,-1 , 0
  3700.9     .05       0  4368.3      .1       0  4518.6     .05       0
  4609.6      .1       0  5007.2     .07       0  5013.2      .1       0
  5702.7     .05       0    5856     .08       0  5937.3     .05       0
Bank Sta=5007.2,5013.2
XS Rating Curve= 0 ,0
Exp/Cntr=0.3,0.1

Type RM Length L Ch R = 1 ,3210    ,640,640,640
BEGIN DESCRIPTION:
UNT 012 in BCW 5.0
END DESCRIPTION:
XS GIS Cut Line= 3
      1951921.09     13508197.34      1952872.49     13507252.89
      1953725.03     13506524.97
#Sta/Elev= 30
  3654.7  632.96  3758.1  633.71  3878.3  630.83  3927.8  628.74  4076.3  624.13
  4175.3  622.28  4238.9  623.02    4246   622.1  4298.3  621.01  4472.3  618.34
  4762.2  615.96  4825.9  614.73  4889.5  614.69  4910.7  613.52  4953.1  613.86
  5006.8   612.9  5007.3   612.4  5012.9   612.4  5013.4   612.9    5038  614.02
  5137.5  614.51  5399.9  617.75  5442.7  618.52  5584.3   622.6  5679.7  623.87
  5889.5  624.68  5945.5     626  6031.2  626.44    6074  627.89  6116.3  628.27
#Mann= 5 ,-1 , 0
  3654.7     .05       0  4298.3      .1       0  5006.8     .07       0
  5013.4      .1       0  5679.7     .05       0
Bank Sta=5006.8,5013.4
XS Rating Curve= 0 ,0
Exp/Cntr=0.3,0.1

Type RM Length L Ch R = 1 ,2570    ,571,571,571
BEGIN DESCRIPTION:
UNT 012 in BCW 4.0
END DESCRIPTION:
XS GIS Cut Line= 3
      1952723.21       13508298.        1953325.       13507675.
      1953636.38     13506645.24
#Sta/Elev= 30
  4200.1  626.61    4253  626.89  4323.7  626.58  4408.6  625.33  4542.9  621.78
  4571.2  620.46  4691.4  616.91  4762.1  615.09  4797.6  614.83  4839.6  613.28
  4924.9  612.69    4946  611.66  4999.2  611.08  4999.7  610.58  5005.5  610.58
    5006  611.08  5030.9  611.65  5059.2  611.09  5062.8  611.82    5088  612.89
  5212.6  612.76  5348.4  614.02    5773  621.72  5882.3  622.64  5933.4  622.27
  5985.4  623.63  6079.7  624.16  6090.4   624.7    6111  624.71  6142.1  625.88
#Mann= 5 ,-1 , 0
  4200.1     .05       0  4839.6      .1       0  4999.2     .07       0
    5006      .1       0  5985.4     .05       0
Bank Sta=4999.2,5006
XS Rating Curve= 0 ,0
Exp/Cntr=0.3,0.1

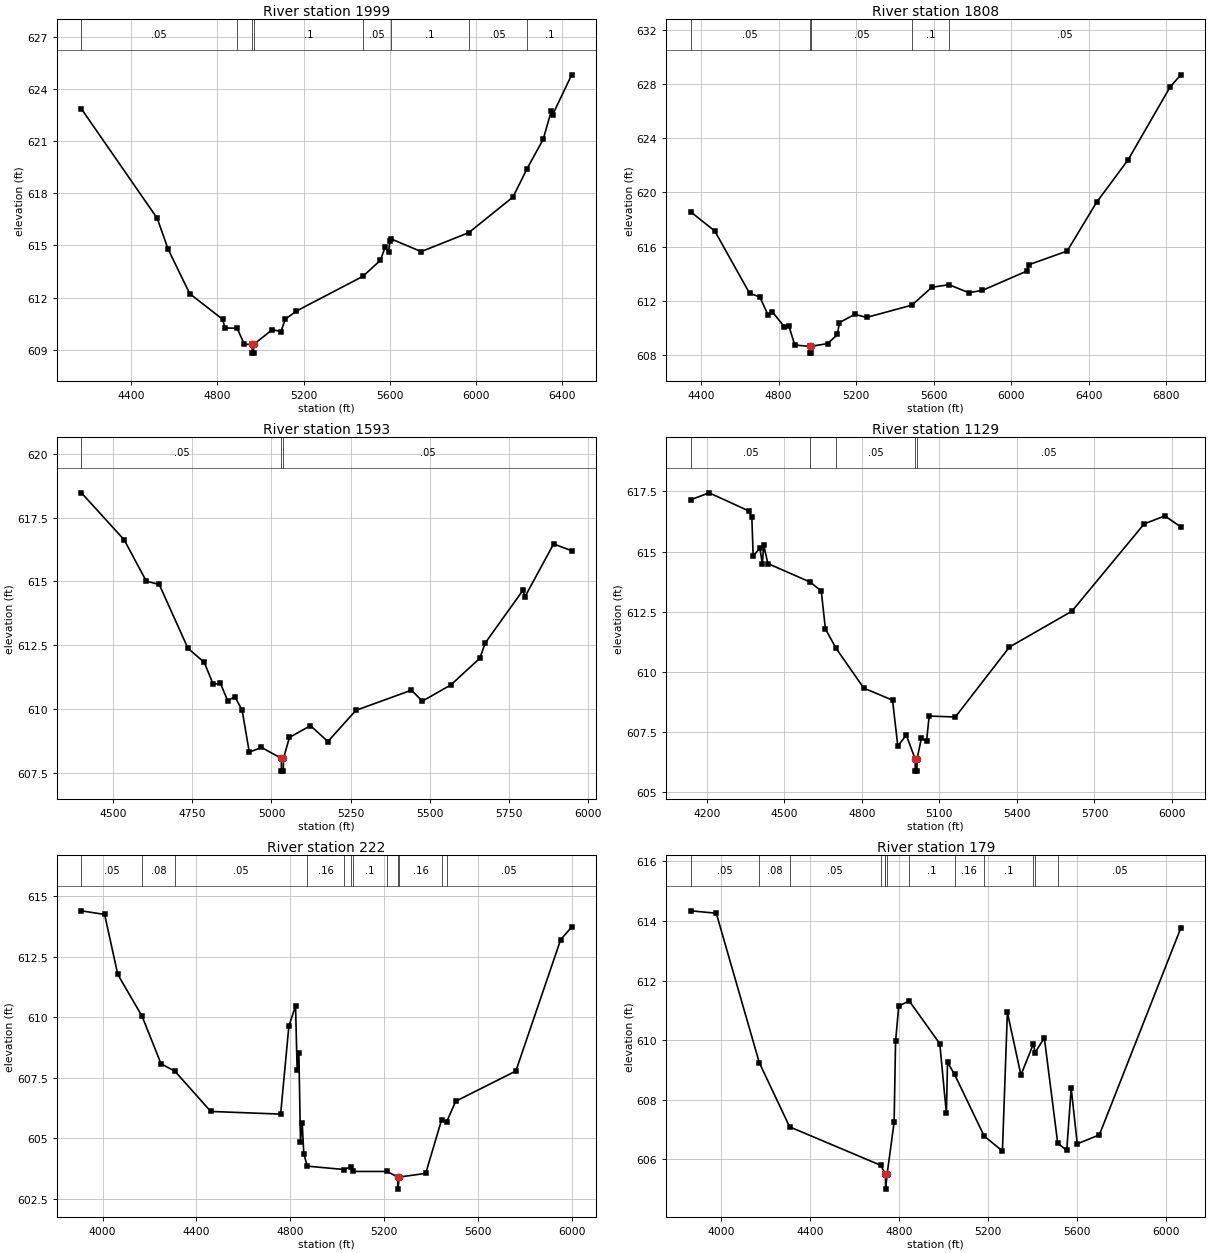
Type RM Length L Ch R = 1 ,1999    ,191,191,191
BEGIN DESCRIPTION:
UNT 012 in BCW 3.0
END DESCRIPTION:
XS GIS Cut Line= 4
      1953073.96     13508437.34      1953649.07     13508393.94
      1953633.88     13507695.15      1954125.01     13506824.98
#Sta/Elev= 30
    4169  622.85    4521  616.55  4571.2  614.78  4671.5  612.22  4824.7  610.74
  4834.7  610.25  4891.7  610.23  4924.7  609.31  4961.3   609.3  4961.8   608.8
  4967.7   608.8  4968.2   609.3  5054.8  610.15  5094.8  610.04  5114.8  610.75
  5166.5  611.22  5475.3  613.22  5556.4  614.14  5578.1  614.89    5594  614.61
  5599.7  615.23  5607.8  615.36  5745.6  614.64  5966.3  615.73  6171.6  617.78
  6236.8  619.41  6311.7   621.1  6349.3  622.73    6355   622.5  6443.9  624.81
#Mann= 8 ,-1 , 0
    4169     .05       0  4891.7      .1       0  4961.3     .07       0
  4968.2      .1       0  5475.3     .05       0  5607.8      .1       0
  5966.3     .05       0  6236.8      .1       0
Bank Sta=4961.3,4968.2
XS Rating Curve= 0 ,0
Exp/Cntr=0.3,0.1

Type RM Length L Ch R = 1 ,1808    ,215,215,215
BEGIN DESCRIPTION:
UNT 012 in BCW 2.0
END DESCRIPTION:
XS GIS Cut Line= 4
      1953306.22     13508580.56      1953779.28     13508424.32
      1953733.71     13507690.81      1954925.02     13507174.99
#Sta/Elev= 30
  4345.6  618.57  4470.2  617.15  4649.7  612.55  4702.9  612.27  4744.5  610.96
  4766.4  611.18  4829.9  610.07  4853.1  610.11  4883.2  608.72  4959.9  608.62
  4960.4  608.12  4966.3  608.12  4966.8  608.62  5053.5  608.83  5103.6   609.5
  5113.6  610.38  5193.8  610.99  5253.9  610.76  5488.2  611.67    5591  612.99
  5679.2  613.18  5781.9  612.59  5852.4  612.76    6080  614.18  6092.3  614.66
  6289.7  615.67  6441.4  619.27  6604.5  622.42  6822.4  627.83  6876.9   628.7
#Mann= 5 ,-1 , 0
  4345.6     .05       0  4959.9     .04       0  4966.8     .05       0
  5488.2      .1       0  5679.2     .05       0
Bank Sta=4959.9,4966.8
XS Rating Curve= 0 ,0
Exp/Cntr=0.3,0.1

Type RM Length L Ch R = 1 ,1593    ,464,464,464
BEGIN DESCRIPTION:
Mapping XS 6a27c066
END DESCRIPTION:
XS GIS Cut Line= 3
      1953329.98     13508604.45      1953545.23     13508604.45
      1954751.81     13508035.84
#Sta/Elev= 30
  4399.5  618.47  4534.5  616.63  4604.5  615.01  4645.4  614.88  4736.1  612.38
  4787.6  611.83  4815.9  610.97  4838.7  611.01  4861.5  610.33  4884.3  610.48
  4907.1  609.97  4929.9  608.31  4968.3   608.5  5031.1  608.07  5031.6  607.57
  5037.5  607.57    5038  608.07  5056.7  608.89  5123.2  609.35  5178.3  608.73
  5266.7  609.95  5442.2  610.74  5476.8  610.31  5567.1  610.95  5658.3  611.99
  5675.5  612.59    5795  614.66  5800.5  614.39  5891.6  616.47  5948.6   616.2
#Mann= 3 ,-1 , 0
  4399.5     .05       0  5031.1    .035       0    5038     .05       0
Bank Sta=5031.1,5038
XS Rating Curve= 0 ,0
Exp/Cntr=0.3,0.1

Type RM Length L Ch R = 1 ,1129    ,907,907,907
BEGIN DESCRIPTION:
Mapping XS d4f91e69
END DESCRIPTION:
XS GIS Cut Line= 4
       1953225.8     13508729.46      1953843.84     13508889.17
      1954434.12      13508798.9       1954815.1      13508258.6
#Sta/Elev= 30
  4137.8  617.15  4209.3  617.44  4364.2  616.68  4374.5  616.42  4379.7   614.8
  4405.5  615.15  4415.2  614.48  4420.4  615.27  4436.5   614.5    4600  613.73
  4643.1  613.36  4659.1  611.78  4700.7  610.97  4807.7  609.32  4918.9  608.82
  4939.2  606.91  4971.9  607.37  5006.4  606.37  5006.9  605.87  5013.1  605.87
  5013.6  606.37  5030.2  607.23  5050.5  607.13  5060.6  608.16  5161.7  608.12
  5371.2  611.03  5612.9  612.52  5892.4  616.15  5972.5  616.48  6034.4  616.02
#Mann= 5 ,-1 , 0
  4137.8     .05       0    4600     .08       0  4700.7     .05       0
  5006.4    .035       0  5013.6     .05       0
Bank Sta=5006.4,5013.6
XS Rating Curve= 0 ,0
Exp/Cntr=0.3,0.1

Type RM Length L Ch R = 1 ,222     ,43,43,43
BEGIN DESCRIPTION:
Mapping XS bbdc443d
END DESCRIPTION:
XS GIS Cut Line= 6
      1953489.19     13508921.53      1954209.65     13509772.19
      1954302.96     13509746.15      1954217.83     13509543.35
      1954339.36     13509260.37      1954545.39     13509039.36
#Sta/Elev= 30
  3909.7  614.39  4008.5  614.24  4064.6  611.76  4168.3  610.03  4248.9  608.07
  4308.3  607.76  4460.9   606.1  4758.6  605.99  4793.7  609.63  4822.1  610.46
  4828.9  607.83  4836.3  608.53  4843.1  604.85  4850.4  605.63  4857.3  604.35
  4872.1  603.84  5029.5   603.7  5059.7  603.82  5066.7  603.62  5211.6  603.62
  5257.4  603.39  5257.9  602.89  5264.7  603.39  5376.7  603.54  5444.1  605.74
  5466.2  605.67  5504.4  606.52  5760.9  607.77  5951.9   613.2  5998.8  613.72
#Mann= 12 ,-1 , 0
  3909.7     .05       0  4168.3     .08       0  4308.3     .05       0
  4872.1     .16       0  5029.5      .1       0  5059.7     .16       0
  5066.7      .1       0  5211.6     .16       0  5257.4     .07       0
  5264.7     .16       0  5444.1      .1       0  5466.2     .05       0
Bank Sta=5257.4,5264.7
XS Rating Curve= 0 ,0
Exp/Cntr=0.3,0.1

Type RM Length L Ch R = 1 ,179     ,49,49,49
BEGIN DESCRIPTION:
Mapping XS 53ea75c6
END DESCRIPTION:
XS GIS Cut Line= 6
      1953454.46     13508932.38      1954135.86     13509780.87
      1954248.71     13509800.41      1954391.15     13509681.37
      1954342.54     13509295.09      1954587.28     13509016.95
#Sta/Elev= 30
  3861.9  614.34  3977.2  614.26    4171  609.24  4307.3  607.09  4717.1   605.8
  4738.2  605.51  4738.8   605.5  4739.3     605  4746.1   605.5  4777.6  607.24
  4784.2  609.96  4798.5  611.14  4845.2  611.32  4983.2  609.88  5012.9  607.54
    5018  609.26  5049.7  608.85    5183  606.78  5265.1  606.28  5287.4  610.93
  5348.4  608.83  5404.8  609.88  5411.4  609.58  5453.8  610.07    5514  606.54
  5554.6   606.3  5574.6  608.39  5601.9  606.52  5701.3  606.82  6068.4  613.77
#Mann= 13 ,-1 , 0
  3861.9     .05       0    4171     .08       0  4307.3     .05       0
  4717.1      .1       0  4738.2     .05       0  4738.8     .07       0
  4746.1     .05       0  4845.2      .1       0  5049.7     .16       0
    5183      .1       0  5404.8     .16       0  5411.4      .1       0
    5514     .05       0
Bank Sta=4738.8,4746.1
XS Rating Curve= 0 ,0
Exp/Cntr=0.3,0.1

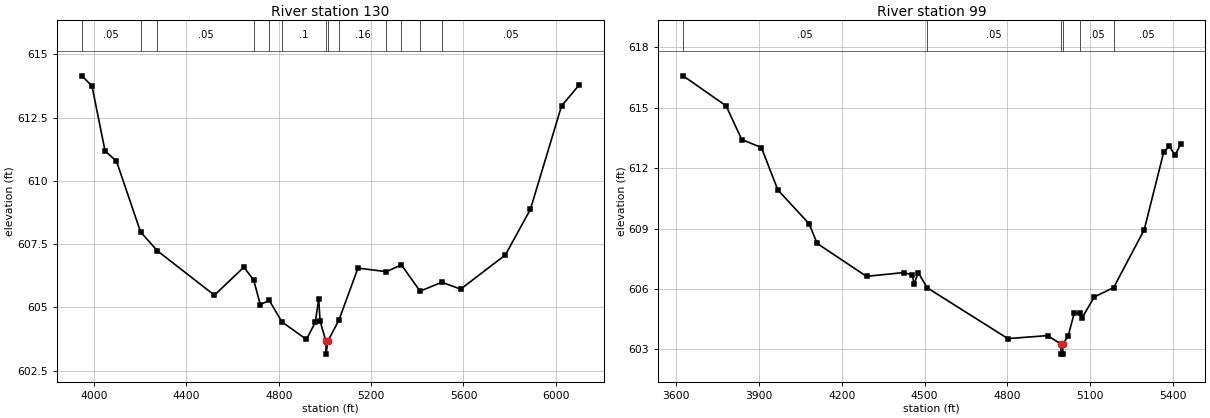
Type RM Length L Ch R = 1 ,130     ,31,31,31
BEGIN DESCRIPTION:
Mapping XS e30955a5
END DESCRIPTION:
XS GIS Cut Line= 6
      1953488.21     13509019.61      1954043.78     13509615.11
      1954158.36     13509837.33      1954432.67     13509727.96
      1954354.54     13509377.26      1954574.72     13509049.59
#Sta/Elev= 30
  3947.1  614.15  3991.2  613.75  4047.9  611.18  4097.2  610.78  4201.7  607.98
  4274.9  607.23  4521.7  605.48  4649.2  606.59  4691.8  606.07  4720.1  605.11
  4759.4  605.27  4813.2  604.43  4919.9  603.73  4958.5  604.41    4973  605.33
  4979.3  604.45  5004.8  603.65  5005.3  603.15  5012.1  603.65  5060.9   604.5
  5143.1  606.55  5266.6  606.41  5331.1  606.68  5412.1  605.64  5506.2  605.99
  5588.1  605.72  5781.5  607.07  5889.8  608.87  6024.8  612.96  6101.3  613.79
#Mann= 13 ,-1 , 0
  3947.1     .05       0  4201.7     .08       0  4274.9     .05       0
  4691.8      .1       0  4759.4     .05       0  4813.2      .1       0
  5004.8     .07       0  5012.1      .1       0  5060.9     .16       0
  5266.6      .1       0  5331.1     .05       0  5412.1      .1       0
  5506.2     .05       0
Bank Sta=5004.8,5012.1
XS Rating Curve= 0 ,0
Exp/Cntr=0.3,0.1

Type RM Length L Ch R = 1 ,99      ,0,0,0
BEGIN DESCRIPTION:
UNT 012 in BCW 1.0
END DESCRIPTION:
XS GIS Cut Line= 4
      1953239.68     13508833.62      1953865.03     13509721.41
      1954319.61     13509948.52      1954524.87     13509914.16
#Sta/Elev= 30
  3625.1  616.58  3780.8  615.09  3837.4  613.42  3908.9  613.02  3968.1  610.92
  4081.3  609.24  4110.9  608.26  4289.5  606.63  4426.2  606.82  4455.8  606.68
  4461.9  606.24  4476.7  606.82  4509.7  606.06  4801.7  603.54  4945.7  603.69
  4993.7  603.27  4994.2  602.77  5000.5  602.77    5001  603.27  5019.8  603.66
  5042.1   604.8  5061.8   604.8  5070.1  604.56  5114.8  605.61  5184.8  606.07
  5295.6  608.94  5366.6  612.81  5386.9  613.08  5407.2  612.64  5427.3  613.18
#Mann= 6 ,-1 , 0
  3625.1     .05       0  4509.7     .05       0  4993.7     .05       0
    5001     .05       0  5061.8     .05       0  5184.8     .05       0
Bank Sta=4993.7,5001
XS Rating Curve= 0 ,0
Exp/Cntr=0.3,0.1
LCMann Table=0

Chan Stop Cuts=-1
Use User Specified Reach Order=0
Composite Channel Slope=5