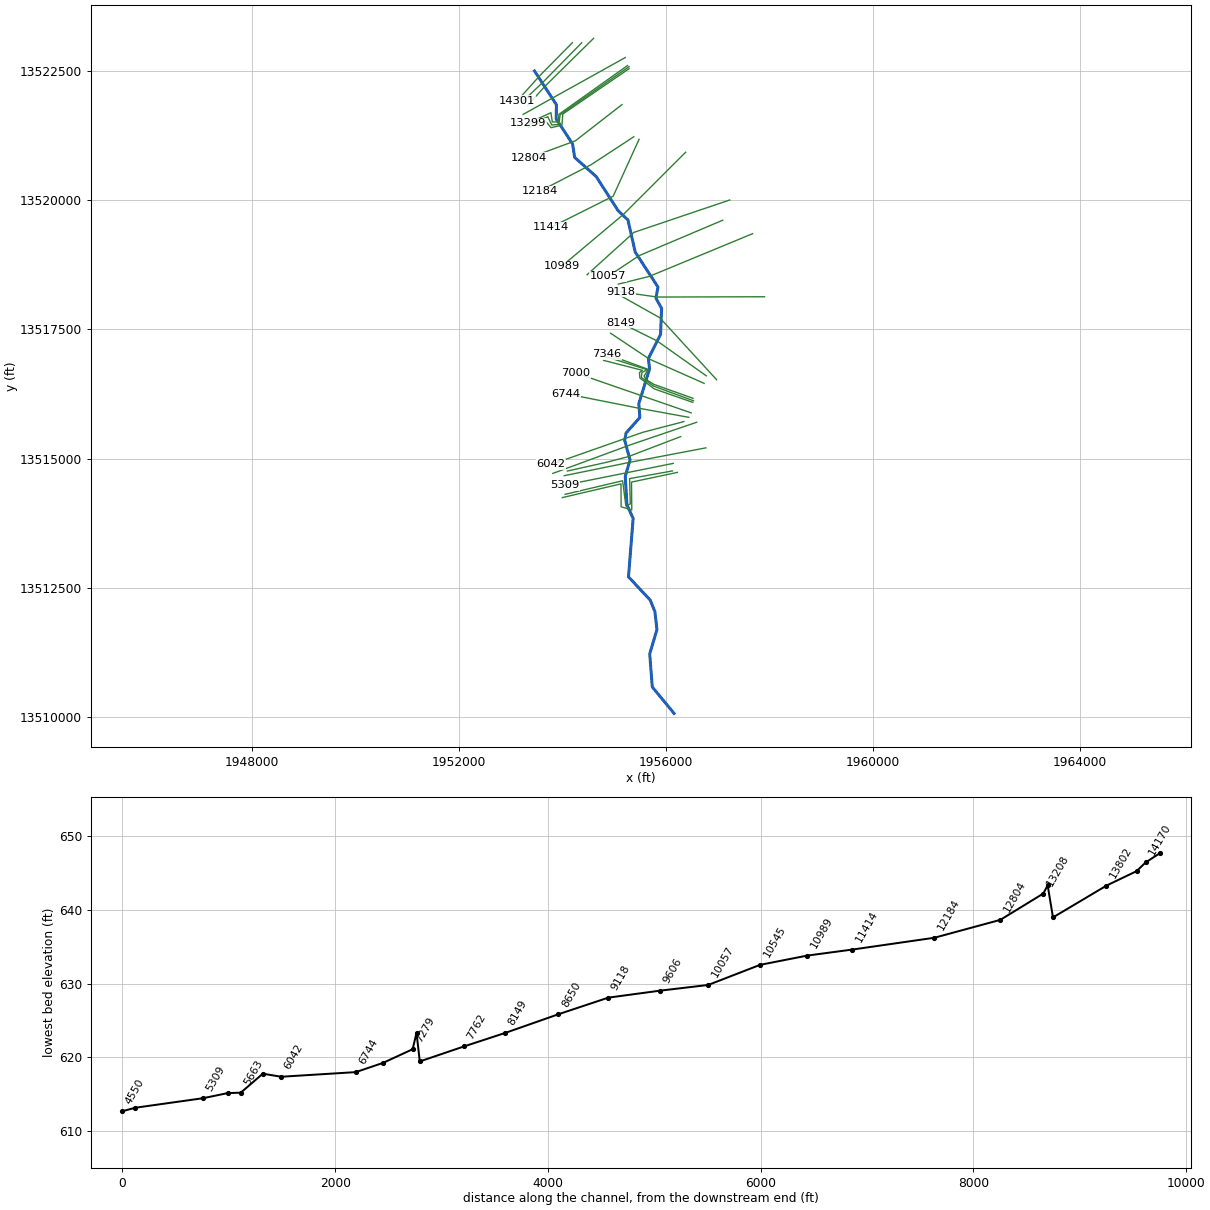
--- UNT 013 in BCW.prj (project) ---

Proj Title=UNT 013 in BCW Base Level Engineering
Current Plan=p01
Default Exp/Contr=0.3,0.1
English Units
Geom File=g01
Flow File=f01
Plan File=p01
BEGIN DESCRIPTION:
UNT 013 in BCW
END DESCRIPTION:

--- UNT 013 in BCW.p01 (plan) ---

Plan Title=Multiple Run
Short Identifier=Multiple
Geom File=g01
Flow File=f01
Subcritical Flow
K Sum by GR= 0
Std Step Tol= 0.01
Critical Tol= 0.01
Num of Std Step Trials= 20
Max Error Tol= 0.3
Flow Tol Ratio= 0.001
Split Flow NTrial= 30
Split Flow Tol= 0.02
Split Flow Ratio= 0.02
Log Output Level= 0
Friction Slope Method= 1
Unsteady Friction Slope Method= 2
Unsteady Bridges Friction Slope Method= 1
Parabolic Critical Depth
Global Vel Dist=  1 , 1 , 1
Global Log Level= 0
CheckData=True
Encroach Param= -1, 0, 0, 0
BEGIN DESCRIPTION:
Multiple Run
END DESCRIPTION:

--- UNT 013 in BCW.f01 (steady flow) ---

Flow Title=Multiple
Number of Profiles=7
Profile Names=10-year,25-year,50-year,1pct_min,100-year,1pct_plu,500-year
River Rch & RM= UNT 013 in BCW,Reach-1,14301
     122     164     199     120     240     479     357
River Rch & RM= UNT 013 in BCW,Reach-1,13299
     187     258     317     195     388     774     593
River Rch & RM= UNT 013 in BCW,Reach-1,9118
     280     393     489     303     604    1206     942
River Rch & RM= UNT 013 in BCW,Reach-1,158
     777    1134    1445     916    1828    3647    2982
Boundary for River Rch & Prof#=UNT 013 in BCW,Reach-1,1
Up Type=0
Dn Type=3
Dn Slope=0.005
Boundary for River Rch & Prof#=UNT 013 in BCW,Reach-1,2
Up Type=0
Dn Type=3
Dn Slope=0.005
Boundary for River Rch & Prof#=UNT 013 in BCW,Reach-1,3
Up Type=0
Dn Type=3
Dn Slope=0.005
Boundary for River Rch & Prof#=UNT 013 in BCW,Reach-1,4
Up Type=0
Dn Type=3
Dn Slope=0.005
Boundary for River Rch & Prof#=UNT 013 in BCW,Reach-1,5
Up Type=0
Dn Type=3
Dn Slope=0.005
Boundary for River Rch & Prof#=UNT 013 in BCW,Reach-1,6
Up Type=0
Dn Type=3
Dn Slope=0.005
Boundary for River Rch & Prof#=UNT 013 in BCW,Reach-1,7
Up Type=0
Dn Type=3
Dn Slope=0.005

--- UNT 013 in BCW.g01 (geometry) ---

Geom Title=Existing Conditions

River Reach=UNT 013 in BCW,Reach-1
Reach XY= 30
      1953454.52     13522495.95      1953878.12     13521844.08
      1953873.78     13521568.48      1954190.80     13521084.54
      1954230.80     13520824.54      1954646.35     13520455.19
      1955070.80     13519794.54      1955260.80     13519614.54
      1955400.80     13518994.54      1955840.80     13518317.61
      1955800.80     13518104.54      1955910.80     13517904.54
      1955890.80     13517404.54      1955656.33     13516937.78
      1955677.17     13516732.92      1955470.80     13516064.54
      1955489.67     13515794.55      1955224.04     13515495.94
      1955197.13     13515355.31      1955300.80     13514974.54
      1955208.42     13514659.13      1955240.80     13514104.54
      1955360.80     13513844.54      1955270.80     13512714.54
      1955690.80     13512264.54      1955780.80     13512044.54
      1955820.80     13511694.54      1955680.80     13511224.54
      1955730.80     13510584.54      1956150.80     13510074.54

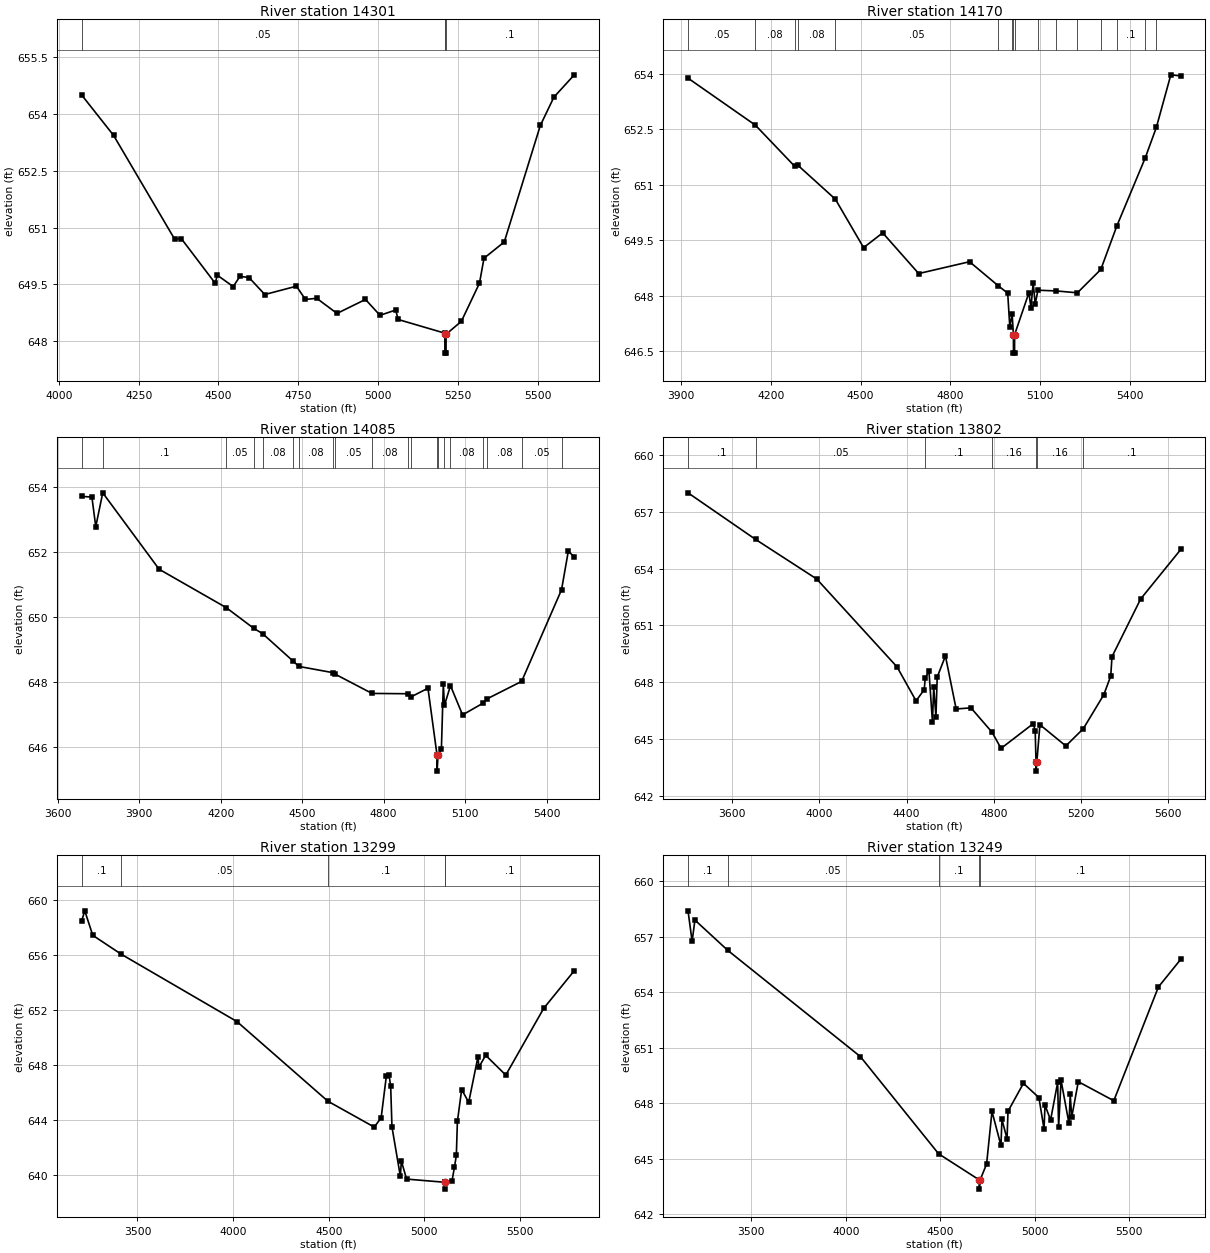
Type RM Length L Ch R = 1,14301,131,131,131
BEGIN DESCRIPTION:
UNT 013 in BCW 28.0
END DESCRIPTION:
XS GIS Cut Line= 3
      1954187.62     13523044.15      1953562.59     13522411.31
      1953124.98     13521924.98
#Sta/Elev= 30
  4071.0  654.51  4171.2  653.44  4362.2  650.70  4383.4  650.71  4489.5  649.53
  4496.5  649.74  4546.1  649.44  4567.2  649.71  4595.5  649.68  4645.1  649.23
  4744.1  649.45  4772.3  649.10  4807.7  649.13  4871.3  648.73  4960.5  649.10
  5005.9  648.68  5055.2  648.82  5062.7  648.57  5208.1  648.21  5209.1  648.18
  5209.3  647.68  5212.8  647.68  5213.1  648.18  5260.8  648.52  5317.6  649.53
  5331.8  650.19  5395.3  650.62  5508.2  653.70  5550.8  654.45  5614.7  655.04
#Mann=4,-1,0
  4071.0    0.05       0  5208.1     0.1       0  5209.1   0.035       0
  5213.1     0.1       0
Bank Sta=5209.1,5213.1
Exp/Cntr=0.3,0.1

Type RM Length L Ch R = 1,14170,85,85,85
BEGIN DESCRIPTION:
UNT 013 in BCW 27.0
END DESCRIPTION:
XS GIS Cut Line= 3
      1954367.29     13523041.53      1953625.09     13522286.31
      1953200.63     13521882.68
#Sta/Elev= 30
  3924.3  653.88  4149.1  652.61  4280.1  651.50  4291.8  651.52  4416.0  650.61
  4510.3  649.30  4574.0  649.70  4694.2  648.60  4863.9  648.92  4959.7  648.27
  4991.3  648.07  4998.2  647.16  5006.0  647.51  5010.3  646.95  5010.6  646.45
  5014.1  646.45  5014.3  646.95  5062.0  648.08  5068.9  647.68  5076.2  648.35
  5083.1  647.78  5092.2  648.15  5154.0  648.13  5223.9  648.08  5302.0  648.71
  5355.7  649.89  5450.0  651.72  5487.4  652.55  5535.7  653.97  5568.9  653.94
#Mann=16,-1,0
  3924.3    0.05       0  4149.1    0.08       0  4280.1    0.05       0
  4291.8    0.08       0  4416.0    0.05       0  4959.7     0.1       0
  5006.0    0.05       0  5010.3    0.07       0  5014.3    0.05       0
  5092.2     0.1       0  5154.0    0.05       0  5223.9     0.1       0
  5302.0    0.05       0  5355.7     0.1       0  5450.0    0.08       0
  5487.4     0.1       0
Bank Sta=5010.3,5014.3
Exp/Cntr=0.3,0.1

Type RM Length L Ch R = 1,14085,283,283,283
BEGIN DESCRIPTION:
UNT 013 in BCW 26.0
END DESCRIPTION:
XS GIS Cut Line= 3
      1954596.44     13523127.45      1953643.32     13522187.35
      1953325.63     13521833.20
#Sta/Elev= 30
  3687.7  653.72  3725.8  653.70  3740.0  652.79  3765.7  653.83  3973.3  651.48
  4220.2  650.30  4322.1  649.66  4354.2  649.50  4467.2  648.65  4488.1  648.49
  4612.2  648.30  4622.1  648.25  4757.3  647.66  4889.9  647.65  4902.4  647.56
  4963.3  647.82  4996.6  645.77  4996.8  645.27  5000.6  645.77  5012.7  645.94
  5019.9  647.94  5023.9  647.29  5046.2  647.90  5090.7  647.00  5166.0  647.36
  5182.5  647.50  5308.2  648.03  5455.2  650.85  5480.2  652.04  5502.2  651.85
#Mann=20,-1,0
  3687.7    0.05       0  3765.7     0.1       0  4220.2    0.05       0
  4322.1     0.1       0  4354.2    0.08       0  4467.2     0.1       0
  4488.1    0.08       0  4612.2     0.1       0  4622.1    0.05       0
  4757.3    0.08       0  4889.9    0.05       0  4902.4    0.08       0
  4996.6    0.07       0  5000.6    0.08       0  5023.9    0.05       0
  5046.2    0.08       0  5166.0    0.05       0  5182.5    0.08       0
  5308.2    0.05       0  5455.2    0.05       0
Bank Sta=4996.6,5000.6
Exp/Cntr=0.3,0.1

Type RM Length L Ch R = 1,13802,503,503,503
BEGIN DESCRIPTION:
Mapping XS bd01620f
END DESCRIPTION:
XS GIS Cut Line= 2
      1955208.43     13522755.59      1953234.43     13521656.60
#Sta/Elev= 30
  3398.2  658.00  3708.1  655.54  3988.4  653.45  4356.6  648.81  4443.7  647.02
  4481.2  647.61  4485.9  648.23  4502.9  648.59  4518.9  645.91  4524.7  647.74
  4534.9  646.19  4540.7  648.27  4578.4  649.39  4627.6  646.59  4695.4  646.65
  4792.4  645.36  4833.4  644.51  4981.6  645.82  4990.0  645.42  4993.7  643.81
  4994.0  643.31  4997.7  643.81  5011.7  645.76  5130.4  644.64  5210.6  645.55
  5304.4  647.34  5336.4  648.33  5342.1  649.35  5473.7  652.40  5657.5  655.01
#Mann=7,-1,0
  3398.2     0.1       0  3708.1    0.05       0  4485.9     0.1       0
  4792.4    0.16       0  4993.7    0.07       0  4997.7    0.16       0
  5210.6     0.1       0
Bank Sta=4993.7,4997.7
Exp/Cntr=0.3,0.1

Type RM Length L Ch R = 1,13299,50,50,50
BEGIN DESCRIPTION:
Mapping XS cbe23620
END DESCRIPTION:
XS GIS Cut Line= 6
      1955251.85     13522601.08      1953928.04     13521659.23
      1953910.68     13521511.66      1953797.83     13521511.66
      1953771.79     13521689.61      1953329.58     13521485.84
#Sta/Elev= 30
  3207.6  658.47  3224.4  659.22  3266.2  657.44  3414.6  656.07  4020.0  651.17
  4495.5  645.38  4737.8  643.50  4773.8  644.17  4800.9  647.19  4815.6  647.26
  4823.7  646.46  4830.4  643.51  4874.3  639.92  4879.4  641.04  4906.7  639.72
  5105.2  639.49  5105.6  638.99  5110.1  639.49  5144.6  639.61  5157.2  640.59
  5166.9  641.44  5172.5  643.91  5194.8  646.23  5231.6  645.30  5280.0  648.61
  5285.0  647.86  5320.3  648.72  5425.4  647.28  5623.6  652.13  5783.7  654.87
#Mann=5,-1,0
  3207.6     0.1       0  3414.6    0.05       0  4495.5     0.1       0
  5105.2    0.07       0  5110.1     0.1       0
Bank Sta=5105.2,5110.1
Exp/Cntr=0.3,0.1

Type RM Length L Ch R = 1,13249,41,41,41
BEGIN DESCRIPTION:
Mapping XS 27e93ba9
END DESCRIPTION:
XS GIS Cut Line= 6
      1955282.18     13522579.35      1953949.74     13521650.55
      1953923.70     13521463.91      1953789.15     13521450.89
      1953711.03     13521611.48      1953299.32     13521433.80
#Sta/Elev= 30
  3164.5  658.40  3186.2  656.75  3201.0  657.90  3375.2  656.26  4077.0  650.52
  4491.6  645.26  4706.7  643.85  4707.1  643.35  4711.6  643.85  4745.7  644.71
  4774.2  647.55  4821.7  645.71  4826.9  647.12  4853.9  646.07  4859.1  647.56
  4940.7  649.07  5022.8  648.30  5049.8  646.60  5055.0  647.89  5084.6  647.09
  5122.0  649.12  5127.0  646.70  5140.1  649.23  5182.0  646.90  5188.6  648.47
  5196.2  647.23  5231.3  649.16  5419.3  648.13  5655.4  654.28  5774.0  655.78
#Mann=5,-1,0
  3164.5     0.1       0  3375.2    0.05       0  4491.6     0.1       0
  4706.7    0.07       0  4711.6     0.1       0
Bank Sta=4706.7,4711.6
Exp/Cntr=0.3,0.1

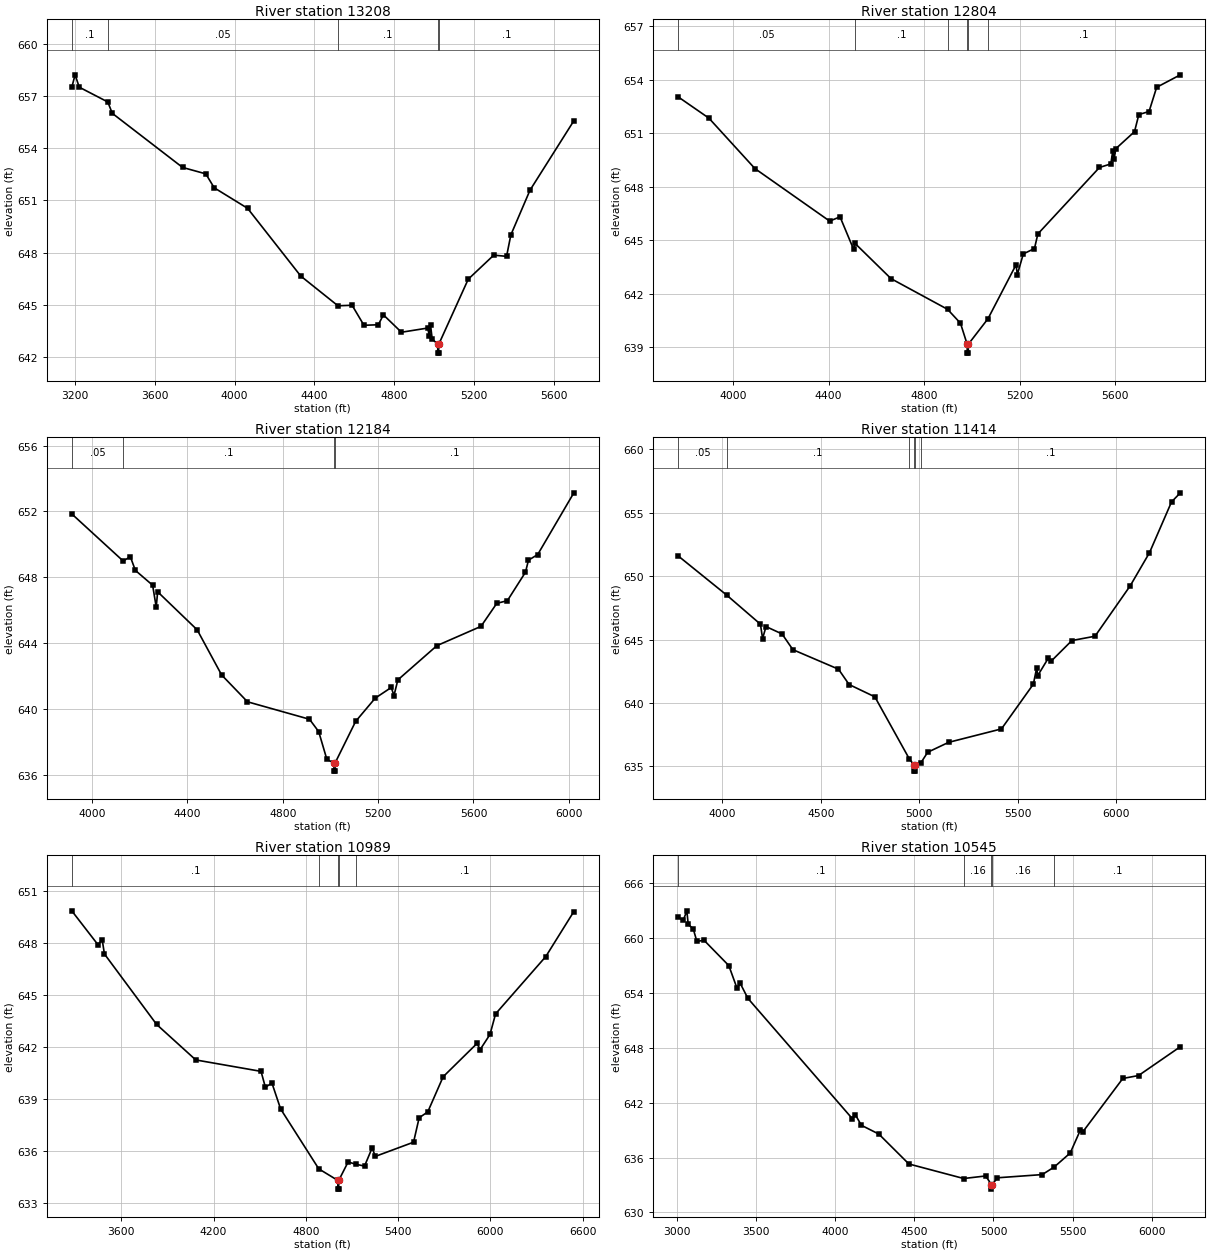
Type RM Length L Ch R = 1,13208,404,404,404
BEGIN DESCRIPTION:
Mapping XS a81c92bd
END DESCRIPTION:
XS GIS Cut Line= 6
      1955282.24     13522540.33      1954001.83     13521663.57
      1953984.47     13521450.89      1953776.13     13521398.81
      1953667.63     13521529.02      1953338.91     13521407.91
#Sta/Elev= 30
  3185.1  657.50  3201.7  658.22  3222.6  657.51  3365.6  656.66  3387.8  656.01
  3739.8  652.90  3856.3  652.53  3898.3  651.73  4065.5  650.55  4331.6  646.66
  4518.0  644.95  4588.8  644.98  4648.2  643.83  4720.2  643.86  4745.5  644.43
  4835.9  643.43  4967.0  643.67  4975.8  643.24  4981.5  643.85  4989.8  643.05
  5017.6  642.73  5017.9  642.23  5022.1  642.23  5022.5  642.73  5170.5  646.48
  5298.2  647.86  5362.3  647.79  5383.7  649.02  5479.6  651.59  5699.2  655.58
#Mann=5,-1,0
  3185.1     0.1       0  3365.6    0.05       0  4518.0     0.1       0
  5017.6    0.07       0  5022.5     0.1       0
Bank Sta=5017.6,5022.5
Exp/Cntr=0.3,0.1

Type RM Length L Ch R = 1,12804,620,620,620
BEGIN DESCRIPTION:
UNT 013 in BCW 25.0
END DESCRIPTION:
XS GIS Cut Line= 3
      1955144.79     13521846.00      1954244.79     13521146.01
      1953342.07     13520812.86
#Sta/Elev= 30
  3770.3  653.04  3898.6  651.85  4091.3  649.02  4404.4  646.07  4447.8  646.31
  4504.8  644.48  4510.5  644.82  4661.4  642.84  4898.0  641.12  4952.1  640.34
  4980.1  639.16  4980.5  638.66  4984.7  638.66  4985.0  639.16  5067.3  640.59
  5184.9  643.62  5190.2  643.07  5215.3  644.23  5262.0  644.53  5276.2  645.35
  5534.1  649.08  5581.8  649.28  5589.6  649.99  5594.9  649.57  5603.1  650.14
  5680.9  651.09  5699.0  652.05  5741.8  652.22  5773.6  653.58  5872.7  654.28
#Mann=6,-1,0
  3770.3    0.05       0  4510.5     0.1       0  4898.0    0.12       0
  4980.1    0.07       0  4985.0    0.12       0  5067.3     0.1       0
Bank Sta=4980.1,4985
Exp/Cntr=0.3,0.1

Type RM Length L Ch R = 1,12184,770,770,770
BEGIN DESCRIPTION:
UNT 013 in BCW 24.0
END DESCRIPTION:
XS GIS Cut Line= 3
      1955374.97     13521224.98      1954553.04     13520687.00
      1953554.78     13520170.51
#Sta/Elev= 30
  3914.7  651.85  4130.3  648.99  4160.4  649.25  4181.5  648.42  4253.9  647.52
  4269.0  646.19  4275.0  647.12  4440.8  644.81  4543.4  642.07  4651.9  640.44
  4912.0  639.38  4950.6  638.63  4984.9  636.94  5014.5  636.73  5014.9  636.23
  5019.2  636.23  5019.6  636.73  5105.6  639.25  5187.6  640.66  5255.0  641.31
  5266.4  640.82  5282.7  641.77  5446.5  643.85  5631.4  645.02  5697.8  646.42
  5742.1  646.58  5818.1  648.31  5830.6  649.04  5869.3  649.38  6021.0  653.13
#Mann=4,-1,0
  3914.7    0.05       0  4130.3     0.1       0  5014.5    0.07       0
  5019.6     0.1       0
Bank Sta=5014.5,5019.6
Exp/Cntr=0.3,0.1

Type RM Length L Ch R = 1,11414,425,425,425
BEGIN DESCRIPTION:
UNT 013 in BCW 23.0
END DESCRIPTION:
XS GIS Cut Line= 3
      1955474.99     13521174.97      1954975.00     13520075.00
      1953775.01     13519475.01
#Sta/Elev= 30
  3775.3  651.60  4020.9  648.52  4192.7  646.22  4203.7  645.09  4221.2  646.03
  4302.5  645.45  4357.5  644.21  4589.2  642.67  4643.1  641.46  4773.8  640.49
  4949.1  635.59  4972.2  635.13  4972.6  634.63  4977.0  634.63  4977.4  635.13
  5007.3  635.28  5042.3  636.12  5148.5  636.90  5416.8  637.96  5578.9  641.49
  5595.7  642.77  5601.3  642.17  5654.4  643.53  5668.4  643.29  5774.6  644.93
  5892.0  645.27  6070.9  649.25  6168.7  651.86  6280.5  655.86  6325.2  656.58
#Mann=6,-1,0
  3775.3    0.05       0  4020.9     0.1       0  4949.1    0.12       0
  4972.2    0.07       0  4977.4    0.12       0  5007.3     0.1       0
Bank Sta=4972.2,4977.4
Exp/Cntr=0.3,0.1

Type RM Length L Ch R = 1,10989,444,444,444
BEGIN DESCRIPTION:
UNT 013 in BCW 22.0
END DESCRIPTION:
XS GIS Cut Line= 3
      1956375.03     13520925.03      1955175.00     13519725.00
      1953975.78     13518716.51
#Sta/Elev= 30
  3278.3  649.88  3448.0  647.93  3476.3  648.20  3490.5  647.39  3829.9  643.32
  4084.4  641.27  4508.7  640.61  4537.0  639.69  4579.4  639.94  4636.0  638.44
  4884.1  634.98  5008.5  634.31  5008.9  633.81  5013.4  633.81  5013.8  634.31
  5074.9  635.38  5123.2  635.25  5181.5  635.14  5231.0  636.19  5251.8  635.70
  5500.2  636.52  5536.6  637.93  5592.6  638.27  5692.7  640.30  5912.5  642.22
  5933.3  641.87  5997.1  642.74  6033.5  643.93  6359.9  647.24  6542.3  649.84
#Mann=5,-1,0
  3278.3     0.1       0  4884.1    0.16       0  5008.5    0.07       0
  5013.8    0.16       0  5123.2     0.1       0
Bank Sta=5008.5,5013.8
Exp/Cntr=0.3,0.1

Type RM Length L Ch R = 1,10545,488,488,488
BEGIN DESCRIPTION:
UNT 013 in BCW 21.0
END DESCRIPTION:
XS GIS Cut Line= 3
      1957226.67     13520001.24      1955375.00     13519375.00
      1954470.57     13518555.92
#Sta/Elev= 30
  3006.6  662.28  3038.2  661.95  3061.1  662.98  3069.7  661.49  3101.1  661.03
  3124.5  659.63  3169.3  659.77  3326.5  656.99  3377.8  654.54  3398.9  655.04
  3447.0  653.41  4107.2  640.26  4127.3  640.66  4164.8  639.53  4275.1  638.57
  4465.1  635.30  4811.7  633.71  4950.9  633.99  4986.7  633.05  4987.1  632.55
  4992.0  633.05  5025.2  633.79  5308.4  634.14  5384.2  634.97  5485.4  636.50
  5549.0  638.99  5563.2  638.77  5817.9  644.65  5917.3  644.97  6181.5  648.12
#Mann=5,-1,0
  3006.6     0.1       0  4811.7    0.16       0  4986.7    0.07       0
  4992.0    0.16       0  5384.2     0.1       0
Bank Sta=4986.7,4992
Exp/Cntr=0.3,0.1

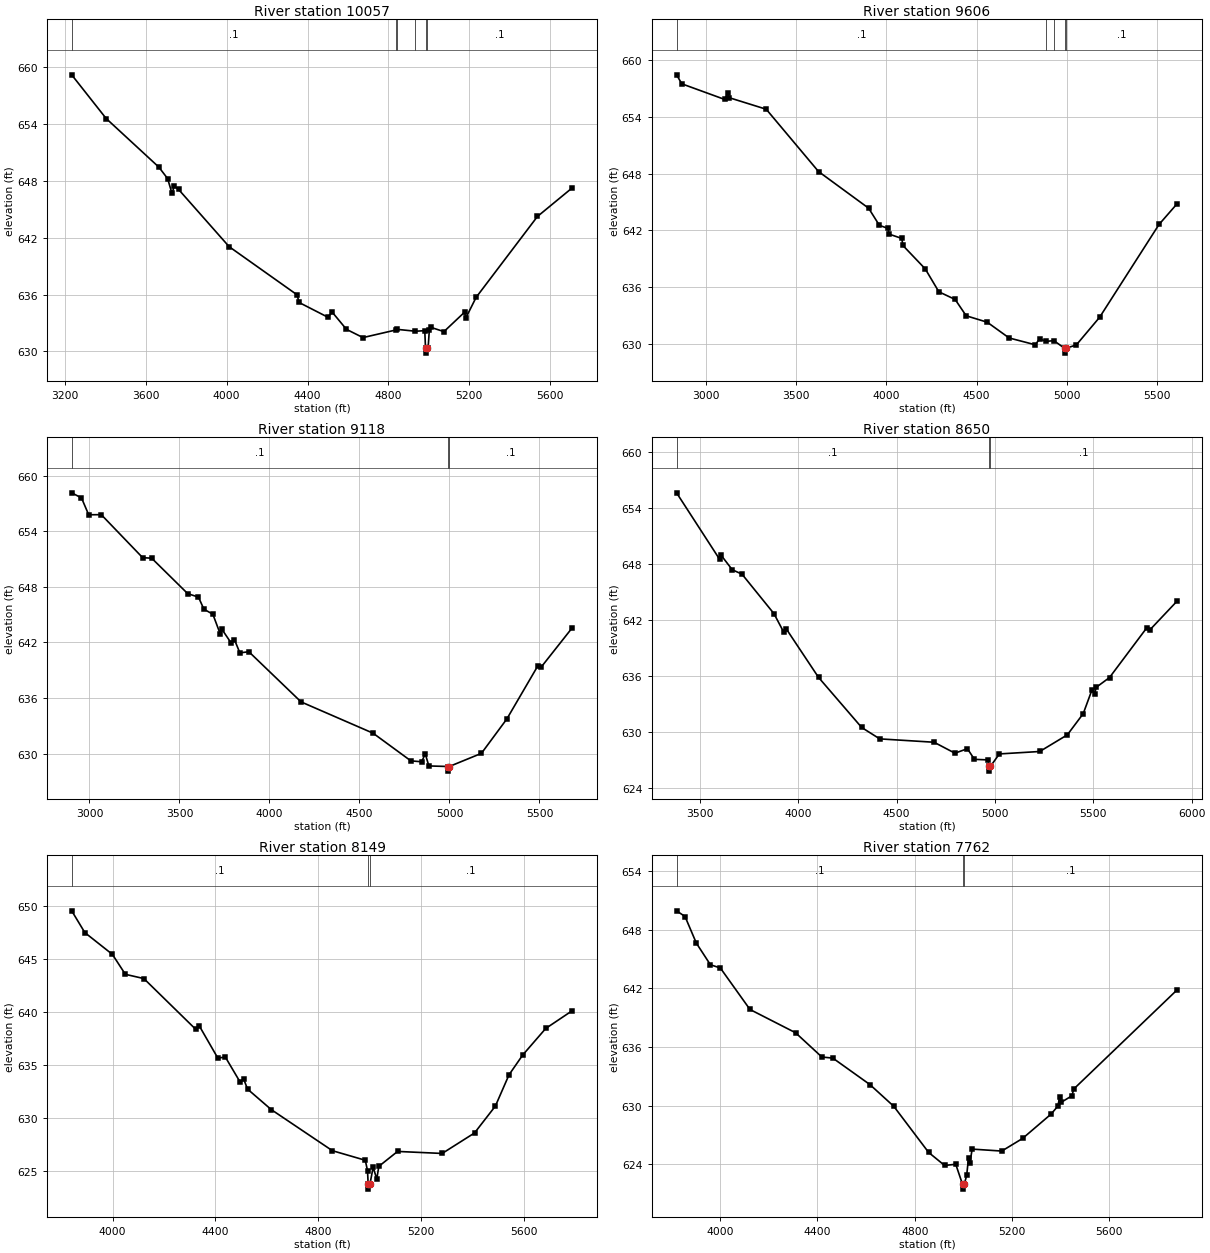
Type RM Length L Ch R = 1,10057,451,451,451
BEGIN DESCRIPTION:
UNT 013 in BCW 20.0
END DESCRIPTION:
XS GIS Cut Line= 3
      1957092.09     13519610.61      1955475.00     13518925.00
      1954875.03     13518525.02
#Sta/Elev= 30
  3233.0  659.19  3403.6  654.58  3664.3  649.45  3707.7  648.24  3729.5  646.67
  3740.3  647.43  3762.1  647.09  4011.9  641.06  4348.6  635.97  4357.9  635.17
  4500.7  633.61  4522.4  634.14  4592.7  632.33  4674.5  631.46  4836.7  632.26
  4843.5  632.33  4934.1  632.13  4980.3  632.19  4984.0  630.32  4984.4  629.82
  4989.5  630.32  4996.9  630.35  5002.9  632.28  5012.0  632.53  5075.1  632.09
  5177.2  634.14  5183.2  633.52  5234.3  635.70  5537.8  644.24  5710.5  647.27
#Mann=6,-1,0
  3233.0     0.1       0  4836.7    0.16       0  4843.5    0.12       0
  4934.1     0.1       0  4984.0    0.07       0  4989.5     0.1       0
Bank Sta=4984,4989.5
Exp/Cntr=0.3,0.1

Type RM Length L Ch R = 1,9606,488,488,488
BEGIN DESCRIPTION:
UNT 013 in BCW 19.0
END DESCRIPTION:
XS GIS Cut Line= 3
      1957669.37     13519350.20      1955675.00     13518525.00
      1955075.02     13518375.00
#Sta/Elev= 30
  2835.9  658.41  2865.1  657.46  3101.9  655.82  3120.4  656.52  3125.8  656.01
  3333.2  654.78  3623.2  648.21  3901.2  644.34  3960.9  642.53  4008.7  642.21
  4014.1  641.61  4085.2  641.15  4091.2  640.41  4215.1  637.94  4290.8  635.52
  4381.2  634.71  4442.3  632.99  4559.3  632.31  4680.4  630.65  4825.4  629.93
  4849.3  630.55  4886.4  630.29  4928.6  630.37  4988.8  629.55  4989.2  629.05
  4994.3  629.55  5053.5  629.92  5182.4  632.83  5512.2  642.63  5612.7  644.82
#Mann=5,-1,0
  2835.9     0.1       0  4886.4    0.12       0  4928.6     0.1       0
  4988.8    0.07       0  4994.3     0.1       0
Bank Sta=4988.8,4994.3
Exp/Cntr=0.3,0.1

Type RM Length L Ch R = 1,9118,468,468,468
BEGIN DESCRIPTION:
UNT 013 in BCW 18.0
END DESCRIPTION:
XS GIS Cut Line= 3
      1957899.45     13518130.58      1955825.00     13518125.00
      1955124.96     13518225.01
#Sta/Elev= 30
  2901.1  658.17  2955.5  657.62  2995.5  655.80  3065.5  655.81  3295.5  651.16
  3345.5  651.11  3545.5  647.28  3605.5  646.90  3635.5  645.60  3685.5  645.05
  3725.5  642.97  3735.5  643.43  3785.5  641.99  3805.5  642.30  3835.5  640.88
  3885.5  641.00  4175.5  635.58  4575.6  632.20  4785.6  629.21  4845.6  629.11
  4865.6  629.97  4885.6  628.66  4992.6  628.60  4993.1  628.10  4999.0  628.60
  5177.6  630.02  5319.0  633.74  5490.7  639.46  5510.9  639.37  5682.7  643.60
#Mann=3,-1,0
  2901.1     0.1       0  4992.6    0.07       0  4999.0     0.1       0
Bank Sta=4992.6,4999
Exp/Cntr=0.3,0.1

Type RM Length L Ch R = 1,8650,501,501,501
BEGIN DESCRIPTION:
UNT 013 in BCW 17.0
END DESCRIPTION:
XS GIS Cut Line= 3
      1956975.00     13516525.00      1955875.00     13517725.00
      1955074.96     13518175.02
#Sta/Elev= 30
  3380.7  655.62  3599.9  648.50  3607.3  648.94  3664.0  647.39  3713.4  646.92
  3876.2  642.69  3925.5  640.72  3939.7  641.03  4102.5  635.88  4322.0  630.52
  4413.8  629.30  4690.1  628.94  4796.2  627.77  4859.7  628.25  4895.4  627.11
  4966.3  627.05  4969.8  626.35  4970.3  625.85  4976.4  626.35  5022.3  627.69
  5227.5  627.95  5367.8  629.73  5448.7  632.00  5492.1  634.48  5508.0  634.15
  5513.7  634.80  5582.3  635.86  5772.5  641.20  5788.5  640.98  5926.5  644.05
#Mann=3,-1,0
  3380.7     0.1       0  4969.8    0.07       0  4976.4     0.1       0
Bank Sta=4969.8,4976.4
Exp/Cntr=0.3,0.1

Type RM Length L Ch R = 1,8149,387,387,387
BEGIN DESCRIPTION:
UNT 013 in BCW 16.0
END DESCRIPTION:
XS GIS Cut Line= 3
      1956773.81     13516601.94      1955825.00     13517275.00
      1955125.01     13517624.99
#Sta/Elev= 30
  3841.2  649.52  3892.3  647.47  3999.3  645.42  4049.8  643.54  4121.7  643.14
  4322.9  638.37  4337.7  638.66  4409.0  635.66  4438.6  635.74  4495.2  633.42
  4509.9  633.66  4524.7  632.73  4616.9  630.80  4854.4  626.93  4982.3  626.03
  4991.0  625.06  4993.5  623.81  4994.0  623.31  5000.7  623.81  5012.9  625.37
  5026.9  624.27  5035.2  625.46  5107.9  626.86  5281.2  626.67  5407.0  628.60
  5488.0  631.13  5541.1  634.08  5594.3  635.94  5683.7  638.44  5787.1  640.12
#Mann=3,-1,0
  3841.2     0.1       0  4993.5    0.07       0  5000.7     0.1       0
Bank Sta=4993.5,5000.7
Exp/Cntr=0.3,0.1

Type RM Length L Ch R = 1,7762,416,416,416
BEGIN DESCRIPTION:
UNT 013 in BCW 15.0
END DESCRIPTION:
XS GIS Cut Line= 3
      1956732.18     13516456.09      1955675.00     13516925.00
      1954924.99     13517425.00
#Sta/Elev= 30
  3821.0  649.92  3855.8  649.34  3902.3  646.62  3960.1  644.41  4000.9  644.08
  4122.7  639.84  4310.2  637.46  4418.3  634.98  4463.3  634.87  4615.5  632.17
  4714.0  629.94  4857.2  625.23  4922.8  623.90  4968.6  624.02  4996.4  621.98
  4996.9  621.48  5003.7  621.98  5013.6  622.89  5021.1  624.67  5027.1  624.20
  5036.1  625.57  5157.8  625.37  5243.4  626.66  5360.6  629.15  5387.6  629.94
  5396.6  630.89  5402.7  630.36  5446.2  631.02  5453.7  631.71  5878.9  641.85
#Mann=3,-1,0
  3821.0     0.1       0  4996.4    0.07       0  5003.7     0.1       0
Bank Sta=4996.4,5003.7
Exp/Cntr=0.3,0.1

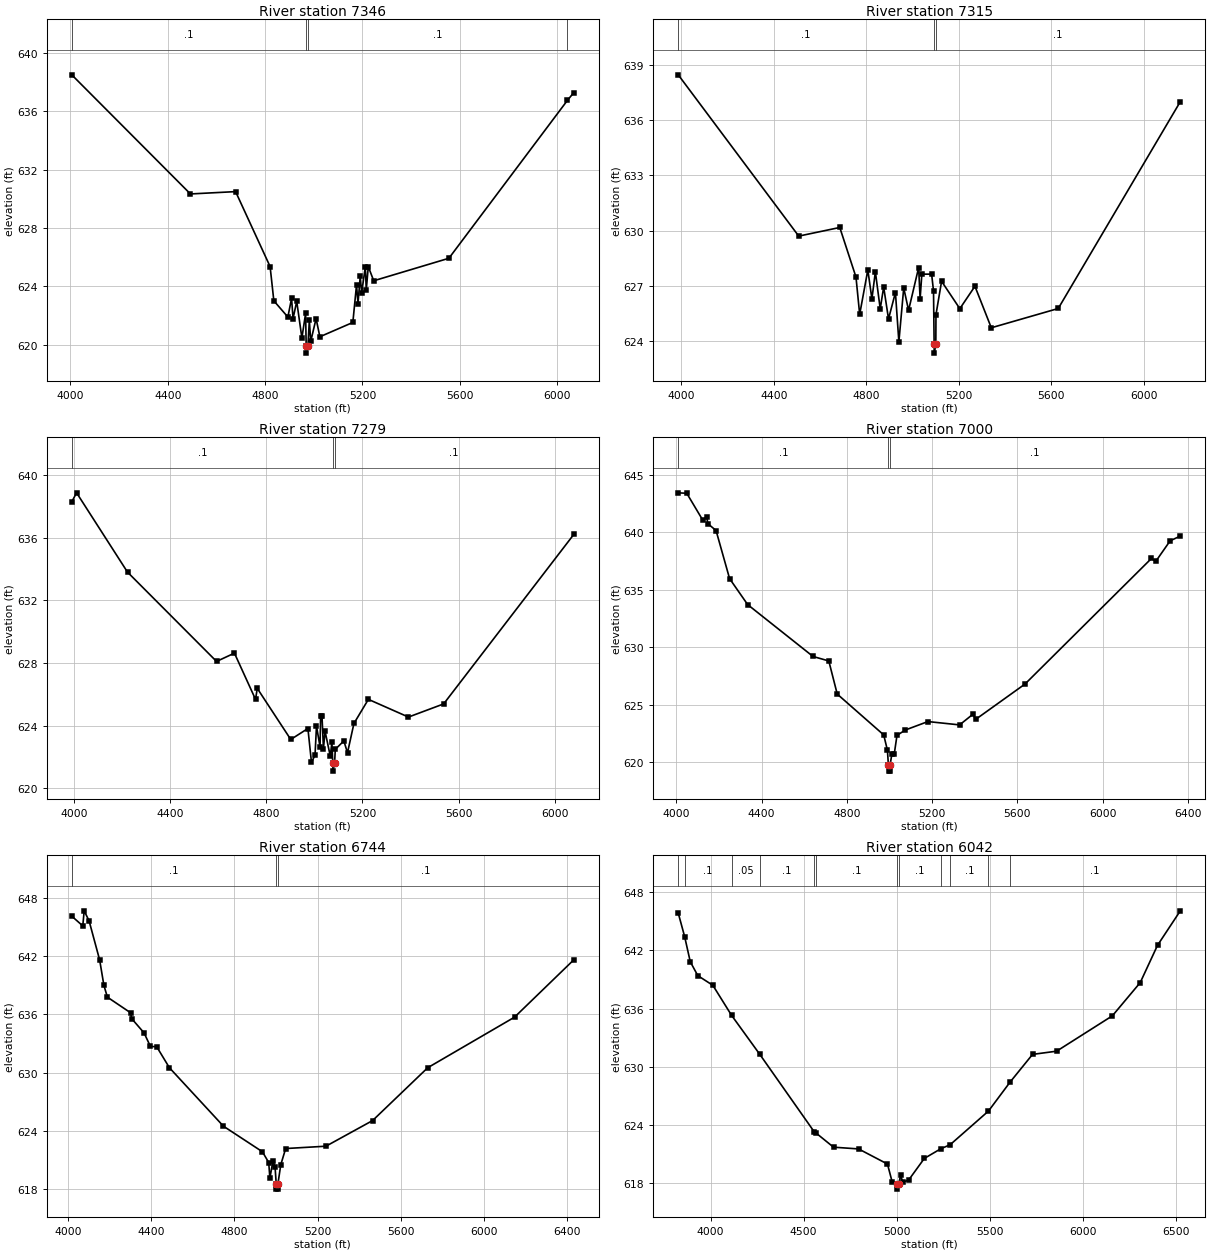
Type RM Length L Ch R = 1,7346,31,31,31
BEGIN DESCRIPTION:
Mapping XS 2887c2a2
END DESCRIPTION:
XS GIS Cut Line= 6
      1956519.16     13516166.33      1955758.77     13516437.16
      1955610.33     13516530.91      1955571.27     13516596.01
      1955651.99     13516726.22      1954853.18     13517020.24
#Sta/Elev= 30
  4005.8  638.48  4493.4  630.33  4679.0  630.49  4820.8  625.36  4836.1  623.02
  4893.8  621.91  4909.0  623.19  4915.0  621.80  4930.2  622.98  4951.4  620.48
  4966.7  622.16  4969.0  619.94  4969.5  619.44  4976.3  619.94  4982.0  621.69
  4987.7  620.24  5009.7  621.80  5025.3  620.56  5160.8  621.54  5175.9  624.11
  5181.9  622.83  5191.1  624.69  5197.0  623.57  5212.2  625.36  5215.9  623.76
  5224.2  625.36  5246.5  624.39  5555.5  625.93  6042.4  636.73  6068.9  637.27
#Mann=4,-1,0
  4005.8     0.1       0  4969.0    0.07       0  4976.3     0.1       0
  6042.4    0.05       0
Bank Sta=4969,4976.3
Exp/Cntr=0.3,0.1

Type RM Length L Ch R = 1,7315,36,36,36
BEGIN DESCRIPTION:
Mapping XS fc51e6ec
END DESCRIPTION:
XS GIS Cut Line= 6
      1956526.97     13516119.46      1955753.56     13516403.30
      1955516.58     13516572.57      1955532.20     13516666.32
      1955631.16     13516721.01      1954821.24     13516976.23
#Sta/Elev= 30
  3986.3  638.48  4507.7  629.70  4685.3  630.17  4755.4  627.47  4771.4  625.44
  4806.7  627.86  4824.3  626.28  4839.3  627.76  4860.3  625.74  4875.2  626.93
  4896.2  625.19  4926.1  626.63  4941.0  623.94  4962.0  626.88  4983.0  625.66
  5026.6  627.99  5032.9  626.28  5040.4  627.63  5082.7  627.63  5090.9  626.72
  5093.6  623.83  5094.1  623.33  5100.9  623.83  5101.5  625.42  5125.8  627.24
  5204.8  625.75  5270.1  626.97  5340.9  624.71  5630.6  625.76  6158.8  637.02
#Mann=3,-1,0
  3986.3     0.1       0  5093.6    0.07       0  5100.9     0.1       0
Bank Sta=5093.6,5100.9
Exp/Cntr=0.3,0.1

Type RM Length L Ch R = 1,7279,279,279,279
BEGIN DESCRIPTION:
Mapping XS e08c485f
END DESCRIPTION:
XS GIS Cut Line= 6
      1956513.96     13516088.20      1955769.18     13516348.61
      1955490.54     13516559.55      1955482.72     13516663.72
      1955540.02     13516707.99      1954790.04     13516900.02
#Sta/Elev= 30
  3989.8  638.29  4009.9  638.86  4221.8  633.80  4592.5  628.10  4666.9  628.63
  4754.7  625.68  4762.0  626.38  4901.4  623.12  4972.8  623.82  4987.6  621.66
  5002.4  622.12  5008.5  623.97  5023.3  622.65  5025.7  624.61  5031.4  624.61
  5037.5  622.54  5044.2  623.64  5065.9  622.06  5072.6  622.93  5076.4  621.60
  5076.9  621.10  5083.8  621.60  5086.8  622.49  5122.4  623.03  5137.6  622.27
  5164.3  624.14  5224.5  625.68  5391.3  624.55  5537.9  625.39  6079.8  636.21
#Mann=3,-1,0
  3989.8     0.1       0  5076.4    0.07       0  5083.8     0.1       0
Bank Sta=5076.4,5083.8
Exp/Cntr=0.3,0.1

Type RM Length L Ch R = 1,7000,256,256,256
BEGIN DESCRIPTION:
Mapping XS b61d204e
END DESCRIPTION:
XS GIS Cut Line= 2
      1956482.76     13515885.06      1954256.12     13516655.92
#Sta/Elev= 30
  4008.4  643.44  4048.4  643.40  4122.4  641.10  4142.0  641.33  4147.3  640.76
  4185.9  640.16  4249.4  635.98  4334.3  633.72  4641.0  629.21  4715.0  628.82
  4754.6  625.94  4972.7  622.39  4990.2  621.05  4994.8  619.74  4995.3  619.24
  5001.8  619.24  5002.3  619.74  5011.3  620.76  5021.9  620.69  5035.0  622.35
  5074.8  622.82  5180.2  623.55  5328.8  623.26  5392.3  624.20  5403.6  623.73
  5635.7  626.81  6229.0  637.73  6249.5  637.48  6317.1  639.27  6364.7  639.68
#Mann=3,-1,0
  4008.4     0.1       0  4994.8    0.07       0  5002.3     0.1       0
Bank Sta=4994.8,5002.3
Exp/Cntr=0.3,0.1

Type RM Length L Ch R = 1,6744,702,702,702
BEGIN DESCRIPTION:
UNT 013 in BCW 13.0
END DESCRIPTION:
XS GIS Cut Line= 3
      1956437.06     13515798.97      1955461.32     13515976.93
      1954065.53     13516254.70
#Sta/Elev= 30
  4017.8  646.10  4070.7  645.10  4077.5  646.65  4101.2  645.61  4152.0  641.58
  4172.4  638.97  4189.2  637.76  4300.8  636.15  4305.9  635.55  4365.5  634.08
  4396.0  632.69  4426.5  632.65  4487.5  630.49  4747.4  624.47  4934.7  621.84
  4965.2  620.73  4970.7  619.11  4985.6  620.91  4995.7  620.24  5001.4  618.49
  5001.9  617.99  5008.6  617.99  5009.1  618.49  5023.3  620.52  5046.7  622.17
  5240.4  622.41  5464.7  625.05  5729.8  630.49  6147.6  635.70  6432.8  641.61
#Mann=3,-1,0
  4017.8     0.1       0  5001.4    0.07       0  5009.1     0.1       0
Bank Sta=5001.4,5009.1
Exp/Cntr=0.3,0.1

Type RM Length L Ch R = 1,6042,172,172,172
BEGIN DESCRIPTION:
UNT 013 in BCW 12.0
END DESCRIPTION:
XS GIS Cut Line= 3
      1956341.51     13515716.51      1955542.92     13515508.18
      1953778.19     13514888.15
#Sta/Elev= 30
  3826.6  645.86  3861.1  643.42  3891.1  640.84  3931.6  639.40  4012.5  638.40
  4113.0  635.30  4264.2  631.28  4557.7  623.25  4566.6  623.15  4660.3  621.69
  4795.0  621.51  4950.0  619.95  4975.6  618.08  5002.6  617.86  5003.1  617.36
  5010.6  617.86  5020.7  618.83  5031.3  618.09  5063.1  618.28  5147.9  620.53
  5236.6  621.53  5286.3  621.94  5492.4  625.42  5608.0  628.40  5729.0  631.27
  5858.2  631.60  6157.5  635.25  6307.1  638.68  6400.0  642.53  6522.4  646.09
#Mann=12,-1,0
  3826.6    0.05       0  3861.1     0.1       0  4113.0    0.05       0
  4264.2     0.1       0  4557.7    0.05       0  4566.6     0.1       0
  5002.6    0.07       0  5010.6     0.1       0  5236.6    0.05       0
  5286.3     0.1       0  5492.4    0.05       0  5608.0     0.1       0
Bank Sta=5002.6,5010.6
Exp/Cntr=0.3,0.1

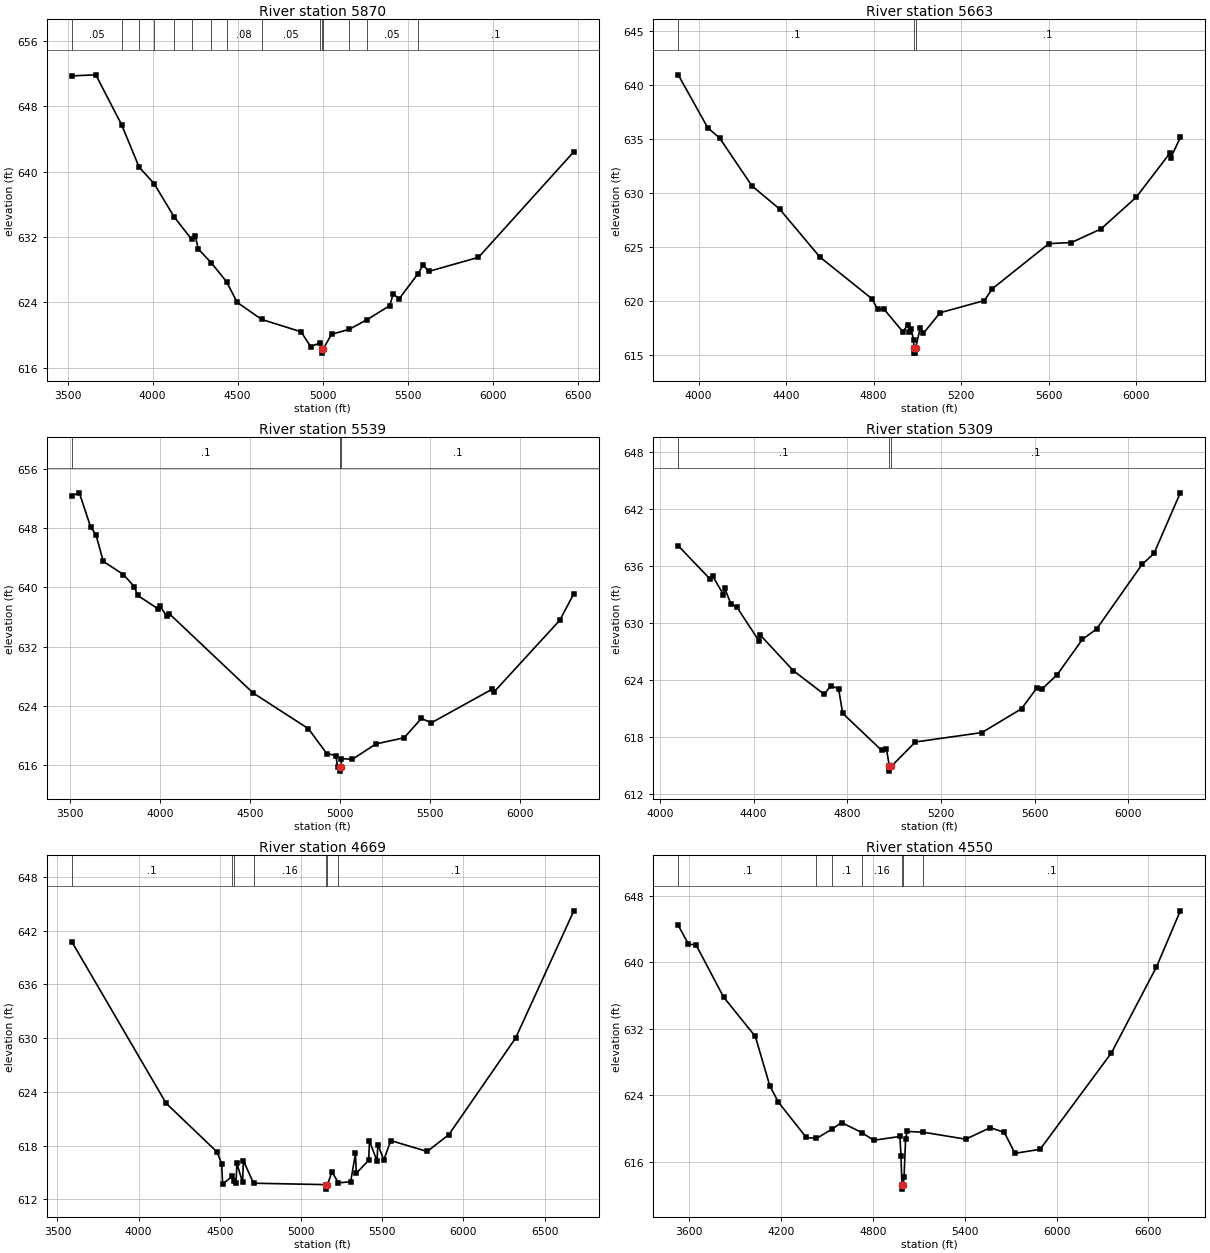
Type RM Length L Ch R = 1,5870,207,207,207
BEGIN DESCRIPTION:
UNT 013 in BCW 11.0
END DESCRIPTION:
XS GIS Cut Line= 3
      1956588.90     13515703.49      1955325.90     13515273.81
      1953808.38     13514714.50
#Sta/Elev= 30
  3524.7  651.70  3666.1  651.83  3818.0  645.71  3920.7  640.53  4008.2  638.53
  4126.2  634.46  4229.0  631.71  4251.0  632.10  4268.2  630.53  4345.9  628.80
  4434.5  626.52  4496.7  624.00  4640.1  621.91  4872.8  620.39  4928.3  618.59
  4981.9  619.00  4994.3  618.28  4994.8  617.78  5002.3  618.28  5051.6  620.08
  5156.3  620.70  5259.9  621.87  5394.1  623.59  5413.9  625.02  5449.7  624.44
  5557.7  627.43  5591.2  628.59  5621.7  627.77  5915.5  629.50  6476.1  642.42
#Mann=15,-1,0
  3524.7    0.05       0  3818.0    0.08       0  3920.7    0.05       0
  4008.2     0.1       0  4126.2    0.08       0  4229.0    0.05       0
  4345.9     0.1       0  4434.5    0.08       0  4640.1    0.05       0
  4981.9     0.1       0  4994.3    0.07       0  5002.3     0.1       0
  5156.3    0.08       0  5259.9    0.05       0  5557.7     0.1       0
Bank Sta=4994.3,5002.3
Exp/Cntr=0.3,0.1

Type RM Length L Ch R = 1,5663,124,124,124
BEGIN DESCRIPTION:
Mapping XS 51b9874f
END DESCRIPTION:
XS GIS Cut Line= 4
      1956279.63     13515426.75      1955266.58     13515038.72
      1954844.70     13514929.34      1954088.49     13514760.43
#Sta/Elev= 30
  3907.0  640.97  4041.8  636.07  4096.5  635.11  4243.9  630.69  4370.1  628.55
  4554.5  624.10  4794.0  620.21  4818.7  619.24  4848.7  619.25  4933.5  617.19
  4958.2  617.84  4963.5  617.12  4972.1  617.45  4982.8  616.38  4984.2  615.70
  4984.7  615.20  4991.7  615.20  4992.2  615.70  5014.1  617.56  5028.1  617.04
  5104.1  618.94  5307.0  620.07  5342.4  621.15  5601.5  625.34  5704.5  625.44
  5839.9  626.70  6001.1  629.64  6154.2  633.70  6159.3  633.31  6202.5  635.17
#Mann=3,-1,0
  3907.0     0.1       0  4984.2    0.07       0  4992.2     0.1       0
Bank Sta=4984.2,4992.2
Exp/Cntr=0.3,0.1

Type RM Length L Ch R = 1,5539,230,230,230
BEGIN DESCRIPTION:
UNT 013 in BCW 10.0
END DESCRIPTION:
XS GIS Cut Line= 3
      1956766.83     13515208.70      1955275.00     13514925.00
      1954029.05     13514670.69
#Sta/Elev= 30
  3507.7  652.39  3549.7  652.79  3612.1  648.20  3641.9  647.14  3682.6  643.52
  3794.6  641.74  3855.7  640.08  3873.2  638.92  3988.0  637.08  3998.2  637.46
  4034.9  636.11  4049.1  636.45  4515.0  625.72  4822.7  620.88  4924.5  617.52
  4975.4  617.24  4985.5  615.64  4996.1  615.64  4996.6  615.14  5004.3  615.64
  5005.9  616.83  5067.1  616.74  5198.0  618.82  5354.6  619.65  5450.6  622.26
  5506.2  621.68  5842.8  626.21  5854.7  625.86  6220.4  635.57  6297.9  639.16
#Mann=3,-1,0
  3507.7     0.1       0  4996.1    0.07       0  5004.3     0.1       0
Bank Sta=4996.1,5004.3
Exp/Cntr=0.3,0.1

Type RM Length L Ch R = 1,5309,640,640,640
BEGIN DESCRIPTION:
Mapping XS 53892888
END DESCRIPTION:
XS GIS Cut Line= 2
      1956136.38     13514908.51      1954034.80     13514486.63
#Sta/Elev= 30
  4077.9  638.12  4211.9  634.67  4225.0  634.92  4270.8  633.00  4275.9  633.68
  4303.7  631.96  4326.8  631.73  4423.5  628.10  4428.6  628.73  4568.9  625.01
  4701.5  622.51  4728.9  623.42  4762.7  623.09  4779.8  620.53  4946.3  616.63
  4966.7  616.80  4979.3  614.95  4979.8  614.45  4987.5  614.95  5090.3  617.51
  5374.6  618.50  5543.4  621.00  5609.2  623.20  5629.6  623.04  5696.1  624.59
  5803.0  628.28  5864.2  629.38  6058.0  636.16  6109.0  637.31  6221.4  643.68
#Mann=3,-1,0
  4077.9     0.1       0  4979.3    0.07       0  4987.5     0.1       0
Bank Sta=4979.3,4987.5
Exp/Cntr=0.3,0.1

Type RM Length L Ch R = 1,4669,119,119,119
BEGIN DESCRIPTION:
Mapping XS 2fa1bddc
END DESCRIPTION:
XS GIS Cut Line= 6
      1956120.77     13514762.68      1955292.62     13514614.24
      1955305.64     13514124.66      1955219.70     13514088.20
      1955157.20     13514572.57      1954046.21     13514309.79
#Sta/Elev= 30
  3588.3  640.76  4169.2  622.73  4482.4  617.30  4511.4  615.99  4516.9  613.73
  4576.3  614.57  4589.1  614.04  4599.6  613.81  4604.8  616.03  4639.8  613.90
  4645.0  616.33  4707.5  613.81  5154.4  613.65  5154.9  613.15  5162.7  613.65
  5190.3  615.09  5229.6  613.85  5305.3  613.97  5334.9  617.13  5340.1  614.92
  5416.2  616.37  5421.3  618.51  5467.6  616.29  5472.7  618.11  5509.6  616.41
  5552.2  618.57  5776.4  617.35  5909.9  619.23  6321.0  630.01  6679.4  644.20
#Mann=7,-1,0
  3588.3     0.1       0  4576.3    0.16       0  4589.1     0.1       0
  4707.5    0.16       0  5154.4    0.07       0  5162.7    0.16       0
  5229.6     0.1       0
Bank Sta=5154.4,5162.7
Exp/Cntr=0.3,0.1

Type RM Length L Ch R = 1,4550,67,67,67
BEGIN DESCRIPTION:
Mapping XS c60d0650
END DESCRIPTION:
XS GIS Cut Line= 6
      1956214.49     13514734.03      1955329.08     13514546.53
      1955334.29     13514007.47      1955128.56     13514069.97
      1955125.95     13514512.68      1953993.18     13514247.06
#Sta/Elev= 30
  3528.8  644.42  3595.6  642.16  3645.3  642.07  3824.7  635.80  4032.6  631.05
  4126.9  625.12  4182.5  623.16  4365.1  618.90  4432.0  618.78  4534.4  619.91
  4595.7  620.69  4728.5  619.48  4806.1  618.56  4976.9  619.02  4984.1  616.65
  4989.9  613.18  4990.4  612.68  4998.2  613.18  5004.1  614.16  5014.1  618.72
  5024.1  619.62  5129.6  619.53  5407.3  618.69  5567.5  620.08  5659.4  619.50
  5728.4  616.99  5892.8  617.47  6359.0  629.08  6652.9  639.41  6808.8  646.17
#Mann=7,-1,0
  3528.8     0.1       0  4432.0    0.16       0  4534.4     0.1       0
  4728.5    0.16       0  4989.9    0.07       0  4998.2    0.16       0
  5129.6     0.1       0
Bank Sta=4989.9,4998.2
Exp/Cntr=0.3,0.1