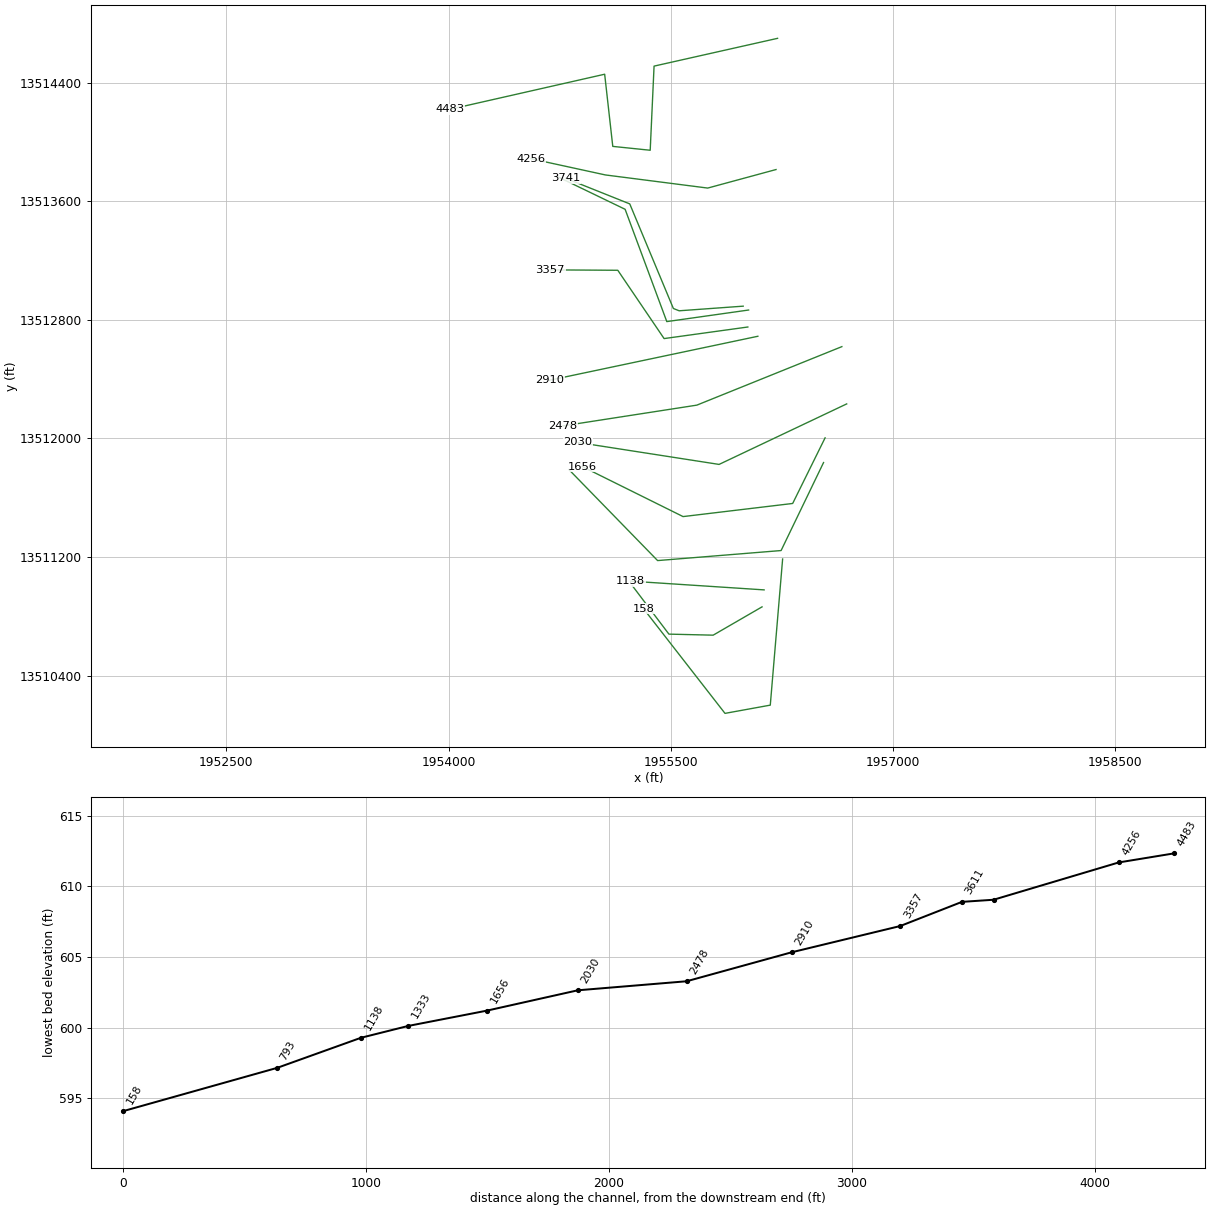
HEC-RAS study UNT 013 in BCW.prj: UNT 013 in BCW Base Level Engineering

--- UNT 013 in BCW.g01 (geometry) --- (continued)

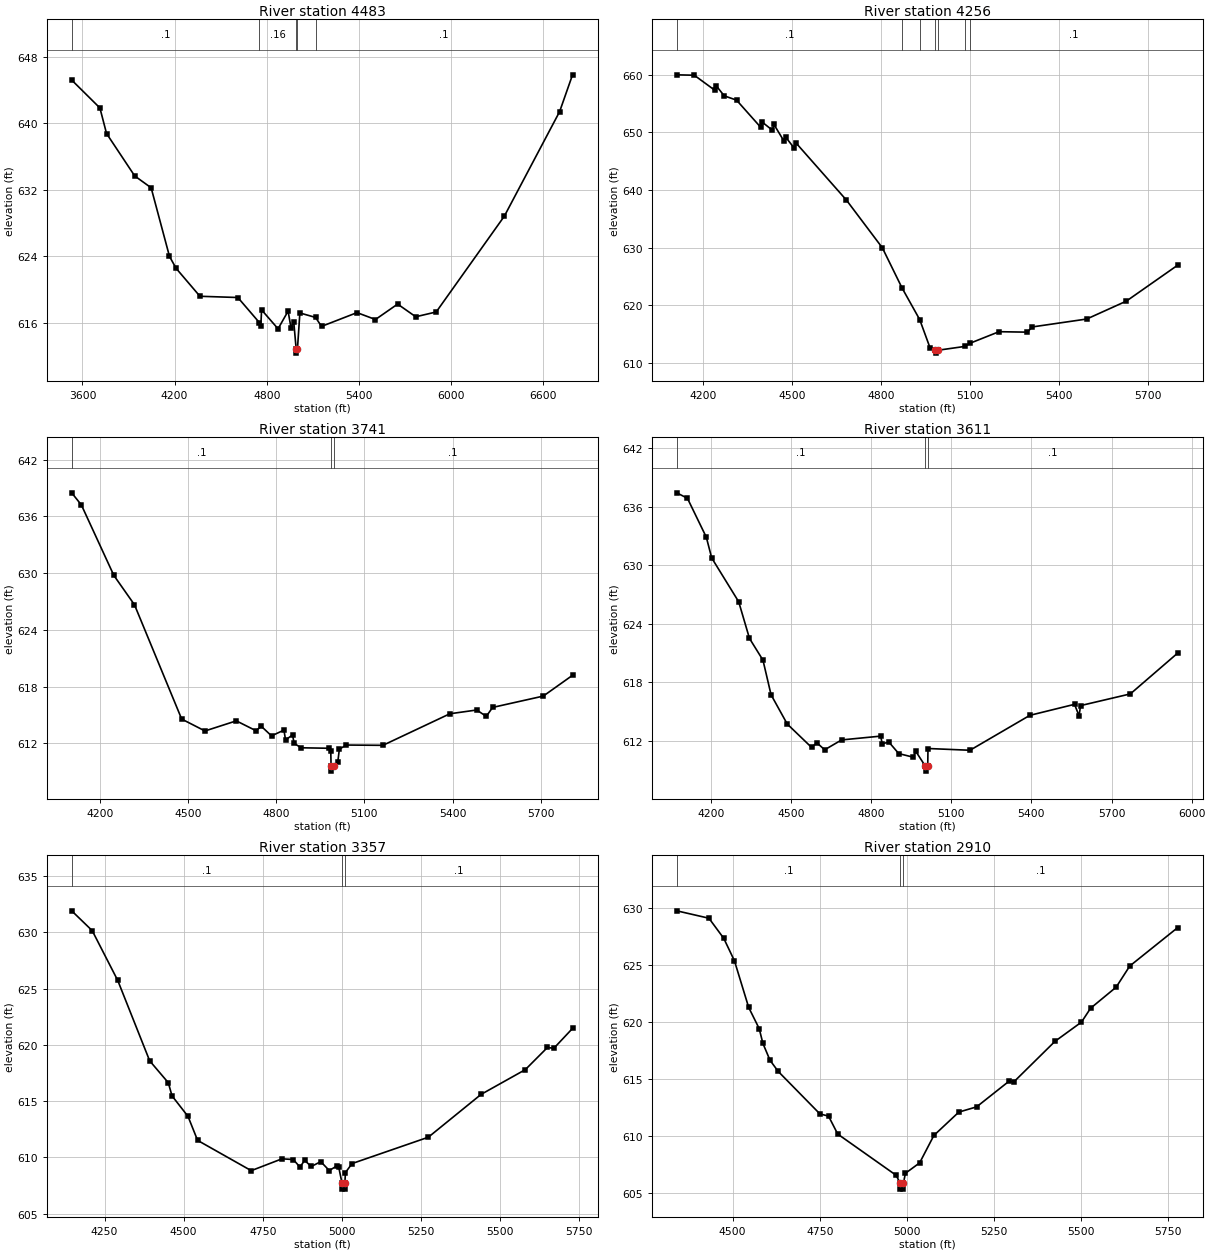
Type RM Length L Ch R = 1,4483,227,227,227
BEGIN DESCRIPTION:
Mapping XS e804fe82
END DESCRIPTION:
XS GIS Cut Line= 6
      1956219.66     13514700.17      1955386.37     13514512.68
      1955360.33     13513944.97      1955107.72     13513971.01
      1955053.04     13514457.99      1954009.35     13514221.14
#Sta/Elev= 30
  3529.9  645.23  3713.5  641.87  3756.7  638.79  3940.1  633.68  4047.2  632.25
  4166.7  623.98  4210.0  622.54  4364.9  619.18  4611.8  619.03  4752.8  615.99
  4761.4  615.61  4766.4  617.54  4873.7  615.26  4939.0  617.39  4957.8  615.41
  4975.8  616.11  4991.6  612.83  4992.1  612.33  4999.9  612.83  5015.8  617.17
  5118.0  616.63  5156.6  615.55  5387.8  617.21  5507.9  616.38  5652.4  618.24
  5770.3  616.71  5903.6  617.29  6347.2  628.83  6707.3  641.43  6791.3  645.86
#Mann=5,-1,0
  3529.9     0.1       0  4752.8    0.16       0  4991.6    0.07       0
  4999.9    0.16       0  5118.0     0.1       0
Bank Sta=4991.6,4999.9
Exp/Cntr=0.3,0.1

Type RM Length L Ch R = 1,4256,515,515,515
BEGIN DESCRIPTION:
Mapping XS 3e1e63f8
END DESCRIPTION:
XS GIS Cut Line= 4
      1956209.31     13513814.77      1955748.35     13513689.76
      1955058.24     13513778.30      1954555.68     13513887.67
#Sta/Elev= 30
  4111.5  660.00  4170.4  659.93  4239.7  657.32  4244.9  658.06  4271.4  656.35
  4312.8  655.61  4393.8  650.92  4399.0  651.81  4433.7  650.38  4438.9  651.38
  4473.5  648.43  4478.7  649.16  4508.1  647.22  4513.3  648.17  4683.2  638.25
  4804.2  629.97  4870.8  622.98  4930.2  617.50  4965.5  612.52  4983.0  612.19
  4983.5  611.69  4991.6  612.19  5082.9  612.86  5098.9  613.39  5197.4  615.41
  5293.1  615.33  5308.7  616.23  5492.9  617.61  5626.5  620.72  5799.2  626.95
#Mann=7,-1,0
  4111.5     0.1       0  4870.8    0.16       0  4930.2     0.1       0
  4983.0    0.07       0  4991.6     0.1       0  5082.9    0.16       0
  5098.9     0.1       0
Bank Sta=4983,4991.6
Exp/Cntr=0.3,0.1

Type RM Length L Ch R = 1,3741,130,130,130
BEGIN DESCRIPTION:
Mapping XS abf2650d
END DESCRIPTION:
XS GIS Cut Line= 5
      1955987.96     13512892.89      1955555.64     13512861.64
      1955516.58     13512877.26      1955222.31     13513582.99
      1954792.65     13513754.85
#Sta/Elev= 30
  4104.9  638.50  4137.9  637.21  4248.2  629.76  4318.4  626.65  4478.8  614.56
  4558.0  613.30  4664.6  614.37  4731.3  613.33  4749.7  613.79  4784.3  612.78
  4826.6  613.39  4832.0  612.35  4855.8  612.88  4861.2  611.99  4885.0  611.52
  4978.8  611.47  4985.8  611.20  4986.8  609.55  4987.3  609.05  4995.5  609.55
  5009.6  610.01  5015.0  611.38  5038.8  611.81  5163.0  611.78  5390.7  615.12
  5482.2  615.52  5514.5  614.84  5536.0  615.79  5708.3  616.99  5807.8  619.19
#Mann=3,-1,0
  4104.9     0.1       0  4986.8    0.07       0  4995.5     0.1       0
Bank Sta=4986.8,4995.5
Exp/Cntr=0.3,0.1

Type RM Length L Ch R = 1,3611,254,254,254
BEGIN DESCRIPTION:
Mapping XS 166ba7a7
END DESCRIPTION:
XS GIS Cut Line= 4
      1956024.37     13512866.84      1955472.31     13512788.72
      1955191.06     13513546.53      1954732.70     13513767.90
#Sta/Elev= 30
  4072.6  637.44  4112.4  636.88  4183.1  632.89  4203.3  630.76  4304.3  626.27
  4344.7  622.51  4395.2  620.28  4425.5  616.73  4486.1  613.73  4576.9  611.34
  4597.1  611.80  4626.3  611.09  4689.6  612.10  4836.1  612.49  4841.4  611.70
  4866.5  611.88  4903.5  610.70  4957.6  610.33  4967.5  610.92  5003.3  609.40
  5003.8  608.90  5012.0  609.40  5013.0  611.22  5170.2  611.04  5394.2  614.62
  5561.6  615.75  5578.5  614.57  5584.2  615.62  5770.6  616.82  5947.5  621.00
#Mann=3,-1,0
  4072.6     0.1       0  5003.3    0.07       0  5012.0     0.1       0
Bank Sta=5003.3,5012
Exp/Cntr=0.3,0.1

Type RM Length L Ch R = 1,3357,447,447,447
BEGIN DESCRIPTION:
Mapping XS 4ee504a3
END DESCRIPTION:
XS GIS Cut Line= 4
      1956019.15     13512752.26      1955454.08     13512674.14
      1955141.58     13513135.07      1954685.81     13513137.68
#Sta/Elev= 30
  4146.1  631.90  4210.9  630.14  4291.6  625.72  4392.6  618.58  4451.4  616.64
  4463.2  615.47  4513.7  613.65  4544.0  611.52  4713.6  608.83  4810.6  609.88
  4846.5  609.82  4867.5  609.15  4882.4  609.74  4903.4  609.20  4933.3  609.63
  4960.4  608.84  4983.4  609.24  4990.3  609.12  5000.8  607.69  5001.3  607.19
  5009.1  607.19  5009.6  607.69  5011.3  608.66  5032.3  609.46  5273.4  611.80
  5440.0  615.60  5580.0  617.80  5650.0  619.77  5670.0  619.69  5729.2  621.46
#Mann=3,-1,0
  4146.1     0.1       0  5000.8    0.07       0  5009.6     0.1       0
Bank Sta=5000.8,5009.6
Exp/Cntr=0.3,0.1

Type RM Length L Ch R = 1,2910,432,432,432
BEGIN DESCRIPTION:
Mapping XS 231d9c4a
END DESCRIPTION:
XS GIS Cut Line= 2
      1956086.86     13512689.75      1954680.65     13512392.89
#Sta/Elev= 30
  4339.7  629.79  4431.9  629.14  4474.5  627.37  4505.1  625.40  4546.0  621.30
  4576.1  619.44  4586.9  618.13  4607.3  616.65  4630.9  615.67  4750.4  611.94
  4775.1  611.75  4801.5  610.17  4969.0  606.55  4981.1  605.83  4981.6  605.33
  4989.4  605.33  4989.9  605.83  4995.7  606.72  5036.6  607.64  5077.5  610.05
  5149.0  612.10  5200.1  612.56  5292.1  614.79  5307.1  614.76  5425.0  618.32
  5501.0  620.01  5527.2  621.23  5600.5  623.08  5639.6  624.94  5776.9  628.31
#Mann=3,-1,0
  4339.7     0.1       0  4981.1    0.07       0  4989.9     0.1       0
Bank Sta=4981.1,4989.9
Exp/Cntr=0.3,0.1

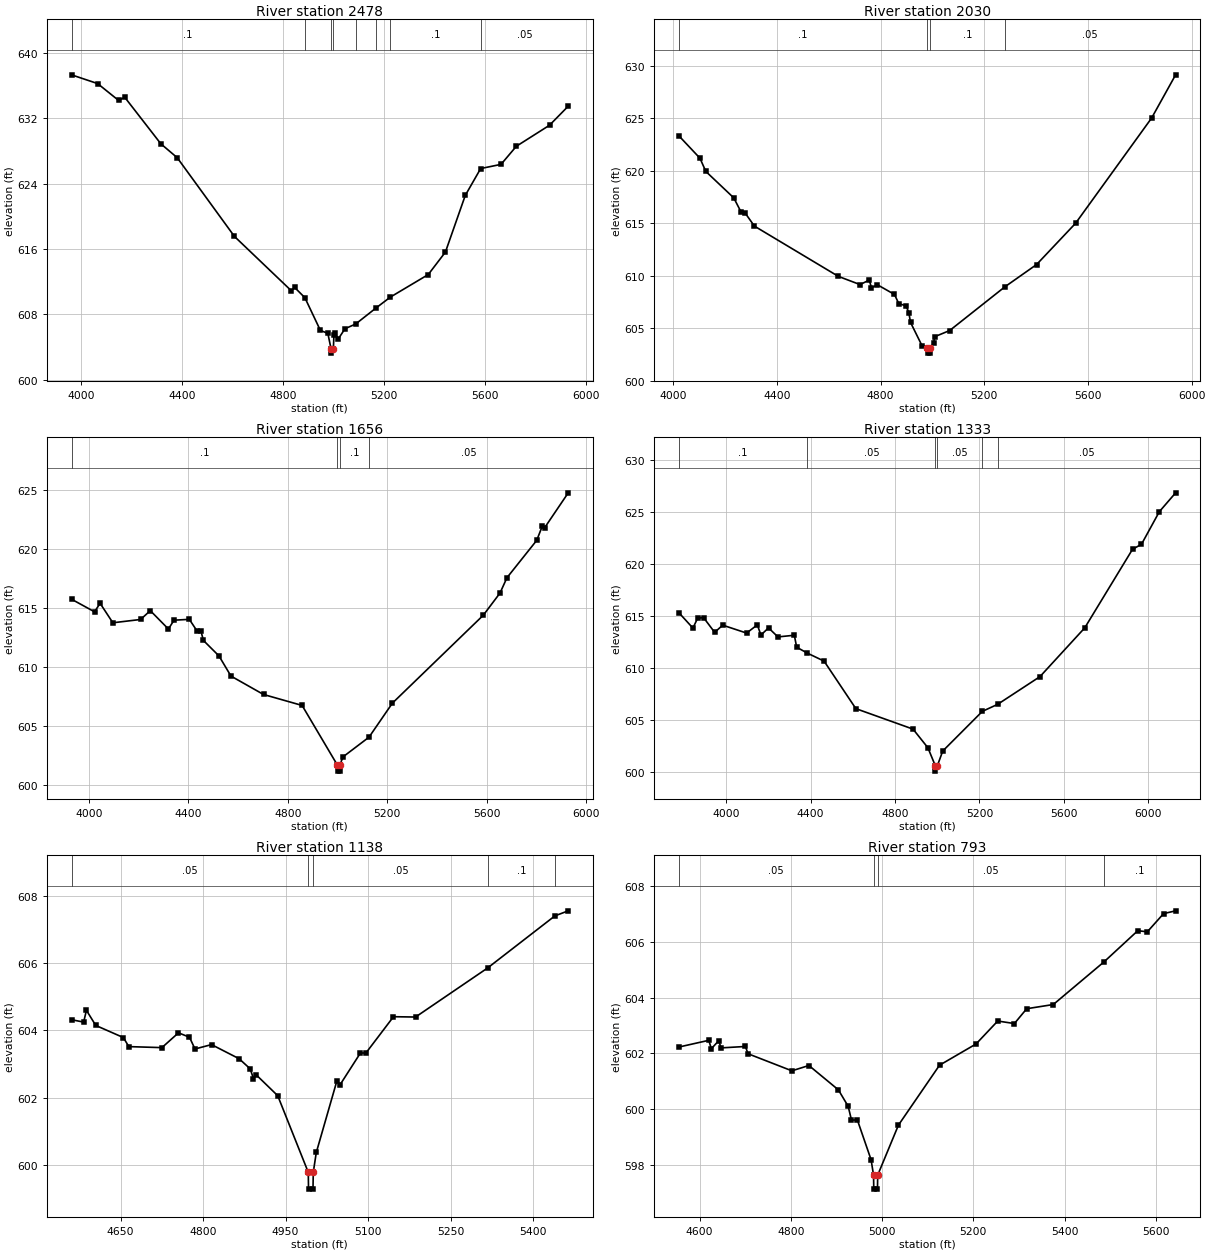
Type RM Length L Ch R = 1,2478,448,448,448
BEGIN DESCRIPTION:
UNT 013 in BCW 3.0
END DESCRIPTION:
XS GIS Cut Line= 3
      1956653.62     13512619.74      1955675.00     13512225.00
      1954771.62     13512085.00
#Sta/Elev= 30
  3961.8  637.28  4065.4  636.21  4148.6  634.15  4172.8  634.54  4316.1  628.85
  4380.8  627.16  4607.7  617.54  4833.7  610.89  4846.6  611.30  4887.1  610.05
  4948.6  606.05  4978.1  605.70  4991.0  603.78  4991.5  603.28  4999.9  603.78
  5002.3  605.45  5007.7  605.74  5019.6  605.02  5046.0  606.26  5088.6  606.84
  5167.2  608.75  5226.2  610.13  5376.2  612.88  5444.3  615.63  5523.0  622.55
  5584.0  625.83  5664.7  626.34  5725.4  628.55  5856.9  631.12  5931.2  633.45
#Mann=8,-1,0
  3961.8     0.1       0  4887.1    0.16       0  4991.0    0.07       0
  4999.9    0.16       0  5088.6     0.1       0  5167.2    0.16       0
  5226.2     0.1       0  5584.0    0.05       0
Bank Sta=4991,4999.9
Exp/Cntr=0.3,0.1

Type RM Length L Ch R = 1,2030,374,374,374
BEGIN DESCRIPTION:
UNT 013 in BCW 2.0
END DESCRIPTION:
XS GIS Cut Line= 3
      1956686.30     13512233.36      1955825.00     13511825.00
      1954873.74     13511972.95
#Sta/Elev= 30
  4022.3  623.34  4103.5  621.21  4126.2  619.95  4234.0  617.43  4262.6  616.06
  4278.3  615.97  4313.6  614.74  4637.5  609.95  4721.0  609.17  4756.7  609.60
  4765.2  608.85  4787.4  609.16  4853.8  608.23  4870.4  607.36  4898.7  607.14
  4909.1  606.50  4915.9  605.56  4961.4  603.28  4981.1  603.14  4981.6  602.64
  4989.6  602.64  4990.1  603.14  5004.4  603.57  5009.5  604.21  5066.6  604.79
  5279.4  608.95  5402.0  611.08  5552.4  615.01  5845.8  625.04  5938.2  629.15
#Mann=4,-1,0
  4022.3     0.1       0  4981.1    0.07       0  4990.1     0.1       0
  5279.4    0.05       0
Bank Sta=4981.1,4990.1
Exp/Cntr=0.3,0.1

Type RM Length L Ch R = 1,1656,323,323,323
BEGIN DESCRIPTION:
Mapping XS 494de5e2
END DESCRIPTION:
XS GIS Cut Line= 4
      1956540.46     13512004.20      1956321.71     13511561.48
      1955582.12     13511472.94      1954901.39     13511810.71
#Sta/Elev= 30
  3929.6  615.78  4022.2  614.71  4044.7  615.43  4096.0  613.78  4207.6  614.06
  4246.6  614.81  4319.5  613.25  4342.0  614.00  4403.7  614.07  4435.5  613.06
  4450.3  613.08  4460.4  612.28  4522.9  610.97  4571.2  609.26  4702.1  607.70
  4857.4  606.77  4999.7  601.70  5000.2  601.20  5008.3  601.20  5008.8  601.70
  5022.1  602.41  5126.6  604.08  5220.9  606.97  5586.4  614.42  5653.6  616.30
  5681.6  617.60  5801.4  620.77  5823.7  621.97  5832.9  621.83  5928.2  624.80
#Mann=4,-1,0
  3929.6     0.1       0  4999.7    0.07       0  5008.8     0.1       0
  5126.6    0.05       0
Bank Sta=4999.7,5008.8
Exp/Cntr=0.3,0.1

Type RM Length L Ch R = 1,1333,195,195,195
BEGIN DESCRIPTION:
Mapping XS d9c1c3ea
END DESCRIPTION:
XS GIS Cut Line= 4
      1956530.05     13511837.55      1956243.58     13511243.77
      1955410.25     13511176.07      1954811.58     13511790.35
#Sta/Elev= 30
  3776.1  615.36  3842.6  613.88  3865.2  614.84  3893.4  614.88  3945.5  613.47
  3983.8  614.16  4096.9  613.40  4147.7  614.19  4164.7  613.21  4200.8  613.90
  4245.3  613.03  4323.0  613.19  4334.1  612.04  4384.7  611.47  4464.0  610.70
  4614.5  606.13  4885.4  604.16  4955.7  602.37  4991.2  600.62  4991.7  600.12
  5000.3  600.62  5025.9  602.05  5213.7  605.87  5285.7  606.54  5486.6  609.21
  5698.7  613.90  5925.1  621.46  5967.5  621.94  6052.2  625.08  6129.2  626.89
#Mann=6,-1,0
  3776.1     0.1       0  4384.7    0.05       0  4991.2   0.035       0
  5000.3    0.05       0  5213.7     0.1       0  5285.7    0.05       0
Bank Sta=4991.2,5000.3
Exp/Cntr=0.3,0.1

Type RM Length L Ch R = 1,1138,345,345,345
BEGIN DESCRIPTION:
Mapping XS 2fc43a1b
END DESCRIPTION:
XS GIS Cut Line= 2
      1956128.96     13510978.35      1955228.09     13511037.26
#Sta/Elev= 30
  4560.9  604.32  4583.0  604.25  4588.0  604.60  4605.0  604.15  4655.1  603.79
  4665.1  603.52  4725.2  603.49  4755.3  603.93  4775.3  603.80  4785.3  603.45
  4815.4  603.58  4865.5  603.16  4885.6  602.86  4891.6  602.57  4896.6  602.68
  4935.7  602.06  4991.2  599.78  4991.7  599.28  4999.8  599.28  5000.3  599.78
  5005.8  600.37  5043.4  602.51  5048.4  602.37  5086.0  603.33  5096.0  603.33
  5146.1  604.41  5186.2  604.40  5317.2  605.86  5439.5  607.41  5463.7  607.56
#Mann=5,-1,0
  4560.9    0.05       0  4991.2   0.035       0  5000.3    0.05       0
  5317.2     0.1       0  5439.5    0.05       0
Bank Sta=4991.2,5000.3
Exp/Cntr=0.3,0.1

Type RM Length L Ch R = 1,793,635,635,635
BEGIN DESCRIPTION:
Mapping XS 8ad09e27
END DESCRIPTION:
XS GIS Cut Line= 4
      1956114.99     13510863.75      1955785.17     13510672.80
      1955486.55     13510679.75      1955240.05     13511006.11
#Sta/Elev= 30
  4554.5  602.23  4620.0  602.47  4625.7  602.17  4641.5  602.45  4647.3  602.20
  4700.3  602.25  4706.1  601.99  4802.2  601.38  4839.5  601.57  4904.1  600.70
  4925.6  600.11  4932.8  599.62  4945.8  599.62  4975.8  598.20  4981.2  597.65
  4981.7  597.15  4989.8  597.15  4990.3  597.65  5035.8  599.44  5125.8  601.58
  5205.9  602.34  5253.4  603.16  5289.9  603.07  5316.9  603.60  5375.2  603.75
  5486.7  605.28  5560.4  606.39  5581.3  606.35  5616.9  607.00  5643.3  607.10
#Mann=4,-1,0
  4554.5    0.05       0  4981.2   0.035       0  4990.3    0.05       0
  5486.7     0.1       0
Bank Sta=4981.2,4990.3
Exp/Cntr=0.3,0.1

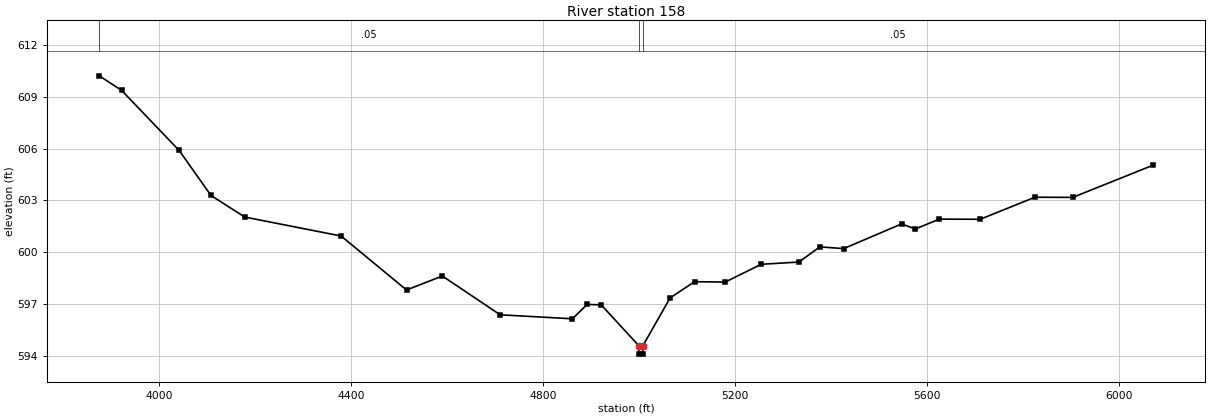
Type RM Length L Ch R = 1,158,0,0,0
BEGIN DESCRIPTION:
UNT 013 in BCW 1.0
END DESCRIPTION:
XS GIS Cut Line= 4
      1956253.91     13511186.65      1956170.58     13510200.58
      1955865.03     13510145.02      1955316.45     13510849.85
#Sta/Elev= 30
  3876.4  610.22  3923.0  609.37  4042.6  605.89  4108.9  603.28  4179.1  602.03
  4379.8  600.93  4516.0  597.80  4590.6  598.61  4711.0  596.36  4861.3  596.13
  4892.0  596.96  4921.3  596.94  4999.2  594.58  4999.7  594.08  5007.9  594.08
  5008.4  594.58  5064.8  597.34  5115.6  598.28  5179.7  598.26  5254.4  599.29
  5333.1  599.42  5376.5  600.30  5426.3  600.20  5546.6  601.63  5575.6  601.34
  5625.3  601.91  5710.4  601.90  5824.4  603.18  5903.1  603.17  6069.7  605.03
#Mann=3,-1,0
  3876.4    0.05       0  4999.2   0.035       0  5008.4    0.05       0
Bank Sta=4999.2,5008.4
Exp/Cntr=0.3,0.1

Chan Stop Cuts=-1