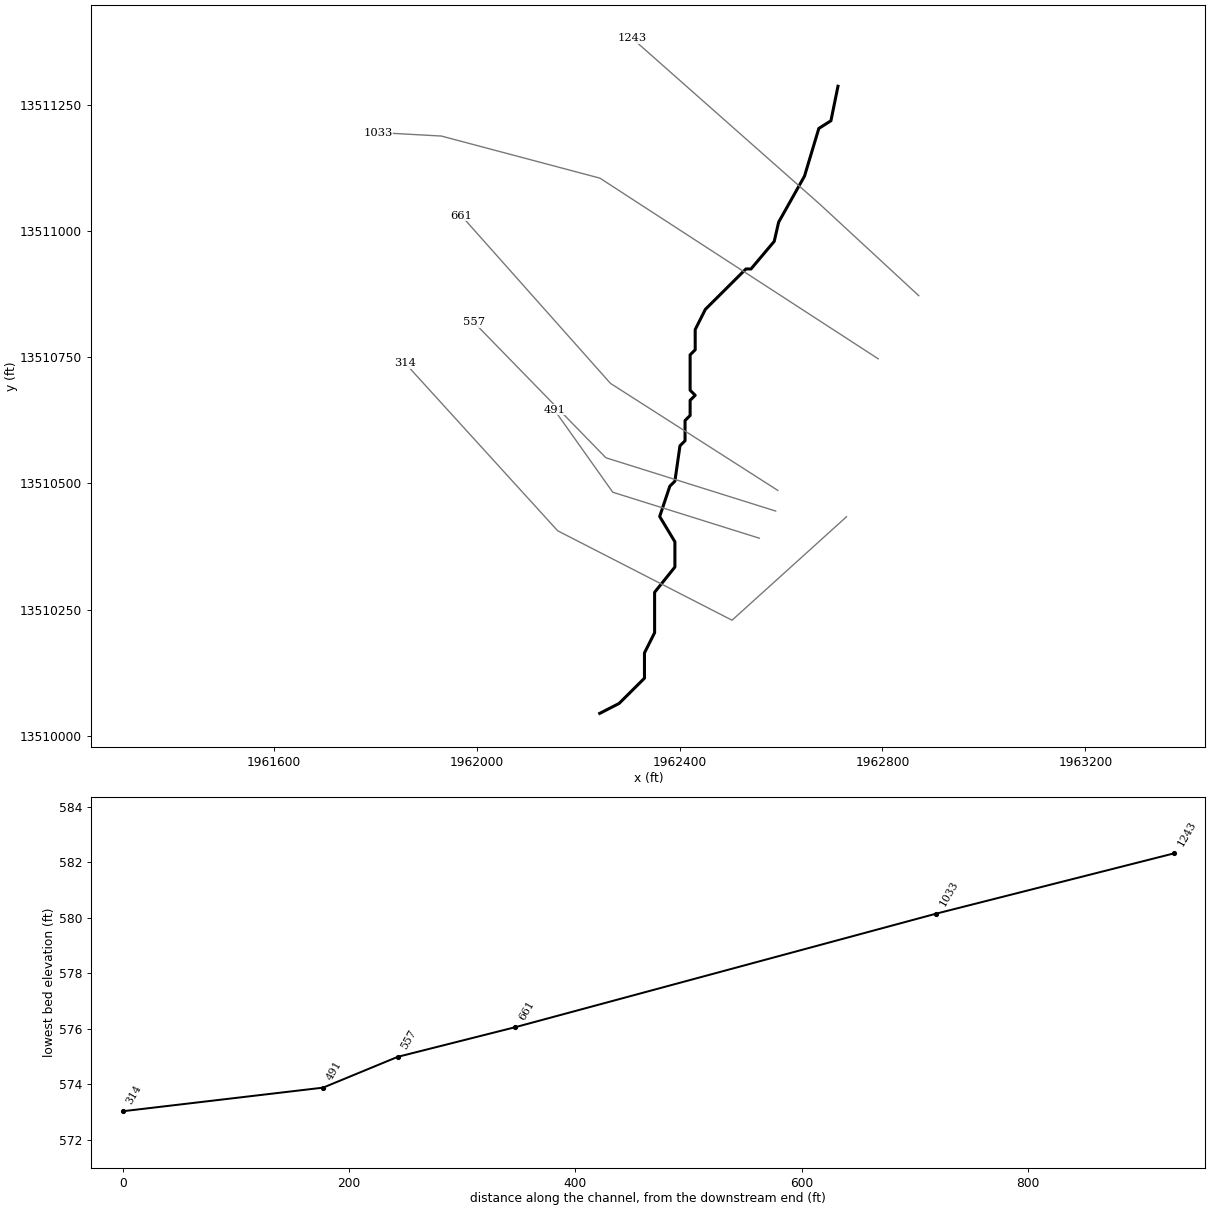
--- UNT 014 in BCW.prj (project) ---

Proj Title=UNT 014 in BCW Base Level Engineering
Current Plan=p01
Default Exp/Contr=0.3,0.1
English Units
Geom File=g01
Flow File=f01
Plan File=p01
BEGIN DESCRIPTION:
UNT 014 in BCW
END DESCRIPTION:

--- UNT 014 in BCW.p01 (plan) ---

Plan Title=Multiple Run
Short Identifier=Multiple
Geom File=g01
Flow File=f01
Subcritical Flow
K Sum by GR= 0
Std Step Tol= 0.01
Critical Tol= 0.01
Num of Std Step Trials= 20
Max Error Tol= 0.3
Flow Tol Ratio= 0.001
Split Flow NTrial= 30
Split Flow Tol= 0.02
Split Flow Ratio= 0.02
Log Output Level= 0
Friction Slope Method= 1
Unsteady Friction Slope Method= 2
Unsteady Bridges Friction Slope Method= 1
Parabolic Critical Depth
Global Vel Dist=  1 , 1 , 1
Global Log Level= 0
CheckData=True
Encroach Param= -1, 0, 0, 0
BEGIN DESCRIPTION:
Multiple Run
END DESCRIPTION:

--- UNT 014 in BCW.f01 (steady flow) ---

Flow Title=Multiple
Number of Profiles=7
Profile Names=10-year,25-year,50-year,1pct_min,100-year,1pct_plu,500-year
River Rch & RM= UNT 014 in BCW,Reach-1,1243
     125     168     203     123     246     490     365
Boundary for River Rch & Prof#=UNT 014 in BCW,Reach-1,1
Up Type=0
Dn Type=3
Dn Slope=0.005
Boundary for River Rch & Prof#=UNT 014 in BCW,Reach-1,2
Up Type=0
Dn Type=3
Dn Slope=0.005
Boundary for River Rch & Prof#=UNT 014 in BCW,Reach-1,3
Up Type=0
Dn Type=3
Dn Slope=0.005
Boundary for River Rch & Prof#=UNT 014 in BCW,Reach-1,4
Up Type=0
Dn Type=3
Dn Slope=0.005
Boundary for River Rch & Prof#=UNT 014 in BCW,Reach-1,5
Up Type=0
Dn Type=3
Dn Slope=0.005
Boundary for River Rch & Prof#=UNT 014 in BCW,Reach-1,6
Up Type=0
Dn Type=3
Dn Slope=0.005
Boundary for River Rch & Prof#=UNT 014 in BCW,Reach-1,7
Up Type=0
Dn Type=3
Dn Slope=0.005

--- UNT 014 in BCW.g01 (geometry) ---

Geom Title=Existing Conditions

River Reach=UNT 014 in BCW,Reach-1
Reach XY= 30
      1962712.25     13511286.17      1962698.35     13511217.87
      1962674.48     13511202.68      1962646.27     13511108.28
      1962595.27     13511017.13      1962586.59     13510979.16
      1962540.80     13510924.54      1962530.80     13510924.54
      1962450.80     13510844.54      1962430.80     13510804.54
      1962430.80     13510764.54      1962420.80     13510754.54
      1962420.80     13510684.54      1962430.80     13510674.54
      1962420.80     13510664.54      1962420.80     13510634.54
      1962410.80     13510624.54      1962410.80     13510584.54
      1962400.80     13510574.54      1962390.80     13510504.54
      1962380.80     13510494.54      1962360.80     13510434.54
      1962390.80     13510384.54      1962390.80     13510334.54
      1962350.80     13510284.54      1962350.80     13510204.54
      1962330.80     13510164.54      1962330.80     13510114.54
      1962280.80     13510064.54      1962242.62     13510044.91

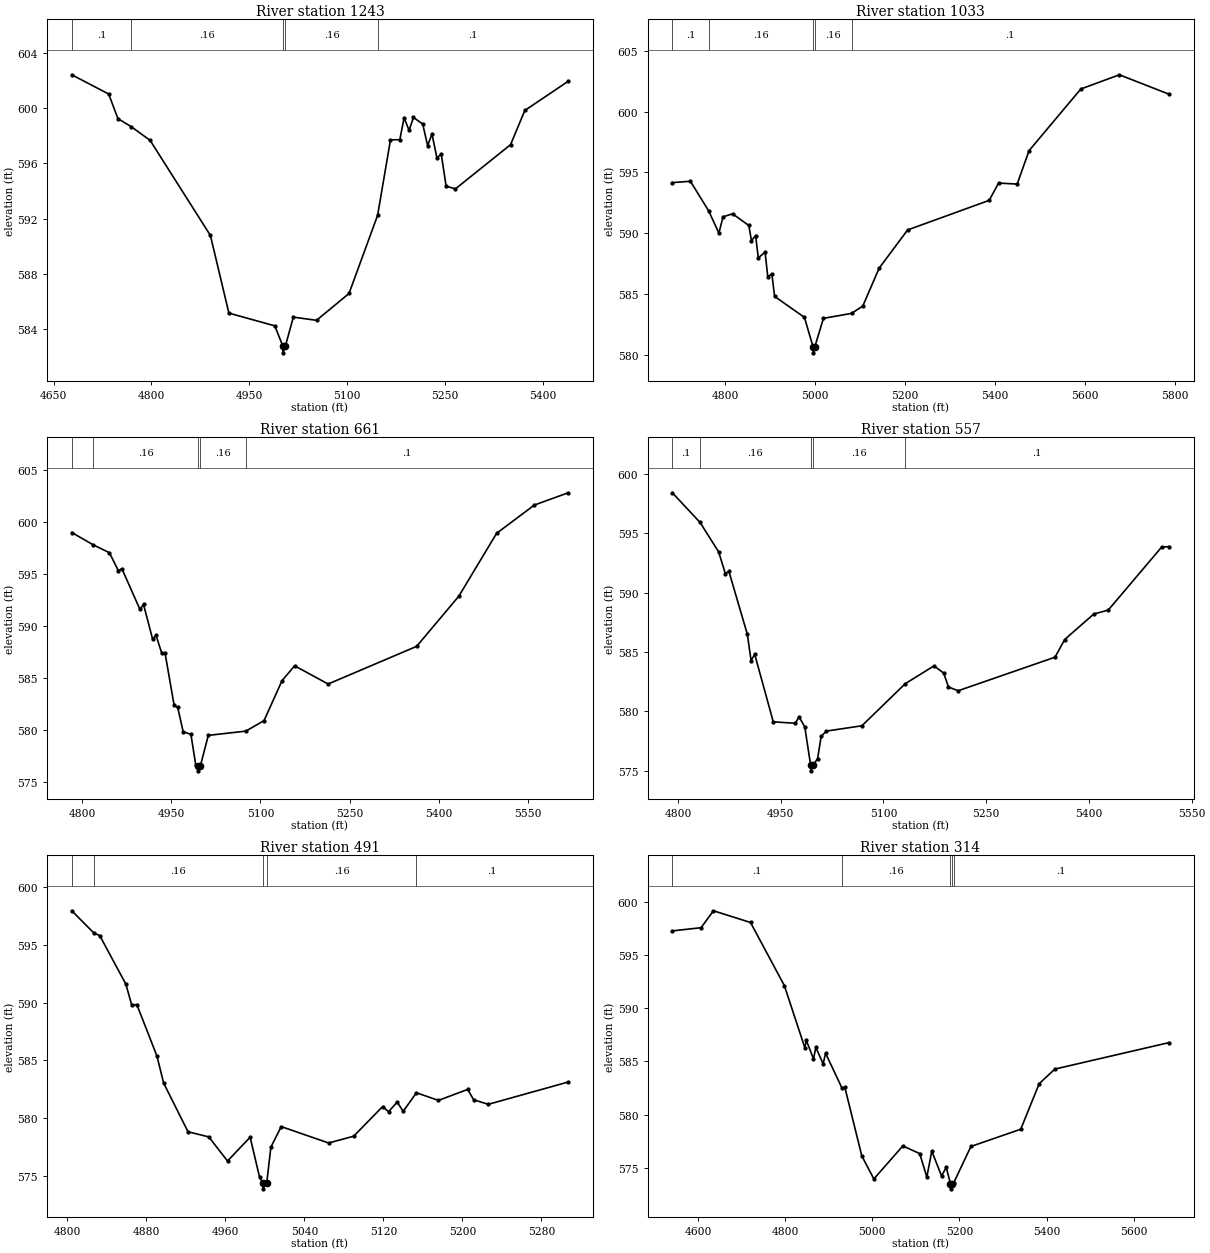
Type RM Length L Ch R = 1,1243,210,210,210
BEGIN DESCRIPTION:
UNT 014 in BCW 2.0
END DESCRIPTION:
XS GIS Cut Line= 3
      1962871.47     13510871.64      1962677.03     13511052.20
      1962306.68     13511381.01
#Sta/Elev= 30
  4678.0  602.40  4734.5  601.01  4748.7  599.23  4769.4  598.64  4798.0  597.66
  4890.4  590.79  4918.7  585.18  4989.0  584.26  5001.3  582.81  5001.5  582.31
  5005.3  582.81  5017.5  584.89  5053.0  584.66  5102.8  586.60  5146.6  592.25
  5166.3  597.70  5180.6  597.71  5187.2  599.30  5194.8  598.38  5201.5  599.32
  5215.7  598.84  5223.2  597.28  5229.9  598.12  5237.4  596.41  5244.1  596.66
  5251.6  594.35  5265.9  594.16  5350.3  597.35  5372.1  599.82  5438.6  601.93
#Mann=5,-1,0
  4678.0     0.1       0  4769.4    0.16       0  5001.3    0.07       0
  5005.3    0.16       0  5146.6     0.1       0
Bank Sta=5001.3,5005.3
Exp/Cntr=0.3,0.1

Type RM Length L Ch R = 1,1033,372,372,372
BEGIN DESCRIPTION:
Mapping XS 0c638272
END DESCRIPTION:
XS GIS Cut Line= 4
      1962791.59     13510746.66      1962243.00     13511104.28
      1961930.50     13511187.61      1961805.47     13511194.56
#Sta/Elev= 30
  4683.0  594.16  4723.2  594.27  4763.8  591.83  4786.5  590.00  4795.7  591.34
  4816.8  591.59  4853.0  590.63  4858.9  589.38  4868.1  589.80  4874.1  587.96
  4889.2  588.43  4895.2  586.41  4904.3  586.64  4910.3  584.79  4976.7  583.06
  4995.8  580.64  4996.1  580.14  4999.8  580.64  5018.9  582.98  5081.5  583.39
  5106.5  584.00  5142.7  587.11  5206.0  590.26  5387.5  592.70  5408.2  594.12
  5449.6  594.04  5476.0  596.79  5591.1  601.87  5676.8  603.04  5786.5  601.45
#Mann=5,-1,0
  4683.0     0.1       0  4763.8    0.16       0  4995.8    0.07       0
  4999.8    0.16       0  5081.5     0.1       0
Bank Sta=4995.8,4999.8
Exp/Cntr=0.3,0.1

Type RM Length L Ch R = 1,661,104,104,104
BEGIN DESCRIPTION:
Mapping XS 60a5af7f
END DESCRIPTION:
XS GIS Cut Line= 3
      1962593.73     13510486.20      1962263.84     13510698.03
      1961969.93     13511029.96
#Sta/Elev= 30
  4782.6  598.97  4819.1  597.77  4845.8  597.03  4861.0  595.30  4866.9  595.49
  4897.3  591.57  4903.3  592.05  4918.5  588.74  4924.4  589.07  4933.7  587.41
  4939.6  587.36  4954.8  582.35  4960.8  582.15  4970.0  579.82  4983.1  579.55
  4991.1  576.64  4995.1  576.55  4995.3  576.05  4999.1  576.55  5012.3  579.46
  5075.6  579.87  5106.1  580.88  5136.5  584.73  5157.6  586.15  5214.0  584.40
  5362.9  588.02  5434.0  592.85  5497.5  598.89  5561.1  601.61  5618.0  602.79
#Mann=5,-1,0
  4782.6     0.1       0  4819.1    0.16       0  4995.1    0.07       0
  4999.1    0.16       0  5075.6     0.1       0
Bank Sta=4995.1,4999.1
Exp/Cntr=0.3,0.1

Type RM Length L Ch R = 1,557,66,66,66
BEGIN DESCRIPTION:
Mapping XS c412b8da
END DESCRIPTION:
XS GIS Cut Line= 3
      1962589.46     13510445.36      1962254.78     13510550.84
      1961994.34     13510819.10
#Sta/Elev= 30
  4791.7  598.42  4832.2  595.92  4859.3  593.44  4869.1  591.61  4874.3  591.79
  4901.2  586.50  4906.7  584.28  4912.0  584.80  4939.1  579.11  4971.4  578.99
  4976.7  579.54  4985.1  578.68  4993.6  575.48  4993.8  574.98  4997.6  575.48
  5003.8  576.01  5009.0  577.88  5016.6  578.33  5068.5  578.78  5131.9  582.33
  5173.8  583.83  5187.9  583.22  5194.9  582.05  5209.0  581.73  5350.5  584.56
  5364.6  586.05  5407.1  588.20  5428.2  588.53  5506.1  593.84  5516.5  593.88
#Mann=5,-1,0
  4791.7     0.1       0  4832.2    0.16       0  4993.6    0.07       0
  4997.6    0.16       0  5131.9     0.1       0
Bank Sta=4993.6,4997.6
Exp/Cntr=0.3,0.1

Type RM Length L Ch R = 1,491,177,177,177
BEGIN DESCRIPTION:
Mapping XS 4db3991c
END DESCRIPTION:
XS GIS Cut Line= 3
      1962557.27     13510391.61      1962268.35     13510482.60
      1962153.08     13510645.78
#Sta/Elev= 30
  4804.5  597.95  4826.9  596.02  4832.8  595.80  4859.3  591.59  4865.1  589.81
  4870.4  589.82  4890.8  585.35  4897.5  583.03  4922.2  578.81  4943.2  578.37
  4962.2  576.28  4985.1  578.34  4994.6  574.90  4997.9  574.37  4998.1  573.87
  5001.9  574.37  5006.1  577.48  5016.6  579.26  5064.6  577.84  5090.0  578.43
  5119.2  580.99  5125.3  580.55  5134.0  581.38  5140.1  580.58  5153.5  582.19
  5175.8  581.53  5205.4  582.48  5211.5  581.58  5226.3  581.19  5307.2  583.12
#Mann=5,-1,0
  4804.5     0.1       0  4826.9    0.16       0  4997.9    0.07       0
  5001.9    0.16       0  5153.5     0.1       0
Bank Sta=4997.9,5001.9
Exp/Cntr=0.3,0.1

Type RM Length L Ch R = 1,314,0,0,0
BEGIN DESCRIPTION:
UNT 014 in BCW 1.0
END DESCRIPTION:
XS GIS Cut Line= 4
      1962729.08     13510434.11      1962503.42     13510229.28
      1962159.67     13510406.36      1961858.79     13510738.36
#Sta/Elev= 30
  4540.9  597.25  4606.9  597.55  4635.2  599.14  4720.4  598.04  4798.1  592.11
  4845.1  586.27  4848.4  586.98  4864.9  585.23  4870.5  586.30  4887.1  584.76
  4892.7  585.76  4930.5  582.47  4937.0  582.54  4975.8  576.12  5003.5  573.95
  5070.0  577.05  5108.8  576.33  5125.1  574.12  5136.5  576.57  5158.9  574.23
  5169.6  575.03  5179.4  573.52  5179.6  573.02  5183.4  573.52  5186.8  573.58
  5226.3  577.00  5340.7  578.62  5383.2  582.91  5419.1  584.27  5680.4  586.75
#Mann=5,-1,0
  4540.9     0.1       0  4930.5    0.16       0  5179.4    0.07       0
  5183.4    0.16       0  5186.8     0.1       0
Bank Sta=5179.4,5183.4
Exp/Cntr=0.3,0.1

Chan Stop Cuts=-1