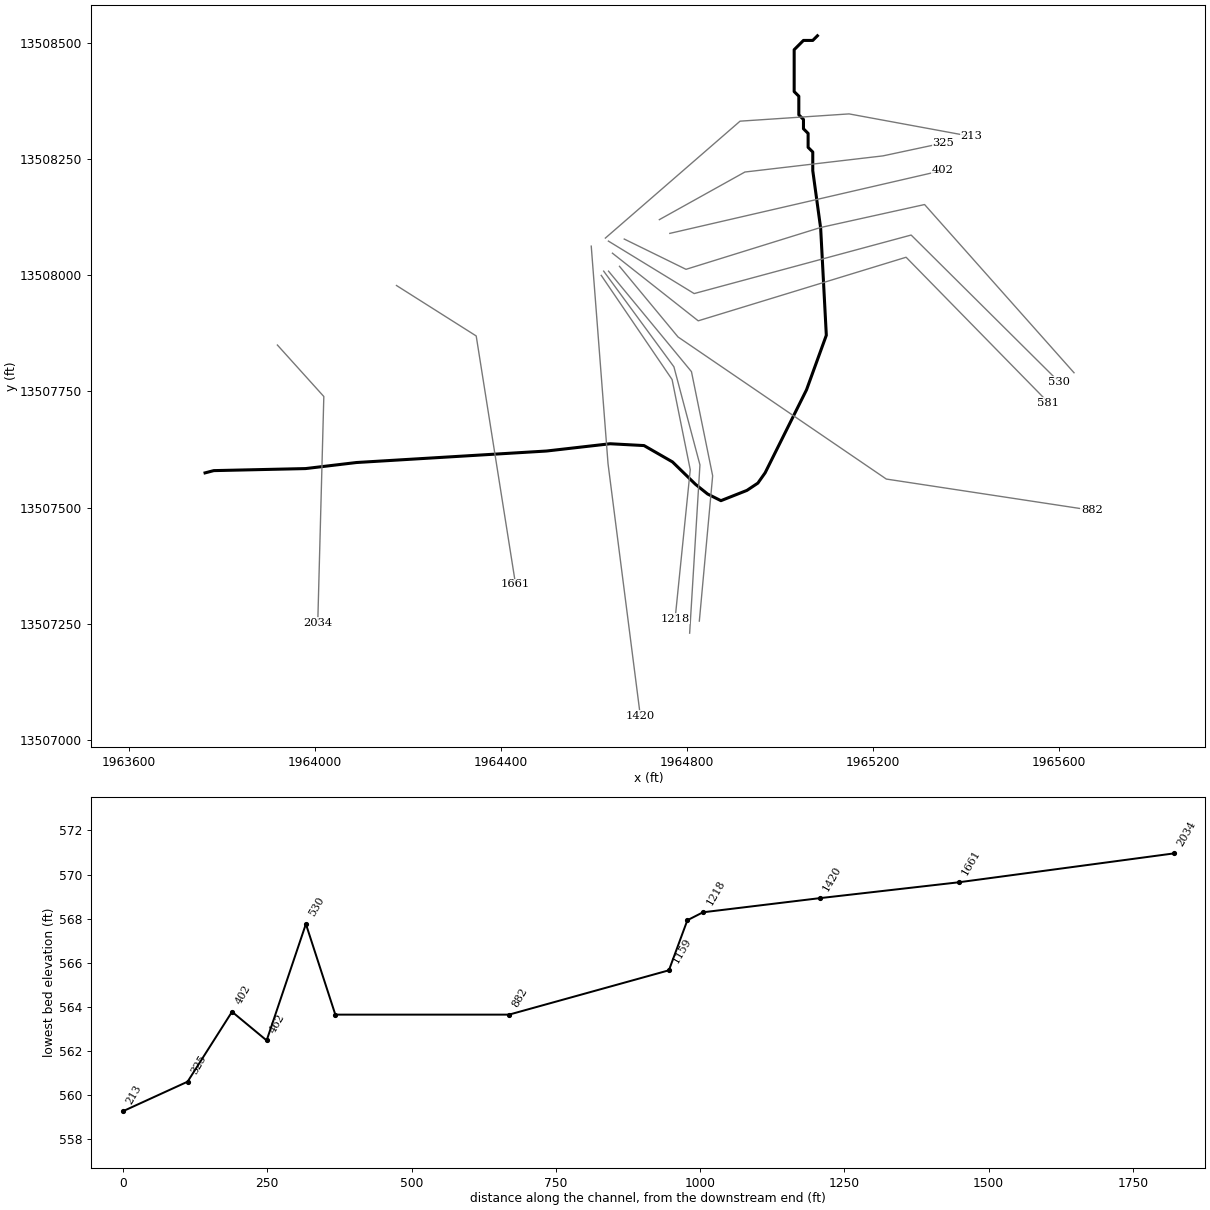
--- UNT 015 in BCW.prj (project) ---

Proj Title=UNT 015 in BCW Base Level Engineering
Current Plan=p01
Default Exp/Contr=0.3,0.1
English Units
Geom File=g01
Flow File=f01
Plan File=p01
BEGIN DESCRIPTION:
UNT 015 in BCW
END DESCRIPTION:

--- UNT 015 in BCW.p01 (plan) ---

Plan Title=Multiple Run
Short Identifier=Multiple
Geom File=g01
Flow File=f01
Subcritical Flow
K Sum by GR= 0
Std Step Tol= 0.01
Critical Tol= 0.01
Num of Std Step Trials= 20
Max Error Tol= 0.3
Flow Tol Ratio= 0.001
Split Flow NTrial= 30
Split Flow Tol= 0.02
Split Flow Ratio= 0.02
Log Output Level= 0
Friction Slope Method= 1
Unsteady Friction Slope Method= 2
Unsteady Bridges Friction Slope Method= 1
Parabolic Critical Depth
Global Vel Dist=  1 , 1 , 1
Global Log Level= 0
CheckData=True
Encroach Param= -1, 0, 0, 0
BEGIN DESCRIPTION:
Multiple Run
END DESCRIPTION:

--- UNT 015 in BCW.f01 (steady flow) ---

Flow Title=Multiple
Number of Profiles=7
Profile Names=10-year,25-year,50-year,1pct_min,100-year,1pct_plu,500-year
River Rch & RM= UNT 015 in BCW,Reach-1,2034
     109     146     175     105     210     420     308
River Rch & RM= UNT 015 in BCW,Reach-1,882
     135     182     221     134     267     532     397
Boundary for River Rch & Prof#=UNT 015 in BCW,Reach-1,1
Up Type=0
Dn Type=3
Dn Slope=0.005
Boundary for River Rch & Prof#=UNT 015 in BCW,Reach-1,2
Up Type=0
Dn Type=3
Dn Slope=0.005
Boundary for River Rch & Prof#=UNT 015 in BCW,Reach-1,3
Up Type=0
Dn Type=3
Dn Slope=0.005
Boundary for River Rch & Prof#=UNT 015 in BCW,Reach-1,4
Up Type=0
Dn Type=3
Dn Slope=0.005
Boundary for River Rch & Prof#=UNT 015 in BCW,Reach-1,5
Up Type=0
Dn Type=3
Dn Slope=0.005
Boundary for River Rch & Prof#=UNT 015 in BCW,Reach-1,6
Up Type=0
Dn Type=3
Dn Slope=0.005
Boundary for River Rch & Prof#=UNT 015 in BCW,Reach-1,7
Up Type=0
Dn Type=3
Dn Slope=0.005

--- UNT 015 in BCW.g01 (geometry) ---

Geom Title=Existing Conditions

River Reach=UNT 015 in BCW,Reach-1
Reach XY= 30
      1963763.92     13507574.54      1963782.66     13507579.40
      1963980.07     13507583.79      1964089.44     13507596.81
      1964498.29     13507621.55      1964635.01     13507637.18
      1964707.93     13507633.27      1964769.13     13507598.12
      1964818.61     13507549.94      1964844.65     13507529.11
      1964873.29     13507514.78      1964929.28     13507536.92
      1964952.72     13507552.54      1964968.35     13507574.68
      1965057.41     13507753.28      1965099.94     13507870.47
      1965087.79     13508100.50      1965070.80     13508224.54
      1965070.80     13508264.54      1965060.80     13508274.54
      1965060.80     13508304.54      1965050.80     13508314.54
      1965050.80     13508334.54      1965040.80     13508344.54
      1965040.80     13508384.54      1965030.80     13508394.54
      1965030.80     13508484.54      1965050.80     13508504.54
      1965070.80     13508504.54      1965080.80     13508514.54

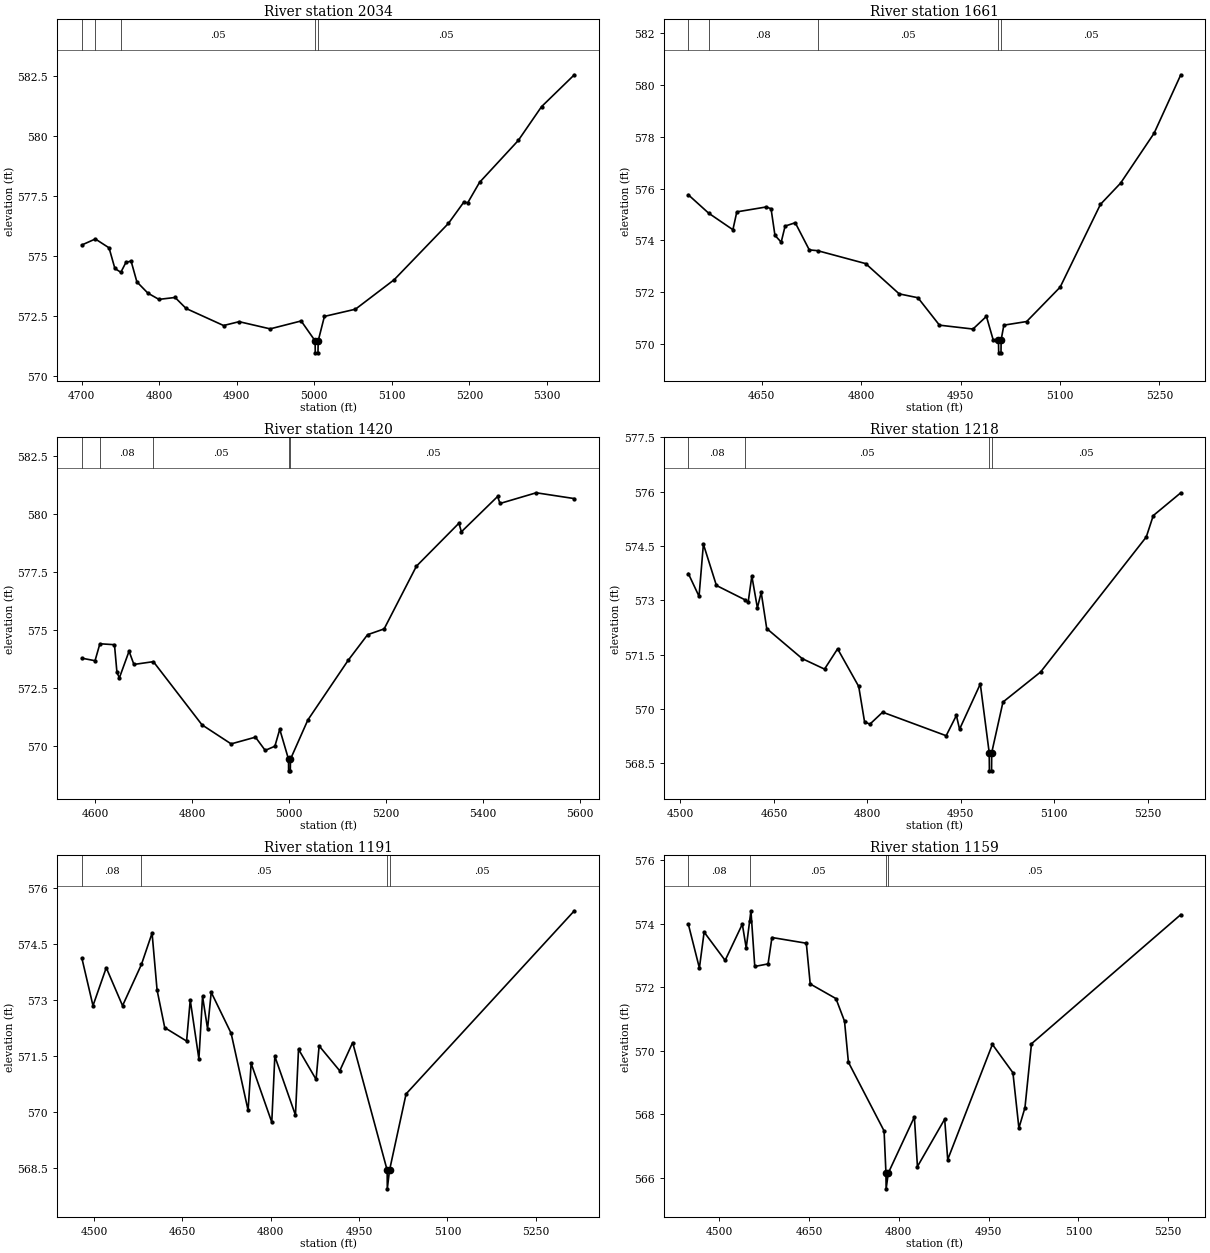
Type RM Length L Ch R = 1,2034,373,373,373
BEGIN DESCRIPTION:
UNT 015 in BCW 1.0
END DESCRIPTION:
XS GIS Cut Line= 3
      1963919.50     13507849.46      1964019.33     13507738.78
      1964006.31     13507252.71
#Sta/Elev= 30
  4700.1  575.46  4717.5  575.71  4735.2  575.34  4742.7  574.48  4750.4  574.32
  4756.9  574.73  4763.6  574.79  4771.1  573.92  4785.3  573.45  4799.5  573.19
  4820.4  573.27  4834.6  572.81  4882.9  572.10  4903.0  572.26  4943.0  571.96
  4983.0  572.29  5001.0  571.46  5001.2  570.96  5004.7  570.96  5005.0  571.46
  5013.0  572.48  5053.0  572.78  5103.0  574.01  5173.0  576.36  5192.9  577.25
  5197.9  577.22  5213.1  578.07  5263.1  579.82  5293.1  581.23  5335.4  582.56
#Mann=5,-1,0
  4700.1    0.05       0  4717.5    0.08       0  4750.4    0.05       0
  5001.0    0.03       0  5005.0    0.05       0
Bank Sta=5001,5005
Exp/Cntr=0.3,0.1

Type RM Length L Ch R = 1,1661,241,241,241
BEGIN DESCRIPTION:
UNT 015 in BCW 2.0
END DESCRIPTION:
XS GIS Cut Line= 3
      1964175.56     13507977.51      1964347.02     13507868.99
      1964431.65     13507335.18
#Sta/Elev= 30
  4539.0  575.76  4569.7  575.05  4606.3  574.41  4612.2  575.10  4656.7  575.29
  4663.9  575.22  4669.8  574.19  4679.2  573.93  4685.1  574.55  4700.4  574.68
  4721.6  573.63  4734.1  573.60  4806.7  573.10  4857.3  571.93  4885.6  571.78
  4918.1  570.72  4968.7  570.57  4989.0  571.06  4999.1  570.16  5007.2  570.15
  5007.5  569.65  5011.0  569.65  5011.2  570.15  5015.3  570.72  5049.7  570.86
  5100.3  572.19  5161.1  575.39  5191.5  576.21  5242.1  578.14  5282.4  580.40
#Mann=5,-1,0
  4539.0     0.1       0  4569.7    0.08       0  4734.1    0.05       0
  5007.2    0.03       0  5011.2    0.05       0
Bank Sta=5007.2,5011.2
Exp/Cntr=0.3,0.1

Type RM Length L Ch R = 1,1420,202,202,202
BEGIN DESCRIPTION:
UNT 015 in BCW 3.0
END DESCRIPTION:
XS GIS Cut Line= 3
      1964594.42     13508062.13      1964630.51     13507594.43
      1964699.97     13507051.85
#Sta/Elev= 30
  4572.9  573.78  4600.1  573.67  4610.1  574.40  4640.2  574.36  4645.3  573.17
  4650.3  572.93  4670.3  574.08  4680.3  573.51  4720.5  573.63  4820.8  570.91
  4880.9  570.09  4931.1  570.38  4951.2  569.81  4971.2  569.99  4981.2  570.72
  4999.3  569.43  4999.5  568.93  5003.0  568.93  5003.3  569.43  5039.2  571.12
  5122.1  573.68  5162.4  574.79  5196.6  575.04  5263.2  577.74  5350.9  579.59
  5356.0  579.22  5430.7  580.74  5435.7  580.44  5510.4  580.90  5589.0  580.65
#Mann=5,-1,0
  4572.9     0.1       0  4610.1    0.08       0  4720.5    0.05       0
  4999.3    0.03       0  5003.3    0.05       0
Bank Sta=4999.3,5003.3
Exp/Cntr=0.3,0.1

Type RM Length L Ch R = 1,1218,27,27,27
BEGIN DESCRIPTION:
Mapping XS d33a03bc
END DESCRIPTION:
XS GIS Cut Line= 4
      1964615.93     13507999.26      1964768.27     13507775.31
      1964807.33     13507581.30      1964774.78     13507261.01
#Sta/Elev= 30
  4512.6  573.74  4529.8  573.11  4536.8  574.55  4557.7  573.41  4602.9  573.02
  4608.6  572.94  4614.6  573.67  4623.5  572.79  4629.6  573.22  4638.5  572.22
  4695.4  571.39  4731.3  571.10  4752.3  571.66  4786.2  570.62  4795.6  569.64
  4804.2  569.58  4824.6  569.91  4926.6  569.26  4943.0  569.82  4948.1  569.44
  4981.4  570.69  4995.7  568.79  4996.0  568.29  4999.5  568.29  4999.7  568.79
  5017.8  570.19  5078.2  571.02  5247.9  574.75  5259.1  575.34  5303.3  575.97
#Mann=4,-1,0
  4512.6    0.08       0  4602.9    0.05       0  4995.7    0.03       0
  4999.7    0.05       0
Bank Sta=4995.7,4999.7
Exp/Cntr=0.3,0.1

Type RM Length L Ch R = 1,1191,32,32,32
BEGIN DESCRIPTION:
Mapping XS 30372f50
END DESCRIPTION:
XS GIS Cut Line= 4
      1964621.12     13508008.41      1964772.18     13507802.65
      1964828.17     13507591.71      1964806.04     13507229.89
#Sta/Elev= 30
  4479.3  574.13  4498.2  572.85  4520.7  573.87  4548.4  572.85  4580.5  573.96
  4598.5  574.80  4607.0  573.27  4620.0  572.26  4657.1  571.90  4663.3  573.00
  4678.0  571.42  4684.2  573.10  4692.7  572.23  4698.9  573.21  4732.7  572.11
  4761.5  570.04  4766.7  571.30  4801.7  569.72  4806.9  571.49  4841.9  569.91
  4847.1  571.68  4876.9  570.87  4882.1  571.77  4917.1  571.10  4939.0  571.86
  4997.6  568.43  4997.8  567.93  5001.6  568.43  5029.7  570.48  5315.3  575.40
#Mann=4,-1,0
  4479.3    0.08       0  4580.5    0.05       0  4997.6    0.03       0
  5001.6    0.05       0
Bank Sta=4997.6,5001.6
Exp/Cntr=0.3,0.1

Type RM Length L Ch R = 1,1159,277,277,277
BEGIN DESCRIPTION:
Mapping XS 62e56931
END DESCRIPTION:
XS GIS Cut Line= 4
      1964631.57     13508008.36      1964809.94     13507792.23
      1964855.51     13507568.28      1964826.86     13507255.76
#Sta/Elev= 30
  4448.4  573.98  4466.9  572.60  4474.8  573.73  4509.9  572.84  4538.6  573.98
  4545.1  573.23  4550.9  574.09  4553.0  574.40  4559.4  572.65  4581.6  572.73
  4588.1  573.56  4645.5  573.38  4652.0  572.10  4695.0  571.64  4709.3  570.93
  4715.8  569.64  4775.4  567.48  4778.5  566.16  4778.8  565.66  4782.5  566.16
  4826.0  567.92  4831.1  566.36  4876.6  567.85  4881.7  566.58  4956.3  570.20
  4990.6  569.31  5000.6  567.57  5010.7  568.21  5021.6  570.22  5271.0  574.28
#Mann=4,-1,0
  4448.4    0.08       0  4550.9    0.05       0  4778.5    0.03       0
  4782.5    0.05       0
Bank Sta=4778.5,4782.5
Exp/Cntr=0.3,0.1

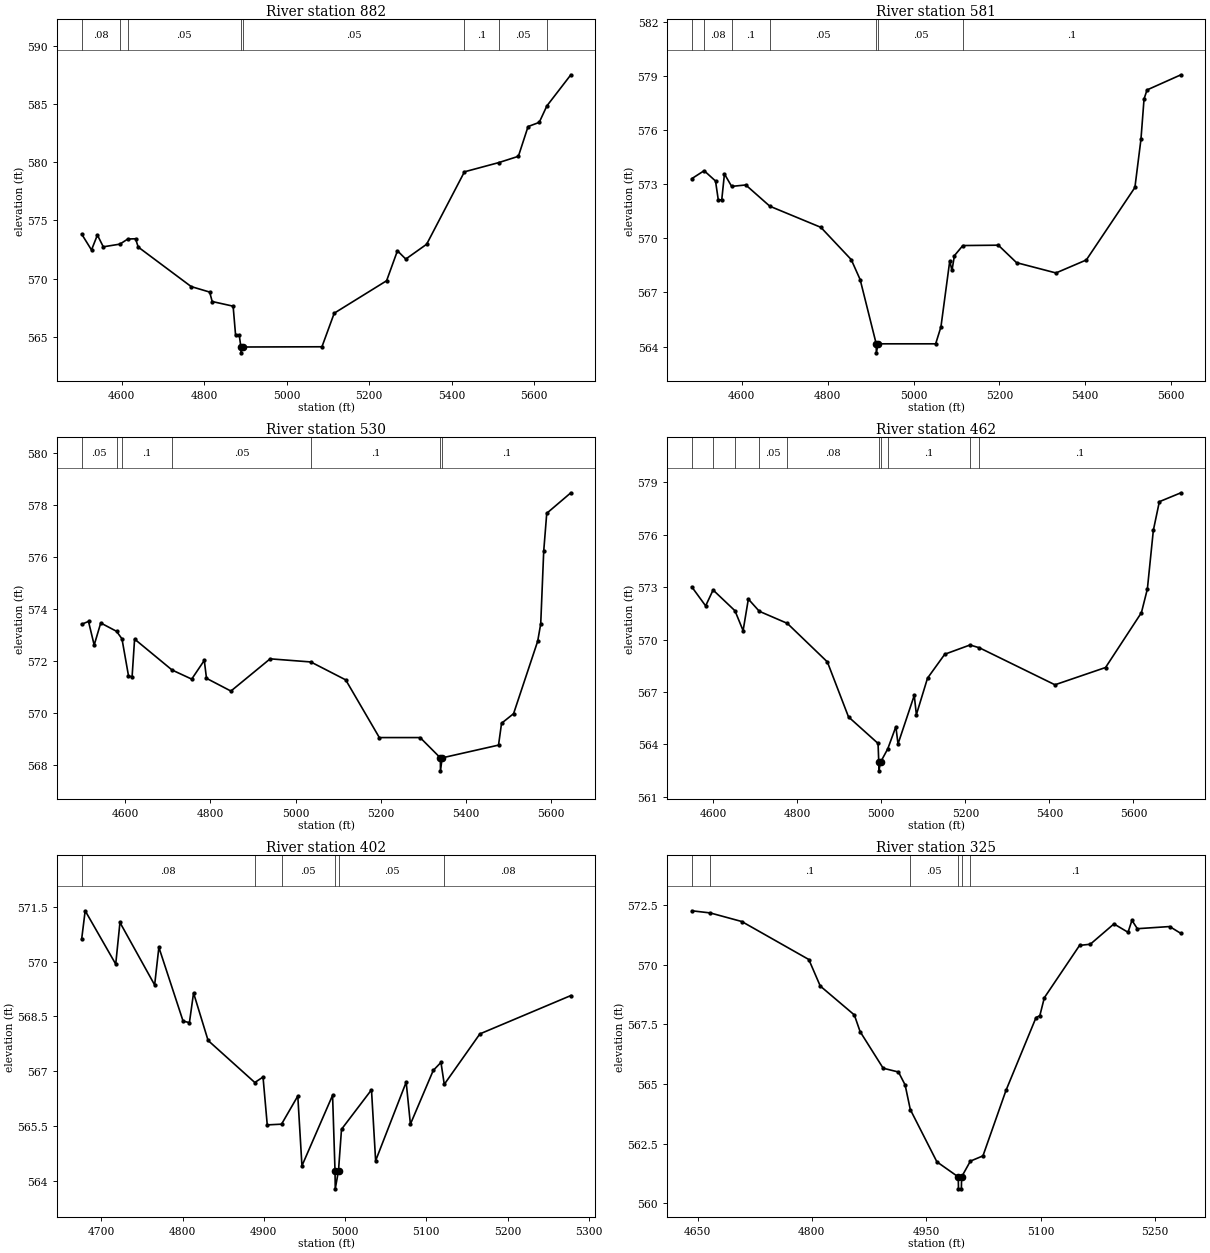
Type RM Length L Ch R = 1,882,301,301,301
BEGIN DESCRIPTION:
UNT 015 in BCW 6.0
END DESCRIPTION:
XS GIS Cut Line= 4
      1964655.19     13508018.73      1964781.05     13507866.82
      1965228.97     13507561.27      1965670.81     13507494.12
#Sta/Elev= 30
  4502.9  573.83  4526.7  572.47  4541.0  573.75  4555.3  572.74  4595.5  572.97
  4614.8  573.41  4633.5  573.43  4640.0  572.72  4768.5  569.33  4813.3  568.86
  4819.4  568.05  4870.2  567.65  4876.2  565.14  4885.1  565.15  4889.0  564.15
  4889.3  563.65  4893.3  564.15  5085.6  564.17  5115.4  567.05  5242.4  569.83
  5268.7  572.40  5288.9  571.69  5339.5  572.96  5431.2  579.17  5514.4  579.96
  5562.0  580.50  5585.5  583.05  5612.6  583.41  5631.1  584.82  5689.3  587.49
#Mann=8,-1,0
  4502.9    0.08       0  4595.5     0.1       0  4614.8    0.05       0
  4889.0   0.033       0  4893.3    0.05       0  5431.2     0.1       0
  5514.4    0.05       0  5631.1    0.08       0
Bank Sta=4889,4893.3
Exp/Cntr=0.3,0.1

Type RM Length L Ch R = 1,581,51,51,51
BEGIN DESCRIPTION:
UNT 015 in BCW 5.0
END DESCRIPTION:
XS GIS Cut Line= 4
      1964639.99     13508046.95      1964824.45     13507901.54
      1965271.50     13508038.26      1965577.47     13507725.79
#Sta/Elev= 30
  4483.3  573.31  4512.1  573.75  4538.6  573.18  4545.0  572.14  4553.1  572.13
  4559.4  573.57  4576.2  572.88  4609.1  572.96  4665.2  571.78  4784.0  570.61
  4854.8  568.82  4875.6  567.71  4913.0  564.15  4913.3  563.65  4917.3  564.15
  5051.5  564.15  5063.8  565.09  5084.3  568.74  5089.5  568.22  5095.2  569.04
  5114.8  569.60  5197.5  569.62  5240.0  568.65  5331.8  568.08  5402.5  568.80
  5515.7  572.82  5529.8  575.49  5537.0  577.73  5544.0  578.23  5623.0  579.07
#Mann=7,-1,0
  4483.3    0.05       0  4512.1    0.08       0  4576.2     0.1       0
  4665.2    0.05       0  4913.0    0.03       0  4917.3    0.05       0
  5114.8     0.1       0
Bank Sta=4913,4917.3
Exp/Cntr=0.3,0.1

Type RM Length L Ch R = 1,530,68,68,68
BEGIN DESCRIPTION:
UNT 015 in BCW 4.0
END DESCRIPTION:
XS GIS Cut Line= 4
      1964631.31     13508072.99      1964815.77     13507960.14
      1965282.35     13508086.01      1965600.29     13507770.24
#Sta/Elev= 30
  4498.4  573.40  4514.4  573.51  4527.7  572.60  4543.1  573.45  4580.1  573.13
  4592.9  572.84  4608.2  571.42  4616.6  571.37  4622.5  572.83  4710.4  571.64
  4756.5  571.29  4786.0  572.01  4791.2  571.32  4848.5  570.83  4940.5  572.07
  5035.9  571.95  5117.8  571.26  5196.7  569.04  5292.4  569.04  5339.8  568.26
  5340.1  567.76  5344.1  568.26  5476.3  568.75  5483.4  569.59  5511.6  569.96
  5568.2  572.75  5575.3  573.42  5582.3  576.21  5589.4  577.67  5646.0  578.46
#Mann=7,-1,0
  4498.4    0.05       0  4580.1    0.08       0  4592.9     0.1       0
  4710.4    0.05       0  5035.9     0.1       0  5339.8    0.03       0
  5344.1     0.1       0
Bank Sta=5339.8,5344.1
Exp/Cntr=0.3,0.1

Type RM Length L Ch R = 1,462,60,60,60
BEGIN DESCRIPTION:
Mapping XS a0957019
END DESCRIPTION:
XS GIS Cut Line= 5
      1964665.41     13508077.39      1964798.22     13508012.29
      1965087.28     13508102.13      1965311.24     13508151.61
      1965632.66     13507789.85
#Sta/Elev= 30
  4549.1  573.02  4582.1  571.93  4599.8  572.84  4651.9  571.65  4671.2  570.51
  4683.7  572.32  4709.8  571.62  4776.3  570.93  4871.7  568.72  4922.0  565.57
  4992.3  564.05  4994.0  562.98  4994.3  562.48  4998.3  562.98  5015.4  563.74
  5034.7  565.01  5039.8  564.02  5078.4  566.80  5083.5  565.70  5110.0  567.79
  5151.0  569.16  5211.1  569.69  5233.4  569.53  5413.2  567.41  5533.6  568.40
  5618.9  571.54  5633.1  572.90  5647.3  576.26  5661.6  577.90  5713.0  578.41
#Mann=10,-1,0
  4549.1    0.05       0  4599.8    0.08       0  4651.9     0.1       0
  4709.8    0.05       0  4776.3    0.08       0  4994.0    0.07       0
  4998.3    0.08       0  5015.4     0.1       0  5211.1    0.08       0
  5233.4     0.1       0
Bank Sta=4994,4998.3
Exp/Cntr=0.3,0.1

Type RM Length L Ch R = 1,402,77,77,77
BEGIN DESCRIPTION:
Mapping XS 5619a1e9
END DESCRIPTION:
XS GIS Cut Line= 2
      1964763.40     13508089.58      1965350.08     13508224.97
#Sta/Elev= 30
  4675.8  570.62  4680.1  571.39  4717.7  569.93  4722.9  571.07  4765.6  569.36
  4770.8  570.39  4800.6  568.37  4808.4  568.33  4813.5  569.14  4831.4  567.84
  4888.9  566.69  4899.0  566.84  4904.2  565.53  4921.8  565.55  4941.8  566.32
  4946.9  564.41  4984.6  566.34  4987.6  564.28  4987.9  563.78  4991.9  564.28
  4995.6  565.41  5032.5  566.49  5037.6  564.55  5075.2  566.70  5080.4  565.55
  5108.5  567.02  5118.0  567.24  5122.1  566.64  5165.9  568.02  5277.9  569.07
#Mann=6,-1,0
  4675.8    0.08       0  4888.9     0.1       0  4921.8    0.05       0
  4987.6    0.04       0  4991.9    0.05       0  5122.1    0.08       0
Bank Sta=4987.6,4991.9
Exp/Cntr=0.3,0.1

Type RM Length L Ch R = 1,325,112,112,112
BEGIN DESCRIPTION:
Mapping XS cefdb01d
END DESCRIPTION:
XS GIS Cut Line= 4
      1964740.87     13508119.12      1964924.86     13508221.53
      1965221.73     13508256.25      1965350.96     13508283.82
#Sta/Elev= 30
  4642.5  572.25  4666.7  572.16  4708.1  571.80  4796.0  570.21  4811.0  569.10
  4855.7  567.89  4863.3  567.19  4893.5  565.66  4913.6  565.50  4922.3  564.96
  4929.1  563.93  4964.0  561.74  4992.0  561.11  4992.3  560.61  4996.1  560.61
  4996.4  561.11  5007.9  561.77  5024.4  561.99  5054.6  564.73  5094.0  567.78
  5099.0  567.86  5104.9  568.61  5151.1  570.80  5165.2  570.85  5196.2  571.70
  5214.7  571.35  5219.8  571.85  5226.9  571.50  5269.3  571.59  5284.1  571.30
#Mann=6,-1,0
  4642.5    0.08       0  4666.7     0.1       0  4929.1    0.05       0
  4992.0    0.04       0  4996.4    0.05       0  5007.9     0.1       0
Bank Sta=4992,4996.4
Exp/Cntr=0.3,0.1

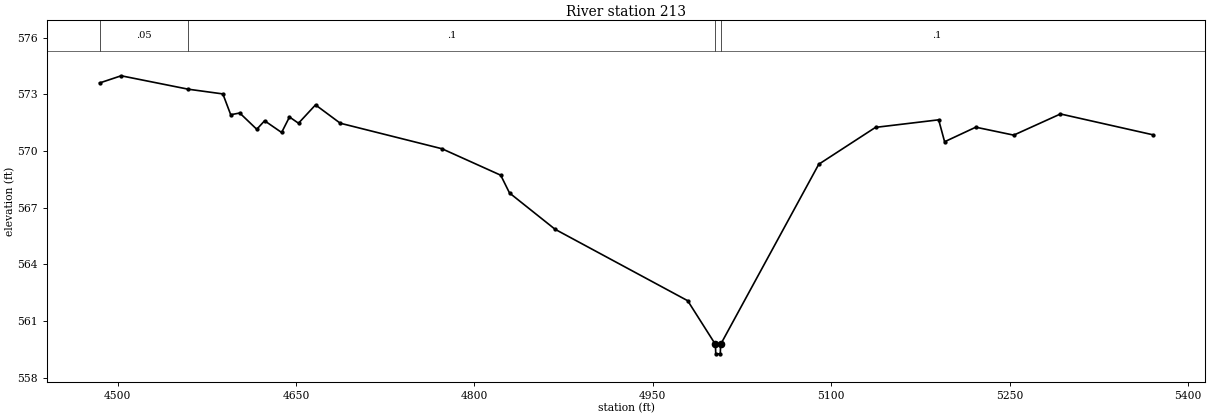
Type RM Length L Ch R = 1,213,0,0,0
BEGIN DESCRIPTION:
UNT 015 in BCW 7.0
END DESCRIPTION:
XS GIS Cut Line= 4
      1964624.78     13508079.47      1964914.44     13508330.90
      1965148.82     13508346.53      1965411.34     13508298.17
#Sta/Elev= 30
  4484.9  573.60  4503.0  573.98  4559.4  573.27  4588.5  573.02  4595.1  571.92
  4602.7  572.01  4617.0  571.15  4623.6  571.60  4637.9  570.98  4644.5  571.80
  4652.1  571.47  4666.4  572.44  4687.2  571.47  4772.7  570.12  4822.1  568.72
  4829.5  567.78  4867.8  565.86  4979.3  562.08  5002.6  559.77  5002.9  559.27
  5006.7  559.27  5007.0  559.77  5089.5  569.30  5137.2  571.25  5190.3  571.65
  5195.3  570.49  5221.5  571.26  5253.4  570.84  5292.7  571.96  5370.3  570.86
#Mann=4,-1,0
  4484.9    0.05       0  4559.4     0.1       0  5002.6    0.07       0
  5007.0     0.1       0
Bank Sta=5002.6,5007
Exp/Cntr=0.3,0.1

Chan Stop Cuts=-1