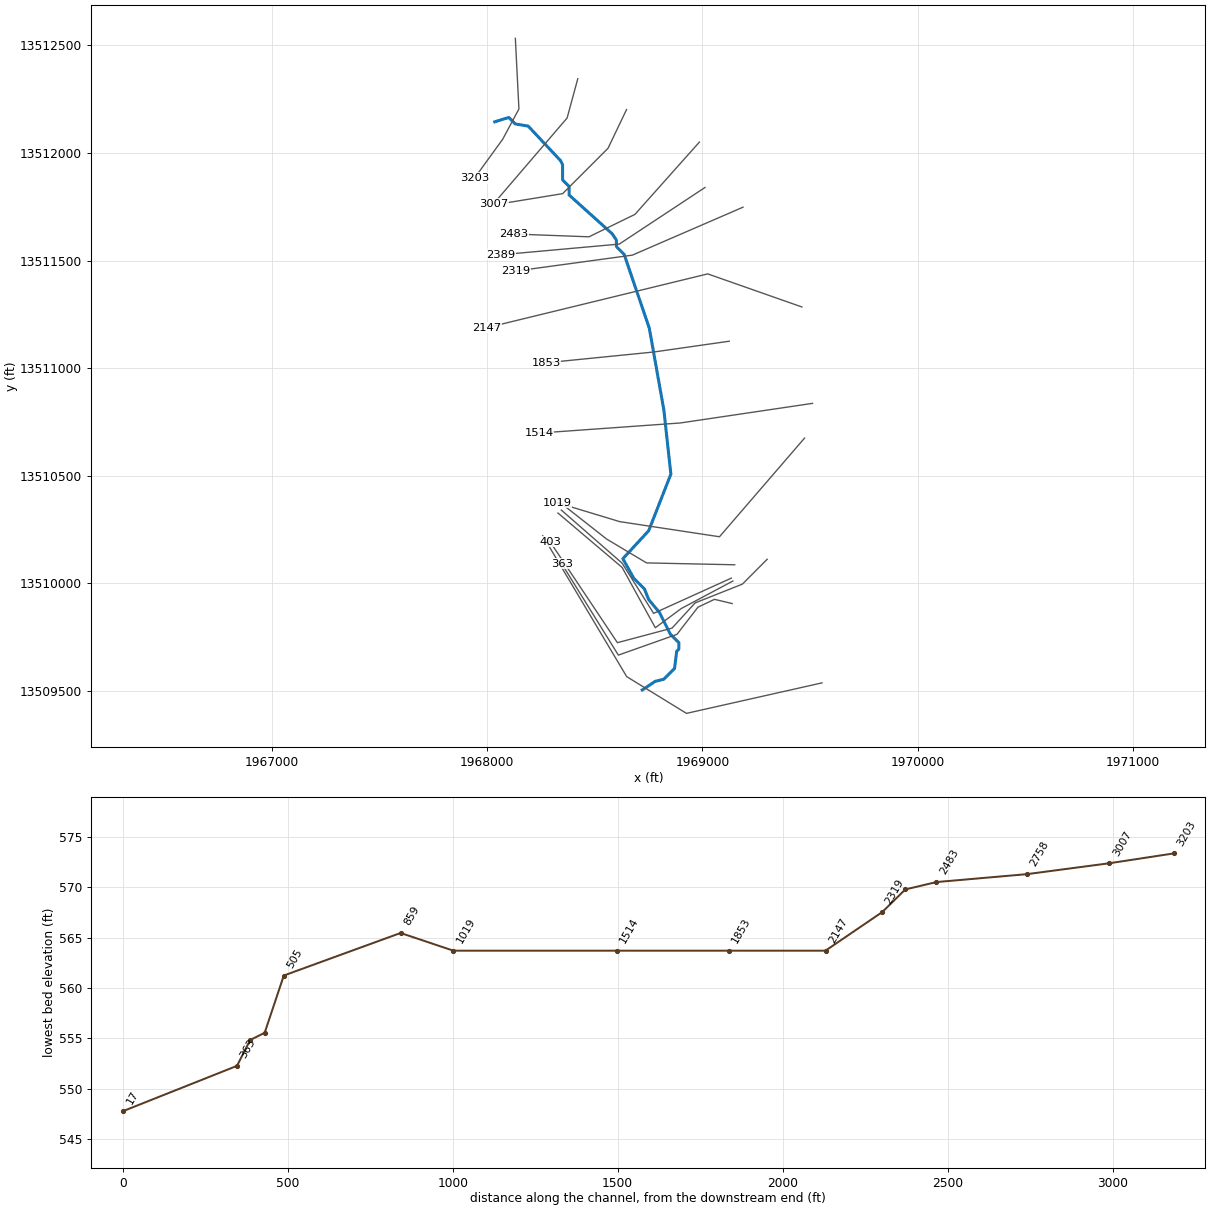
--- UNT 016 in BCW.prj (project) ---

Proj Title=UNT 016 in BCW Base Level Engineering
Current Plan=p01
Default Exp/Contr=0.3,0.1
English Units
Geom File=g01
Flow File=f01
Plan File=p01
BEGIN DESCRIPTION:
UNT 016 in BCW
END DESCRIPTION:

--- UNT 016 in BCW.p01 (plan) ---

Plan Title=Multiple Run
Short Identifier=Multiple
Geom File=g01
Flow File=f01
Subcritical Flow
K Sum by GR= 0
Std Step Tol= 0.01
Critical Tol= 0.01
Num of Std Step Trials= 20
Max Error Tol= 0.3
Flow Tol Ratio= 0.001
Split Flow NTrial= 30
Split Flow Tol= 0.02
Split Flow Ratio= 0.02
Log Output Level= 0
Friction Slope Method= 1
Unsteady Friction Slope Method= 2
Unsteady Bridges Friction Slope Method= 1
Parabolic Critical Depth
Global Vel Dist=  1 , 1 , 1
Global Log Level= 0
CheckData=True
Encroach Param= -1, 0, 0, 0
BEGIN DESCRIPTION:
Multiple Run
END DESCRIPTION:

--- UNT 016 in BCW.f01 (steady flow) ---

Flow Title=Multiple
Number of Profiles=7
Profile Names=10-year,25-year,50-year,1pct_min,100-year,1pct_plu,500-year
River Rch & RM= UNT 016 in BCW,Reach-1,3203
     104     140     169     102     204     406     302
River Rch & RM= UNT 016 in BCW,Reach-1,3007
     170     235     288     177     354     706     542
River Rch & RM= UNT 016 in BCW,Reach-1,1514
     201     280     345     213     426     850     658
River Rch & RM= UNT 016 in BCW,Reach-1,17
     909    1332    1701    1081    2156    4303    3532
Boundary for River Rch & Prof#=UNT 016 in BCW,Reach-1,1
Up Type=0
Dn Type=3
Dn Slope=0.005
Boundary for River Rch & Prof#=UNT 016 in BCW,Reach-1,2
Up Type=0
Dn Type=3
Dn Slope=0.005
Boundary for River Rch & Prof#=UNT 016 in BCW,Reach-1,3
Up Type=0
Dn Type=3
Dn Slope=0.005
Boundary for River Rch & Prof#=UNT 016 in BCW,Reach-1,4
Up Type=0
Dn Type=3
Dn Slope=0.005
Boundary for River Rch & Prof#=UNT 016 in BCW,Reach-1,5
Up Type=0
Dn Type=3
Dn Slope=0.005
Boundary for River Rch & Prof#=UNT 016 in BCW,Reach-1,6
Up Type=0
Dn Type=3
Dn Slope=0.005
Boundary for River Rch & Prof#=UNT 016 in BCW,Reach-1,7
Up Type=0
Dn Type=3
Dn Slope=0.005

--- UNT 016 in BCW.g01 (geometry) ---

Geom Title=Existing Conditions

River Reach=UNT 016 in BCW,Reach-1
Reach XY= 30
      1968035.71     13512144.54      1968100.80     13512164.54
      1968130.80     13512134.54      1968190.80     13512124.54
      1968340.80     13511964.54      1968350.80     13511944.54
      1968350.80     13511874.54      1968380.80     13511844.54
      1968380.80     13511804.54      1968580.80     13511624.54
      1968600.80     13511594.54      1968600.80     13511564.54
      1968636.71     13511528.63      1968753.53     13511185.81
      1968821.24     13510805.60      1968853.79     13510507.43
      1968750.80     13510244.54      1968630.80     13510114.54
      1968680.80     13510024.54      1968730.80     13509974.54
      1968750.80     13509924.54      1968800.80     13509864.54
      1968850.80     13509764.54      1968890.80     13509724.54
      1968890.80     13509694.54      1968880.80     13509684.54
      1968870.80     13509604.54      1968820.80     13509554.54
      1968780.80     13509544.54      1968720.80     13509504.54

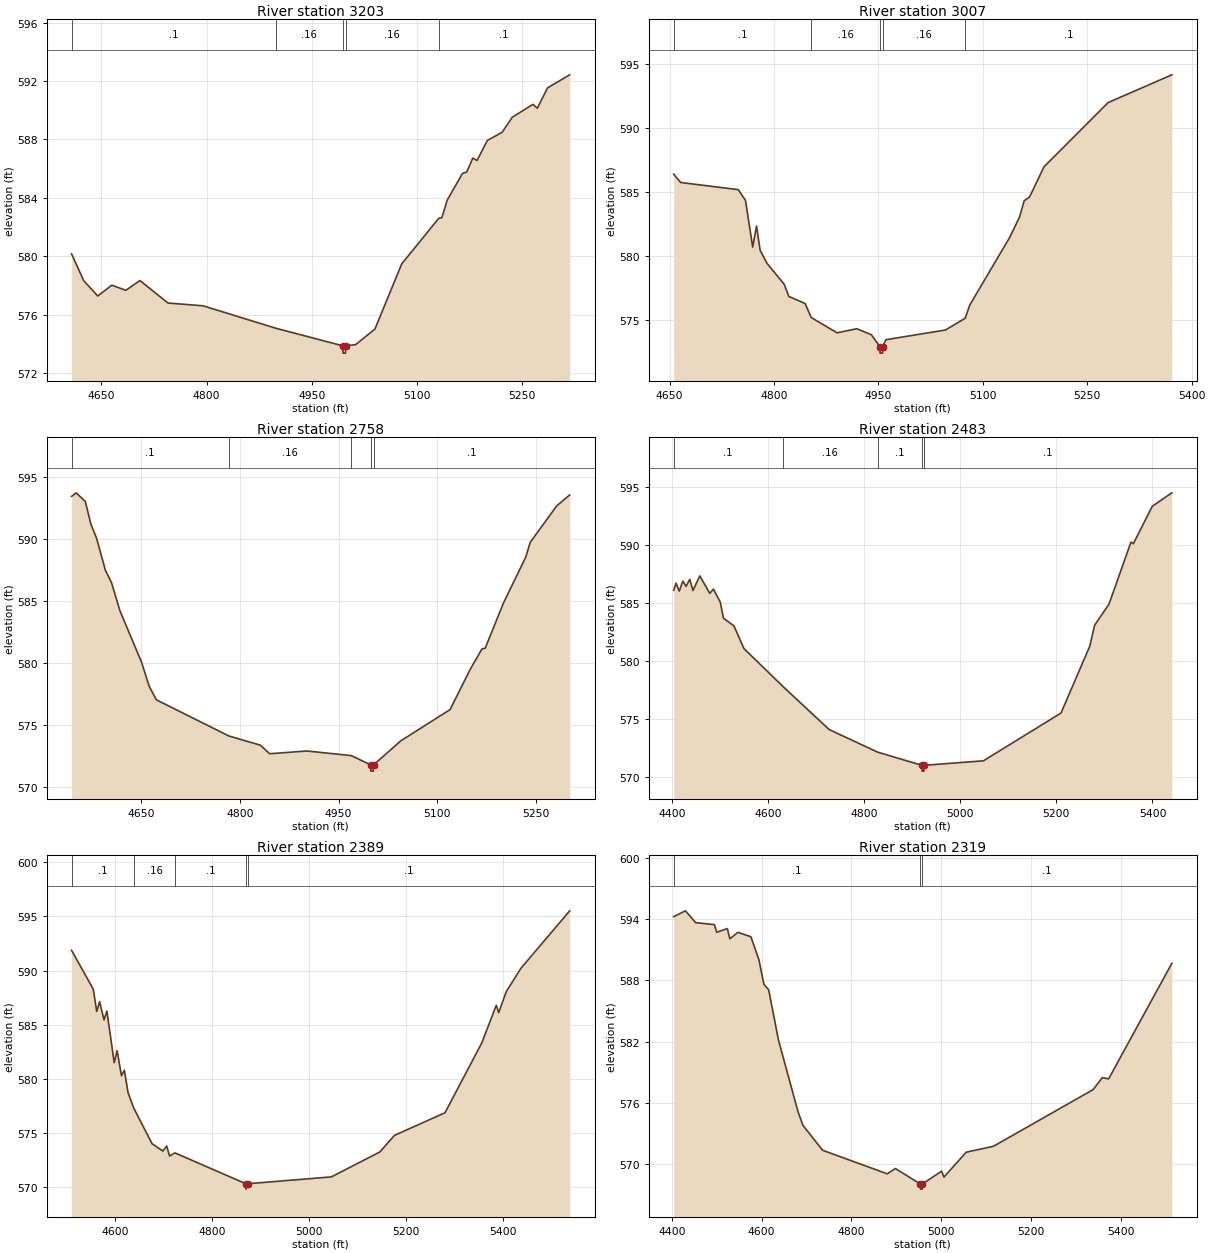
Type RM Length L Ch R = 1,3203,196,196,196
BEGIN DESCRIPTION:
UNT 016 in BCW 6.0
END DESCRIPTION:
XS GIS Cut Line= 4
      1968131.25     13512532.28      1968147.82     13512203.88
      1968072.30     13512063.26      1967942.12     13511883.61
#Sta/Elev= 30
  4607.4  580.17  4624.7  578.33  4644.7  577.28  4664.8  578.02  4684.8  577.67
  4704.8  578.34  4744.9  576.80  4794.9  576.61  4898.2  575.08  4994.2  573.87
  4994.5  573.37  4998.0  573.37  4998.2  573.87  5012.4  573.95  5040.0  575.02
  5078.2  579.48  5131.0  582.60  5135.4  582.64  5143.1  583.85  5164.8  585.67
  5170.9  585.77  5179.5  586.72  5185.6  586.56  5200.3  587.93  5221.2  588.48
  5235.9  589.52  5265.3  590.40  5271.5  590.13  5286.2  591.53  5317.7  592.42
#Mann=5,-1,0
  4607.4     0.1       0  4898.2    0.16       0  4994.2    0.07       0
  4998.2    0.16       0  5131.0     0.1       0
Bank Sta=4994.2,4998.2
Exp/Cntr=0.3,0.1

Type RM Length L Ch R = 1,3007,249,249,249
BEGIN DESCRIPTION:
Mapping XS fc9ba505
END DESCRIPTION:
XS GIS Cut Line= 3
      1968421.27     13512344.55      1968371.78     13512162.22
      1968029.03     13511762.34
#Sta/Elev= 30
  4655.9  586.40  4665.9  585.75  4748.7  585.19  4759.1  584.34  4769.4  580.69
  4774.9  582.34  4780.1  580.44  4790.1  579.41  4814.8  577.77  4821.2  576.83
  4844.8  576.27  4853.4  575.18  4890.5  573.98  4919.0  574.30  4939.9  573.83
  4952.1  572.89  4952.3  572.39  4955.9  572.39  4956.2  572.89  4960.7  573.44
  5046.3  574.20  5074.6  575.12  5081.4  576.17  5138.5  581.44  5152.8  583.05
  5159.4  584.32  5167.1  584.61  5187.9  586.98  5280.1  592.01  5371.5  594.18
#Mann=5,-1,0
  4655.9     0.1       0  4853.4    0.16       0  4952.1    0.07       0
  4956.2    0.16       0  5074.6     0.1       0
Bank Sta=4952.1,4956.2
Exp/Cntr=0.3,0.1

Type RM Length L Ch R = 1,2758,275,275,275
BEGIN DESCRIPTION:
Mapping XS c4b1e5d7
END DESCRIPTION:
XS GIS Cut Line= 4
      1968647.83     13512201.30      1968561.89     13512021.59
      1968350.95     13511810.66      1968095.74     13511768.99
#Sta/Elev= 30
  4544.7  593.42  4551.7  593.71  4565.6  593.01  4573.9  591.21  4582.7  590.05
  4596.0  587.48  4605.4  586.47  4618.2  584.20  4650.7  580.11  4662.5  578.14
  4673.4  577.05  4783.4  574.14  4831.2  573.40  4845.4  572.71  4901.9  572.93
  4969.2  572.56  4998.9  571.81  4999.1  571.31  5002.7  571.31  5003.0  571.81
  5044.7  573.76  5119.2  576.26  5149.6  579.48  5167.6  581.14  5172.6  581.21
  5200.2  584.83  5234.1  588.54  5240.8  589.72  5281.3  592.67  5300.8  593.54
#Mann=5,-1,0
  4544.7     0.1       0  4783.4    0.16       0  4969.2     0.1       0
  4998.9    0.07       0  5003.0     0.1       0
Bank Sta=4998.9,5003
Exp/Cntr=0.3,0.1

Type RM Length L Ch R = 1,2483,94,94,94
BEGIN DESCRIPTION:
Mapping XS 67cd1347
END DESCRIPTION:
XS GIS Cut Line= 4
      1968986.36     13512050.23      1968686.89     13511714.30
      1968473.34     13511610.13      1968124.42     13511623.15
#Sta/Elev= 30
  4403.5  586.13  4408.4  586.75  4415.1  586.05  4422.6  586.92  4429.3  586.47
  4436.9  587.08  4443.6  586.11  4457.8  587.37  4478.7  585.86  4486.2  586.23
  4500.4  585.11  4507.1  583.72  4528.8  583.06  4549.7  581.10  4630.3  577.85
  4727.0  574.11  4828.0  572.16  4920.3  571.02  4920.6  570.52  4924.2  570.52
  4924.5  571.02  5048.1  571.41  5209.6  575.53  5269.6  581.31  5279.6  583.11
  5309.6  584.94  5355.2  590.28  5360.2  590.15  5399.7  593.38  5440.3  594.54
#Mann=5,-1,0
  4403.5     0.1       0  4630.3    0.16       0  4828.0     0.1       0
  4920.3    0.07       0  4924.5     0.1       0
Bank Sta=4920.3,4924.5
Exp/Cntr=0.3,0.1

Type RM Length L Ch R = 1,2389,70,70,70
BEGIN DESCRIPTION:
Mapping XS 47e4105d
END DESCRIPTION:
XS GIS Cut Line= 3
      1969012.37     13511839.28      1968613.97     13511576.28
      1968064.47     13511526.80
#Sta/Elev= 30
  4509.4  591.87  4554.2  588.28  4561.4  586.21  4567.3  587.12  4576.4  585.44
  4582.4  586.25  4597.5  581.48  4603.5  582.59  4612.5  580.27  4618.5  580.78
  4626.1  578.71  4638.0  577.27  4675.7  573.99  4698.0  573.31  4705.9  573.78
  4711.8  572.85  4723.0  573.14  4869.3  570.29  4869.6  569.79  4873.5  570.29
  5046.0  570.92  5146.4  573.23  5176.5  574.76  5280.9  576.85  5357.2  583.34
  5386.8  586.79  5391.8  586.11  5407.4  588.04  5437.6  590.20  5538.5  595.52
#Mann=5,-1,0
  4509.4     0.1       0  4638.0    0.16       0  4723.0     0.1       0
  4869.3    0.07       0  4873.5     0.1       0
Bank Sta=4869.3,4873.5
Exp/Cntr=0.3,0.1

Type RM Length L Ch R = 1,2319,172,172,172
BEGIN DESCRIPTION:
UNT 016 in BCW 5.0
END DESCRIPTION:
XS GIS Cut Line= 3
      1969189.02     13511747.72      1968675.00     13511525.00
      1968131.73     13511450.85
#Sta/Elev= 30
  4404.4  594.25  4430.6  594.82  4453.4  593.66  4494.9  593.47  4500.3  592.72
  4523.8  593.08  4529.3  592.08  4547.3  592.71  4576.2  592.28  4594.1  590.02
  4605.1  587.62  4615.8  587.08  4637.6  582.15  4681.2  575.11  4692.1  573.79
  4735.7  571.35  4879.7  569.04  4897.7  569.56  4953.5  568.04  4953.8  567.54
  4957.4  567.54  4957.7  568.04  5000.7  569.30  5005.8  568.72  5055.4  571.16
  5116.0  571.74  5338.0  577.30  5358.2  578.47  5372.3  578.35  5512.9  589.67
#Mann=3,-1,0
  4404.4     0.1       0  4953.5    0.07       0  4957.7     0.1       0
Bank Sta=4953.5,4957.7
Exp/Cntr=0.3,0.1

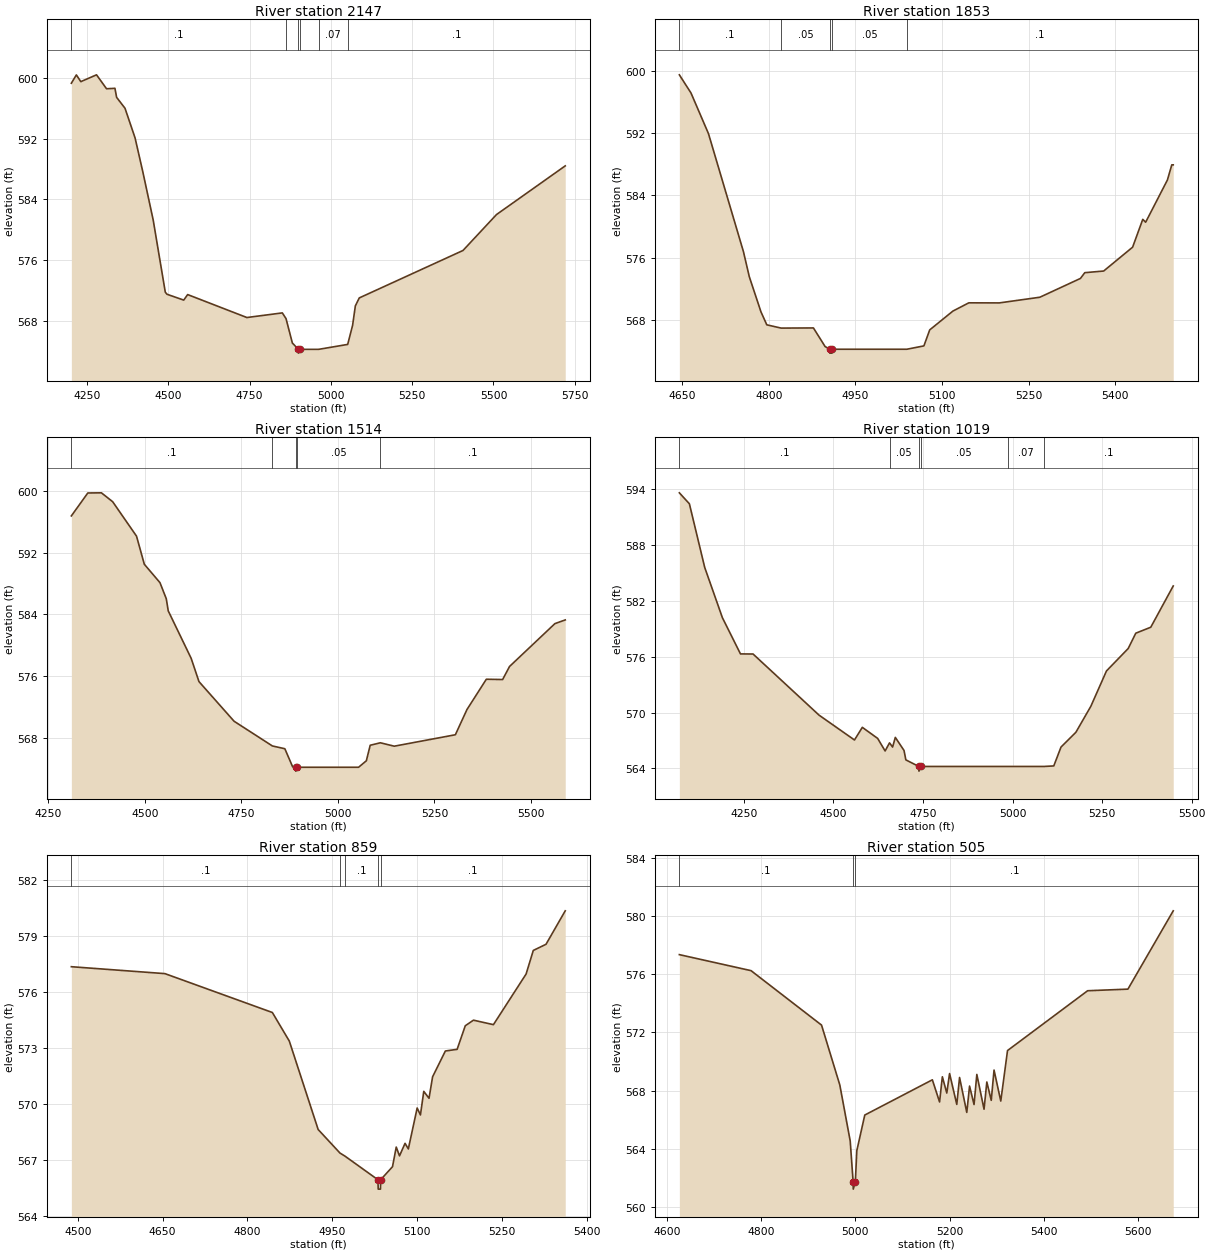
Type RM Length L Ch R = 1,2147,294,294,294
BEGIN DESCRIPTION:
Mapping XS 9033dea0
END DESCRIPTION:
XS GIS Cut Line= 3
      1969462.47     13511284.18      1969024.98     13511437.83
      1967999.47     13511187.96
#Sta/Elev= 30
  4201.5  599.33  4216.9  600.43  4230.6  599.54  4278.9  600.44  4309.8  598.60
  4335.5  598.66  4340.8  597.46  4366.5  596.03  4397.5  592.11  4421.4  587.62
  4453.2  581.28  4490.5  571.74  4495.8  571.47  4547.2  570.70  4559.2  571.43
  4741.4  568.40  4850.4  569.01  4861.8  568.26  4881.3  565.04  4899.8  564.20
  4900.1  563.70  4904.0  564.20  4962.3  564.20  5051.5  564.85  5066.6  567.37
  5075.1  569.94  5087.2  570.99  5406.2  577.25  5509.2  581.99  5720.7  588.42
#Mann=6,-1,0
  4201.5     0.1       0  4861.8    0.05       0  4899.8    0.07       0
  4904.0    0.05       0  4962.3    0.07       0  5051.5     0.1       0
Bank Sta=4899.8,4904
Exp/Cntr=0.3,0.1

Type RM Length L Ch R = 1,1853,339,339,339
BEGIN DESCRIPTION:
UNT 016 in BCW 4.0
END DESCRIPTION:
XS GIS Cut Line= 3
      1969125.03     13511125.00      1968775.00     13511075.00
      1968274.98     13511025.00
#Sta/Elev= 30
  4644.7  599.50  4664.9  597.16  4695.2  591.93  4755.8  576.75  4765.9  573.54
  4786.2  569.00  4796.3  567.34  4821.1  566.92  4877.1  566.94  4897.3  564.55
  4905.3  564.20  4905.5  563.70  4909.2  563.70  4909.5  564.20  5039.0  564.20
  5068.6  564.63  5078.7  566.69  5118.9  569.11  5146.5  570.17  5199.3  570.16
  5269.6  570.89  5340.0  573.31  5347.5  574.05  5380.2  574.26  5430.4  577.33
  5448.0  580.91  5453.0  580.54  5490.7  585.97  5498.3  587.92  5500.8  587.92
#Mann=5,-1,0
  4644.7     0.1       0  4821.1    0.05       0  4905.3   0.033       0
  4909.5    0.05       0  5039.0     0.1       0
Bank Sta=4905.3,4909.5
Exp/Cntr=0.3,0.1

Type RM Length L Ch R = 1,1514,495,495,495
BEGIN DESCRIPTION:
UNT 016 in BCW 3.0
END DESCRIPTION:
XS GIS Cut Line= 3
      1969511.98     13510836.27      1968897.37     13510745.12
      1968241.07     13510698.24
#Sta/Elev= 30
  4309.5  596.75  4352.1  599.72  4387.3  599.74  4416.5  598.59  4478.3  594.13
  4498.5  590.49  4539.0  588.11  4555.4  586.02  4560.5  584.45  4619.8  578.31
  4640.1  575.29  4731.0  570.16  4830.2  566.96  4862.5  566.60  4882.7  564.26
  4890.4  564.20  4890.7  563.70  4895.0  564.20  5053.5  564.20  5073.6  565.04
  5083.6  567.05  5109.9  567.37  5145.9  566.93  5304.2  568.41  5334.2  571.67
  5384.4  575.60  5426.6  575.56  5444.5  577.25  5562.0  582.80  5588.8  583.28
#Mann=5,-1,0
  4309.5     0.1       0  4830.2    0.05       0  4890.4   0.033       0
  4895.0    0.05       0  5109.9     0.1       0
Bank Sta=4890.4,4895
Exp/Cntr=0.3,0.1

Type RM Length L Ch R = 1,1019,160,160,160
BEGIN DESCRIPTION:
UNT 016 in BCW 2.0
END DESCRIPTION:
XS GIS Cut Line= 4
      1969475.01     13510675.01      1969079.66     13510216.47
      1968616.12     13510286.79      1968324.97     13510375.01
#Sta/Elev= 30
  4070.1  593.64  4098.1  592.46  4140.9  585.61  4190.3  580.20  4240.7  576.31
  4275.8  576.30  4460.1  569.72  4558.9  567.05  4580.8  568.41  4623.6  567.22
  4644.4  565.87  4656.7  566.74  4665.3  566.29  4672.9  567.33  4697.2  565.92
  4702.3  564.91  4738.6  564.20  4738.9  563.70  4743.3  564.20  4987.6  564.20
  5087.5  564.20  5115.2  564.26  5135.4  566.29  5176.9  567.88  5218.7  570.68
  5262.3  574.48  5322.9  576.89  5344.1  578.54  5385.9  579.18  5448.6  583.62
#Mann=6,-1,0
  4070.1     0.1       0  4656.7    0.05       0  4738.6    0.07       0
  4743.3    0.05       0  4987.6    0.07       0  5087.5     0.1       0
Bank Sta=4738.6,4743.3
Exp/Cntr=0.3,0.1

Type RM Length L Ch R = 1,859,354,354,354
BEGIN DESCRIPTION:
Mapping XS 1cf1466c
END DESCRIPTION:
XS GIS Cut Line= 4
      1969150.44     13510086.29      1968740.76     13510094.97
      1968554.99     13510206.08      1968360.56     13510358.85
#Sta/Elev= 30
  4488.5  577.36  4654.0  576.99  4844.0  574.91  4874.0  573.38  4925.0  568.65
  4963.6  567.39  4972.7  567.22  5030.8  565.96  5031.2  565.46  5035.2  565.46
  5035.5  565.96  5056.5  566.66  5063.1  567.71  5068.9  567.24  5078.7  567.91
  5084.5  567.61  5100.1  569.80  5105.9  569.43  5111.8  570.69  5121.1  570.32
  5127.4  571.47  5150.0  572.85  5170.8  572.94  5185.2  574.20  5199.7  574.50
  5235.0  574.26  5292.8  576.97  5305.5  578.23  5328.0  578.56  5362.0  580.35
#Mann=5,-1,0
  4488.5     0.1       0  4963.6    0.07       0  4972.7     0.1       0
  5030.8    0.07       0  5035.5     0.1       0
Bank Sta=5030.8,5035.5
Exp/Cntr=0.3,0.1

Type RM Length L Ch R = 1,505,58,58,58
BEGIN DESCRIPTION:
Mapping XS 38e0d6c7
END DESCRIPTION:
XS GIS Cut Line= 4
      1969134.97     13510024.38      1968773.64     13509860.54
      1968627.16     13510093.83      1968344.67     13510340.60
#Sta/Elev= 30
  4626.8  577.34  4778.8  576.24  4928.3  572.50  4967.1  568.38  4989.1  564.54
  4995.3  561.73  4995.6  561.23  5000.0  561.73  5003.1  563.87  5020.0  566.32
  5163.3  568.74  5178.6  567.22  5184.5  568.95  5193.9  567.83  5199.8  569.17
  5215.1  567.05  5221.0  568.90  5236.3  566.50  5242.2  568.31  5251.7  567.04
  5257.6  569.11  5272.9  566.72  5278.8  568.59  5288.2  567.33  5294.1  569.41
  5308.4  567.28  5322.7  570.75  5492.6  574.86  5578.0  574.97  5674.1  580.35
#Mann=3,-1,0
  4626.8     0.1       0  4995.3    0.07       0  5000.0     0.1       0
Bank Sta=4995.3,5000
Exp/Cntr=0.3,0.1

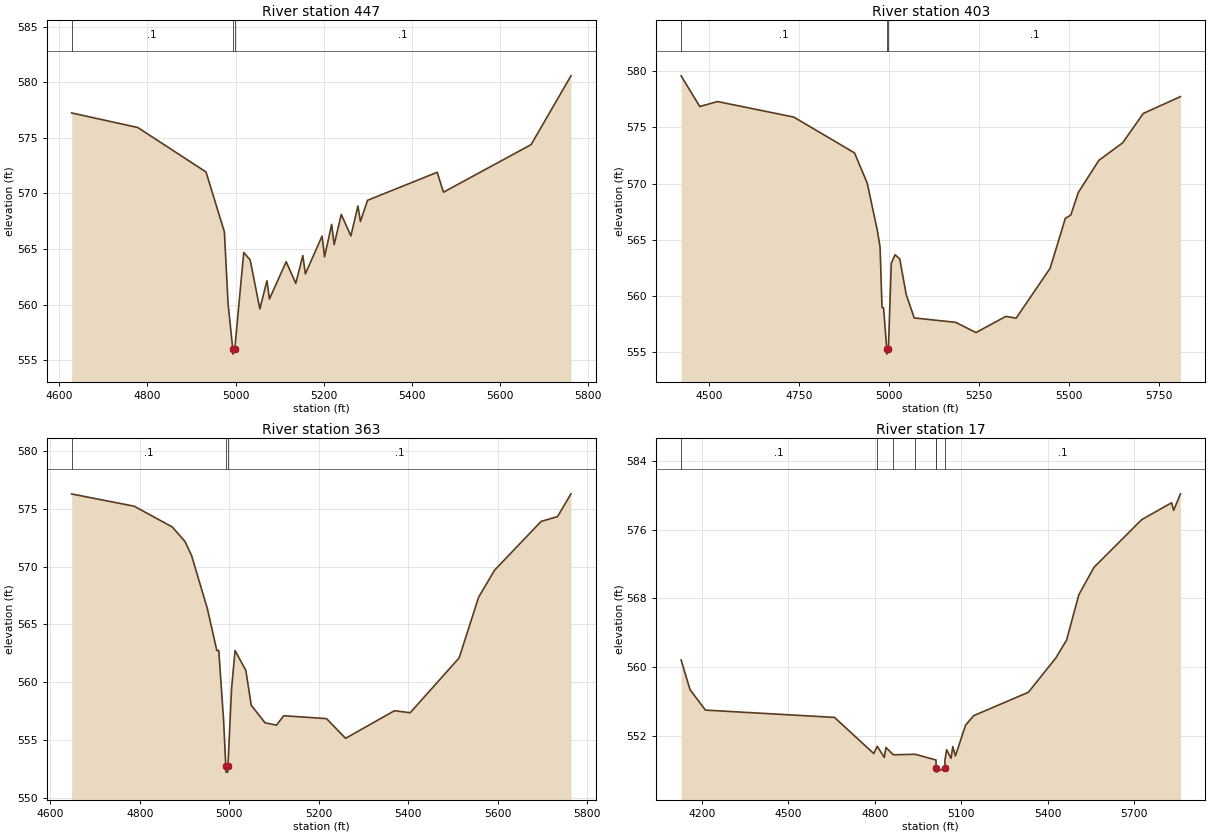
Type RM Length L Ch R = 1,447,44,44,44
BEGIN DESCRIPTION:
Mapping XS 8de43c82
END DESCRIPTION:
XS GIS Cut Line= 5
      1969141.97     13510010.77      1968902.38     13509883.16
      1968781.56     13509793.76      1968627.48     13510073.71
      1968329.02     13510326.75
#Sta/Elev= 30
  4628.3  577.24  4778.3  575.93  4933.1  571.93  4974.8  566.54  4983.2  560.04
  4993.7  556.04  4994.0  555.54  4998.4  556.04  5018.7  564.69  5033.3  564.01
  5055.2  559.61  5071.3  562.14  5077.0  560.50  5114.9  563.85  5136.7  561.91
  5152.7  564.41  5158.5  562.76  5196.3  566.16  5202.0  564.30  5218.1  567.21
  5223.8  565.40  5239.9  568.11  5261.7  566.18  5277.7  568.87  5283.4  567.47
  5299.5  569.38  5457.4  571.90  5471.7  570.11  5670.5  574.39  5760.9  580.58
#Mann=3,-1,0
  4628.3     0.1       0  4993.7    0.07       0  4998.4     0.1       0
Bank Sta=4993.7,4998.4
Exp/Cntr=0.3,0.1

Type RM Length L Ch R = 1,403,40,40,40
BEGIN DESCRIPTION:
Mapping XS d171a442
END DESCRIPTION:
XS GIS Cut Line= 6
      1969301.27     13510111.91      1969186.24     13509996.44
      1968966.45     13509909.12      1968859.42     13509792.02
      1968605.51     13509724.31      1968291.70     13510194.37
#Sta/Elev= 30
  4422.6  579.59  4474.4  576.86  4523.8  577.30  4735.3  575.92  4904.0  572.73
  4939.1  570.05  4967.5  565.80  4974.9  564.33  4980.3  558.96  4984.6  558.96
  4993.3  555.32  4993.7  554.82  4998.0  555.32  5006.0  562.90  5016.4  563.67
  5029.6  563.29  5047.4  560.13  5069.7  558.04  5184.9  557.65  5241.2  556.74
  5324.0  558.18  5352.6  558.02  5447.1  562.47  5489.2  566.91  5504.2  567.19
  5525.2  569.21  5582.3  572.07  5648.4  573.63  5705.5  576.24  5808.7  577.74
#Mann=3,-1,0
  4422.6     0.1       0  4993.3    0.07       0  4998.0     0.1       0
Bank Sta=4993.3,4998
Exp/Cntr=0.3,0.1

Type RM Length L Ch R = 1,363,346,346,346
BEGIN DESCRIPTION:
Mapping XS f6f3e719
END DESCRIPTION:
XS GIS Cut Line= 6
      1969138.50     13509906.16      1969056.46     13509925.70
      1968979.64     13509889.24      1968881.99     13509762.94
      1968609.85     13509666.58      1968347.18     13510090.49
#Sta/Elev= 30
  4647.8  576.27  4787.8  575.21  4873.1  573.41  4901.5  572.15  4916.0  570.95
  4951.3  566.36  4972.4  562.75  4976.8  562.75  4987.6  556.70  4992.5  552.75
  4992.8  552.25  4996.8  552.25  4997.2  552.75  5005.4  559.47  5013.2  562.75
  5037.3  561.03  5049.4  558.02  5080.3  556.51  5105.8  556.31  5122.1  557.12
  5217.6  556.87  5260.3  555.17  5369.5  557.55  5404.8  557.38  5514.3  562.12
  5557.7  567.35  5593.5  569.69  5697.5  573.90  5734.1  574.31  5764.2  576.28
#Mann=3,-1,0
  4647.8     0.1       0  4992.5    0.07       0  4997.2     0.1       0
Bank Sta=4992.5,4997.2
Exp/Cntr=0.3,0.1

Type RM Length L Ch R = 1,17,0,0,0
BEGIN DESCRIPTION:
UNT 016 in BCW 1.0
END DESCRIPTION:
XS GIS Cut Line= 4
      1969556.27     13509537.67      1968926.37     13509395.87
      1968648.59     13509566.59      1968258.54     13510221.30
#Sta/Elev= 30
  4127.7  560.82  4158.6  557.36  4212.1  554.97  4660.2  554.12  4796.5  549.91
  4808.8  550.75  4833.2  549.46  4839.0  550.62  4864.4  549.76  4940.5  549.82
  5012.8  549.15  5013.1  548.24  5013.6  547.74  5043.7  548.24  5043.8  549.15
  5049.7  550.35  5065.1  549.35  5071.0  550.72  5080.1  549.63  5115.6  553.22
  5144.1  554.33  5333.6  557.05  5429.1  561.06  5466.1  563.13  5508.9  568.44
  5561.5  571.62  5726.9  577.17  5830.9  579.14  5837.9  578.25  5861.5  580.18
#Mann=7,-1,0
  4127.7     0.1       0  4808.8    0.07       0  4864.4     0.1       0
  4940.5    0.12       0  5012.8     0.1       0  5013.1    0.07       0
  5043.7     0.1       0
Bank Sta=5013.1,5043.7
Exp/Cntr=0.3,0.1

Chan Stop Cuts=-1