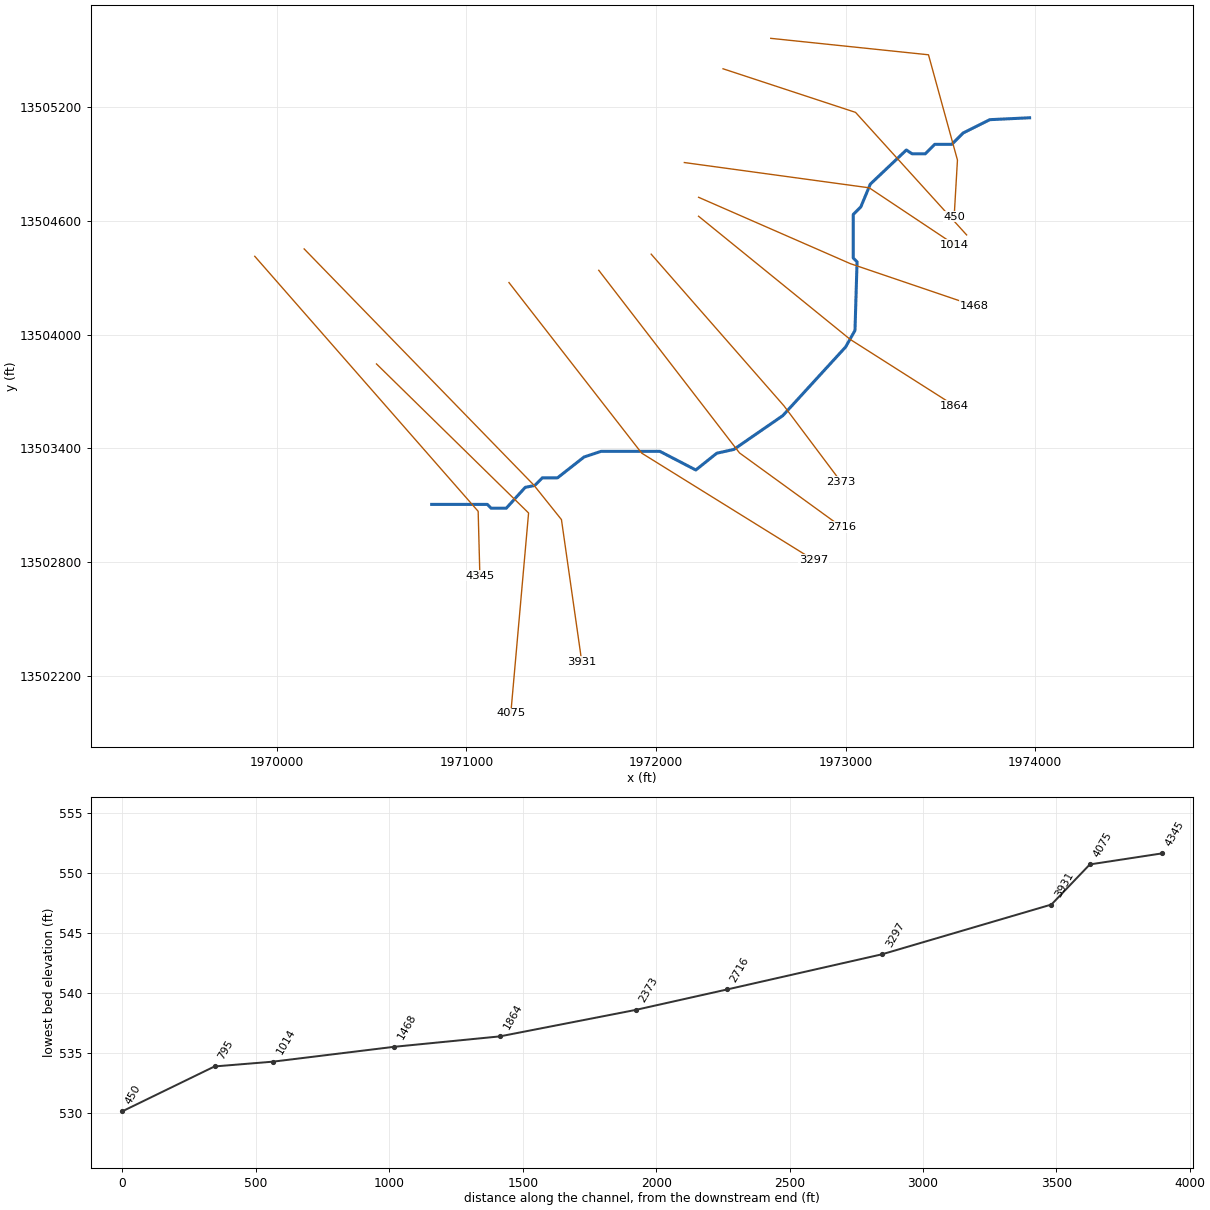
--- UNT 017 in BCW.prj (project) ---

Proj Title=UNT 017 in BCW Base Level Engineering
Current Plan=p01
Default Exp/Contr=0.3,0.1
English Units
Geom File=g01
Flow File=f01
Plan File=p01
BEGIN DESCRIPTION:
UNT 017 in BCW
END DESCRIPTION:

--- UNT 017 in BCW.p01 (plan) ---

Plan Title=Multiple Run
Short Identifier=Multiple
Geom File=g01
Flow File=f01
Subcritical Flow
K Sum by GR= 0
Std Step Tol= 0.01
Critical Tol= 0.01
Num of Std Step Trials= 20
Max Error Tol= 0.3
Flow Tol Ratio= 0.001
Split Flow NTrial= 30
Split Flow Tol= 0.02
Split Flow Ratio= 0.02
Log Output Level= 0
Friction Slope Method= 1
Unsteady Friction Slope Method= 2
Unsteady Bridges Friction Slope Method= 1
Parabolic Critical Depth
Global Vel Dist=  1 , 1 , 1
Global Log Level= 0
CheckData=True
Encroach Param= -1, 0, 0, 0
BEGIN DESCRIPTION:
Multiple Run
END DESCRIPTION:

--- UNT 017 in BCW.f01 (steady flow) ---

Flow Title=Multiple
Number of Profiles=7
Profile Names=10-year,25-year,50-year,1pct_min,100-year,1pct_plu,500-year
River Rch & RM= UNT 017 in BCW,Reach-1,4345
     146     199     242     148     295     588     444
River Rch & RM= UNT 017 in BCW,Reach-1,2716
     248     347     430     266     531    1059     823
Boundary for River Rch & Prof#=UNT 017 in BCW,Reach-1,1
Up Type=0
Dn Type=3
Dn Slope=0.005
Boundary for River Rch & Prof#=UNT 017 in BCW,Reach-1,2
Up Type=0
Dn Type=3
Dn Slope=0.005
Boundary for River Rch & Prof#=UNT 017 in BCW,Reach-1,3
Up Type=0
Dn Type=3
Dn Slope=0.005
Boundary for River Rch & Prof#=UNT 017 in BCW,Reach-1,4
Up Type=0
Dn Type=3
Dn Slope=0.005
Boundary for River Rch & Prof#=UNT 017 in BCW,Reach-1,5
Up Type=0
Dn Type=3
Dn Slope=0.005
Boundary for River Rch & Prof#=UNT 017 in BCW,Reach-1,6
Up Type=0
Dn Type=3
Dn Slope=0.005
Boundary for River Rch & Prof#=UNT 017 in BCW,Reach-1,7
Up Type=0
Dn Type=3
Dn Slope=0.005

--- UNT 017 in BCW.g01 (geometry) ---

Geom Title=Existing Conditions

River Reach=UNT 017 in BCW,Reach-1
Reach XY= 30
      1970817.25     13503104.54      1971110.80     13503104.54
      1971130.80     13503084.54      1971210.80     13503084.54
      1971310.80     13503194.54      1971360.80     13503204.54
      1971400.80     13503244.54      1971480.80     13503244.54
      1971620.80     13503354.54      1971710.80     13503384.54
      1972020.80     13503384.54      1972210.43     13503286.13
      1972320.80     13503374.54      1972410.80     13503394.54
      1972669.14     13503572.87      1973000.45     13503935.14
      1973049.93     13504022.38      1973060.80     13504384.54
      1973040.80     13504404.54      1973040.80     13504634.54
      1973080.80     13504674.54      1973130.80     13504794.54
      1973320.80     13504974.54      1973350.80     13504954.54
      1973420.80     13504954.54      1973470.80     13505004.54
      1973560.80     13505004.54      1973620.80     13505064.54
      1973760.80     13505134.54      1973970.80     13505144.54

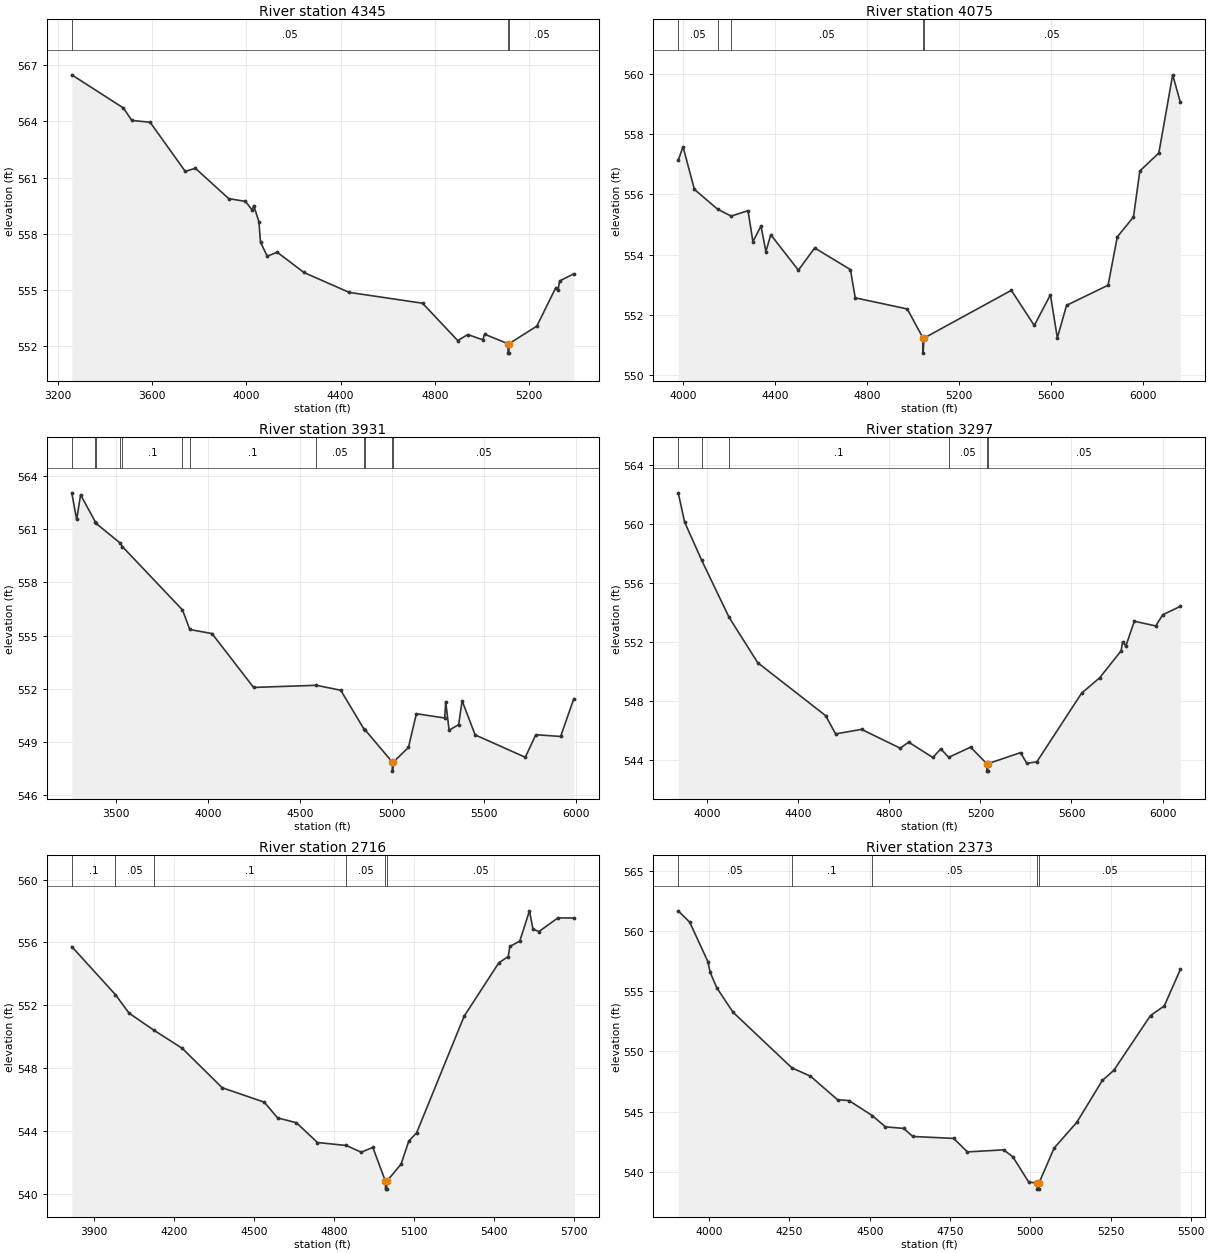
Type RM Length L Ch R = 1,4345,270,270,270
BEGIN DESCRIPTION:
UNT 017 in BCW 9.0
END DESCRIPTION:
XS GIS Cut Line= 3
      1969884.35     13504413.53      1971062.50     13503068.06
      1971071.57     13502728.07
#Sta/Elev= 30
  3260.1  566.48  3479.3  564.71  3514.4  564.05  3592.3  563.95  3741.3  561.33
  3784.0  561.50  3925.4  559.88  3996.6  559.73  4025.0  559.27  4031.7  559.51
  4053.5  558.64  4060.2  557.56  4088.6  556.81  4131.3  557.02  4244.3  555.94
  4436.0  554.88  4747.3  554.30  4896.3  552.31  4939.0  552.63  5002.6  552.35
  5010.2  552.65  5109.6  552.14  5109.8  551.64  5113.3  551.64  5113.6  552.14
  5231.6  553.08  5311.6  555.12  5321.6  555.00  5328.1  555.49  5388.6  555.87
#Mann=3,-1,0
  3260.1    0.05       0  5109.6   0.035       0  5113.6    0.05       0
Bank Sta=5109.6,5113.6
Exp/Cntr=0.3,0.1

Type RM Length L Ch R = 1,4075,144,144,144
BEGIN DESCRIPTION:
Mapping XS 09f8b834
END DESCRIPTION:
XS GIS Cut Line= 3
      1970526.31     13503845.73      1971328.42     13503059.24
      1971234.67     13502001.95
#Sta/Elev= 30
  3977.7  557.13  3998.5  557.59  4048.0  556.17  4148.8  555.51  4208.1  555.28
  4281.4  555.46  4302.6  554.43  4338.0  554.95  4359.1  554.10  4380.4  554.66
  4500.6  553.48  4571.3  554.22  4726.9  553.50  4748.0  552.56  4974.3  552.19
  5043.1  551.22  5043.3  550.72  5047.1  551.22  5427.2  552.81  5527.0  551.64
  5597.2  552.66  5627.4  551.23  5667.5  552.31  5848.2  552.98  5888.4  554.59
  5958.7  555.25  5986.4  556.78  6069.1  557.38  6129.3  559.98  6162.5  559.07
#Mann=5,-1,0
  3977.7    0.05       0  4148.8    0.08       0  4208.1    0.05       0
  5043.1    0.04       0  5047.1    0.05       0
Bank Sta=5043.1,5047.1
Exp/Cntr=0.3,0.1

Type RM Length L Ch R = 1,3931,634,634,634
BEGIN DESCRIPTION:
UNT 017 in BCW 8.0
END DESCRIPTION:
XS GIS Cut Line= 4
      1970144.77     13504452.58      1971355.70     13503206.93
      1971501.79     13503024.41      1971609.01     13502273.75
#Sta/Elev= 30
  3259.7  563.03  3286.4  561.53  3307.7  562.92  3388.6  561.38  3389.5  561.33
  3522.0  560.21  3535.3  560.00  3861.6  556.44  3901.3  555.34  4022.0  555.11
  4248.1  552.08  4589.3  552.20  4721.9  551.92  4847.3  549.75  4856.1  549.67
  5002.8  547.87  5003.1  547.37  5006.8  547.87  5089.7  548.70  5132.9  550.60
  5287.2  550.36  5292.3  551.28  5310.9  549.67  5363.0  549.99  5381.6  551.33
  5452.4  549.41  5725.1  548.15  5782.2  549.42  5917.0  549.32  5989.0  551.45
#Mann=12,-1,0
  3259.7     0.1       0  3388.6    0.08       0  3389.5     0.1       0
  3522.0    0.08       0  3535.3     0.1       0  3861.6    0.05       0
  3901.3     0.1       0  4589.3    0.05       0  4847.3     0.1       0
  4856.1    0.05       0  5002.8    0.03       0  5006.8    0.05       0
Bank Sta=5002.8,5006.8
Exp/Cntr=0.3,0.1

Type RM Length L Ch R = 1,3297,581,581,581
BEGIN DESCRIPTION:
UNT 017 in BCW 7.0
END DESCRIPTION:
XS GIS Cut Line= 3
      1971225.00     13504275.01      1971925.00     13503375.00
      1972830.63     13502812.46
#Sta/Elev= 30
  3871.9  562.14  3900.0  560.15  3974.8  557.56  4095.5  553.67  4221.2  550.59
  4519.8  546.99  4563.3  545.75  4677.3  546.06  4847.4  544.78  4884.5  545.19
  4990.4  544.15  5025.7  544.73  5060.6  544.16  5156.7  544.85  5227.9  543.72
  5228.2  543.22  5231.7  543.22  5231.9  543.72  5376.4  544.48  5403.5  543.75
  5447.7  543.85  5644.4  548.52  5723.5  549.56  5818.0  551.40  5824.4  552.00
  5839.3  551.74  5875.9  553.41  5970.3  553.09  6000.9  553.85  6078.2  554.42
#Mann=6,-1,0
  3871.9     0.1       0  3974.8    0.05       0  4095.5     0.1       0
  5060.6    0.05       0  5227.9    0.07       0  5231.9    0.05       0
Bank Sta=5227.9,5231.9
Exp/Cntr=0.3,0.1

Type RM Length L Ch R = 1,2716,343,343,343
BEGIN DESCRIPTION:
UNT 017 in BCW 6.0
END DESCRIPTION:
XS GIS Cut Line= 3
      1971698.58     13504339.74      1972440.77     13503376.20
      1972979.00     13502985.55
#Sta/Elev= 30
  3818.2  555.73  3981.8  552.67  4033.0  551.49  4124.5  550.42  4232.3  549.25
  4381.8  546.74  4539.5  545.82  4589.3  544.82  4659.9  544.51  4738.8  543.25
  4847.3  543.06  4902.8  542.63  4946.3  542.94  4993.6  540.78  4993.9  540.28
  4998.2  540.28  4998.6  540.78  5052.0  541.87  5081.0  543.34  5110.4  543.87
  5288.2  551.29  5418.0  554.69  5453.6  555.10  5459.8  555.74  5496.9  556.08
  5533.2  558.01  5546.3  556.85  5568.8  556.69  5639.9  557.56  5699.5  557.55
#Mann=6,-1,0
  3818.2     0.1       0  3981.8    0.05       0  4124.5     0.1       0
  4847.3    0.05       0  4993.6    0.03       0  4998.6    0.05       0
Bank Sta=4993.6,4998.6
Exp/Cntr=0.3,0.1

Type RM Length L Ch R = 1,2373,509,509,509
BEGIN DESCRIPTION:
UNT 017 in BCW 5.0
END DESCRIPTION:
XS GIS Cut Line= 3
      1971974.97     13504425.03      1972675.00     13503625.00
      1972975.03     13503224.97
#Sta/Elev= 30
  3903.9  561.67  3939.5  560.73  3996.5  557.44  4003.1  556.58  4024.0  555.28
  4074.3  553.26  4257.9  548.63  4315.4  547.95  4399.9  545.99  4435.4  545.92
  4507.7  544.68  4548.9  543.74  4605.8  543.61  4634.3  542.94  4761.5  542.78
  4804.2  541.66  4917.1  541.83  4945.6  541.25  4995.1  539.16  5021.6  539.07
  5022.0  538.57  5026.5  538.57  5026.9  539.07  5074.2  541.98  5145.1  544.13
  5224.2  547.59  5259.7  548.42  5374.2  552.98  5417.0  553.77  5467.0  556.80
#Mann=5,-1,0
  3903.9    0.05       0  4257.9     0.1       0  4507.7    0.05       0
  5021.6    0.03       0  5026.9    0.05       0
Bank Sta=5021.6,5026.9
Exp/Cntr=0.3,0.1

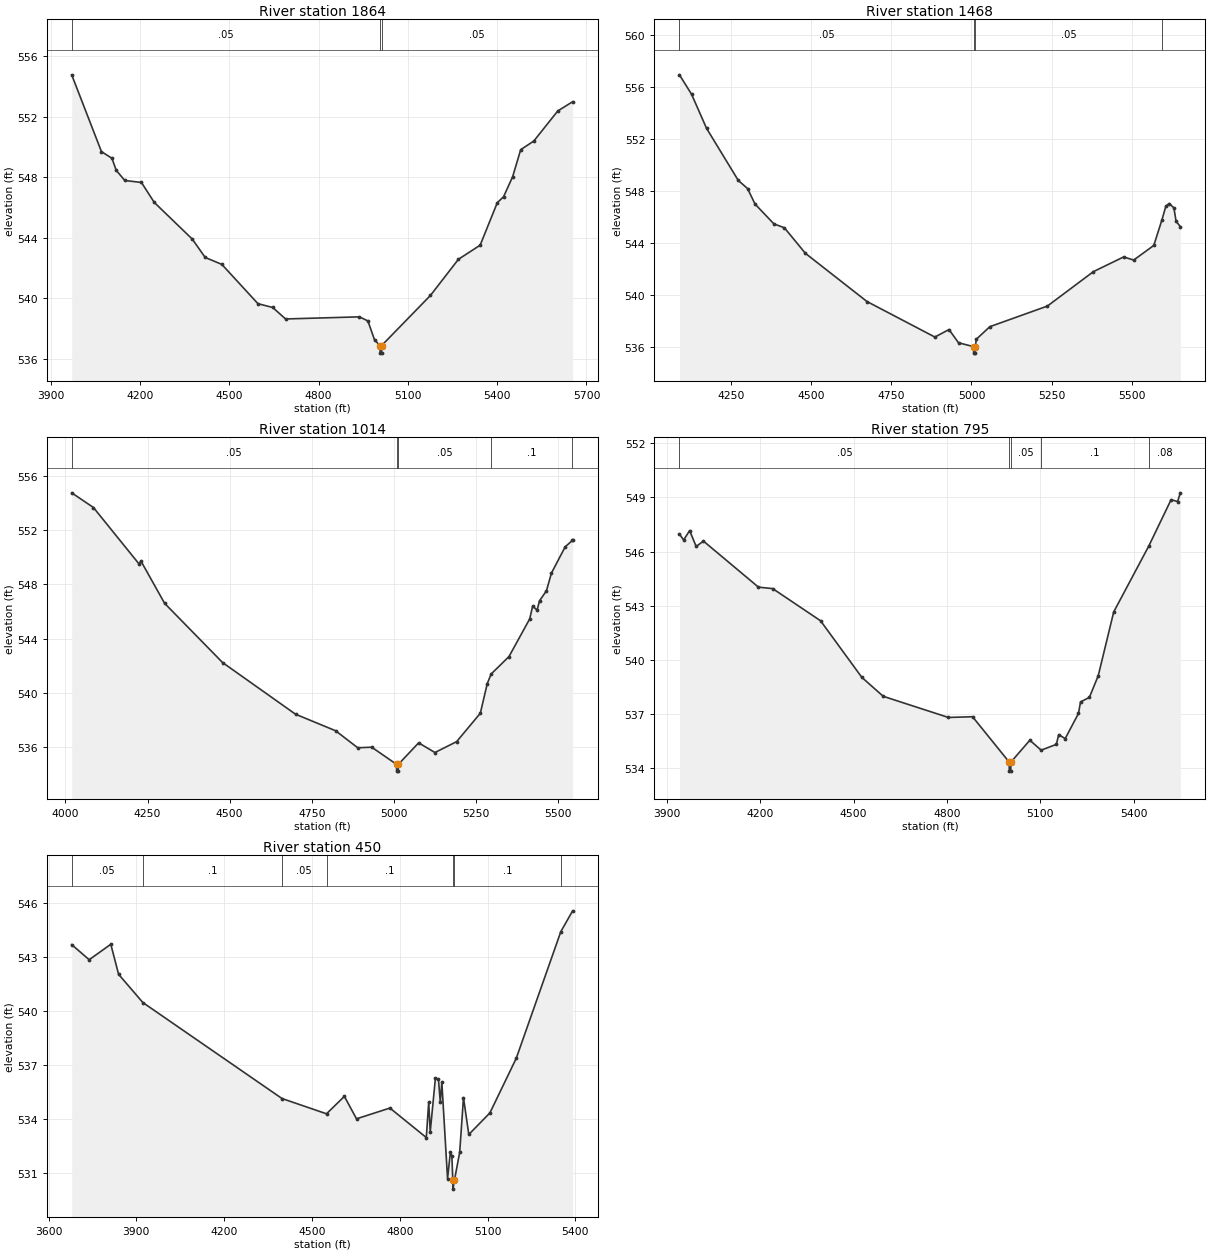
Type RM Length L Ch R = 1,1864,396,396,396
BEGIN DESCRIPTION:
UNT 017 in BCW 4.0
END DESCRIPTION:
XS GIS Cut Line= 3
      1972224.97     13504625.02      1973025.00     13503975.00
      1973574.97     13503625.02
#Sta/Elev= 30
  3970.9  554.77  4070.8  549.69  4106.0  549.25  4120.3  548.46  4149.1  547.78
  4205.1  547.65  4248.2  546.33  4376.1  543.90  4419.2  542.69  4475.2  542.23
  4596.6  539.63  4646.1  539.38  4689.3  538.62  4937.3  538.76  4965.8  538.49
  4988.1  537.24  5006.6  536.86  5007.1  536.36  5011.6  536.36  5012.0  536.86
  5176.1  540.18  5270.1  542.57  5342.9  543.50  5400.5  546.31  5421.7  546.71
  5452.1  548.03  5479.2  549.82  5523.2  550.39  5603.7  552.38  5653.6  552.99
#Mann=3,-1,0
  3970.9    0.05       0  5006.6    0.03       0  5012.0    0.05       0
Bank Sta=5006.6,5012
Exp/Cntr=0.3,0.1

Type RM Length L Ch R = 1,1468,454,454,454
BEGIN DESCRIPTION:
UNT 017 in BCW 3.0
END DESCRIPTION:
XS GIS Cut Line= 3
      1972225.02     13504724.99      1973025.00     13504375.00
      1973677.73     13504153.12
#Sta/Elev= 30
  4089.0  556.96  4126.8  555.46  4173.6  552.83  4272.6  548.81  4301.4  548.19
  4324.8  546.99  4383.7  545.46  4416.4  545.16  4481.9  543.19  4674.1  539.47
  4885.8  536.73  4929.8  537.31  4959.5  536.29  5006.6  535.99  5007.0  535.49
  5011.6  535.49  5012.0  535.99  5015.0  536.56  5057.2  537.53  5236.8  539.12
  5380.5  541.78  5474.6  542.91  5506.0  542.67  5568.8  543.80  5594.2  545.78
  5606.5  546.84  5617.0  547.03  5631.5  546.69  5638.2  545.66  5651.6  545.25
#Mann=4,-1,0
  4089.0    0.05       0  5006.6    0.03       0  5012.0    0.05       0
  5594.2    0.08       0
Bank Sta=5006.6,5012
Exp/Cntr=0.3,0.1

Type RM Length L Ch R = 1,1014,219,219,219
BEGIN DESCRIPTION:
UNT 017 in BCW 2.0
END DESCRIPTION:
XS GIS Cut Line= 3
      1972149.95     13504908.32      1973125.00     13504775.00
      1973575.04     13504474.97
#Sta/Elev= 30
  4019.2  554.73  4085.3  553.65  4224.7  549.48  4229.7  549.72  4302.0  546.60
  4478.5  542.24  4700.5  538.44  4822.7  537.22  4889.9  535.97  4932.7  536.01
  5008.1  534.75  5008.5  534.25  5013.1  534.25  5013.6  534.75  5075.4  536.33
  5125.0  535.62  5191.1  536.42  5263.2  538.51  5284.3  540.69  5296.2  541.40
  5350.4  542.68  5413.5  545.45  5422.5  546.39  5436.0  546.10  5443.5  546.79
  5464.5  547.52  5479.6  548.82  5521.6  550.76  5543.7  551.23  5544.2  551.23
#Mann=5,-1,0
  4019.2    0.05       0  5008.1    0.03       0  5013.6    0.05       0
  5296.2     0.1       0  5543.7    0.08       0
Bank Sta=5008.1,5013.6
Exp/Cntr=0.3,0.1

Type RM Length L Ch R = 1,795,345,345,345
BEGIN DESCRIPTION:
Mapping XS e5910a4e
END DESCRIPTION:
XS GIS Cut Line= 3
      1972353.98     13505403.10      1973052.75     13505173.07
      1973638.68     13504526.39
#Sta/Elev= 30
  3941.1  546.97  3954.5  546.64  3973.8  547.16  3994.8  546.28  4018.1  546.58
  4194.8  544.03  4240.5  543.95  4394.2  542.17  4526.6  539.04  4595.4  537.99
  4804.5  536.82  4882.2  536.86  4999.8  534.35  5000.2  533.85  5004.8  533.85
  5005.3  534.35  5066.1  535.56  5102.3  535.01  5151.2  535.33  5158.7  535.87
  5179.6  535.65  5222.2  537.04  5228.9  537.68  5257.3  537.93  5285.7  539.13
  5335.4  542.66  5448.1  546.31  5519.6  548.87  5540.5  548.77  5549.4  549.25
#Mann=5,-1,0
  3941.1    0.05       0  4999.8    0.03       0  5005.3    0.05       0
  5102.3     0.1       0  5448.1    0.08       0
Bank Sta=4999.8,5005.3
Exp/Cntr=0.3,0.1

Type RM Length L Ch R = 1,450,0,0,0
BEGIN DESCRIPTION:
UNT 017 in BCW 1.0
END DESCRIPTION:
XS GIS Cut Line= 4
      1972605.66     13505563.70      1973437.54     13505476.91
      1973590.32     13504921.36      1973572.96     13504622.74
#Sta/Elev= 30
  3679.1  543.71  3738.8  542.87  3812.7  543.73  3839.3  542.06  3922.1  540.49
  4397.6  535.15  4549.8  534.30  4610.8  535.27  4652.3  534.02  4766.4  534.62
  4890.8  532.98  4899.0  534.96  4904.2  533.30  4922.0  536.30  4932.3  536.22
  4938.6  534.95  4943.8  536.07  4963.4  530.69  4973.0  532.16  4978.2  531.95
  4981.3  530.61  4981.8  530.11  4987.0  530.61  5004.9  532.16  5017.8  535.20
  5036.0  533.15  5108.1  534.35  5198.2  537.39  5350.4  544.43  5390.8  545.59
#Mann=7,-1,0
  3679.1    0.05       0  3922.1     0.1       0  4397.6    0.05       0
  4549.8     0.1       0  4981.3    0.07       0  4987.0     0.1       0
  5350.4    0.08       0
Bank Sta=4981.3,4987
Exp/Cntr=0.3,0.1

Chan Stop Cuts=-1