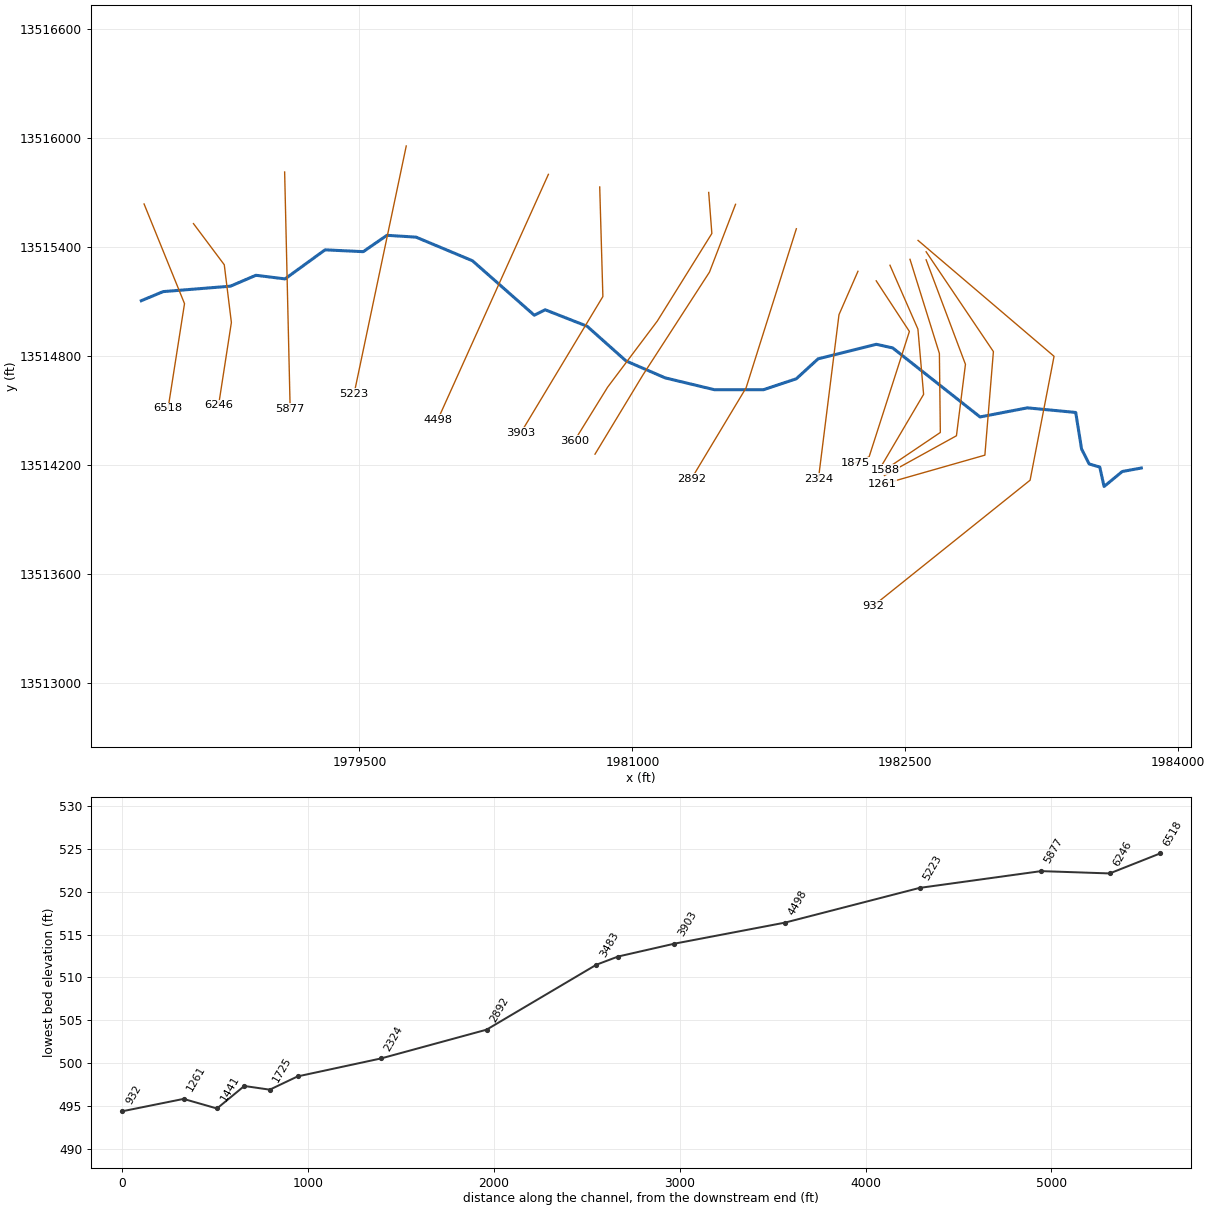
--- UNT 019 in BCW.prj (project) ---

Proj Title=UNT 019 in BCW Base Level Engineering
Current Plan=p01
Default Exp/Contr=0.3,0.1
English Units
Geom File=g01
Flow File=f01
Plan File=p01
BEGIN DESCRIPTION:
UNT 019 in BCW
END DESCRIPTION:

--- UNT 019 in BCW.p01 (plan) ---

Plan Title=Multiple Run
Short Identifier=Multiple
Geom File=g01
Flow File=f01
Subcritical Flow
K Sum by GR= 0
Std Step Tol= 0.01
Critical Tol= 0.01
Num of Std Step Trials= 20
Max Error Tol= 0.3
Flow Tol Ratio= 0.001
Split Flow NTrial= 30
Split Flow Tol= 0.02
Split Flow Ratio= 0.02
Log Output Level= 0
Friction Slope Method= 1
Unsteady Friction Slope Method= 2
Unsteady Bridges Friction Slope Method= 1
Parabolic Critical Depth
Global Vel Dist=  1 , 1 , 1
Global Log Level= 0
CheckData=True
Encroach Param= -1, 0, 0, 0
BEGIN DESCRIPTION:
Multiple Run
END DESCRIPTION:

--- UNT 019 in BCW.f01 (steady flow) ---

Flow Title=Multiple
Number of Profiles=7
Profile Names=10-year,25-year,50-year,1pct_min,100-year,1pct_plu,500-year
River Rch & RM= UNT 019 in BCW,Reach-1,6518
     184     253     309     189     377     752     568
River Rch & RM= UNT 019 in BCW,Reach-1,5877
     193     266     325     199     397     792     600
River Rch & RM= UNT 019 in BCW,Reach-1,4498
     232     321     396     243     485     967     739
Boundary for River Rch & Prof#=UNT 019 in BCW,Reach-1,1
Up Type=0
Dn Type=3
Dn Slope=0.005
Boundary for River Rch & Prof#=UNT 019 in BCW,Reach-1,2
Up Type=0
Dn Type=3
Dn Slope=0.005
Boundary for River Rch & Prof#=UNT 019 in BCW,Reach-1,3
Up Type=0
Dn Type=3
Dn Slope=0.005
Boundary for River Rch & Prof#=UNT 019 in BCW,Reach-1,4
Up Type=0
Dn Type=3
Dn Slope=0.005
Boundary for River Rch & Prof#=UNT 019 in BCW,Reach-1,5
Up Type=0
Dn Type=3
Dn Slope=0.005
Boundary for River Rch & Prof#=UNT 019 in BCW,Reach-1,6
Up Type=0
Dn Type=3
Dn Slope=0.005
Boundary for River Rch & Prof#=UNT 019 in BCW,Reach-1,7
Up Type=0
Dn Type=3
Dn Slope=0.005

--- UNT 019 in BCW.g01 (geometry) ---

Geom Title=Existing Conditions

River Reach=UNT 019 in BCW,Reach-1
Reach XY= 30
      1978300.80     13515104.54      1978420.80     13515154.54
      1978790.80     13515184.54      1978930.80     13515244.54
      1979090.80     13515224.54      1979310.80     13515384.54
      1979520.80     13515374.54      1979650.80     13515464.54
      1979810.80     13515454.54      1980120.80     13515324.54
      1980460.80     13515024.54      1980520.80     13515054.54
      1980751.03     13514964.01      1980965.09     13514772.86
      1981180.19     13514679.63      1981450.80     13514614.54
      1981720.80     13514614.54      1981900.80     13514674.54
      1982020.80     13514784.54      1982340.80     13514864.54
      1982430.80     13514844.54      1982910.80     13514464.54
      1983170.80     13514514.54      1983436.69     13514489.27
      1983468.94     13514287.73      1983510.61     13514205.79
      1983568.94     13514188.43      1983592.55     13514081.48
      1983692.55     13514164.12      1983797.31     13514183.32

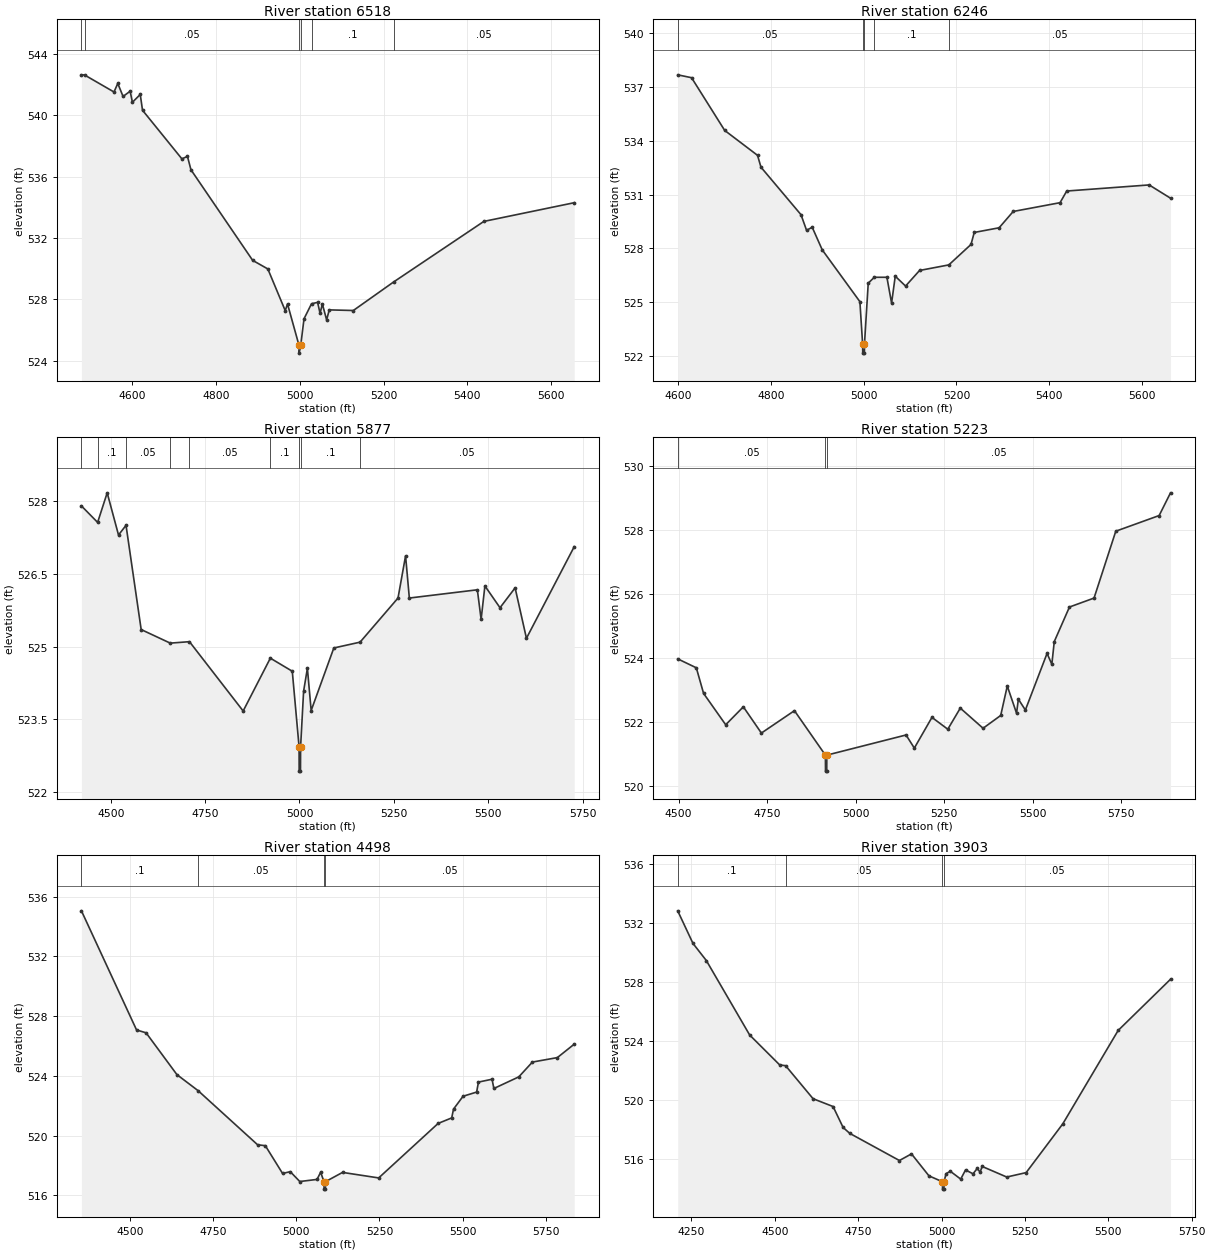
Type RM Length L Ch R = 1,6518,272,272,272
BEGIN DESCRIPTION:
UNT 019 in BCW 9.0
END DESCRIPTION:
XS GIS Cut Line= 3
      1978316.11     13515637.06      1978538.34     13515088.41
      1978448.06     13514511.98
#Sta/Elev= 30
  4479.4  542.65  4486.9  542.64  4557.1  541.53  4566.1  542.09  4578.7  541.24
  4595.6  541.58  4601.0  540.86  4619.7  541.37  4625.1  540.34  4719.0  537.17
  4732.3  537.33  4740.6  536.46  4887.8  530.55  4924.0  529.99  4965.5  527.27
  4970.9  527.71  4998.4  525.00  4998.6  524.50  5002.4  525.00  5010.3  526.74
  5028.2  527.72  5042.7  527.81  5048.6  527.09  5054.0  527.71  5064.2  526.67
  5070.5  527.32  5127.9  527.28  5224.5  529.15  5439.2  533.09  5654.8  534.31
#Mann=6,-1,0
  4479.4     0.1       0  4486.9    0.05       0  4998.4    0.03       0
  5002.4    0.05       0  5028.2     0.1       0  5224.5    0.05       0
Bank Sta=4998.4,5002.4
Exp/Cntr=0.3,0.1

Type RM Length L Ch R = 1,6246,369,369,369
BEGIN DESCRIPTION:
Mapping XS b8956318
END DESCRIPTION:
XS GIS Cut Line= 4
      1978587.59     13515528.99      1978756.88     13515302.39
      1978795.95     13514984.68      1978725.71     13514529.43
#Sta/Elev= 30
  4598.4  537.68  4628.3  537.52  4699.8  534.58  4770.7  533.19  4778.1  532.53
  4864.5  529.88  4876.5  529.01  4888.7  529.18  4910.3  527.92  4991.6  525.03
  4997.5  522.66  4997.8  522.16  5001.3  522.16  5001.5  522.66  5009.6  526.06
  5022.7  526.39  5049.9  526.39  5060.0  524.95  5067.9  526.45  5090.2  525.90
  5120.4  526.77  5183.5  527.08  5231.4  528.22  5238.4  528.89  5292.1  529.15
  5322.5  530.06  5423.6  530.55  5438.0  531.20  5615.9  531.54  5662.0  530.80
#Mann=5,-1,0
  4598.4    0.05       0  4997.5    0.03       0  5001.5    0.05       0
  5022.7     0.1       0  5183.5    0.05       0
Bank Sta=4997.5,5001.5
Exp/Cntr=0.3,0.1

Type RM Length L Ch R = 1,5877,654,654,654
BEGIN DESCRIPTION:
Mapping XS db0acdbb
END DESCRIPTION:
XS GIS Cut Line= 2
      1979088.69     13515813.20      1979119.03     13514508.45
#Sta/Elev= 30
  4422.5  527.90  4465.4  527.56  4490.7  528.17  4520.7  527.30  4540.6  527.50
  4580.7  525.35  4657.7  525.07  4708.6  525.10  4850.8  523.67  4922.8  524.76
  4980.9  524.49  4998.9  522.93  4999.1  522.43  5002.6  522.43  5002.9  522.93
  5010.9  524.08  5020.9  524.55  5030.9  523.68  5090.9  524.97  5160.4  525.09
  5260.9  526.00  5280.9  526.87  5290.9  526.00  5471.0  526.17  5481.0  525.56
  5491.0  526.25  5531.0  525.80  5571.0  526.21  5601.0  525.17  5727.6  527.06
#Mann=9,-1,0
  4422.5    0.05       0  4465.4     0.1       0  4540.6    0.05       0
  4657.7     0.1       0  4708.6    0.05       0  4922.8     0.1       0
  4998.9    0.07       0  5002.9     0.1       0  5160.4    0.05       0
Bank Sta=4998.9,5002.9
Exp/Cntr=0.3,0.1

Type RM Length L Ch R = 1,5223,725,725,725
BEGIN DESCRIPTION:
Mapping XS 1b4b271f
END DESCRIPTION:
XS GIS Cut Line= 2
      1979757.10     13515956.49      1979470.63     13514593.57
#Sta/Elev= 30
  4497.3  523.98  4549.9  523.70  4570.4  522.90  4632.9  521.92  4682.8  522.48
  4733.8  521.66  4827.2  522.36  4914.7  520.97  4915.0  520.47  4918.5  520.47
  4918.7  520.97  5142.6  521.60  5166.0  521.19  5215.8  522.15  5260.6  521.78
  5295.9  522.44  5360.3  521.81  5410.1  522.21  5428.7  523.13  5454.9  522.28
  5460.0  522.72  5479.8  522.38  5541.1  524.15  5554.6  523.81  5561.5  524.52
  5604.4  525.60  5673.9  525.88  5735.3  527.97  5857.9  528.46  5890.0  529.17
#Mann=3,-1,0
  4497.3    0.05       0  4914.7    0.03       0  4918.7    0.05       0
Bank Sta=4914.7,4918.7
Exp/Cntr=0.3,0.1

Type RM Length L Ch R = 1,4498,595,595,595
BEGIN DESCRIPTION:
Mapping XS 839bae4b
END DESCRIPTION:
XS GIS Cut Line= 2
      1980538.33     13515800.19      1979930.69     13514450.35
#Sta/Elev= 30
  4354.8  535.05  4520.4  527.07  4549.0  526.88  4641.6  524.08  4705.5  523.00
  4884.0  519.38  4907.2  519.32  4959.0  517.46  4982.1  517.58  5010.7  516.92
  5062.5  517.06  5073.3  517.54  5083.4  516.91  5083.8  516.41  5087.6  516.41
  5087.9  516.91  5139.1  517.53  5247.7  517.16  5426.2  520.81  5467.0  521.18
  5472.5  521.77  5501.1  522.63  5541.9  522.91  5547.4  523.58  5588.2  523.77
  5593.7  523.15  5668.6  523.93  5709.4  524.92  5784.4  525.22  5835.1  526.12
#Mann=4,-1,0
  4354.8     0.1       0  4705.5    0.05       0  5083.4   0.035       0
  5087.9    0.05       0
Bank Sta=5083.4,5087.9
Exp/Cntr=0.3,0.1

Type RM Length L Ch R = 1,3903,303,303,303
BEGIN DESCRIPTION:
Mapping XS 2b5c4bda
END DESCRIPTION:
XS GIS Cut Line= 3
      1980820.46     13515730.75      1980837.82     13515127.47
      1980387.43     13514378.26
#Sta/Elev= 30
  4208.9  532.82  4254.7  530.61  4294.7  529.45  4424.7  524.40  4514.8  522.37
  4532.4  522.32  4614.8  520.08  4674.8  519.55  4704.9  518.13  4724.9  517.73
  4873.7  515.89  4909.9  516.34  4962.3  514.85  5002.8  514.45  5003.1  513.95
  5007.0  513.95  5007.3  514.45  5013.7  515.00  5026.4  515.16  5057.5  514.63
  5072.0  515.25  5094.4  514.99  5107.0  515.35  5115.8  515.10  5121.6  515.49
  5195.5  514.77  5253.7  515.07  5363.7  518.38  5529.6  524.71  5686.6  528.18
#Mann=4,-1,0
  4208.9     0.1       0  4532.4    0.05       0  5002.8   0.035       0
  5007.3    0.05       0
Bank Sta=5002.8,5007.3
Exp/Cntr=0.3,0.1

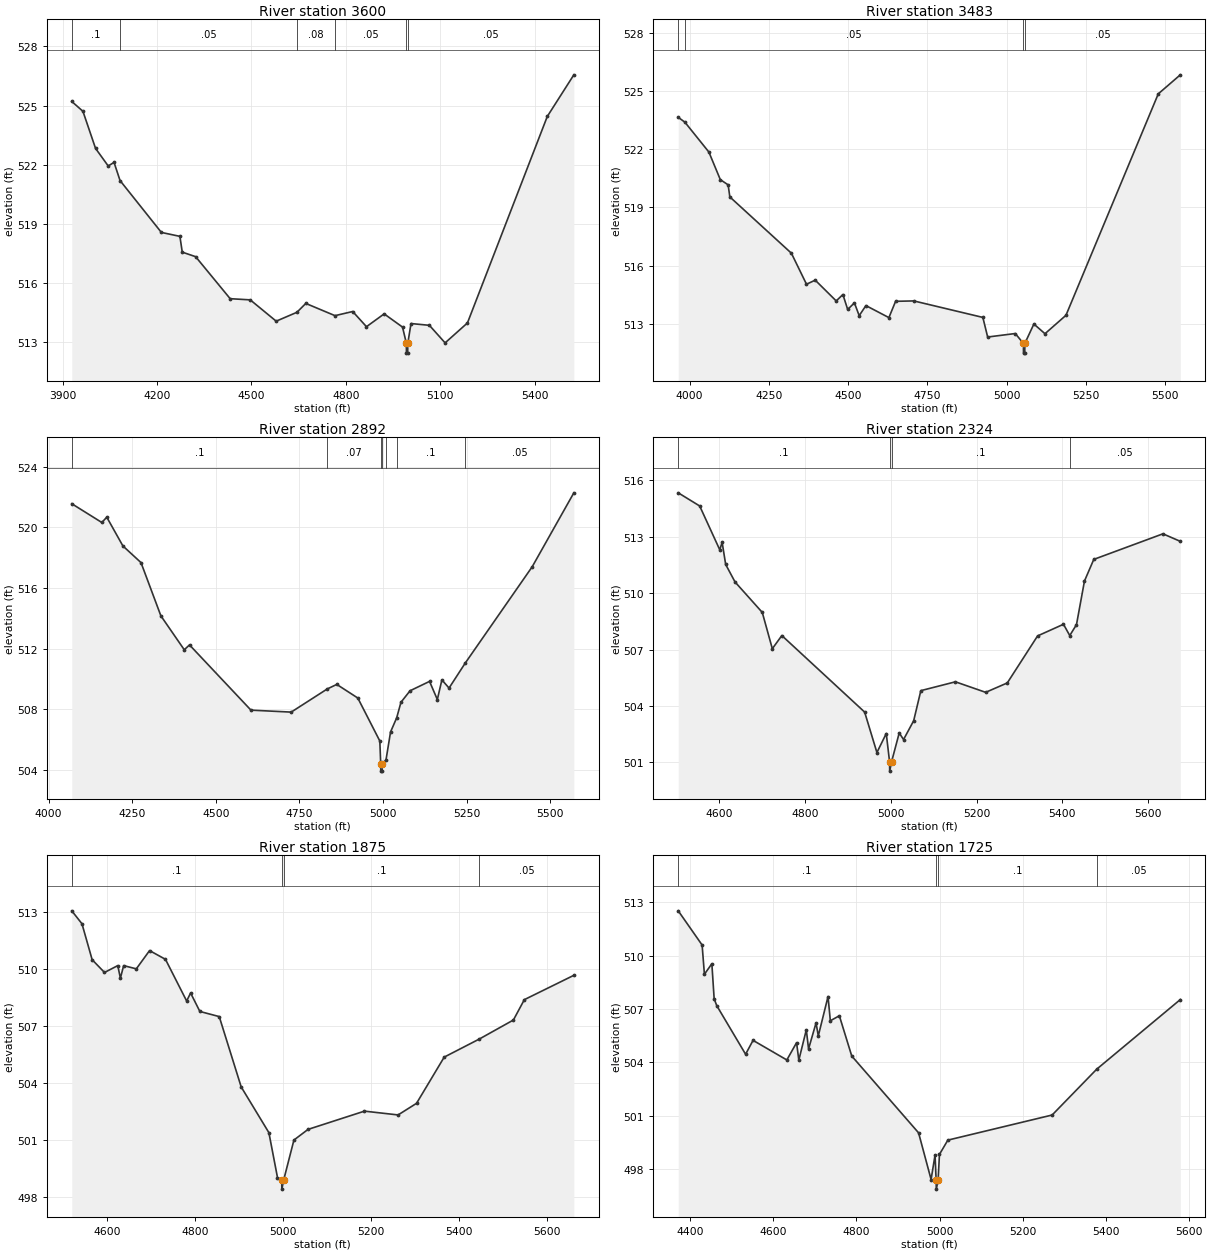
Type RM Length L Ch R = 1,3600,117,117,117
BEGIN DESCRIPTION:
Mapping XS ed7388f1
END DESCRIPTION:
XS GIS Cut Line= 5
      1981419.42     13515700.41      1981436.78     13515474.69
      1981137.30     13514992.92      1980863.86     13514628.34
      1980681.56     13514333.18
#Sta/Elev= 30
  3928.6  525.21  3964.1  524.71  4004.2  522.83  4044.4  521.94  4063.0  522.12
  4082.1  521.20  4213.5  518.57  4272.4  518.37  4279.9  517.57  4322.4  517.34
  4432.2  515.21  4496.1  515.15  4578.5  514.07  4644.4  514.52  4672.7  514.97
  4765.5  514.35  4821.8  514.56  4865.6  513.79  4921.8  514.44  4980.2  513.77
  4992.4  512.95  4992.7  512.45  4996.6  512.45  4997.0  512.95  5007.2  513.95
  5065.6  513.86  5115.6  512.97  5186.6  513.98  5440.5  524.45  5524.9  526.56
#Mann=6,-1,0
  3928.6     0.1       0  4082.1    0.05       0  4644.4    0.08       0
  4765.5    0.05       0  4992.4    0.04       0  4997.0    0.05       0
Bank Sta=4992.4,4997
Exp/Cntr=0.3,0.1

Type RM Length L Ch R = 1,3483,591,591,591
BEGIN DESCRIPTION:
Mapping XS e5204e33
END DESCRIPTION:
XS GIS Cut Line= 4
      1981566.99     13515635.29      1981423.76     13515262.02
      1981059.18     13514697.78      1980794.58     13514259.67
#Sta/Elev= 30
  3964.4  523.64  3985.4  523.39  4061.1  521.85  4097.1  520.43  4121.8  520.16
  4127.1  519.54  4321.2  516.64  4368.9  515.04  4396.4  515.25  4462.6  514.18
  4483.7  514.51  4498.8  513.74  4520.0  514.08  4535.1  513.42  4556.3  513.94
  4628.8  513.32  4649.9  514.16  4707.3  514.18  4925.1  513.33  4940.2  512.32
  5027.4  512.50  5052.9  511.99  5053.3  511.49  5057.2  511.49  5057.5  511.99
  5086.0  512.99  5121.0  512.49  5187.2  513.44  5478.3  524.85  5547.8  525.83
#Mann=4,-1,0
  3964.4     0.1       0  3985.4    0.05       0  5052.9    0.04       0
  5057.5    0.05       0
Bank Sta=5052.9,5057.5
Exp/Cntr=0.3,0.1

Type RM Length L Ch R = 1,2892,568,568,568
BEGIN DESCRIPTION:
UNT 019 in BCW 3.0
END DESCRIPTION:
XS GIS Cut Line= 3
      1981901.20     13515500.78      1981625.00     13514625.00
      1981325.00     13514124.99
#Sta/Elev= 30
  4069.5  521.57  4159.4  520.33  4174.2  520.68  4222.4  518.78  4276.5  517.68
  4336.0  514.16  4405.9  511.92  4421.6  512.24  4605.3  507.93  4725.7  507.80
  4833.5  509.33  4862.0  509.63  4924.9  508.73  4990.7  505.89  4993.3  504.40
  4993.6  503.90  4997.6  503.90  4997.9  504.40  5009.1  504.63  5022.8  506.49
  5041.1  507.42  5053.9  508.45  5081.1  509.21  5139.4  509.83  5162.7  508.63
  5176.3  509.93  5197.7  509.39  5246.1  511.04  5446.5  517.41  5570.9  522.29
#Mann=7,-1,0
  4069.5     0.1       0  4833.5    0.07       0  4993.3    0.07       0
  4997.9    0.07       0  5009.1    0.12       0  5041.1     0.1       0
  5246.1    0.05       0
Bank Sta=4993.3,4997.9
Exp/Cntr=0.3,0.1

Type RM Length L Ch R = 1,2324,449,449,449
BEGIN DESCRIPTION:
Mapping XS 95dbe2f4
END DESCRIPTION:
XS GIS Cut Line= 3
      1982239.74     13515266.38      1982135.57     13515027.64
      1982022.72     13514124.85
#Sta/Elev= 30
  4504.6  515.34  4554.6  514.64  4601.4  512.31  4606.9  512.71  4615.2  511.53
  4637.0  510.60  4700.5  508.98  4723.9  507.05  4746.1  507.75  4939.1  503.68
  4967.7  501.53  4989.5  502.54  4997.2  501.04  4997.5  500.54  5001.9  501.04
  5019.7  502.57  5029.8  502.22  5053.4  503.22  5070.1  504.82  5150.7  505.29
  5221.2  504.73  5271.6  505.23  5342.2  507.73  5402.6  508.35  5417.2  507.75
  5432.9  508.33  5451.5  510.65  5473.2  511.80  5634.4  513.16  5674.9  512.76
#Mann=4,-1,0
  4504.6     0.1       0  4997.2    0.07       0  5001.9     0.1       0
  5417.2    0.05       0
Bank Sta=4997.2,5001.9
Exp/Cntr=0.3,0.1

Type RM Length L Ch R = 1,1875,150,150,150
BEGIN DESCRIPTION:
Mapping XS 8f89d72d
END DESCRIPTION:
XS GIS Cut Line= 4
      1982340.22     13515213.85      1982522.51     13514935.20
      1982301.16     13514245.10      1982222.99     13514211.23
#Sta/Elev= 30
  4519.3  513.07  4542.5  512.39  4565.7  510.50  4593.8  509.83  4624.0  510.19
  4630.0  509.53  4637.4  510.19  4666.2  510.02  4696.4  510.98  4732.6  510.52
  4780.8  508.33  4789.8  508.75  4810.9  507.78  4855.0  507.51  4905.0  503.81
  4968.0  501.41  4987.6  499.05  4997.2  498.94  4997.5  498.44  5001.9  498.94
  5025.0  501.02  5057.1  501.58  5185.6  502.54  5262.1  502.34  5304.1  502.95
  5367.1  505.38  5447.0  506.33  5524.6  507.33  5549.5  508.40  5662.2  509.68
#Mann=4,-1,0
  4519.3     0.1       0  4997.2    0.07       0  5001.9     0.1       0
  5447.0    0.05       0
Bank Sta=4997.2,5001.9
Exp/Cntr=0.3,0.1

Type RM Length L Ch R = 1,1725,137,137,137
BEGIN DESCRIPTION:
Mapping XS ee3a920b
END DESCRIPTION:
XS GIS Cut Line= 4
      1982415.75     13515299.76      1982569.38     13514948.22
      1982600.63     13514588.85      1982366.28     13514190.44
#Sta/Elev= 30
  4372.0  512.51  4429.4  510.59  4434.9  508.95  4452.8  509.54  4458.3  507.58
  4464.5  507.19  4533.9  504.46  4551.8  505.24  4633.0  504.14  4656.4  505.11
  4661.8  504.13  4679.8  505.83  4685.2  504.76  4703.2  506.22  4708.6  505.49
  4732.0  507.70  4737.5  506.34  4759.2  506.62  4789.0  504.36  4949.6  500.05
  4979.7  497.43  4989.2  498.81  4991.8  497.39  4992.2  496.89  4996.5  497.39
  4999.8  498.84  5019.9  499.64  5270.6  501.05  5377.6  503.62  5578.6  507.53
#Mann=4,-1,0
  4372.0     0.1       0  4991.8    0.07       0  4996.5     0.1       0
  5377.6    0.05       0
Bank Sta=4991.8,4996.5
Exp/Cntr=0.3,0.1

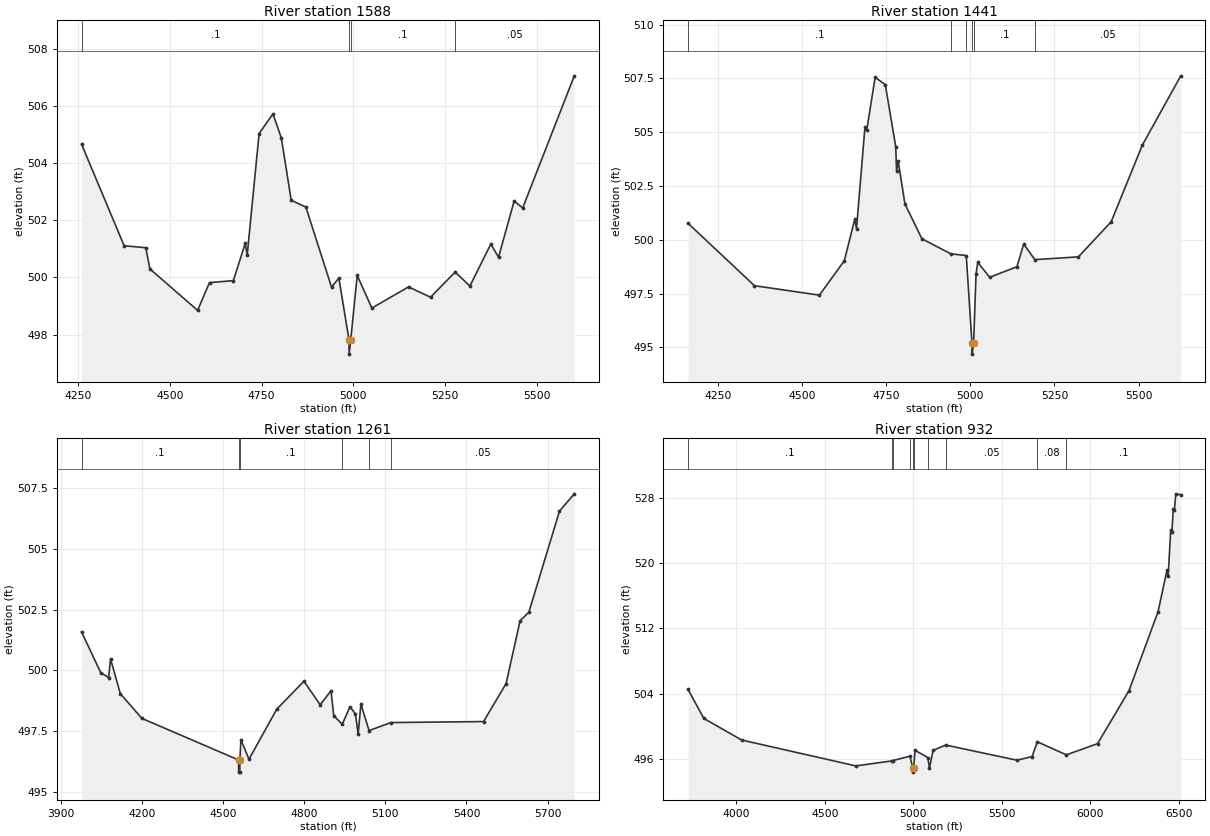
Type RM Length L Ch R = 1,1588,147,147,147
BEGIN DESCRIPTION:
UNT 019 in BCW 2.0
END DESCRIPTION:
XS GIS Cut Line= 4
      1982525.91     13515332.29      1982687.39     13514814.01
      1982692.59     13514379.12      1982388.99     13514174.12
#Sta/Elev= 30
  4258.7  504.66  4374.8  501.11  4433.9  501.04  4445.1  500.30  4575.2  498.85
  4607.7  499.82  4672.7  499.89  4705.2  501.19  4710.5  500.78  4743.0  505.03
  4780.8  505.72  4803.6  504.88  4830.6  502.70  4870.6  502.46  4940.6  499.66
  4960.6  499.98  4988.2  497.82  4988.5  497.32  4993.0  497.82  5010.6  500.07
  5050.6  498.93  5150.6  499.67  5210.6  499.31  5277.9  500.19  5318.0  499.70
  5375.1  501.17  5396.1  500.71  5438.7  502.67  5462.0  502.43  5602.8  507.05
#Mann=4,-1,0
  4258.7     0.1       0  4988.2    0.07       0  4993.0     0.1       0
  5277.9    0.05       0
Bank Sta=4988.2,4993
Exp/Cntr=0.3,0.1

Type RM Length L Ch R = 1,1441,180,180,180
BEGIN DESCRIPTION:
Mapping XS 437e1afc
END DESCRIPTION:
XS GIS Cut Line= 4
      1982614.48     13515329.60      1982830.62     13514754.12
      1982781.14     13514360.89      1982385.32     13514142.15
#Sta/Elev= 30
  4162.0  500.77  4359.2  497.87  4552.1  497.43  4626.2  499.03  4657.1  500.95
  4662.4  500.52  4687.3  505.22  4692.7  505.09  4717.6  507.55  4747.8  507.21
  4778.8  504.33  4781.3  503.22  4786.3  503.64  4806.1  501.67  4856.5  500.05
  4942.3  499.35  4988.3  499.27  5005.3  495.19  5005.6  494.69  5010.1  495.19
  5017.3  498.41  5022.4  498.95  5058.0  498.26  5138.7  498.75  5158.8  499.80
  5192.2  499.08  5321.3  499.21  5418.6  500.84  5511.4  504.41  5625.3  507.62
#Mann=6,-1,0
  4162.0     0.1       0  4942.3    0.12       0  4988.3     0.1       0
  5005.3    0.07       0  5010.1     0.1       0  5192.2    0.05       0
Bank Sta=5005.3,5010.1
Exp/Cntr=0.3,0.1

Type RM Length L Ch R = 1,1261,329,329,329
BEGIN DESCRIPTION:
Mapping XS 261ee07b
END DESCRIPTION:
XS GIS Cut Line= 4
      1982614.49     13515373.88      1982984.26     13514824.43
      1982937.39     13514254.12      1982372.33     13514092.67
#Sta/Elev= 30
  3976.6  501.58  4047.6  499.90  4076.9  499.70  4083.7  500.47  4119.9  499.04
  4199.8  498.02  4557.3  496.31  4557.7  495.81  4561.8  495.81  4562.1  496.31
  4565.9  497.14  4595.7  496.34  4698.5  498.40  4798.9  499.55  4859.1  498.58
  4899.2  499.16  4909.2  498.13  4940.6  497.78  4969.4  498.50  4989.5  498.20
  4999.5  497.38  5009.6  498.61  5039.8  497.52  5120.7  497.85  5463.2  497.89
  5546.4  499.45  5598.4  502.04  5630.7  502.39  5744.0  506.55  5798.8  507.26
#Mann=6,-1,0
  3976.6     0.1       0  4557.3    0.07       0  4562.1     0.1       0
  4940.6    0.12       0  5039.8     0.1       0  5120.7    0.05       0
Bank Sta=4557.3,4562.1
Exp/Cntr=0.3,0.1

Type RM Length L Ch R = 1,932,0,0,0
BEGIN DESCRIPTION:
UNT 019 in BCW 1.0
END DESCRIPTION:
XS GIS Cut Line= 4
      1982570.18     13515436.43      1983317.59     13514798.39
      1983185.91     13514116.19      1982325.04     13513425.03
#Sta/Elev= 30
  3728.2  504.50  3817.6  500.95  4030.6  498.31  4676.1  495.13  4879.7  495.75
  4883.1  495.78  4980.8  496.32  4997.1  494.87  4997.5  494.37  5001.9  494.87
  5009.7  497.04  5081.8  496.16  5091.2  494.87  5111.6  497.04  5182.8  497.69
  5585.6  495.83  5670.5  496.28  5699.8  498.09  5863.7  496.49  6040.1  497.86
  6217.7  504.37  6381.5  514.03  6432.1  519.15  6438.5  518.40  6452.9  524.02
  6459.4  523.75  6467.3  526.61  6473.8  526.49  6481.7  528.48  6509.7  528.37
#Mann=10,-1,0
  3728.2     0.1       0  4879.7    0.12       0  4883.1    0.07       0
  4980.8    0.12       0  4997.1    0.07       0  5001.9    0.12       0
  5081.8    0.07       0  5182.8    0.05       0  5699.8    0.08       0
  5863.7     0.1       0
Bank Sta=4997.1,5001.9
Exp/Cntr=0.3,0.1

Chan Stop Cuts=-1