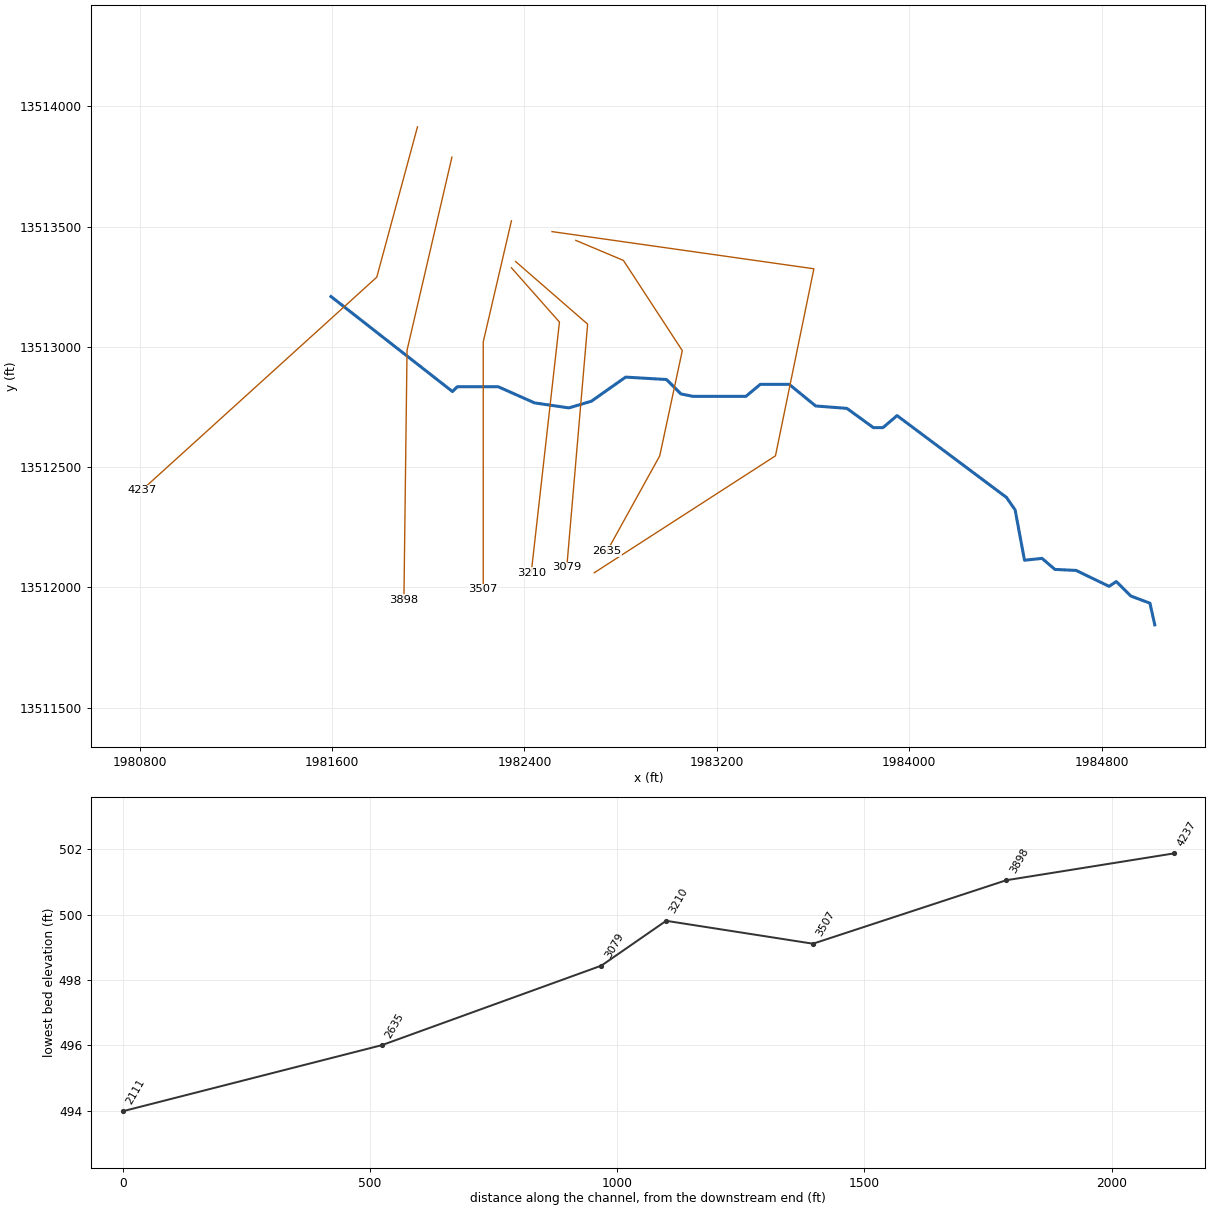
--- UNT 020 in BCW.prj (project) ---

Proj Title=UNT 020 in BCW Base Level Engineering
Current Plan=p01
Default Exp/Contr=0.3,0.1
English Units
Geom File=g01
Flow File=f01
Plan File=p01
BEGIN DESCRIPTION:
UNT 020 in BCW
END DESCRIPTION:

--- UNT 020 in BCW.p01 (plan) ---

Plan Title=Multiple Run
Short Identifier=Multiple
Geom File=g01
Flow File=f01
Subcritical Flow
K Sum by GR= 0
Std Step Tol= 0.01
Critical Tol= 0.01
Num of Std Step Trials= 20
Max Error Tol= 0.3
Flow Tol Ratio= 0.001
Split Flow NTrial= 30
Split Flow Tol= 0.02
Split Flow Ratio= 0.02
Log Output Level= 0
Friction Slope Method= 1
Unsteady Friction Slope Method= 2
Unsteady Bridges Friction Slope Method= 1
Parabolic Critical Depth
Global Vel Dist=  1 , 1 , 1
Global Log Level= 0
CheckData=True
Encroach Param= -1, 0, 0, 0
BEGIN DESCRIPTION:
Multiple Run
END DESCRIPTION:

--- UNT 020 in BCW.f01 (steady flow) ---

Flow Title=Multiple
Number of Profiles=7
Profile Names=10-year,25-year,50-year,1pct_min,100-year,1pct_plu,500-year
River Rch & RM= UNT 020 in BCW,Reach-1,4237
     140     190     229     139     276     551     408
River Rch & RM= UNT 020 in BCW,Reach-1,3507
     206     283     346     211     422     842     636
Boundary for River Rch & Prof#=UNT 020 in BCW,Reach-1,1
Up Type=0
Dn Type=3
Dn Slope=0.005
Boundary for River Rch & Prof#=UNT 020 in BCW,Reach-1,2
Up Type=0
Dn Type=3
Dn Slope=0.005
Boundary for River Rch & Prof#=UNT 020 in BCW,Reach-1,3
Up Type=0
Dn Type=3
Dn Slope=0.005
Boundary for River Rch & Prof#=UNT 020 in BCW,Reach-1,4
Up Type=0
Dn Type=3
Dn Slope=0.005
Boundary for River Rch & Prof#=UNT 020 in BCW,Reach-1,5
Up Type=0
Dn Type=3
Dn Slope=0.005
Boundary for River Rch & Prof#=UNT 020 in BCW,Reach-1,6
Up Type=0
Dn Type=3
Dn Slope=0.005
Boundary for River Rch & Prof#=UNT 020 in BCW,Reach-1,7
Up Type=0
Dn Type=3
Dn Slope=0.005

--- UNT 020 in BCW.g01 (geometry) ---

Geom Title=Existing Conditions

River Reach=UNT 020 in BCW,Reach-1
Reach XY= 30
      1981595.80     13513209.54      1982100.80     13512814.54
      1982120.80     13512834.54      1982290.94     13512834.54
      1982442.33     13512767.36      1982584.69     13512746.52
      1982678.44     13512774.30      1982820.80     13512874.54
      1982990.80     13512864.54      1983050.80     13512804.54
      1983100.80     13512794.54      1983320.80     13512794.54
      1983380.80     13512844.54      1983500.80     13512844.54
      1983610.80     13512754.54      1983740.80     13512744.54
      1983850.80     13512664.54      1983890.80     13512664.54
      1983949.28     13512714.54      1984404.14     13512374.30
      1984440.25     13512322.22      1984479.14     13512113.19
      1984552.05     13512120.83      1984605.53     13512075.00
      1984693.72     13512070.83      1984830.80     13512004.54
      1984860.80     13512024.54      1984920.80     13511964.54
      1985000.80     13511934.54      1985020.80     13511844.54

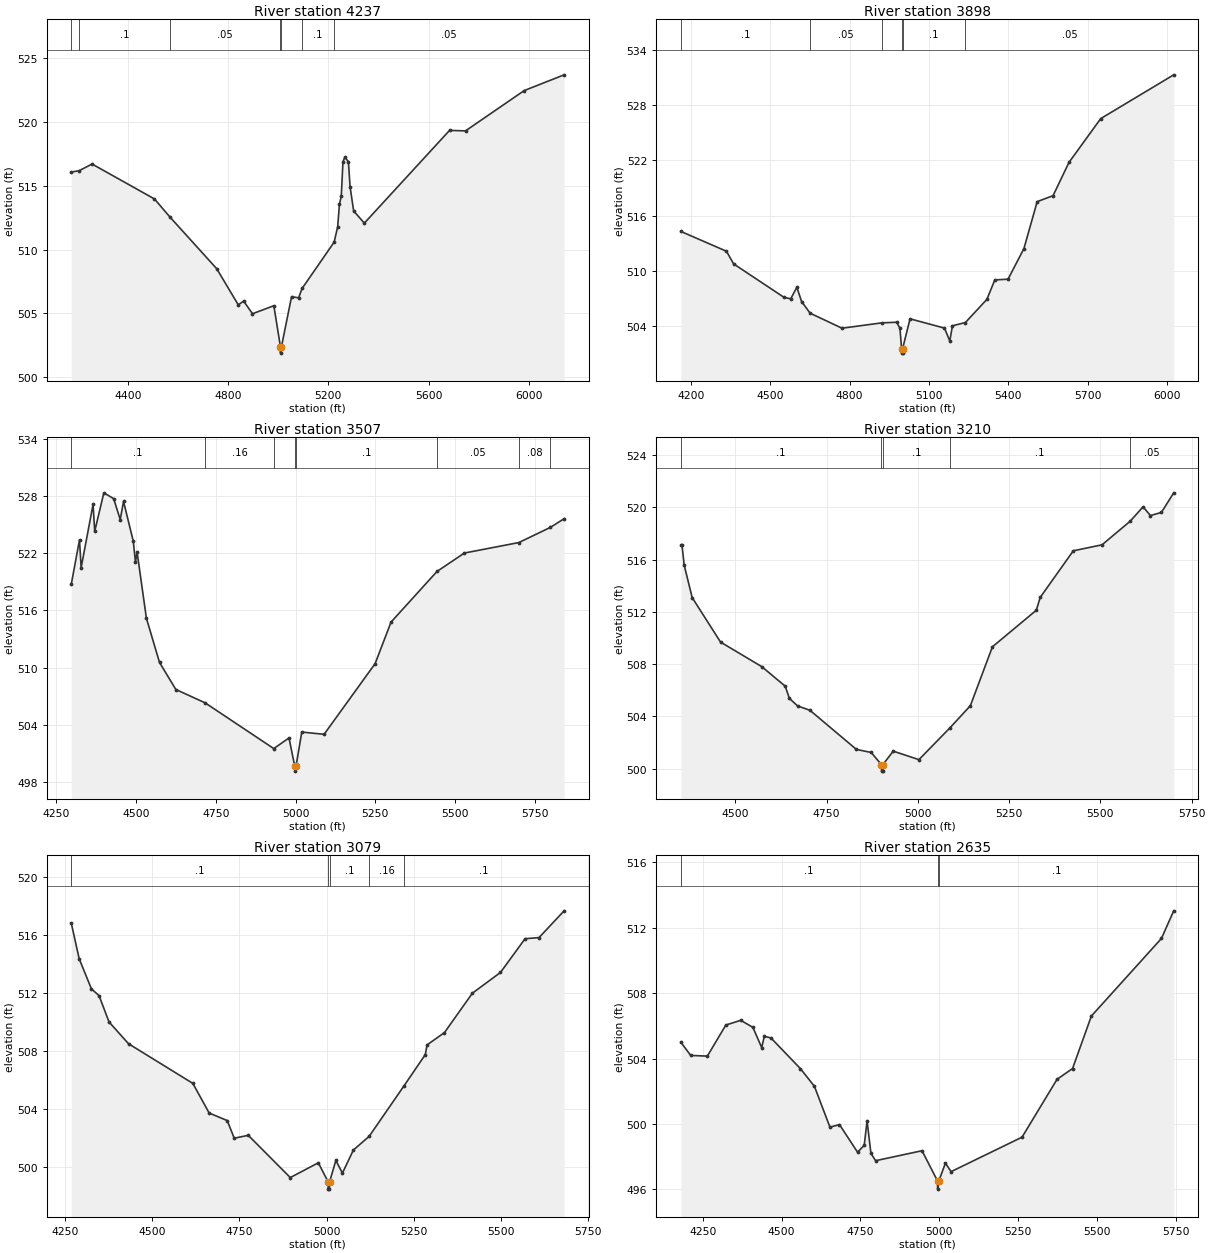
Type RM Length L Ch R = 1,4237,339,339,339
BEGIN DESCRIPTION:
UNT 020 in BCW 2.0
END DESCRIPTION:
XS GIS Cut Line= 3
      1981955.35     13513914.96      1981786.09     13513290.00
      1980809.73     13512404.77
#Sta/Elev= 30
  4175.0  516.08  4205.6  516.18  4257.8  516.71  4506.6  513.97  4567.9  512.56
  4755.1  508.49  4840.8  505.66  4862.4  505.95  4897.6  504.96  4982.7  505.59
  5009.1  502.37  5009.3  501.87  5013.1  502.37  5053.4  506.30  5081.4  506.21
  5095.6  506.95  5223.2  510.58  5237.5  511.80  5244.2  513.54  5251.7  514.19
  5258.4  516.88  5265.9  517.25  5280.1  516.89  5286.8  514.93  5301.0  513.03
  5343.6  512.07  5683.5  519.35  5747.1  519.31  5980.9  522.47  6140.4  523.71
#Mann=7,-1,0
  4175.0    0.05       0  4205.6     0.1       0  4567.9    0.05       0
  5009.1    0.04       0  5013.1    0.05       0  5095.6     0.1       0
  5223.2    0.05       0
Bank Sta=5009.1,5013.1
Exp/Cntr=0.3,0.1

Type RM Length L Ch R = 1,3898,391,391,391
BEGIN DESCRIPTION:
Mapping XS f7d86d46
END DESCRIPTION:
XS GIS Cut Line= 3
      1982098.59     13513789.13      1981911.95     13512986.18
      1981898.94     13511949.42
#Sta/Elev= 30
  4163.0  514.28  4335.0  512.13  4362.3  510.75  4553.3  507.10  4577.9  506.96
  4601.0  508.21  4619.0  506.65  4651.3  505.39  4771.5  503.76  4922.0  504.34
  4978.3  504.41  4990.4  503.74  4996.5  501.55  4996.8  501.05  5000.3  501.05
  5000.5  501.55  5028.5  504.78  5158.6  503.77  5178.6  502.37  5188.6  504.02
  5237.6  504.38  5318.6  506.89  5348.6  509.01  5398.6  509.09  5458.6  512.42
  5508.6  517.52  5568.6  518.17  5628.6  521.78  5748.6  526.55  6024.2  531.31
#Mann=6,-1,0
  4163.0     0.1       0  4651.3    0.05       0  4922.0     0.1       0
  4996.5    0.07       0  5000.5     0.1       0  5237.6    0.05       0
Bank Sta=4996.5,5000.5
Exp/Cntr=0.3,0.1

Type RM Length L Ch R = 1,3507,297,297,297
BEGIN DESCRIPTION:
Mapping XS 27432b5b
END DESCRIPTION:
XS GIS Cut Line= 3
      1982345.98     13513524.38      1982228.80     13513020.90
      1982228.80     13511992.24
#Sta/Elev= 30
  4296.7  518.78  4322.4  523.42  4327.5  520.49  4365.0  527.16  4370.1  524.32
  4398.7  528.37  4429.5  527.76  4450.1  525.56  4460.5  527.46  4491.1  523.28
  4497.9  521.08  4503.0  522.15  4532.2  515.19  4573.3  510.54  4624.6  507.69
  4716.4  506.29  4931.7  501.48  4979.5  502.60  4997.5  499.61  4997.8  499.11
  5001.5  499.61  5019.5  503.22  5089.5  502.98  5249.5  510.41  5299.5  514.78
  5443.5  520.10  5529.5  522.04  5700.2  523.14  5798.8  524.73  5842.3  525.65
#Mann=8,-1,0
  4296.7     0.1       0  4716.4    0.16       0  4931.7     0.1       0
  4997.5    0.07       0  5001.5     0.1       0  5443.5    0.05       0
  5700.2    0.08       0  5798.8    0.05       0
Bank Sta=4997.5,5001.5
Exp/Cntr=0.3,0.1

Type RM Length L Ch R = 1,3210,131,131,131
BEGIN DESCRIPTION:
Mapping XS e1d6623e
END DESCRIPTION:
XS GIS Cut Line= 3
      1982345.97     13513329.08      1982545.64     13513103.37
      1982428.45     13512061.69
#Sta/Elev= 30
  4351.2  517.10  4354.3  517.10  4360.3  515.58  4382.1  513.10  4459.9  509.69
  4572.8  507.81  4637.0  506.31  4648.3  505.38  4671.0  504.80  4704.6  504.47
  4832.0  501.47  4872.3  501.24  4900.4  500.31  4900.7  499.81  4904.3  499.81
  4904.5  500.31  4932.7  501.34  5003.1  500.69  5087.9  503.12  5144.0  504.82
  5204.4  509.33  5324.6  512.13  5335.2  513.11  5425.8  516.68  5504.6  517.14
  5581.8  518.95  5617.0  520.05  5637.1  519.38  5667.3  519.62  5700.8  521.12
#Mann=5,-1,0
  4351.2     0.1       0  4900.4    0.07       0  4904.5     0.1       0
  5087.9     0.1       0  5581.8    0.05       0
Bank Sta=4900.4,4904.5
Exp/Cntr=0.3,0.1

Type RM Length L Ch R = 1,3079,444,444,444
BEGIN DESCRIPTION:
Mapping XS 28652427
END DESCRIPTION:
XS GIS Cut Line= 3
      1982363.34     13513355.10      1982662.82     13513094.69
      1982576.01     13512083.37
#Sta/Elev= 30
  4268.8  516.82  4291.3  514.37  4326.5  512.28  4348.3  511.82  4376.8  510.00
  4432.8  508.49  4617.0  505.75  4663.8  503.70  4715.5  503.18  4735.6  501.96
  4775.8  502.16  4896.2  499.24  4976.5  500.26  5004.6  498.94  5004.8  498.44
  5008.4  498.44  5008.7  498.94  5026.7  500.42  5045.6  499.55  5076.9  501.14
  5122.2  502.09  5221.4  505.56  5283.0  507.74  5288.0  508.41  5337.8  509.26
  5418.1  511.99  5498.4  513.42  5568.7  515.75  5608.8  515.83  5680.7  517.68
#Mann=5,-1,0
  4268.8     0.1       0  5004.6    0.07       0  5008.7     0.1       0
  5122.2    0.16       0  5221.4     0.1       0
Bank Sta=5004.6,5008.7
Exp/Cntr=0.3,0.1

Type RM Length L Ch R = 1,2635,524,524,524
BEGIN DESCRIPTION:
Mapping XS 78ae592e
END DESCRIPTION:
XS GIS Cut Line= 5
      1982613.64     13513443.02      1982811.57     13513359.68
      1983056.36     13512984.68      1982962.61     13512547.18
      1982743.85     13512151.33
#Sta/Elev= 30
  4181.0  505.00  4212.1  504.19  4265.0  504.15  4323.5  506.05  4370.8  506.34
  4409.3  505.91  4437.2  504.67  4445.5  505.36  4466.6  505.26  4560.1  503.38
  4604.4  502.30  4653.6  499.80  4683.8  499.96  4741.1  498.27  4762.2  498.69
  4771.3  500.18  4783.5  498.20  4798.4  497.75  4945.5  498.36  4994.6  496.51
  4994.9  496.01  4998.7  496.51  5019.7  497.60  5037.6  497.08  5262.6  499.19
  5373.5  502.73  5422.7  503.39  5482.3  506.60  5704.5  511.35  5743.3  513.04
#Mann=3,-1,0
  4181.0     0.1       0  4994.6    0.07       0  4998.7     0.1       0
Bank Sta=4994.6,4998.7
Exp/Cntr=0.3,0.1

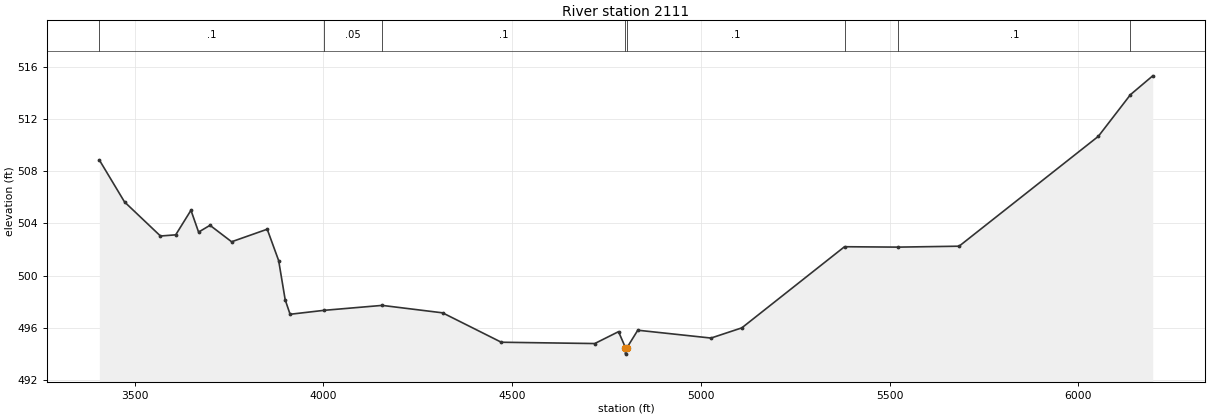
Type RM Length L Ch R = 1,2111,0,0,0
BEGIN DESCRIPTION:
UNT 020 in BCW 1.0
END DESCRIPTION:
XS GIS Cut Line= 4
      1982514.68     13513479.48      1983603.45     13513324.95
      1983443.73     13512547.17      1982690.22     13512061.04
#Sta/Elev= 30
  3406.5  508.85  3473.2  505.64  3568.4  503.03  3608.8  503.12  3649.2  505.00
  3669.4  503.33  3699.7  503.85  3756.9  502.59  3851.2  503.55  3881.5  501.15
  3898.8  498.15  3911.8  497.04  4001.1  497.34  4155.7  497.72  4315.8  497.15
  4471.3  494.90  4718.8  494.80  4781.8  495.71  4800.1  494.49  4800.3  493.99
  4804.3  494.49  4832.8  495.82  5026.8  495.22  5108.4  496.00  5380.4  502.21
  5522.6  502.18  5683.9  502.25  6052.8  510.66  6137.9  513.85  6196.9  515.29
#Mann=8,-1,0
  3406.5     0.1       0  4001.1    0.05       0  4155.7     0.1       0
  4800.1    0.07       0  4804.3     0.1       0  5380.4    0.05       0
  5522.6     0.1       0  6137.9    0.05       0
Bank Sta=4800.1,4804.3
Exp/Cntr=0.3,0.1

Chan Stop Cuts=-1