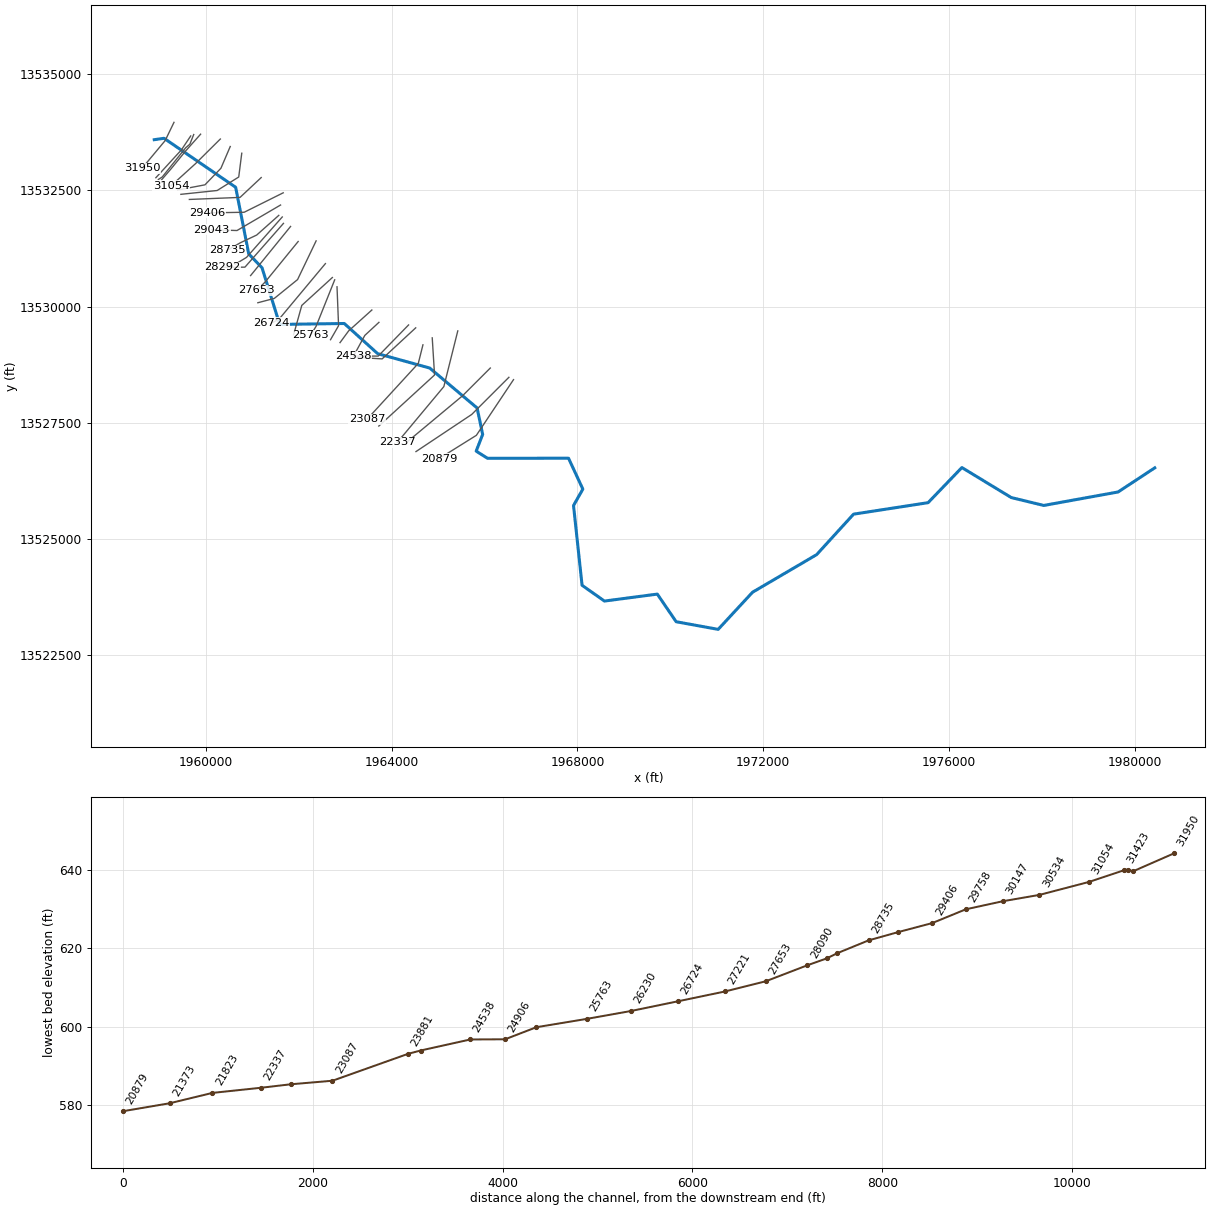
--- UNT 021 in BCW.prj (project) ---

Proj Title=UNT 021 in BCW Base Level Engineering
Current Plan=p01
Default Exp/Contr=0.3,0.1
English Units
Geom File=g01
Flow File=f01
Plan File=p01
Y Axis Title=Elevation
X Axis Title(PF)=Main Channel Distance
X Axis Title(XS)=Station
BEGIN DESCRIPTION:
UNT 021 in BCW
END DESCRIPTION:
DSS Export Rating Curves= 0
DSS Export Rating Curve Sorted= 0
DSS Export Volume Flow Curves= 0
DXF OffsetX= 0
DXF OffsetY= 0
DXF ScaleX= 1
DXF ScaleY= 10

--- UNT 021 in BCW.p01 (plan) ---

Plan Title=Multiple Run
Short Identifier=Multiple
Geom File=g01
Flow File=f01
Subcritical Flow
K Sum by GR= 0
Std Step Tol= 0.01
Critical Tol= 0.01
Num of Std Step Trials= 20
Max Error Tol= 0.3
Flow Tol Ratio= 0.001
Split Flow NTrial= 30
Split Flow Tol= 0.02
Split Flow Ratio= 0.02
Log Output Level= 0
Friction Slope Method= 1
Unsteady Friction Slope Method= 2
Unsteady Bridges Friction Slope Method= 1
Parabolic Critical Depth
Global Vel Dist=  1 , 1 , 1
Global Log Level= 0
CheckData=True
Encroach Param= -1, 0, 0, 0
BEGIN DESCRIPTION:
Multiple Run
END DESCRIPTION:

--- UNT 021 in BCW.f01 (steady flow) ---

Flow Title=Multiple
Program Version=5.05
Number of Profiles= 7
Profile Names=10-year,25-year,50-year,1pct_min,100-year,1pct_plu,500-year
River Rch & RM=UNT 021 in BCW,Reach-1         ,31950
     165     228     281     173     345     689     530
River Rch & RM=UNT 021 in BCW,Reach-1         ,30534
     219     306     379     235     468     934     727
River Rch & RM=UNT 021 in BCW,Reach-1         ,23087
     364     520     654     411     819    1634    1309
River Rch & RM=UNT 021 in BCW,Reach-1         ,22337
     364     520     654     411     819    1634    1309
River Rch & RM=UNT 021 in BCW,Reach-1         ,14824
     407     585     737     464     925    1846    1485
River Rch & RM=UNT 021 in BCW,Reach-1         ,12398
     681    1000    1279     815    1627    3246    2681
River Rch & RM=UNT 021 in BCW,Reach-1         ,8210
     704    1032    1320     841    1678    3348    2760
River Rch & RM=UNT 021 in BCW,Reach-1         ,4705
     843    1243    1595    1018    2031    4052    3353
Boundary for River Rch & Prof#=UNT 021 in BCW,Reach-1         , 1
Up Type= 0
Dn Type= 3
Dn Slope=0.005
Boundary for River Rch & Prof#=UNT 021 in BCW,Reach-1         , 2
Up Type= 0
Dn Type= 3
Dn Slope=0.005
Boundary for River Rch & Prof#=UNT 021 in BCW,Reach-1         , 3
Up Type= 0
Dn Type= 3
Dn Slope=0.005
Boundary for River Rch & Prof#=UNT 021 in BCW,Reach-1         , 4
Up Type= 0
Dn Type= 3
Dn Slope=0.005
Boundary for River Rch & Prof#=UNT 021 in BCW,Reach-1         , 5
Up Type= 0
Dn Type= 3
Dn Slope=0.005
Boundary for River Rch & Prof#=UNT 021 in BCW,Reach-1         , 6
Up Type= 0
Dn Type= 3
Dn Slope=0.005
Boundary for River Rch & Prof#=UNT 021 in BCW,Reach-1         , 7
Up Type= 0
Dn Type= 3
Dn Slope=0.005
DSS Import GetInterval= 0
DSS Import GetPeak= 0
DSS Import FillOption= 0

--- UNT 021 in BCW.g01 (geometry) ---

Geom Title=Existing Conditions

River Reach=UNT 021 in BCW,Reach-1
Reach XY= 30
      1958890.80     13533594.54      1959100.80     13533624.54
      1960643.07     13532569.28      1960923.99     13531134.33
      1961210.80     13530834.54      1961590.80     13529614.54
      1962980.80     13529634.54      1963700.80     13528984.54
      1964820.80     13528674.54      1965840.80     13527814.54
      1965960.80     13527244.54      1965820.80     13526884.54
      1966065.31     13526730.31      1967809.23     13526732.05
      1968117.39     13526066.25      1967916.87     13525712.95
      1968100.80     13523994.54      1968582.20     13523654.57
      1969720.80     13523804.54      1970126.48     13523209.26
      1971030.80     13523044.54      1971770.80     13523844.54
      1973150.80     13524654.54      1973945.93     13525526.68
      1975550.80     13525774.54      1976277.87     13526530.84
      1977340.80     13525884.54      1978040.80     13525714.54
      1979640.80     13526004.54      1980430.80     13526524.54

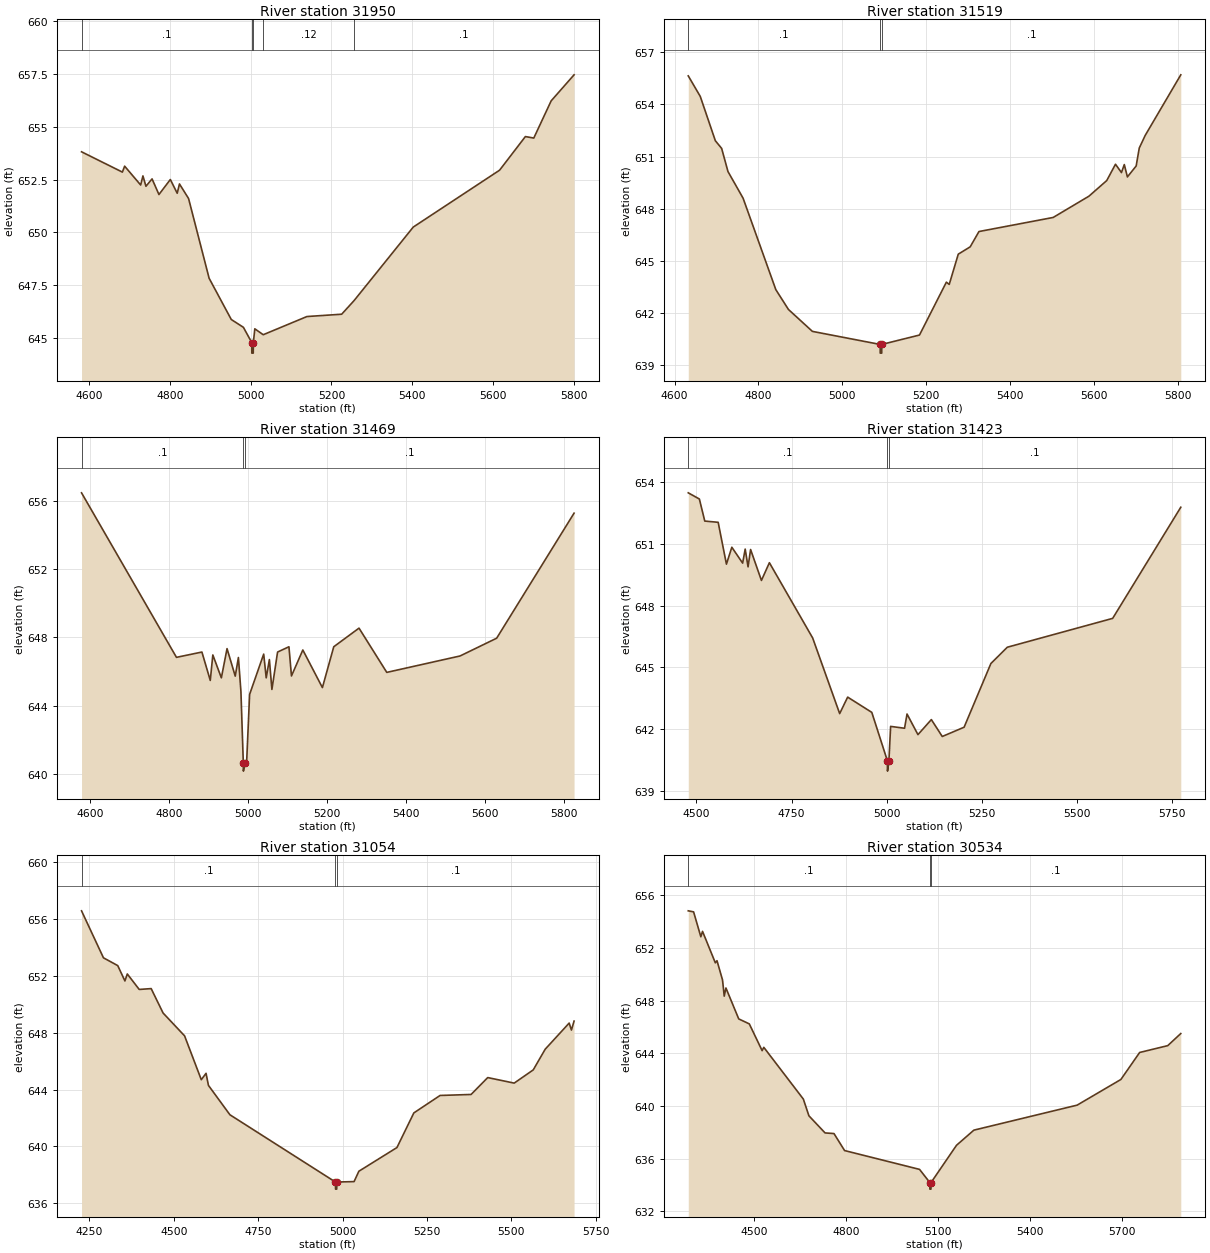
Type RM Length L Ch R = 1,31950,431,431,431
BEGIN DESCRIPTION:
UNT 021 in BCW 51.0
END DESCRIPTION:
XS GIS Cut Line= 3
      1959315.24     13533968.38      1959125.00     13533575.00
      1958625.00     13532975.00
#Sta/Elev= 30
  4582.0  653.81  4683.0  652.85  4688.6  653.13  4728.2  652.24  4733.8  652.67
  4741.3  652.18  4756.4  652.53  4773.4  651.79  4801.6  652.50  4818.6  651.85
  4824.2  652.29  4846.7  651.60  4897.5  647.83  4952.3  645.88  4982.3  645.51
  5002.9  644.79  5003.1  644.29  5006.6  644.29  5006.9  644.79  5010.5  645.44
  5031.3  645.16  5139.4  646.02  5225.3  646.13  5255.8  646.77  5402.3  650.25
  5615.8  652.94  5679.6  654.53  5700.4  654.46  5743.4  656.22  5800.0  657.45
#Mann=5,-1,0
  4582.0     0.1       0  5002.9    0.07       0  5006.9     0.1       0
  5031.3    0.12       0  5255.8     0.1       0
Bank Sta=5002.9,5006.9
Exp/Cntr=0.3,0.1

Type RM Length L Ch R = 1,31519,50,50,50
BEGIN DESCRIPTION:
UNT 021 in BCW 50.0
END DESCRIPTION:
XS GIS Cut Line= 3
      1959675.01     13533675.01      1959475.00     13533375.00
      1958925.01     13532775.01
#Sta/Elev= 30
  4632.6  655.64  4661.2  654.46  4697.2  651.91  4712.2  651.47  4727.3  650.14
  4763.3  648.61  4841.4  643.35  4871.5  642.21  4928.6  640.95  5090.1  640.20
  5090.4  639.70  5093.9  639.70  5094.1  640.20  5184.0  640.74  5248.1  643.78
  5254.9  643.65  5276.5  645.39  5304.9  645.81  5325.8  646.69  5502.8  647.50
  5587.9  648.72  5630.5  649.62  5651.4  650.56  5665.6  650.08  5672.4  650.54
  5679.8  649.83  5700.7  650.46  5708.1  651.49  5722.3  652.22  5807.1  655.70
#Mann=3,-1,0
  4632.6     0.1       0  5090.1    0.07       0  5094.1     0.1       0
Bank Sta=5090.1,5094.1
Exp/Cntr=0.3,0.1

Type RM Length L Ch R = 1,31469,46,46,46
BEGIN DESCRIPTION:
Mapping XS 62d5c02e
END DESCRIPTION:
XS GIS Cut Line= 5
      1959739.73     13533705.40      1959656.40     13533497.06
      1959567.86     13533421.54      1959062.65     13532791.33
      1958978.34     13532737.68
#Sta/Elev= 30
  4578.1  656.45  4818.7  646.82  4883.2  647.13  4904.4  645.47  4910.9  646.96
  4932.5  645.62  4946.9  647.33  4967.7  645.72  4975.7  646.81  4982.1  644.82
  4988.1  640.66  4988.4  640.16  4992.1  640.66  4996.6  640.70  5004.1  644.65
  5039.8  647.01  5046.2  645.62  5054.2  646.69  5060.6  644.94  5075.0  647.13
  5103.8  647.44  5110.2  645.73  5139.0  647.25  5188.6  645.05  5217.4  647.44
  5281.4  648.53  5351.8  645.94  5537.5  646.90  5630.3  647.94  5826.5  655.26
#Mann=3,-1,0
  4578.1     0.1       0  4988.1    0.07       0  4992.1     0.1       0
Bank Sta=4988.1,4992.1
Exp/Cntr=0.3,0.1

Type RM Length L Ch R = 1,31423,369,369,369
BEGIN DESCRIPTION:
Mapping XS 38c113b3
END DESCRIPTION:
XS GIS Cut Line= 4
      1959888.18     13533713.22      1959570.46     13533356.44
      1959257.96     13532973.62      1959047.52     13532729.40
#Sta/Elev= 30
  4478.5  653.47  4507.7  653.17  4521.9  652.10  4557.1  652.04  4578.8  650.01
  4593.0  650.83  4621.4  650.06  4628.1  650.74  4635.6  649.88  4642.3  650.72
  4670.8  649.22  4691.7  650.08  4805.4  646.43  4876.4  642.76  4897.4  643.56
  4960.8  642.82  5001.8  640.47  5002.1  639.97  5005.8  640.47  5010.3  642.14
  5046.9  642.05  5053.4  642.74  5082.1  641.74  5117.3  642.47  5146.0  641.65
  5203.4  642.10  5273.8  645.19  5316.9  645.98  5593.8  647.38  5772.8  652.77
#Mann=3,-1,0
  4478.5     0.1       0  5001.8    0.07       0  5005.8     0.1       0
Bank Sta=5001.8,5005.8
Exp/Cntr=0.3,0.1

Type RM Length L Ch R = 1,31054,520,520,520
BEGIN DESCRIPTION:
UNT 021 in BCW 49.0
END DESCRIPTION:
XS GIS Cut Line= 3
      1960312.66     13533609.05      1959775.00     13533075.00
      1959255.34     13532603.81
#Sta/Elev= 30
  4226.6  656.59  4291.5  653.28  4333.9  652.73  4355.1  651.65  4362.2  652.14
  4397.5  651.05  4432.9  651.11  4468.2  649.39  4531.9  647.78  4581.4  644.69
  4595.5  645.14  4602.6  644.29  4666.2  642.22  4978.9  637.48  4979.2  636.98
  4982.7  636.98  4982.9  637.48  5034.1  637.51  5048.3  638.24  5161.1  639.91
  5211.2  642.35  5288.9  643.58  5380.8  643.65  5430.1  644.84  5508.5  644.45
  5564.9  645.38  5600.4  646.84  5671.4  648.68  5678.1  648.19  5685.9  648.82
#Mann=3,-1,0
  4226.6     0.1       0  4978.9    0.07       0  4982.9     0.1       0
Bank Sta=4978.9,4982.9
Exp/Cntr=0.3,0.1

Type RM Length L Ch R = 1,30534,387,387,387
BEGIN DESCRIPTION:
UNT 021 in BCW 48.0
END DESCRIPTION:
XS GIS Cut Line= 4
      1960526.19     13533447.58      1960325.67     13532978.83
      1959981.92     13532622.06      1959393.35     13532510.08
#Sta/Elev= 30
  4286.7  654.82  4304.1  654.74  4327.7  652.85  4333.2  653.26  4374.9  650.87
  4380.3  651.03  4398.3  649.57  4403.9  648.34  4409.4  648.96  4451.1  646.61
  4485.6  646.23  4527.3  644.20  4532.8  644.45  4661.6  640.52  4679.7  639.25
  4732.3  637.95  4761.4  637.90  4795.9  636.61  5040.1  635.18  5073.6  634.18
  5073.8  633.68  5077.3  633.68  5077.6  634.18  5160.5  637.01  5217.1  638.16
  5553.5  640.06  5696.0  642.01  5757.1  644.06  5848.7  644.58  5891.1  645.50
#Mann=3,-1,0
  4286.7     0.1       0  5073.6    0.07       0  5077.6     0.1       0
Bank Sta=5073.6,5077.6
Exp/Cntr=0.3,0.1

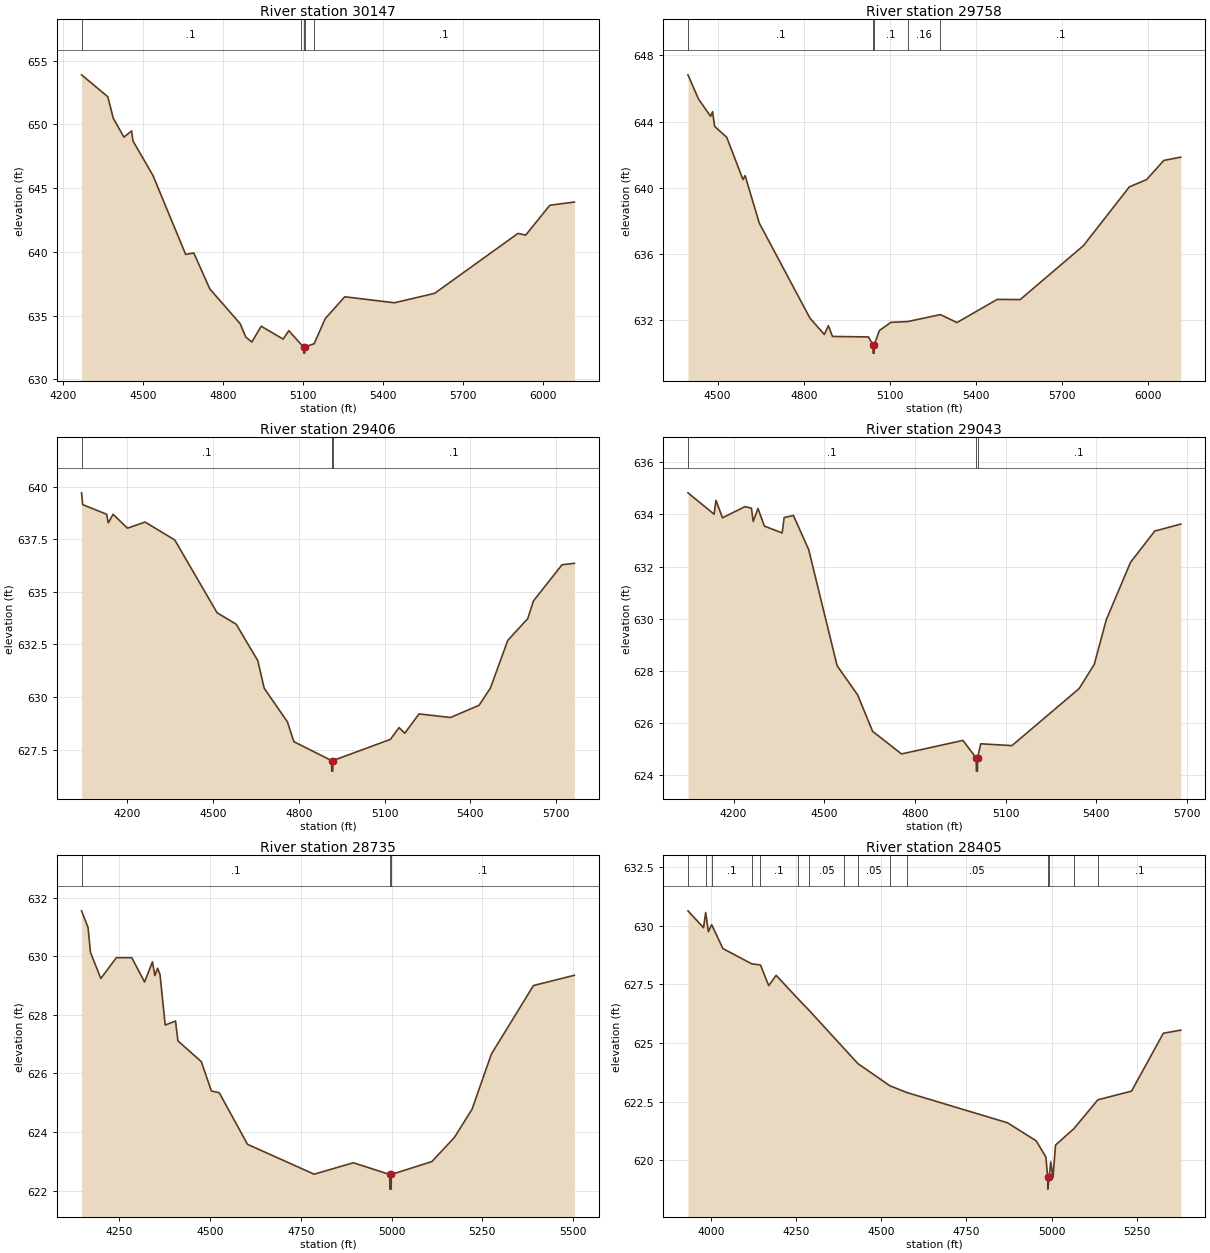
Type RM Length L Ch R = 1,30147,389,389,389
BEGIN DESCRIPTION:
Mapping XS f961b2ff
END DESCRIPTION:
XS GIS Cut Line= 4
      1960774.15     13533302.81      1960709.04     13532790.64
      1960244.63     13532499.84      1959463.41     13532417.37
#Sta/Elev= 30
  4269.0  653.88  4367.6  652.16  4387.8  650.49  4428.1  648.99  4456.9  649.48
  4461.9  648.70  4536.9  645.99  4659.9  639.79  4690.2  639.91  4750.7  637.08
  4864.3  634.36  4885.5  633.31  4908.0  632.92  4943.4  634.16  5025.8  633.15
  5047.0  633.81  5091.2  632.78  5102.7  632.55  5103.0  632.05  5106.6  632.05
  5106.8  632.55  5141.8  632.78  5183.8  634.76  5256.8  636.47  5443.5  636.00
  5594.3  636.74  5907.2  641.44  5936.2  641.31  6026.7  643.65  6118.8  643.90
#Mann=5,-1,0
  4269.0     0.1       0  5091.2    0.16       0  5102.7    0.07       0
  5106.8    0.16       0  5141.8     0.1       0
Bank Sta=5102.7,5106.8
Exp/Cntr=0.3,0.1

Type RM Length L Ch R = 1,29758,352,352,352
BEGIN DESCRIPTION:
UNT 021 in BCW 46.0
END DESCRIPTION:
XS GIS Cut Line= 3
      1961192.88     13532778.33      1960737.13     13532351.23
      1959646.03     13532306.96
#Sta/Elev= 30
  4396.7  646.83  4433.1  645.38  4475.6  644.32  4482.4  644.60  4489.7  643.71
  4531.8  643.05  4588.4  640.49  4595.8  640.73  4645.1  637.86  4821.9  632.10
  4871.7  631.12  4885.9  631.65  4900.1  631.00  5024.9  630.97  5041.4  630.49
  5041.7  629.99  5045.3  629.99  5045.5  630.49  5063.5  631.36  5103.5  631.85
  5161.9  631.90  5276.2  632.32  5333.7  631.84  5473.8  633.24  5553.9  633.23
  5774.1  636.49  5934.2  640.05  5994.2  640.49  6054.3  641.65  6113.3  641.85
#Mann=5,-1,0
  4396.7     0.1       0  5041.4    0.07       0  5045.5     0.1       0
  5161.9    0.16       0  5276.2     0.1       0
Bank Sta=5041.4,5045.5
Exp/Cntr=0.3,0.1

Type RM Length L Ch R = 1,29406,363,363,363
BEGIN DESCRIPTION:
UNT 021 in BCW 45.0
END DESCRIPTION:
XS GIS Cut Line= 3
      1961666.78     13532450.17      1960825.67     13532030.91
      1960041.78     13532017.89
#Sta/Elev= 30
  4039.9  639.71  4043.9  639.15  4127.8  638.69  4133.4  638.28  4150.2  638.69
  4200.5  638.03  4262.1  638.32  4365.9  637.47  4513.9  634.01  4581.0  633.46
  4656.4  631.73  4678.8  630.42  4760.1  628.82  4782.5  627.88  4914.7  626.98
  4915.0  626.48  4918.6  626.48  4918.9  626.98  5120.4  627.99  5150.4  628.55
  5170.4  628.28  5220.4  629.20  5330.4  629.03  5430.4  629.61  5470.4  630.44
  5530.5  632.69  5600.5  633.73  5620.5  634.57  5720.5  636.29  5763.7  636.36
#Mann=3,-1,0
  4039.9     0.1       0  4914.7    0.07       0  4918.9     0.1       0
Bank Sta=4914.7,4918.9
Exp/Cntr=0.3,0.1

Type RM Length L Ch R = 1,29043,308,308,308
BEGIN DESCRIPTION:
Mapping XS 14f82328
END DESCRIPTION:
XS GIS Cut Line= 3
      1961609.52     13532187.16      1960672.02     13531637.69
      1960128.90     13531653.28
#Sta/Elev= 30
  4049.0  634.83  4135.4  634.01  4141.7  634.54  4163.2  633.87  4237.5  634.30
  4259.0  634.24  4264.8  633.73  4280.5  634.23  4302.0  633.55  4360.6  633.29
  4367.2  633.88  4397.8  633.96  4448.3  632.65  4542.3  628.19  4610.6  627.06
  4659.6  625.67  4755.4  624.80  4958.6  625.32  5002.6  624.64  5002.9  624.14
  5006.6  624.14  5006.8  624.64  5017.3  625.19  5120.6  625.12  5342.8  627.31
  5392.8  628.24  5432.8  629.96  5512.8  632.16  5592.9  633.36  5679.0  633.63
#Mann=3,-1,0
  4049.0     0.1       0  5002.6    0.07       0  5006.8     0.1       0
Bank Sta=5002.6,5006.8
Exp/Cntr=0.3,0.1

Type RM Length L Ch R = 1,28735,330,330,330
BEGIN DESCRIPTION:
Mapping XS 1767890a
END DESCRIPTION:
XS GIS Cut Line= 4
      1961571.35     13531963.75      1961095.64     13531540.12
      1960743.20     13531373.45      1960457.49     13531208.43
#Sta/Elev= 30
  4146.6  631.55  4164.5  630.98  4171.2  630.13  4199.7  629.24  4242.3  629.95
  4284.9  629.95  4320.1  629.12  4341.8  629.81  4348.5  629.34  4356.0  629.59
  4362.7  629.37  4376.9  627.65  4405.3  627.79  4412.0  627.11  4476.4  626.40
  4504.0  625.40  4525.7  625.34  4603.5  623.58  4786.9  622.56  4894.9  622.95
  4995.1  622.55  4995.4  622.05  4999.1  622.05  4999.3  622.55  5111.0  622.99
  5173.5  623.82  5221.8  624.78  5274.9  626.66  5390.8  629.00  5503.4  629.35
#Mann=3,-1,0
  4146.6     0.1       0  4995.1    0.07       0  4999.3     0.1       0
Bank Sta=4995.1,4999.3
Exp/Cntr=0.3,0.1

Type RM Length L Ch R = 1,28405,113,113,113
BEGIN DESCRIPTION:
Mapping XS f0cb7ac6
END DESCRIPTION:
XS GIS Cut Line= 3
      1961645.96     13531929.33      1960877.75     13531059.56
      1960631.27     13530909.92
#Sta/Elev= 30
  3931.2  630.64  3977.0  629.92  3983.3  630.57  3991.3  629.75  4000.9  630.05
  4033.9  629.03  4118.6  628.38  4144.4  628.33  4168.6  627.45  4190.4  627.89
  4253.9  626.90  4287.8  626.39  4389.3  624.78  4431.2  624.12  4524.6  623.18
  4574.7  622.89  4870.5  621.60  4955.0  620.83  4983.4  620.14  4988.8  619.27
  4989.1  618.77  4993.2  619.27  4997.6  619.93  5004.3  619.27  5011.9  620.65
  5065.9  621.35  5136.3  622.58  5235.3  622.95  5328.8  625.42  5380.0  625.55
#Mann=15,-1,0
  3931.2     0.1       0  3983.3    0.05       0  4000.9     0.1       0
  4118.6    0.05       0  4144.4     0.1       0  4253.9    0.08       0
  4287.8    0.05       0  4389.3    0.08       0  4431.2    0.05       0
  4524.6    0.08       0  4574.7    0.05       0  4988.8    0.04       0
  4993.2    0.05       0  5065.9    0.08       0  5136.3     0.1       0
Bank Sta=4988.8,4993.2
Exp/Cntr=0.3,0.1

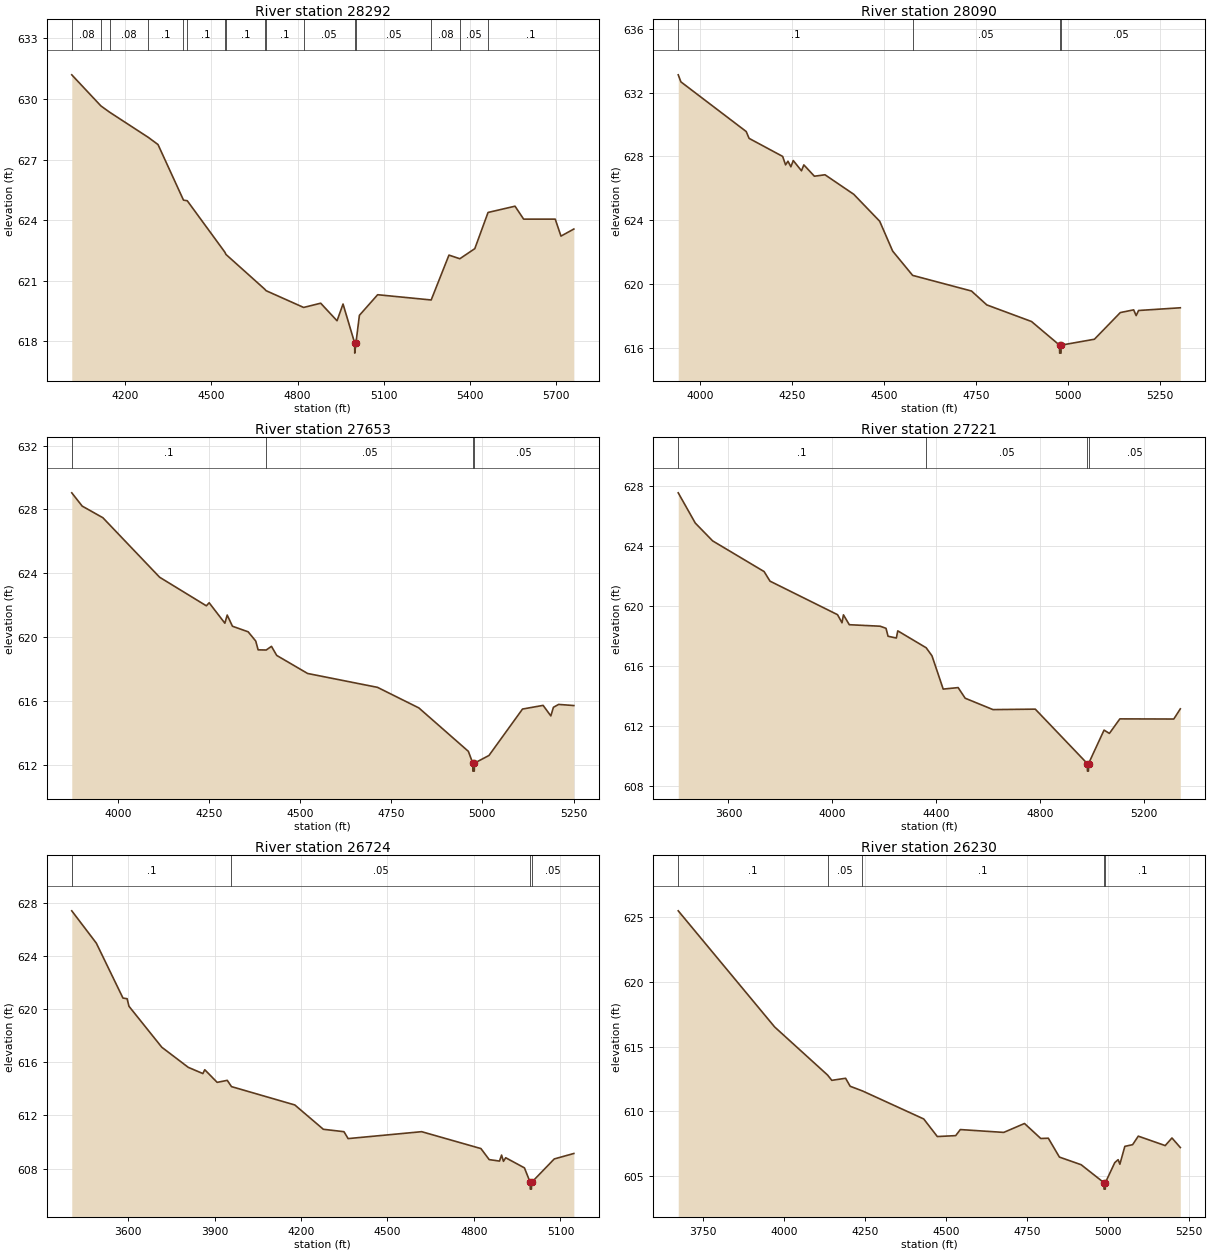
Type RM Length L Ch R = 1,28292,202,202,202
BEGIN DESCRIPTION:
Mapping XS 036496f5
END DESCRIPTION:
XS GIS Cut Line= 3
      1961672.00     13531791.31      1960842.58     13530848.54
      1960350.19     13530843.43
#Sta/Elev= 30
  4013.7  631.19  4115.3  629.65  4145.6  629.34  4280.7  628.09  4314.0  627.74
  4402.7  624.99  4415.8  624.96  4546.5  622.42  4550.8  622.30  4685.9  620.58
  4690.2  620.51  4821.0  619.68  4880.4  619.89  4937.3  619.02  4958.2  619.85
  4998.7  617.92  4999.0  617.42  5003.1  617.92  5015.2  619.29  5078.7  620.31
  5265.1  620.05  5327.0  622.27  5364.8  622.09  5417.0  622.59  5463.1  624.38
  5557.0  624.69  5587.0  624.05  5697.0  624.05  5717.0  623.21  5761.8  623.56
#Mann=16,-1,0
  4013.7    0.08       0  4115.3    0.05       0  4145.6    0.08       0
  4280.7     0.1       0  4402.7    0.08       0  4415.8     0.1       0
  4546.5    0.08       0  4550.8     0.1       0  4685.9    0.05       0
  4690.2     0.1       0  4821.0    0.05       0  4998.7    0.03       0
  5003.1    0.05       0  5265.1    0.08       0  5364.8    0.05       0
  5463.1     0.1       0
Bank Sta=4998.7,5003.1
Exp/Cntr=0.3,0.1

Type RM Length L Ch R = 1,28090,437,437,437
BEGIN DESCRIPTION:
UNT 021 in BCW 44.0
END DESCRIPTION:
XS GIS Cut Line= 3
      1961825.00     13531725.00      1961175.00     13530925.00
      1960964.50     13530666.81
#Sta/Elev= 30
  3940.5  633.11  3947.7  632.67  4125.1  629.56  4133.0  629.13  4224.2  628.00
  4232.1  627.47  4238.6  627.70  4246.5  627.35  4253.0  627.74  4275.3  627.10
  4281.7  627.47  4310.4  626.76  4339.2  626.85  4417.2  625.63  4487.8  623.94
  4523.0  622.07  4577.2  620.55  4737.1  619.57  4778.7  618.70  4900.2  617.66
  4976.3  616.18  4976.6  615.68  4980.4  615.68  4980.7  616.18  5071.1  616.55
  5141.4  618.22  5177.7  618.39  5184.5  618.03  5191.0  618.35  5304.4  618.52
#Mann=4,-1,0
  3940.5     0.1       0  4577.2    0.05       0  4976.3   0.035       0
  4980.7    0.05       0
Bank Sta=4976.3,4980.7
Exp/Cntr=0.3,0.1

Type RM Length L Ch R = 1,27653,432,432,432
BEGIN DESCRIPTION:
UNT 021 in BCW 43.0
END DESCRIPTION:
XS GIS Cut Line= 3
      1961988.77     13531401.15      1961275.00     13530525.00
      1961099.52     13530351.30
#Sta/Elev= 30
  3873.7  629.04  3902.2  628.21  3959.0  627.48  4114.7  623.75  4242.8  621.96
  4250.5  622.15  4293.6  620.87  4300.0  621.38  4314.4  620.68  4357.5  620.33
  4378.3  619.75  4384.8  619.20  4407.0  619.19  4421.4  619.42  4435.8  618.85
  4520.5  617.72  4712.2  616.85  4825.7  615.56  4961.4  612.84  4973.5  612.10
  4973.8  611.60  4977.7  611.60  4978.0  612.10  5017.9  612.58  5109.9  615.49
  5166.4  615.72  5187.6  615.06  5194.7  615.60  5208.9  615.78  5250.7  615.71
#Mann=4,-1,0
  3873.7     0.1       0  4407.0    0.05       0  4973.5   0.035       0
  4978.0    0.05       0
Bank Sta=4973.5,4978
Exp/Cntr=0.3,0.1

Type RM Length L Ch R = 1,27221,497,497,497
BEGIN DESCRIPTION:
UNT 021 in BCW 42.0
END DESCRIPTION:
XS GIS Cut Line= 4
      1962375.08     13531414.22      1961975.76     13530580.84
      1961475.00     13530175.00      1961120.75     13530081.72
#Sta/Elev= 30
  3406.3  627.56  3472.0  625.54  3538.9  624.35  3737.3  622.30  3760.0  621.66
  4020.3  619.42  4037.4  618.88  4043.0  619.41  4065.6  618.75  4184.5  618.65
  4207.1  618.51  4214.9  617.98  4246.9  617.86  4252.4  618.34  4361.9  617.21
  4384.3  616.67  4427.5  614.45  4485.0  614.55  4512.2  613.84  4619.3  613.08
  4782.4  613.11  4983.1  609.47  4983.4  608.97  4987.3  608.97  4987.6  609.47
  5047.4  611.71  5068.0  611.49  5108.3  612.46  5316.2  612.45  5341.3  613.13
#Mann=4,-1,0
  3406.3     0.1       0  4361.9    0.05       0  4983.1   0.035       0
  4987.6    0.05       0
Bank Sta=4983.1,4987.6
Exp/Cntr=0.3,0.1

Type RM Length L Ch R = 1,26724,494,494,494
BEGIN DESCRIPTION:
UNT 021 in BCW 41.0
END DESCRIPTION:
XS GIS Cut Line= 3
      1962574.97     13530924.97      1961575.00     13529725.00
      1961414.15     13529644.66
#Sta/Elev= 30
  3404.7  627.38  3489.9  624.95  3582.3  620.82  3596.7  620.77  3603.2  620.20
  3717.1  617.12  3808.8  615.61  3859.6  615.14  3866.1  615.43  3909.1  614.48
  3944.2  614.63  3958.8  614.16  4178.5  612.78  4277.5  610.95  4349.0  610.77
  4363.4  610.25  4618.5  610.77  4824.2  609.50  4852.8  608.67  4888.6  608.56
  4895.8  609.01  4902.3  608.54  4910.1  608.81  4975.1  608.05  4995.2  606.95
  4995.5  606.45  4999.4  606.45  4999.7  606.95  5078.5  608.72  5146.5  609.13
#Mann=4,-1,0
  3404.7     0.1       0  3958.8    0.05       0  4995.2   0.035       0
  4999.7    0.05       0
Bank Sta=4995.2,4999.7
Exp/Cntr=0.3,0.1

Type RM Length L Ch R = 1,26230,467,467,467
BEGIN DESCRIPTION:
UNT 021 in BCW 40.0
END DESCRIPTION:
XS GIS Cut Line= 3
      1962724.98     13530624.98      1962066.73     13530024.35
      1961889.97     13529390.11
#Sta/Elev= 30
  3673.1  625.51  3970.7  616.52  4134.0  612.80  4147.0  612.39  4189.6  612.55
  4203.8  611.93  4241.7  611.57  4430.8  609.40  4472.7  608.04  4529.4  608.11
  4543.6  608.58  4677.7  608.36  4741.7  609.05  4791.9  607.89  4815.3  607.91
  4849.5  606.45  4916.5  605.86  4986.9  604.47  4987.2  603.97  4991.1  603.97
  4991.4  604.47  5020.3  606.02  5030.7  606.25  5036.1  605.90  5051.4  607.28
  5075.4  607.41  5092.9  608.07  5176.0  607.34  5196.8  607.93  5222.6  607.19
#Mann=5,-1,0
  3673.1     0.1       0  4134.0    0.05       0  4241.7     0.1       0
  4986.9    0.07       0  4991.4     0.1       0
Bank Sta=4986.9,4991.4
Exp/Cntr=0.3,0.1

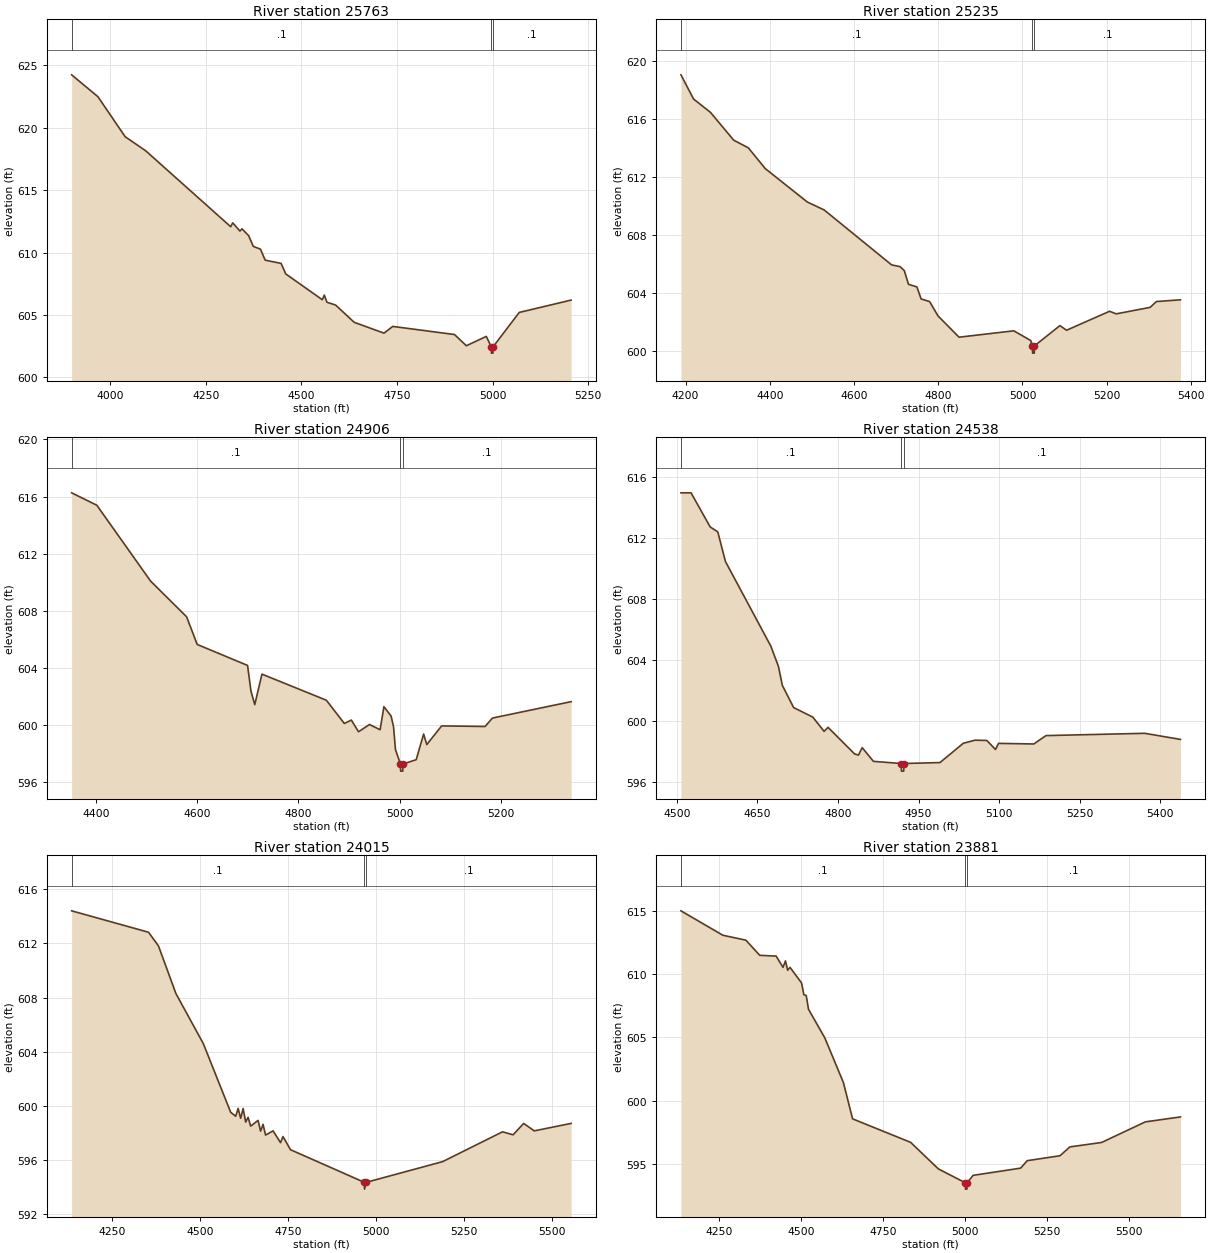
Type RM Length L Ch R = 1,25763,528,528,528
BEGIN DESCRIPTION:
UNT 021 in BCW 39.0
END DESCRIPTION:
XS GIS Cut Line= 3
      1962775.02     13530575.04      1962375.00     13529575.00
      1962254.71     13529379.29
#Sta/Elev= 30
  3898.9  624.25  3967.6  622.50  4039.0  619.29  4092.8  618.16  4315.0  612.08
  4320.3  612.39  4339.2  611.73  4344.6  611.91  4362.1  611.36  4374.2  610.50
  4393.0  610.28  4405.2  609.40  4446.9  609.14  4459.0  608.30  4554.6  606.23
  4560.0  606.60  4566.7  606.03  4589.6  605.80  4638.1  604.42  4716.1  603.55
  4739.0  604.09  4900.6  603.44  4931.6  602.54  4983.7  603.29  4996.9  602.45
  4997.2  601.95  5001.1  601.95  5001.4  602.45  5069.9  605.21  5205.7  606.20
#Mann=3,-1,0
  3898.9     0.1       0  4996.9    0.07       0  5001.4     0.1       0
Bank Sta=4996.9,5001.4
Exp/Cntr=0.3,0.1

Type RM Length L Ch R = 1,25235,329,329,329
BEGIN DESCRIPTION:
UNT 021 in BCW 38.0
END DESCRIPTION:
XS GIS Cut Line= 3
      1962825.00     13530424.99      1962858.40     13529586.85
      1962685.44     13529285.46
#Sta/Elev= 30
  4188.9  619.04  4218.9  617.37  4259.0  616.45  4314.2  614.53  4349.0  614.00
  4389.1  612.57  4489.1  610.26  4529.2  609.71  4689.3  605.92  4709.3  605.80
  4719.3  605.53  4729.3  604.58  4749.3  604.40  4759.3  603.57  4779.4  603.39
  4799.4  602.40  4849.4  600.93  4979.5  601.37  5019.6  600.70  5023.8  600.33
  5024.1  599.83  5028.1  599.83  5028.5  600.33  5089.0  601.73  5104.8  601.41
  5206.9  602.72  5222.7  602.54  5303.3  602.99  5318.1  603.39  5375.2  603.51
#Mann=3,-1,0
  4188.9     0.1       0  5023.8    0.07       0  5028.5     0.1       0
Bank Sta=5023.8,5028.5
Exp/Cntr=0.3,0.1

Type RM Length L Ch R = 1,24906,368,368,368
BEGIN DESCRIPTION:
UNT 021 in BCW 37.0
END DESCRIPTION:
XS GIS Cut Line= 3
      1963575.03     13529925.03      1963075.00     13529475.00
      1962889.85     13529222.54
#Sta/Elev= 30
  4352.3  616.26  4402.0  615.39  4508.2  610.07  4579.2  607.57  4600.1  605.63
  4699.5  604.16  4706.2  602.36  4713.7  601.41  4727.9  603.55  4855.0  601.72
  4890.5  600.09  4904.3  600.33  4918.5  599.51  4940.2  600.02  4961.1  599.65
  4968.6  601.27  4982.8  600.61  4987.6  599.86  4991.4  598.26  5001.3  597.25
  5001.6  596.75  5005.8  596.75  5006.2  597.25  5032.3  597.55  5047.0  599.35
  5053.2  598.61  5082.5  599.92  5168.2  599.88  5182.8  600.47  5338.1  601.62
#Mann=3,-1,0
  4352.3     0.1       0  5001.3    0.07       0  5006.2     0.1       0
Bank Sta=5001.3,5006.2
Exp/Cntr=0.3,0.1

Type RM Length L Ch R = 1,24538,523,523,523
BEGIN DESCRIPTION:
Mapping XS cb7cba1e
END DESCRIPTION:
XS GIS Cut Line= 3
      1963727.52     13529659.27      1963423.68     13529378.00
      1963176.12     13528925.43
#Sta/Elev= 30
  4507.6  614.94  4526.4  614.94  4562.1  612.70  4576.2  612.38  4590.4  610.44
  4674.9  604.89  4689.1  603.56  4696.4  602.31  4717.4  600.86  4753.1  600.23
  4774.1  599.30  4781.5  599.56  4830.8  597.82  4838.1  597.74  4845.0  598.23
  4866.0  597.33  4917.7  597.19  4918.1  596.69  4922.3  596.69  4922.6  597.19
  4989.8  597.25  5033.4  598.52  5055.2  598.72  5077.1  598.70  5093.2  598.11
  5098.9  598.51  5164.4  598.47  5187.2  599.02  5371.1  599.17  5437.5  598.77
#Mann=3,-1,0
  4507.6     0.1       0  4917.7    0.07       0  4922.6     0.1       0
Bank Sta=4917.7,4922.6
Exp/Cntr=0.3,0.1

Type RM Length L Ch R = 1,24015,134,134,134
BEGIN DESCRIPTION:
Mapping XS be35202b
END DESCRIPTION:
XS GIS Cut Line= 3
      1964365.27     13529603.22      1963712.08     13528932.67
      1963230.28     13528932.67
#Sta/Elev= 30
  4136.3  614.41  4354.5  612.83  4382.8  611.82  4432.2  608.31  4510.1  604.61
  4587.8  599.54  4602.0  599.25  4608.9  599.83  4616.1  599.10  4623.1  599.82
  4630.3  598.82  4637.2  599.17  4644.4  598.52  4665.5  598.94  4672.7  598.15
  4679.7  598.65  4686.8  597.86  4708.0  598.17  4729.3  597.30  4736.3  597.75
  4757.6  596.78  4967.3  594.37  4967.7  593.87  4972.3  594.37  5189.5  595.90
  5359.5  598.10  5389.5  597.88  5419.5  598.72  5449.5  598.17  5554.2  598.72
#Mann=3,-1,0
  4136.3     0.1       0  4967.3    0.07       0  4972.3     0.1       0
Bank Sta=4967.3,4972.3
Exp/Cntr=0.3,0.1

Type RM Length L Ch R = 1,23881,794,794,794
BEGIN DESCRIPTION:
Mapping XS 93d4f79e
END DESCRIPTION:
XS GIS Cut Line= 3
      1964519.27     13529541.00      1963796.71     13528871.91
      1963258.16     13528904.35
#Sta/Elev= 30
  4133.2  615.01  4261.0  613.08  4331.3  612.69  4373.8  611.49  4423.7  611.43
  4444.7  610.54  4452.1  611.05  4458.9  610.31  4466.1  610.54  4501.4  609.30
  4508.2  608.38  4515.6  608.31  4522.4  607.23  4572.3  604.96  4629.0  601.43
  4656.9  598.56  4834.1  596.70  4918.7  594.60  5001.2  593.50  5001.6  593.00
  5005.9  593.00  5006.3  593.50  5024.9  594.09  5169.8  594.66  5189.8  595.25
  5290.0  595.64  5320.1  596.34  5417.0  596.69  5550.5  598.32  5657.5  598.71
#Mann=3,-1,0
  4133.2     0.1       0  5001.2    0.07       0  5006.3     0.1       0
Bank Sta=5001.2,5006.3
Exp/Cntr=0.3,0.1

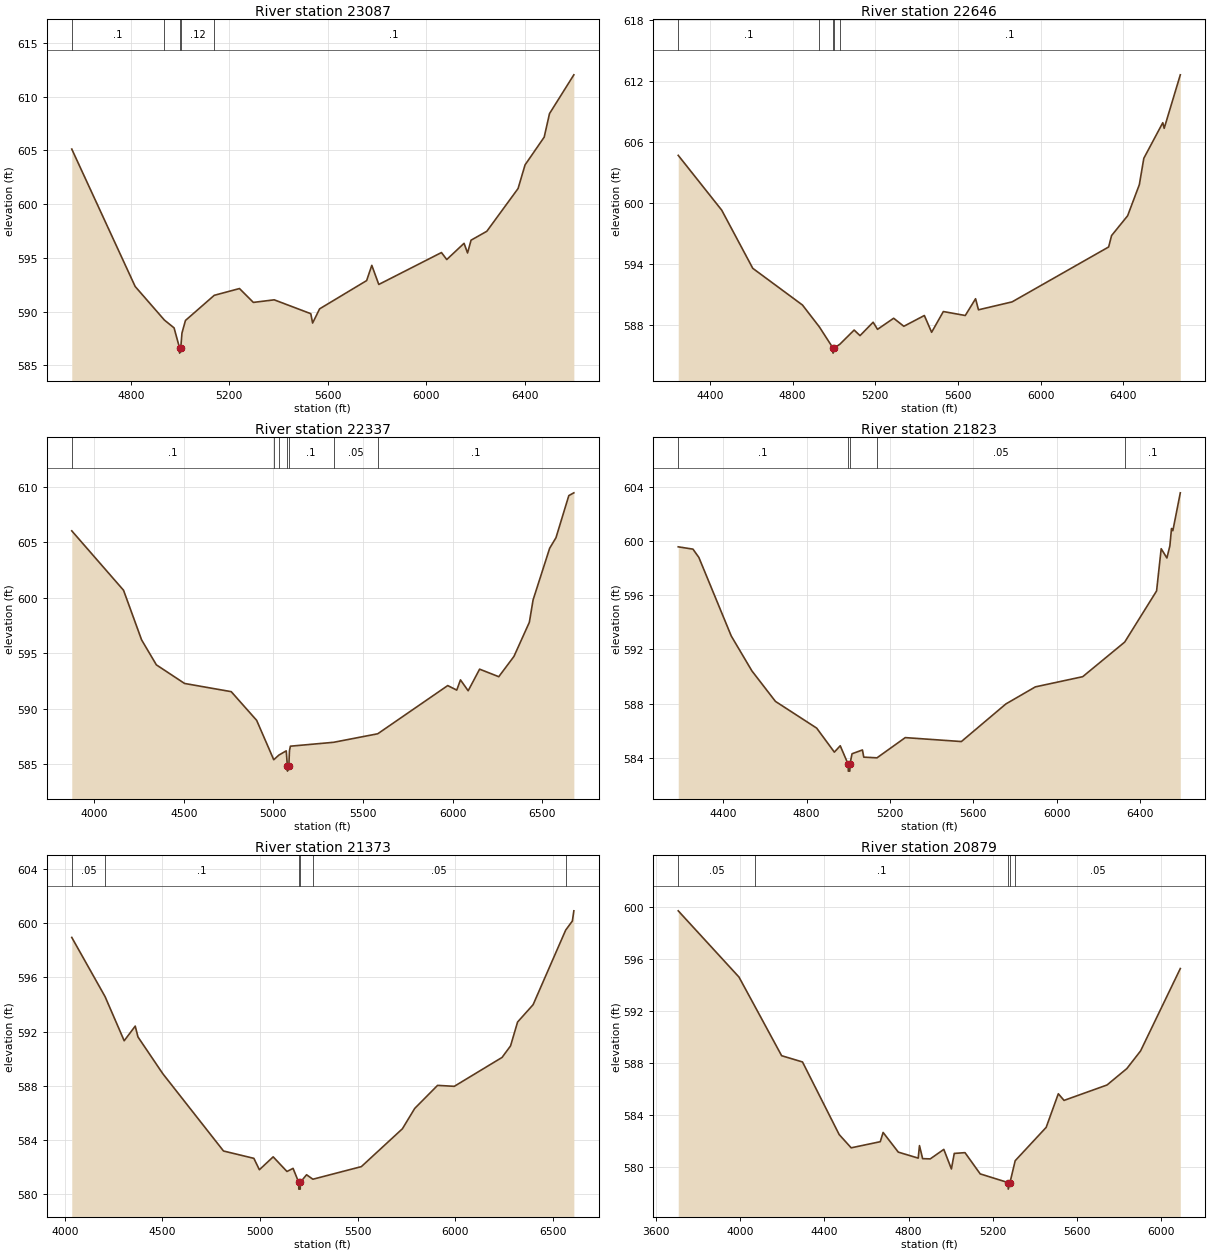
Type RM Length L Ch R = 1,23087,441,441,441
BEGIN DESCRIPTION:
UNT 021 in BCW 33.0
END DESCRIPTION:
XS GIS Cut Line= 3
      1964675.01     13529175.03      1964575.00     13528775.00
      1963475.02     13527575.02
#Sta/Elev= 30
  4559.9  605.13  4817.6  592.34  4936.2  589.22  4975.6  588.49  4997.7  586.64
  4998.1  586.14  5002.8  586.64  5007.7  588.01  5021.9  589.18  5138.9  591.52
  5241.4  592.15  5297.8  590.86  5382.6  591.10  5531.2  589.81  5538.6  588.94
  5567.0  590.26  5758.1  592.89  5779.1  594.31  5807.5  592.53  6062.1  595.50
  6083.7  594.85  6154.0  596.36  6168.2  595.46  6182.4  596.65  6246.5  597.48
  6373.5  601.46  6401.9  603.66  6479.6  606.24  6501.2  608.43  6600.1  612.04
#Mann=5,-1,0
  4559.9     0.1       0  4936.2    0.12       0  4997.7    0.07       0
  5002.8    0.12       0  5138.9     0.1       0
Bank Sta=4997.7,5002.8
Exp/Cntr=0.3,0.1

Type RM Length L Ch R = 1,22646,309,309,309
BEGIN DESCRIPTION:
UNT 021 in BCW 32.0
END DESCRIPTION:
XS GIS Cut Line= 3
      1964875.00     13529324.99      1964925.00     13528525.00
      1963725.03     13527425.02
#Sta/Elev= 30
  4246.9  604.68  4457.3  599.29  4607.6  593.57  4848.1  589.96  4930.1  587.80
  4995.7  585.73  4996.1  585.23  5001.1  585.73  5028.7  586.10  5098.1  587.50
  5126.5  586.95  5190.0  588.27  5211.2  587.57  5289.2  588.66  5338.6  587.87
  5437.8  588.93  5473.0  587.28  5529.7  589.32  5635.8  588.93  5685.7  590.58
  5699.6  589.49  5862.4  590.27  6329.5  595.67  6343.7  596.79  6421.4  598.74
  6478.1  601.80  6499.7  604.39  6591.5  607.89  6598.3  607.34  6676.3  612.60
#Mann=5,-1,0
  4246.9     0.1       0  4930.1    0.12       0  4995.7    0.07       0
  5001.1    0.12       0  5028.7     0.1       0
Bank Sta=4995.7,5001.1
Exp/Cntr=0.3,0.1

Type RM Length L Ch R = 1,22337,514,514,514
BEGIN DESCRIPTION:
UNT 021 in BCW 31.0
END DESCRIPTION:
XS GIS Cut Line= 3
      1965424.99     13529474.98      1965125.00     13528275.00
      1964124.97     13527074.97
#Sta/Elev= 30
  3876.0  606.03  4164.6  600.67  4265.1  596.20  4347.6  593.94  4504.8  592.26
  4765.0  591.52  4906.8  588.93  5002.0  585.38  5030.9  585.80  5071.7  586.18
  5077.8  584.85  5078.3  584.35  5086.1  584.85  5089.7  586.20  5094.9  586.60
  5335.4  586.95  5581.8  587.72  5972.0  592.07  6022.2  591.66  6043.0  592.58
  6085.9  591.60  6149.7  593.55  6256.5  592.87  6341.1  594.70  6427.0  597.78
  6447.8  599.80  6540.2  604.46  6575.4  605.41  6647.0  609.21  6675.0  609.46
#Mann=7,-1,0
  3876.0     0.1       0  5002.0    0.12       0  5030.9     0.1       0
  5077.8    0.07       0  5086.1     0.1       0  5335.4    0.05       0
  5581.8     0.1       0
Bank Sta=5077.8,5086.1
Exp/Cntr=0.3,0.1

Type RM Length L Ch R = 1,21823,450,450,450
BEGIN DESCRIPTION:
UNT 021 in BCW 30.0
END DESCRIPTION:
XS GIS Cut Line= 3
      1966125.02     13528675.02      1965525.00     13528075.00
      1964325.01     13527075.00
#Sta/Elev= 30
  4183.5  599.56  4254.2  599.39  4282.5  598.78  4438.1  592.99  4537.1  590.42
  4650.2  588.17  4848.2  586.20  4933.1  584.43  4961.3  584.90  4999.6  583.53
  5000.1  583.03  5007.4  583.03  5007.9  583.53  5017.9  584.31  5067.9  584.59
  5074.4  584.06  5137.8  584.01  5273.5  585.50  5543.0  585.21  5756.5  587.98
  5898.3  589.24  6125.5  589.99  6327.1  592.54  6480.2  596.31  6502.3  599.42
  6529.7  598.74  6544.0  599.63  6551.8  600.91  6558.3  600.75  6594.1  603.54
#Mann=5,-1,0
  4183.5     0.1       0  4999.6    0.07       0  5007.9     0.1       0
  5137.8    0.05       0  6327.1     0.1       0
Bank Sta=4999.6,5007.9
Exp/Cntr=0.3,0.1

Type RM Length L Ch R = 1,21373,494,494,494
BEGIN DESCRIPTION:
UNT 021 in BCW 29.0
END DESCRIPTION:
XS GIS Cut Line= 3
      1966525.03     13528475.03      1965725.00     13527675.00
      1964525.02     13526875.02
#Sta/Elev= 30
  4035.0  598.94  4205.5  594.58  4303.7  591.32  4360.3  592.40  4374.4  591.60
  4501.7  588.89  4812.9  583.19  4968.4  582.65  4996.7  581.81  5067.4  582.76
  5138.1  581.68  5169.4  581.91  5198.3  580.88  5198.8  580.38  5206.1  580.38
  5206.6  580.88  5238.5  581.44  5270.9  581.11  5519.5  582.04  5729.8  584.83
  5792.9  586.33  5910.1  588.03  5995.7  587.96  6240.6  590.09  6284.1  590.94
  6320.2  592.70  6399.8  593.98  6566.8  599.48  6601.1  600.15  6608.6  600.90
#Mann=6,-1,0
  4035.0    0.05       0  4205.5     0.1       0  5198.3    0.07       0
  5206.6     0.1       0  5270.9    0.05       0  6566.8     0.1       0
Bank Sta=5198.3,5206.6
Exp/Cntr=0.3,0.1

Type RM Length L Ch R = 1,20879,654,654,654
BEGIN DESCRIPTION:
UNT 021 in BCW 28.0
END DESCRIPTION:
XS GIS Cut Line= 3
      1966625.03     13528425.04      1965825.00     13527225.00
      1965024.97     13526724.98
#Sta/Elev= 30
  3705.8  599.70  3994.3  594.62  4071.7  592.32  4197.1  588.58  4296.3  588.10
  4470.5  582.53  4527.6  581.51  4665.8  581.98  4679.3  582.69  4751.5  581.18
  4846.1  580.72  4852.1  581.68  4867.1  580.68  4903.2  580.66  4967.8  581.39
  5003.8  579.89  5017.4  581.08  5068.4  581.14  5140.6  579.51  5273.4  578.84
  5273.9  578.34  5282.1  578.84  5306.9  580.52  5454.1  583.08  5511.9  585.66
  5539.0  585.15  5743.0  586.33  5837.3  587.59  5902.8  588.95  6091.5  595.27
#Mann=5,-1,0
  3705.8    0.05       0  4071.7     0.1       0  5273.4    0.07       0
  5282.1     0.1       0  5306.9    0.05       0
Bank Sta=5273.4,5282.1
Exp/Cntr=0.3,0.1