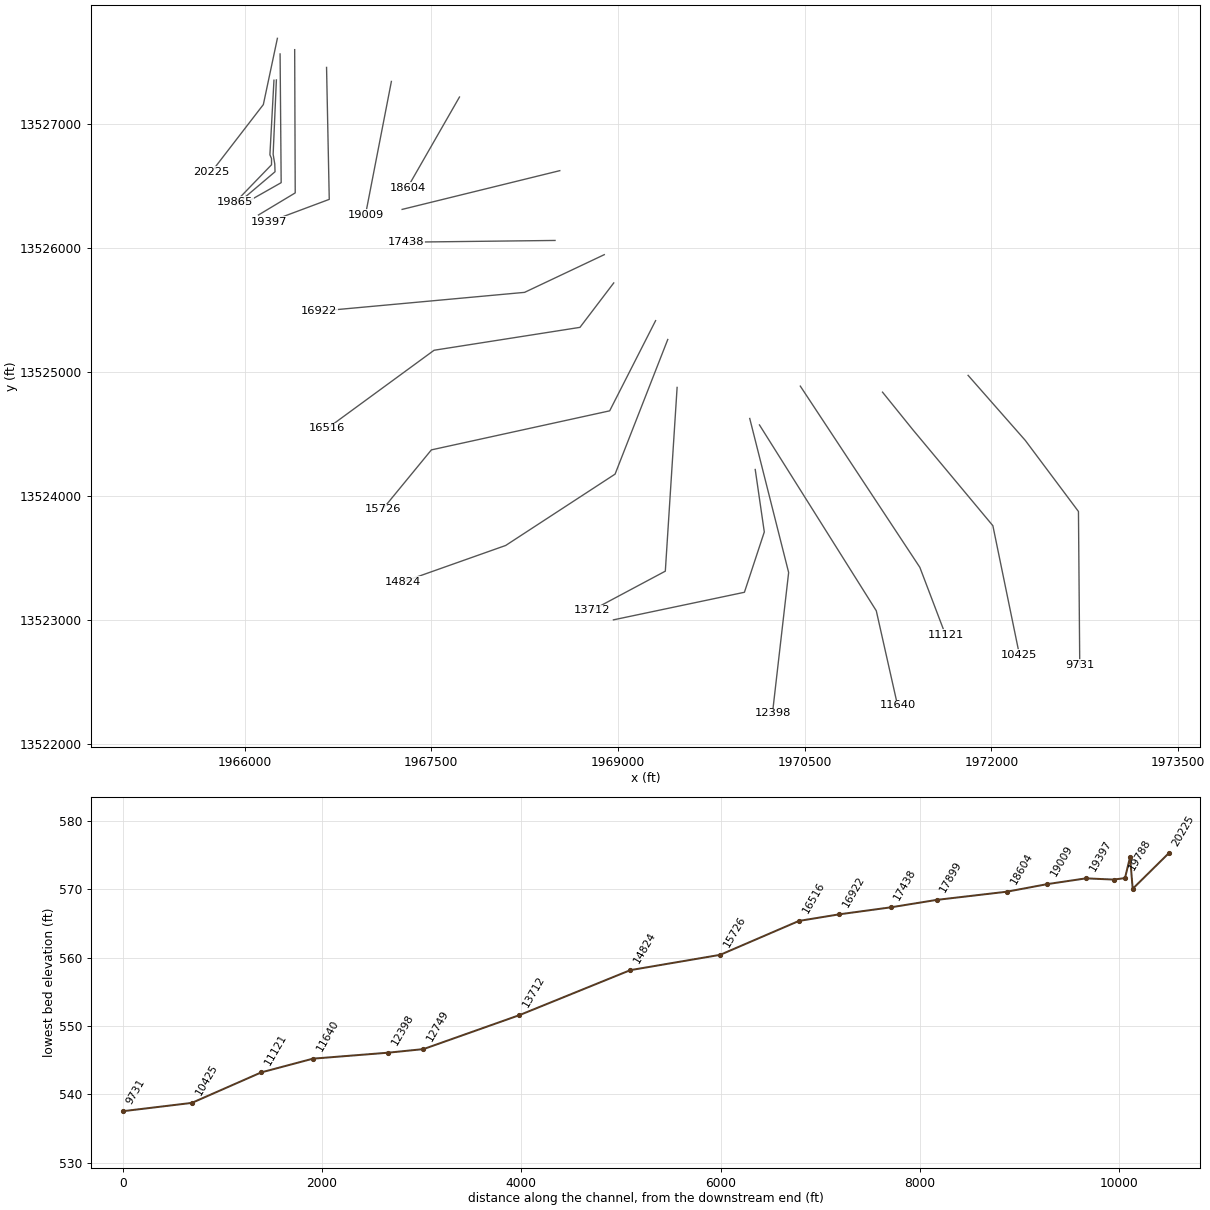
HEC-RAS study UNT 021 in BCW.prj: UNT 021 in BCW Base Level Engineering

--- UNT 021 in BCW.g01 (geometry) --- (continued)

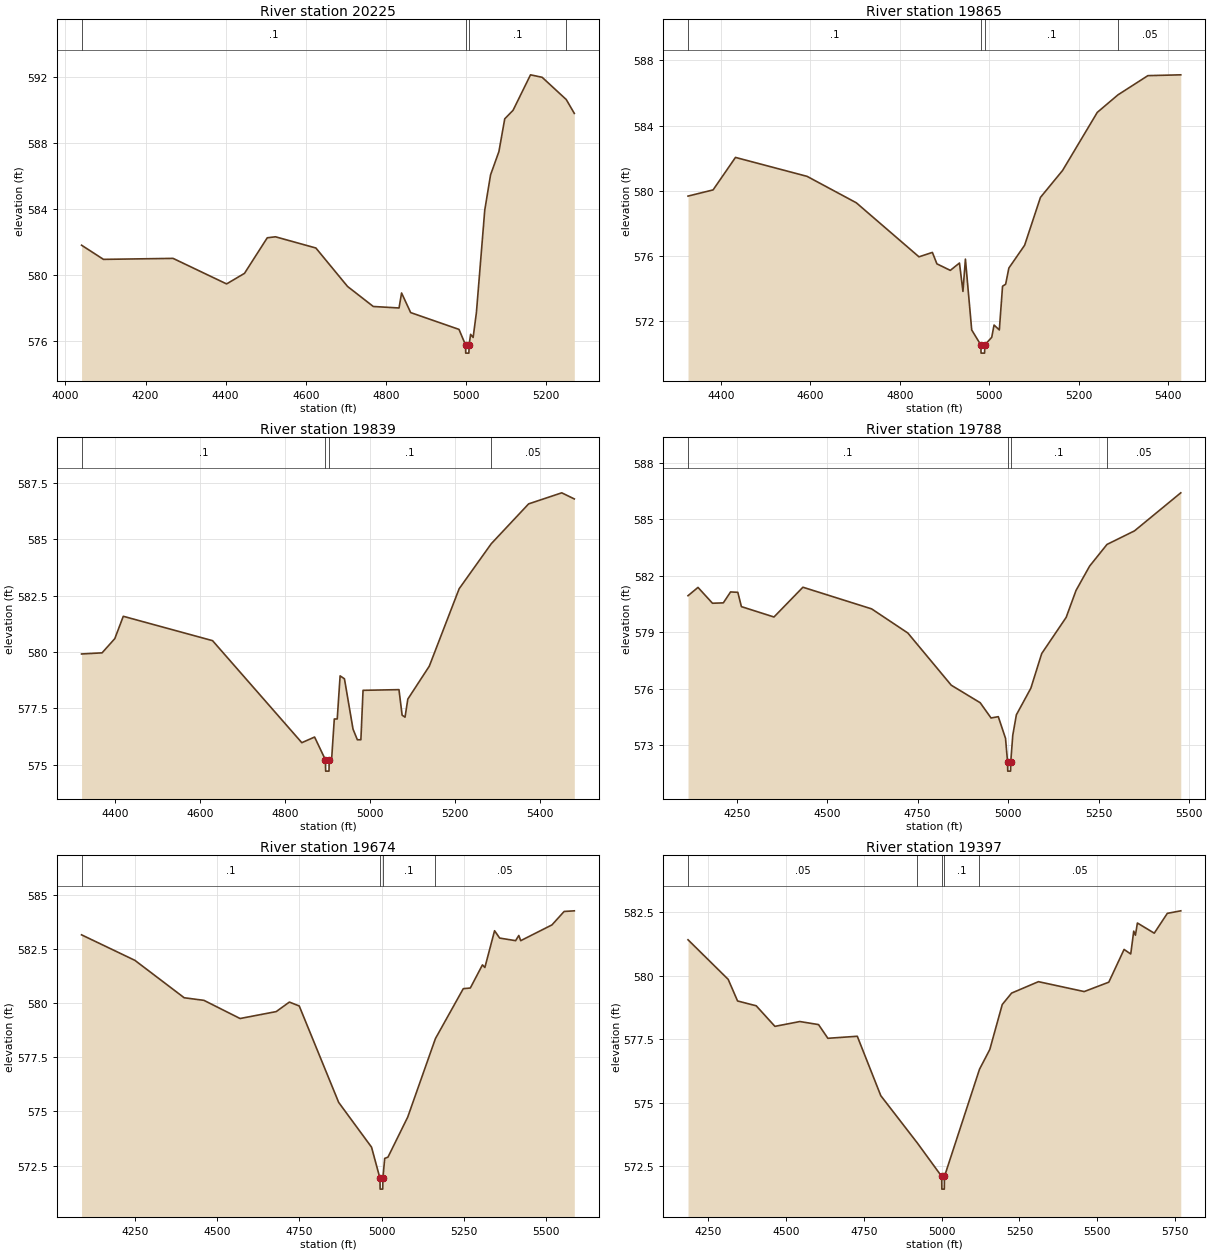
Type RM Length L Ch R = 1,20225,360,360,360
BEGIN DESCRIPTION:
Mapping XS 784cabab
END DESCRIPTION:
XS GIS Cut Line= 3
      1966263.96     13527688.51      1966151.10     13527154.63
      1965734.41     13526612.06
#Sta/Elev= 30
  4040.4  581.79  4095.1  580.93  4268.8  580.99  4402.4  579.44  4447.0  580.08
  4503.9  582.24  4524.4  582.30  4625.2  581.62  4704.1  579.29  4768.5  578.07
  4832.8  577.98  4839.1  578.89  4861.8  577.70  4982.4  576.68  4998.7  575.74
  4999.2  575.24  5007.1  575.24  5007.6  575.74  5011.4  576.38  5017.7  576.19
  5025.9  577.71  5046.7  583.92  5061.2  586.06  5082.0  587.47  5096.6  589.46
  5117.4  589.98  5160.9  592.13  5189.9  591.98  5250.1  590.63  5270.2  589.79
#Mann=4,-1,0
  4040.4     0.1       0  4998.7    0.07       0  5007.6     0.1       0
  5250.1    0.05       0
Bank Sta=4998.7,5007.6
Exp/Cntr=0.3,0.1

Type RM Length L Ch R = 1,19865,26,26,26
BEGIN DESCRIPTION:
Mapping XS aeea166e
END DESCRIPTION:
XS GIS Cut Line= 5
      1966236.38     13527351.05      1966203.83     13526749.95
      1966216.85     13526719.56      1966216.85     13526669.65
      1965926.99     13526368.97
#Sta/Elev= 30
  4326.2  579.68  4382.3  580.06  4432.4  582.05  4592.6  580.89  4702.8  579.27
  4843.0  575.96  4873.0  576.23  4883.1  575.53  4913.1  575.13  4933.6  575.58
  4941.4  573.84  4946.9  575.82  4961.0  571.48  4981.4  570.56  4981.9  570.06
  4989.8  570.06  4990.3  570.56  5005.8  571.03  5011.0  571.78  5022.8  571.48
  5030.0  574.16  5036.9  574.28  5044.1  575.27  5079.4  576.67  5114.8  579.60
  5164.3  581.25  5242.0  584.81  5288.1  585.88  5355.2  587.06  5428.8  587.11
#Mann=4,-1,0
  4326.2     0.1       0  4981.4    0.07       0  4990.3     0.1       0
  5288.1    0.05       0
Bank Sta=4981.4,4990.3
Exp/Cntr=0.3,0.1

Type RM Length L Ch R = 1,19839,51,51,51
BEGIN DESCRIPTION:
Mapping XS 99655a40
END DESCRIPTION:
XS GIS Cut Line= 5
      1966255.91     13527353.24      1966229.87     13526754.29
      1966242.89     13526676.16      1966245.06     13526613.23
      1965926.09     13526341.99
#Sta/Elev= 30
  4321.1  579.91  4369.4  579.96  4399.4  580.59  4419.4  581.58  4629.6  580.50
  4839.8  575.98  4869.9  576.23  4895.4  575.22  4895.9  574.72  4903.8  574.72
  4904.3  575.22  4909.9  575.22  4916.3  577.03  4923.2  577.03  4930.0  578.94
  4940.2  578.81  4960.4  576.58  4970.6  576.11  4978.9  576.11  4984.0  578.30
  5068.6  578.33  5076.0  577.20  5082.9  577.11  5089.4  577.91  5140.0  579.37
  5210.3  582.80  5285.7  584.79  5373.9  586.56  5451.9  587.05  5481.5  586.78
#Mann=4,-1,0
  4321.1     0.1       0  4895.4    0.07       0  4904.3     0.1       0
  5285.7    0.05       0
Bank Sta=4895.4,4904.3
Exp/Cntr=0.3,0.1

Type RM Length L Ch R = 1,19788,114,114,114
BEGIN DESCRIPTION:
Mapping XS d3eecf0c
END DESCRIPTION:
XS GIS Cut Line= 3
      1966285.65     13527562.59      1966294.33     13526525.29
      1966012.18     13526364.68
#Sta/Elev= 30
  4115.2  580.94  4142.8  581.38  4182.8  580.54  4212.8  580.56  4232.8  581.14
  4252.8  581.12  4262.8  580.36  4352.8  579.81  4432.8  581.39  4622.8  580.24
  4722.8  578.96  4842.8  576.19  4922.8  575.26  4952.8  574.45  4972.8  574.52
  4992.8  573.37  4998.4  572.13  4998.9  571.63  5006.8  571.63  5007.3  572.13
  5012.8  573.53  5022.8  574.62  5062.8  576.03  5092.8  577.87  5160.4  579.79
  5187.7  581.22  5225.2  582.51  5273.2  583.66  5349.2  584.38  5477.2  586.40
#Mann=4,-1,0
  4115.2     0.1       0  4998.4    0.07       0  5007.3     0.1       0
  5273.2    0.05       0
Bank Sta=4998.4,5007.3
Exp/Cntr=0.3,0.1

Type RM Length L Ch R = 1,19674,277,277,277
BEGIN DESCRIPTION:
Mapping XS 249399bd
END DESCRIPTION:
XS GIS Cut Line= 3
      1966402.84     13527597.33      1966407.18     13526442.82
      1966112.00     13526264.85
#Sta/Elev= 30
  4087.2  583.17  4249.5  581.99  4399.5  580.26  4459.5  580.14  4569.5  579.30
  4679.5  579.62  4719.5  580.06  4749.5  579.88  4869.5  575.42  4969.5  573.35
  4995.1  571.91  4995.6  571.41  5003.5  571.41  5004.0  571.91  5009.5  572.83
  5019.5  572.89  5079.5  574.74  5163.8  578.37  5248.6  580.68  5270.0  580.71
  5306.9  581.78  5314.3  581.66  5343.8  583.36  5359.3  583.02  5407.8  582.90
  5417.5  583.14  5423.4  582.90  5518.5  583.63  5555.4  584.25  5586.4  584.28
#Mann=4,-1,0
  4087.2     0.1       0  4995.1    0.07       0  5004.0     0.1       0
  5163.8    0.05       0
Bank Sta=4995.1,5004
Exp/Cntr=0.3,0.1

Type RM Length L Ch R = 1,19397,388,388,388
BEGIN DESCRIPTION:
Mapping XS adcd8a47
END DESCRIPTION:
XS GIS Cut Line= 3
      1966658.92     13527454.08      1966680.62     13526390.74
      1966194.54     13526208.46
#Sta/Elev= 30
  4185.4  581.41  4314.5  579.85  4344.5  579.00  4404.5  578.81  4464.5  578.00
  4544.6  578.19  4604.6  578.07  4634.6  577.53  4729.1  577.61  4804.6  575.27
  4922.4  573.40  5000.2  572.09  5000.7  571.59  5008.6  571.59  5009.1  572.09
  5121.6  576.31  5154.7  577.09  5194.7  578.86  5224.7  579.31  5310.9  579.76
  5457.9  579.37  5536.9  579.74  5586.0  581.03  5607.4  580.85  5617.0  581.75
  5622.4  581.59  5628.8  582.07  5682.9  581.67  5724.9  582.45  5768.1  582.55
#Mann=5,-1,0
  4185.4    0.05       0  4922.4     0.1       0  5000.2    0.07       0
  5009.1     0.1       0  5121.6    0.05       0
Bank Sta=5000.2,5009.1
Exp/Cntr=0.3,0.1

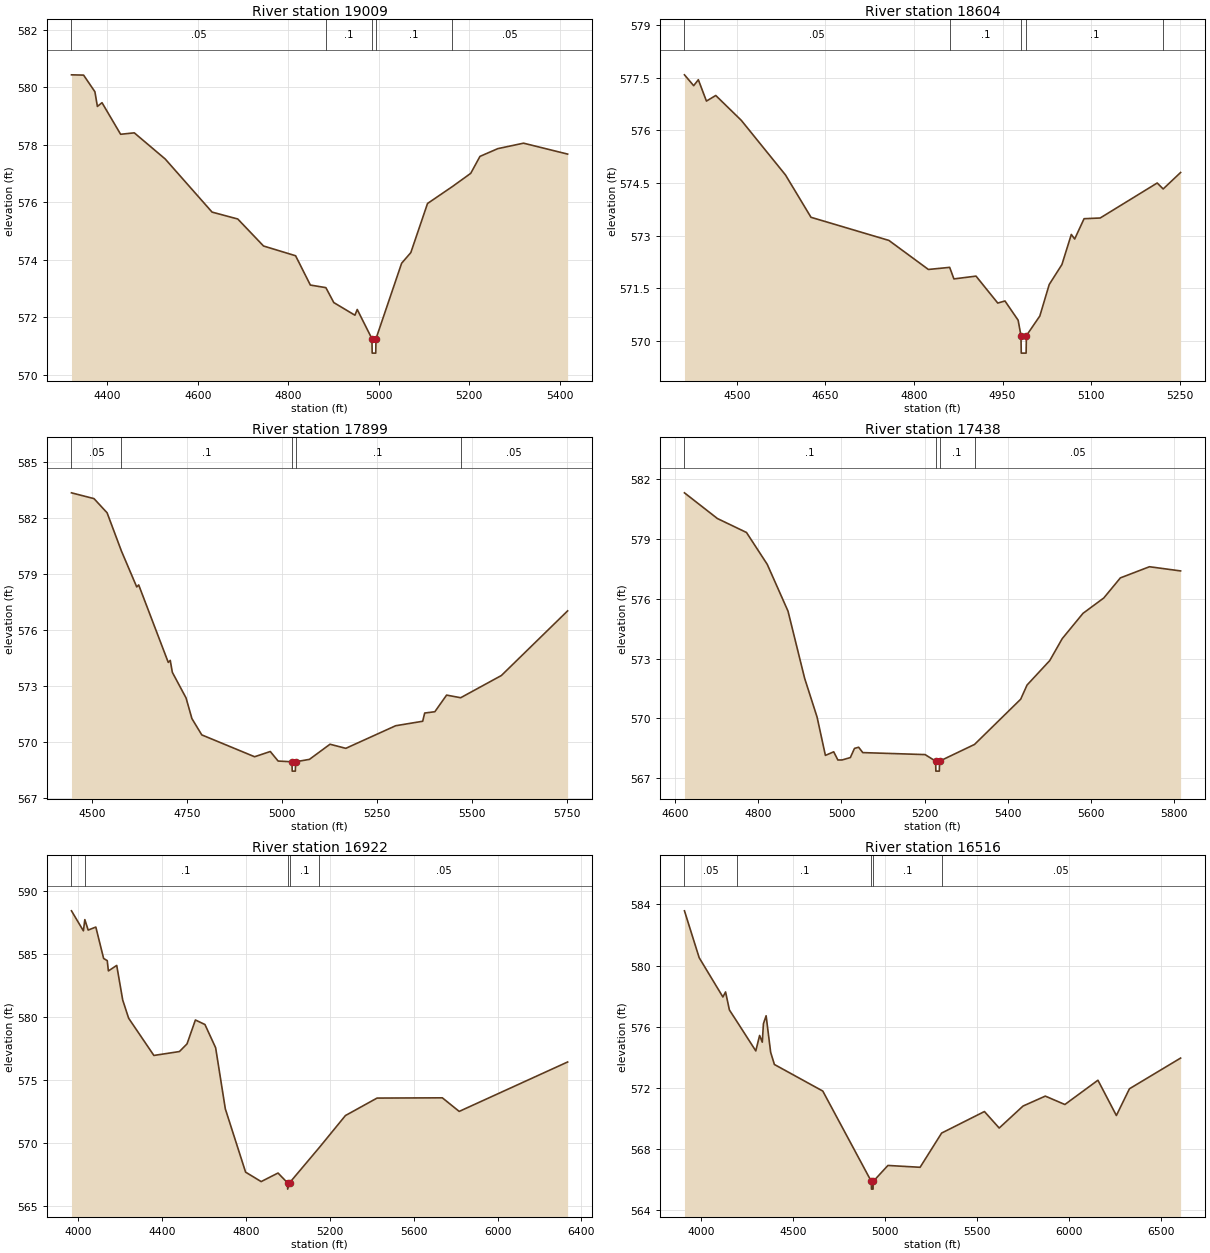
Type RM Length L Ch R = 1,19009,405,405,405
BEGIN DESCRIPTION:
Mapping XS 2b9924e9
END DESCRIPTION:
XS GIS Cut Line= 2
      1967179.75     13527341.26      1966971.41     13526264.84
#Sta/Elev= 30
  4320.9  580.44  4347.7  580.43  4372.7  579.85  4378.2  579.34  4388.4  579.47
  4429.5  578.37  4459.7  578.42  4528.0  577.51  4631.6  575.66  4688.4  575.42
  4745.3  574.48  4816.2  574.14  4848.8  573.12  4883.1  573.03  4900.6  572.51
  4947.3  572.07  4952.4  572.27  4984.9  571.25  4985.4  570.75  4993.3  570.75
  4993.8  571.25  5050.5  573.88  5070.8  574.25  5107.7  575.96  5162.7  576.55
  5203.2  577.01  5223.6  577.60  5263.1  577.87  5319.9  578.06  5417.3  577.68
#Mann=5,-1,0
  4320.9    0.05       0  4883.1     0.1       0  4984.9    0.07       0
  4993.8     0.1       0  5162.7    0.05       0
Bank Sta=4984.9,4993.8
Exp/Cntr=0.3,0.1

Type RM Length L Ch R = 1,18604,705,705,705
BEGIN DESCRIPTION:
Mapping XS 5e87d2f8
END DESCRIPTION:
XS GIS Cut Line= 2
      1967726.64     13527215.41      1967309.98     13526486.26
#Sta/Elev= 30
  4411.6  577.59  4427.2  577.28  4435.1  577.45  4448.8  576.84  4464.6  577.00
  4507.8  576.29  4582.6  574.73  4625.8  573.52  4757.6  572.86  4824.5  572.03
  4860.5  572.09  4867.7  571.76  4905.1  571.84  4941.9  571.07  4954.1  571.13
  4976.4  570.58  4981.2  570.14  4981.7  569.64  4989.9  569.64  4990.4  570.14
  5013.1  570.70  5029.0  571.60  5050.5  572.17  5066.4  573.03  5072.1  572.90
  5088.0  573.48  5115.3  573.50  5211.8  574.50  5221.9  574.33  5251.4  574.80
#Mann=5,-1,0
  4411.6    0.05       0  4860.5     0.1       0  4981.2    0.07       0
  4990.4     0.1       0  5221.9    0.05       0
Bank Sta=4981.2,4990.4
Exp/Cntr=0.3,0.1

Type RM Length L Ch R = 1,17899,461,461,461
BEGIN DESCRIPTION:
Mapping XS 5ef5106f
END DESCRIPTION:
XS GIS Cut Line= 2
      1968532.48     13526622.08      1967266.01     13526309.80
#Sta/Elev= 30
  4446.5  583.34  4505.7  583.03  4540.2  582.27  4577.9  580.22  4618.1  578.30
  4623.2  578.41  4701.0  574.26  4706.2  574.37  4711.7  573.73  4747.7  572.36
  4763.2  571.25  4789.1  570.38  4928.0  569.21  4969.2  569.49  4989.8  568.98
  5026.3  568.94  5026.8  568.44  5035.1  568.44  5035.6  568.94  5072.2  569.07
  5126.2  569.88  5167.7  569.66  5298.8  570.87  5369.9  571.11  5375.1  571.55
  5401.8  571.62  5432.7  572.51  5469.8  572.37  5576.8  573.56  5750.9  577.02
#Mann=5,-1,0
  4446.5    0.05       0  4577.9     0.1       0  5026.3    0.07       0
  5035.6     0.1       0  5469.8    0.05       0
Bank Sta=5026.3,5035.6
Exp/Cntr=0.3,0.1

Type RM Length L Ch R = 1,17438,516,516,516
BEGIN DESCRIPTION:
Mapping XS d649be08
END DESCRIPTION:
XS GIS Cut Line= 2
      1968494.31     13526059.59      1967299.99     13526045.71
#Sta/Elev= 30
  4622.1  581.32  4701.4  580.03  4771.4  579.33  4821.4  577.73  4871.4  575.38
  4911.4  572.01  4941.4  570.06  4961.4  568.14  4981.4  568.32  4991.4  567.91
  5001.4  567.91  5021.4  568.03  5031.4  568.49  5041.4  568.55  5051.4  568.28
  5201.4  568.18  5226.8  567.85  5227.3  567.35  5235.7  567.35  5236.2  567.85
  5320.4  568.69  5431.5  570.96  5446.8  571.67  5501.5  572.90  5531.5  574.00
  5581.5  575.27  5631.5  576.04  5671.5  577.05  5741.5  577.61  5816.5  577.40
#Mann=4,-1,0
  4622.1     0.1       0  5226.8    0.07       0  5236.2     0.1       0
  5320.4    0.05       0
Bank Sta=5226.8,5236.2
Exp/Cntr=0.3,0.1

Type RM Length L Ch R = 1,16922,406,406,406
BEGIN DESCRIPTION:
Mapping XS 35d54e6a
END DESCRIPTION:
XS GIS Cut Line= 3
      1968889.89     13525945.06      1968249.71     13525641.24
      1966600.41     13525489.33
#Sta/Elev= 30
  3969.2  588.46  4026.0  586.87  4032.9  587.76  4048.8  586.93  4085.3  587.17
  4122.5  584.67  4139.7  584.50  4145.2  583.68  4184.9  584.12  4213.4  581.37
  4241.7  579.92  4362.0  576.96  4483.8  577.27  4520.0  577.88  4559.9  579.78
  4605.4  579.42  4656.4  577.57  4702.6  572.71  4799.2  567.68  4873.4  566.93
  4953.7  567.61  4999.2  566.83  4999.7  566.33  5008.6  566.83  5150.6  569.64
  5275.0  572.18  5425.7  573.57  5737.0  573.59  5817.3  572.51  6334.1  576.44
#Mann=5,-1,0
  3969.2    0.05       0  4032.9     0.1       0  4999.2    0.07       0
  5008.6     0.1       0  5150.6    0.05       0
Bank Sta=4999.2,5008.6
Exp/Cntr=0.3,0.1

Type RM Length L Ch R = 1,16516,790,790,790
BEGIN DESCRIPTION:
Mapping XS 87a9458a
END DESCRIPTION:
XS GIS Cut Line= 4
      1968965.85     13525717.18      1968694.59     13525359.13
      1967522.72     13525174.66      1966665.54     13524545.34
#Sta/Elev= 30
  3909.2  583.58  3989.3  580.51  4118.3  577.94  4132.8  578.27  4153.7  577.09
  4195.8  576.31  4297.2  574.41  4318.0  575.42  4332.6  574.98  4338.8  576.19
  4353.4  576.71  4378.2  574.31  4398.5  573.52  4661.7  571.78  4925.9  565.86
  4926.4  565.36  4935.1  565.36  4935.6  565.86  5016.0  566.91  5191.0  566.79
  5308.1  569.03  5541.0  570.44  5621.3  569.36  5751.0  570.80  5872.1  571.45
  5978.6  570.90  6158.4  572.49  6258.7  570.18  6329.8  571.93  6608.1  573.94
#Mann=5,-1,0
  3909.2    0.05       0  4195.8     0.1       0  4925.9    0.07       0
  4935.6     0.1       0  5308.1    0.05       0
Bank Sta=4925.9,4935.6
Exp/Cntr=0.3,0.1

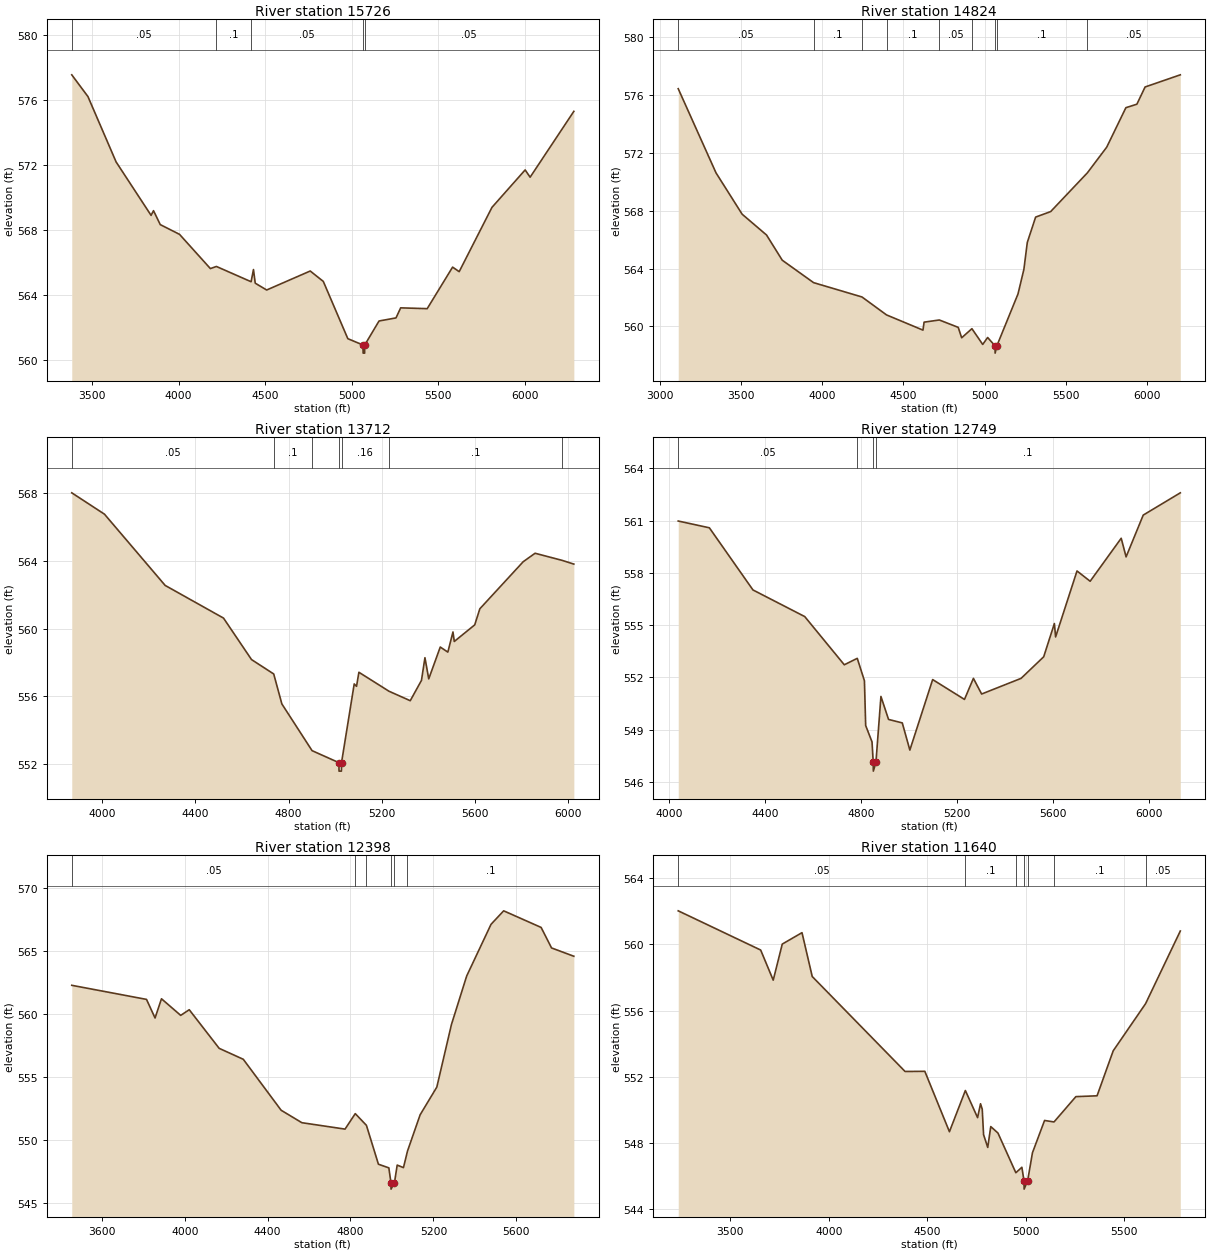
Type RM Length L Ch R = 1,15726,902,902,902
BEGIN DESCRIPTION:
Mapping XS a6b24e54
END DESCRIPTION:
XS GIS Cut Line= 4
      1969302.22     13525413.36      1968933.31     13524686.38
      1967501.02     13524371.71      1967110.42     13523894.32
#Sta/Elev= 30
  3383.6  577.55  3477.0  576.21  3639.7  572.18  3841.5  568.89  3855.5  569.18
  3894.4  568.32  4005.7  567.72  4183.8  565.61  4218.7  565.74  4418.9  564.80
  4432.6  565.55  4442.8  564.71  4508.8  564.29  4760.2  565.46  4835.7  564.82
  4977.3  561.29  5065.1  560.90  5065.6  560.40  5074.4  560.40  5074.9  560.90
  5157.5  562.38  5255.3  562.57  5282.4  563.19  5435.5  563.14  5582.2  565.70
  5620.2  565.42  5809.3  569.38  6001.0  571.69  6029.7  571.24  6282.1  575.30
#Mann=5,-1,0
  3383.6    0.05       0  4218.7     0.1       0  4418.9    0.05       0
  5065.1   0.035       0  5074.9    0.05       0
Bank Sta=5065.1,5074.9
Exp/Cntr=0.3,0.1

Type RM Length L Ch R = 1,14824,1112,1112,1112
BEGIN DESCRIPTION:
Mapping XS c544575d
END DESCRIPTION:
XS GIS Cut Line= 4
      1969399.87     13525261.43      1968976.71     13524176.40
      1968097.81     13523601.31      1967273.16     13523308.35
#Sta/Elev= 30
  3114.6  576.43  3346.9  570.62  3507.9  567.76  3658.2  566.32  3754.8  564.58
  3947.6  563.03  4245.5  562.04  4396.6  560.80  4620.8  559.75  4627.8  560.30
  4721.6  560.45  4837.9  559.94  4859.0  559.22  4922.1  559.85  4988.6  558.76
  5018.9  559.24  5064.5  558.66  5065.0  558.16  5075.5  558.66  5205.8  562.25
  5242.0  563.95  5263.0  565.81  5314.3  567.56  5406.8  567.94  5632.9  570.62
  5751.7  572.39  5869.8  575.12  5937.4  575.36  5987.9  576.55  6204.7  577.39
#Mann=9,-1,0
  3114.6    0.05       0  3947.6     0.1       0  4245.5    0.05       0
  4396.6     0.1       0  4721.6    0.05       0  4922.1     0.1       0
  5064.5    0.07       0  5075.5     0.1       0  5632.9    0.05       0
Bank Sta=5064.5,5075.5
Exp/Cntr=0.3,0.1

Type RM Length L Ch R = 1,13712,963,963,963
BEGIN DESCRIPTION:
UNT 021 in BCW 19.0
END DESCRIPTION:
XS GIS Cut Line= 3
      1969475.00     13524875.05      1969380.27     13523394.21
      1968788.26     13523077.43
#Sta/Elev= 30
  3869.0  568.02  4009.3  566.76  4269.9  562.55  4520.4  560.62  4640.6  558.17
  4735.9  557.32  4770.9  555.55  4900.5  552.79  5015.8  552.08  5016.3  551.58
  5026.5  551.58  5027.0  552.08  5081.5  556.73  5091.5  556.59  5101.6  557.42
  5230.7  556.30  5322.0  555.74  5370.2  556.94  5385.1  558.28  5401.4  557.03
  5450.9  558.91  5483.4  558.61  5505.4  559.80  5511.1  559.24  5598.8  560.22
  5620.8  561.17  5806.9  563.95  5857.9  564.45  5974.1  564.03  6024.3  563.81
#Mann=7,-1,0
  3869.0    0.05       0  4735.9     0.1       0  4900.5    0.16       0
  5015.8    0.07       0  5027.0    0.16       0  5230.7     0.1       0
  5974.1    0.05       0
Bank Sta=5015.8,5027
Exp/Cntr=0.3,0.1

Type RM Length L Ch R = 1,12749,351,351,351
BEGIN DESCRIPTION:
UNT 021 in BCW 18.0
END DESCRIPTION:
XS GIS Cut Line= 4
      1970102.50     13524213.64      1970175.41     13523710.18
      1970015.69     13523224.07      1968963.58     13523001.85
#Sta/Elev= 30
  4036.8  560.98  4166.8  560.59  4348.7  557.02  4564.8  555.49  4729.9  552.72
  4784.1  553.09  4814.0  551.80  4819.2  549.23  4845.7  548.29  4850.7  547.11
  4851.2  546.61  4862.0  547.11  4882.9  550.90  4914.7  549.58  4972.0  549.38
  5003.6  547.82  5098.8  551.87  5231.6  550.73  5268.9  551.94  5303.2  551.04
  5467.9  551.94  5562.3  553.18  5606.9  555.09  5612.0  554.32  5701.3  558.11
  5756.2  557.52  5885.8  559.99  5906.2  558.92  5977.7  561.32  6132.5  562.60
#Mann=4,-1,0
  4036.8    0.05       0  4784.1     0.1       0  4850.7    0.07       0
  4862.0     0.1       0
Bank Sta=4850.7,4862
Exp/Cntr=0.3,0.1

Type RM Length L Ch R = 1,12398,758,758,758
BEGIN DESCRIPTION:
UNT 021 in BCW 17.0
END DESCRIPTION:
XS GIS Cut Line= 3
      1970058.45     13524624.76      1970370.95     13523383.43
      1970240.95     13522248.11
#Sta/Elev= 30
  3455.0  562.29  3815.7  561.17  3856.9  559.69  3887.9  561.22  3980.7  559.90
  4021.9  560.35  4166.3  557.28  4282.7  556.41  4465.3  552.36  4565.3  551.37
  4773.7  550.86  4823.0  552.09  4876.9  551.16  4934.8  548.07  4985.1  547.78
  4995.3  546.59  4995.8  546.09  5012.0  546.59  5025.4  548.00  5055.6  547.80
  5075.0  549.11  5136.1  552.00  5216.6  554.20  5287.1  559.17  5360.7  563.03
  5478.3  567.14  5539.2  568.21  5719.9  566.89  5770.2  565.26  5877.8  564.60
#Mann=6,-1,0
  3455.0    0.05       0  4823.0     0.1       0  4876.9    0.07       0
  4995.3    0.07       0  5012.0    0.07       0  5075.0     0.1       0
Bank Sta=4995.3,5012
Exp/Cntr=0.3,0.1

Type RM Length L Ch R = 1,11640,519,519,519
BEGIN DESCRIPTION:
UNT 021 in BCW 16.0
END DESCRIPTION:
XS GIS Cut Line= 3
      1970136.56     13524572.69      1971075.00     13523075.00
      1971245.96     13522312.65
#Sta/Elev= 30
  3235.3  562.03  3653.8  559.66  3717.5  557.84  3763.4  560.02  3863.6  560.71
  3915.5  558.06  4386.9  552.32  4487.1  552.33  4612.0  548.68  4692.9  551.17
  4754.9  549.53  4769.9  550.37  4778.5  550.04  4785.3  548.50  4806.5  547.73
  4821.8  548.99  4858.3  548.60  4949.1  546.20  4979.7  546.53  4990.7  545.71
  4991.2  545.21  5008.9  545.71  5033.5  547.41  5094.9  549.36  5142.9  549.27
  5253.9  550.80  5361.4  550.85  5443.4  553.57  5607.8  556.42  5784.0  560.81
#Mann=7,-1,0
  3235.3    0.05       0  4692.9     0.1       0  4949.1    0.16       0
  4990.7    0.07       0  5008.9    0.16       0  5142.9     0.1       0
  5607.8    0.05       0
Bank Sta=4990.7,5008.9
Exp/Cntr=0.3,0.1

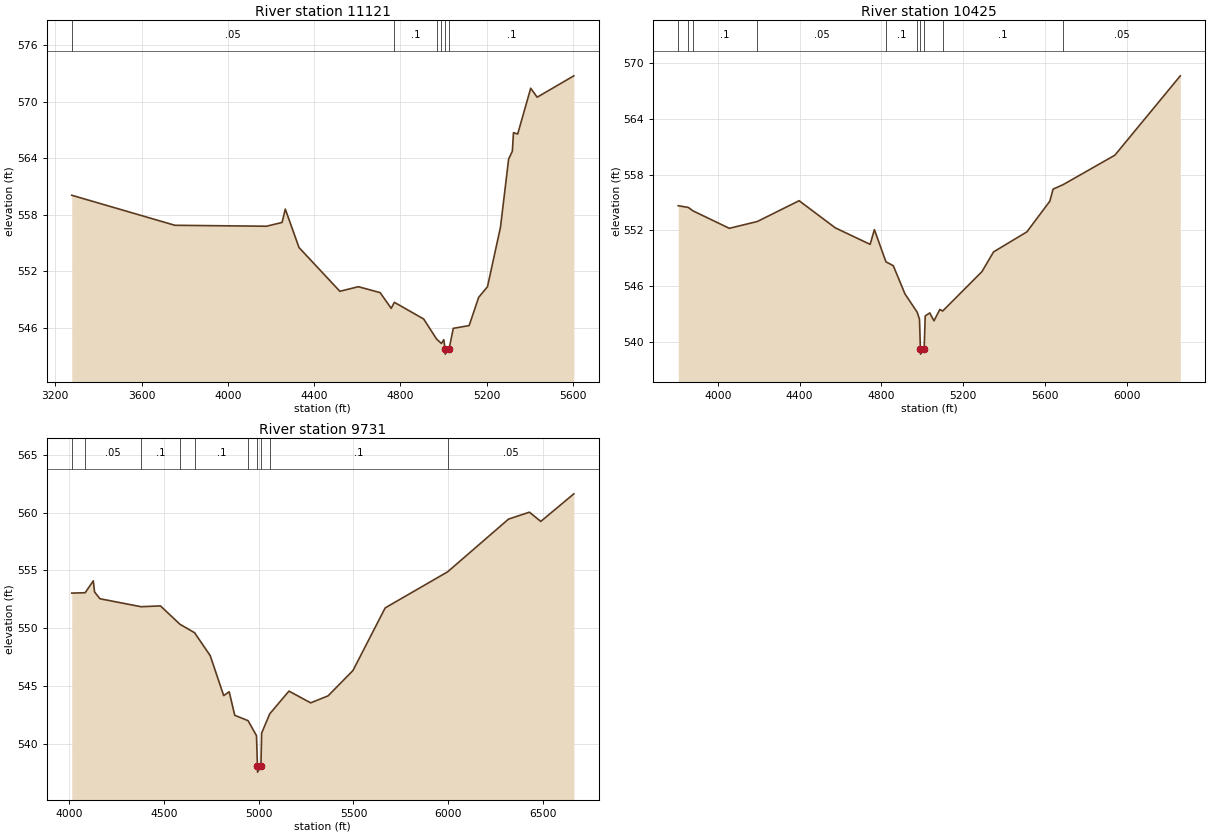
Type RM Length L Ch R = 1,11121,696,696,696
BEGIN DESCRIPTION:
UNT 021 in BCW 15.0
END DESCRIPTION:
XS GIS Cut Line= 3
      1970464.73     13524885.56      1971425.00     13523425.00
      1971630.68     13522882.22
#Sta/Elev= 30
  3276.4  560.07  3754.5  556.88  4179.3  556.78  4251.6  557.18  4266.7  558.60
  4330.2  554.52  4519.8  549.87  4605.5  550.36  4706.5  549.73  4757.8  548.06
  4772.5  548.70  4908.4  546.93  4968.3  544.80  4990.5  544.33  5001.7  544.73
  5007.7  543.70  5008.2  543.20  5025.9  543.70  5045.7  545.94  5119.2  546.23
  5163.4  549.23  5204.3  550.36  5264.6  556.68  5302.4  563.91  5319.6  564.74
  5324.9  566.72  5344.4  566.57  5404.7  571.43  5434.8  570.48  5604.8  572.75
#Mann=6,-1,0
  3276.4    0.05       0  4772.5     0.1       0  4968.3    0.16       0
  4990.5     0.1       0  5007.7    0.07       0  5025.9     0.1       0
Bank Sta=5007.7,5025.9
Exp/Cntr=0.3,0.1

Type RM Length L Ch R = 1,10425,694,694,694
BEGIN DESCRIPTION:
UNT 021 in BCW 14.0
END DESCRIPTION:
XS GIS Cut Line= 4
      1971125.05     13524836.93      1971370.95     13524531.44
      1972011.58     13523760.60      1972225.00     13522719.51
#Sta/Elev= 30
  3805.7  554.65  3854.9  554.47  3878.0  554.10  4055.7  552.23  4192.8  552.96
  4397.3  555.19  4574.3  552.28  4744.9  550.51  4765.7  552.09  4822.2  548.64
  4858.2  548.22  4915.5  545.19  4975.0  543.24  4986.4  542.49  4991.0  539.24
  4991.5  538.74  5009.2  539.24  5014.4  542.83  5036.6  543.16  5057.4  542.31
  5086.0  543.53  5099.9  543.36  5292.3  547.59  5348.8  549.70  5512.1  551.85
  5624.4  555.14  5640.1  556.43  5689.2  556.91  5942.6  560.07  6262.9  568.58
#Mann=10,-1,0
  3805.7     0.1       0  3854.9    0.05       0  3878.0     0.1       0
  4192.8    0.05       0  4822.2     0.1       0  4975.0    0.12       0
  4991.0    0.07       0  5009.2    0.12       0  5099.9     0.1       0
  5689.2    0.05       0
Bank Sta=4991,5009.2
Exp/Cntr=0.3,0.1

Type RM Length L Ch R = 1,9731,670,670,670
BEGIN DESCRIPTION:
Mapping XS dcb6525e
END DESCRIPTION:
XS GIS Cut Line= 4
      1971812.56     13524972.34      1972271.99     13524448.10
      1972699.08     13523875.19      1972709.50     13522640.79
#Sta/Elev= 30
  4015.4  553.03  4085.8  553.06  4128.9  554.09  4135.5  553.13  4164.0  552.54
  4380.7  551.85  4482.9  551.92  4585.6  550.33  4662.6  549.60  4745.1  547.61
  4816.1  544.15  4845.1  544.48  4874.4  542.44  4944.5  541.98  4989.0  540.68
  4994.0  538.02  4994.5  537.52  5012.4  538.02  5016.1  540.90  5058.8  542.57
  5160.0  544.54  5274.7  543.52  5366.4  544.13  5497.2  546.32  5667.3  551.75
  5996.0  554.87  6317.3  559.44  6427.3  560.04  6487.3  559.24  6661.5  561.63
#Mann=10,-1,0
  4015.4     0.1       0  4085.8    0.05       0  4380.7     0.1       0
  4585.6    0.05       0  4662.6     0.1       0  4944.5    0.12       0
  4994.0    0.07       0  5012.4    0.12       0  5058.8     0.1       0
  5996.0    0.05       0
Bank Sta=4994,5012.4
Exp/Cntr=0.3,0.1