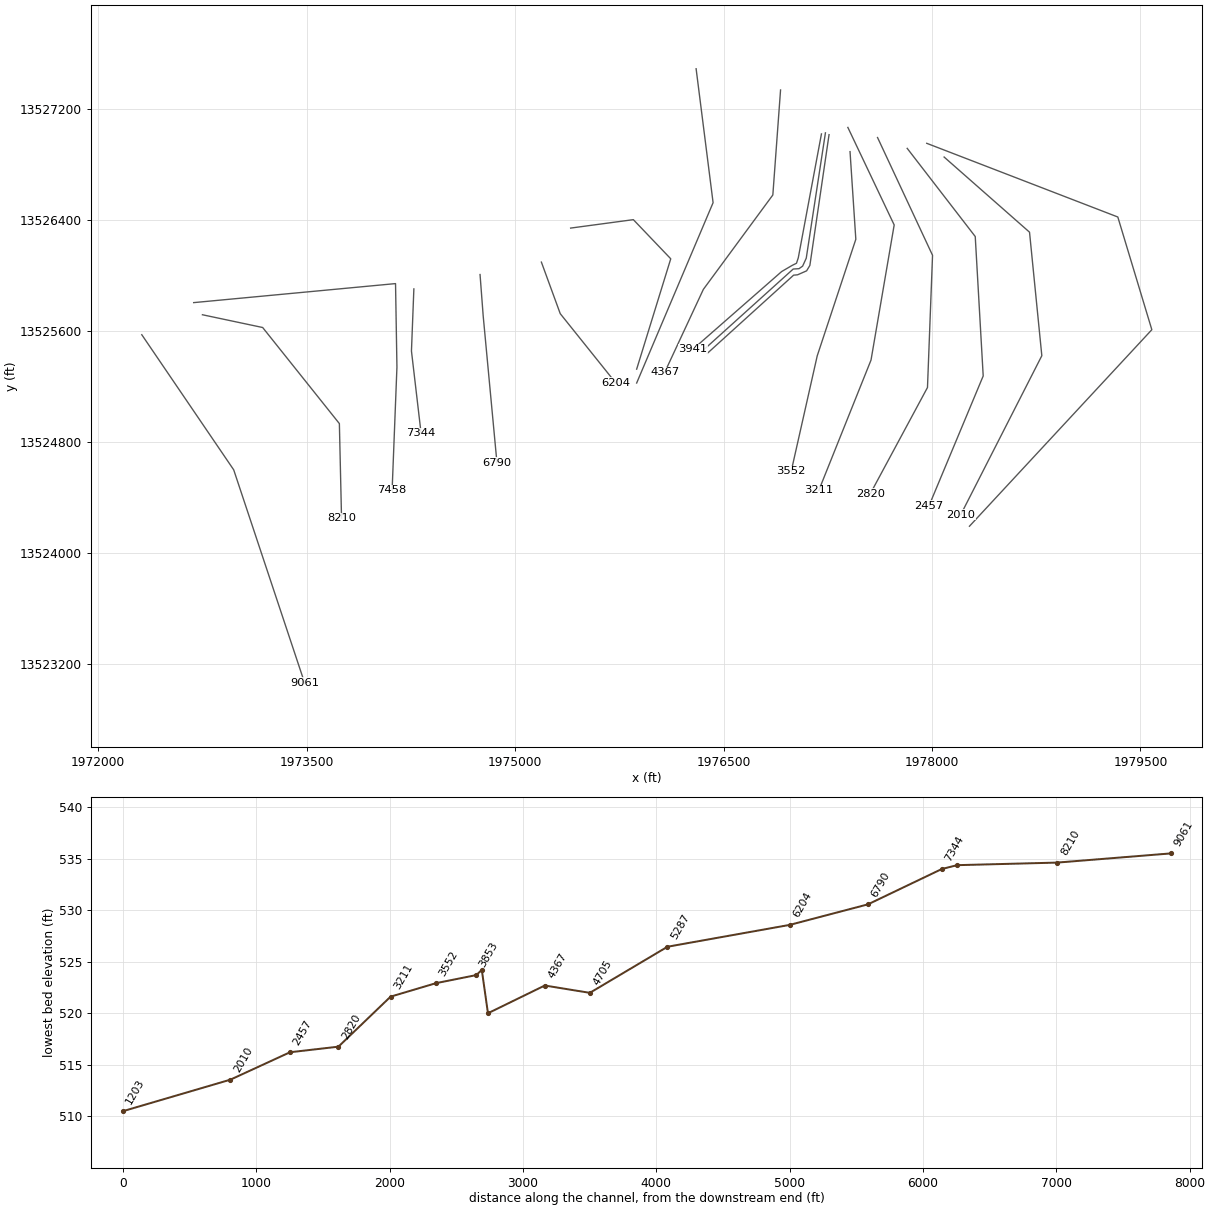
HEC-RAS study UNT 021 in BCW.prj: UNT 021 in BCW Base Level Engineering

--- UNT 021 in BCW.g01 (geometry) --- (continued)

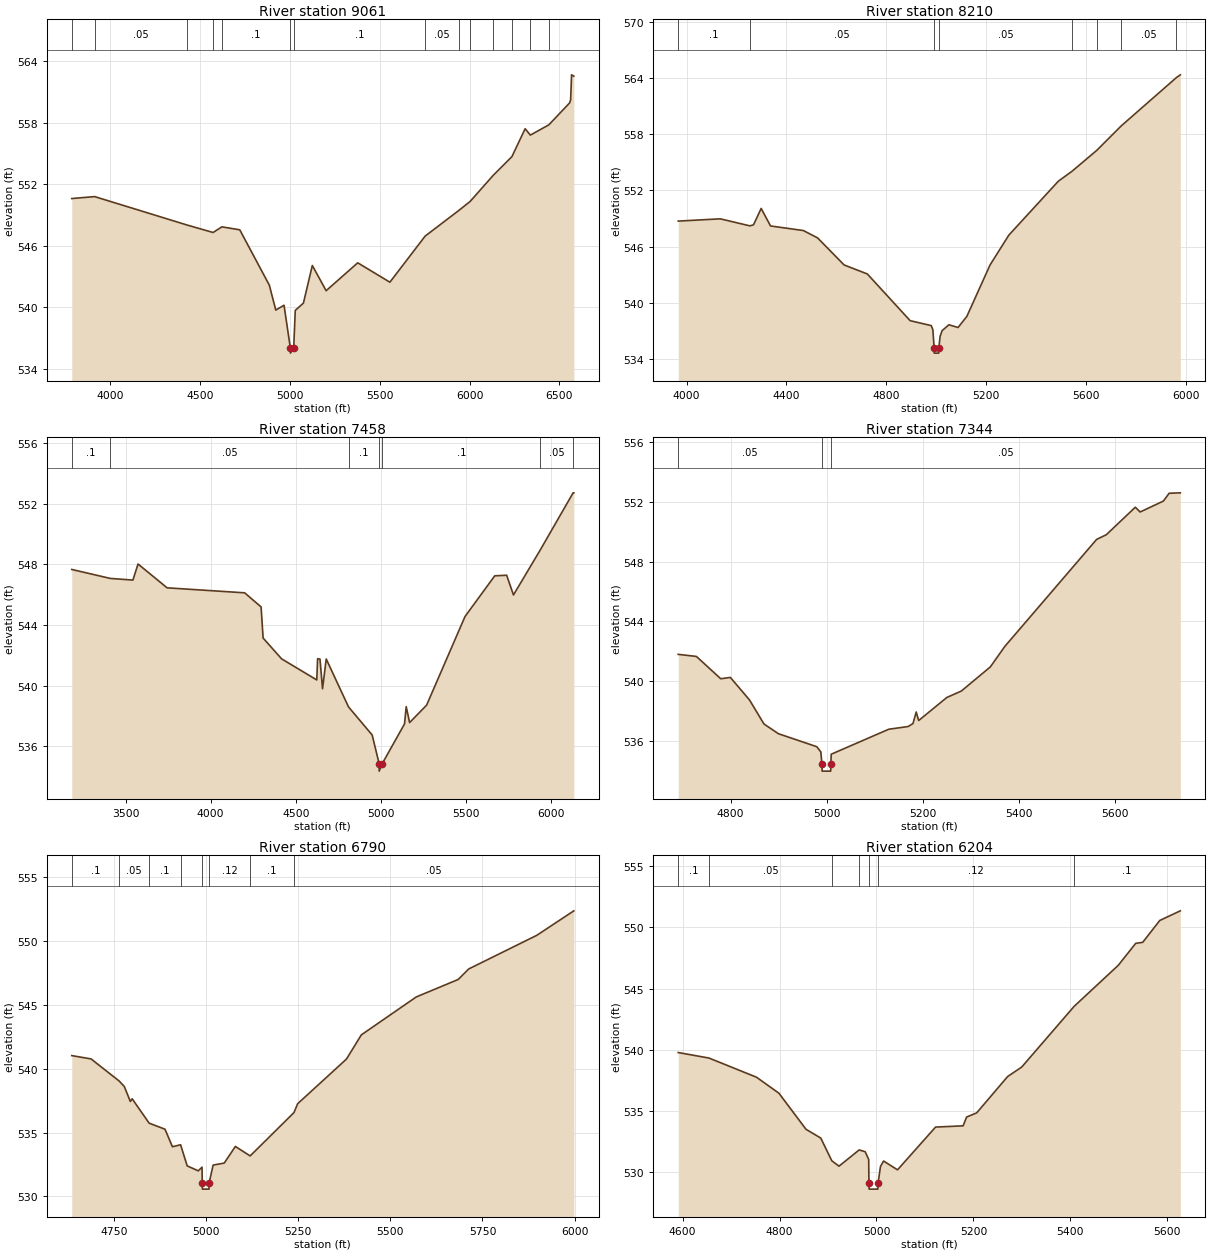
Type RM Length L Ch R = 1,9061,851,851,851
BEGIN DESCRIPTION:
Mapping XS 472ef344
END DESCRIPTION:
XS GIS Cut Line= 3
      1972313.66     13525573.11      1972975.12     13524599.14
      1973485.55     13523062.65
#Sta/Elev= 30
  3784.4  550.59  3911.9  550.78  4428.0  548.00  4571.5  547.28  4620.4  547.83
  4720.1  547.54  4884.8  542.14  4920.7  539.71  4966.6  540.18  5002.0  536.01
  5002.5  535.51  5020.4  536.01  5029.3  539.68  5074.6  540.39  5124.2  544.06
  5201.2  541.60  5377.1  544.32  5556.2  542.43  5752.8  546.93  5941.0  549.44
  6003.3  550.31  6130.5  552.83  6235.9  554.68  6309.5  557.40  6338.7  556.78
  6441.5  557.78  6557.3  559.92  6562.9  560.21  6568.1  562.66  6580.8  562.53
#Mann=14,-1,0
  3784.4     0.1       0  3911.9    0.05       0  4428.0     0.1       0
  4571.5    0.05       0  4620.4     0.1       0  5002.0    0.07       0
  5020.4     0.1       0  5752.8    0.05       0  5941.0     0.1       0
  6003.3    0.05       0  6130.5     0.1       0  6235.9    0.08       0
  6338.7     0.1       0  6441.5    0.05       0
Bank Sta=5002,5020.4
Exp/Cntr=0.3,0.1

Type RM Length L Ch R = 1,8210,752,752,752
BEGIN DESCRIPTION:
UNT 021 in BCW 8.0
END DESCRIPTION:
XS GIS Cut Line= 4
      1972750.05     13525717.13      1973183.45     13525625.19
      1973735.54     13524932.48      1973751.16     13524250.21
#Sta/Elev= 30
  3966.8  548.73  4135.4  548.97  4253.9  548.22  4268.3  548.33  4299.0  550.08
  4336.6  548.21  4468.1  547.72  4525.2  546.93  4631.4  544.04  4724.3  543.08
  4895.7  538.09  4980.5  537.56  4986.9  537.11  4992.0  535.12  4992.5  534.62
  5010.2  534.62  5010.7  535.12  5015.8  536.41  5023.8  537.02  5051.0  537.65
  5087.8  537.36  5123.1  538.55  5215.7  544.03  5291.2  547.23  5489.4  552.99
  5545.0  554.07  5643.5  556.29  5742.1  558.92  5961.8  564.05  5978.1  564.36
#Mann=8,-1,0
  3966.8     0.1       0  4253.9    0.05       0  4992.0    0.07       0
  5010.7    0.05       0  5545.0    0.05       0  5643.5     0.1       0
  5742.1    0.05       0  5961.8     0.1       0
Bank Sta=4992,5010.7
Exp/Cntr=0.3,0.1

Type RM Length L Ch R = 1,7458,114,114,114
BEGIN DESCRIPTION:
UNT 021 in BCW 7.0
END DESCRIPTION:
XS GIS Cut Line= 4
      1972687.15     13525804.59      1974139.70     13525941.71
      1974149.80     13525340.18      1974115.08     13524450.39
#Sta/Elev= 30
  3183.7  547.66  3409.8  547.07  3543.1  546.96  3573.3  548.02  3744.0  546.45
  4200.0  546.12  4296.5  545.19  4308.4  543.14  4417.0  541.77  4623.7  540.38
  4628.7  541.78  4642.7  541.75  4657.6  539.80  4679.4  541.76  4810.5  538.60
  4949.5  536.75  4990.1  534.87  4990.6  534.37  5008.9  534.87  5139.5  537.48
  5149.5  538.62  5169.5  537.57  5269.5  538.72  5495.2  544.56  5669.8  547.24
  5739.9  547.28  5779.9  545.98  5937.7  548.95  6130.6  552.71  6134.8  552.71
#Mann=7,-1,0
  3183.7     0.1       0  3409.8    0.05       0  4810.5     0.1       0
  4990.1    0.07       0  5008.9     0.1       0  5937.7    0.05       0
  6130.6     0.1       0
Bank Sta=4990.1,5008.9
Exp/Cntr=0.3,0.1

Type RM Length L Ch R = 1,7344,554,554,554
BEGIN DESCRIPTION:
UNT 021 in BCW 6.0
END DESCRIPTION:
XS GIS Cut Line= 3
      1974271.64     13525903.51      1974254.28     13525455.60
      1974323.72     13524861.89
#Sta/Elev= 30
  4690.8  541.80  4728.7  541.66  4779.4  540.17  4799.4  540.26  4839.4  538.75
  4869.4  537.15  4899.5  536.50  4979.5  535.63  4987.9  535.28  4990.1  534.50
  4990.6  534.00  5008.4  534.00  5008.9  534.50  5009.5  535.13  5129.6  536.80
  5169.9  536.98  5179.9  537.18  5186.6  537.95  5191.7  537.38  5250.4  538.92
  5280.6  539.35  5341.0  540.96  5371.2  542.33  5562.5  549.48  5582.6  549.79
  5643.1  551.63  5653.1  551.31  5701.6  552.04  5713.5  552.56  5736.8  552.59
#Mann=3,-1,0
  4690.8    0.05       0  4990.1    0.04       0  5008.9    0.05       0
Bank Sta=4990.1,5008.9
Exp/Cntr=0.3,0.1

Type RM Length L Ch R = 1,6790,586,586,586
BEGIN DESCRIPTION:
UNT 021 in BCW 5.0
END DESCRIPTION:
XS GIS Cut Line= 3
      1974747.89     13526007.10      1974770.55     13525708.43
      1974869.50     13524651.18
#Sta/Elev= 30
  4636.3  541.02  4688.6  540.76  4764.9  539.03  4778.8  538.60  4795.1  537.43
  4800.1  537.64  4846.2  535.73  4889.1  535.26  4909.2  533.89  4931.4  534.04
  4949.3  532.39  4979.4  532.00  4989.5  532.29  4990.1  531.07  4990.6  530.57
  5008.4  530.57  5008.9  531.07  5019.6  532.45  5049.8  532.61  5079.9  533.91
  5120.0  533.17  5238.8  536.56  5248.7  537.25  5381.2  540.75  5421.4  542.64
  5570.4  545.61  5684.3  546.98  5712.6  547.80  5897.1  550.43  5997.7  552.35
#Mann=8,-1,0
  4636.3     0.1       0  4764.9    0.05       0  4846.2     0.1       0
  4931.4    0.12       0  4990.1    0.07       0  5008.9    0.12       0
  5120.0     0.1       0  5238.8    0.05       0
Bank Sta=4990.1,5008.9
Exp/Cntr=0.3,0.1

Type RM Length L Ch R = 1,6204,917,917,917
BEGIN DESCRIPTION:
UNT 021 in BCW 4.0
END DESCRIPTION:
XS GIS Cut Line= 3
      1975189.29     13526096.70      1975325.00     13525725.00
      1975724.99     13525225.01
#Sta/Elev= 30
  4590.9  539.76  4654.3  539.31  4752.4  537.74  4798.7  536.43  4854.5  533.48
  4885.0  532.76  4907.8  530.90  4922.7  530.46  4964.3  531.79  4976.7  531.64
  4983.9  531.01  4984.4  529.08  4984.9  528.58  5002.8  528.58  5003.3  529.08
  5008.2  530.43  5014.6  530.88  5043.4  530.16  5121.9  533.66  5178.7  533.76
  5185.9  534.48  5206.7  534.82  5270.7  537.80  5299.6  538.57  5407.8  543.54
  5498.9  546.90  5534.9  548.70  5549.3  548.78  5584.5  550.57  5626.9  551.36
#Mann=7,-1,0
  4590.9     0.1       0  4654.3    0.05       0  4907.8     0.1       0
  4964.3    0.12       0  4984.4    0.07       0  5003.3    0.12       0
  5407.8     0.1       0
Bank Sta=4984.4,5003.3
Exp/Cntr=0.3,0.1

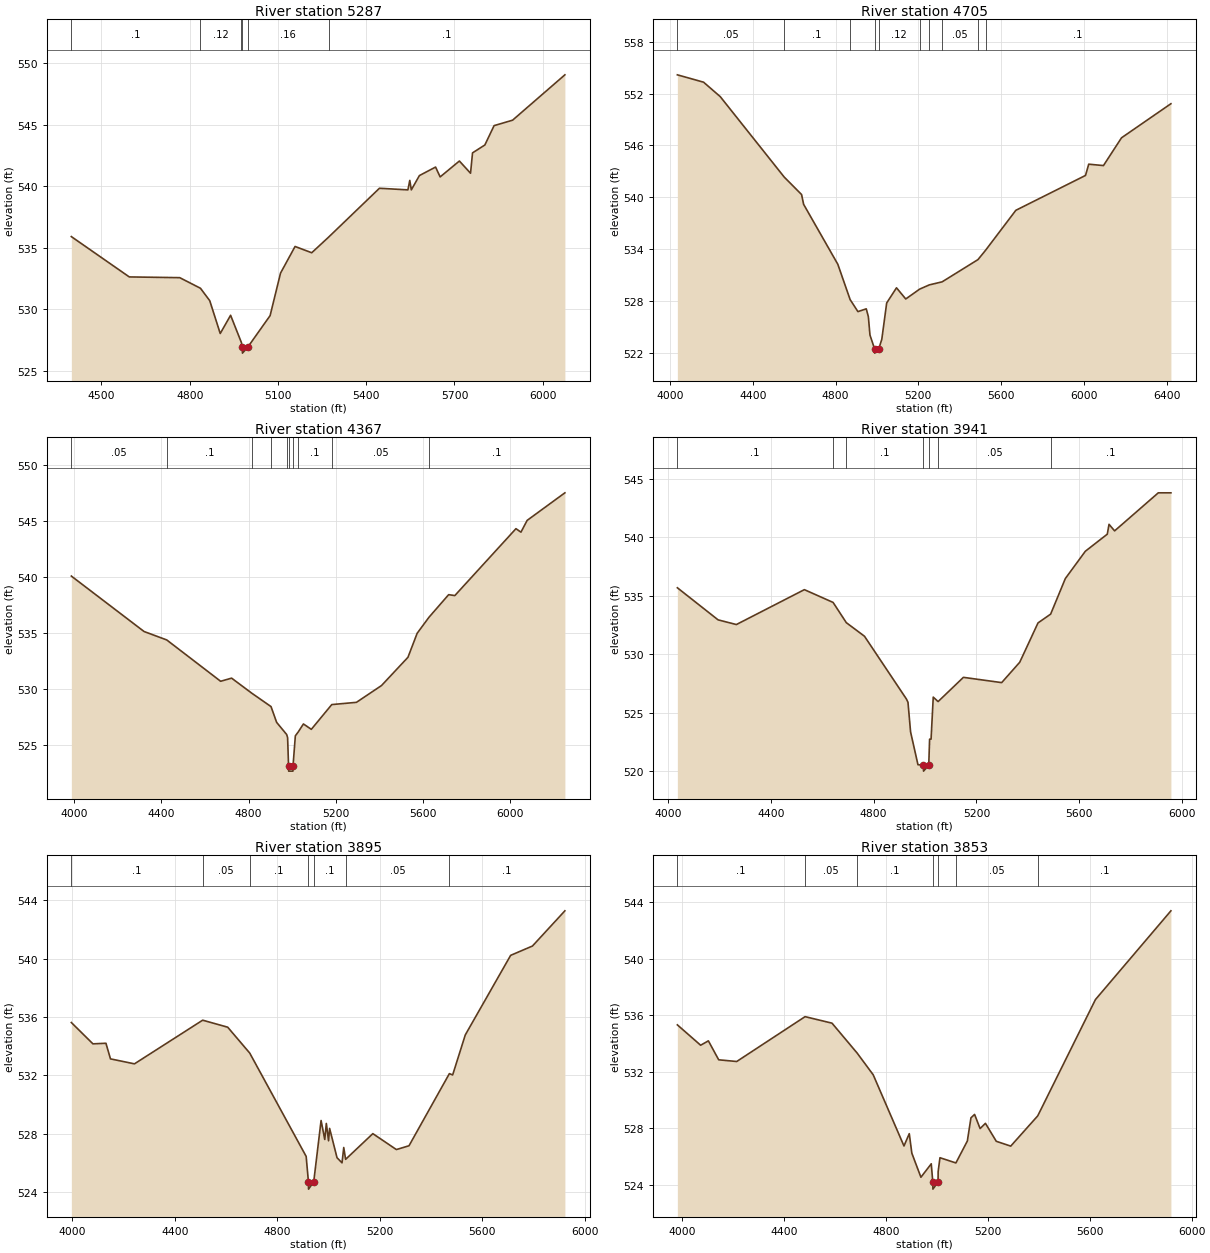
Type RM Length L Ch R = 1,5287,582,582,582
BEGIN DESCRIPTION:
UNT 021 in BCW 3.0
END DESCRIPTION:
XS GIS Cut Line= 4
      1975399.80     13526341.91      1975851.19     13526402.68
      1976120.29     13526120.56      1975874.99     13525324.95
#Sta/Elev= 30
  4397.6  535.91  4594.6  532.64  4766.1  532.58  4836.6  531.72  4868.2  530.71
  4903.8  528.05  4939.0  529.53  4975.9  527.31  4978.9  526.96  4979.4  526.46
  4997.8  526.96  5073.3  529.50  5108.8  532.95  5158.2  535.11  5214.8  534.60
  5271.9  535.86  5445.0  539.83  5541.8  539.70  5548.2  540.47  5553.4  539.70
  5580.9  540.86  5635.9  541.55  5651.4  540.75  5716.8  542.04  5754.7  541.05
  5761.5  542.70  5803.4  543.34  5834.8  544.91  5897.6  545.35  6075.5  549.03
#Mann=6,-1,0
  4397.6     0.1       0  4836.6    0.12       0  4975.9    0.16       0
  4978.9    0.07       0  4997.8    0.16       0  5271.9     0.1       0
Bank Sta=4978.9,4997.8
Exp/Cntr=0.3,0.1

Type RM Length L Ch R = 1,4705,338,338,338
BEGIN DESCRIPTION:
UNT 021 in BCW 2.0
END DESCRIPTION:
XS GIS Cut Line= 3
      1976302.82     13527490.59      1976425.00     13526525.00
      1975874.98     13525224.96
#Sta/Elev= 30
  4035.6  554.16  4162.2  553.31  4242.8  551.64  4552.0  542.34  4635.9  540.32
  4645.7  539.19  4811.0  532.26  4870.4  528.18  4908.1  526.79  4948.4  527.11
  4958.5  526.20  4966.3  524.08  4988.5  522.49  4989.0  521.99  5009.2  522.49
  5023.5  523.60  5047.1  527.79  5094.5  529.54  5139.2  528.25  5206.5  529.39
  5253.3  529.88  5315.0  530.23  5488.2  532.80  5524.9  533.88  5671.2  538.50
  6007.8  542.53  6023.4  543.83  6094.5  543.67  6181.8  546.88  6420.5  550.82
#Mann=10,-1,0
  4035.6    0.05       0  4552.0     0.1       0  4870.4    0.12       0
  4988.5    0.07       0  5009.2    0.12       0  5206.5     0.1       0
  5253.3    0.16       0  5315.0    0.05       0  5488.2    0.16       0
  5524.9     0.1       0
Bank Sta=4988.5,5009.2
Exp/Cntr=0.3,0.1

Type RM Length L Ch R = 1,4367,426,426,426
BEGIN DESCRIPTION:
Mapping XS 3a62bc3a
END DESCRIPTION:
XS GIS Cut Line= 4
      1976910.53     13527337.50      1976854.97     13526580.60
      1976354.97     13525900.05      1976077.19     13525302.81
#Sta/Elev= 30
  3987.8  540.11  4321.2  535.16  4425.0  534.41  4672.1  530.72  4722.3  531.00
  4815.3  529.65  4903.0  528.46  4928.8  527.05  4974.6  525.97  4979.0  525.70
  4983.3  523.20  4983.8  522.70  5003.5  522.70  5004.0  523.20  5014.5  525.85
  5028.2  526.21  5051.5  526.91  5087.7  526.43  5181.4  528.64  5294.5  528.84
  5409.5  530.34  5530.6  532.86  5572.7  535.00  5626.8  536.43  5717.1  538.45
  5745.5  538.37  6025.6  544.34  6048.5  544.03  6076.9  545.08  6249.9  547.54
#Mann=10,-1,0
  3987.8    0.05       0  4425.0     0.1       0  4815.3    0.16       0
  4903.0    0.12       0  4974.6    0.16       0  4983.3    0.07       0
  5004.0    0.16       0  5028.2     0.1       0  5181.4    0.05       0
  5626.8     0.1       0
Bank Sta=4983.3,5004
Exp/Cntr=0.3,0.1

Type RM Length L Ch R = 1,3941,46,46,46
BEGIN DESCRIPTION:
Mapping XS fbf8af56
END DESCRIPTION:
XS GIS Cut Line= 6
      1977204.80     13527020.69      1977038.13     13526127.48
      1977025.11     13526088.42      1976993.86     13526072.79
      1976918.34     13526028.52      1976281.10     13525469.31
#Sta/Elev= 30
  4036.6  535.67  4195.0  532.93  4266.2  532.53  4530.7  535.51  4642.4  534.42
  4693.9  532.69  4764.6  531.53  4927.4  526.18  4933.8  525.89  4943.9  523.36
  4972.6  520.56  4993.9  520.51  4994.4  520.01  5014.6  520.51  5017.9  522.74
  5023.6  522.74  5032.1  526.33  5051.0  525.95  5149.4  528.02  5298.3  527.57
  5368.6  529.31  5439.7  532.67  5488.8  533.42  5546.0  536.46  5623.8  538.79
  5709.2  540.25  5715.9  541.09  5737.7  540.53  5907.6  543.78  5956.7  543.78
#Mann=7,-1,0
  4036.6     0.1       0  4642.4    0.05       0  4693.9     0.1       0
  4993.9    0.07       0  5014.6     0.1       0  5051.0    0.05       0
  5488.8     0.1       0
Bank Sta=4993.9,5014.6
Exp/Cntr=0.3,0.1

Type RM Length L Ch R = 1,3895,42,42,42
BEGIN DESCRIPTION:
Mapping XS e490f220
END DESCRIPTION:
XS GIS Cut Line= 6
      1977233.45     13527028.54      1977095.43     13526124.87
      1977069.38     13526067.58      1977043.34     13526049.35
      1977001.68     13526046.75      1976351.63     13525459.11
#Sta/Elev= 30
  3995.6  535.62  4079.9  534.16  4130.7  534.20  4148.4  533.13  4242.0  532.79
  4508.3  535.78  4606.1  535.30  4692.0  533.53  4912.4  526.45  4921.2  524.71
  4921.7  524.21  4941.9  524.71  4970.6  528.91  4985.0  527.61  4991.1  528.71
  4999.8  527.52  5003.9  528.37  5032.9  526.36  5052.4  526.01  5059.1  527.06
  5066.4  526.25  5172.7  528.01  5264.6  526.92  5313.9  527.18  5471.5  532.12
  5484.3  532.03  5533.6  534.77  5710.7  540.22  5795.9  540.86  5922.5  543.27
#Mann=7,-1,0
  3995.6     0.1       0  4508.3    0.05       0  4692.0     0.1       0
  4921.2    0.07       0  4941.9     0.1       0  5066.4    0.05       0
  5471.5     0.1       0
Bank Sta=4921.2,4941.9
Exp/Cntr=0.3,0.1

Type RM Length L Ch R = 1,3853,301,301,301
BEGIN DESCRIPTION:
Mapping XS b3113059
END DESCRIPTION:
XS GIS Cut Line= 6
      1977259.48     13527015.46      1977121.47     13526072.79
      1977098.03     13526033.73      1977032.93     13526005.08
      1977004.28     13526002.48      1976383.32     13525438.67
#Sta/Elev= 30
  3981.7  535.32  4073.1  533.88  4103.4  534.19  4143.9  532.85  4214.6  532.73
  4482.9  535.90  4588.6  535.44  4687.1  533.33  4750.3  531.79  4871.0  526.76
  4891.8  527.63  4901.9  526.25  4937.5  524.55  4978.1  525.50  4984.1  524.21
  4984.6  523.71  5004.8  524.21  5005.1  524.95  5012.3  525.93  5074.8  525.56
  5119.7  527.11  5133.9  528.75  5148.1  528.99  5169.8  527.99  5190.7  528.36
  5233.3  527.09  5290.0  526.75  5396.0  528.89  5622.5  537.11  5918.6  543.38
#Mann=7,-1,0
  3981.7     0.1       0  4482.9    0.05       0  4687.1     0.1       0
  4984.1    0.07       0  5004.8     0.1       0  5074.8    0.05       0
  5396.0     0.1       0
Bank Sta=4984.1,5004.8
Exp/Cntr=0.3,0.1

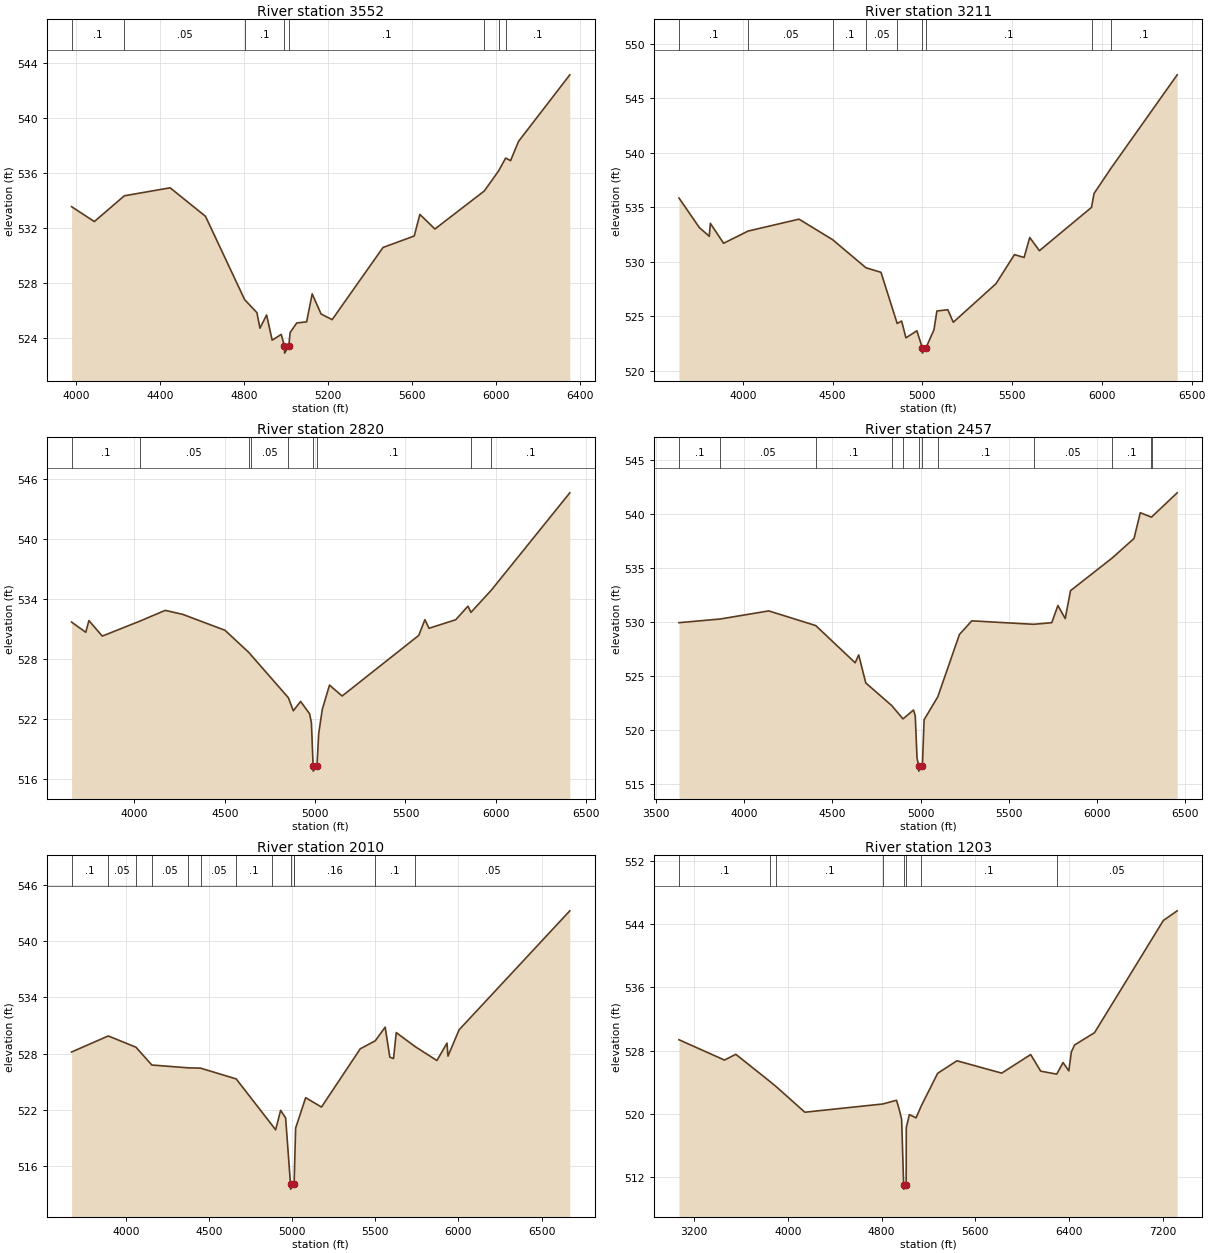
Type RM Length L Ch R = 1,3552,341,341,341
BEGIN DESCRIPTION:
Mapping XS d02352af
END DESCRIPTION:
XS GIS Cut Line= 4
      1977410.53     13526893.09      1977452.20     13526261.16
      1977174.42     13525420.88      1976987.20     13524588.79
#Sta/Elev= 30
  3980.4  533.56  4088.7  532.48  4231.5  534.35  4449.5  534.93  4617.8  532.86
  4804.2  526.81  4862.4  525.87  4876.9  524.74  4908.6  525.70  4935.1  523.87
  4978.3  524.29  4993.5  523.43  4994.0  522.93  5014.2  523.43  5020.4  524.42
  5052.0  525.12  5099.0  525.20  5125.5  527.23  5167.9  525.77  5220.5  525.36
  5462.8  530.60  5611.2  531.43  5638.0  533.00  5709.7  531.94  5944.7  534.70
  6012.9  536.16  6046.4  537.09  6069.6  536.90  6107.7  538.30  6351.6  543.13
#Mann=8,-1,0
  3980.4     0.1       0  4231.5    0.05       0  4804.2     0.1       0
  4993.5    0.07       0  5014.2     0.1       0  5944.7    0.08       0
  6012.9    0.05       0  6046.4     0.1       0
Bank Sta=4993.5,5014.2
Exp/Cntr=0.3,0.1

Type RM Length L Ch R = 1,3211,391,391,391
BEGIN DESCRIPTION:
Mapping XS aa340624
END DESCRIPTION:
XS GIS Cut Line= 4
      1977394.92     13527067.55      1977728.24     13526364.46
      1977561.57     13525390.50      1977186.58     13524453.03
#Sta/Elev= 30
  3643.7  535.84  3757.2  533.13  3812.5  532.33  3818.5  533.52  3892.3  531.69
  4029.1  532.81  4312.6  533.90  4499.7  532.02  4685.9  529.44  4769.2  529.03
  4859.5  524.34  4884.3  524.56  4908.2  523.02  4969.1  523.67  4999.3  522.12
  4999.8  521.62  5020.1  522.12  5064.5  523.76  5080.7  525.48  5141.6  525.60
  5172.0  524.45  5409.9  527.98  5512.8  530.65  5566.6  530.39  5598.1  532.22
  5651.9  531.01  5942.2  534.98  5956.2  536.25  6049.7  538.54  6419.6  547.13
#Mann=9,-1,0
  3643.7     0.1       0  4029.1    0.05       0  4499.7     0.1       0
  4685.9    0.05       0  4859.5     0.1       0  4999.3    0.07       0
  5020.1     0.1       0  5942.2    0.05       0  6049.7     0.1       0
Bank Sta=4999.3,5020.1
Exp/Cntr=0.3,0.1

Type RM Length L Ch R = 1,2820,363,363,363
BEGIN DESCRIPTION:
Mapping XS dcbf6897
END DESCRIPTION:
XS GIS Cut Line= 4
      1977608.44     13526994.69      1978004.28     13526145.71
      1977967.82     13525192.58      1977557.18     13524428.49
#Sta/Elev= 30
  3651.8  531.67  3730.4  530.65  3747.7  531.82  3821.8  530.27  4029.3  531.76
  4170.0  532.84  4267.3  532.44  4501.0  530.85  4632.1  528.65  4647.0  528.34
  4851.8  524.11  4879.4  522.80  4919.5  523.74  4969.5  522.50  4979.5  521.59
  4988.9  517.27  4989.4  516.77  5010.2  517.27  5019.6  520.49  5039.6  522.94
  5079.6  525.37  5149.6  524.28  5573.7  530.34  5607.7  531.91  5630.4  531.05
  5778.0  531.90  5846.1  533.26  5862.5  532.64  5976.3  534.88  6409.8  544.59
#Mann=9,-1,0
  3651.8     0.1       0  4029.3    0.05       0  4632.1     0.1       0
  4647.0    0.05       0  4851.8     0.1       0  4988.9    0.07       0
  5010.2     0.1       0  5862.5    0.08       0  5976.3     0.1       0
Bank Sta=4988.9,5010.2
Exp/Cntr=0.3,0.1

Type RM Length L Ch R = 1,2457,447,447,447
BEGIN DESCRIPTION:
Mapping XS aa454dfe
END DESCRIPTION:
XS GIS Cut Line= 4
      1977821.96     13526916.57      1978311.57     13526281.12
      1978368.86     13525275.92      1977978.57     13524339.21
#Sta/Elev= 30
  3630.3  529.96  3864.3  530.30  4139.3  531.05  4405.8  529.69  4628.9  526.25
  4649.0  526.98  4689.0  524.39  4836.4  522.29  4900.0  521.06  4959.5  521.88
  4969.5  521.34  4979.5  517.46  4988.8  516.73  4989.3  516.23  5010.2  516.73
  5019.6  520.98  5097.1  523.10  5219.9  528.87  5290.0  530.13  5640.9  529.81
  5743.3  529.96  5778.0  531.55  5819.5  530.34  5849.5  532.92  6086.3  535.95
  6209.5  537.75  6244.9  540.13  6306.5  539.73  6309.5  539.74  6454.1  541.97
#Mann=12,-1,0
  3630.3     0.1       0  3864.3    0.05       0  4405.8     0.1       0
  4836.4    0.07       0  4900.0    0.12       0  4988.8    0.07       0
  5010.2    0.12       0  5097.1     0.1       0  5640.9    0.05       0
  6086.3     0.1       0  6306.5    0.05       0  6309.5     0.1       0
Bank Sta=4988.8,5010.2
Exp/Cntr=0.3,0.1

Type RM Length L Ch R = 1,2010,807,807,807
BEGIN DESCRIPTION:
Mapping XS c23e0807
END DESCRIPTION:
XS GIS Cut Line= 4
      1978087.58     13526854.07      1978702.20     13526312.37
      1978790.74     13525421.75      1978207.43     13524275.96
#Sta/Elev= 30
  3670.4  528.19  3891.4  529.90  4058.1  528.70  4153.7  526.80  4373.3  526.50
  4446.8  526.47  4661.6  525.32  4878.2  520.38  4899.0  519.89  4929.2  521.97
  4959.3  521.16  4988.8  514.07  4989.3  513.57  5010.2  514.07  5012.7  515.67
  5019.6  520.08  5079.9  523.32  5175.2  522.32  5408.7  528.53  5498.8  529.38
  5558.8  530.84  5586.7  527.64  5608.9  527.49  5625.5  530.26  5738.0  528.78
  5870.2  527.28  5930.9  529.14  5936.9  527.75  6003.6  530.55  6670.4  543.24
#Mann=13,-1,0
  3670.4     0.1       0  3891.4    0.05       0  4058.1     0.1       0
  4153.7    0.05       0  4373.3     0.1       0  4446.8    0.05       0
  4661.6     0.1       0  4878.2    0.12       0  4988.8    0.07       0
  5010.2    0.12       0  5012.7    0.16       0  5498.8     0.1       0
  5738.0    0.05       0
Bank Sta=4988.8,5010.2
Exp/Cntr=0.3,0.1

Type RM Length L Ch R = 1,1203,0,0,0
BEGIN DESCRIPTION:
UNT 021 in BCW 1.0
END DESCRIPTION:
XS GIS Cut Line= 4
      1977962.60     13526953.00      1979337.61     13526421.75
      1979582.41     13525609.25      1978269.95     13524192.63
#Sta/Elev= 30
  3069.3  529.39  3457.8  526.82  3554.5  527.55  3846.3  524.11  3899.6  523.46
  4143.9  520.23  4809.4  521.27  4926.4  521.74  4947.3  520.73  4970.5  519.32
  4987.6  511.01  4988.1  510.51  5009.0  511.01  5010.0  518.28  5036.5  519.93
  5093.5  519.52  5139.1  521.06  5278.0  525.15  5442.5  526.73  5824.7  525.17
  6072.4  527.52  6157.5  525.42  6294.7  525.04  6348.5  526.51  6397.9  525.45
  6419.4  527.85  6447.4  528.73  6617.3  530.28  7204.7  544.46  7323.1  545.68
#Mann=8,-1,0
  3069.3     0.1       0  3846.3    0.05       0  3899.6     0.1       0
  4809.4    0.16       0  4987.6    0.07       0  5009.0    0.16       0
  5139.1     0.1       0  6294.7    0.05       0
Bank Sta=4987.6,5009
Exp/Cntr=0.3,0.1

Chan Stop Cuts=-1