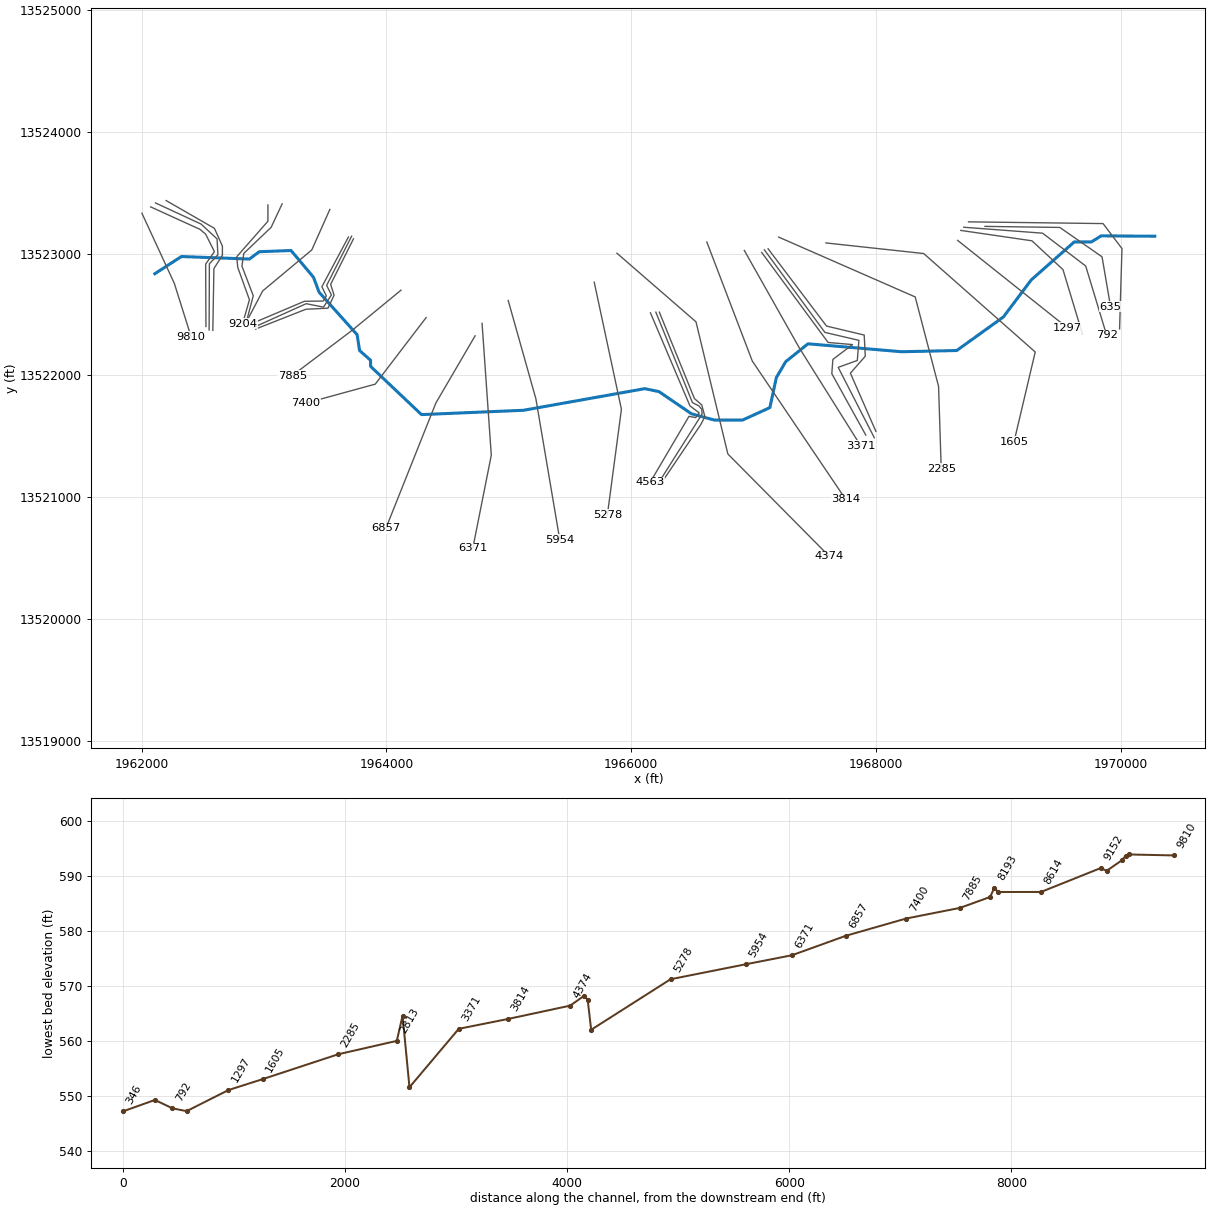
--- UNT 022 in BCW.prj (project) ---

Proj Title=UNT 022 in BCW Base Level Engineering
Current Plan=p01
Default Exp/Contr=0.3,0.1
English Units
Geom File=g01
Flow File=f01
Plan File=p01
BEGIN DESCRIPTION:
UNT 022 in BCW
END DESCRIPTION:

--- UNT 022 in BCW.p01 (plan) ---

Plan Title=Multiple Run
Short Identifier=Multiple
Geom File=g01
Flow File=f01
Subcritical Flow
K Sum by GR= 0
Std Step Tol= 0.01
Critical Tol= 0.01
Num of Std Step Trials= 20
Max Error Tol= 0.3
Flow Tol Ratio= 0.001
Split Flow NTrial= 30
Split Flow Tol= 0.02
Split Flow Ratio= 0.02
Log Output Level= 0
Friction Slope Method= 1
Unsteady Friction Slope Method= 2
Unsteady Bridges Friction Slope Method= 1
Parabolic Critical Depth
Global Vel Dist=  1 , 1 , 1
Global Log Level= 0
CheckData=True
Encroach Param= -1, 0, 0, 0
BEGIN DESCRIPTION:
Multiple Run
END DESCRIPTION:

--- UNT 022 in BCW.f01 (steady flow) ---

Flow Title=Multiple
Number of Profiles=7
Profile Names=10-year,25-year,50-year,1pct_min,100-year,1pct_plu,500-year
River Rch & RM= UNT 022 in BCW,Reach-1,9810
     154     212     261     161     321     640     493
River Rch & RM= UNT 022 in BCW,Reach-1,9403
     165     228     280     173     345     688     531
River Rch & RM= UNT 022 in BCW,Reach-1,6857
     239     337     420     262     523    1043     824
River Rch & RM= UNT 022 in BCW,Reach-1,3814
     328     469     590     371     739    1475    1183
Boundary for River Rch & Prof#=UNT 022 in BCW,Reach-1,1
Up Type=0
Dn Type=3
Dn Slope=0.005
Boundary for River Rch & Prof#=UNT 022 in BCW,Reach-1,2
Up Type=0
Dn Type=3
Dn Slope=0.005
Boundary for River Rch & Prof#=UNT 022 in BCW,Reach-1,3
Up Type=0
Dn Type=3
Dn Slope=0.005
Boundary for River Rch & Prof#=UNT 022 in BCW,Reach-1,4
Up Type=0
Dn Type=3
Dn Slope=0.005
Boundary for River Rch & Prof#=UNT 022 in BCW,Reach-1,5
Up Type=0
Dn Type=3
Dn Slope=0.005
Boundary for River Rch & Prof#=UNT 022 in BCW,Reach-1,6
Up Type=0
Dn Type=3
Dn Slope=0.005
Boundary for River Rch & Prof#=UNT 022 in BCW,Reach-1,7
Up Type=0
Dn Type=3
Dn Slope=0.005

--- UNT 022 in BCW.g01 (geometry) ---

Geom Title=Existing Conditions

River Reach=UNT 022 in BCW,Reach-1
Reach XY= 30
      1962107.65     13522834.24      1962324.97     13522975.17
      1962880.80     13522954.54      1962960.80     13523014.54
      1963220.80     13523024.54      1963403.96     13522805.90
      1963449.97     13522682.64      1963760.80     13522334.54
      1963780.80     13522204.54      1963870.80     13522124.54
      1963870.80     13522074.54      1964286.78     13521679.17
      1965120.80     13521714.54      1966111.43     13521891.84
      1966227.75     13521867.53      1966492.51     13521686.11
      1966680.01     13521634.54      1966910.80     13521634.54
      1967133.79     13521736.21      1967186.74     13521982.74
      1967263.13     13522112.95      1967445.42     13522259.65
      1968210.80     13522194.54      1968660.80     13522204.54
      1969042.47     13522479.79      1969270.80     13522784.54
      1969620.80     13523094.54      1969760.80     13523094.54
      1969840.80     13523144.54      1970279.27     13523141.60

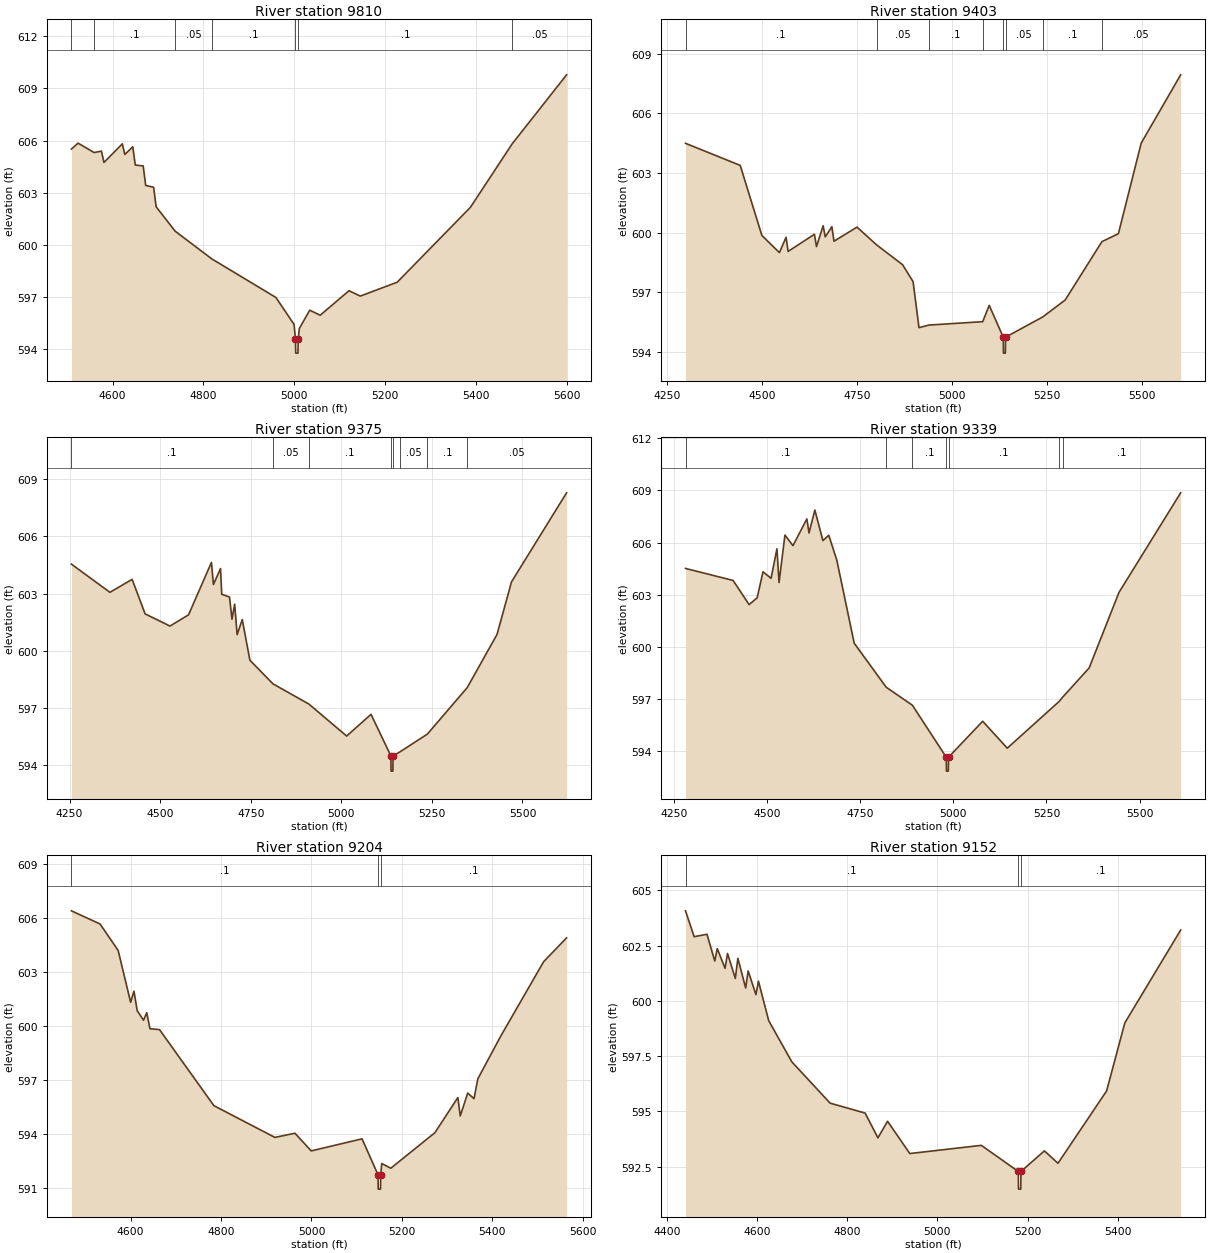
Type RM Length L Ch R = 1,9810,407,407,407
BEGIN DESCRIPTION:
UNT 022 in BCW 16.0
END DESCRIPTION:
XS GIS Cut Line= 3
      1962002.35     13523329.96      1962267.09     13522754.90
      1962403.60     13522319.37
#Sta/Elev= 30
  4509.4  605.51  4524.0  605.85  4559.3  605.31  4575.5  605.39  4581.0  604.74
  4621.4  605.81  4626.9  605.20  4644.4  605.64  4649.9  604.59  4667.3  604.54
  4672.8  603.42  4690.3  603.31  4695.8  602.19  4737.5  600.79  4817.8  599.20
  4959.4  596.97  4999.3  595.42  5002.4  594.57  5002.9  593.77  5007.9  593.77
  5008.4  594.57  5010.9  595.19  5033.8  596.24  5056.8  595.95  5120.2  597.36
  5145.0  597.05  5226.2  597.85  5387.4  602.16  5479.5  605.82  5598.9  609.78
#Mann=7,-1,0
  4509.4    0.05       0  4559.3     0.1       0  4737.5    0.05       0
  4817.8     0.1       0  5002.4    0.07       0  5008.4     0.1       0
  5479.5    0.05       0
Bank Sta=5002.4,5008.4
Exp/Cntr=0.3,0.1

Type RM Length L Ch R = 1,9403,28,28,28
BEGIN DESCRIPTION:
Mapping XS 6a47ece9
END DESCRIPTION:
XS GIS Cut Line= 6
      1962073.92     13523382.08      1962477.60     13523197.61
      1962523.17     13523158.55      1962594.78     13523015.32
      1962523.17     13522913.32      1962525.34     13522401.17
#Sta/Elev= 30
  4297.9  604.49  4441.9  603.38  4498.9  599.86  4545.0  599.00  4562.5  599.77
  4568.0  599.06  4637.1  599.92  4642.6  599.30  4660.1  600.35  4665.6  599.79
  4683.1  600.30  4688.6  599.57  4749.2  600.28  4800.7  599.39  4869.2  598.39
  4896.8  597.54  4912.3  595.23  4938.8  595.36  5080.0  595.53  5097.1  596.35
  5134.1  594.75  5134.6  593.95  5139.6  593.95  5140.1  594.75  5238.2  595.77
  5297.1  596.62  5393.7  599.55  5437.1  599.95  5497.1  604.50  5600.9  607.93
#Mann=8,-1,0
  4297.9     0.1       0  4800.7    0.05       0  4938.8     0.1       0
  5080.0    0.05       0  5134.1    0.07       0  5140.1    0.05       0
  5238.2     0.1       0  5393.7    0.05       0
Bank Sta=5134.1,5140.1
Exp/Cntr=0.3,0.1

Type RM Length L Ch R = 1,9375,36,36,36
BEGIN DESCRIPTION:
Mapping XS 7ad4bd43
END DESCRIPTION:
XS GIS Cut Line= 6
      1962113.05     13523414.60      1962486.28     13523241.01
      1962616.48     13523119.48      1962622.99     13522989.27
      1962553.55     13522915.49      1962551.38     13522372.98
#Sta/Elev= 30
  4255.0  604.55  4361.3  603.07  4422.6  603.75  4458.4  601.94  4527.1  601.30
  4578.3  601.89  4641.5  604.64  4647.0  603.48  4666.6  604.32  4669.9  602.97
  4691.4  602.82  4698.2  601.66  4705.6  602.45  4712.4  600.85  4726.6  601.64
  4747.6  599.51  4811.3  598.27  4910.4  597.21  5014.8  595.53  5082.0  596.67
  5136.8  594.49  5137.3  593.69  5142.3  593.69  5142.8  594.49  5161.0  594.69
  5237.4  595.63  5347.5  598.07  5429.8  600.86  5469.8  603.62  5621.8  608.29
#Mann=8,-1,0
  4255.0     0.1       0  4811.3    0.05       0  4910.4     0.1       0
  5136.8    0.07       0  5142.8     0.1       0  5161.0    0.05       0
  5237.4     0.1       0  5347.5    0.05       0
Bank Sta=5136.8,5142.8
Exp/Cntr=0.3,0.1

Type RM Length L Ch R = 1,9339,135,135,135
BEGIN DESCRIPTION:
Mapping XS 62357b3b
END DESCRIPTION:
XS GIS Cut Line= 6
      1962199.80     13523434.16      1962594.78     13523206.29
      1962659.89     13523060.89      1962659.89     13522984.93
      1962590.44     13522876.43      1962581.77     13522369.34
#Sta/Elev= 30
  4280.3  604.51  4408.1  603.82  4451.2  602.43  4472.8  602.82  4488.5  604.32
  4510.1  603.94  4525.9  605.64  4531.6  603.70  4547.4  606.43  4569.0  605.82
  4606.3  607.36  4612.1  606.55  4627.8  607.87  4649.4  606.11  4665.2  606.42
  4686.7  604.99  4733.5  600.21  4819.3  597.68  4889.8  596.64  4980.8  593.65
  4981.3  592.85  4986.3  592.85  4986.8  593.65  5078.6  595.72  5144.7  594.17
  5284.0  596.86  5293.7  597.11  5364.7  598.79  5444.7  603.13  5610.4  608.86
#Mann=7,-1,0
  4280.3     0.1       0  4819.3    0.05       0  4889.8     0.1       0
  4980.8    0.07       0  4986.8     0.1       0  5284.0    0.05       0
  5293.7     0.1       0
Bank Sta=4980.8,4986.8
Exp/Cntr=0.3,0.1

Type RM Length L Ch R = 1,9204,52,52,52
BEGIN DESCRIPTION:
UNT 022 in BCW 15.0
END DESCRIPTION:
XS GIS Cut Line= 6
      1963031.96     13523398.36      1963031.96     13523264.70
      1962776.75     13522973.04      1962785.43     13522886.23
      1962880.91     13522620.61      1962825.00     13522425.00
#Sta/Elev= 30
  4469.0  606.40  4532.4  605.67  4572.4  604.20  4600.0  601.33  4607.4  601.94
  4614.5  600.86  4628.6  600.33  4635.6  600.75  4642.7  599.86  4663.9  599.81
  4784.2  595.59  4919.1  593.83  4963.5  594.06  4999.5  593.08  5111.9  593.75
  5147.2  591.76  5147.7  590.96  5152.7  590.96  5153.2  591.76  5155.5  592.38
  5175.6  592.12  5273.1  594.09  5323.9  596.04  5329.2  595.02  5345.7  596.29
  5359.6  595.98  5368.1  597.08  5418.8  599.45  5513.7  603.58  5564.4  604.90
#Mann=3,-1,0
  4469.0     0.1       0  5147.2    0.07       0  5153.2     0.1       0
Bank Sta=5147.2,5153.2
Exp/Cntr=0.3,0.1

Type RM Length L Ch R = 1,9152,538,538,538
BEGIN DESCRIPTION:
Mapping XS dbbb7d1f
END DESCRIPTION:
XS GIS Cut Line= 6
      1963148.29     13523407.10      1963058.00     13523214.36
      1962834.84     13523000.89      1962819.59     13522896.71
      1962912.16     13522653.59      1962858.69     13522449.79
#Sta/Elev= 30
  4441.6  604.07  4460.8  602.90  4489.2  603.01  4506.5  601.80  4512.0  602.36
  4529.3  601.47  4534.8  602.14  4552.1  601.01  4557.7  601.92  4575.0  600.58
  4580.5  601.35  4597.8  600.28  4603.3  600.89  4626.1  599.10  4677.3  597.24
  4762.2  595.37  4839.9  594.92  4868.2  593.80  4889.6  594.55  4938.9  593.09
  5097.5  593.46  5179.4  592.28  5179.9  591.48  5184.9  591.48  5185.4  592.28
  5237.3  593.21  5267.4  592.65  5375.2  595.92  5415.6  599.00  5539.4  603.20
#Mann=3,-1,0
  4441.6     0.1       0  5179.4    0.07       0  5185.4     0.1       0
Bank Sta=5179.4,5185.4
Exp/Cntr=0.3,0.1

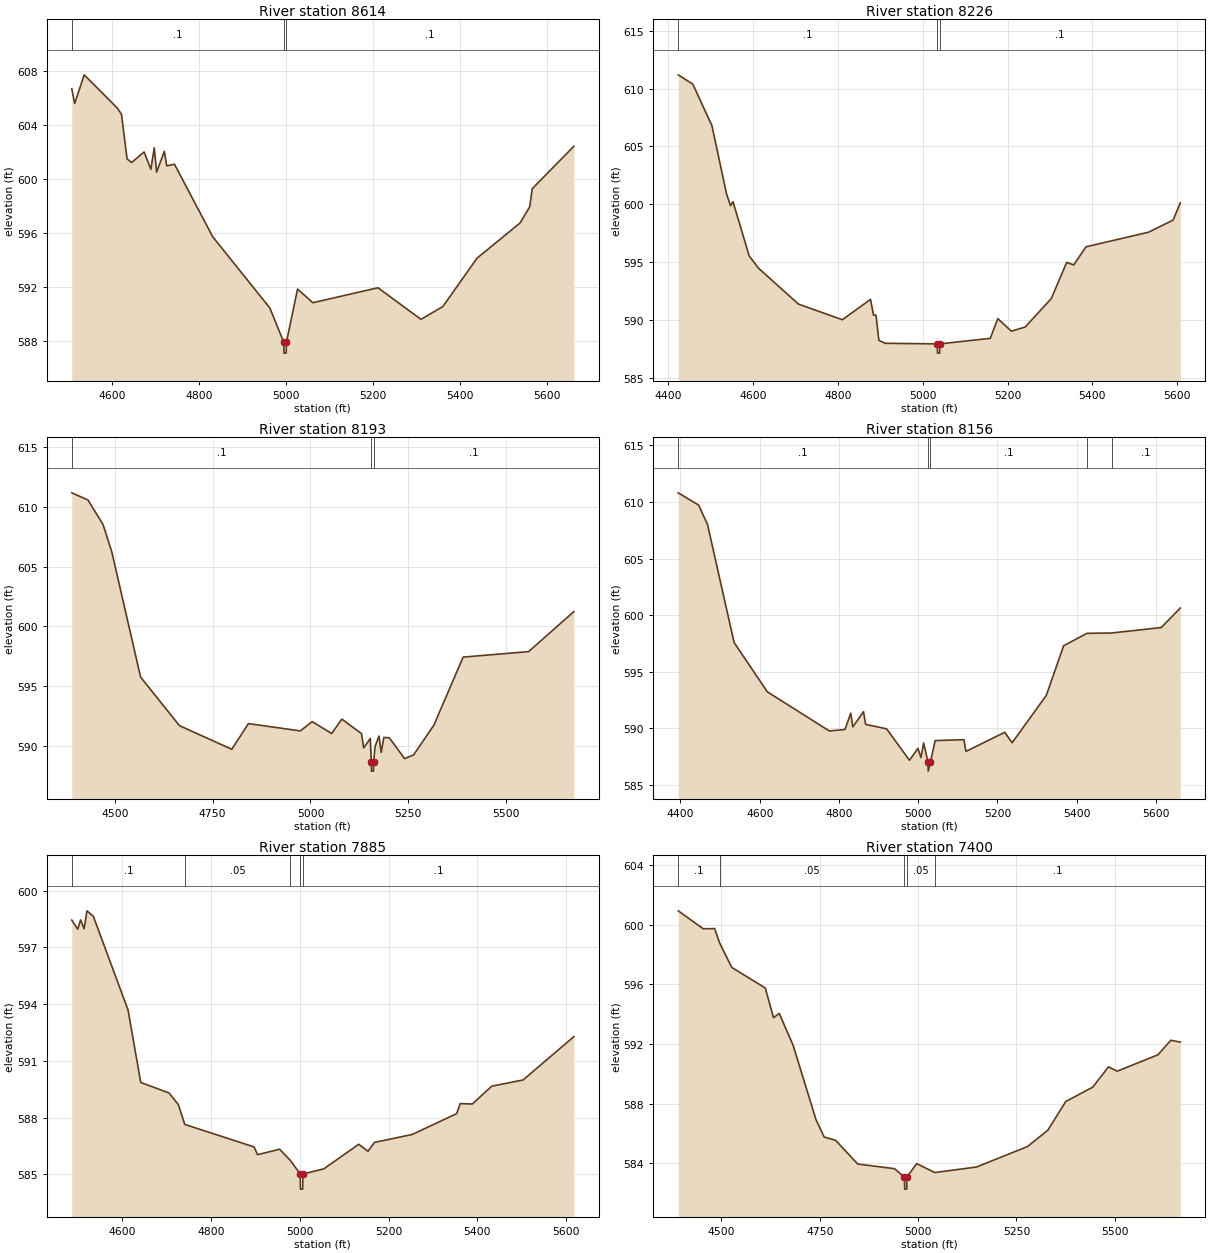
Type RM Length L Ch R = 1,8614,388,388,388
BEGIN DESCRIPTION:
Mapping XS 93a48a4d
END DESCRIPTION:
XS GIS Cut Line= 4
      1963537.92     13523361.16      1963390.34     13523029.09
      1962988.86     13522692.72      1962865.16     13522456.16
#Sta/Elev= 30
  4508.2  606.69  4514.9  605.60  4536.8  607.72  4613.4  605.24  4622.5  604.80
  4635.3  601.50  4645.8  601.23  4674.5  602.01  4690.0  600.73  4697.8  602.32
  4703.3  600.52  4721.0  602.06  4726.5  600.98  4744.3  601.10  4832.3  595.73
  4963.5  590.46  4995.6  587.92  4996.1  587.12  5001.1  587.12  5001.6  587.92
  5027.2  591.86  5062.4  590.85  5212.0  591.96  5310.9  589.62  5361.3  590.57
  5439.8  594.15  5538.9  596.76  5561.0  597.96  5566.6  599.29  5662.3  602.43
#Mann=3,-1,0
  4508.2     0.1       0  4995.6    0.07       0  5001.6     0.1       0
Bank Sta=4995.6,5001.6
Exp/Cntr=0.3,0.1

Type RM Length L Ch R = 1,8226,33,33,33
BEGIN DESCRIPTION:
Mapping XS 5fa6325b
END DESCRIPTION:
XS GIS Cut Line= 6
      1963689.83     13523135.44      1963472.81     13522727.44
      1963509.70     13522651.49      1963483.66     13522610.25
      1963329.58     13522608.08      1962938.39     13522441.67
#Sta/Elev= 30
  4423.0  611.19  4457.5  610.38  4502.5  606.79  4536.8  600.91  4546.4  599.86
  4552.1  600.22  4590.4  595.52  4612.3  594.46  4706.7  591.35  4810.1  590.00
  4876.6  591.76  4883.7  590.40  4889.5  590.40  4896.3  588.21  4911.6  587.96
  5034.1  587.91  5034.6  587.11  5039.6  587.11  5040.1  587.91  5159.0  588.39
  5176.8  590.09  5208.9  589.01  5241.5  589.37  5303.1  591.84  5339.3  594.96
  5355.9  594.74  5384.9  596.31  5532.2  597.57  5590.3  598.62  5607.3  600.12
#Mann=3,-1,0
  4423.0     0.1       0  5034.1    0.07       0  5040.1     0.1       0
Bank Sta=5034.1,5040.1
Exp/Cntr=0.3,0.1

Type RM Length L Ch R = 1,8193,37,37,37
BEGIN DESCRIPTION:
UNT 022 in BCW 14.0
END DESCRIPTION:
XS GIS Cut Line= 6
      1963715.85     13523141.92      1963511.87     13522738.29
      1963550.93     13522660.17      1963485.83     13522560.34
      1963344.77     13522588.55      1962912.90     13522393.24
#Sta/Elev= 30
  4390.2  611.19  4431.6  610.59  4470.2  608.53  4492.5  606.24  4566.0  595.76
  4665.2  591.69  4799.0  589.71  4841.5  591.86  4974.2  591.25  5004.4  592.03
  5054.1  591.03  5080.2  592.24  5130.4  591.02  5136.0  589.83  5152.8  590.62
  5155.4  588.68  5155.9  587.88  5160.9  587.88  5161.4  588.68  5165.0  589.95
  5175.1  590.82  5180.7  589.45  5187.4  590.70  5201.4  590.67  5240.4  588.93
  5263.5  589.24  5315.2  591.73  5390.0  597.43  5557.3  597.89  5672.8  601.24
#Mann=3,-1,0
  4390.2     0.1       0  5155.4    0.07       0  5161.4     0.1       0
Bank Sta=5155.4,5161.4
Exp/Cntr=0.3,0.1

Type RM Length L Ch R = 1,8156,271,271,271
BEGIN DESCRIPTION:
Mapping XS cd3a7c62
END DESCRIPTION:
XS GIS Cut Line= 6
      1963731.04     13523120.22      1963544.42     13522746.97
      1963572.63     13522658.00      1963522.72     13522551.66
      1963342.60     13522542.98      1962930.28     13522380.22
#Sta/Elev= 30
  4394.3  610.81  4445.9  609.72  4468.3  608.00  4535.3  597.58  4619.2  593.22
  4775.7  589.76  4815.3  589.89  4829.7  591.33  4835.0  590.12  4862.0  591.47
  4867.3  590.34  4920.2  589.95  4978.0  587.17  4999.3  588.22  5007.0  587.41
  5013.6  588.70  5024.8  587.01  5025.3  586.21  5030.8  587.01  5042.8  588.91
  5115.4  588.99  5120.5  587.95  5218.3  589.64  5237.2  588.72  5323.3  592.90
  5367.1  597.29  5425.9  598.39  5488.1  598.42  5613.5  598.90  5661.6  600.63
#Mann=5,-1,0
  4394.3     0.1       0  5024.8    0.07       0  5030.8     0.1       0
  5425.9    0.08       0  5488.1     0.1       0
Bank Sta=5024.8,5030.8
Exp/Cntr=0.3,0.1

Type RM Length L Ch R = 1,7885,485,485,485
BEGIN DESCRIPTION:
UNT 022 in BCW 13.0
END DESCRIPTION:
XS GIS Cut Line= 3
      1964119.51     13522699.23      1963724.54     13522373.71
      1963231.04     13521999.26
#Sta/Elev= 30
  4486.1  598.44  4499.5  597.96  4506.0  598.45  4513.9  597.98  4520.3  598.93
  4534.7  598.64  4612.9  593.69  4641.5  589.86  4705.4  589.30  4726.2  588.69
  4740.8  587.64  4896.9  586.45  4904.8  586.04  4954.3  586.33  4978.6  585.74
  5000.8  585.02  5001.3  584.22  5006.4  584.22  5006.9  585.02  5053.8  585.29
  5132.8  586.59  5153.6  586.22  5168.1  586.69  5253.4  587.11  5353.3  588.21
  5361.4  588.74  5388.7  588.72  5432.3  589.66  5503.0  589.99  5617.4  592.28
#Mann=5,-1,0
  4486.1     0.1       0  4740.8    0.05       0  4978.6     0.1       0
  5000.8    0.07       0  5006.9     0.1       0
Bank Sta=5000.8,5006.9
Exp/Cntr=0.3,0.1

Type RM Length L Ch R = 1,7400,543,543,543
BEGIN DESCRIPTION:
UNT 022 in BCW 12.0
END DESCRIPTION:
XS GIS Cut Line= 3
      1964324.97     13522474.96      1963909.00     13521928.83
      1963340.39     13521772.57
#Sta/Elev= 30
  4390.2  600.92  4453.6  599.72  4482.7  599.73  4495.5  598.76  4526.3  597.13
  4611.5  595.75  4632.4  593.76  4646.9  594.05  4682.3  591.91  4740.4  586.93
  4761.2  585.77  4790.3  585.55  4846.5  583.96  4940.0  583.65  4965.3  583.08
  4965.8  582.28  4970.9  582.28  4971.4  583.08  4996.2  583.99  5042.4  583.39
  5148.0  583.76  5277.9  585.13  5329.8  586.23  5375.3  588.15  5443.8  589.11
  5483.8  590.47  5506.1  590.18  5609.8  591.28  5642.2  592.25  5666.4  592.13
#Mann=5,-1,0
  4390.2     0.1       0  4495.5    0.05       0  4965.3   0.035       0
  4971.4    0.05       0  5042.4     0.1       0
Bank Sta=4965.3,4971.4
Exp/Cntr=0.3,0.1

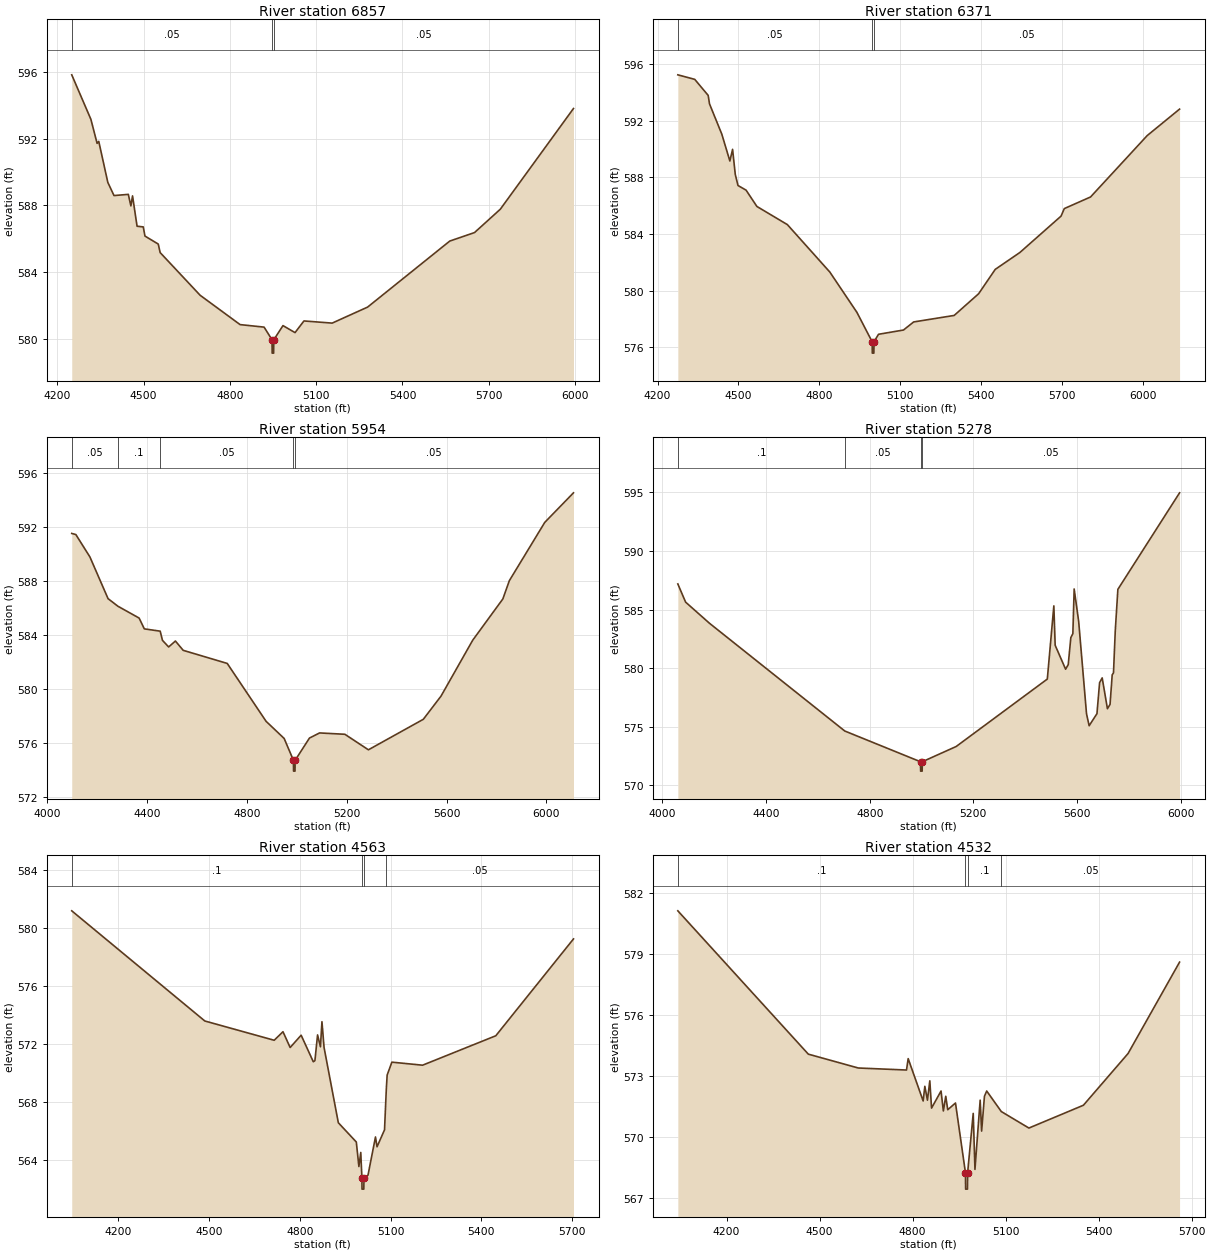
Type RM Length L Ch R = 1,6857,486,486,486
BEGIN DESCRIPTION:
UNT 022 in BCW 11.0
END DESCRIPTION:
XS GIS Cut Line= 3
      1964725.01     13522325.01      1964404.23     13521773.88
      1963995.38     13520745.24
#Sta/Elev= 30
  4250.1  595.83  4316.7  593.16  4338.2  591.72  4344.0  591.84  4375.5  589.38
  4397.0  588.59  4446.8  588.66  4455.7  587.97  4461.5  588.57  4477.2  586.75
  4498.7  586.71  4504.7  586.16  4550.9  585.68  4557.5  585.17  4696.5  582.61
  4835.5  580.85  4918.9  580.70  4946.5  579.94  4947.0  579.14  4952.1  579.14
  4952.6  579.94  4984.6  580.79  5026.5  580.37  5057.5  581.07  5155.6  580.94
  5278.8  581.90  5564.5  585.86  5650.6  586.37  5740.3  587.77  5994.7  593.81
#Mann=3,-1,0
  4250.1    0.05       0  4946.5   0.035       0  4952.6    0.05       0
Bank Sta=4946.5,4952.6
Exp/Cntr=0.3,0.1

Type RM Length L Ch R = 1,6371,417,417,417
BEGIN DESCRIPTION:
UNT 022 in BCW 10.0
END DESCRIPTION:
XS GIS Cut Line= 3
      1964781.83     13522427.57      1964857.35     13521346.80
      1964706.32     13520583.82
#Sta/Elev= 30
  4275.2  595.23  4337.9  594.91  4387.7  593.78  4392.7  593.18  4438.2  591.05
  4468.2  589.15  4478.3  589.97  4488.3  588.20  4498.3  587.42  4528.4  587.09
  4568.5  585.94  4681.5  584.66  4839.1  581.31  4939.4  578.47  4996.1  576.39
  4996.6  575.59  5002.4  575.59  5002.9  576.39  5019.6  576.92  5112.2  577.22
  5149.9  577.79  5300.3  578.25  5391.0  579.78  5452.6  581.50  5543.9  582.69
  5696.8  585.26  5708.8  585.79  5806.2  586.61  6016.2  590.94  6136.4  592.81
#Mann=3,-1,0
  4275.2    0.05       0  4996.1   0.035       0  5002.9    0.05       0
Bank Sta=4996.1,5002.9
Exp/Cntr=0.3,0.1

Type RM Length L Ch R = 1,5954,676,676,676
BEGIN DESCRIPTION:
UNT 022 in BCW 9.0
END DESCRIPTION:
XS GIS Cut Line= 3
      1964995.37     13522615.05      1965221.94     13521807.74
      1965417.24     13520651.52
#Sta/Elev= 30
  4097.4  591.55  4113.8  591.47  4170.2  589.81  4242.9  586.72  4282.2  586.16
  4367.5  585.28  4388.3  584.48  4451.9  584.31  4461.0  583.63  4485.8  583.14
  4512.9  583.58  4544.1  582.89  4720.6  581.92  4876.4  577.63  4948.8  576.36
  4986.0  574.74  4986.5  573.94  4992.3  573.94  4992.8  574.74  5050.2  576.39
  5090.8  576.77  5192.2  576.67  5286.5  575.52  5506.6  577.78  5577.6  579.50
  5704.6  583.64  5825.5  586.70  5851.4  588.05  5993.4  592.37  6108.5  594.56
#Mann=5,-1,0
  4097.4    0.05       0  4282.2     0.1       0  4451.9    0.05       0
  4986.0   0.035       0  4992.8    0.05       0
Bank Sta=4986,4992.8
Exp/Cntr=0.3,0.1

Type RM Length L Ch R = 1,5278,715,715,715
BEGIN DESCRIPTION:
UNT 022 in BCW 8.0
END DESCRIPTION:
XS GIS Cut Line= 3
      1965698.51     13522764.31      1965920.72     13521722.67
      1965806.26     13520859.00
#Sta/Elev= 30
  4059.6  587.18  4089.6  585.63  4181.6  583.83  4703.9  574.64  4996.1  572.02
  4996.6  571.22  5002.5  571.22  5003.0  572.02  5133.8  573.32  5485.5  579.07
  5510.7  585.31  5515.8  581.95  5556.1  579.91  5566.2  580.30  5576.3  582.61
  5584.1  582.94  5589.1  586.75  5606.5  583.99  5636.8  576.11  5646.9  575.09
  5677.1  576.12  5687.2  578.76  5697.3  579.17  5717.5  576.54  5727.6  576.91
  5735.9  579.43  5740.9  579.60  5747.7  583.16  5757.8  586.72  5995.9  594.95
#Mann=4,-1,0
  4059.6     0.1       0  4703.9    0.05       0  4996.1   0.035       0
  5003.0    0.05       0
Bank Sta=4996.1,5003
Exp/Cntr=0.3,0.1

Type RM Length L Ch R = 1,4563,31,31,31
BEGIN DESCRIPTION:
Mapping XS 8f680608
END DESCRIPTION:
XS GIS Cut Line= 6
      1966157.76     13522513.88      1966480.67     13521750.89
      1966556.19     13521693.59      1966527.54     13521654.53
      1966472.86     13521664.95      1966155.17     13521123.31
#Sta/Elev= 30
  4045.5  581.21  4485.7  573.61  4715.2  572.28  4744.3  572.87  4768.0  571.78
  4804.4  572.63  4844.5  570.80  4849.9  570.87  4858.7  572.65  4868.2  571.83
  4873.2  573.56  4880.2  571.78  4927.4  566.59  4986.9  565.26  4995.4  563.57
  5001.6  564.54  5005.3  562.81  5005.8  562.01  5011.7  562.01  5012.2  562.81
  5025.5  562.97  5050.3  565.61  5055.4  564.93  5080.2  566.10  5086.1  568.90
  5088.9  569.88  5104.5  570.77  5206.1  570.56  5448.3  572.59  5705.3  579.27
#Mann=4,-1,0
  4045.5     0.1       0  5005.3    0.07       0  5012.2     0.1       0
  5086.1    0.05       0
Bank Sta=5005.3,5012.2
Exp/Cntr=0.3,0.1

Type RM Length L Ch R = 1,4532,30,30,30
BEGIN DESCRIPTION:
Mapping XS 7ee291ec
END DESCRIPTION:
XS GIS Cut Line= 6
      1966202.03     13522519.10      1966501.50     13521776.93
      1966553.59     13521750.89      1966577.02     13521722.24
      1966579.63     13521683.18      1966215.06     13521105.09
#Sta/Elev= 30
  4042.7  581.11  4463.6  574.07  4624.6  573.39  4780.3  573.29  4785.7  573.85
  4834.0  571.77  4839.4  572.49  4847.8  571.81  4855.5  572.76  4861.1  571.42
  4891.7  572.26  4899.2  571.28  4906.9  572.00  4913.3  571.34  4938.3  571.67
  4970.5  568.24  4971.0  567.44  4976.9  567.44  4977.4  568.24  4995.5  571.16
  5001.1  568.41  5017.9  571.81  5022.6  570.29  5031.7  572.00  5039.0  572.26
  5086.1  571.25  5175.1  570.44  5350.9  571.56  5494.9  574.10  5661.1  578.59
#Mann=4,-1,0
  4042.7     0.1       0  4970.5    0.07       0  4977.4     0.1       0
  5086.1    0.05       0
Bank Sta=4970.5,4977.4
Exp/Cntr=0.3,0.1

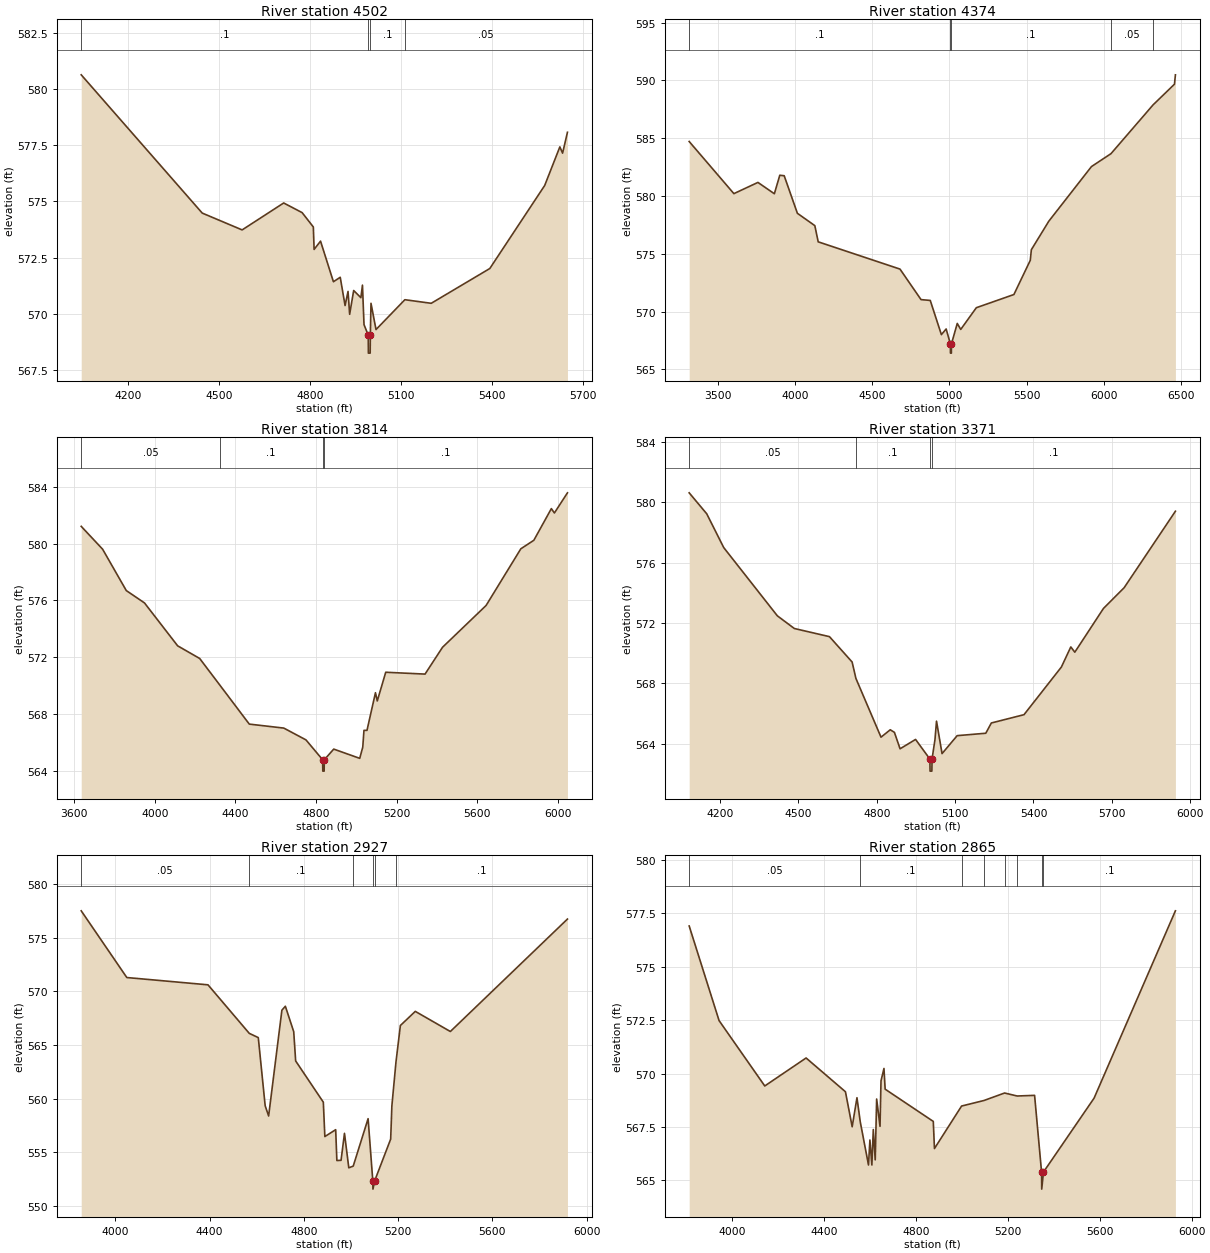
Type RM Length L Ch R = 1,4502,128,128,128
BEGIN DESCRIPTION:
Mapping XS 0342fcb7
END DESCRIPTION:
XS GIS Cut Line= 6
      1966230.66     13522519.14      1966517.13     13521810.78
      1966577.02     13521758.70      1966603.06     13521662.34
      1966569.21     13521597.24      1966243.68     13521112.84
#Sta/Elev= 30
  4046.9  580.64  4445.2  574.48  4576.6  573.73  4713.4  574.93  4774.1  574.50
  4811.0  573.86  4813.5  572.86  4834.7  573.23  4877.1  571.42  4899.5  571.62
  4915.5  570.36  4925.2  570.99  4930.5  569.97  4943.8  571.03  4967.5  570.71
  4972.7  571.27  4977.8  569.51  4991.7  569.04  4992.2  568.24  4998.1  568.24
  4998.6  569.04  5000.8  570.46  5017.3  569.29  5112.3  570.62  5199.1  570.46
  5391.9  572.01  5572.6  575.71  5622.5  577.43  5631.5  577.15  5647.5  578.08
#Mann=4,-1,0
  4046.9     0.1       0  4991.7    0.07       0  4998.6     0.1       0
  5112.3    0.05       0
Bank Sta=4991.7,4998.6
Exp/Cntr=0.3,0.1

Type RM Length L Ch R = 1,4374,560,560,560
BEGIN DESCRIPTION:
Mapping XS 457d9c36
END DESCRIPTION:
XS GIS Cut Line= 4
      1965884.29     13523002.16      1966530.10     13522439.68
      1966790.51     13521356.35      1967617.55     13520518.91
#Sta/Elev= 30
  3315.5  584.72  3604.8  580.21  3760.5  581.18  3866.9  580.20  3902.0  581.80
  3930.5  581.76  4015.9  578.51  4128.9  577.44  4150.7  576.04  4680.2  573.68
  4816.4  571.04  4876.1  570.97  4948.1  568.01  4979.0  568.50  5006.4  567.21
  5006.9  566.41  5012.8  566.41  5013.3  567.21  5050.9  568.98  5073.3  568.46
  5174.4  570.34  5417.5  571.48  5523.6  574.44  5530.6  575.36  5643.8  577.83
  5919.6  582.55  6046.2  583.67  6318.6  587.89  6457.0  589.68  6463.1  590.49
#Mann=5,-1,0
  3315.5     0.1       0  5006.4    0.07       0  5013.3     0.1       0
  6046.2    0.05       0  6318.6     0.1       0
Bank Sta=5006.4,5013.3
Exp/Cntr=0.3,0.1

Type RM Length L Ch R = 1,3814,443,443,443
BEGIN DESCRIPTION:
UNT 022 in BCW 5.0
END DESCRIPTION:
XS GIS Cut Line= 3
      1966618.63     13523094.21      1966990.17     13522118.50
      1967754.04     13520983.10
#Sta/Elev= 30
  3634.9  581.21  3741.1  579.60  3858.5  576.69  3948.8  575.82  4113.3  572.80
  4222.6  571.91  4322.4  570.04  4468.7  567.29  4639.9  567.01  4749.9  566.18
  4832.8  564.78  4833.5  563.98  4840.2  563.98  4840.9  564.78  4887.8  565.53
  5016.8  564.88  5031.8  565.67  5037.8  566.85  5052.8  566.85  5094.8  569.50
  5103.8  568.92  5145.8  570.94  5340.8  570.81  5427.7  572.70  5643.7  575.64
  5816.1  579.63  5880.7  580.23  5967.6  582.46  5982.6  582.15  6047.4  583.57
#Mann=4,-1,0
  3634.9    0.05       0  4322.4     0.1       0  4832.8    0.07       0
  4840.9     0.1       0
Bank Sta=4832.8,4840.9
Exp/Cntr=0.3,0.1

Type RM Length L Ch R = 1,3371,444,444,444
BEGIN DESCRIPTION:
UNT 022 in BCW 4.0
END DESCRIPTION:
XS GIS Cut Line= 3
      1966925.00     13523024.99      1967375.00     13522225.00
      1967875.02     13521424.97
#Sta/Elev= 30
  4082.1  580.63  4149.3  579.24  4214.4  577.00  4419.6  572.48  4484.6  571.64
  4619.1  571.10  4705.8  569.42  4720.4  568.33  4816.4  564.44  4851.8  564.93
  4867.7  564.76  4889.4  563.67  4948.7  564.29  5003.5  562.99  5004.2  562.19
  5011.1  562.19  5011.8  562.99  5023.0  564.28  5028.9  565.50  5050.1  563.35
  5107.9  564.54  5217.5  564.70  5238.8  565.38  5363.8  565.93  5507.0  569.09
  5543.0  570.42  5558.3  570.07  5668.0  572.97  5747.0  574.34  5943.4  579.41
#Mann=4,-1,0
  4082.1    0.05       0  4720.4     0.1       0  5003.5    0.07       0
  5011.8     0.1       0
Bank Sta=5003.5,5011.8
Exp/Cntr=0.3,0.1

Type RM Length L Ch R = 1,2927,62,62,62
BEGIN DESCRIPTION:
Mapping XS 6c18271b
END DESCRIPTION:
XS GIS Cut Line= 6
      1967067.16     13523008.40      1967609.67     13522270.58
      1967809.32     13522253.22      1967648.73     13522131.70
      1967640.05     13522014.51      1967917.84     13521511.01
#Sta/Elev= 30
  3855.0  577.53  4048.5  571.30  4392.9  570.62  4568.0  566.09  4606.4  565.69
  4635.6  559.33  4650.3  558.37  4706.6  568.25  4721.3  568.62  4756.8  566.24
  4765.0  563.51  4882.4  559.66  4888.9  556.45  4934.8  557.09  4939.9  554.21
  4957.6  554.23  4972.2  556.75  4990.5  553.53  5009.3  553.69  5072.4  558.12
  5092.3  552.34  5093.0  551.54  5100.7  552.34  5168.2  556.21  5173.3  559.31
  5190.7  563.41  5209.4  566.82  5272.7  568.14  5421.5  566.26  5918.4  576.76
#Mann=6,-1,0
  3855.0    0.05       0  4568.0     0.1       0  5009.3    0.05       0
  5092.3    0.07       0  5100.7    0.05       0  5190.7     0.1       0
Bank Sta=5092.3,5100.7
Exp/Cntr=0.3,0.1

Type RM Length L Ch R = 1,2865,52,52,52
BEGIN DESCRIPTION:
Mapping XS 7fcff9ea
END DESCRIPTION:
XS GIS Cut Line= 6
      1967088.86     13523030.10      1967583.63     13522353.05
      1967861.40     13522287.95      1967848.38     13522123.01
      1967692.13     13522066.59      1967987.12     13521489.63
#Sta/Elev= 30
  3811.5  576.91  3941.7  572.48  4140.7  569.42  4320.7  570.73  4492.1  569.15
  4521.4  567.51  4542.3  568.87  4556.5  567.75  4592.5  565.72  4598.7  566.89
  4607.2  565.72  4613.4  567.38  4621.8  565.96  4628.0  568.81  4642.7  567.53
  4647.0  569.66  4659.9  570.24  4665.0  569.27  4874.7  567.76  4879.8  566.49
  4998.0  568.48  5095.7  568.74  5185.3  569.09  5240.1  568.95  5315.9  568.98
  5346.3  565.39  5347.0  564.59  5354.7  565.39  5575.1  568.85  5929.3  577.62
#Mann=8,-1,0
  3811.5    0.05       0  4556.5     0.1       0  4998.0    0.05       0
  5095.7     0.1       0  5185.3    0.05       0  5240.1     0.1       0
  5346.3   0.033       0  5354.7     0.1       0
Bank Sta=5346.3,5354.7
Exp/Cntr=0.3,0.1

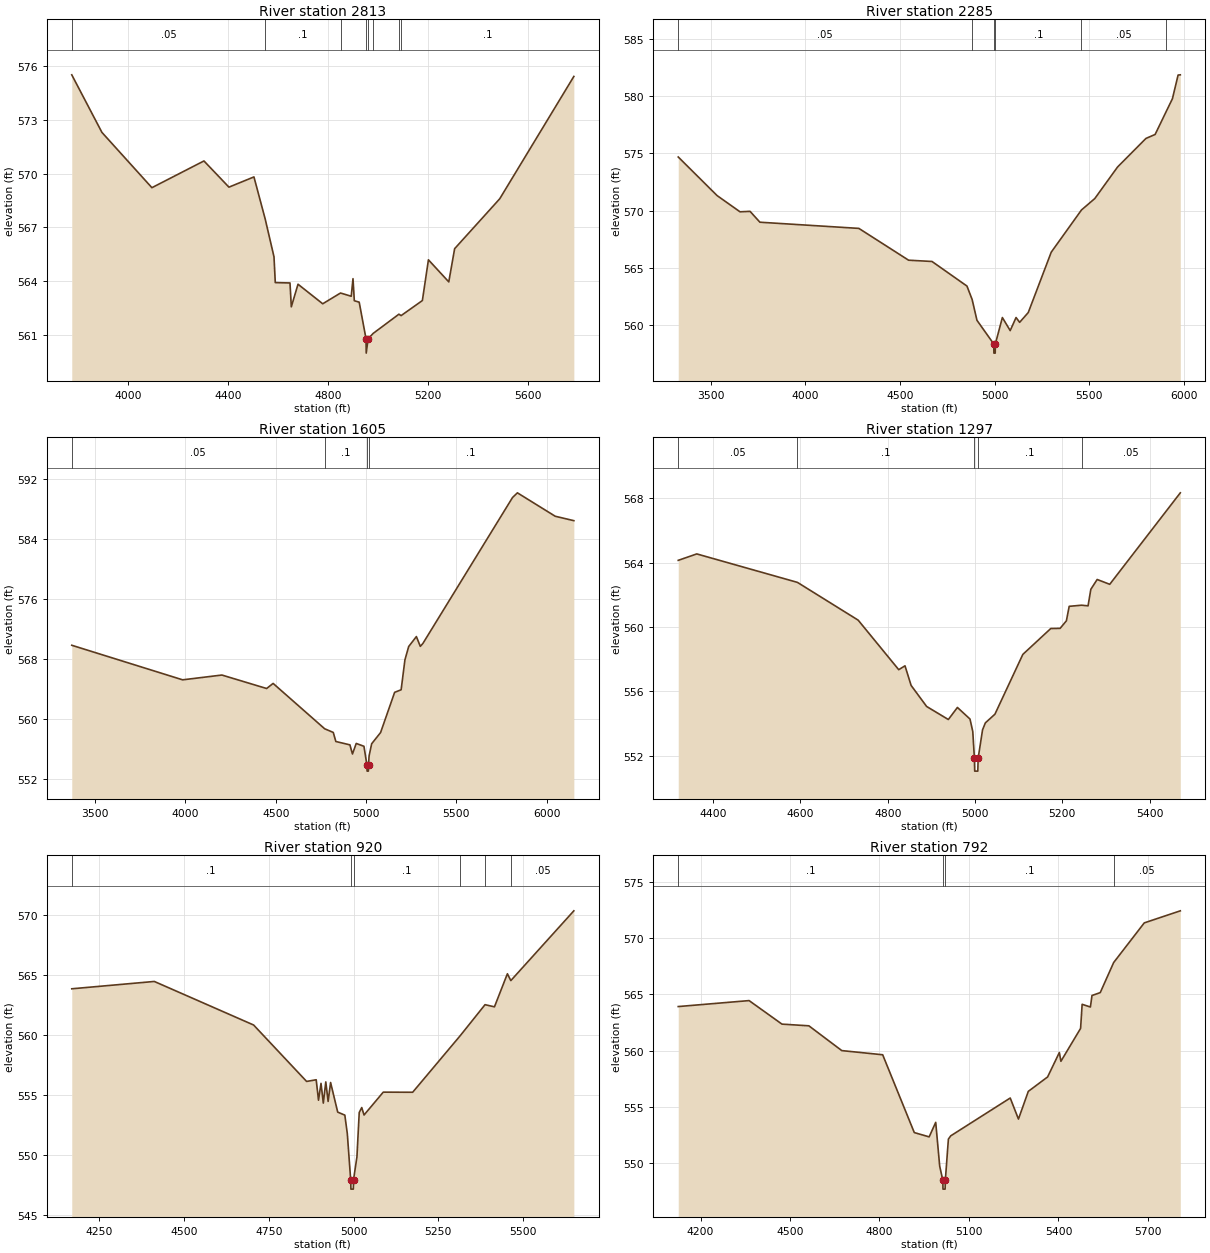
Type RM Length L Ch R = 1,2813,528,528,528
BEGIN DESCRIPTION:
Mapping XS 0716d0f0
END DESCRIPTION:
XS GIS Cut Line= 6
      1967119.23     13523038.79      1967596.65     13522405.13
      1967904.81     13522331.35      1967913.49     13522157.74
      1967791.96     13522018.85      1968000.14     13521541.77
#Sta/Elev= 30
  3775.8  575.50  3896.5  572.29  4096.3  569.21  4304.5  570.70  4404.4  569.24
  4504.4  569.81  4549.5  567.46  4584.6  565.36  4589.8  563.92  4648.6  563.90
  4653.9  562.57  4680.7  563.83  4779.5  562.74  4850.7  563.34  4893.5  563.16
  4900.6  564.14  4905.9  562.91  4925.4  562.83  4952.7  560.79  4953.5  559.99
  4961.1  560.79  4981.4  561.09  5084.3  562.16  5093.0  562.08  5178.1  562.92
  5202.3  565.19  5283.7  563.96  5307.1  565.81  5487.4  568.59  5783.9  575.41
#Mann=8,-1,0
  3775.8    0.05       0  4549.5     0.1       0  4850.7    0.05       0
  4952.7    0.07       0  4961.1    0.05       0  4981.4     0.1       0
  5084.3    0.05       0  5093.0     0.1       0
Bank Sta=4952.7,4961.1
Exp/Cntr=0.3,0.1

Type RM Length L Ch R = 1,2285,680,680,680
BEGIN DESCRIPTION:
UNT 022 in BCW 3.0
END DESCRIPTION:
XS GIS Cut Line= 4
      1967205.99     13523134.31      1968321.47     13522643.85
      1968512.45     13521910.34      1968534.15     13521233.29
#Sta/Elev= 30
  3327.5  574.69  3532.7  571.32  3654.1  569.90  3707.1  569.94  3759.2  568.99
  4282.3  568.45  4545.2  565.67  4668.9  565.56  4853.7  563.41  4881.0  562.24
  4906.5  560.42  4995.3  558.35  4996.1  557.55  5003.0  557.55  5003.7  558.35
  5040.9  560.66  5082.2  559.52  5113.2  560.66  5132.1  560.24  5177.8  561.10
  5299.1  566.37  5459.0  570.06  5529.5  571.06  5649.5  573.81  5799.6  576.31
  5848.3  576.66  5905.0  578.60  5939.7  579.78  5969.7  581.85  5981.4  581.87
#Mann=6,-1,0
  3327.5    0.05       0  4881.0     0.1       0  4995.3    0.07       0
  5003.7     0.1       0  5459.0    0.05       0  5905.0     0.1       0
Bank Sta=4995.3,5003.7
Exp/Cntr=0.3,0.1

Type RM Length L Ch R = 1,1605,308,308,308
BEGIN DESCRIPTION:
UNT 022 in BCW 2.0
END DESCRIPTION:
XS GIS Cut Line= 4
      1967592.28     13523086.56      1968390.92     13522999.75
      1969302.38     13522192.46      1969128.77     13521454.62
#Sta/Elev= 30
  3371.3  569.84  3984.9  565.22  4202.3  565.86  4449.8  564.06  4485.8  564.74
  4771.0  558.68  4818.7  558.19  4832.9  556.98  4910.7  556.53  4924.9  555.31
  4945.8  556.72  4988.5  556.34  5005.1  553.82  5005.9  553.02  5012.9  553.02
  5013.7  553.82  5016.9  555.05  5031.2  556.68  5080.5  558.17  5158.3  563.55
  5194.3  563.89  5215.2  567.88  5236.1  569.67  5278.7  571.00  5300.5  569.69
  5314.7  570.08  5810.8  589.58  5837.8  590.21  6047.1  587.08  6150.2  586.49
#Mann=4,-1,0
  3371.3    0.05       0  4771.0     0.1       0  5005.1    0.07       0
  5013.7     0.1       0
Bank Sta=5005.1,5013.7
Exp/Cntr=0.3,0.1

Type RM Length L Ch R = 1,1297,377,377,377
BEGIN DESCRIPTION:
Mapping XS b66ecf65
END DESCRIPTION:
XS GIS Cut Line= 2
      1968668.18     13523107.65      1969566.83     13522389.42
#Sta/Elev= 30
  4320.0  564.14  4362.5  564.54  4593.1  562.77  4732.3  560.42  4825.2  557.34
  4839.6  557.58  4853.6  556.36  4889.2  555.05  4938.9  554.24  4959.7  554.99
  4988.5  554.27  4994.9  553.49  4998.6  551.83  4999.3  551.03  5006.4  551.03
  5007.2  551.83  5017.3  553.60  5023.7  554.03  5045.6  554.57  5109.6  558.29
  5173.6  559.90  5195.0  559.91  5209.4  560.38  5215.8  561.28  5244.3  561.35
  5259.0  561.31  5265.4  562.34  5279.9  562.95  5308.7  562.65  5470.4  568.34
#Mann=5,-1,0
  4320.0    0.05       0  4593.1     0.1       0  4998.6    0.07       0
  5007.2     0.1       0  5244.3    0.05       0
Bank Sta=4998.6,5007.2
Exp/Cntr=0.3,0.1

Type RM Length L Ch R = 1,920,128,128,128
BEGIN DESCRIPTION:
Mapping XS 4ed4a774
END DESCRIPTION:
XS GIS Cut Line= 4
      1968693.97     13523189.25      1969275.55     13523104.18
      1969529.02     13522868.07      1969687.02     13522343.73
#Sta/Elev= 30
  4168.2  563.84  4411.8  564.45  4704.9  560.83  4861.3  556.14  4889.6  556.28
  4896.4  554.58  4903.8  555.98  4910.6  554.34  4917.9  556.10  4924.8  554.48
  4932.1  556.05  4953.1  553.59  4974.1  553.34  4981.4  551.81  4991.3  547.99
  4992.1  547.19  4999.2  547.19  4999.9  547.99  5009.8  549.86  5016.6  553.56
  5024.0  553.97  5030.8  553.35  5087.5  555.25  5174.3  555.24  5314.3  559.93
  5387.9  562.52  5415.7  562.34  5453.9  565.09  5464.0  564.52  5650.0  570.32
#Mann=6,-1,0
  4168.2     0.1       0  4991.3    0.07       0  4999.9     0.1       0
  5314.3    0.05       0  5387.9     0.1       0  5464.0    0.05       0
Bank Sta=4991.3,4999.9
Exp/Cntr=0.3,0.1

Type RM Length L Ch R = 1,792,157,157,157
BEGIN DESCRIPTION:
Mapping XS ae740199
END DESCRIPTION:
XS GIS Cut Line= 4
      1968718.21     13523215.30      1969362.35     13523166.68
      1969714.78     13522897.59      1969886.37     13522329.11
#Sta/Elev= 30
  4125.3  563.92  4362.8  564.45  4473.1  562.36  4563.3  562.21  4673.6  560.01
  4810.7  559.64  4916.7  552.73  4966.6  552.35  4988.5  553.64  5001.9  549.74
  5012.2  548.51  5012.9  547.71  5020.0  547.71  5020.8  548.51  5031.0  552.15
  5038.8  552.44  5238.3  555.80  5265.9  553.93  5298.9  556.39  5363.6  557.67
  5403.0  559.84  5408.2  559.06  5474.2  561.98  5479.4  564.12  5507.1  563.88
  5512.4  564.90  5540.1  565.16  5585.1  567.83  5687.7  571.35  5808.5  572.42
#Mann=4,-1,0
  4125.3     0.1       0  5012.2    0.07       0  5020.8     0.1       0
  5585.1    0.05       0
Bank Sta=5012.2,5020.8
Exp/Cntr=0.3,0.1

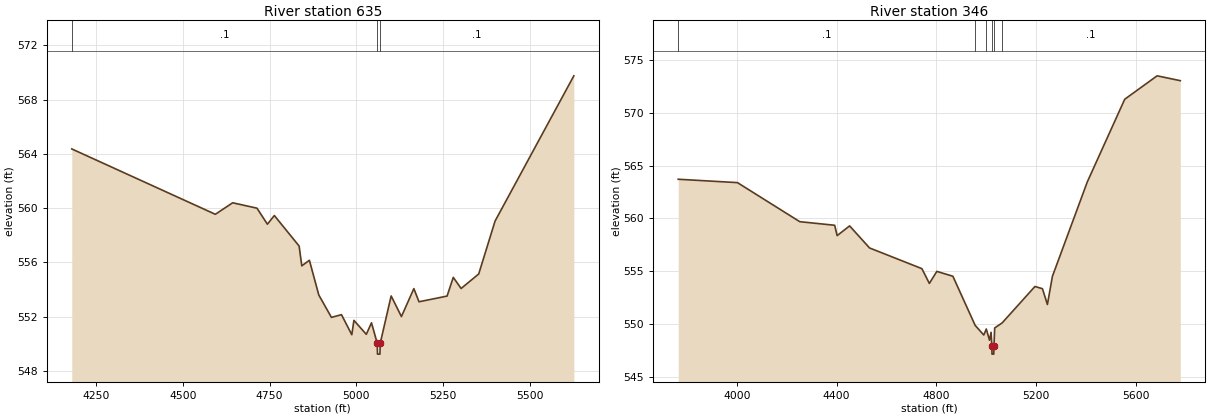
Type RM Length L Ch R = 1,635,289,289,289
BEGIN DESCRIPTION:
Mapping XS 21a1b5fb
END DESCRIPTION:
XS GIS Cut Line= 4
      1968891.37     13523222.37      1969503.36     13523213.69
      1969848.41     13522972.80      1969917.85     13522564.84
#Sta/Elev= 30
  4179.8  564.36  4593.5  559.54  4643.5  560.39  4713.5  559.99  4743.5  558.81
  4763.5  559.45  4834.9  557.20  4842.6  555.74  4864.5  556.15  4891.6  553.59
  4928.0  551.94  4957.0  552.14  4986.7  550.66  4992.8  551.72  5028.5  550.69
  5043.4  551.54  5060.0  550.03  5060.7  549.23  5067.8  549.23  5068.6  550.03
  5100.1  553.52  5129.7  552.00  5165.5  554.06  5180.3  553.09  5261.2  553.51
  5279.1  554.89  5301.7  554.07  5352.4  555.14  5399.5  559.04  5626.5  569.75
#Mann=3,-1,0
  4179.8     0.1       0  5060.0    0.07       0  5068.6     0.1       0
Bank Sta=5060,5068.6
Exp/Cntr=0.3,0.1

Type RM Length L Ch R = 1,346,0,0,0
BEGIN DESCRIPTION:
UNT 022 in BCW 1.0
END DESCRIPTION:
XS GIS Cut Line= 4
      1968757.30     13523259.57      1969856.66     13523245.37
      1970011.17     13523040.51      1969991.69     13522381.95
#Sta/Elev= 30
  3764.5  563.71  4002.2  563.39  4252.2  559.69  4392.3  559.35  4402.3  558.37
  4452.3  559.29  4532.3  557.20  4742.3  555.24  4772.3  553.84  4802.3  554.98
  4866.7  554.52  4956.2  549.86  4990.8  548.95  5000.8  549.52  5013.7  548.46
  5020.0  549.21  5023.0  547.94  5023.7  547.14  5030.8  547.14  5031.6  547.94
  5034.5  549.62  5064.5  550.10  5196.1  553.55  5226.1  553.34  5246.1  551.84
  5266.1  554.51  5406.2  563.46  5556.3  571.29  5686.3  573.51  5779.4  573.05
#Mann=6,-1,0
  3764.5     0.1       0  4956.2    0.07       0  5000.8    0.12       0
  5023.0    0.07       0  5031.6    0.12       0  5064.5     0.1       0
Bank Sta=5023,5031.6
Exp/Cntr=0.3,0.1

Chan Stop Cuts=-1