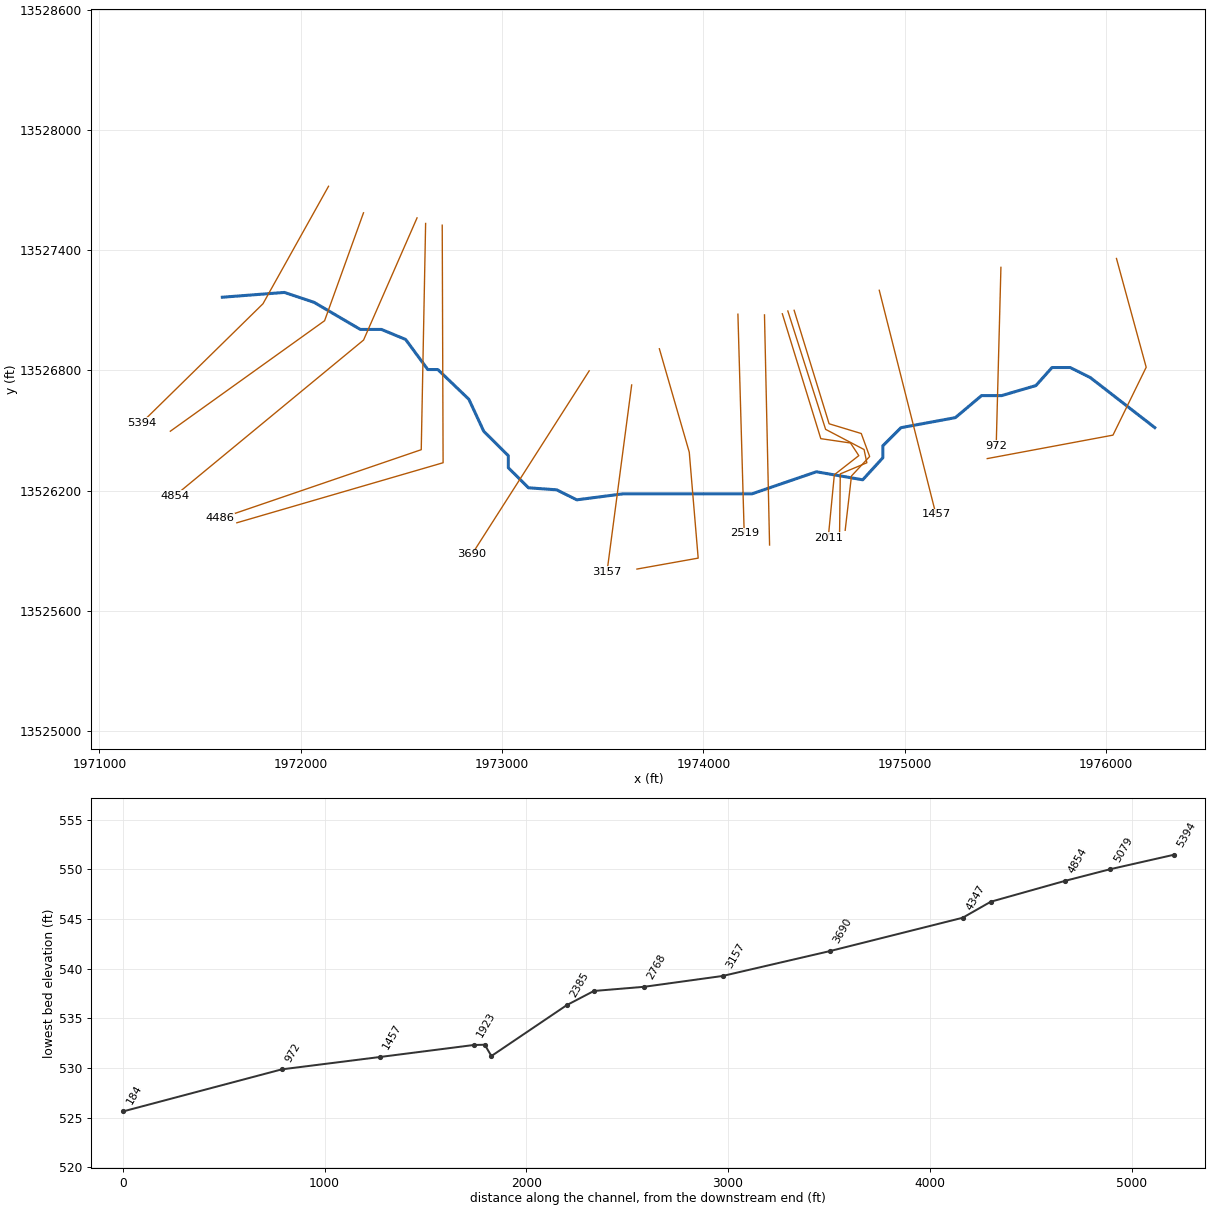
--- UNT 023 in BCW.prj (project) ---

Proj Title=UNT 023 in BCW Base Level Engineering
Current Plan=p01
Default Exp/Contr=0.3,0.1
English Units
Geom File=g01
Flow File=f01
Plan File=p01
BEGIN DESCRIPTION:
UNT 023 in BCW
END DESCRIPTION:

--- UNT 023 in BCW.p01 (plan) ---

Plan Title=Multiple Run
Short Identifier=Multiple
Geom File=g01
Flow File=f01
Subcritical Flow
K Sum by GR= 0
Std Step Tol= 0.01
Critical Tol= 0.01
Num of Std Step Trials= 20
Max Error Tol= 0.3
Flow Tol Ratio= 0.001
Split Flow NTrial= 30
Split Flow Tol= 0.02
Split Flow Ratio= 0.02
Log Output Level= 0
Friction Slope Method= 1
Unsteady Friction Slope Method= 2
Unsteady Bridges Friction Slope Method= 1
Parabolic Critical Depth
Global Vel Dist=  1 , 1 , 1
Global Log Level= 0
CheckData=True
Encroach Param= -1, 0, 0, 0
BEGIN DESCRIPTION:
Multiple Run
END DESCRIPTION:

--- UNT 023 in BCW.f01 (steady flow) ---

Flow Title=Multiple
Number of Profiles=7
Profile Names=10-year,25-year,50-year,1pct_min,100-year,1pct_plu,500-year
River Rch & RM= UNT 023 in BCW,Reach-1,5394
     114     152     182     109     217     433     314
River Rch & RM= UNT 023 in BCW,Reach-1,5079
     179     243     296     180     358     715     535
River Rch & RM= UNT 023 in BCW,Reach-1,2011
     226     312     382     234     466     931     706
Boundary for River Rch & Prof#=UNT 023 in BCW,Reach-1,1
Up Type=0
Dn Type=3
Dn Slope=0.005
Boundary for River Rch & Prof#=UNT 023 in BCW,Reach-1,2
Up Type=0
Dn Type=3
Dn Slope=0.005
Boundary for River Rch & Prof#=UNT 023 in BCW,Reach-1,3
Up Type=0
Dn Type=3
Dn Slope=0.005
Boundary for River Rch & Prof#=UNT 023 in BCW,Reach-1,4
Up Type=0
Dn Type=3
Dn Slope=0.005
Boundary for River Rch & Prof#=UNT 023 in BCW,Reach-1,5
Up Type=0
Dn Type=3
Dn Slope=0.005
Boundary for River Rch & Prof#=UNT 023 in BCW,Reach-1,6
Up Type=0
Dn Type=3
Dn Slope=0.005
Boundary for River Rch & Prof#=UNT 023 in BCW,Reach-1,7
Up Type=0
Dn Type=3
Dn Slope=0.005

--- UNT 023 in BCW.g01 (geometry) ---

Geom Title=Existing Conditions

River Reach=UNT 023 in BCW,Reach-1
Reach XY= 30
      1971610.62     13527165.24      1971918.78     13527189.11
      1972066.29     13527139.66      1972295.77     13527004.54
      1972400.80     13527004.54      1972520.80     13526954.54
      1972630.80     13526804.54      1972680.80     13526804.54
      1972834.84     13526656.16      1972908.76     13526496.58
      1973030.80     13526374.54      1973030.80     13526314.54
      1973130.80     13526214.54      1973270.80     13526204.54
      1973370.80     13526154.54      1973600.80     13526184.54
      1974240.80     13526184.54      1974560.80     13526294.54
      1974790.80     13526254.54      1974890.80     13526364.54
      1974890.80     13526424.54      1974980.80     13526514.54
      1975250.80     13526564.54      1975380.80     13526674.54
      1975480.80     13526674.54      1975650.80     13526724.54
      1975730.80     13526814.54      1975820.80     13526814.54
      1975920.80     13526764.54      1976241.06     13526514.87

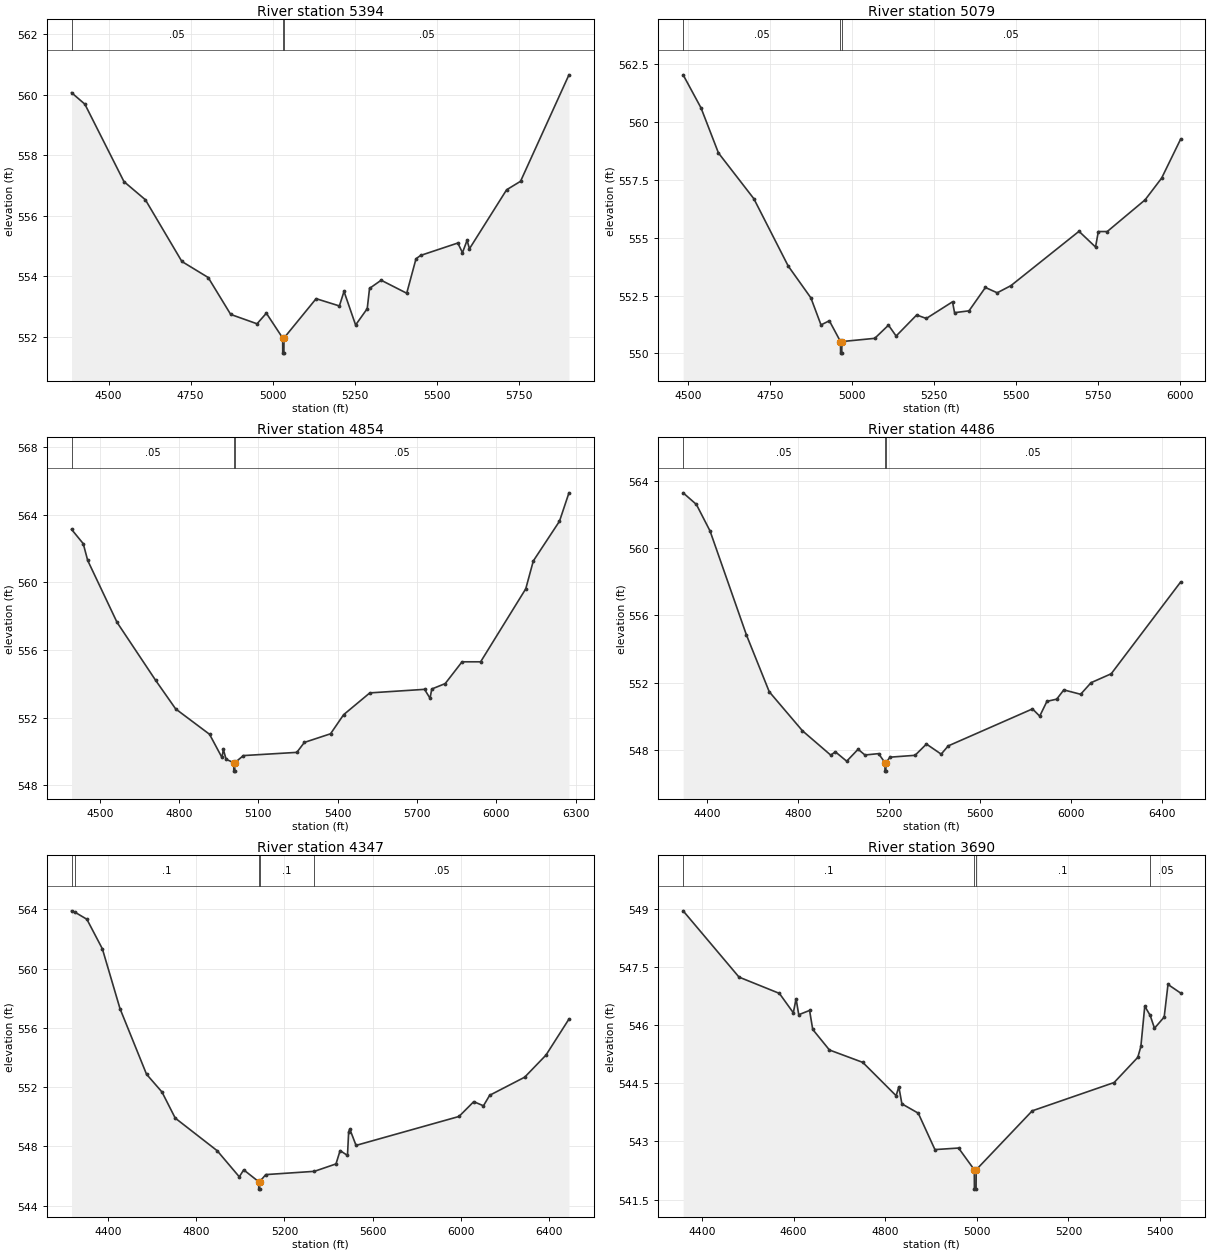
Type RM Length L Ch R = 1,5394,315,315,315
BEGIN DESCRIPTION:
Mapping XS 06d3ec40
END DESCRIPTION:
XS GIS Cut Line= 3
      1972137.97     13527718.64      1971812.44     13527132.69
      1971211.32     13526540.25
#Sta/Elev= 30
  4387.3  560.07  4427.9  559.69  4546.9  557.13  4612.1  556.53  4723.2  554.49
  4803.3  553.96  4871.8  552.74  4952.0  552.43  4980.4  552.78  5030.1  551.96
  5030.3  551.46  5033.8  551.46  5034.1  551.96  5131.9  553.26  5202.7  553.02
  5216.8  553.50  5252.1  552.39  5287.5  552.93  5294.5  553.60  5329.9  553.87
  5407.7  553.44  5436.0  554.58  5450.1  554.69  5563.3  555.10  5577.4  554.78
  5591.5  555.19  5598.7  554.91  5711.8  556.86  5754.2  557.14  5901.6  560.66
#Mann=3,-1,0
  4387.3    0.05       0  5030.1   0.035       0  5034.1    0.05       0
Bank Sta=5030.1,5034.1
Exp/Cntr=0.3,0.1

Type RM Length L Ch R = 1,5079,225,225,225
BEGIN DESCRIPTION:
Mapping XS e008c1b8
END DESCRIPTION:
XS GIS Cut Line= 3
      1972311.58     13527586.27      1972118.43     13527048.05
      1971352.36     13526496.83
#Sta/Elev= 30
  4485.4  562.05  4539.9  560.62  4593.0  558.67  4700.9  556.69  4805.5  553.78
  4874.7  552.40  4905.5  551.23  4930.9  551.41  4964.9  550.51  4965.2  550.01
  4968.8  550.01  4969.0  550.51  5069.3  550.65  5111.1  551.22  5134.4  550.75
  5197.0  551.66  5226.4  551.51  5306.2  552.23  5312.4  551.76  5356.5  551.84
  5406.4  552.85  5442.4  552.62  5484.2  552.93  5691.6  555.28  5742.0  554.60
  5750.5  555.27  5777.6  555.27  5892.9  556.64  5943.3  557.58  6001.0  559.26
#Mann=3,-1,0
  4485.4    0.05       0  4964.9   0.035       0  4969.0    0.05       0
Bank Sta=4964.9,4969
Exp/Cntr=0.3,0.1

Type RM Length L Ch R = 1,4854,368,368,368
BEGIN DESCRIPTION:
UNT 023 in BCW 2.0
END DESCRIPTION:
XS GIS Cut Line= 3
      1972577.56     13527560.97      1972311.93     13526951.57
      1971375.00     13526175.00
#Sta/Elev= 30
  4393.0  563.14  4437.3  562.29  4454.1  561.30  4565.3  557.63  4711.3  554.20
  4787.0  552.51  4915.1  551.01  4961.9  549.64  4967.4  550.11  4977.7  549.53
  5006.7  549.33  5006.9  548.83  5010.5  548.83  5010.8  549.33  5043.1  549.75
  5245.2  549.94  5273.9  550.53  5372.8  551.04  5422.3  552.17  5521.4  553.46
  5728.4  553.67  5749.2  553.14  5755.7  553.69  5806.5  554.01  5870.3  555.30
  5940.6  555.30  6111.3  559.62  6139.9  561.27  6238.9  563.62  6274.7  565.30
#Mann=3,-1,0
  4393.0    0.05       0  5006.7   0.035       0  5010.8    0.05       0
Bank Sta=5006.7,5010.8
Exp/Cntr=0.3,0.1

Type RM Length L Ch R = 1,4486,139,139,139
BEGIN DESCRIPTION:
UNT 023 in BCW 1.0
END DESCRIPTION:
XS GIS Cut Line= 3
      1972620.09     13527533.17      1972598.38     13526404.70
      1971600.11     13526061.81
#Sta/Elev= 30
  4295.5  563.28  4353.7  562.59  4413.7  561.01  4573.7  554.82  4673.7  551.45
  4819.4  549.13  4943.8  547.68  4963.8  547.88  5013.8  547.32  5063.8  548.03
  5093.8  547.69  5153.8  547.77  5181.8  547.23  5182.0  546.73  5185.6  546.73
  5185.9  547.23  5203.8  547.56  5313.9  547.67  5363.9  548.34  5428.6  547.74
  5459.5  548.23  5829.5  550.43  5861.3  550.00  5893.0  550.88  5935.9  551.01
  5967.1  551.56  6041.0  551.30  6086.8  551.99  6175.3  552.52  6479.7  557.97
#Mann=3,-1,0
  4295.5    0.05       0  5181.8    0.04       0  5185.9    0.05       0
Bank Sta=5181.8,5185.9
Exp/Cntr=0.3,0.1

Type RM Length L Ch R = 1,4347,657,657,657
BEGIN DESCRIPTION:
UNT 023 in BCW 4.0
END DESCRIPTION:
XS GIS Cut Line= 3
      1972702.55     13527524.51      1972706.89     13526339.59
      1971682.60     13526040.12
#Sta/Elev= 30
  4236.1  563.89  4251.2  563.80  4305.6  563.32  4375.6  561.33  4455.6  557.29
  4575.6  552.87  4645.6  551.67  4705.6  549.91  4895.6  547.71  4995.6  545.95
  5015.6  546.42  5083.6  545.62  5083.8  545.12  5087.4  545.12  5087.7  545.62
  5115.6  546.10  5335.6  546.32  5433.4  546.82  5452.1  547.72  5485.5  547.39
  5490.8  548.99  5496.0  549.17  5524.2  548.07  5990.3  550.02  6057.2  551.02
  6101.0  550.74  6129.3  551.45  6287.7  552.67  6384.2  554.16  6488.2  556.59
#Mann=5,-1,0
  4236.1    0.05       0  4251.2     0.1       0  5083.6    0.07       0
  5087.7     0.1       0  5335.6    0.05       0
Bank Sta=5083.6,5087.7
Exp/Cntr=0.3,0.1

Type RM Length L Ch R = 1,3690,533,533,533
BEGIN DESCRIPTION:
Mapping XS 53977264
END DESCRIPTION:
XS GIS Cut Line= 2
      1973432.37     13526797.89      1972849.49     13525881.92
#Sta/Elev= 30
  4359.0  548.95  4481.0  547.24  4569.1  546.82  4599.5  546.32  4605.5  546.68
  4611.4  546.27  4635.0  546.38  4641.9  545.89  4678.3  545.36  4751.1  545.04
  4823.9  544.18  4829.8  544.41  4836.5  543.97  4872.2  543.73  4908.6  542.79
  4960.2  542.83  4994.5  542.27  4994.8  541.77  4998.4  541.77  4998.7  542.27
  5121.0  543.79  5299.7  544.52  5351.4  545.17  5358.1  545.45  5366.6  546.49
  5378.5  546.25  5387.8  545.92  5409.0  546.21  5417.3  547.05  5444.7  546.83
#Mann=4,-1,0
  4359.0     0.1       0  4994.5    0.07       0  4998.7     0.1       0
  5378.5    0.05       0
Bank Sta=4994.5,4998.7
Exp/Cntr=0.3,0.1

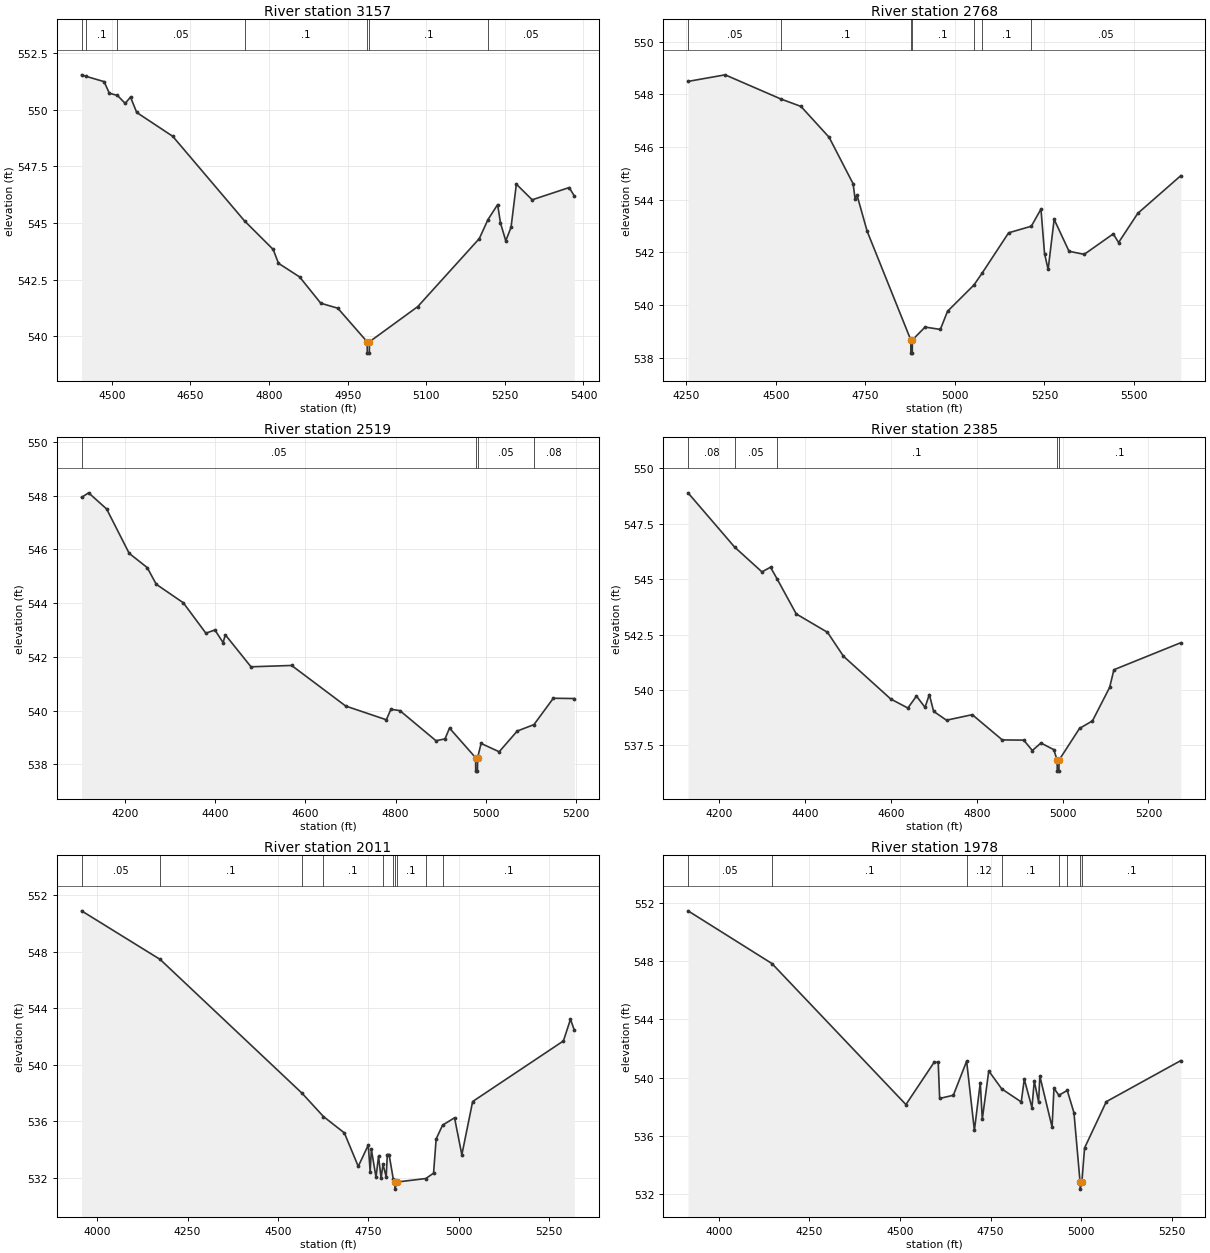
Type RM Length L Ch R = 1,3157,389,389,389
BEGIN DESCRIPTION:
Mapping XS 0724bf8a
END DESCRIPTION:
XS GIS Cut Line= 2
      1973643.30     13526727.59      1973520.90     13525795.29
#Sta/Elev= 30
  4442.2  551.53  4449.8  551.47  4485.2  551.23  4495.2  550.72  4510.7  550.62
  4525.5  550.27  4535.6  550.55  4547.5  549.87  4616.2  548.82  4753.2  545.09
  4807.9  543.83  4818.0  543.22  4858.3  542.62  4898.7  541.46  4931.2  541.24
  4987.2  539.76  4987.5  539.26  4991.3  539.26  4991.6  539.76  5083.7  541.31
  5201.2  544.31  5217.8  545.15  5236.2  545.81  5241.6  545.00  5251.7  544.21
  5261.8  544.81  5271.9  546.71  5302.1  546.02  5372.7  546.56  5382.5  546.19
#Mann=7,-1,0
  4442.2    0.05       0  4449.8     0.1       0  4510.7    0.05       0
  4753.2     0.1       0  4987.2    0.07       0  4991.6     0.1       0
  5217.8    0.05       0
Bank Sta=4987.2,4991.6
Exp/Cntr=0.3,0.1

Type RM Length L Ch R = 1,2768,249,249,249
BEGIN DESCRIPTION:
Mapping XS 6414ba89
END DESCRIPTION:
XS GIS Cut Line= 4
      1973780.89     13526908.07      1973929.32     13526392.48
      1973973.59     13525863.83      1973669.48     13525809.25
#Sta/Elev= 30
  4254.8  548.49  4358.4  548.74  4514.5  547.82  4570.2  547.54  4648.7  546.37
  4715.9  544.60  4721.3  544.03  4726.5  544.18  4755.0  542.80  4876.9  538.67
  4877.2  538.17  4881.0  538.17  4881.3  538.67  4916.8  539.16  4959.4  539.07
  4979.5  539.76  5053.4  540.76  5077.1  541.23  5150.1  542.74  5213.4  542.99
  5240.4  543.64  5250.4  541.95  5260.4  541.35  5277.2  543.25  5318.7  542.04
  5361.0  541.92  5442.3  542.70  5457.1  542.37  5510.8  543.48  5630.8  544.91
#Mann=7,-1,0
  4254.8    0.05       0  4514.5     0.1       0  4876.9    0.07       0
  4881.3     0.1       0  5053.4    0.05       0  5077.1     0.1       0
  5213.4    0.05       0
Bank Sta=4876.9,4881.3
Exp/Cntr=0.3,0.1

Type RM Length L Ch R = 1,2519,134,134,134
BEGIN DESCRIPTION:
Mapping XS a3ace69e
END DESCRIPTION:
XS GIS Cut Line= 2
      1974170.95     13527080.57      1974202.15     13525988.42
#Sta/Elev= 30
  4103.6  547.93  4119.2  548.10  4159.2  547.50  4209.2  545.85  4249.2  545.32
  4269.2  544.70  4329.3  544.01  4379.3  542.88  4399.3  543.00  4417.4  542.53
  4422.4  542.82  4479.3  541.63  4569.4  541.68  4689.4  540.17  4779.4  539.66
  4789.5  540.05  4809.5  540.00  4889.5  538.88  4909.5  538.95  4919.5  539.35
  4977.3  538.25  4977.6  537.75  4981.4  537.75  4981.8  538.25  4989.5  538.78
  5029.6  538.47  5069.6  539.24  5106.7  539.48  5149.6  540.46  5196.2  540.45
#Mann=4,-1,0
  4103.6    0.05       0  4977.3    0.04       0  4981.8    0.05       0
  5106.7    0.08       0
Bank Sta=4977.3,4981.8
Exp/Cntr=0.3,0.1

Type RM Length L Ch R = 1,2385,374,374,374
BEGIN DESCRIPTION:
Mapping XS ec77a5b4
END DESCRIPTION:
XS GIS Cut Line= 2
      1974302.89     13527077.13      1974328.17     13525929.20
#Sta/Elev= 30
  4127.2  548.90  4235.8  546.45  4299.4  545.33  4319.4  545.54  4334.3  545.03
  4379.4  543.43  4452.2  542.60  4489.4  541.52  4599.4  539.59  4639.5  539.18
  4659.5  539.72  4679.5  539.21  4689.5  539.79  4699.5  539.03  4729.5  538.63
  4789.5  538.88  4859.5  537.74  4909.5  537.73  4929.5  537.26  4949.5  537.60
  4979.5  537.30  4987.3  536.83  4987.6  536.33  4991.4  536.33  4991.8  536.83
  5039.5  538.26  5069.6  538.60  5109.6  540.11  5119.6  540.91  5275.4  542.13
#Mann=5,-1,0
  4127.2    0.08       0  4235.8    0.05       0  4334.3     0.1       0
  4987.3    0.07       0  4991.8     0.1       0
Bank Sta=4987.3,4991.8
Exp/Cntr=0.3,0.1

Type RM Length L Ch R = 1,2011,33,33,33
BEGIN DESCRIPTION:
Mapping XS 8a9225cd
END DESCRIPTION:
XS GIS Cut Line= 6
      1974391.55     13527082.60      1974582.53     13526459.75
      1974730.10     13526438.05      1974771.33     13526375.12
      1974649.80     13526279.63      1974619.42     13525964.94
#Sta/Elev= 30
  3956.5  550.90  4174.0  547.46  4566.8  537.99  4626.0  536.34  4683.9  535.18
  4722.4  532.81  4750.1  534.32  4755.3  532.42  4758.7  534.01  4771.5  532.04
  4778.5  533.53  4785.6  531.97  4790.8  532.96  4799.7  532.07  4802.9  533.65
  4807.7  533.65  4819.2  531.93  4823.6  531.70  4824.0  531.20  4828.7  531.70
  4909.4  531.95  4930.8  532.33  4938.0  534.75  4955.8  535.73  4988.9  536.25
  5009.1  533.63  5039.0  537.40  5290.2  541.69  5309.8  543.22  5320.4  542.46
#Mann=10,-1,0
  3956.5    0.05       0  4174.0     0.1       0  4566.8    0.12       0
  4626.0     0.1       0  4790.8    0.12       0  4819.2     0.1       0
  4823.6    0.07       0  4828.7     0.1       0  4909.4    0.07       0
  4955.8     0.1       0
Bank Sta=4823.6,4828.7
Exp/Cntr=0.3,0.1

Type RM Length L Ch R = 1,1978,55,55,55
BEGIN DESCRIPTION:
Mapping XS 96903b77
END DESCRIPTION:
XS GIS Cut Line= 6
      1974418.89     13527096.51      1974606.40     13526506.19
      1974797.37     13526405.50      1974811.26     13526339.53
      1974679.32     13526283.97      1974675.85     13525989.46
#Sta/Elev= 30
  3914.7  551.46  4146.3  547.84  4516.3  538.15  4594.0  541.05  4605.4  541.06
  4609.4  538.57  4647.2  538.79  4683.9  541.13  4705.3  536.37  4721.6  539.66
  4727.1  537.14  4745.0  540.46  4780.7  539.23  4834.7  538.33  4843.0  539.89
  4864.2  537.94  4870.6  539.77  4882.6  538.32  4886.0  540.11  4919.8  536.60
  4925.0  539.27  4938.6  538.79  4961.7  539.12  4980.2  537.59  4997.0  532.84
  4997.4  532.34  5002.1  532.84  5009.5  535.17  5069.5  538.35  5275.1  541.17
#Mann=8,-1,0
  3914.7    0.05       0  4146.3     0.1       0  4683.9    0.12       0
  4780.7     0.1       0  4938.6    0.07       0  4961.7     0.1       0
  4997.0    0.07       0  5002.1     0.1       0
Bank Sta=4997,5002.1
Exp/Cntr=0.3,0.1

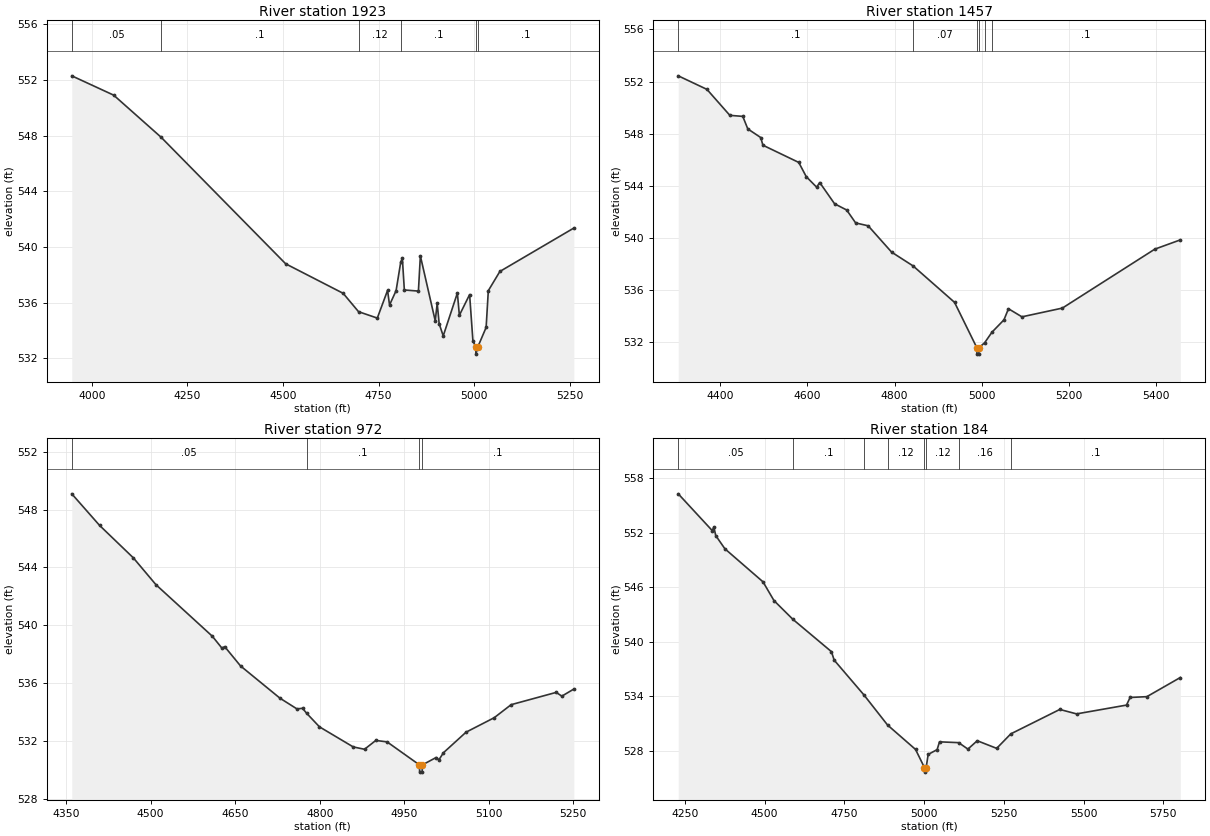
Type RM Length L Ch R = 1,1923,466,466,466
BEGIN DESCRIPTION:
Mapping XS 49564264
END DESCRIPTION:
XS GIS Cut Line= 6
      1974450.16     13527099.91      1974623.76     13526533.97
      1974783.48     13526485.36      1974825.15     13526370.78
      1974734.87     13526273.55      1974703.62     13526002.74
#Sta/Elev= 30
  3947.7  552.31  4057.4  550.92  4181.2  547.90  4507.2  538.80  4657.5  536.68
  4697.7  535.36  4746.8  534.90  4773.6  536.89  4778.8  535.84  4795.9  536.87
  4808.1  538.93  4812.3  539.19  4817.5  536.92  4854.3  536.84  4859.4  539.37
  4898.3  534.70  4903.4  535.96  4908.6  534.49  4919.2  533.62  4956.2  536.70
  4961.4  535.10  4988.2  536.59  4996.8  533.28  5004.3  532.81  5004.7  532.31
  5009.4  532.81  5031.4  534.23  5037.1  536.87  5067.3  538.25  5260.8  541.37
#Mann=6,-1,0
  3947.7    0.05       0  4181.2     0.1       0  4697.7    0.12       0
  4808.1     0.1       0  5004.3    0.07       0  5009.4     0.1       0
Bank Sta=5004.3,5009.4
Exp/Cntr=0.3,0.1

Type RM Length L Ch R = 1,1457,485,485,485
BEGIN DESCRIPTION:
Mapping XS 1025404c
END DESCRIPTION:
XS GIS Cut Line= 2
      1974872.89     13527199.77      1975154.13     13526082.63
#Sta/Elev= 30
  4303.7  552.44  4369.6  551.40  4422.1  549.41  4451.8  549.33  4463.3  548.37
  4492.9  547.71  4498.0  547.12  4580.2  545.80  4597.4  544.71  4621.3  543.90
  4628.3  544.26  4662.4  542.63  4690.2  542.15  4710.8  541.16  4739.5  540.94
  4793.3  538.92  4842.7  537.86  4937.7  535.07  4988.7  531.60  4989.1  531.10
  4993.4  531.10  4993.8  531.60  5006.7  531.97  5023.5  532.78  5051.1  533.73
  5061.4  534.58  5092.3  533.96  5185.1  534.63  5397.2  539.15  5455.7  539.86
#Mann=6,-1,0
  4303.7     0.1       0  4842.7    0.07       0  4988.7    0.07       0
  4993.8    0.07       0  5006.7    0.12       0  5023.5     0.1       0
Bank Sta=4988.7,4993.8
Exp/Cntr=0.3,0.1

Type RM Length L Ch R = 1,972,788,788,788
BEGIN DESCRIPTION:
Mapping XS d9f35794
END DESCRIPTION:
XS GIS Cut Line= 2
      1975477.06     13527314.32      1975453.62     13526423.72
#Sta/Elev= 30
  4360.0  549.09  4409.3  546.91  4469.4  544.66  4509.4  542.81  4609.4  539.25
  4626.4  538.43  4631.4  538.53  4659.4  537.20  4729.4  534.97  4759.5  534.23
  4769.5  534.27  4776.7  533.93  4799.5  532.99  4859.5  531.60  4879.5  531.44
  4899.5  532.05  4919.5  531.95  4976.9  530.36  4977.3  529.86  4981.7  529.86
  4982.1  530.36  5006.5  530.87  5011.5  530.71  5019.5  531.20  5059.6  532.62
  5109.6  533.62  5139.6  534.52  5219.6  535.37  5229.6  535.11  5250.9  535.60
#Mann=4,-1,0
  4360.0    0.05       0  4776.7     0.1       0  4976.9    0.07       0
  4982.1     0.1       0
Bank Sta=4976.9,4982.1
Exp/Cntr=0.3,0.1

Type RM Length L Ch R = 1,184,0,0,0
BEGIN DESCRIPTION:
UNT 023 in BCW 3.0
END DESCRIPTION:
XS GIS Cut Line= 4
      1976050.84     13527358.42      1976198.41     13526815.87
      1976033.48     13526477.33      1975409.20     13526360.28
#Sta/Elev= 30
  4229.1  556.30  4335.6  552.25  4340.8  552.64  4346.6  551.70  4375.4  550.24
  4494.8  546.60  4529.3  544.53  4588.4  542.47  4709.4  538.90  4717.9  537.97
  4810.6  534.16  4885.4  530.81  4973.1  528.12  5001.0  526.12  5001.4  525.62
  5006.3  526.12  5012.6  527.57  5040.7  528.10  5048.2  528.96  5108.1  528.87
  5137.2  528.16  5166.5  529.08  5227.4  528.24  5271.8  529.84  5425.3  532.53
  5477.9  532.04  5634.4  533.01  5645.7  533.85  5698.3  533.94  5803.1  536.05
#Mann=8,-1,0
  4229.1    0.05       0  4588.4     0.1       0  4810.6    0.07       0
  4885.4    0.12       0  5001.0    0.07       0  5006.3    0.12       0
  5108.1    0.16       0  5271.8     0.1       0
Bank Sta=5001,5006.3
Exp/Cntr=0.3,0.1

Chan Stop Cuts=-1