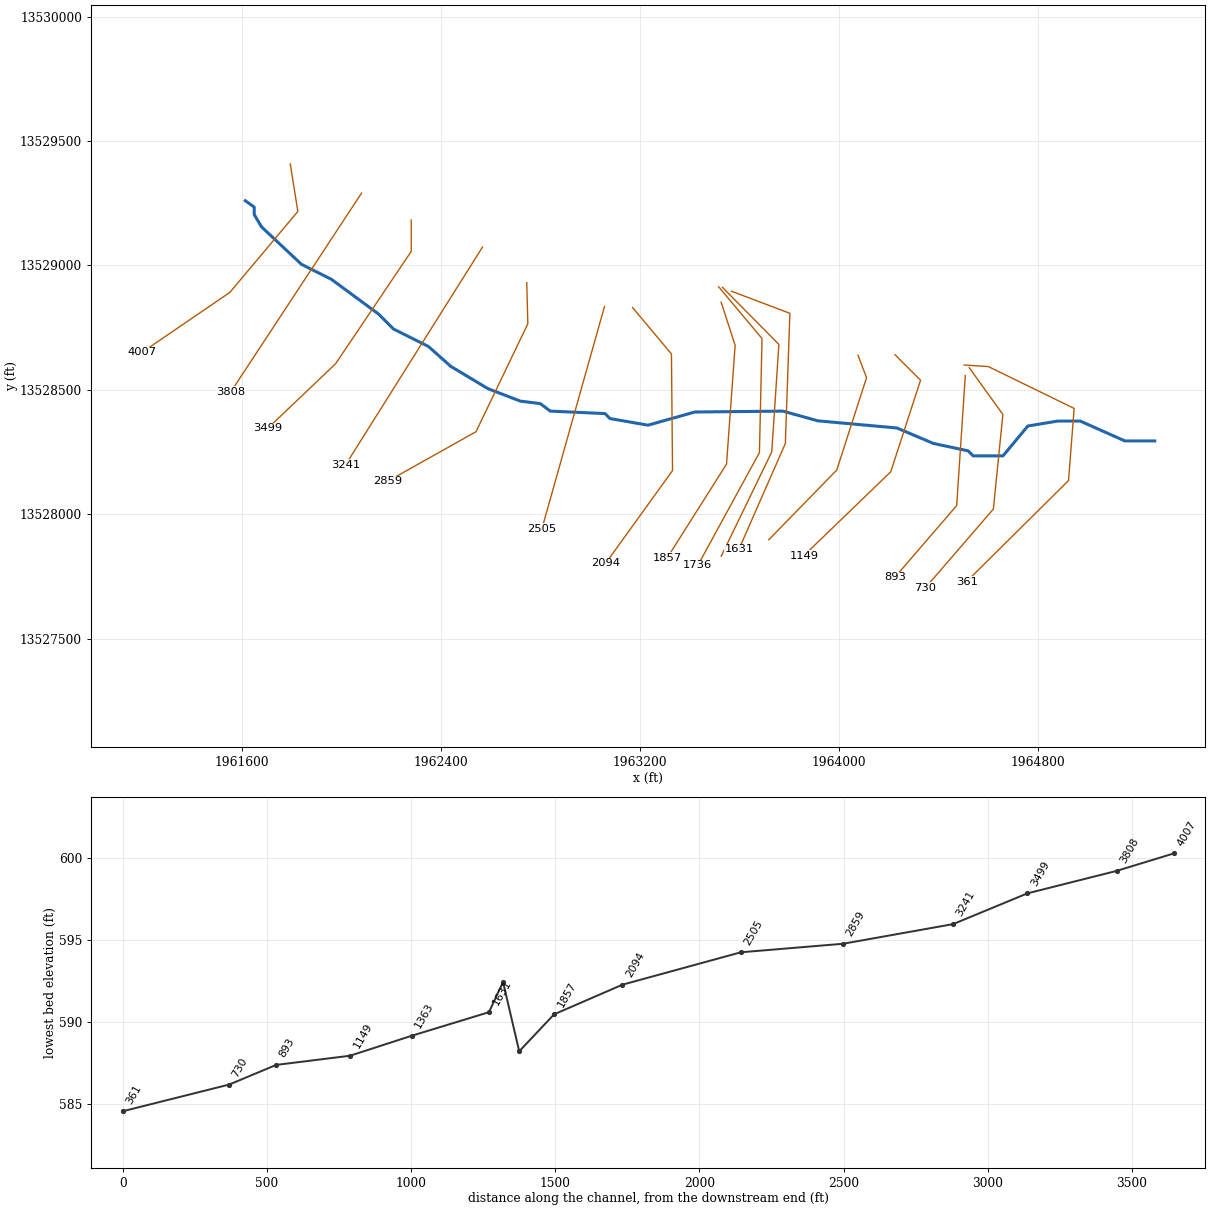
--- UNT 024 in BCW.prj (project) ---

Proj Title=UNT 024 in BCW Base Level Engineering
Current Plan=p01
Default Exp/Contr=0.3,0.1
English Units
Geom File=g01
Flow File=f01
Plan File=p01
BEGIN DESCRIPTION:
UNT 024 in BCW
END DESCRIPTION:

--- UNT 024 in BCW.p01 (plan) ---

Plan Title=Multiple Run
Short Identifier=Multiple
Geom File=g01
Flow File=f01
Subcritical Flow
K Sum by GR= 0
Std Step Tol= 0.01
Critical Tol= 0.01
Num of Std Step Trials= 20
Max Error Tol= 0.3
Flow Tol Ratio= 0.001
Split Flow NTrial= 30
Split Flow Tol= 0.02
Split Flow Ratio= 0.02
Log Output Level= 0
Friction Slope Method= 1
Unsteady Friction Slope Method= 2
Unsteady Bridges Friction Slope Method= 1
Parabolic Critical Depth
Global Vel Dist=  1 , 1 , 1
Global Log Level= 0
CheckData=True
Encroach Param= -1, 0, 0, 0
BEGIN DESCRIPTION:
Multiple Run
END DESCRIPTION:

--- UNT 024 in BCW.f01 (steady flow) ---

Flow Title=Multiple
Number of Profiles=7
Profile Names=10-year,25-year,50-year,1pct_min,100-year,1pct_plu,500-year
River Rch & RM= UNT 024 in BCW,Reach-1,4007
     192     268     332     205     410     818     637
Boundary for River Rch & Prof#=UNT 024 in BCW,Reach-1,1
Up Type=0
Dn Type=3
Dn Slope=0.005
Boundary for River Rch & Prof#=UNT 024 in BCW,Reach-1,2
Up Type=0
Dn Type=3
Dn Slope=0.005
Boundary for River Rch & Prof#=UNT 024 in BCW,Reach-1,3
Up Type=0
Dn Type=3
Dn Slope=0.005
Boundary for River Rch & Prof#=UNT 024 in BCW,Reach-1,4
Up Type=0
Dn Type=3
Dn Slope=0.005
Boundary for River Rch & Prof#=UNT 024 in BCW,Reach-1,5
Up Type=0
Dn Type=3
Dn Slope=0.005
Boundary for River Rch & Prof#=UNT 024 in BCW,Reach-1,6
Up Type=0
Dn Type=3
Dn Slope=0.005
Boundary for River Rch & Prof#=UNT 024 in BCW,Reach-1,7
Up Type=0
Dn Type=3
Dn Slope=0.005

--- UNT 024 in BCW.g01 (geometry) ---

Geom Title=Existing Conditions

River Reach=UNT 024 in BCW,Reach-1
Reach XY= 30
      1961615.07     13529260.26      1961650.80     13529234.54
      1961650.80     13529204.54      1961680.80     13529154.54
      1961840.80     13529004.54      1961960.80     13528944.54
      1962150.80     13528804.54      1962210.80     13528744.54
      1962350.80     13528674.54      1962440.80     13528594.54
      1962590.80     13528504.54      1962720.80     13528454.54
      1962800.80     13528444.54      1962840.80     13528414.54
      1963060.80     13528404.54      1963080.80     13528384.54
      1963233.71     13528357.92      1963422.08     13528410.87
      1963776.24     13528414.34      1963916.87     13528375.28
      1964234.58     13528346.63      1964380.80     13528284.54
      1964520.80     13528254.54      1964540.80     13528234.54
      1964660.80     13528234.54      1964760.80     13528354.54
      1964880.80     13528374.54      1964970.80     13528374.54
      1965150.80     13528294.54      1965270.80     13528294.54

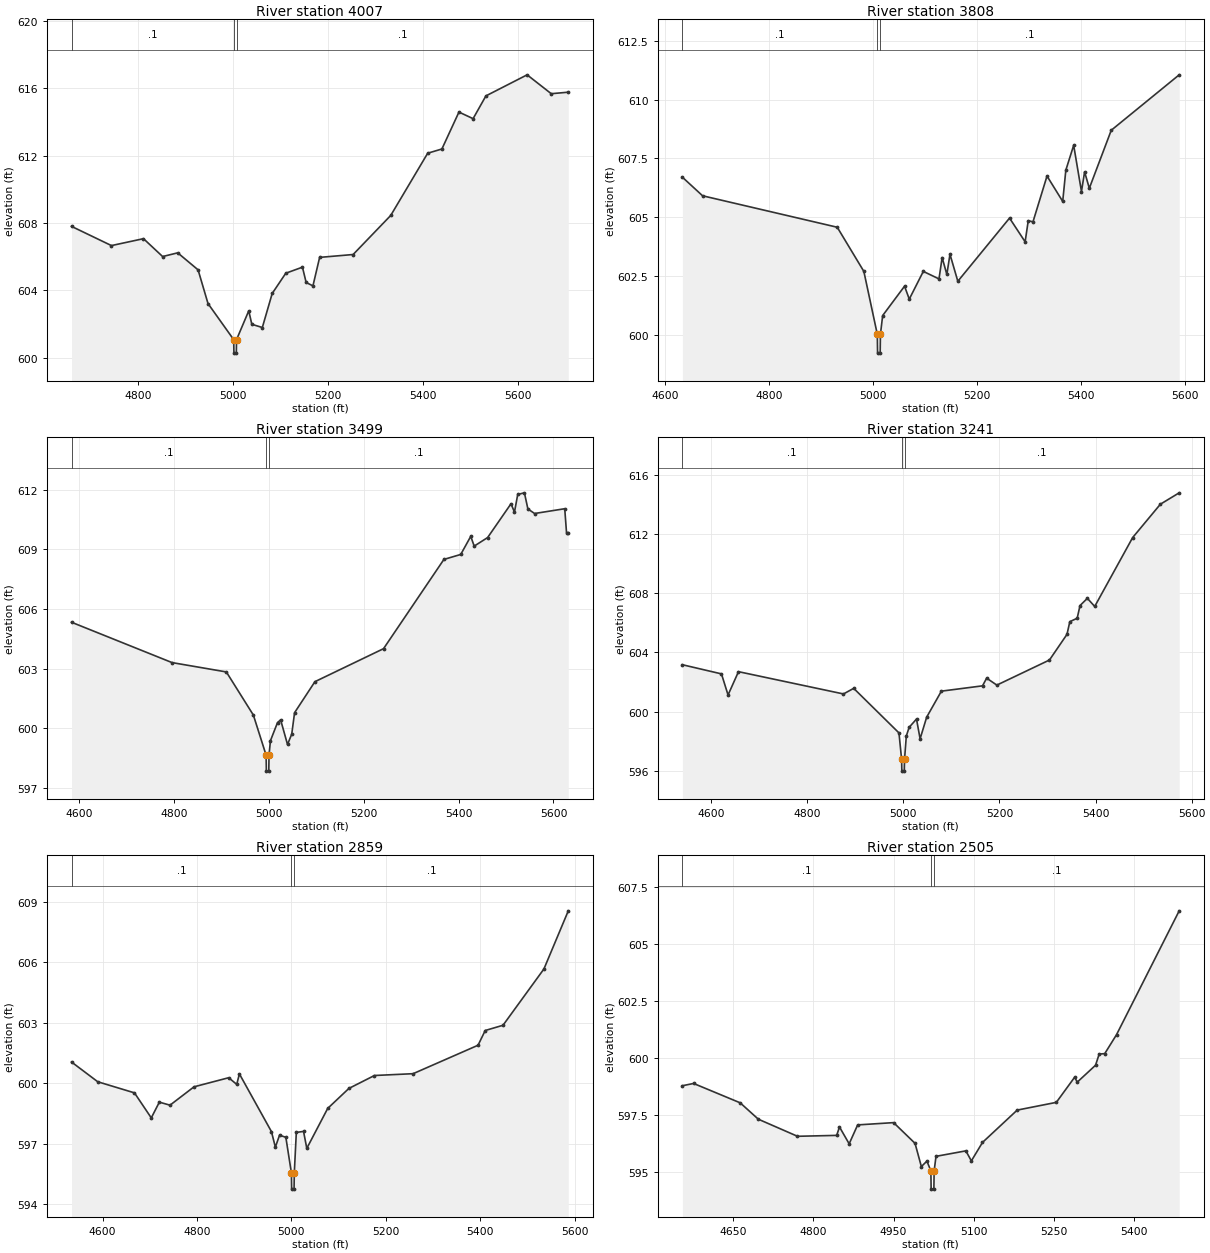
Type RM Length L Ch R = 1,4007,199,199,199
BEGIN DESCRIPTION:
UNT 024 in BCW 1.0
END DESCRIPTION:
XS GIS Cut Line= 4
      1961795.90     13529408.02      1961826.28     13529217.06
      1961552.84     13528891.54      1961199.56     13528650.27
#Sta/Elev= 30
  4659.0  607.80  4743.1  606.66  4810.6  607.07  4850.9  606.01  4882.7  606.23
  4925.6  605.22  4946.5  603.22  5000.6  601.08  5001.1  600.28  5006.1  600.28
  5006.6  601.08  5032.3  602.79  5038.8  601.99  5060.9  601.80  5081.7  603.82
  5110.3  605.02  5145.4  605.38  5153.2  604.47  5167.5  604.27  5181.6  605.96
  5252.1  606.13  5331.4  608.45  5409.2  612.14  5439.1  612.39  5475.0  614.58
  5504.8  614.19  5531.8  615.54  5618.6  616.79  5669.4  615.67  5705.3  615.76
#Mann=3,-1,0
  4659.0     0.1       0  5000.6    0.07       0  5006.6     0.1       0
Bank Sta=5000.6,5006.6
Exp/Cntr=0.3,0.1

Type RM Length L Ch R = 1,3808,309,309,309
BEGIN DESCRIPTION:
UNT 024 in BCW 2.0
END DESCRIPTION:
XS GIS Cut Line= 2
      1962082.36     13529290.85      1961557.19     13528492.25
#Sta/Elev= 30
  4633.3  606.70  4672.1  605.91  4931.2  604.57  4982.4  602.69  5008.3  600.01
  5008.8  599.21  5013.8  599.21  5014.3  600.01  5018.6  600.81  5060.7  602.06
  5069.8  601.51  5096.8  602.69  5127.0  602.37  5133.0  603.28  5142.1  602.56
  5148.1  603.42  5163.2  602.27  5262.7  604.96  5292.7  603.95  5298.7  604.85
  5307.8  604.80  5334.8  606.75  5365.0  605.67  5371.0  607.00  5386.1  608.06
  5401.1  606.09  5407.1  606.93  5416.2  606.23  5458.4  608.70  5589.1  611.06
#Mann=3,-1,0
  4633.3     0.1       0  5008.3    0.07       0  5014.3     0.1       0
Bank Sta=5008.3,5014.3
Exp/Cntr=0.3,0.1

Type RM Length L Ch R = 1,3499,258,258,258
BEGIN DESCRIPTION:
UNT 024 in BCW 3.0
END DESCRIPTION:
XS GIS Cut Line= 4
      1962282.01     13529182.31      1962282.01     13529056.47
      1961978.19     13528605.08      1961704.72     13528344.64
#Sta/Elev= 30
  4583.7  605.33  4795.7  603.30  4910.2  602.83  4967.2  600.66  4994.1  598.64
  4994.6  597.84  4999.7  597.84  5000.2  598.64  5003.2  599.37  5018.1  600.28
  5024.7  600.42  5039.2  599.18  5048.1  599.70  5054.1  600.78  5097.0  602.34
  5241.7  604.00  5369.0  608.49  5404.5  608.74  5425.6  609.65  5432.9  609.16
  5461.2  609.59  5510.5  611.29  5517.8  610.87  5524.7  611.76  5538.8  611.84
  5546.1  611.03  5560.2  610.80  5623.8  611.04  5627.6  609.83  5631.3  609.83
#Mann=3,-1,0
  4583.7     0.1       0  4994.1    0.07       0  5000.2     0.1       0
Bank Sta=4994.1,5000.2
Exp/Cntr=0.3,0.1

Type RM Length L Ch R = 1,3241,382,382,382
BEGIN DESCRIPTION:
UNT 024 in BCW 4.0
END DESCRIPTION:
XS GIS Cut Line= 2
      1962568.45     13529073.80      1962018.15     13528198.51
#Sta/Elev= 30
  4540.2  603.17  4621.5  602.55  4635.2  601.12  4656.9  602.70  4875.4  601.19
  4896.7  601.57  4990.9  598.55  4996.4  596.76  4996.9  595.96  5002.0  595.96
  5002.5  596.76  5006.2  598.34  5012.1  598.93  5027.4  599.49  5034.9  598.15
  5048.6  599.62  5079.2  601.38  5164.8  601.74  5173.4  602.26  5194.6  601.79
  5304.1  603.49  5340.6  605.23  5346.5  606.09  5361.8  606.32  5367.7  607.18
  5383.0  607.67  5398.3  607.12  5477.3  611.79  5535.0  614.05  5574.1  614.82
#Mann=3,-1,0
  4540.2     0.1       0  4996.4    0.07       0  5002.5     0.1       0
Bank Sta=4996.4,5002.5
Exp/Cntr=0.3,0.1

Type RM Length L Ch R = 1,2859,354,354,354
BEGIN DESCRIPTION:
UNT 024 in BCW 5.0
END DESCRIPTION:
XS GIS Cut Line= 4
      1962746.42     13528930.56      1962750.76     13528765.67
      1962542.42     13528331.64      1962188.24     13528132.95
#Sta/Elev= 30
  4534.3  601.06  4589.9  600.08  4667.7  599.53  4703.3  598.29  4720.4  599.07
  4743.0  598.92  4793.9  599.83  4867.3  600.28  4884.4  599.95  4890.0  600.47
  4957.9  597.61  4966.2  596.84  4975.0  597.43  4988.4  597.33  5000.2  595.56
  5000.7  594.76  5005.8  594.76  5006.3  595.56  5010.6  597.57  5025.9  597.62
  5032.8  596.78  5077.1  598.76  5122.0  599.75  5176.1  600.39  5258.0  600.48
  5395.6  601.89  5410.8  602.62  5448.5  602.88  5535.2  605.67  5586.8  608.55
#Mann=3,-1,0
  4534.3     0.1       0  5000.2    0.07       0  5006.3     0.1       0
Bank Sta=5000.2,5006.3
Exp/Cntr=0.3,0.1

Type RM Length L Ch R = 1,2505,411,411,411
BEGIN DESCRIPTION:
UNT 024 in BCW 6.0
END DESCRIPTION:
XS GIS Cut Line= 2
      1963058.92     13528835.12      1962807.17     13527940.98
#Sta/Elev= 30
  4555.2  598.78  4576.1  598.88  4663.2  598.03  4697.2  597.31  4770.4  596.56
  4843.7  596.60  4848.9  596.97  4867.0  596.23  4882.9  597.06  4950.1  597.16
  4990.2  596.25  5002.0  595.23  5012.4  595.47  5019.8  595.04  5020.3  594.24
  5025.4  594.24  5025.9  595.04  5029.4  595.68  5085.2  595.92  5095.5  595.48
  5116.3  596.29  5181.2  597.71  5254.4  598.05  5288.5  599.15  5293.6  598.94
  5327.7  599.68  5334.5  600.17  5344.9  600.19  5366.9  601.02  5484.1  606.46
#Mann=3,-1,0
  4555.2     0.1       0  5019.8    0.07       0  5025.9     0.1       0
Bank Sta=5019.8,5025.9
Exp/Cntr=0.3,0.1

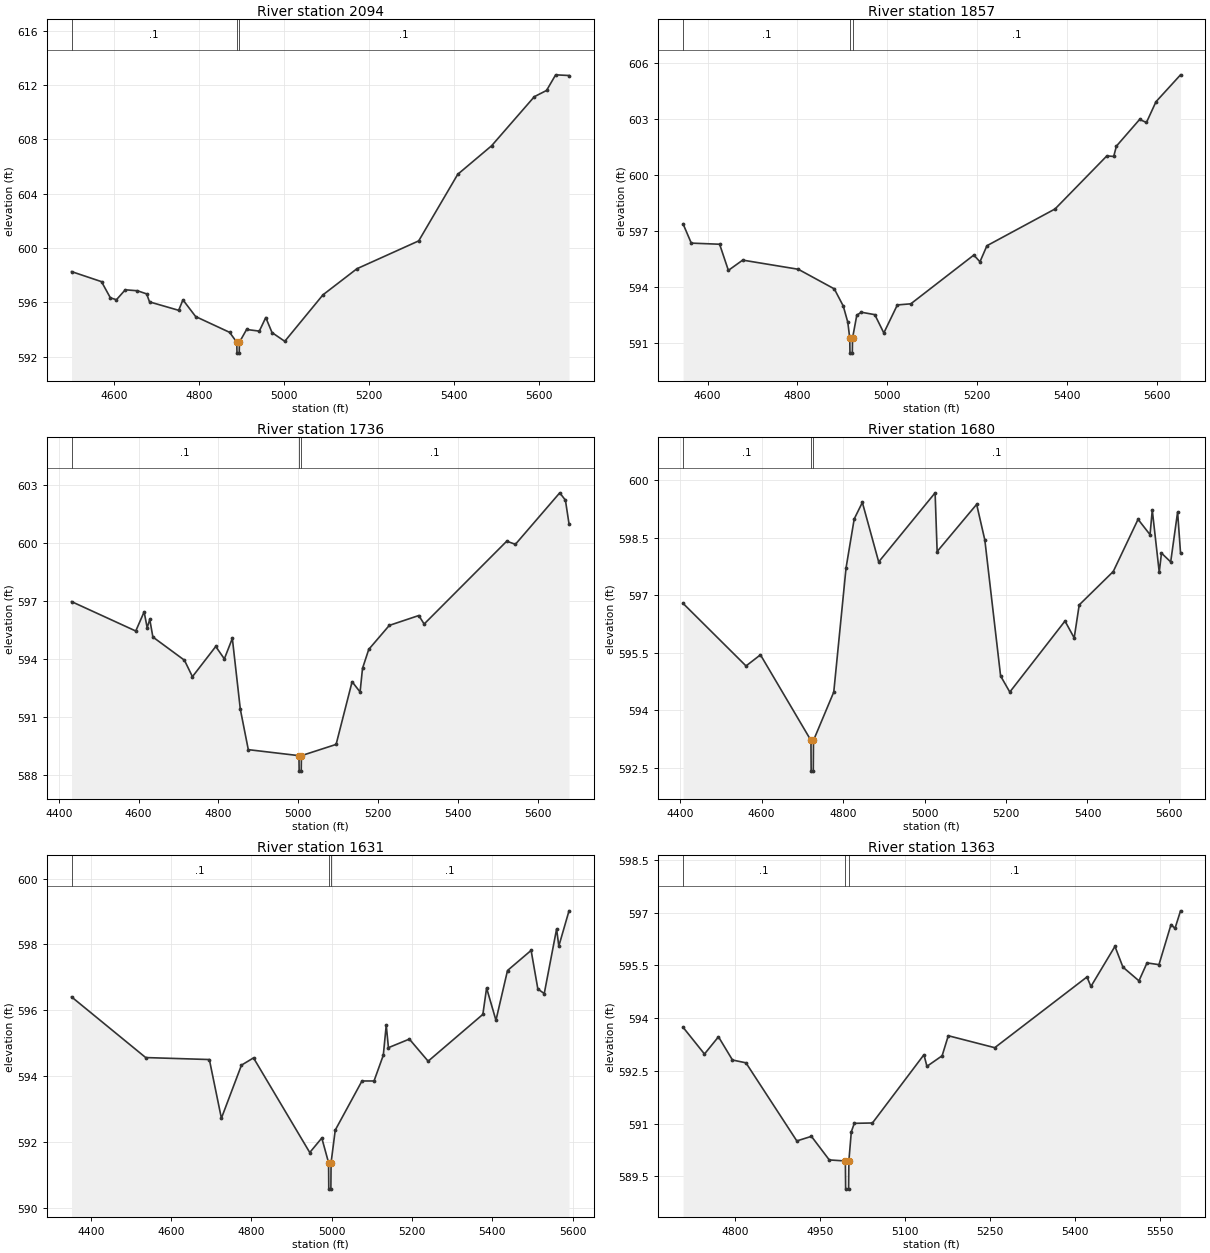
Type RM Length L Ch R = 1,2094,237,237,237
BEGIN DESCRIPTION:
UNT 024 in BCW 7.0
END DESCRIPTION:
XS GIS Cut Line= 4
      1963171.79     13528830.74      1963328.01     13528644.14
      1963332.35     13528175.39      1963063.25     13527802.11
#Sta/Elev= 30
  4499.5  598.26  4570.1  597.52  4591.0  596.33  4605.3  596.19  4626.1  596.92
  4654.7  596.85  4676.5  596.62  4683.3  596.03  4752.0  595.41  4762.0  596.18
  4792.0  594.95  4872.0  593.79  4888.9  593.06  4889.4  592.26  4894.6  592.26
  4895.1  593.06  4912.0  594.00  4942.0  593.88  4957.2  594.88  4972.0  593.77
  5002.0  593.13  5092.0  596.55  5172.0  598.47  5317.6  600.52  5409.6  605.42
  5489.4  607.52  5590.0  611.13  5618.9  611.59  5640.3  612.74  5671.8  612.69
#Mann=3,-1,0
  4499.5     0.1       0  4888.9    0.07       0  4895.1     0.1       0
Bank Sta=4888.9,4895.1
Exp/Cntr=0.3,0.1

Type RM Length L Ch R = 1,1857,121,121,121
BEGIN DESCRIPTION:
UNT 024 in BCW 8.0
END DESCRIPTION:
XS GIS Cut Line= 4
      1963527.68     13528852.44      1963584.09     13528678.86
      1963549.37     13528201.43      1963310.67     13527823.86
#Sta/Elev= 30
  4545.3  597.37  4563.6  596.34  4626.7  596.28  4646.2  594.88  4678.1  595.43
  4801.9  594.94  4882.1  593.89  4902.1  592.97  4912.2  592.10  4916.5  591.25
  4917.0  590.45  4922.2  590.45  4922.7  591.25  4932.2  592.48  4942.2  592.64
  4972.3  592.51  4992.4  591.53  5022.5  593.03  5052.5  593.09  5192.8  595.70
  5206.5  595.34  5222.0  596.20  5373.8  598.17  5489.1  601.01  5504.4  600.98
  5510.3  601.53  5562.0  602.96  5577.3  602.80  5598.5  603.91  5653.2  605.35
#Mann=3,-1,0
  4545.3     0.1       0  4916.5    0.07       0  4922.7     0.1       0
Bank Sta=4916.5,4922.7
Exp/Cntr=0.3,0.1

Type RM Length L Ch R = 1,1736,56,56,56
BEGIN DESCRIPTION:
Mapping XS 68a5b5ad
END DESCRIPTION:
XS GIS Cut Line= 4
      1963517.64     13528914.44      1963692.11     13528706.11
      1963681.70     13528247.78      1963434.28     13527794.61
#Sta/Elev= 30
  4431.9  596.95  4592.8  595.43  4613.8  596.42  4621.4  595.60  4627.9  596.03
  4635.7  595.12  4714.8  593.92  4734.8  593.07  4793.2  594.63  4814.8  593.99
  4834.8  595.05  4854.8  591.39  4874.8  589.30  5001.7  588.99  5002.2  588.19
  5007.4  588.19  5007.9  588.99  5094.8  589.57  5134.9  592.81  5154.9  592.28
  5161.0  593.50  5176.6  594.48  5228.1  595.72  5302.0  596.23  5315.4  595.79
  5522.3  600.07  5544.1  599.91  5655.2  602.57  5669.4  602.19  5678.4  600.97
#Mann=3,-1,0
  4431.9     0.1       0  5001.7    0.07       0  5007.9     0.1       0
Bank Sta=5001.7,5007.9
Exp/Cntr=0.3,0.1

Type RM Length L Ch R = 1,1680,49,49,49
BEGIN DESCRIPTION:
Mapping XS e5732172
END DESCRIPTION:
XS GIS Cut Line= 4
      1963533.25     13528911.85      1963759.82     13528682.67
      1963731.18     13528250.38      1963528.05     13527831.10
#Sta/Elev= 30
  4407.1  596.79  4561.7  595.16  4597.1  595.45  4721.1  593.22  4721.6  592.42
  4726.8  592.42  4727.3  593.22  4777.1  594.48  4807.2  597.71  4827.3  598.99
  4847.3  599.42  4887.4  597.87  5025.9  599.67  5030.9  598.14  5127.9  599.37
  5148.0  598.44  5186.7  594.90  5209.3  594.48  5344.8  596.33  5367.4  595.89
  5379.7  596.75  5463.3  597.62  5524.2  598.98  5553.6  598.58  5559.1  599.22
  5576.2  597.60  5581.7  598.10  5604.3  597.87  5621.3  599.17  5628.5  598.10
#Mann=3,-1,0
  4407.1     0.1       0  4721.1    0.07       0  4727.3     0.1       0
Bank Sta=4721.1,4727.3
Exp/Cntr=0.3,0.1

Type RM Length L Ch R = 1,1631,268,268,268
BEGIN DESCRIPTION:
Mapping XS 1cfbb794
END DESCRIPTION:
XS GIS Cut Line= 4
      1963569.72     13528896.21      1963804.09     13528807.67
      1963785.86     13528284.23      1963598.97     13527858.54
#Sta/Elev= 30
  4352.0  596.41  4536.7  594.57  4695.3  594.51  4725.3  592.73  4775.3  594.34
  4805.3  594.56  4945.4  591.69  4975.4  592.13  4992.3  591.38  4992.8  590.58
  4998.0  590.58  4998.5  591.38  5008.9  592.37  5075.5  593.86  5105.5  593.86
  5128.6  594.64  5135.9  595.55  5141.4  594.87  5193.5  595.13  5240.3  594.46
  5376.6  595.88  5385.9  596.68  5409.2  595.70  5438.0  597.21  5496.8  597.82
  5513.6  596.65  5529.5  596.51  5560.3  598.47  5565.8  597.95  5591.2  599.02
#Mann=3,-1,0
  4352.0     0.1       0  4992.3    0.07       0  4998.5     0.1       0
Bank Sta=4992.3,4998.5
Exp/Cntr=0.3,0.1

Type RM Length L Ch R = 1,1363,214,214,214
BEGIN DESCRIPTION:
Mapping XS cdec2549
END DESCRIPTION:
XS GIS Cut Line= 4
      1964077.90     13528638.94      1964112.25     13528548.99
      1963992.46     13528177.46      1963719.07     13527897.16
#Sta/Elev= 30
  4708.0  593.74  4745.8  592.98  4770.5  593.47  4795.2  592.81  4819.0  592.73
  4908.8  590.51  4934.6  590.64  4966.1  589.97  4994.5  589.94  4995.0  589.14
  5000.2  589.14  5000.7  589.94  5005.0  590.77  5010.3  591.01  5042.3  591.02
  5133.2  592.96  5138.5  592.63  5165.3  592.93  5176.2  593.50  5258.2  593.16
  5421.0  595.17  5428.0  594.90  5470.4  596.04  5484.5  595.45  5512.8  595.06
  5527.0  595.57  5548.1  595.52  5569.4  596.66  5576.4  596.55  5586.2  597.05
#Mann=3,-1,0
  4708.0     0.1       0  4994.5    0.07       0  5000.7     0.1       0
Bank Sta=4994.5,5000.7
Exp/Cntr=0.3,0.1

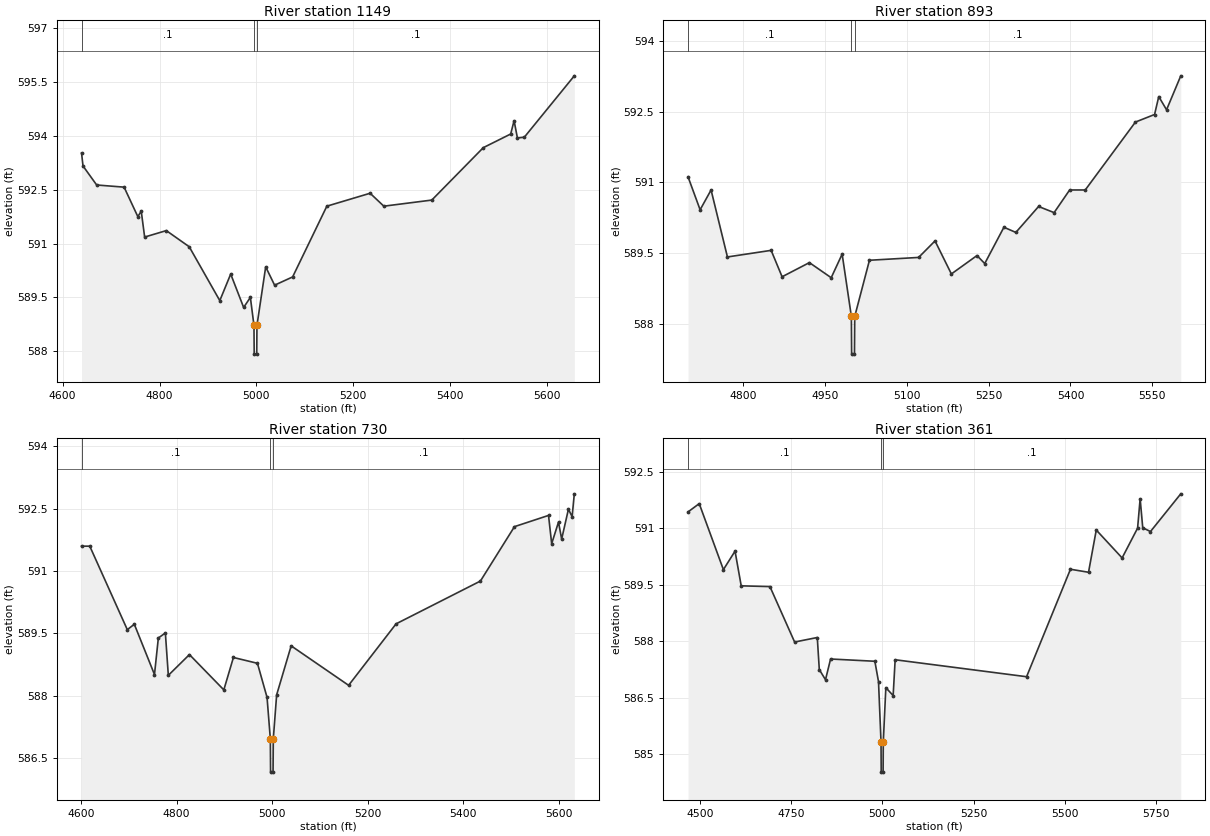
Type RM Length L Ch R = 1,1149,256,256,256
BEGIN DESCRIPTION:
Mapping XS 9b28cd96
END DESCRIPTION:
XS GIS Cut Line= 4
      1964226.83     13528641.01      1964329.27     13528538.57
      1964209.47     13528170.52      1963860.52     13527833.72
#Sta/Elev= 30
  4639.1  593.52  4642.1  593.16  4670.3  592.63  4726.9  592.57  4755.2  591.75
  4762.3  591.90  4769.3  591.18  4814.0  591.36  4861.3  590.91  4924.4  589.41
  4946.9  590.15  4973.6  589.22  4987.5  589.50  4994.9  588.72  4995.4  587.92
  5000.6  587.92  5001.1  588.72  5019.1  590.35  5037.5  589.84  5074.7  590.07
  5145.3  592.04  5234.6  592.40  5262.9  592.04  5361.9  592.21  5468.2  593.67
  5524.7  594.05  5531.7  594.42  5538.6  593.94  5552.8  593.96  5656.0  595.67
#Mann=3,-1,0
  4639.1     0.1       0  4994.9    0.07       0  5001.1     0.1       0
Bank Sta=4994.9,5001.1
Exp/Cntr=0.3,0.1

Type RM Length L Ch R = 1,893,163,163,163
BEGIN DESCRIPTION:
Mapping XS 442ccb39
END DESCRIPTION:
XS GIS Cut Line= 3
      1964509.20     13528557.17      1964474.48     13528034.64
      1964226.20     13527746.42
#Sta/Elev= 30
  4698.3  591.12  4720.5  590.42  4740.6  590.84  4770.6  589.42  4850.8  589.56
  4870.9  589.00  4921.0  589.30  4961.0  588.98  4981.1  589.48  4998.0  588.16
  4998.5  587.36  5003.7  587.36  5004.2  588.16  5031.2  589.35  5121.4  589.41
  5151.5  589.76  5181.5  589.06  5228.5  589.45  5242.7  589.28  5277.9  590.05
  5299.8  589.94  5341.5  590.49  5370.0  590.36  5398.5  590.84  5427.1  590.84
  5519.2  592.28  5554.3  592.44  5562.0  592.82  5576.3  592.54  5602.4  593.26
#Mann=3,-1,0
  4698.3     0.1       0  4998.0    0.07       0  5004.2     0.1       0
Bank Sta=4998,5004.2
Exp/Cntr=0.3,0.1

Type RM Length L Ch R = 1,730,369,369,369
BEGIN DESCRIPTION:
Mapping XS b2d02647
END DESCRIPTION:
XS GIS Cut Line= 4
      1964524.97     13528589.00      1964660.25     13528400.96
      1964622.05     13528020.75      1964348.86     13527704.33
#Sta/Elev= 30
  4601.1  591.60  4618.3  591.60  4696.9  589.59  4711.6  589.72  4753.8  588.51
  4761.9  589.39  4776.6  589.51  4782.8  588.49  4827.0  588.99  4899.0  588.14
  4919.1  588.92  4969.4  588.78  4989.5  587.96  4996.4  586.96  4996.9  586.16
  5002.1  586.16  5002.6  586.96  5009.6  588.02  5040.0  589.20  5160.3  588.25
  5259.7  589.73  5436.3  590.76  5507.6  592.07  5578.9  592.34  5585.5  591.66
  5599.8  592.18  5606.4  591.77  5620.6  592.49  5628.3  592.31  5632.9  592.86
#Mann=3,-1,0
  4601.1     0.1       0  4996.4    0.07       0  5002.6     0.1       0
Bank Sta=4996.4,5002.6
Exp/Cntr=0.3,0.1

Type RM Length L Ch R = 1,361,0,0,0
BEGIN DESCRIPTION:
UNT 024 in BCW 9.0
END DESCRIPTION:
XS GIS Cut Line= 5
      1964504.32     13528599.86      1964602.02     13528593.40
      1964946.71     13528425.26      1964924.14     13528135.33
      1964514.01     13527728.66
#Sta/Elev= 30
  4467.7  591.43  4498.4  591.65  4564.6  589.90  4596.5  590.39  4613.4  589.47
  4692.1  589.45  4759.7  587.98  4821.8  588.10  4827.3  587.25  4844.3  586.98
  4858.2  587.53  4979.5  587.47  4989.5  586.93  4996.4  585.33  4996.9  584.53
  5002.1  584.53  5002.6  585.33  5009.6  586.77  5029.6  586.56  5035.1  587.51
  5395.1  587.06  5515.3  589.91  5564.8  589.83  5586.0  590.95  5656.8  590.21
  5699.2  591.00  5706.2  591.78  5713.3  591.01  5734.5  590.91  5817.5  591.91
#Mann=3,-1,0
  4467.7     0.1       0  4996.4    0.07       0  5002.6     0.1       0
Bank Sta=4996.4,5002.6
Exp/Cntr=0.3,0.1

Chan Stop Cuts=-1