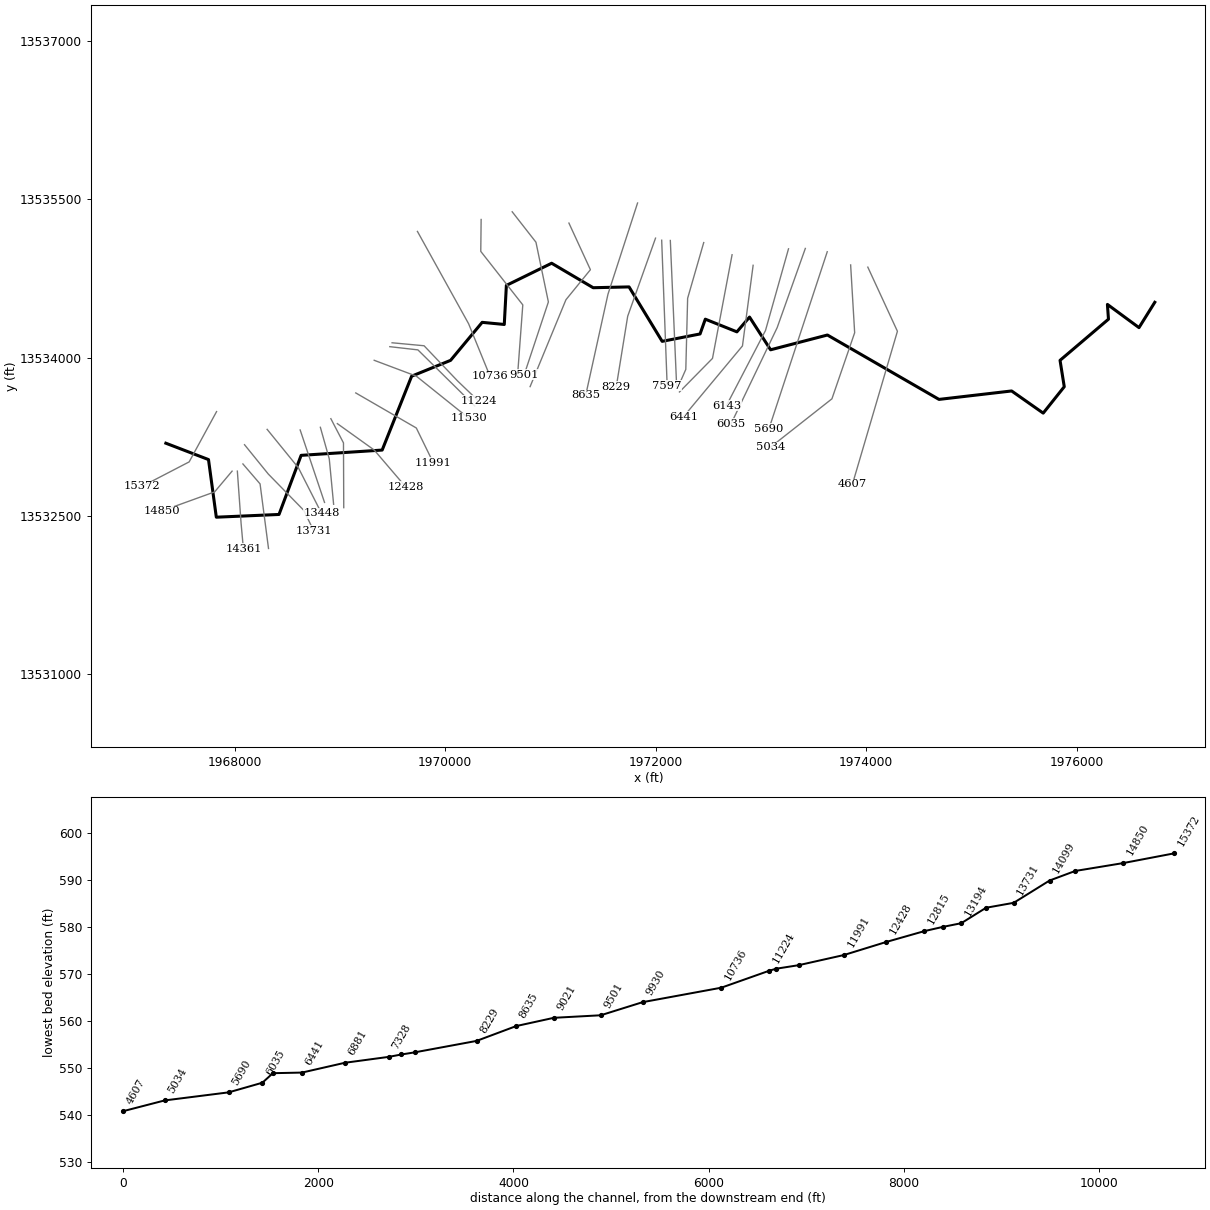
--- UNT 026 in BCW.prj (project) ---

Proj Title=UNT 026 in BCW Base Level Engineering
Current Plan=p01
Default Exp/Contr=0.3,0.1
English Units
Geom File=g01
Flow File=f01
Plan File=p01
BEGIN DESCRIPTION:
UNT 026 in BCW
END DESCRIPTION:

--- UNT 026 in BCW.p01 (plan) ---

Plan Title=Multiple Run
Short Identifier=Multiple
Geom File=g01
Flow File=f01
Subcritical Flow
K Sum by GR= 0
Std Step Tol= 0.01
Critical Tol= 0.01
Num of Std Step Trials= 20
Max Error Tol= 0.3
Flow Tol Ratio= 0.001
Split Flow NTrial= 30
Split Flow Tol= 0.02
Split Flow Ratio= 0.02
Log Output Level= 0
Friction Slope Method= 1
Unsteady Friction Slope Method= 2
Unsteady Bridges Friction Slope Method= 1
Parabolic Critical Depth
Global Vel Dist=  1 , 1 , 1
Global Log Level= 0
CheckData=True
Encroach Param= -1, 0, 0, 0
BEGIN DESCRIPTION:
Multiple Run
END DESCRIPTION:

--- UNT 026 in BCW.f01 (steady flow) ---

Flow Title=Multiple
Number of Profiles=7
Profile Names=10-year,25-year,50-year,1pct_min,100-year,1pct_plu,500-year
River Rch & RM= UNT 026 in BCW,Reach-1,15372
     143     195     237     144     288     574     432
River Rch & RM= UNT 026 in BCW,Reach-1,13194
     161     220     269     164     327     653     494
River Rch & RM= UNT 026 in BCW,Reach-1,10736
     246     343     424     262     522    1041     804
River Rch & RM= UNT 026 in BCW,Reach-1,4078
     283     397     492     304     607    1212     942
Boundary for River Rch & Prof#=UNT 026 in BCW,Reach-1,1
Up Type=0
Dn Type=3
Dn Slope=0.005
Boundary for River Rch & Prof#=UNT 026 in BCW,Reach-1,2
Up Type=0
Dn Type=3
Dn Slope=0.005
Boundary for River Rch & Prof#=UNT 026 in BCW,Reach-1,3
Up Type=0
Dn Type=3
Dn Slope=0.005
Boundary for River Rch & Prof#=UNT 026 in BCW,Reach-1,4
Up Type=0
Dn Type=3
Dn Slope=0.005
Boundary for River Rch & Prof#=UNT 026 in BCW,Reach-1,5
Up Type=0
Dn Type=3
Dn Slope=0.005
Boundary for River Rch & Prof#=UNT 026 in BCW,Reach-1,6
Up Type=0
Dn Type=3
Dn Slope=0.005
Boundary for River Rch & Prof#=UNT 026 in BCW,Reach-1,7
Up Type=0
Dn Type=3
Dn Slope=0.005

--- UNT 026 in BCW.g01 (geometry) ---

Geom Title=Existing Conditions

River Reach=UNT 026 in BCW,Reach-1
Reach XY= 30
      1967345.80     13533189.54      1967750.80     13533034.54
      1967825.12     13532488.62      1968420.80     13532514.54
      1968630.80     13533074.54      1969400.80     13533124.54
      1969680.80     13533824.54      1970050.80     13533974.54
      1970350.80     13534334.54      1970560.80     13534314.54
      1970580.80     13534684.54      1971010.80     13534894.54
      1971405.30     13534662.62      1971746.28     13534670.26
      1972060.80     13534154.54      1972420.80     13534224.54
      1972470.80     13534364.54      1972770.80     13534244.54
      1972890.80     13534384.54      1973090.80     13534074.54
      1973630.80     13534214.54      1974690.80     13533604.54
      1975380.80     13533684.54      1975680.80     13533474.54
      1975880.80     13533724.54      1975840.80     13533974.54
      1976300.80     13534364.54      1976290.80     13534504.54
      1976590.80     13534284.54      1976740.80     13534524.54

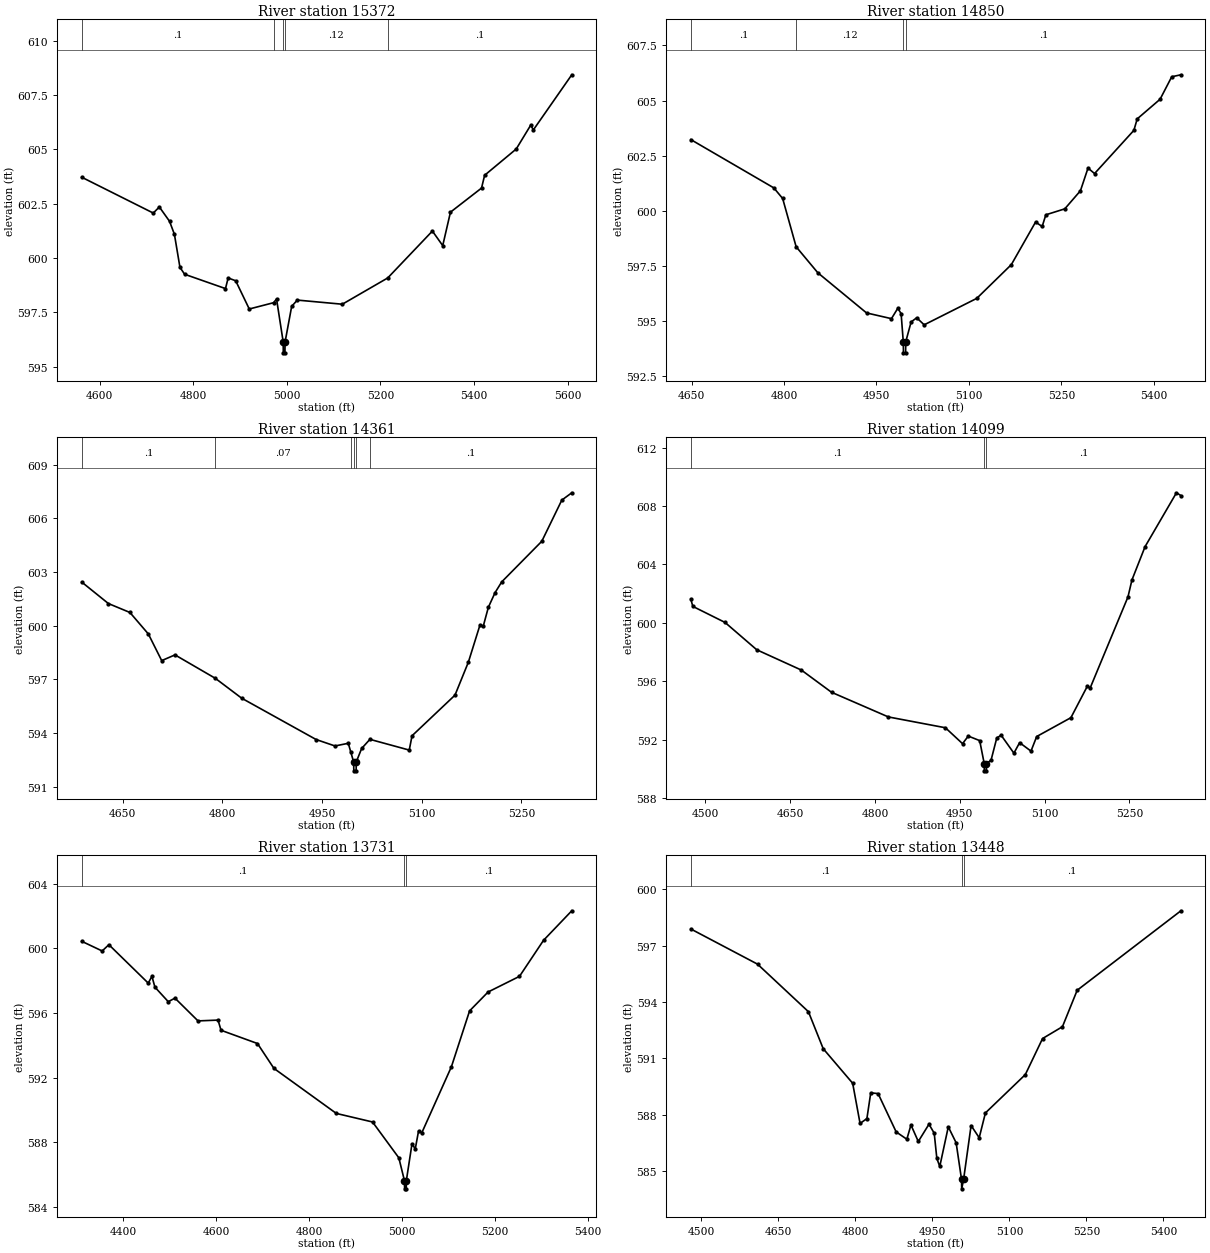
Type RM Length L Ch R = 1,15372,522,522,522
BEGIN DESCRIPTION:
UNT 026 in BCW 20.0
END DESCRIPTION:
XS GIS Cut Line= 3
      1967827.50     13533489.07      1967567.10     13533012.54
      1967119.60     13532780.98
#Sta/Elev= 30
  4561.8  603.72  4714.6  602.07  4727.6  602.35  4749.4  601.69  4759.8  601.09
  4771.6  599.57  4781.6  599.25  4868.9  598.59  4874.6  599.08  4890.7  598.95
  4919.7  597.65  4971.7  597.94  4978.0  598.11  4992.2  596.13  4992.4  595.63
  4995.9  595.63  4996.2  596.13  5010.3  597.77  5022.3  598.06  5118.5  597.87
  5215.5  599.08  5310.9  601.24  5333.0  600.57  5349.5  602.11  5415.9  603.22
  5422.5  603.81  5490.0  605.02  5521.0  606.12  5526.6  605.90  5608.7  608.44
#Mann=5,-1,0
  4561.8     0.1       0  4971.7    0.12       0  4992.2    0.07       0
  4996.2    0.12       0  5215.5     0.1       0
Bank Sta=4992.2,4996.2
Exp/Cntr=0.3,0.1

Type RM Length L Ch R = 1,14850,489,489,489
BEGIN DESCRIPTION:
UNT 026 in BCW 19.0
END DESCRIPTION:
XS GIS Cut Line= 3
      1967974.99     13532924.98      1967808.86     13532728.25
      1967303.21     13532545.96
#Sta/Elev= 30
  4648.9  603.23  4783.5  601.04  4797.8  600.56  4819.7  598.37  4854.9  597.19
  4933.9  595.37  4974.3  595.11  4984.6  595.58  4990.0  595.34  4993.5  594.06
  4993.8  593.56  4997.3  593.56  4997.5  594.06  5006.2  594.96  5015.3  595.15
  5027.4  594.83  5112.7  596.03  5168.8  597.56  5208.1  599.49  5218.8  599.29
  5224.8  599.82  5255.5  600.09  5280.9  600.91  5293.2  601.94  5303.8  601.69
  5367.6  603.65  5373.0  604.17  5410.1  605.06  5429.0  606.08  5443.9  606.17
#Mann=4,-1,0
  4648.9     0.1       0  4819.7    0.12       0  4993.5    0.07       0
  4997.5     0.1       0
Bank Sta=4993.5,4997.5
Exp/Cntr=0.3,0.1

Type RM Length L Ch R = 1,14361,262,262,262
BEGIN DESCRIPTION:
UNT 026 in BCW 18.0
END DESCRIPTION:
XS GIS Cut Line= 3
      1968025.00     13532924.98      1968060.59     13532428.77
      1968082.30     13532190.04
#Sta/Elev= 30
  4588.5  602.44  4628.6  601.24  4661.0  600.74  4688.7  599.54  4708.8  598.05
  4728.8  598.37  4789.5  597.06  4829.1  595.95  4941.1  593.64  4969.5  593.28
  4989.5  593.43  4993.4  592.92  4997.5  592.39  4997.8  591.89  5001.3  591.89
  5001.5  592.39  5009.6  593.14  5022.0  593.65  5081.2  593.05  5085.4  593.85
  5150.0  596.12  5170.1  597.96  5187.5  600.03  5192.5  599.97  5200.2  601.03
  5210.3  601.85  5220.3  602.45  5280.6  604.72  5310.7  607.02  5325.7  607.43
#Mann=6,-1,0
  4588.5     0.1       0  4789.5    0.07       0  4993.4    0.12       0
  4997.5    0.07       0  5001.5    0.12       0  5022.0     0.1       0
Bank Sta=4997.5,5001.5
Exp/Cntr=0.3,0.1

Type RM Length L Ch R = 1,14099,368,368,368
BEGIN DESCRIPTION:
Mapping XS b24fe713
END DESCRIPTION:
XS GIS Cut Line= 3
      1968077.98     13532992.98      1968240.72     13532804.21
      1968321.02     13532192.18
#Sta/Elev= 30
  4474.6  601.60  4478.1  601.12  4535.1  600.02  4591.1  598.15  4670.0  596.76
  4723.3  595.24  4823.9  593.55  4924.7  592.81  4955.0  591.72  4965.1  592.24
  4985.3  591.93  4993.3  590.36  4993.6  589.86  4997.1  589.86  4997.3  590.36
  5005.4  590.59  5015.5  592.11  5023.2  592.30  5045.8  591.07  5055.9  591.79
  5076.0  591.21  5086.1  592.21  5146.6  593.50  5175.7  595.66  5180.7  595.54
  5247.5  601.77  5254.5  602.93  5277.7  605.21  5333.2  608.90  5341.1  608.71
#Mann=3,-1,0
  4474.6     0.1       0  4993.3    0.07       0  4997.3     0.1       0
Bank Sta=4993.3,4997.3
Exp/Cntr=0.3,0.1

Type RM Length L Ch R = 1,13731,283,283,283
BEGIN DESCRIPTION:
Mapping XS 5fa93be9
END DESCRIPTION:
XS GIS Cut Line= 4
      1968093.17     13533175.27      1968318.84     13532897.52
      1968655.21     13532554.64      1968750.17     13532360.41
#Sta/Elev= 30
  4310.9  600.44  4354.9  599.84  4369.3  600.23  4454.0  597.85  4461.9  598.27
  4468.4  597.60  4497.1  596.70  4511.5  596.92  4561.1  595.51  4604.2  595.56
  4610.6  594.93  4689.0  594.11  4724.4  592.57  4858.7  589.78  4936.6  589.25
  4993.2  587.03  5005.3  585.61  5005.6  585.11  5009.1  585.11  5009.3  585.61
  5021.5  587.90  5028.5  587.58  5035.6  588.69  5042.6  588.58  5106.3  592.67
  5145.4  596.13  5185.2  597.30  5252.8  598.27  5304.5  600.50  5365.3  602.33
#Mann=3,-1,0
  4310.9     0.1       0  5005.3    0.07       0  5009.3     0.1       0
Bank Sta=5005.3,5009.3
Exp/Cntr=0.3,0.1

Type RM Length L Ch R = 1,13448,254,254,254
BEGIN DESCRIPTION:
UNT 026 in BCW 17.0
END DESCRIPTION:
XS GIS Cut Line= 3
      1968308.00     13533320.69      1968605.30     13532956.12
      1968825.00     13532525.00
#Sta/Elev= 30
  4479.7  597.89  4609.5  596.02  4708.6  593.49  4737.4  591.52  4794.8  589.68
  4809.2  587.54  4822.5  587.80  4830.0  589.17  4844.3  589.13  4879.5  587.09
  4900.3  586.70  4908.3  587.46  4922.6  586.58  4943.4  587.50  4953.6  587.02
  4958.7  585.68  4964.4  585.25  4981.0  587.36  4996.3  586.51  5006.8  584.56
  5007.1  584.06  5010.8  584.56  5025.4  587.43  5041.2  586.78  5053.3  588.10
  5131.0  590.14  5164.6  592.06  5203.3  592.69  5232.0  594.63  5434.0  598.86
#Mann=3,-1,0
  4479.7     0.1       0  5006.8    0.07       0  5010.8     0.1       0
Bank Sta=5006.8,5010.8
Exp/Cntr=0.3,0.1

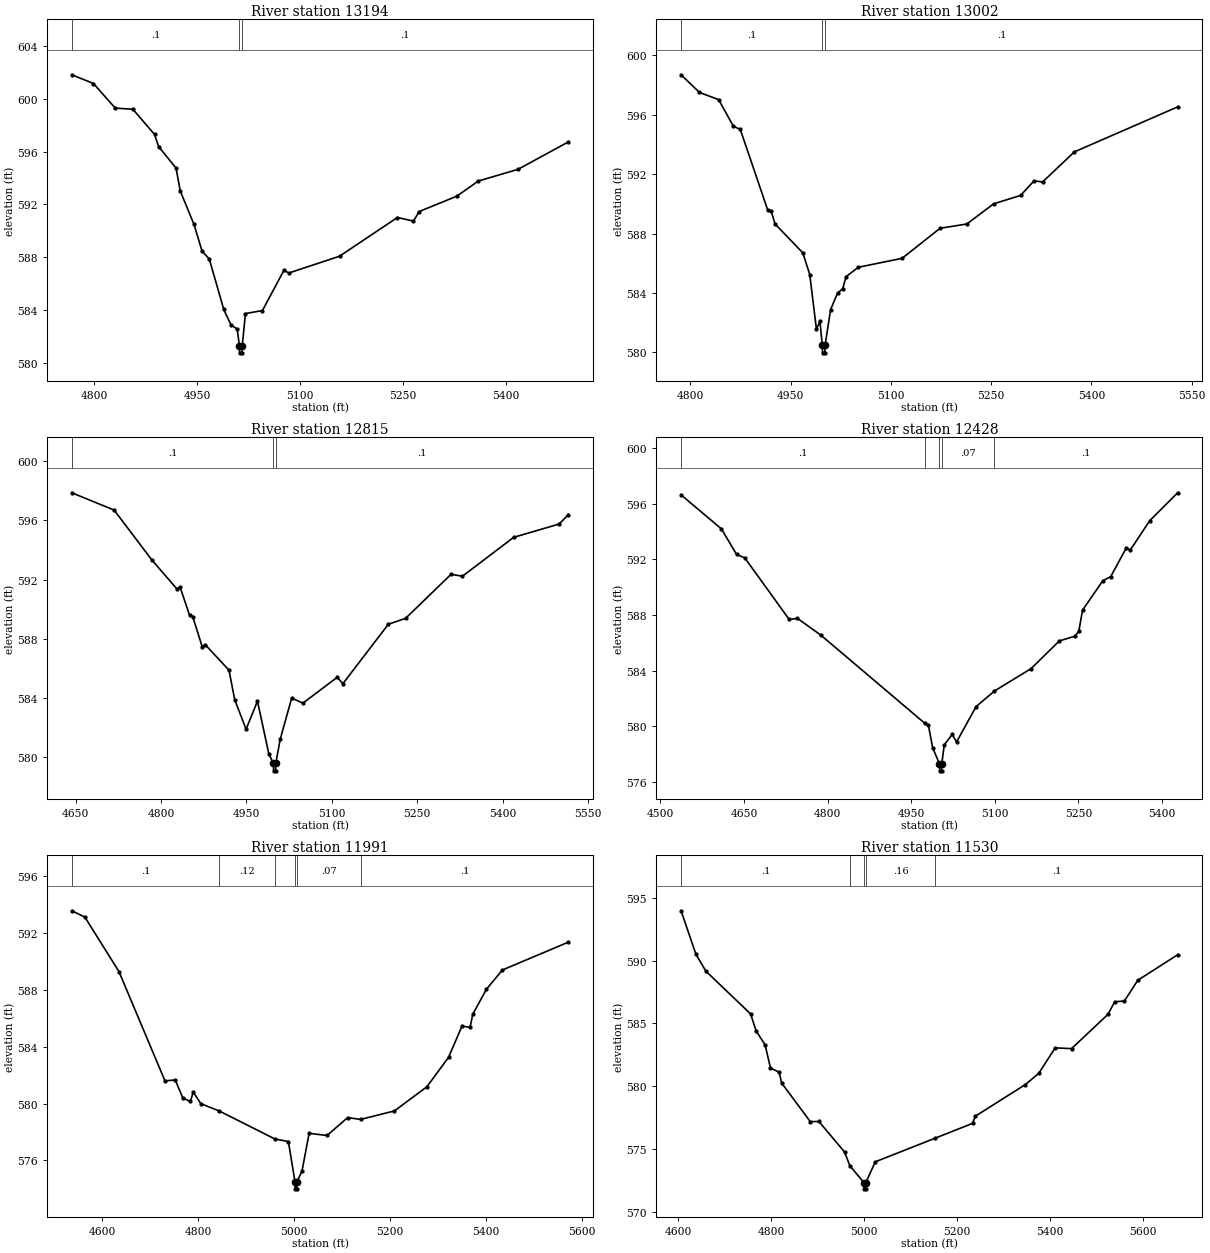
Type RM Length L Ch R = 1,13194,192,192,192
BEGIN DESCRIPTION:
Mapping XS 7bb1ce13
END DESCRIPTION:
XS GIS Cut Line= 2
      1968621.73     13533314.95      1968853.08     13532628.70
#Sta/Elev= 30
  4767.4  601.81  4799.0  601.15  4830.7  599.29  4856.5  599.20  4888.0  597.30
  4894.0  596.38  4919.4  594.75  4925.6  593.01  4945.6  590.49  4957.3  588.47
  4967.9  587.87  4989.0  584.05  4999.5  582.89  5008.6  582.57  5011.9  581.27
  5012.1  580.77  5015.6  580.77  5015.9  581.27  5020.6  583.74  5045.4  583.97
  5076.8  587.02  5083.9  586.81  5157.8  588.08  5242.2  591.01  5265.7  590.74
  5273.9  591.46  5328.7  592.62  5360.2  593.77  5417.9  594.65  5491.6  596.73
#Mann=3,-1,0
  4767.4     0.1       0  5011.9    0.07       0  5015.9     0.1       0
Bank Sta=5011.9,5015.9
Exp/Cntr=0.3,0.1

Type RM Length L Ch R = 1,13002,187,187,187
BEGIN DESCRIPTION:
UNT 026 in BCW 16.0
END DESCRIPTION:
XS GIS Cut Line= 3
      1968813.62     13533340.28      1968898.27     13533040.75
      1968939.50     13532611.08
#Sta/Elev= 30
  4786.2  598.68  4813.7  597.49  4842.4  597.01  4864.4  595.22  4874.8  595.00
  4915.6  589.61  4920.8  589.53  4926.8  588.64  4968.3  586.70  4978.7  585.24
  4988.7  581.56  4993.9  582.10  4997.5  580.47  4997.8  579.97  5001.3  579.97
  5001.6  580.47  5009.9  582.88  5020.3  583.99  5027.9  584.28  5033.1  585.10
  5051.5  585.73  5116.9  586.33  5173.6  588.35  5213.7  588.64  5253.9  590.00
  5294.1  590.56  5314.2  591.54  5327.1  591.47  5374.5  593.49  5529.1  596.52
#Mann=3,-1,0
  4786.2     0.1       0  4997.5    0.07       0  5001.6     0.1       0
Bank Sta=4997.5,5001.6
Exp/Cntr=0.3,0.1

Type RM Length L Ch R = 1,12815,387,387,387
BEGIN DESCRIPTION:
Mapping XS 97ecda11
END DESCRIPTION:
XS GIS Cut Line= 3
      1968913.40     13533421.71      1969033.19     13533192.53
      1969035.79     13532578.94
#Sta/Elev= 30
  4643.4  597.87  4717.7  596.70  4784.0  593.33  4828.1  591.37  4833.8  591.47
  4850.2  589.60  4855.8  589.50  4872.3  587.48  4877.9  587.60  4919.5  585.88
  4929.5  583.89  4949.5  581.89  4969.5  583.79  4989.5  580.22  4997.5  579.58
  4997.8  579.08  5001.3  579.08  5001.6  579.58  5009.5  581.22  5029.5  583.99
  5049.5  583.66  5109.5  585.40  5119.5  584.97  5199.5  588.99  5229.5  589.38
  5309.5  592.36  5329.5  592.23  5419.5  594.86  5499.5  595.76  5515.6  596.40
#Mann=3,-1,0
  4643.4     0.1       0  4997.5    0.07       0  5001.6     0.1       0
Bank Sta=4997.5,5001.6
Exp/Cntr=0.3,0.1

Type RM Length L Ch R = 1,12428,437,437,437
BEGIN DESCRIPTION:
UNT 026 in BCW 15.0
END DESCRIPTION:
XS GIS Cut Line= 3
      1968975.02     13533374.99      1969325.00     13533125.00
      1969625.02     13532774.98
#Sta/Elev= 30
  4537.1  596.63  4609.6  594.18  4636.6  592.35  4651.4  592.10  4731.2  587.67
  4746.0  587.75  4787.8  586.55  4974.4  580.21  4980.9  580.07  4988.6  578.45
  5000.8  577.29  5001.1  576.79  5004.7  576.79  5004.9  577.29  5009.4  578.66
  5023.7  579.41  5031.4  578.86  5066.5  581.41  5099.5  582.53  5165.3  584.14
  5215.8  586.13  5243.8  586.47  5250.9  586.84  5257.5  588.34  5293.7  590.45
  5308.0  590.75  5336.0  592.81  5343.1  592.66  5378.2  594.78  5428.2  596.78
#Mann=5,-1,0
  4537.1     0.1       0  4974.4    0.07       0  5000.8    0.07       0
  5004.9    0.07       0  5099.5     0.1       0
Bank Sta=5000.8,5004.9
Exp/Cntr=0.3,0.1

Type RM Length L Ch R = 1,11991,461,461,461
BEGIN DESCRIPTION:
UNT 026 in BCW 14.0
END DESCRIPTION:
XS GIS Cut Line= 3
      1969150.00     13533665.75      1969725.09     13533333.72
      1969887.84     13533001.72
#Sta/Elev= 30
  4537.2  593.58  4564.5  593.13  4635.3  589.30  4731.1  581.60  4752.6  581.66
  4768.4  580.38  4784.2  580.15  4790.0  580.82  4805.7  579.99  4843.9  579.48
  4959.6  577.51  4988.1  577.32  5001.8  574.49  5002.1  573.99  5005.7  573.99
  5006.0  574.49  5016.4  575.24  5031.2  577.90  5068.5  577.75  5111.6  579.01
  5138.4  578.88  5208.9  579.48  5276.4  581.18  5321.4  583.25  5349.5  585.45
  5366.4  585.37  5371.9  586.29  5400.3  588.05  5433.7  589.41  5571.0  591.37
#Mann=6,-1,0
  4537.2     0.1       0  4843.9    0.12       0  4959.6    0.07       0
  5001.8    0.07       0  5006.0    0.07       0  5138.4     0.1       0
Bank Sta=5001.8,5006
Exp/Cntr=0.3,0.1

Type RM Length L Ch R = 1,11530,235,235,235
BEGIN DESCRIPTION:
UNT 026 in BCW 13.0
END DESCRIPTION:
XS GIS Cut Line= 3
      1969325.03     13533974.99      1969725.00     13533825.00
      1970225.01     13533424.99
#Sta/Elev= 30
  4606.8  593.97  4638.8  590.50  4660.2  589.16  4756.3  585.76  4767.9  584.43
  4787.4  583.30  4799.0  581.46  4817.7  581.12  4823.0  580.26  4884.5  577.19
  4903.1  577.20  4958.3  574.77  4969.7  573.67  4999.8  572.34  5000.1  571.84
  5003.8  571.84  5004.1  572.34  5024.2  573.99  5152.9  575.87  5233.3  577.05
  5239.7  577.63  5346.9  580.14  5375.7  581.03  5411.0  583.06  5446.2  583.00
  5524.6  585.73  5539.0  586.73  5559.8  586.79  5588.6  588.44  5674.3  590.47
#Mann=5,-1,0
  4606.8     0.1       0  4969.7    0.16       0  4999.8    0.07       0
  5004.1    0.16       0  5152.9     0.1       0
Bank Sta=4999.8,5004.1
Exp/Cntr=0.3,0.1

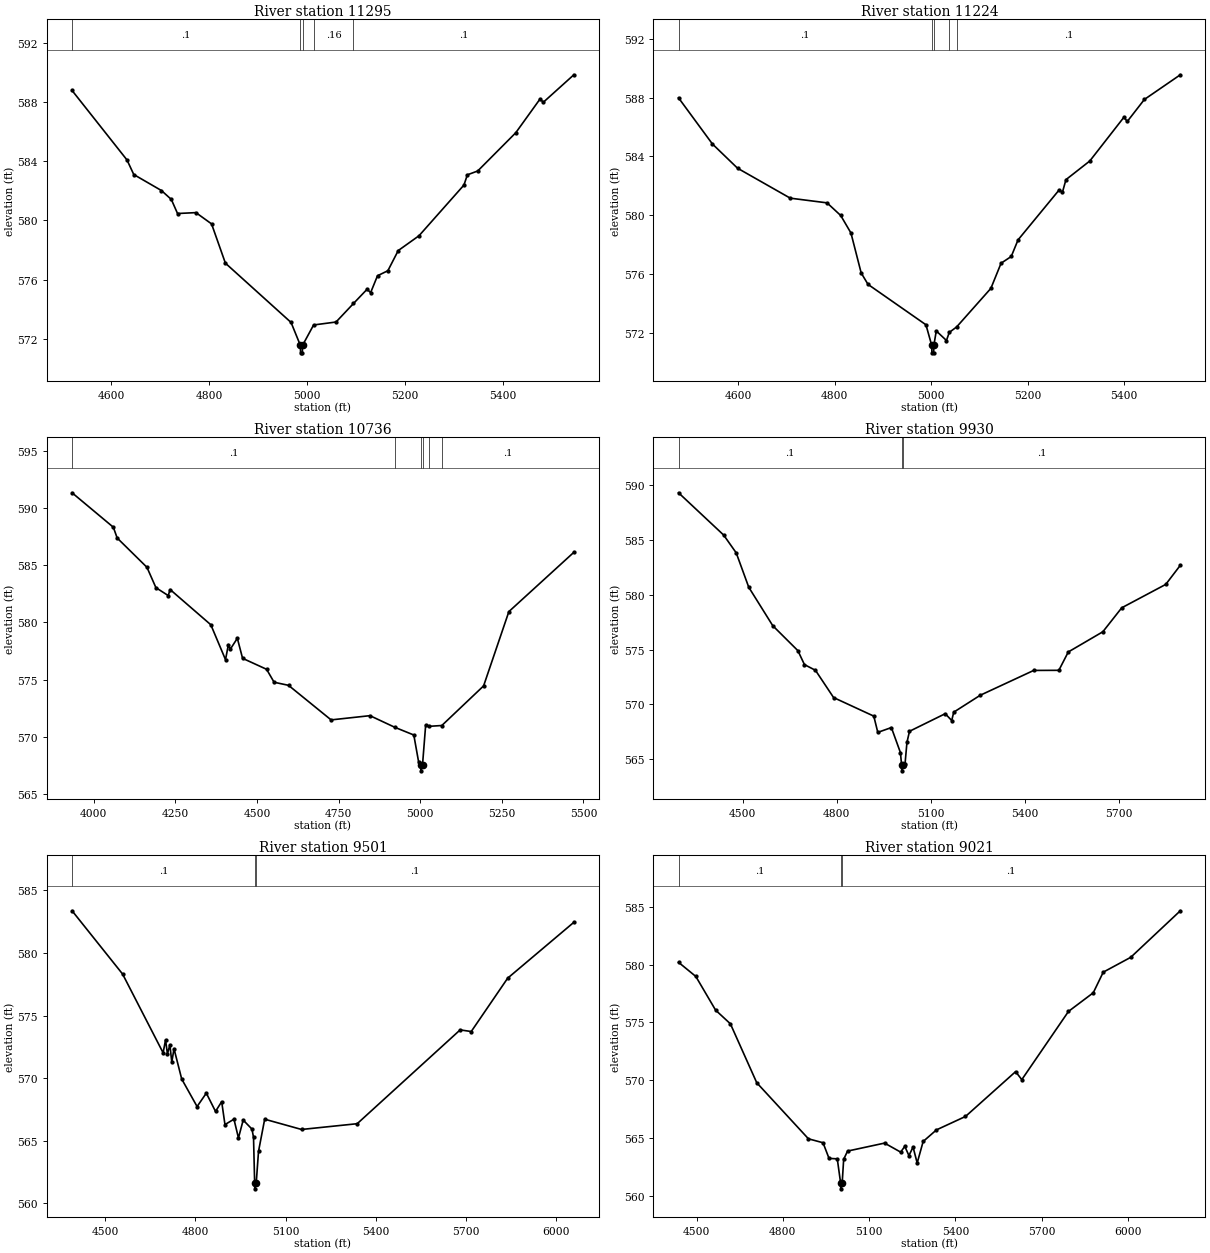
Type RM Length L Ch R = 1,11295,71,71,71
BEGIN DESCRIPTION:
Mapping XS f51e6cfb
END DESCRIPTION:
XS GIS Cut Line= 3
      1969473.34     13534104.12      1969740.28     13534073.74
      1970280.33     13533542.36
#Sta/Elev= 30
  4519.4  588.77  4631.8  584.08  4645.6  583.10  4702.2  582.02  4722.4  581.42
  4735.1  580.47  4772.7  580.53  4804.7  579.77  4833.0  577.12  4967.3  573.12
  4986.4  571.57  4986.7  571.07  4990.4  571.07  4990.7  571.57  5013.4  572.95
  5059.3  573.15  5095.0  574.40  5122.8  575.36  5130.0  575.13  5144.1  576.27
  5165.3  576.61  5186.5  577.97  5229.0  578.97  5320.9  582.39  5327.9  583.08
  5349.1  583.34  5426.9  585.92  5476.4  588.19  5483.4  587.98  5545.7  589.83
#Mann=5,-1,0
  4519.4     0.1       0  4986.4    0.07       0  4990.7     0.1       0
  5013.4    0.16       0  5095.0     0.1       0
Bank Sta=4986.4,4990.7
Exp/Cntr=0.3,0.1

Type RM Length L Ch R = 1,11224,488,488,488
BEGIN DESCRIPTION:
UNT 026 in BCW 12.0
END DESCRIPTION:
XS GIS Cut Line= 4
      1969495.07     13534141.01      1969798.88     13534112.80
      1970117.89     13533778.60      1970315.27     13533589.89
#Sta/Elev= 30
  4476.1  587.99  4546.3  584.85  4598.4  583.20  4707.7  581.16  4784.0  580.84
  4812.3  579.98  4833.5  578.79  4854.7  576.07  4868.9  575.29  4989.0  572.54
  5001.0  571.13  5001.3  570.63  5005.0  570.63  5005.3  571.13  5010.4  572.12
  5031.5  571.47  5037.3  572.02  5052.5  572.39  5123.6  575.02  5144.7  576.73
  5165.8  577.19  5179.9  578.32  5265.1  581.72  5272.0  581.57  5279.2  582.42
  5328.6  583.69  5399.4  586.67  5406.3  586.38  5441.8  587.88  5516.3  589.56
#Mann=5,-1,0
  4476.1     0.1       0  5001.0    0.07       0  5005.3     0.1       0
  5037.3    0.16       0  5052.5     0.1       0
Bank Sta=5001,5005.3
Exp/Cntr=0.3,0.1

Type RM Length L Ch R = 1,10736,806,806,806
BEGIN DESCRIPTION:
UNT 026 in BCW 11.0
END DESCRIPTION:
XS GIS Cut Line= 3
      1969735.95     13535195.68      1970222.05     13534321.13
      1970425.00     13533825.00
#Sta/Elev= 30
  3934.0  591.33  4060.4  588.32  4072.1  587.38  4163.3  584.82  4190.8  583.04
  4228.5  582.35  4234.2  582.88  4358.9  579.80  4403.9  576.75  4412.7  578.07
  4418.4  577.66  4440.1  578.62  4456.1  576.87  4529.7  575.91  4552.6  574.78
  4596.8  574.51  4727.2  571.49  4846.2  571.86  4922.6  570.84  4980.5  570.17
  4995.2  567.82  5001.9  567.54  5002.3  567.04  5007.1  567.54  5016.8  571.04
  5028.3  570.93  5066.3  571.00  5194.2  574.46  5271.6  580.95  5470.6  586.13
#Mann=6,-1,0
  3934.0     0.1       0  4922.6    0.12       0  5001.9    0.07       0
  5007.1    0.12       0  5028.3    0.07       0  5066.3     0.1       0
Bank Sta=5001.9,5007.1
Exp/Cntr=0.3,0.1

Type RM Length L Ch R = 1,9930,429,429,429
BEGIN DESCRIPTION:
Mapping XS 3635828c
END DESCRIPTION:
XS GIS Cut Line= 4
      1970340.98     13535308.99      1970337.50     13535006.90
      1970736.81     13534499.95      1970688.30     13533848.59
#Sta/Elev= 30
  4295.1  589.27  4439.1  585.42  4479.1  583.80  4519.1  580.67  4595.7  577.17
  4675.8  574.90  4696.7  573.63  4731.9  573.11  4789.7  570.63  4917.9  568.94
  4930.7  567.46  4974.0  567.90  5002.9  565.62  5006.7  564.46  5007.1  563.96
  5012.0  564.46  5017.4  564.54  5023.7  566.55  5031.8  567.56  5145.7  569.16
  5166.5  568.54  5172.9  569.30  5257.5  570.84  5428.0  573.10  5508.2  573.11
  5538.3  574.78  5648.6  576.62  5708.8  578.80  5849.2  580.93  5895.7  582.67
#Mann=3,-1,0
  4295.1     0.1       0  5006.7    0.07       0  5012.0     0.1       0
Bank Sta=5006.7,5012
Exp/Cntr=0.3,0.1

Type RM Length L Ch R = 1,9501,480,480,480
BEGIN DESCRIPTION:
Mapping XS 6bc04cbc
END DESCRIPTION:
XS GIS Cut Line= 4
      1970636.09     13535381.93      1970861.81     13535093.70
      1970979.87     13534527.73      1970750.71     13533840.26
#Sta/Elev= 30
  4389.6  583.37  4557.6  578.32  4692.4  572.03  4700.5  573.06  4706.8  571.94
  4714.9  572.67  4721.3  571.28  4728.6  572.36  4754.2  569.94  4805.4  567.74
  4836.1  568.81  4866.7  567.35  4887.2  568.13  4898.1  566.30  4928.0  566.73
  4943.0  565.23  4958.7  566.66  4987.9  565.94  4993.1  565.28  4996.8  561.67
  4997.3  561.17  5002.2  561.67  5009.7  564.16  5030.2  566.73  5152.8  565.91
  5337.9  566.37  5680.3  573.86  5717.2  573.73  5838.4  577.99  6058.5  582.45
#Mann=3,-1,0
  4389.6     0.1       0  4996.8    0.07       0  5002.2     0.1       0
Bank Sta=4996.8,5002.2
Exp/Cntr=0.3,0.1

Type RM Length L Ch R = 1,9021,386,386,386
BEGIN DESCRIPTION:
UNT 026 in BCW 10.0
END DESCRIPTION:
XS GIS Cut Line= 4
      1971175.00     13535275.00      1971379.17     13534833.29
      1971146.53     13534548.56      1970806.25     13533725.64
#Sta/Elev= 30
  4437.2  580.19  4497.3  578.97  4566.1  576.06  4617.5  574.88  4709.2  569.79
  4888.9  564.95  4939.6  564.61  4960.5  563.26  4989.2  563.22  5000.8  561.13
  5001.3  560.63  5006.2  561.13  5011.4  563.18  5024.9  563.89  5153.6  564.58
  5209.6  563.80  5223.9  564.30  5238.3  563.50  5252.7  564.24  5267.0  562.86
  5287.8  564.72  5334.0  565.72  5435.0  566.88  5609.2  570.75  5630.8  570.06
  5793.1  575.95  5879.3  577.56  5914.0  579.34  6009.5  580.62  6182.0  584.64
#Mann=3,-1,0
  4437.2     0.1       0  5000.8    0.07       0  5006.2     0.1       0
Bank Sta=5000.8,5006.2
Exp/Cntr=0.3,0.1

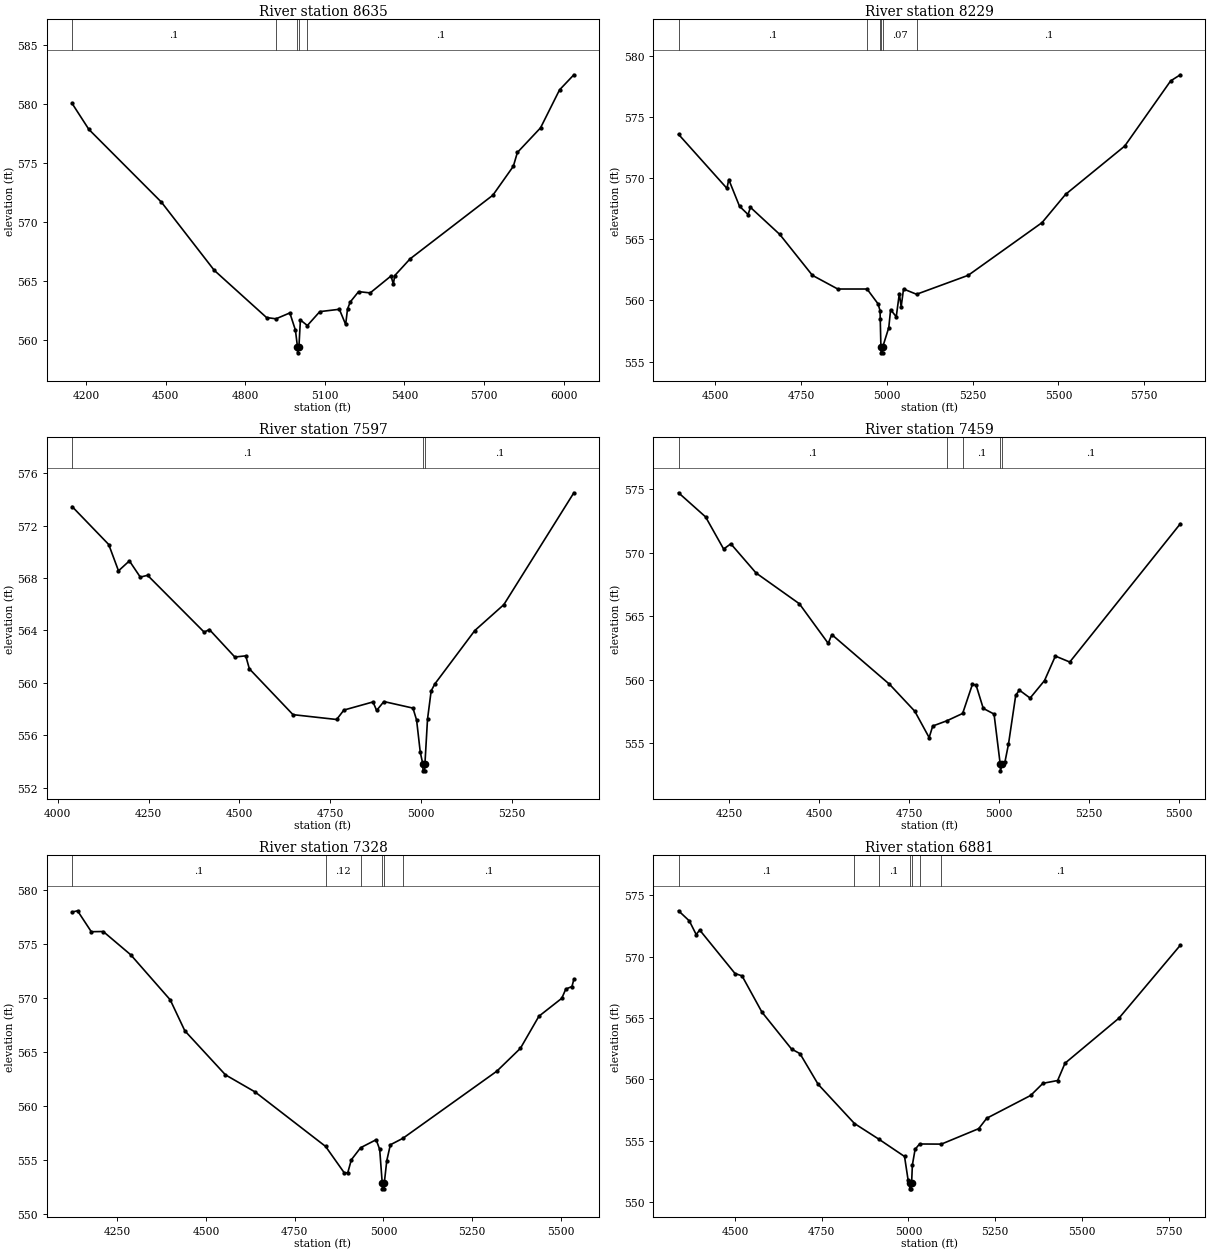
Type RM Length L Ch R = 1,8635,406,406,406
BEGIN DESCRIPTION:
UNT 026 in BCW 9.0
END DESCRIPTION:
XS GIS Cut Line= 3
      1971827.08     13535465.22      1971545.84     13534600.65
      1971334.04     13533642.34
#Sta/Elev= 30
  4147.5  580.06  4210.8  577.85  4484.2  571.67  4683.2  565.88  4880.1  561.87
  4915.7  561.76  4968.0  562.26  4989.0  560.80  4996.8  559.37  4997.2  558.87
  5002.2  559.37  5007.8  561.66  5034.0  561.19  5080.8  562.37  5154.6  562.57
  5178.3  561.28  5185.3  562.59  5195.6  563.19  5227.1  564.07  5270.7  563.96
  5349.2  565.40  5358.0  564.70  5363.2  565.43  5420.9  566.85  5732.9  572.26
  5810.1  574.72  5825.3  575.89  5912.5  577.98  5984.2  581.21  6038.1  582.49
#Mann=5,-1,0
  4147.5     0.1       0  4915.7    0.12       0  4996.8    0.07       0
  5002.2    0.12       0  5034.0     0.1       0
Bank Sta=4996.8,5002.2
Exp/Cntr=0.3,0.1

Type RM Length L Ch R = 1,8229,632,632,632
BEGIN DESCRIPTION:
UNT 026 in BCW 8.0
END DESCRIPTION:
XS GIS Cut Line= 3
      1971997.67     13535132.21      1971733.34     13534392.31
      1971625.01     13533725.05
#Sta/Elev= 30
  4393.5  573.58  4534.5  569.16  4539.8  569.88  4571.1  567.70  4596.1  567.02
  4602.9  567.61  4688.5  565.39  4783.4  562.05  4857.3  560.93  4942.6  560.93
  4974.6  559.72  4980.5  559.16  4981.1  558.45  4983.0  556.21  4983.5  555.71
  4988.1  555.71  4988.5  556.21  5005.9  557.77  5011.3  559.24  5027.7  558.66
  5036.7  560.56  5042.0  559.47  5048.9  560.93  5086.9  560.50  5237.3  562.05
  5452.4  566.36  5520.9  568.67  5693.2  572.62  5827.0  577.95  5855.2  578.45
#Mann=6,-1,0
  4393.5     0.1       0  4942.6    0.12       0  4981.1    0.07       0
  4983.0    0.07       0  4988.5    0.07       0  5086.9     0.1       0
Bank Sta=4983,4988.5
Exp/Cntr=0.3,0.1

Type RM Length L Ch R = 1,7597,138,138,138
BEGIN DESCRIPTION:
Mapping XS 503af088
END DESCRIPTION:
XS GIS Cut Line= 2
      1972056.26     13535112.67      1972108.35     13533732.45
#Sta/Elev= 30
  4039.5  573.46  4140.4  570.56  4167.3  568.55  4197.3  569.31  4227.3  568.07
  4247.3  568.21  4403.1  563.87  4417.4  564.07  4487.5  561.97  4517.5  562.06
  4527.5  561.07  4647.6  557.57  4767.7  557.20  4787.7  557.92  4867.8  558.54
  4877.8  557.89  4897.8  558.57  4977.8  558.07  4987.8  557.16  4997.9  554.71
  5005.1  553.78  5005.5  553.28  5010.2  553.28  5010.7  553.78  5017.9  557.23
  5027.9  559.38  5037.9  559.91  5148.0  563.99  5228.0  565.97  5420.7  574.51
#Mann=3,-1,0
  4039.5     0.1       0  5005.1    0.07       0  5010.7     0.1       0
Bank Sta=5005.1,5010.7
Exp/Cntr=0.3,0.1

Type RM Length L Ch R = 1,7459,131,131,131
BEGIN DESCRIPTION:
Mapping XS 212fb122
END DESCRIPTION:
XS GIS Cut Line= 2
      1972138.29     13535110.07      1972198.99     13533718.39
#Sta/Elev= 30
  4109.9  574.72  4185.0  572.82  4235.1  570.29  4255.1  570.70  4325.2  568.40
  4445.3  565.98  4525.4  562.86  4535.4  563.55  4695.5  559.64  4765.6  557.52
  4805.6  555.44  4815.6  556.35  4854.6  556.76  4898.6  557.34  4925.7  559.63
  4935.8  559.58  4955.8  557.74  4985.8  557.29  5003.0  553.32  5003.5  552.82
  5008.6  553.32  5015.8  553.49  5025.8  554.91  5045.9  558.76  5055.9  559.18
  5085.9  558.55  5125.9  559.93  5156.0  561.86  5196.0  561.39  5502.9  572.28
#Mann=5,-1,0
  4109.9     0.1       0  4854.6    0.07       0  4898.6     0.1       0
  5003.0    0.07       0  5008.6     0.1       0
Bank Sta=5003,5008.6
Exp/Cntr=0.3,0.1

Type RM Length L Ch R = 1,7328,447,447,447
BEGIN DESCRIPTION:
Mapping XS 962e08e8
END DESCRIPTION:
XS GIS Cut Line= 4
      1972455.57     13535090.26      1972302.78     13534562.45
      1972285.42     13533888.84      1972208.18     13533714.28
#Sta/Elev= 30
  4122.5  577.95  4137.9  578.07  4176.7  576.13  4210.3  576.15  4287.9  573.99
  4399.1  569.82  4440.3  566.95  4554.8  562.87  4638.1  561.29  4837.0  556.24
  4889.5  553.80  4899.5  553.80  4909.5  555.00  4935.7  556.12  4979.5  556.86
  4989.5  555.96  4996.7  552.81  4997.2  552.31  5001.9  552.31  5002.3  552.81
  5009.5  554.93  5019.5  556.39  5054.8  556.99  5319.6  563.21  5386.1  565.33
  5438.2  568.30  5502.6  569.96  5514.0  570.82  5531.3  571.05  5536.7  571.72
#Mann=6,-1,0
  4122.5     0.1       0  4837.0    0.12       0  4935.7    0.07       0
  4996.7    0.07       0  5002.3    0.07       0  5054.8     0.1       0
Bank Sta=4996.7,5002.3
Exp/Cntr=0.3,0.1

Type RM Length L Ch R = 1,6881,440,440,440
BEGIN DESCRIPTION:
UNT 026 in BCW 7.0
END DESCRIPTION:
XS GIS Cut Line= 3
      1972724.99     13534974.97      1972538.89     13533993.01
      1972224.98     13533674.98
#Sta/Elev= 30
  4337.2  573.75  4368.4  572.92  4388.1  571.81  4398.2  572.18  4500.0  568.63
  4520.2  568.44  4577.6  565.48  4662.9  562.47  4687.3  562.09  4739.6  559.59
  4844.3  556.39  4914.7  555.11  4988.6  553.70  4998.7  551.81  5003.3  551.56
  5003.7  551.06  5008.5  551.06  5009.0  551.56  5011.2  553.01  5019.1  554.29
  5031.9  554.72  5094.8  554.71  5202.3  555.97  5225.5  556.82  5352.1  558.68
  5387.5  559.67  5429.9  559.90  5451.1  561.31  5606.7  564.99  5783.5  570.94
#Mann=7,-1,0
  4337.2     0.1       0  4844.3    0.12       0  4914.7     0.1       0
  5003.3    0.07       0  5009.0     0.1       0  5031.9    0.12       0
  5094.8     0.1       0
Bank Sta=5003.3,5009
Exp/Cntr=0.3,0.1

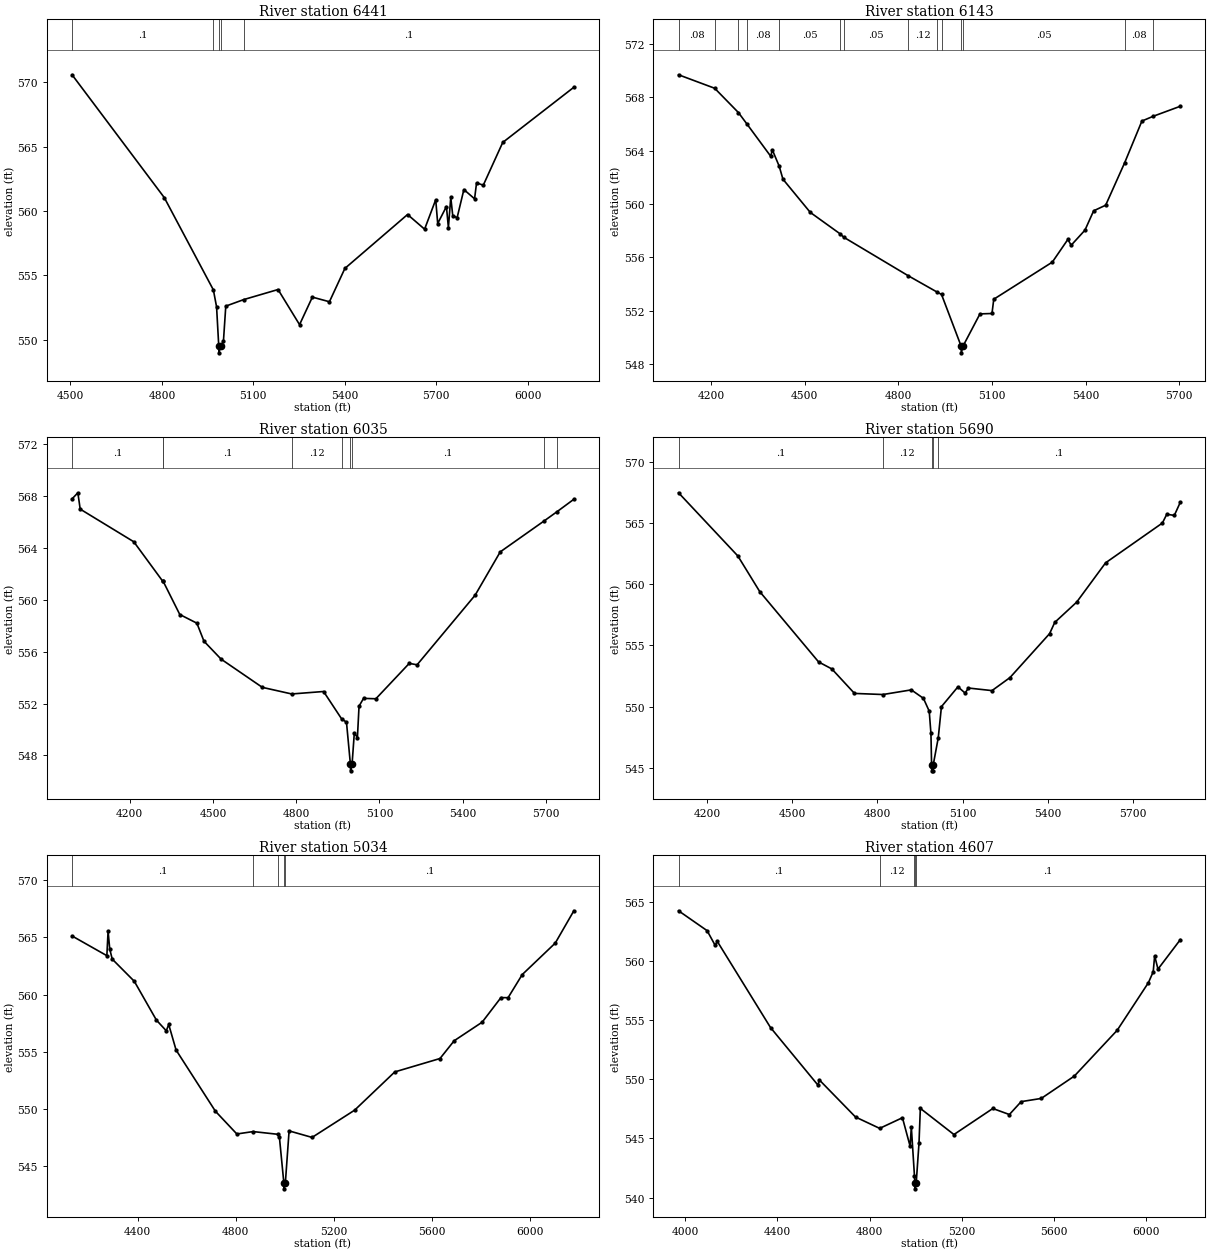
Type RM Length L Ch R = 1,6441,298,298,298
BEGIN DESCRIPTION:
UNT 026 in BCW 6.0
END DESCRIPTION:
XS GIS Cut Line= 3
      1972925.00     13534875.04      1972823.62     13534111.06
      1972262.18     13533438.73
#Sta/Elev= 30
  4505.2  570.58  4807.9  561.03  4968.9  553.86  4979.4  552.54  4986.6  549.47
  4987.0  548.97  4992.3  549.47  5001.9  549.87  5009.6  552.60  5068.7  553.11
  5181.1  553.89  5251.7  551.16  5293.7  553.30  5349.7  552.94  5400.4  555.53
  5606.1  559.72  5662.0  558.58  5698.5  560.87  5705.0  559.02  5733.6  560.34
  5740.1  558.71  5747.9  561.05  5754.4  559.63  5768.7  559.47  5790.9  561.66
  5826.0  560.94  5832.5  562.18  5854.6  562.00  5918.4  565.32  6151.8  569.61
#Mann=5,-1,0
  4505.2     0.1       0  4968.9    0.07       0  4986.6    0.07       0
  4992.3    0.07       0  5068.7     0.1       0
Bank Sta=4986.6,4992.3
Exp/Cntr=0.3,0.1

Type RM Length L Ch R = 1,6143,108,108,108
BEGIN DESCRIPTION:
Mapping XS 3df3d5a0
END DESCRIPTION:
XS GIS Cut Line= 3
      1973261.12     13535031.23      1973042.37     13534256.90
      1972670.82     13533545.07
#Sta/Elev= 30
  4096.1  569.69  4211.8  568.68  4287.8  566.86  4315.2  566.00  4391.4  563.58
  4396.6  564.06  4418.5  562.84  4430.6  561.86  4518.2  559.37  4613.3  557.77
  4625.3  557.51  4832.0  554.62  4924.2  553.40  4938.6  553.22  5001.5  549.34
  5002.0  548.84  5007.4  549.34  5061.8  551.76  5100.3  551.79  5106.0  552.86
  5293.5  555.64  5343.3  557.34  5354.1  556.91  5398.2  558.04  5426.0  559.49
  5464.5  559.91  5525.5  563.10  5580.6  566.22  5617.0  566.58  5703.7  567.33
#Mann=14,-1,0
  4096.1    0.08       0  4211.8    0.05       0  4287.8     0.1       0
  4315.2    0.08       0  4418.5    0.05       0  4613.3    0.08       0
  4625.3    0.05       0  4832.0    0.12       0  4924.2    0.08       0
  4938.6    0.05       0  5001.5    0.04       0  5007.4    0.05       0
  5525.5    0.08       0  5617.0    0.05       0
Bank Sta=5001.5,5007.4
Exp/Cntr=0.3,0.1

Type RM Length L Ch R = 1,6035,345,345,345
BEGIN DESCRIPTION:
UNT 026 in BCW 5.0
END DESCRIPTION:
XS GIS Cut Line= 3
      1973420.85     13535034.72      1973153.48     13534284.68
      1972714.59     13533371.55
#Sta/Elev= 30
  3991.8  567.79  4012.7  568.26  4021.1  567.00  4214.4  564.48  4318.6  561.44
  4320.3  561.43  4380.2  558.87  4441.9  558.20  4467.4  556.81  4529.0  555.43
  4677.8  553.25  4783.8  552.74  4898.7  552.93  4963.7  550.82  4981.3  550.56
  4995.5  547.31  4996.0  546.81  5001.4  547.31  5009.6  549.74  5020.7  549.37
  5026.6  551.80  5042.9  552.40  5087.3  552.37  5207.7  555.10  5235.9  554.99
  5445.2  560.36  5535.7  563.70  5694.8  566.10  5741.1  566.81  5801.2  567.76
#Mann=9,-1,0
  3991.8     0.1       0  4318.6    0.05       0  4320.3     0.1       0
  4783.8    0.12       0  4963.7     0.1       0  4995.5    0.07       0
  5001.4     0.1       0  5694.8    0.05       0  5741.1     0.1       0
Bank Sta=4995.5,5001.4
Exp/Cntr=0.3,0.1

Type RM Length L Ch R = 1,5690,656,656,656
BEGIN DESCRIPTION:
UNT 026 in BCW 4.0
END DESCRIPTION:
XS GIS Cut Line= 3
      1973629.18     13535003.46      1973361.81     13534194.40
      1973075.00     13533324.99
#Sta/Elev= 30
  4099.7  567.46  4308.7  562.30  4385.8  559.39  4593.1  553.65  4639.7  553.08
  4719.5  551.08  4819.8  550.99  4919.6  551.37  4962.3  550.68  4982.8  549.63
  4988.8  547.81  4991.1  545.26  4991.6  544.76  4996.5  544.76  4997.0  545.26
  5014.6  547.46  5025.8  550.00  5084.0  551.62  5109.1  551.11  5121.0  551.52
  5203.9  551.31  5267.1  552.37  5406.8  555.96  5425.0  556.88  5502.1  558.53
  5604.0  561.74  5804.1  564.99  5819.7  565.71  5846.1  565.61  5867.3  566.69
#Mann=5,-1,0
  4099.7     0.1       0  4819.8    0.12       0  4991.1    0.07       0
  4997.0    0.12       0  5014.6     0.1       0
Bank Sta=4991.1,4997
Exp/Cntr=0.3,0.1

Type RM Length L Ch R = 1,5034,427,427,427
BEGIN DESCRIPTION:
UNT 026 in BCW 3.0
END DESCRIPTION:
XS GIS Cut Line= 4
      1973851.39     13534878.47      1973889.59     13534236.06
      1973673.64     13533610.01      1973090.95     13533152.71
#Sta/Elev= 30
  4132.7  565.12  4274.6  563.40  4279.6  565.54  4286.4  563.97  4296.5  563.10
  4386.6  561.16  4476.8  557.77  4516.9  556.84  4526.9  557.39  4556.9  555.16
  4717.2  549.82  4804.7  547.83  4871.1  548.04  4973.2  547.80  4978.4  547.53
  4996.5  543.54  4997.0  543.04  5002.5  543.54  5017.8  548.10  5111.5  547.53
  5285.1  549.91  5448.9  553.25  5633.3  554.42  5691.0  555.97  5805.1  557.59
  5881.9  559.74  5910.9  559.73  5968.7  561.75  6103.4  564.50  6179.2  567.32
#Mann=5,-1,0
  4132.7     0.1       0  4871.1    0.12       0  4973.2     0.1       0
  4996.5    0.07       0  5002.5     0.1       0
Bank Sta=4996.5,5002.5
Exp/Cntr=0.3,0.1

Type RM Length L Ch R = 1,4607,529,529,529
BEGIN DESCRIPTION:
UNT 026 in BCW 2.0
END DESCRIPTION:
XS GIS Cut Line= 3
      1974014.59     13534857.59      1974295.84     13534249.95
      1973868.74     13532802.00
#Sta/Elev= 30
  3970.3  564.24  4094.4  562.56  4129.5  561.31  4138.4  561.66  4369.8  554.37
  4576.0  549.50  4581.5  549.95  4738.9  546.81  4843.8  545.85  4942.7  546.75
  4976.0  544.34  4981.3  545.96  4994.9  541.83  4996.5  541.24  4997.0  540.74
  5002.5  541.24  5014.6  544.60  5020.4  547.54  5166.3  545.33  5335.2  547.53
  5407.1  547.02  5458.3  548.11  5545.5  548.38  5689.2  550.27  5875.3  554.14
  6010.8  558.16  6031.7  559.08  6038.0  560.43  6052.5  559.31  6149.5  561.80
#Mann=5,-1,0
  3970.3     0.1       0  4843.8    0.12       0  4994.9     0.1       0
  4996.5    0.07       0  5002.5     0.1       0
Bank Sta=4996.5,5002.5
Exp/Cntr=0.3,0.1