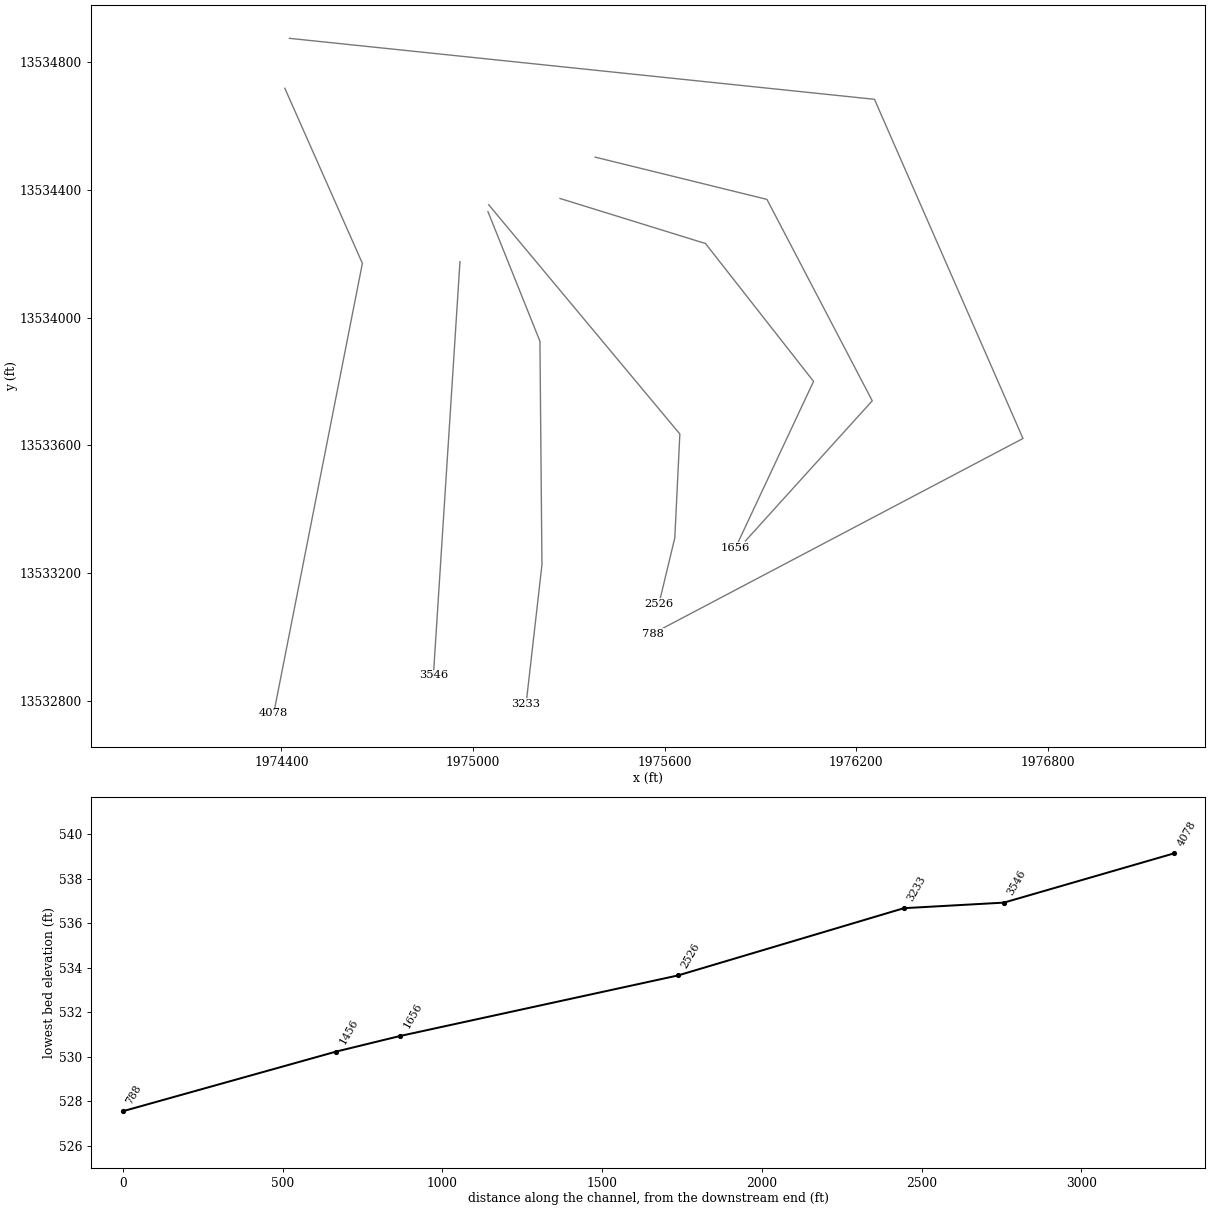
HEC-RAS study UNT 026 in BCW.prj: UNT 026 in BCW Base Level Engineering

--- UNT 026 in BCW.g01 (geometry) --- (continued)

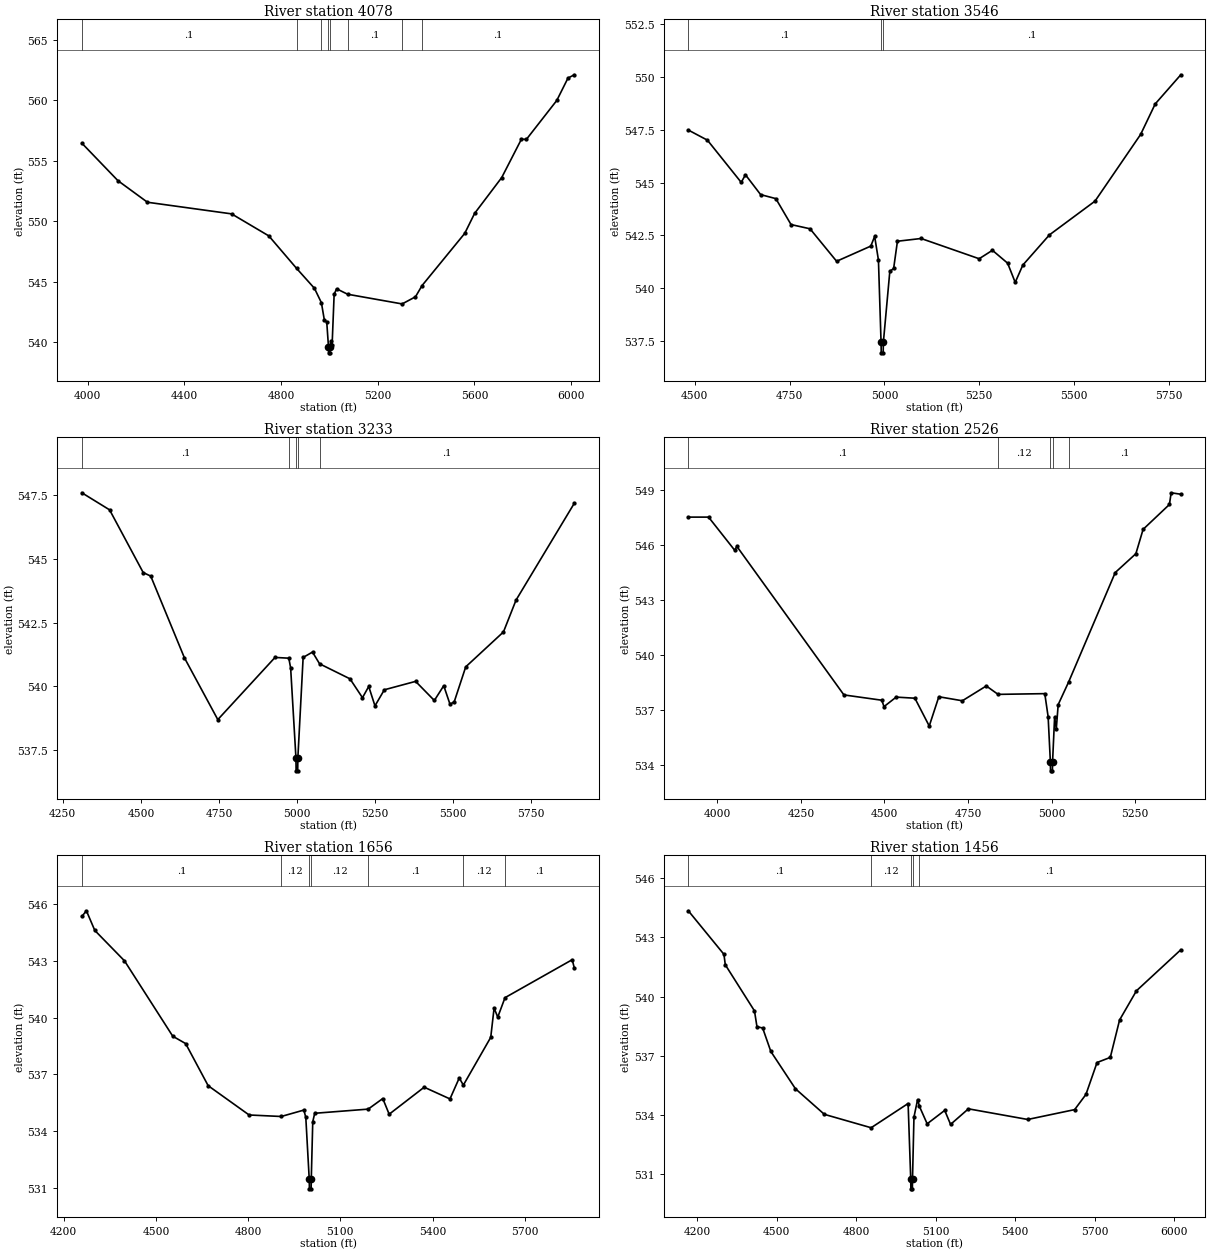
Type RM Length L Ch R = 1,4078,532,532,532
BEGIN DESCRIPTION:
Mapping XS d880163c
END DESCRIPTION:
XS GIS Cut Line= 3
      1974410.42     13534718.72      1974653.48     13534170.09
      1974375.70     13532760.35
#Sta/Elev= 30
  3976.4  556.46  4125.8  553.36  4247.7  551.58  4595.7  550.62  4749.7  548.80
  4864.4  546.12  4938.4  544.47  4967.2  543.28  4979.1  541.88  4989.3  541.68
  4996.5  539.64  4997.0  539.14  5002.1  539.14  5002.6  539.64  5006.4  540.14
  5011.5  539.80  5019.9  543.98  5030.1  544.43  5075.7  543.98  5301.1  543.18
  5356.3  543.77  5383.6  544.70  5560.1  549.01  5600.9  550.66  5713.0  553.62
  5794.5  556.79  5814.9  556.77  5940.8  559.99  5987.1  561.84  6013.3  562.11
#Mann=8,-1,0
  3976.4     0.1       0  4864.4    0.12       0  4967.2    0.16       0
  4996.5    0.07       0  5002.6    0.16       0  5075.7     0.1       0
  5301.1    0.12       0  5383.6     0.1       0
Bank Sta=4996.5,5002.6
Exp/Cntr=0.3,0.1

Type RM Length L Ch R = 1,3546,313,313,313
BEGIN DESCRIPTION:
Mapping XS 63be5bdd
END DESCRIPTION:
XS GIS Cut Line= 2
      1974959.19     13534175.34      1974875.90     13532879.21
#Sta/Elev= 30
  4482.9  547.49  4533.3  547.01  4622.4  545.01  4633.6  545.37  4673.6  544.43
  4713.7  544.24  4753.8  543.01  4803.9  542.81  4874.0  541.27  4964.2  541.99
  4974.3  542.45  4984.3  541.33  4991.2  537.43  4991.7  536.93  4996.8  536.93
  4997.3  537.43  5014.3  540.79  5024.4  540.93  5034.4  542.22  5096.8  542.35
  5249.9  541.39  5284.9  541.79  5325.0  541.18  5345.0  540.27  5365.1  541.09
  5435.2  542.52  5555.4  544.12  5675.7  547.28  5714.3  548.73  5781.7  550.11
#Mann=3,-1,0
  4482.9     0.1       0  4991.2    0.07       0  4997.3     0.1       0
Bank Sta=4991.2,4997.3
Exp/Cntr=0.3,0.1

Type RM Length L Ch R = 1,3233,707,707,707
BEGIN DESCRIPTION:
Mapping XS 3fe8f40c
END DESCRIPTION:
XS GIS Cut Line= 4
      1975046.85     13534332.10      1975209.63     13533926.26
      1975215.98     13533225.65      1975166.28     13532789.58
#Sta/Elev= 30
  4311.0  547.59  4399.8  546.92  4507.4  544.46  4531.6  544.32  4639.2  541.12
  4746.3  538.69  4929.5  541.13  4973.6  541.10  4979.5  540.72  4996.5  537.18
  4997.0  536.68  5002.1  536.68  5002.6  537.18  5019.5  541.13  5049.5  541.34
  5072.1  540.88  5169.5  540.29  5209.5  539.55  5229.5  539.99  5249.5  539.23
  5279.5  539.86  5379.6  540.19  5439.6  539.44  5469.7  540.02  5489.8  539.29
  5503.3  539.39  5540.1  540.76  5660.9  542.13  5701.2  543.38  5887.8  547.18
#Mann=5,-1,0
  4311.0     0.1       0  4973.6    0.07       0  4996.5    0.07       0
  5002.6    0.07       0  5072.1     0.1       0
Bank Sta=4996.5,5002.6
Exp/Cntr=0.3,0.1

Type RM Length L Ch R = 1,2526,870,870,870
BEGIN DESCRIPTION:
Mapping XS fe0e7992
END DESCRIPTION:
XS GIS Cut Line= 4
      1975049.02     13534353.80      1975647.99     13533635.46
      1975632.15     13533310.16      1975582.67     13533104.41
#Sta/Elev= 30
  3913.6  547.53  3974.1  547.53  4052.2  545.72  4058.7  545.93  4378.9  537.81
  4492.2  537.52  4498.7  537.17  4535.1  537.69  4591.1  537.63  4634.0  536.11
  4662.7  537.71  4733.0  537.49  4804.6  538.30  4839.8  537.84  4979.5  537.88
  4989.5  536.62  4996.2  534.16  4996.7  533.66  5002.3  533.66  5002.8  534.16
  5008.9  536.60  5013.9  535.95  5019.6  537.28  5050.9  538.52  5190.2  544.50
  5251.9  545.53  5273.5  546.86  5352.2  548.22  5357.4  548.86  5386.2  548.78
#Mann=5,-1,0
  3913.6     0.1       0  4839.8    0.12       0  4996.2    0.07       0
  5002.8    0.12       0  5050.9     0.1       0
Bank Sta=4996.2,5002.8
Exp/Cntr=0.3,0.1

Type RM Length L Ch R = 1,1656,200,200,200
BEGIN DESCRIPTION:
Mapping XS 3a964036
END DESCRIPTION:
XS GIS Cut Line= 4
      1975272.52     13534373.32      1975728.29     13534232.25
      1976066.83     13533800.39      1975822.23     13533278.73
#Sta/Elev= 30
  4259.2  545.36  4274.0  545.66  4301.3  544.62  4397.9  543.01  4554.9  539.02
  4596.8  538.63  4670.1  536.40  4803.3  534.85  4907.7  534.77  4981.4  535.11
  4987.7  534.72  4998.9  531.44  4999.4  530.94  5005.0  530.94  5005.5  531.44
  5010.3  534.49  5016.7  534.94  5190.6  535.16  5238.1  535.72  5258.9  534.89
  5372.8  536.32  5456.7  535.70  5486.9  536.81  5500.2  536.43  5589.3  538.96
  5600.2  540.51  5612.1  540.03  5635.7  541.06  5854.3  543.07  5861.2  542.63
#Mann=7,-1,0
  4259.2     0.1       0  4907.7    0.12       0  4998.9    0.07       0
  5005.5    0.12       0  5190.6     0.1       0  5500.2    0.12       0
  5635.7     0.1       0
Bank Sta=4998.9,5005.5
Exp/Cntr=0.3,0.1

Type RM Length L Ch R = 1,1456,668,668,668
BEGIN DESCRIPTION:
Mapping XS c869f122
END DESCRIPTION:
XS GIS Cut Line= 4
      1975382.61     13534502.86      1975920.78     13534370.49
      1976250.70     13533739.54      1975853.49     13533300.59
#Sta/Elev= 30
  4167.2  544.35  4301.6  542.14  4306.7  541.61  4416.8  539.27  4426.2  538.47
  4447.7  538.40  4478.6  537.21  4571.3  535.32  4680.5  534.02  4857.0  533.34
  4996.5  534.57  5006.4  530.74  5006.9  530.24  5012.6  530.24  5013.1  530.74
  5018.6  533.88  5032.3  534.77  5039.4  534.42  5068.4  533.54  5134.6  534.22
  5156.7  533.51  5224.1  534.30  5447.8  533.76  5624.9  534.26  5667.5  535.03
  5709.4  536.65  5759.4  536.91  5794.5  538.81  5858.1  540.29  6025.4  542.37
#Mann=5,-1,0
  4167.2     0.1       0  4857.0    0.12       0  5006.4    0.07       0
  5013.1    0.12       0  5039.4     0.1       0
Bank Sta=5006.4,5013.1
Exp/Cntr=0.3,0.1

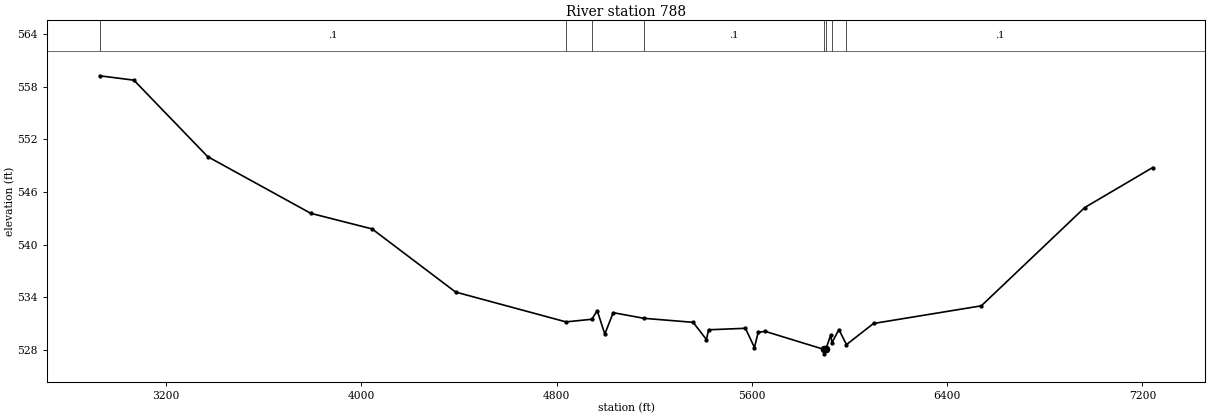
Type RM Length L Ch R = 1,788,0,0,0
BEGIN DESCRIPTION:
UNT 026 in BCW 1.0
END DESCRIPTION:
XS GIS Cut Line= 4
      1974425.02     13534875.00      1976257.64     13534683.98
      1976722.92     13533621.48      1975563.24     13533010.39
#Sta/Elev= 30
  2928.8  559.24  3069.0  558.74  3371.2  550.03  3793.4  543.57  4044.8  541.79
  4386.6  534.60  4838.9  531.20  4945.0  531.50  4966.7  532.49  4997.8  529.81
  5032.2  532.25  5157.3  531.61  5359.7  531.15  5414.3  529.18  5422.6  530.30
  5573.8  530.47  5610.8  528.28  5626.0  530.01  5654.9  530.12  5896.1  528.06
  5896.6  527.56  5903.0  528.06  5923.0  529.70  5928.2  528.82  5956.5  530.33
  5987.6  528.61  6098.5  531.02  6540.0  533.03  6963.6  544.23  7242.1  548.79
#Mann=8,-1,0
  2928.8     0.1       0  4838.9    0.07       0  4945.0    0.12       0
  5157.3     0.1       0  5896.1    0.07       0  5903.0     0.1       0
  5928.2    0.07       0  5987.6     0.1       0
Bank Sta=5896.1,5903
Exp/Cntr=0.3,0.1

Chan Stop Cuts=-1