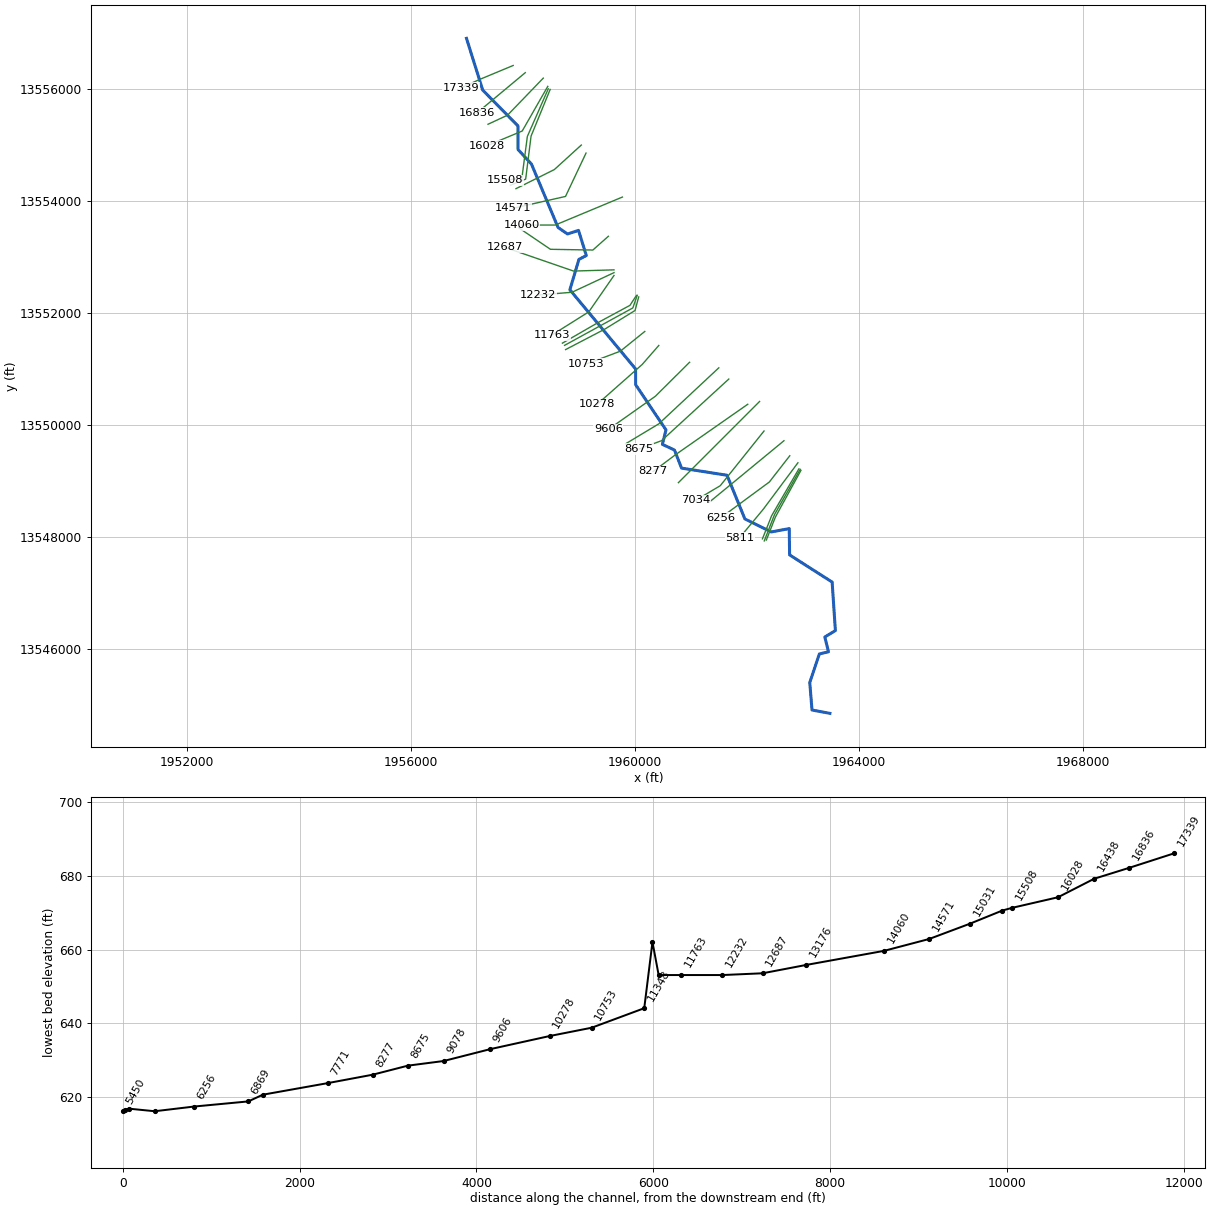
--- UNT 028 in BCW.prj (project) ---

Proj Title=UNT 028 in BCW Base Level Engineering
Current Plan=p01
Default Exp/Contr=0.3,0.1
English Units
Geom File=g01
Flow File=f01
Plan File=p01
Y Axis Title=Elevation
X Axis Title(PF)=Main Channel Distance
X Axis Title(XS)=Station
BEGIN DESCRIPTION:
UNT 028 in BCW
END DESCRIPTION:
DSS Export Rating Curves= 0
DSS Export Rating Curve Sorted= 0
DSS Export Volume Flow Curves= 0
DXF OffsetX= 0
DXF OffsetY= 0
DXF ScaleX= 1
DXF ScaleY= 10

--- UNT 028 in BCW.p01 (plan) ---

Plan Title=Multiple Run
Short Identifier=Multiple
Geom File=g01
Flow File=f01
Subcritical Flow
K Sum by GR= 0
Std Step Tol= 0.01
Critical Tol= 0.01
Num of Std Step Trials= 20
Max Error Tol= 0.3
Flow Tol Ratio= 0.001
Split Flow NTrial= 30
Split Flow Tol= 0.02
Split Flow Ratio= 0.02
Log Output Level= 0
Friction Slope Method= 1
Unsteady Friction Slope Method= 2
Unsteady Bridges Friction Slope Method= 1
Parabolic Critical Depth
Global Vel Dist=  1 , 1 , 1
Global Log Level= 0
CheckData=True
Encroach Param= -1, 0, 0, 0
BEGIN DESCRIPTION:
Multiple Run
END DESCRIPTION:

--- UNT 028 in BCW.f01 (steady flow) ---

Flow Title=Multiple
Number of Profiles=7
Profile Names=10-year,25-year,50-year,1pct_min,100-year,1pct_plu,500-year
River Rch & RM= UNT 028 in BCW,Reach-1,17339
     706    1008    1262     781    1558    3109    2379
River Rch & RM= UNT 028 in BCW,Reach-1,16438
    1112    1624    2063    1293    2579    5146    4041
River Rch & RM= UNT 028 in BCW,Reach-1,7034
    1221    1794    2290    1442    2877    5741    4562
Boundary for River Rch & Prof#=UNT 028 in BCW,Reach-1,1
Up Type=0
Dn Type=3
Dn Slope=0.005
Boundary for River Rch & Prof#=UNT 028 in BCW,Reach-1,2
Up Type=0
Dn Type=3
Dn Slope=0.005
Boundary for River Rch & Prof#=UNT 028 in BCW,Reach-1,3
Up Type=0
Dn Type=3
Dn Slope=0.005
Boundary for River Rch & Prof#=UNT 028 in BCW,Reach-1,4
Up Type=0
Dn Type=3
Dn Slope=0.005
Boundary for River Rch & Prof#=UNT 028 in BCW,Reach-1,5
Up Type=0
Dn Type=3
Dn Slope=0.005
Boundary for River Rch & Prof#=UNT 028 in BCW,Reach-1,6
Up Type=0
Dn Type=3
Dn Slope=0.005
Boundary for River Rch & Prof#=UNT 028 in BCW,Reach-1,7
Up Type=0
Dn Type=3
Dn Slope=0.005

--- UNT 028 in BCW.g01 (geometry) ---

Geom Title=Existing Conditions
Program Version=5.05

River Reach=UNT 028 in BCW  ,Reach-1
Reach XY= 30
       1956990.8     13556909.54       1957280.8     13555984.54
       1957910.8     13555344.54       1957910.8     13554924.54
       1958150.8     13554664.54      1958626.21     13553531.63
      1958794.61     13553415.31      1958991.66     13553479.54
      1959130.55     13553030.76       1958998.6     13552962.18
      1958837.14     13552419.65       1960010.8     13551004.54
       1960010.8     13550724.54      1960553.26     13549916.72
      1960489.37     13549658.39      1960704.65     13549557.69
       1960830.8     13549234.54      1961643.12     13549106.87
      1961962.13     13548326.71      1962433.05      13548094.5
      1962754.23     13548154.18       1962760.8     13547684.54
      1963520.29     13547199.32       1963578.3     13546333.36
       1963389.5     13546218.34      1963454.61     13545954.67
      1963291.85     13545915.61       1963120.8     13545404.54
       1963160.8     13544914.54       1963480.8     13544854.54

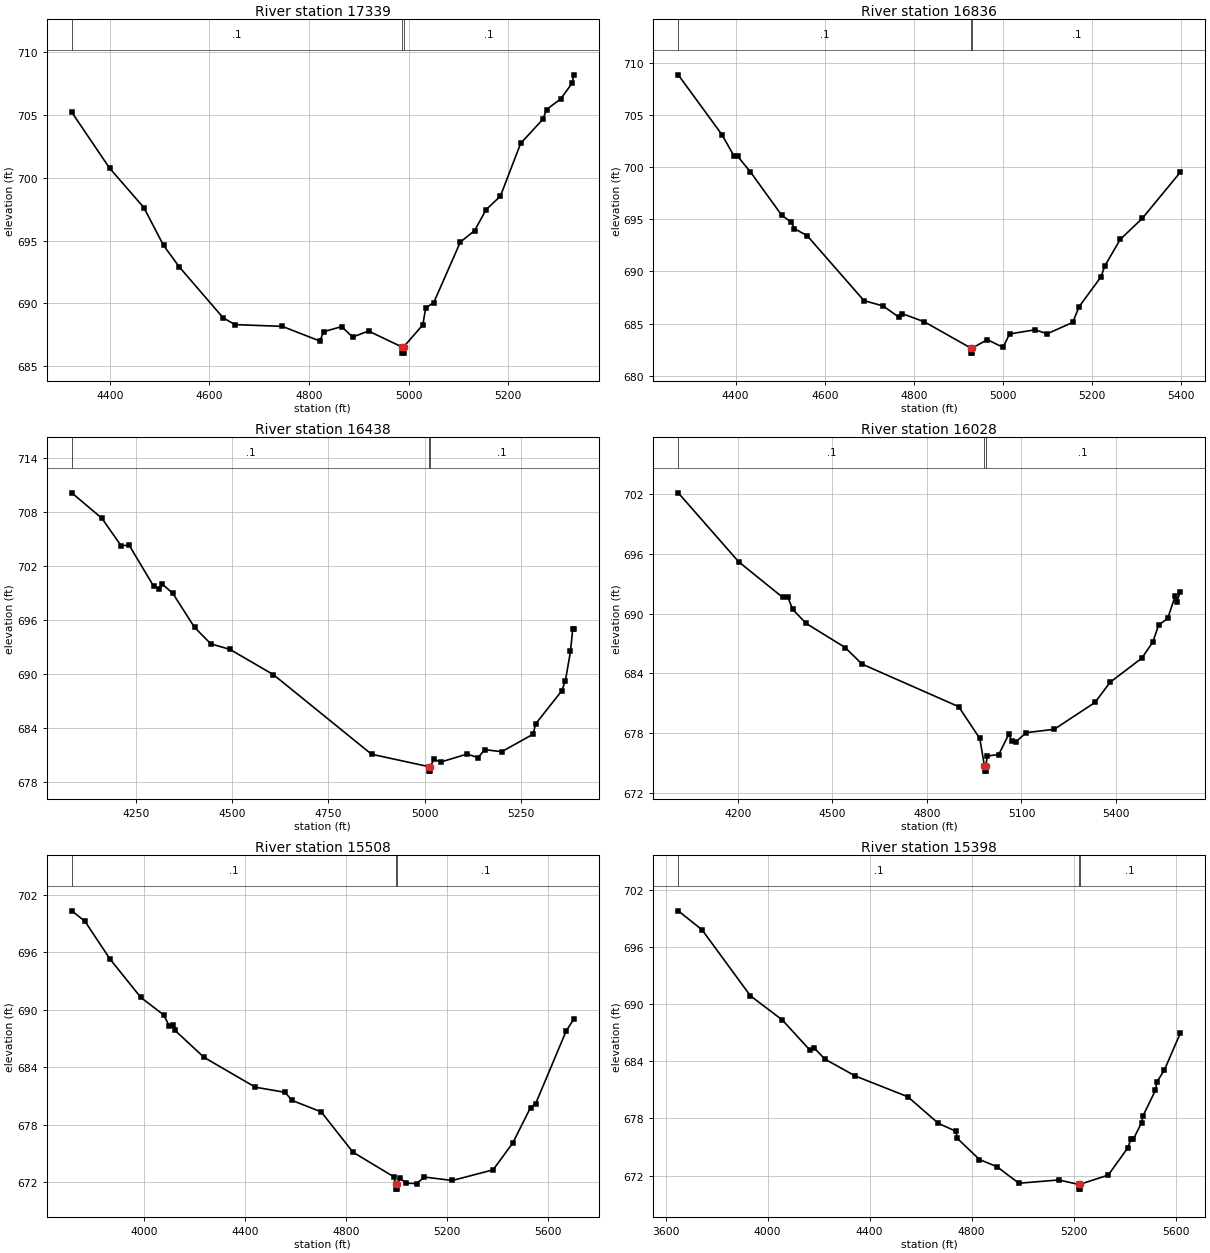
Type RM Length L Ch R = 1 ,17339   ,503,503,503
BEGIN DESCRIPTION:
UNT 028 in BCW 29.0
END DESCRIPTION:
XS GIS Cut Line= 3
      1957824.98     13556424.99        1957225.       13556175.
       1956898.5     13556028.13
#Sta/Elev= 30
  4323.8  705.22  4399.6  700.78  4468.4  697.64    4508  694.63  4539.9   692.9
  4627.7  688.86  4651.5  688.32  4746.3  688.18  4822.1  687.01  4829.2  687.75
  4865.5  688.16  4887.7  687.33  4919.6  687.81  4986.1  686.55  4986.4  686.05
  4989.9  686.05  4990.1  686.55  5028.6   688.3  5034.4  689.65  5050.5  690.07
  5103.9  694.89  5132.5   695.8  5155.7  697.47  5184.3  698.54  5225.1  702.75
  5269.8  704.67  5276.9  705.44  5305.5  706.28  5328.7  707.56  5331.8   708.2
#Mann= 3 ,-1 , 0
  4323.8      .1       0  4986.1     .07       0  4990.1      .1       0
Bank Sta=4986.1,4990.1
XS Rating Curve= 0 ,0
Exp/Cntr=0.3,0.1

Type RM Length L Ch R = 1 ,16836   ,398,398,398
BEGIN DESCRIPTION:
UNT 028 in BCW 28.0
END DESCRIPTION:
XS GIS Cut Line= 3
      1958040.68     13556296.55        1957475.       13555825.
      1957174.97     13555574.98
#Sta/Elev= 30
  4271.1  708.88  4369.1  703.14  4396.4  701.08  4404.2  701.07  4432.9  699.57
  4503.2  695.41  4525.3  694.71  4531.8  694.11  4560.4  693.44    4688   687.2
  4730.9  686.69  4766.1  685.62  4773.2  685.96  4823.4  685.17  4927.4  682.66
  4927.7  682.16  4931.2  682.16  4931.4  682.66  4965.2  683.45  5000.4  682.71
  5014.7     684    5072   684.4  5099.3  684.02  5156.6  685.11  5170.9  686.62
  5220.4   689.5  5228.2   690.5  5263.3  693.08  5312.8   695.1  5398.1  699.53
#Mann= 3 ,-1 , 0
  4271.1      .1       0  4927.4     .07       0  4931.4      .1       0
Bank Sta=4927.4,4931.4
XS Rating Curve= 0 ,0
Exp/Cntr=0.3,0.1

Type RM Length L Ch R = 1 ,16438   ,410,410,410
BEGIN DESCRIPTION:
UNT 028 in BCW 27.0
END DESCRIPTION:
XS GIS Cut Line= 3
       1958361.9     13556198.93      1957723.86     13555537.02
        1957375.       13555375.
#Sta/Elev= 30
  4083.8  710.16  4162.1  707.32  4211.8  704.28  4232.9  704.33  4296.7  699.75
  4310.8  699.49  4317.8  700.04  4346.1  698.98  4402.6  695.19  4445.1  693.35
  4494.5  692.74  4607.7  689.92  4862.4  681.07  5010.9  679.69  5011.2  679.19
  5014.7  679.19  5014.9  679.69  5024.6  680.51    5042   680.2  5110.7  681.09
  5139.1  680.69  5156.3  681.58  5200.4  681.35    5282   683.3  5288.6  684.45
  5356.2  688.11  5365.7  689.22  5379.1  692.51    5385  695.05  5387.8  695.05
#Mann= 3 ,-1 , 0
  4083.8      .1       0  5010.9     .07       0  5014.9      .1       0
Bank Sta=5010.9,5014.9
XS Rating Curve= 0 ,0
Exp/Cntr=0.3,0.1

Type RM Length L Ch R = 1 ,16028   ,520,520,520
BEGIN DESCRIPTION:
UNT 028 in BCW 26.0
END DESCRIPTION:
XS GIS Cut Line= 3
      1958442.19     13556051.37      1957986.45      13555254.9
      1957363.64     13554994.49
#Sta/Elev= 30
  4011.2  702.14  4202.9  695.21  4342.3  691.64  4358.2  691.72    4374  690.43
  4417.2  689.01  4540.9  686.59  4594.2  684.93  4900.7  680.65  4967.9  677.45
  4982.6  674.67  4982.9  674.17  4986.4  674.17  4986.7  674.67  4991.7  675.69
    5028  675.84  5060.5  677.92  5068.5  677.18  5082.2   677.1  5114.7  678.04
  5203.8  678.37  5333.6  681.08  5381.2   683.1  5481.9  685.53  5516.5  687.13
  5534.9  688.83  5564.1  689.54  5587.9  691.79  5593.3  691.21  5603.9  692.22
#Mann= 3 ,-1 , 0
  4011.2      .1       0  4982.6     .07       0  4986.7      .1       0
Bank Sta=4982.6,4986.7
XS Rating Curve= 0 ,0
Exp/Cntr=0.3,0.1

Type RM Length L Ch R = 1 ,15508   ,110,110,110
BEGIN DESCRIPTION:
UNT 028 in BCW 25.0
END DESCRIPTION:
XS GIS Cut Line= 4
      1958450.87     13556007.96      1958077.59     13555157.25
      1957979.94     13554412.89      1957675.02       13554375.
#Sta/Elev= 30
  3714.8   700.3    3767  699.21  3865.9  695.28  3988.2  691.27  4078.4  689.46
  4100.2  688.33  4115.9  688.43  4122.1  687.87  4238.2  685.03  4441.5  681.92
  4558.3  681.39  4587.1  680.54  4701.9  679.35  4827.6  675.15    4989  672.59
    4997   671.8  4997.3   671.3  5000.9   671.3  5001.2   671.8  5011.9  672.44
  5039.4  671.92  5079.8  671.88    5110  672.56    5221   672.2  5382.3  673.31
    5460  676.11  5530.5   679.8  5550.7  680.21  5671.6  687.79  5701.8  689.02
#Mann= 3 ,-1 , 0
  3714.8      .1       0    4997     .07       0  5001.2      .1       0
Bank Sta=4997,5001.2
XS Rating Curve= 0 ,0
Exp/Cntr=0.3,0.1

Type RM Length L Ch R = 1 ,15398   ,367,367,367
BEGIN DESCRIPTION:
Mapping XS 568b2620
END DESCRIPTION:
XS GIS Cut Line= 4
      1958485.15      13555997.1        1958144.     13555163.76
      1958047.65     13554395.53      1957774.23     13554286.16
#Sta/Elev= 30
  3649.6   699.8  3743.1   697.8  3932.8  690.87  4058.1  688.33  4164.9   685.2
  4181.3  685.44  4224.6  684.23  4343.4  682.46  4550.1  680.27  4669.8  677.48
  4739.1  676.64  4744.1   675.9    4831  673.68  4900.1  672.92  4985.6  671.19
  5141.6  671.53  5219.9  671.07  5220.2  670.57  5223.8  670.57  5224.1  671.07
  5335.9  672.04  5413.3  674.92  5424.7  675.84  5434.9  675.83  5467.2  677.56
  5473.2   678.3    5521  680.94  5527.1  681.84  5556.7   683.1  5618.8  686.95
#Mann= 3 ,-1 , 0
  3649.6      .1       0  5219.9     .07       0  5224.1      .1       0
Bank Sta=5219.9,5224.1
XS Rating Curve= 0 ,0
Exp/Cntr=0.3,0.1

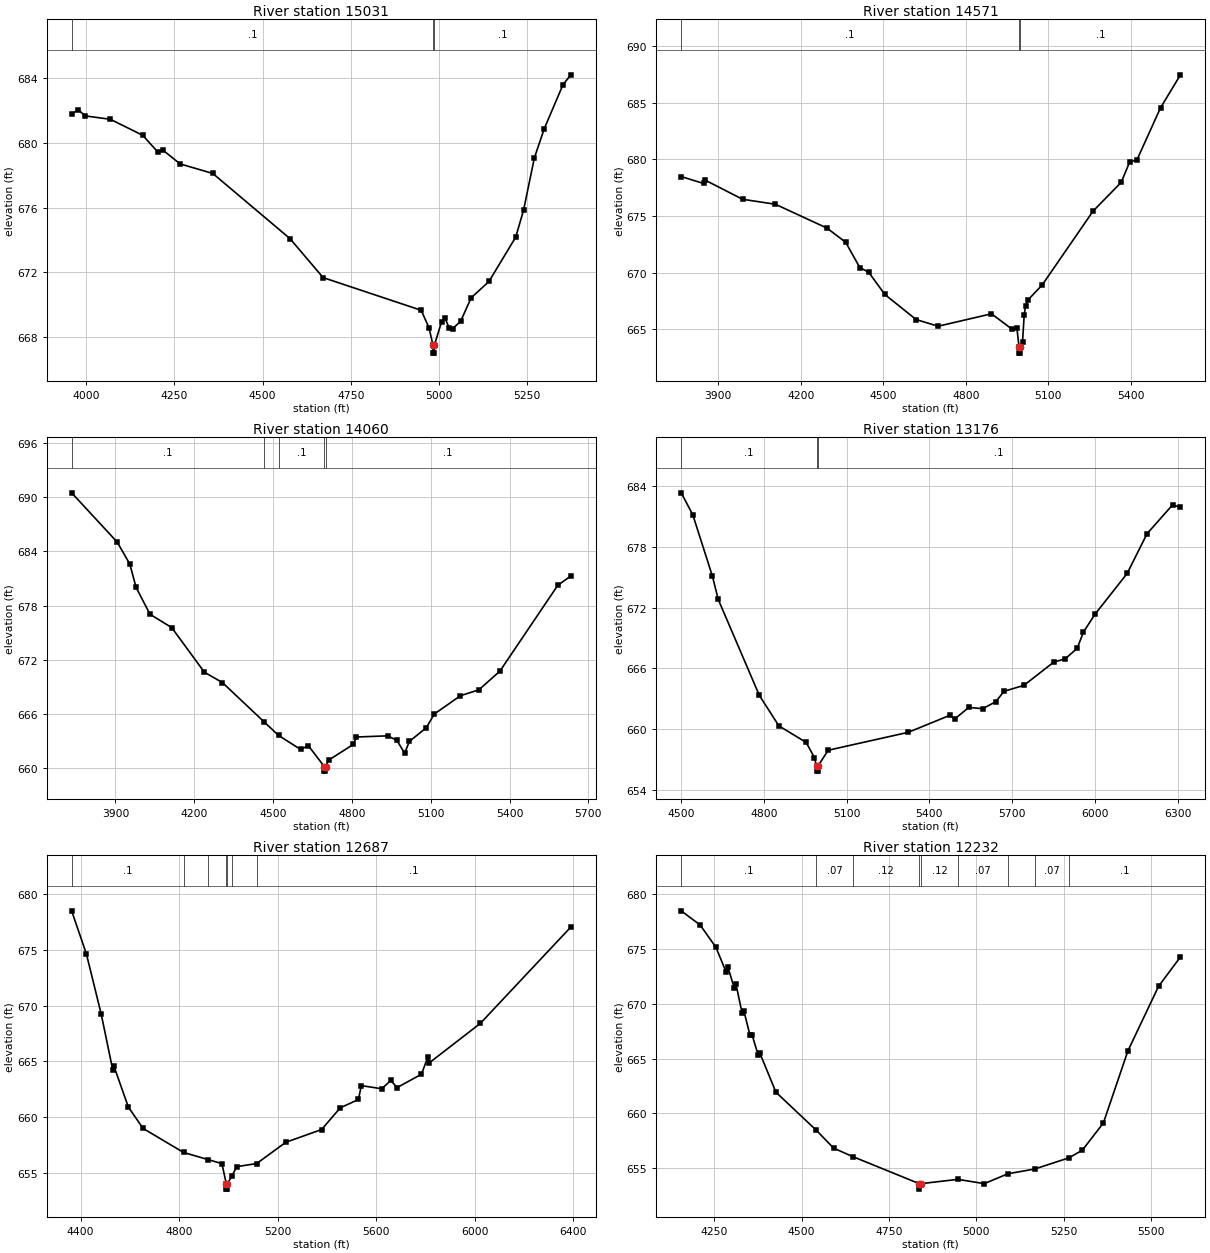
Type RM Length L Ch R = 1 ,15031   ,460,460,460
BEGIN DESCRIPTION:
UNT 028 in BCW 24.0
END DESCRIPTION:
XS GIS Cut Line= 3
      1959041.12     13555004.02      1958559.36     13554565.67
        1957875.       13554225.
#Sta/Elev= 30
  3958.4  681.76  3976.3  682.06  3997.3  681.67  4068.2  681.46  4160.1  680.47
  4202.7  679.44  4216.9  679.56  4266.2   678.7  4358.8  678.11  4577.7  674.08
  4671.7  671.67  4949.7  669.65  4972.1  668.56    4983   667.5  4983.3     667
    4987     667  4987.3   667.5  5007.6  668.94  5016.8  669.18  5029.9  668.53
  5039.1  668.52  5061.4  668.96  5091.5  670.42  5141.9  671.43  5217.8  674.17
  5240.2  675.85  5270.7  679.07  5298.6  680.87  5351.9   683.6  5374.2  684.21
#Mann= 3 ,-1 , 0
  3958.4      .1       0    4983     .07       0  4987.3      .1       0
Bank Sta=4983,4987.3
XS Rating Curve= 0 ,0
Exp/Cntr=0.3,0.1

Type RM Length L Ch R = 1 ,14571   ,511,511,511
BEGIN DESCRIPTION:
UNT 028 in BCW 23.0
END DESCRIPTION:
XS GIS Cut Line= 3
      1959125.77     13554860.79      1958759.02     13554086.06
      1957825.02       13553875.
#Sta/Elev= 30
  3765.4  678.49  3846.4  677.88  3851.9  678.18  3988.4  676.48  4107.7  676.04
  4295.2  673.93  4363.4  672.67  4414.5  670.44  4446.7  670.03  4505.5  668.06
  4619.2  665.84  4699.5  665.25  4893.2  666.35  4968.9  664.97  4985.5  665.11
  4993.5  663.37  4993.8  662.87  4997.6  662.87  4997.9  663.37    5006  663.83
  5012.1  666.26  5017.2  667.05  5026.5  667.59  5077.8  668.91  5262.3  675.43
  5364.8  677.98  5395.6  679.79  5421.3  679.93  5507.6  684.57  5580.1  687.49
#Mann= 3 ,-1 , 0
  3765.4      .1       0  4993.5     .07       0  4997.9      .1       0
Bank Sta=4993.5,4997.9
XS Rating Curve= 0 ,0
Exp/Cntr=0.3,0.1

Type RM Length L Ch R = 1 ,14060   ,884,884,884
BEGIN DESCRIPTION:
UNT 028 in BCW 22.0
END DESCRIPTION:
XS GIS Cut Line= 3
      1959774.97     13554074.99        1958575.       13553575.
      1957974.97       13553575.
#Sta/Elev= 30
  3733.5  690.49  3907.3  685.02    3955  682.59  3978.8  680.01  4031.9  677.03
  4114.3  675.56  4238.8  670.61  4307.6  669.46  4466.7  665.09    4521  663.61
    4605  662.05  4634.3  662.47  4695.4  660.15  4695.7  659.65  4699.5  659.65
  4699.8  660.15  4711.2  660.86    4806  662.62  4817.3  663.43    4936  663.56
  4971.2  663.07    5001  661.63  5018.8  662.94  5083.5  664.46  5113.5  665.97
  5213.5  668.01  5283.5  668.66  5363.5  670.73  5583.5  680.23  5633.5  681.28
#Mann= 5 ,-1 , 0
  3733.5      .1       0  4466.7     .12       0    4521      .1       0
  4695.4     .07       0  4699.8      .1       0
Bank Sta=4695.4,4699.8
XS Rating Curve= 0 ,0
Exp/Cntr=0.3,0.1

Type RM Length L Ch R = 1 ,13176   ,489,489,489
BEGIN DESCRIPTION:
UNT 028 in BCW 21.0
END DESCRIPTION:
XS GIS Cut Line= 4
      1959524.97     13553374.97       1959247.3     13553129.03
      1958489.92     13553142.05        1957925.       13553525.
#Sta/Elev= 30
  4499.7  683.37  4541.9  681.18    4613   675.1  4633.9  672.82  4782.8  663.33
  4853.9   660.3  4952.9  658.66  4982.9  657.16  4990.4  656.32  4990.8  655.82
  4995.1  655.82  4995.4  656.32    5033  657.89    5323  659.66    5473  661.33
    5493  661.01    5543  662.13    5593     662  5641.2   662.7  5670.3  663.72
  5742.8  664.31  5850.8  666.61  5892.8  666.94  5936.1  667.98  5958.6  669.58
  6000.6  671.35  6117.3  675.39  6189.3  679.32  6282.1  682.18  6310.6  681.93
#Mann= 3 ,-1 , 0
  4499.7      .1       0  4990.4     .07       0  4995.4      .1       0
Bank Sta=4990.4,4995.4
XS Rating Curve= 0 ,0
Exp/Cntr=0.3,0.1

Type RM Length L Ch R = 1 ,12687   ,455,455,455
BEGIN DESCRIPTION:
UNT 028 in BCW 20.0
END DESCRIPTION:
XS GIS Cut Line= 3
      1959624.97       13552775.      1958902.25      13552753.6
       1957669.8     13553178.88
#Sta/Elev= 30
  4363.6  678.48  4423.6  674.62  4483.6  669.25  4530.6  664.24  4535.6  664.57
  4593.7  660.93  4653.7  659.01  4818.2  656.86  4916.5  656.23  4973.8  655.86
  4991.3  654.08  4991.7  653.58    4996  653.58  4996.3  654.08  5014.8  654.78
  5033.9  655.59    5115  655.87    5233  657.77  5378.4  658.91    5454  660.85
    5528   661.6  5539.7  662.84  5622.7  662.56  5659.2   663.3  5685.1  662.67
    5784  663.86  5809.9  665.41  5815.2  664.87  6022.9  668.41  6390.4  677.03
#Mann= 7 ,-1 , 0
  4363.6      .1       0  4818.2     .07       0  4916.5     .12       0
  4991.3     .07       0  4996.3     .12       0  5014.8     .07       0
    5115      .1       0
Bank Sta=4991.3,4996.3
XS Rating Curve= 0 ,0
Exp/Cntr=0.3,0.1

Type RM Length L Ch R = 1 ,12232   ,469,469,469
BEGIN DESCRIPTION:
UNT 028 in BCW 19.0
END DESCRIPTION:
XS GIS Cut Line= 3
      1959625.02     13552725.01        1958875.       13552375.
      1958275.05       13552325.
#Sta/Elev= 30
  4155.2  678.46  4209.6  677.16  4254.5  675.14  4283.7  672.89  4289.2   673.3
  4306.6  671.47  4312.1  671.77  4329.4  669.15  4334.9  669.31  4352.3   667.1
  4357.8  667.19  4375.1  665.36  4380.7  665.47  4426.4  661.93  4541.2  658.49
  4591.9  656.83  4648.2  656.04  4836.8   653.6  4837.2   653.1    4842   653.6
  4947.5  653.99    5023   653.6  5090.8   654.5  5167.1  654.93  5265.5  655.95
    5304  656.65  5364.2  659.13  5434.4   665.7  5522.2  671.58  5584.9  674.26
#Mann= 9 ,-1 , 0
  4155.2      .1       0  4541.2     .07       0  4648.2     .12       0
  4836.8     .07       0    4842     .12       0  4947.5     .07       0
  5090.8     .12       0  5167.1     .07       0  5265.5      .1       0
Bank Sta=4836.8,4842
XS Rating Curve= 0 ,0
Exp/Cntr=0.3,0.1

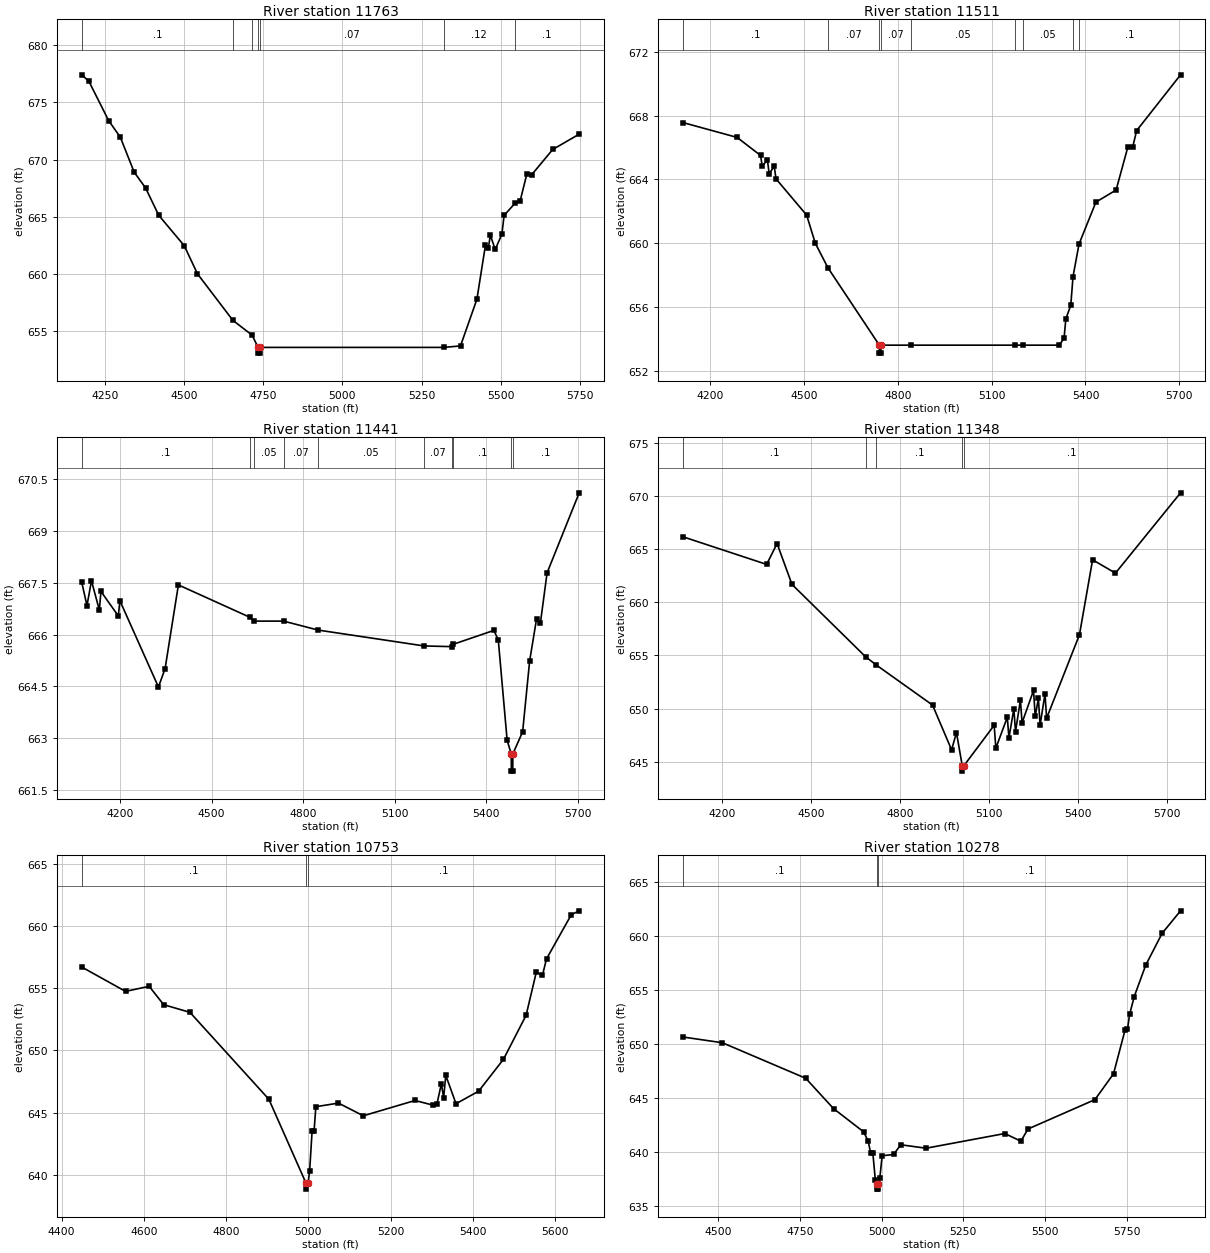
Type RM Length L Ch R = 1 ,11763   ,252,252,252
BEGIN DESCRIPTION:
UNT 028 in BCW 18.0
END DESCRIPTION:
XS GIS Cut Line= 3
      1959624.98     13552674.98        1959175.       13552025.
       1958514.1      13551609.5
#Sta/Elev= 30
  4176.8   677.4  4199.1  676.84  4261.9  673.39  4298.4  671.96  4342.3   668.9
  4378.1  667.53    4420  665.13  4500.4  662.48  4542.3  660.02  4654.1  655.96
  4714.8  654.67  4733.6   653.6    4734   653.1  4738.5   653.1  4738.9   653.6
  5320.6   653.6  5373.1  653.73  5424.9  657.81    5452  662.55  5461.4  662.32
  5467.3  663.41  5482.6  662.15  5503.8  663.48  5510.7  665.12  5544.7  666.17
  5561.5   666.4  5582.7  668.75    5598  668.68  5664.3  670.88    5748  672.22
#Mann= 7 ,-1 , 0
  4176.8      .1       0  4654.1     .12       0  4714.8     .07       0
  4733.6     .07       0  4738.9     .07       0  5320.6     .12       0
  5544.7      .1       0
Bank Sta=4733.6,4738.9
XS Rating Curve= 0 ,0
Exp/Cntr=0.3,0.1

Type RM Length L Ch R = 1 ,11511   ,70,70,70
BEGIN DESCRIPTION:
UNT 028 in BCW 17.0
END DESCRIPTION:
XS GIS Cut Line= 4
      1960024.07     13552315.47      1959909.88     13552141.21
      1959334.54     13551830.42      1958703.46      13551465.8
#Sta/Elev= 30
  4113.1  667.57  4285.9  666.64  4360.7  665.51  4366.4  664.82  4382.6  665.25
  4388.3  664.36  4404.5  664.83  4410.2  664.04  4508.3  661.76  4535.8     660
  4576.2  658.46  4740.7   653.6  4741.1   653.1  4745.6   653.1    4746   653.6
  4842.6   653.6  5174.1   653.6  5198.7   653.6  5315.8   653.6  5331.5  654.02
  5337.3  655.25  5353.1  656.11  5360.3  657.91  5379.5  659.95  5433.5  662.58
  5498.1  663.34  5535.4  666.02  5551.2  666.04  5563.8  667.07  5704.2  670.57
#Mann= 9 ,-1 , 0
  4113.1      .1       0  4576.2     .07       0  4740.7    .033       0
    4746     .07       0  4842.6     .05       0  5174.1     .07       0
  5198.7     .05       0  5360.3     .12       0  5379.5      .1       0
Bank Sta=4740.7,4746
XS Rating Curve= 0 ,0
Exp/Cntr=0.3,0.1

Type RM Length L Ch R = 1 ,11441   ,93,93,93
BEGIN DESCRIPTION:
Mapping XS 5c907a26
END DESCRIPTION:
XS GIS Cut Line= 3
      1960040.06     13552321.05      1959961.11     13552094.98
      1958742.56     13551426.76
#Sta/Elev= 30
  4074.7  667.51  4091.7  666.84  4106.4  667.56  4132.2  666.71  4137.5  667.25
  4194.3  666.54  4199.6  666.98  4325.7  664.48  4347.5  665.01  4391.1  667.44
  4625.6   666.5  4639.1  666.39  4735.8  666.39  4848.8  666.13  5195.9  665.67
    5286  665.65  5291.9  665.72  5424.2  666.12  5438.8  665.85  5467.9  662.93
  5481.3  662.54  5481.7  662.04  5486.2  662.04  5486.6  662.54  5518.6  663.18
  5541.5  665.23  5564.3  666.46  5576.9  666.34  5598.7  667.79  5703.9  670.11
#Mann= 10 ,-1 , 0
  4074.7      .1       0  4625.6     .07       0  4639.1     .05       0
  4735.8     .07       0  4848.8     .05       0  5195.9     .07       0
    5286     .05       0  5291.9      .1       0  5481.3    .033       0
  5486.6      .1       0
Bank Sta=5481.3,5486.6
XS Rating Curve= 0 ,0
Exp/Cntr=0.3,0.1

Type RM Length L Ch R = 1 ,11348   ,595,595,595
BEGIN DESCRIPTION:
UNT 028 in BCW 16.0
END DESCRIPTION:
XS GIS Cut Line= 4
      1960065.93     13552291.36      1960000.83     13552049.19
      1959459.54     13551715.84      1958760.81     13551351.25
#Sta/Elev= 30
    4070  666.15  4351.1  663.56  4386.3  665.52  4436.4  661.68  4684.8  654.86
  4720.3   654.1  4909.7  650.33  4973.8  646.12  4990.2  647.75  5009.7  644.62
  5010.1  644.12    5015  644.62  5117.1  648.43  5122.8  646.28  5161.3  649.18
  5166.9  647.26  5183.4  649.98    5189  647.84  5205.5  650.79  5211.1  648.67
  5249.7  651.71  5255.3  649.28  5266.1  650.95  5271.7  648.43  5288.2  651.37
  5293.8   649.1  5404.3  656.95  5448.5  663.99  5525.5  662.74  5744.6  670.29
#Mann= 5 ,-1 , 0
    4070      .1       0  4684.8     .05       0  4720.3      .1       0
  5009.7     .07       0    5015      .1       0
Bank Sta=5009.7,5015
XS Rating Curve= 0 ,0
Exp/Cntr=0.3,0.1

Type RM Length L Ch R = 1 ,10753   ,475,475,475
BEGIN DESCRIPTION:
UNT 028 in BCW 15.0
END DESCRIPTION:
XS GIS Cut Line= 3
        1960175.       13551675.      1959738.18     13551322.61
      1959131.46     13551093.46
#Sta/Elev= 30
  4449.1  656.72  4555.5  654.76    4613  655.17  4648.2  653.69  4712.2  653.07
  4904.1  646.07  4994.2  639.33  4994.6  638.83  4999.6  639.33  5003.3  640.31
  5009.2  643.48    5014  643.48  5018.4  645.47  5073.4  645.76  5133.8  644.74
  5259.6  645.97  5304.2  645.59    5313   645.7  5323.7  647.33  5329.1  646.18
  5334.4  647.99  5359.3  645.71  5414.3  646.72  5474.7  649.29  5529.7  652.83
  5554.5   656.3  5569.6  656.07  5579.4  657.38  5639.7  660.94  5658.9  661.25
#Mann= 3 ,-1 , 0
  4449.1      .1       0  4994.2     .07       0  4999.6      .1       0
Bank Sta=4994.2,4999.6
XS Rating Curve= 0 ,0
Exp/Cntr=0.3,0.1

Type RM Length L Ch R = 1 ,10278   ,672,672,672
BEGIN DESCRIPTION:
UNT 028 in BCW 14.0
END DESCRIPTION:
XS GIS Cut Line= 3
        1960425.       13551425.      1960129.68      13551086.5
      1959325.03     13550375.02
#Sta/Elev= 30
  4392.1  650.67  4512.2  650.14  4767.5  646.85  4852.7  644.04  4944.7  641.89
  4958.9  641.03  4966.5   639.9  4973.1  639.92  4980.7  637.43  4984.7  637.08
  4985.1  636.58  4989.7  636.58  4990.1  637.08  4994.4   637.6  5001.6  639.67
  5036.7  639.79  5058.5  640.69  5136.3  640.37  5377.2  641.73  5426.5  641.02
  5448.2  642.15  5653.2  644.87  5710.1  647.26  5745.2  651.29  5752.8  651.37
  5759.4  652.77  5773.6  654.42  5808.8  657.33    5859  660.28  5915.4  662.36
#Mann= 3 ,-1 , 0
  4392.1      .1       0  4984.7     .07       0  4990.1      .1       0
Bank Sta=4984.7,4990.1
XS Rating Curve= 0 ,0
Exp/Cntr=0.3,0.1

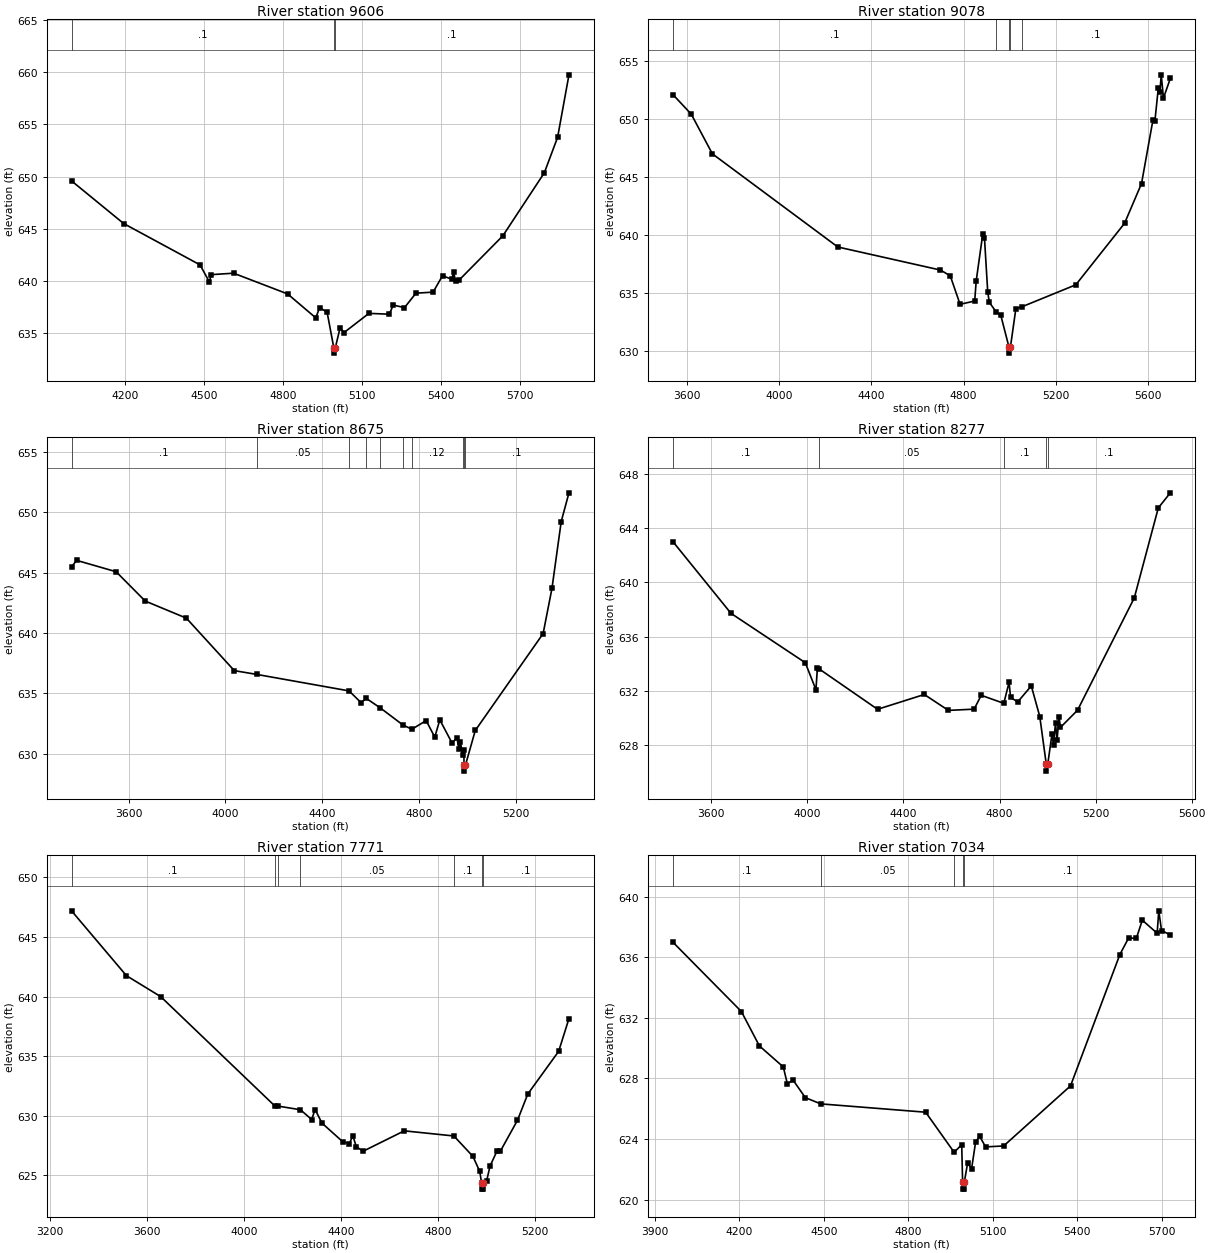
Type RM Length L Ch R = 1 ,9606    ,528,528,528
BEGIN DESCRIPTION:
UNT 028 in BCW 13.0
END DESCRIPTION:
XS GIS Cut Line= 3
      1960975.03     13551125.03      1960364.05     13550517.92
      1959525.02     13549925.01
#Sta/Elev= 30
  3997.6  649.58  4195.6  645.48  4485.5  641.51  4520.9  639.87    4528  640.57
  4612.8  640.71  4817.9  638.72  4924.9  636.42  4939.7  637.41    4968  636.96
  4993.5  633.53  4993.9  633.03    4999  633.53  5017.2  635.45    5032     635
  5126.8  636.85  5204.3  636.77  5219.1  637.65  5261.8   637.4  5305.3  638.79
  5370.5  638.89  5406.2  640.47  5441.9  640.12    5448  640.78  5456.7  639.92
    5470  640.07  5635.2   644.3  5792.8  650.36  5843.2  653.77  5886.3  659.77
#Mann= 3 ,-1 , 0
  3997.6      .1       0  4993.5     .07       0    4999      .1       0
Bank Sta=4993.5,4999
XS Rating Curve= 0 ,0
Exp/Cntr=0.3,0.1

Type RM Length L Ch R = 1 ,9078    ,403,403,403
BEGIN DESCRIPTION:
UNT 028 in BCW 12.0
END DESCRIPTION:
XS GIS Cut Line= 3
      1961496.84     13551025.71        1960425.       13550025.
      1959830.19     13549667.22
#Sta/Elev= 30
  3537.4   652.1  3617.1  650.41  3708.9  646.99  4253.6  638.96  4699.7  636.97
  4742.2  636.47  4784.7  634.02  4848.2   634.3    4855  636.07  4883.4  640.09
  4890.7  639.75  4904.8   635.1  4911.7  634.19  4941.7  633.36  4961.5  633.08
  4997.4  630.31  4997.9  629.81  5003.3  630.31  5027.1  633.65  5051.6  633.79
  5287.4   635.7  5499.1     641  5572.9  644.43  5622.3  649.89  5631.2  649.86
  5645.6  652.64  5652.6   652.3  5658.4   653.8  5668.1  651.79  5697.9  653.49
#Mann= 5 ,-1 , 0
  3537.4      .1       0  4941.7     .12       0  4997.4     .07       0
  5003.3     .12       0  5051.6      .1       0
Bank Sta=4997.4,5003.3
XS Rating Curve= 0 ,0
Exp/Cntr=0.3,0.1

Type RM Length L Ch R = 1 ,8675    ,398,398,398
BEGIN DESCRIPTION:
UNT 028 in BCW 11.0
END DESCRIPTION:
XS GIS Cut Line= 3
      1961675.03     13550825.03        1960475.       13549725.
      1960075.02     13549575.01
#Sta/Elev= 30
  3364.5   645.5  3385.8  646.03  3548.6  645.09  3668.8  642.66    3839  641.24
    4037  636.89  4128.9  636.58  4511.2  635.21  4560.5  634.24  4582.2  634.59
  4640.8  633.79  4733.3  632.39  4770.5  632.03  4829.6  632.75  4865.1  631.38
  4886.1  632.81    4936  630.91    4957  631.31  4964.4  630.43  4971.2  630.99
  4979.8  629.92  4985.3  630.33  4986.1  629.06  4986.5  628.56    4992  629.06
  5032.5  631.93  5312.8  639.96  5349.3   643.7  5387.6  649.25  5419.6  651.63
#Mann= 10 ,-1 , 0
  3364.5      .1       0  4128.9     .05       0  4511.2      .1       0
  4582.2     .05       0  4640.8      .1       0  4733.3     .05       0
  4770.5     .12       0  4979.8      .1       0  4986.1     .07       0
    4992      .1       0
Bank Sta=4986.1,4992
XS Rating Curve= 0 ,0
Exp/Cntr=0.3,0.1

Type RM Length L Ch R = 1 ,8277    ,506,506,506
BEGIN DESCRIPTION:
UNT 028 in BCW 10.0
END DESCRIPTION:
XS GIS Cut Line= 3
      1962013.38     13550374.71        1960725.       13549475.
      1960325.03     13549175.02
#Sta/Elev= 30
  3439.7     643  3681.7  637.72    3991  634.09  4035.4   632.1  4041.6  633.73
  4049.6  633.62    4292  630.66  4486.7  631.75  4586.8  630.58  4694.1  630.67
  4723.7  631.69  4817.7   631.1  4839.7  632.65  4845.8  631.54  4875.5   631.2
  4932.2  632.38  4967.5  630.13  4994.6  626.61  4995.1  626.11  5000.6  626.61
  5018.4  628.84  5024.7  628.01    5033  629.68  5039.3  628.37  5047.6  630.09
  5053.8  629.33  5124.7  630.59  5361.1  638.86  5461.1  645.48  5511.1  646.59
#Mann= 5 ,-1 , 0
  3439.7      .1       0  4049.6     .05       0  4817.7      .1       0
  4994.6     .07       0  5000.6      .1       0
Bank Sta=4994.6,5000.6
XS Rating Curve= 0 ,0
Exp/Cntr=0.3,0.1

Type RM Length L Ch R = 1 ,7771    ,737,737,737
BEGIN DESCRIPTION:
UNT 028 in BCW 9.0
END DESCRIPTION:
XS GIS Cut Line= 3
      1962225.03     13550425.03        1961025.       13549225.
      1960774.97     13548974.97
#Sta/Elev= 30
  3288.1  647.19  3514.4  641.75  3655.8  639.99  4126.6  630.81  4138.5  630.81
  4231.7   630.5  4278.1  629.68  4292.2  630.52  4320.5  629.38  4405.4  627.83
  4433.7  627.66  4447.8  628.33  4461.9   627.4  4490.2  627.02  4659.9  628.73
  4864.3   628.3  4942.8  626.59  4971.1  625.32  4978.7  624.34  4979.2  623.84
  4984.2  623.84  4984.7  624.34  4999.3  624.53  5013.5  625.78  5041.8  627.02
  5055.9  627.02  5126.6  629.62  5169.1  631.82  5296.3   635.4  5338.8  638.15
#Mann= 7 ,-1 , 0
  3288.1      .1       0  4126.6     .12       0  4138.5      .1       0
  4231.7     .05       0  4864.3      .1       0  4978.7     .07       0
  4984.7      .1       0
Bank Sta=4978.7,4984.7
XS Rating Curve= 0 ,0
Exp/Cntr=0.3,0.1

Type RM Length L Ch R = 1 ,7034    ,165,165,165
BEGIN DESCRIPTION:
UNT 028 in BCW 8.0
END DESCRIPTION:
XS GIS Cut Line= 3
      1962304.16     13549897.27      1961522.91      13548920.7
      1961078.99     13548656.51
#Sta/Elev= 30
    3964     637  4207.3  632.42  4271.3  630.15  4356.2  628.76  4370.6  627.65
  4391.4  627.88  4434.6  626.73  4489.5  626.32    4862  625.77  4963.3  623.12
  4990.1  623.63  4993.2  621.19  4993.7  620.69  4999.3  620.69  4999.8  621.19
  5010.9   622.4  5025.3  622.05  5039.7  623.83  5054.1  624.17  5074.9  623.48
    5139  623.54  5376.7  627.51  5551.9  636.18  5583.1  637.28  5610.4  637.25
  5631.8  638.45  5684.4  637.59  5690.2  639.07    5700  637.77  5731.2  637.48
#Mann= 5 ,-1 , 0
    3964      .1       0  4489.5     .05       0  4963.3      .1       0
  4993.2     .07       0  4999.8      .1       0
Bank Sta=4993.2,4999.8
XS Rating Curve= 0 ,0
Exp/Cntr=0.3,0.1

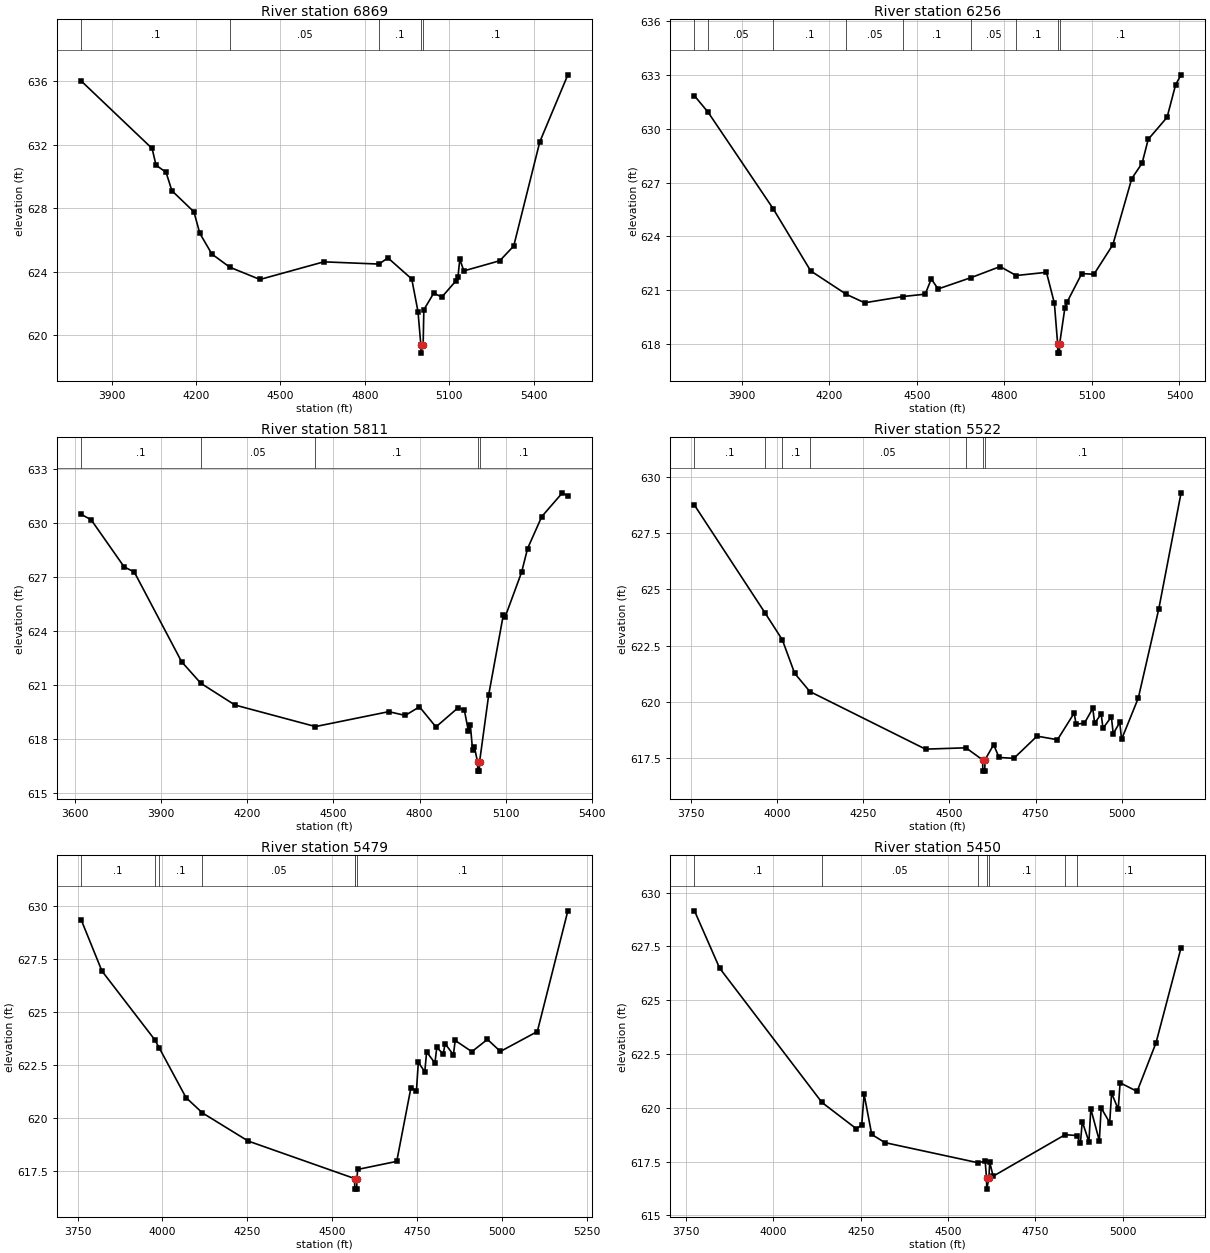
Type RM Length L Ch R = 1 ,6869    ,613,613,613
BEGIN DESCRIPTION:
UNT 028 in BCW 7.0
END DESCRIPTION:
XS GIS Cut Line= 3
      1962660.07     13549723.66      1961722.56     13548951.08
      1961325.01     13548625.01
#Sta/Elev= 30
  3792.5  636.01  4044.3  631.76  4058.2  630.71  4093.8  630.26  4114.6   629.1
  4192.8  627.77  4213.7  626.42  4256.7  625.11  4320.5  624.28  4427.4  623.51
  4654.3  624.62  4850.4  624.48  4882.2  624.87  4966.8  623.54    4989  621.49
  4999.2  619.37  4999.7  618.87  5005.8  619.37  5007.3  619.37  5009.8   621.6
    5045  622.65  5073.7   622.4  5123.2  623.41  5131.1  623.68  5137.6  624.79
  5151.9  624.05  5279.7  624.69  5329.2  625.62  5421.8  632.18  5521.5   636.4
#Mann= 5 ,-1 , 0
  3792.5      .1       0  4320.5     .05       0  4850.4      .1       0
  4999.2     .07       0  5005.8      .1       0
Bank Sta=4999.2,5005.8
XS Rating Curve= 0 ,0
Exp/Cntr=0.3,0.1

Type RM Length L Ch R = 1 ,6256    ,445,445,445
BEGIN DESCRIPTION:
UNT 028 in BCW 6.0
END DESCRIPTION:
XS GIS Cut Line= 3
      1962763.78      13549455.4      1962399.21     13548986.67
      1961534.27     13548349.35
#Sta/Elev= 30
  3737.4  631.84  3784.2  630.92  4007.1  625.54  4135.7  622.07  4258.2  620.76
  4320.7  620.29  4452.5  620.64  4528.4  620.77  4549.3  621.62  4572.4  621.06
  4686.6   621.7  4785.3  622.31  4840.3  621.81  4944.1  621.99  4971.2  620.27
  4982.5  617.98    4983  617.48  4988.6  617.48  4989.1  617.98  5007.2     620
  5015.1  620.34  5065.2  621.92  5106.9  621.88  5171.7  623.53  5236.5  627.22
    5272  628.08  5292.9  629.41  5357.6  630.64  5386.9  632.46  5405.6  633.01
#Mann= 9 ,-1 , 0
  3737.4      .1       0  3784.2     .05       0  4007.1      .1       0
  4258.2     .05       0  4452.5      .1       0  4686.6     .05       0
  4840.3      .1       0  4982.5     .07       0  4989.1      .1       0
Bank Sta=4982.5,4989.1
XS Rating Curve= 0 ,0
Exp/Cntr=0.3,0.1

Type RM Length L Ch R = 1 ,5811    ,289,289,289
BEGIN DESCRIPTION:
UNT 028 in BCW 5.0
END DESCRIPTION:
XS GIS Cut Line= 3
      1962909.19     13549329.56      1962294.36     13548504.86
      1961869.85     13547992.93
#Sta/Elev= 30
  3622.4   630.5  3656.9   630.2  3771.6  627.58    3807  627.29  3971.7   622.3
  4038.6   621.1  4157.3  619.89  4437.6  618.69  4692.8  619.52  4750.1  619.31
  4799.6  619.79  4856.9  618.67    4935  619.75  4955.9   619.6  4970.2  618.42
  4976.7  618.78  4984.5  617.38    4991  617.53    5002  616.71  5002.5  616.21
  5008.2  616.21  5008.7  616.71  5040.6  620.46  5091.3  624.89  5097.8  624.79
  5155.1  627.28  5175.9   628.6  5225.4  630.38  5297.1   631.7  5316.1  631.52
#Mann= 5 ,-1 , 0
  3622.4      .1       0  4038.6     .05       0  4437.6      .1       0
    5002     .07       0  5008.7      .1       0
Bank Sta=5002,5008.7
XS Rating Curve= 0 ,0
Exp/Cntr=0.3,0.1

Type RM Length L Ch R = 1 ,5522    ,43,43,43
BEGIN DESCRIPTION:
Mapping XS 5c3f65cc
END DESCRIPTION:
XS GIS Cut Line= 3
      1962926.55     13549221.04      1962440.44     13548385.54
      1962275.52     13547971.07
#Sta/Elev= 30
  3759.7  628.76  3965.2  623.94  4014.6  622.76  4050.6  621.26  4094.6  620.45
  4430.4  617.88  4547.8  617.94  4596.3   617.4  4596.8   616.9  4602.5   616.9
    4603   617.4  4628.2  618.08  4643.9  617.51  4686.9  617.47  4754.2  618.46
  4813.5   618.3  4862.1  619.49  4867.5  618.99  4891.8  619.04  4916.1   619.7
  4921.4  619.03  4940.3  619.45  4945.7  618.81    4970  619.32  4975.4  618.57
  4994.3  619.07  4999.7  618.32  5048.2  620.16  5107.6  624.13  5172.4  629.31
#Mann= 7 ,-1 , 0
  3759.7      .1       0  3965.2     .05       0  4014.6      .1       0
  4094.6     .05       0  4547.8      .1       0  4596.3     .07       0
    4603      .1       0
Bank Sta=4596.3,4603
XS Rating Curve= 0 ,0
Exp/Cntr=0.3,0.1

Type RM Length L Ch R = 1 ,5479    ,29,29,29
BEGIN DESCRIPTION:
Mapping XS 8630b993
END DESCRIPTION:
XS GIS Cut Line= 3
      1962950.42     13549212.36      1962492.52     13548407.25
      1962308.06     13547934.15
#Sta/Elev= 30
  3760.9  629.36  3821.8  626.95  3977.2  623.71  3990.3  623.33  4069.7  620.97
  4117.9  620.25  4252.8  618.92  4566.4  617.15  4566.5  617.15    4567  616.65
  4572.7  616.65  4573.2  617.15  4575.6  617.58  4690.6  617.96  4732.5  621.44
  4748.8   621.3  4754.2  622.64  4773.3  622.19  4778.7  623.13  4803.2   622.6
  4808.6  623.34  4827.7  623.03  4833.1  623.52  4857.6  622.99  4862.9  623.67
  4911.9  623.14  4957.9  623.72  4996.1  623.15  5104.9  624.09  5194.9  629.79
#Mann= 7 ,-1 , 0
  3760.9      .1       0  3977.2     .05       0  3990.3      .1       0
  4117.9     .05       0  4566.4      .1       0  4566.5     .07       0
  4573.2      .1       0
Bank Sta=4566.5,4573.2
XS Rating Curve= 0 ,0
Exp/Cntr=0.3,0.1

Type RM Length L Ch R = 1 ,5450    ,494,494,494
BEGIN DESCRIPTION:
Mapping XS f0a20a5d
END DESCRIPTION:
XS GIS Cut Line= 3
      1962963.44       13549195.      1962507.72     13548361.67
       1962345.1     13547949.71
#Sta/Elev= 30
  3774.2  629.15  3846.1  626.49  4138.9  620.25  4237.8  619.02  4252.9  619.21
  4259.7  620.63  4281.5  618.76  4319.4  618.38  4584.6  617.45  4606.2  617.51
  4610.1  616.72  4610.6  616.22  4616.8  616.72  4619.2  617.47    4629  616.82
  4835.2  618.75  4868.1  618.71  4878.8  618.36  4884.1  619.36  4903.1  618.42
  4908.5  619.95  4932.9  618.47  4938.2  619.99  4962.6  619.31    4968  620.68
    4987  619.93  4992.4  621.16  5041.1  620.76  5095.2  623.02  5166.9  627.44
#Mann= 7 ,-1 , 0
  3774.2      .1       0  4138.9     .05       0  4584.6      .1       0
  4610.1     .07       0  4616.8      .1       0  4835.2     .05       0
  4868.1      .1       0
Bank Sta=4610.1,4616.8
XS Rating Curve= 0 ,0
Exp/Cntr=0.3,0.1