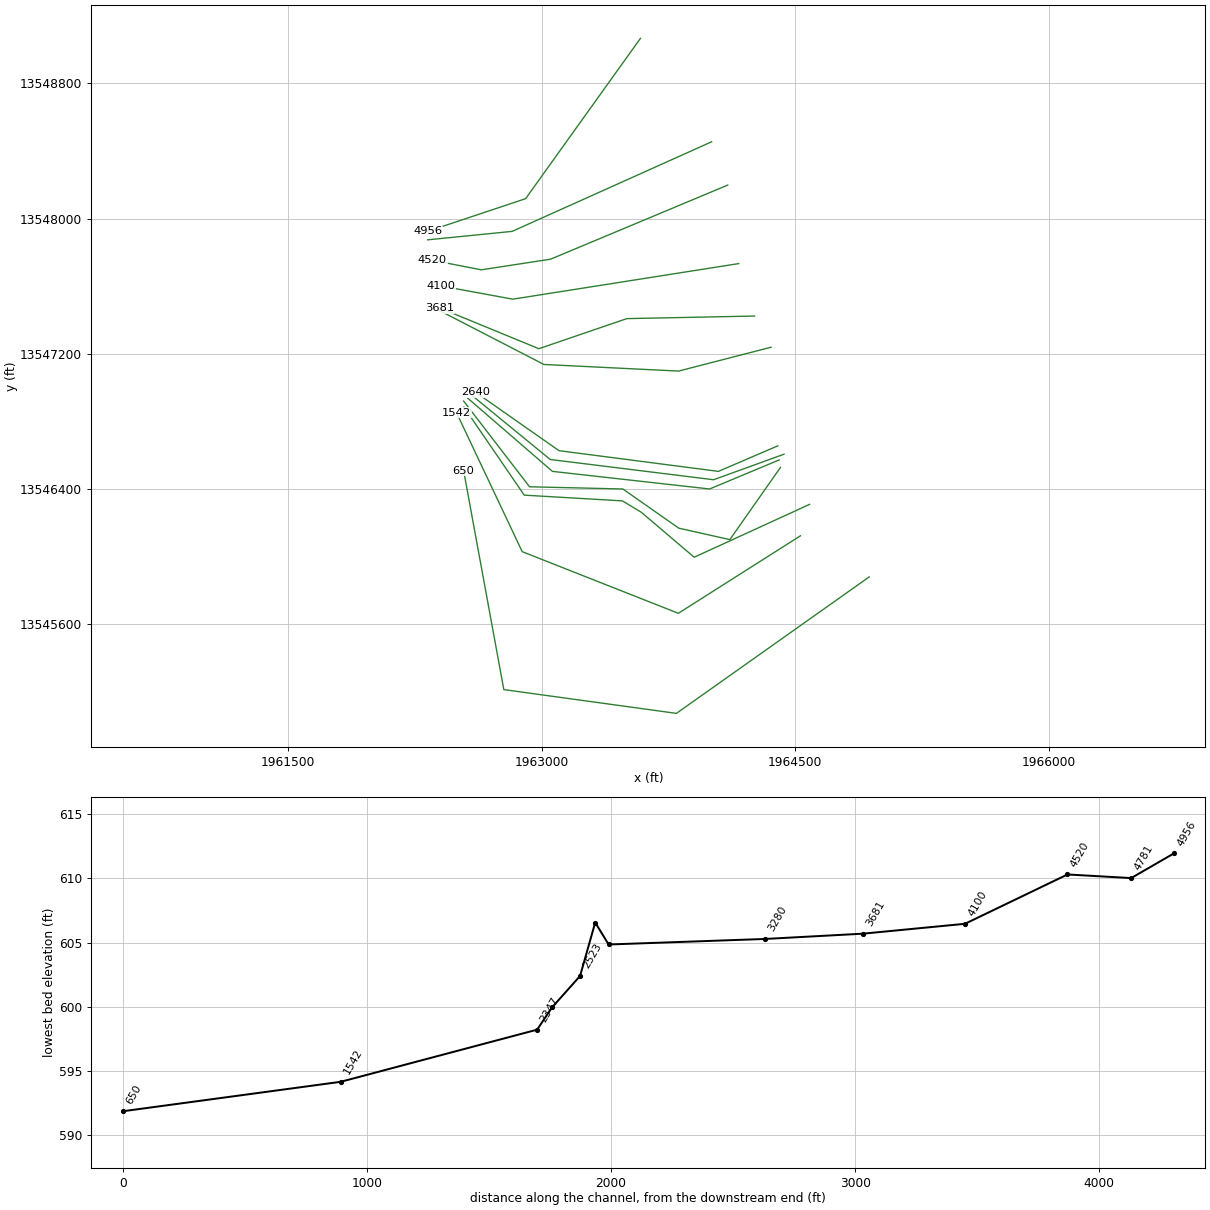
HEC-RAS study UNT 028 in BCW.prj: UNT 028 in BCW Base Level Engineering

--- UNT 028 in BCW.g01 (geometry) --- (continued)

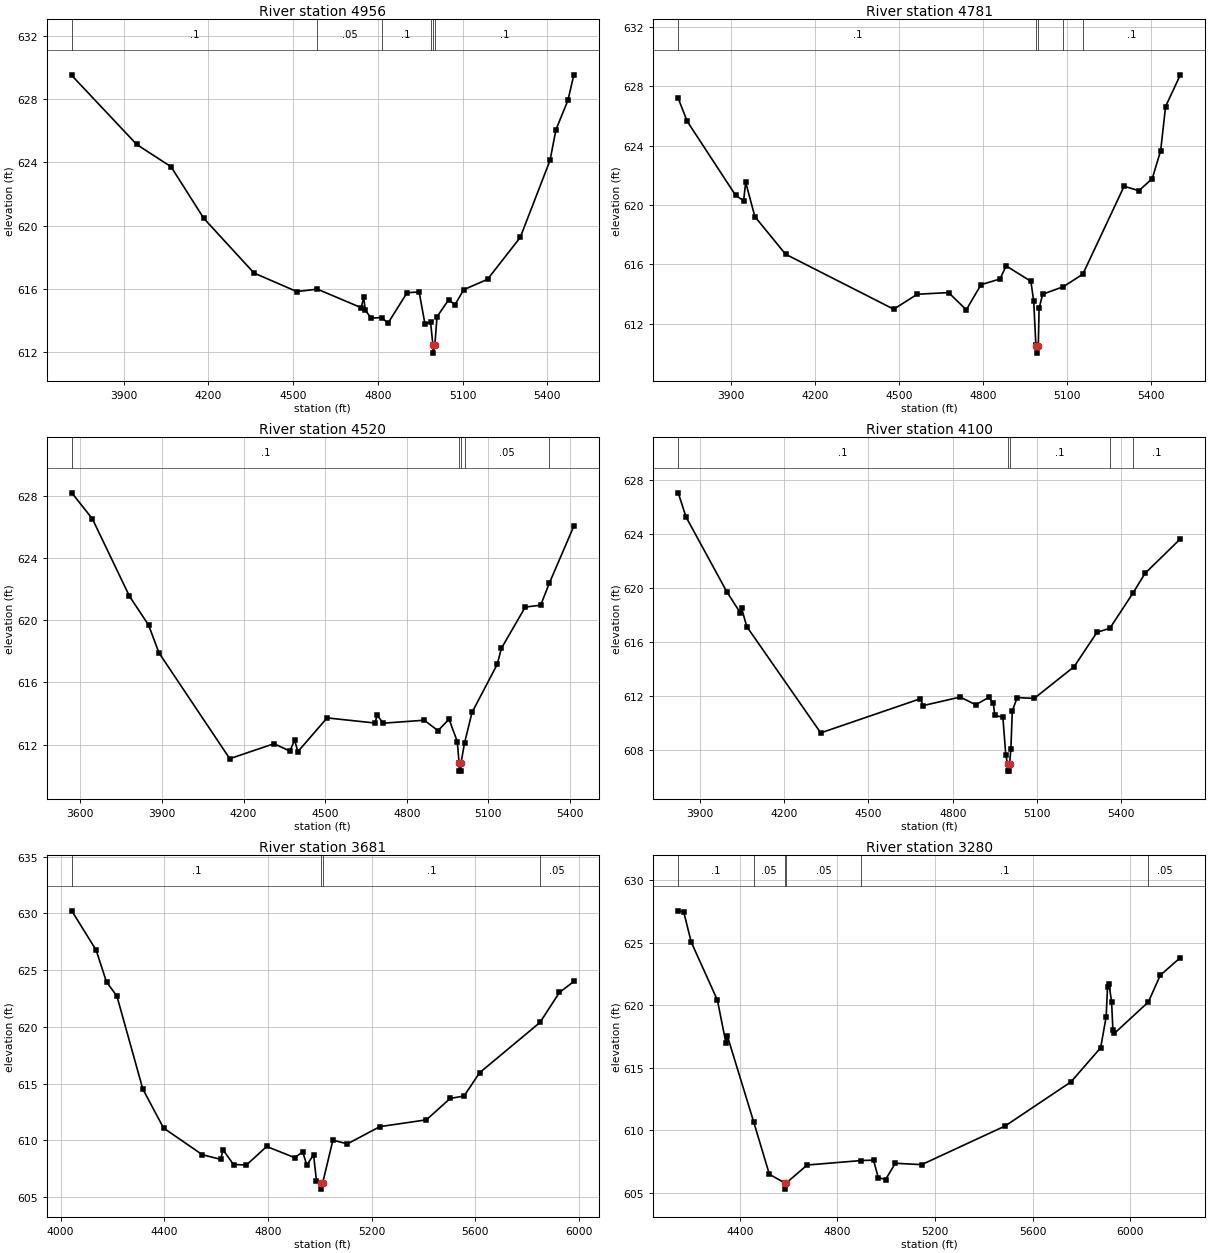
Type RM Length L Ch R = 1 ,4956    ,175,175,175
BEGIN DESCRIPTION:
UNT 028 in BCW 4.0
END DESCRIPTION:
XS GIS Cut Line= 3
      1963584.09     13549066.94      1962904.85     13548118.62
        1962325.       13547925.
#Sta/Elev= 30
  3716.1  629.48  3946.2  625.12  4067.8  623.71  4183.3  620.46  4361.4     617
  4512.5  615.83    4586  615.98    4741  614.81  4749.5  615.46  4755.7  614.64
  4776.6  614.15  4814.1  614.19  4835.5  613.82  4903.5  615.76  4946.2   615.8
  4966.8  613.77  4986.4  613.92    4995  612.44  4995.5  611.94  5001.7  612.44
  5009.4  614.24  5051.1  615.32  5072.6  614.99  5104.2  615.95  5188.2   616.6
  5304.1  619.25  5409.6  624.12  5430.6  626.06  5472.8   627.9  5493.9  629.52
#Mann= 6 ,-1 , 0
  3716.1      .1       0    4586     .05       0  4814.1      .1       0
  4986.4     .05       0    4995    .035       0  5001.7      .1       0
Bank Sta=4995,5001.7
XS Rating Curve= 0 ,0
Exp/Cntr=0.3,0.1

Type RM Length L Ch R = 1 ,4781    ,261,261,261
BEGIN DESCRIPTION:
UNT 028 in BCW 3.0
END DESCRIPTION:
XS GIS Cut Line= 3
      1964005.09     13548454.98        1962825.       13547925.
      1962325.03       13547875.
#Sta/Elev= 30
  3710.4  627.19  3742.4  625.65  3915.6  620.66  3944.2  620.29  3951.7  621.53
  3984.6  619.22  4094.2  616.69  4481.3  612.98  4565.5  613.99  4677.6   614.1
  4740.9  612.94  4793.4  614.63  4861.5  615.02  4883.5   615.9    4972  614.86
  4982.1  613.51  4989.7  610.59  4991.8  610.52  4992.3  610.02  4998.5  610.52
  5001.3  613.04  5014.1  613.99  5088.2   614.5  5157.7  615.34  5305.5  621.27
  5358.3  620.97    5406  621.78  5436.2  623.67  5453.8  626.64  5506.5  628.78
#Mann= 5 ,-1 , 0
  3710.4      .1       0  4991.8     .07       0  4998.5      .1       0
  5088.2     .05       0  5157.7      .1       0
Bank Sta=4991.8,4998.5
XS Rating Curve= 0 ,0
Exp/Cntr=0.3,0.1

Type RM Length L Ch R = 1 ,4520    ,420,420,420
BEGIN DESCRIPTION:
Mapping XS d572f250
END DESCRIPTION:
XS GIS Cut Line= 4
      1964100.61     13548198.92      1963052.42     13547760.54
      1962642.26     13547697.61      1962353.65     13547754.03
#Sta/Elev= 30
  3568.8  628.18  3644.5  626.51  3780.8  621.54  3851.2  619.68  3889.2   617.9
  4149.4   611.1    4312  612.06  4370.5  611.59  4387.8   612.3  4399.7  611.55
  4507.1  613.72  4683.2  613.39  4691.3   613.9    4713  613.38  4864.2  613.57
  4914.8   612.9  4955.3  613.64  4985.6   612.2  4992.4   610.8  4992.9   610.3
  4998.6   610.3  4999.1   610.8  5012.4  612.12  5039.8  614.07  5132.4  617.16
  5147.7  618.19  5235.5  620.84  5292.1  620.96  5323.5  622.36    5414  626.04
#Mann= 5 ,-1 , 0
  3568.8      .1       0  4992.4     .07       0  4999.1      .1       0
  5012.4     .05       0  5323.5      .1       0
Bank Sta=4992.4,4999.1
XS Rating Curve= 0 ,0
Exp/Cntr=0.3,0.1

Type RM Length L Ch R = 1 ,4100    ,419,419,419
BEGIN DESCRIPTION:
UNT 028 in BCW 2.0
END DESCRIPTION:
XS GIS Cut Line= 3
      1964165.68      13547734.5       1962828.9       13547524.
      1962403.57     13547602.12
#Sta/Elev= 30
  3823.8  627.05  3851.3  625.27  3996.6  619.73  4043.9  618.19  4048.9  618.53
  4067.4  617.16  4330.6  609.29  4684.2  611.81  4695.1  611.31  4826.7  611.94
  4881.8  611.37  4927.9  611.91  4944.4  611.52  4949.4   610.6  4978.5  610.43
  4988.7  607.67  4995.4  606.96  4995.9  606.46  5001.6  606.46  5002.1  606.96
  5006.9   608.1  5011.9  610.91  5029.2   611.9  5089.9  611.84  5231.9  614.19
  5313.2  616.73    5359  617.03  5441.9  619.66    5484  621.09  5609.5  623.64
#Mann= 5 ,-1 , 0
  3823.8      .1       0  4995.4     .07       0  5002.1      .1       0
    5359     .05       0  5441.9      .1       0
Bank Sta=4995.4,5002.1
XS Rating Curve= 0 ,0
Exp/Cntr=0.3,0.1

Type RM Length L Ch R = 1 ,3681    ,401,401,401
BEGIN DESCRIPTION:
Mapping XS 8c1543a0
END DESCRIPTION:
XS GIS Cut Line= 4
      1964259.06     13547424.17      1963503.81     13547408.98
      1962982.98     13547231.03      1962398.53      13547471.3
#Sta/Elev= 30
  4042.9  630.23    4137  626.76    4177  623.95    4217  622.72    4317  614.52
    4397  611.08  4547.1  608.72  4617.1  608.32  4627.1  609.14  4667.1  607.86
  4717.1  607.82  4795.2  609.45  4902.7  608.47  4934.4  608.97    4950   607.8
  4976.1  608.72  4987.3  606.43    5004  606.19  5004.5  605.69  5010.7  606.19
  5050.7  610.01  5106.6  609.68  5231.9   611.2  5411.4   611.8  5503.5  613.69
  5556.9   613.9  5616.8  615.95  5850.1  620.39  5924.8  623.03  5980.6     624
#Mann= 4 ,-1 , 0
  4042.9      .1       0    5004     .07       0  5010.7      .1       0
  5850.1     .05       0
Bank Sta=5004,5010.7
XS Rating Curve= 0 ,0
Exp/Cntr=0.3,0.1

Type RM Length L Ch R = 1 ,3280    ,640,640,640
BEGIN DESCRIPTION:
Mapping XS 90692db9
END DESCRIPTION:
XS GIS Cut Line= 4
      1964356.67     13547239.71       1963809.8     13547098.65
      1963013.36     13547137.71      1962394.85     13547456.73
#Sta/Elev= 30
  4147.6  627.56    4170  627.47    4201  625.05    4308  620.42  4343.5  616.94
  4348.7  617.56  4457.1  610.65  4521.1  606.47  4584.1  605.78  4584.6  605.28
  4590.9  605.78    4676  607.21  4898.4  607.57  4948.2   607.6  4967.5   606.2
  4997.5  606.05  5037.6  607.35  5145.4  607.24  5488.1  610.34  5757.9  613.87
  5879.2   616.6  5901.7  619.08  5907.4   621.5    5913  621.74  5923.9  620.29
  5929.5  617.98  5935.5  617.75  6074.7  620.26  6123.4   622.4  6205.7  623.81
#Mann= 6 ,-1 , 0
  4147.6      .1       0  4457.1     .05       0  4584.1     .07       0
  4590.9     .05       0  4898.4      .1       0  6074.7     .05       0
Bank Sta=4584.1,4590.9
XS Rating Curve= 0 ,0
Exp/Cntr=0.3,0.1

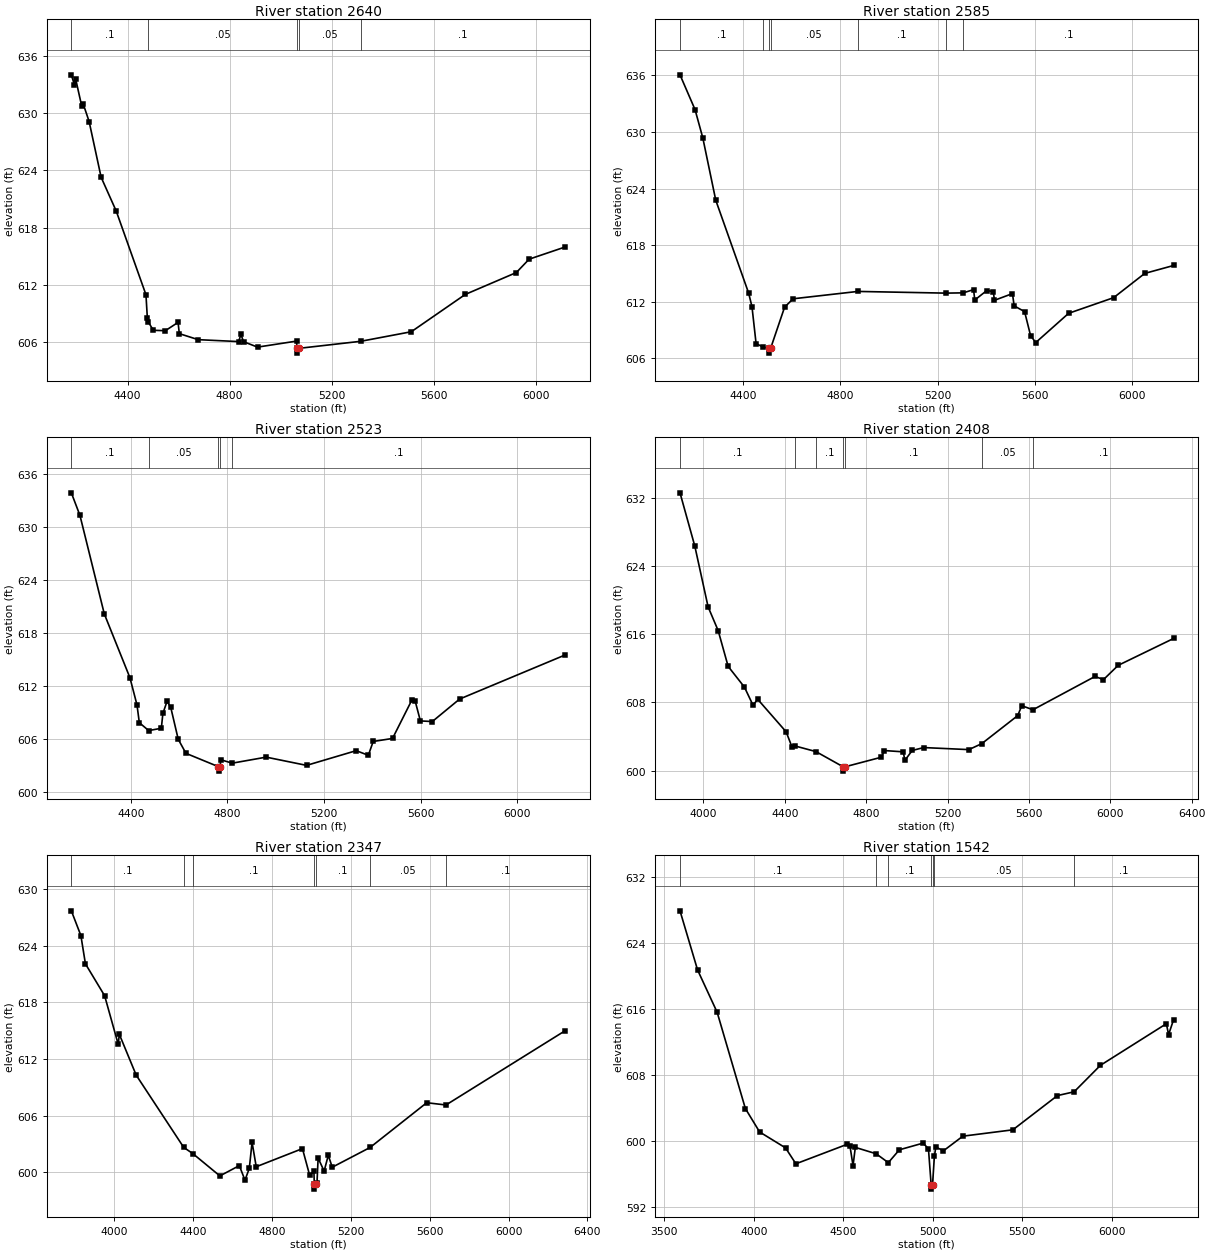
Type RM Length L Ch R = 1 ,2640    ,55,55,55
BEGIN DESCRIPTION:
Mapping XS a1650124
END DESCRIPTION:
XS GIS Cut Line= 4
      1964396.74     13546656.37      1964045.19     13546505.34
      1963102.48     13546627.73      1962608.84     13546973.28
#Sta/Elev= 30
  4179.5     634  4191.2  632.98  4196.7  633.53  4220.2  630.72  4225.7  630.98
  4249.2  629.11  4296.3  623.27  4355.5  619.73  4472.1  610.97  4477.5  608.56
  4481.4  608.11  4501.1  607.24  4548.2   607.2    4598  608.07    4603  606.89
  4677.1  606.26  4835.5  606.06  4844.7  606.81  4854.7  606.05  4909.6  605.48
  5062.9  606.11  5064.2  605.35  5064.7  604.85  5071.7  605.35  5314.6  606.09
  5512.7  607.09  5724.6     611  5924.7  613.29  5974.8  614.69  6115.3  615.96
#Mann= 5 ,-1 , 0
  4179.5      .1       0  4481.4     .05       0  5064.2    .033       0
  5071.7     .05       0  5314.6      .1       0
Bank Sta=5064.2,5071.7
XS Rating Curve= 0 ,0
Exp/Cntr=0.3,0.1

Type RM Length L Ch R = 1 ,2585    ,62,62,62
BEGIN DESCRIPTION:
Mapping XS b8c01732
END DESCRIPTION:
XS GIS Cut Line= 4
      1964433.21      13546606.9      1964016.54     13546455.86
      1963050.39     13546575.65      1962576.42     13546963.68
#Sta/Elev= 30
  4140.9  636.06  4202.8  632.37  4234.7  629.37  4287.9  622.77    4423  612.93
  4436.8  611.49  4453.7  607.57  4480.4  607.23  4505.9  607.06  4506.4  606.56
  4513.4  607.06  4570.9  611.43  4605.8  612.32  4872.1   613.1  5233.7  612.92
  5305.3  612.95  5347.8  613.29  5352.9  612.19  5401.9  613.19  5428.8  613.09
  5433.8  612.16  5507.7  612.87  5514.7  611.57  5557.6  610.96  5582.2  608.42
  5603.4  607.68  5738.6  610.78  5923.8  612.44  6051.6  615.01  6170.2  615.85
#Mann= 7 ,-1 , 0
  4140.9      .1       0  4480.4     .05       0  4505.9     .07       0
  4513.4     .05       0  4872.1      .1       0  5233.7     .05       0
  5305.3      .1       0
Bank Sta=4505.9,4513.4
XS Rating Curve= 0 ,0
Exp/Cntr=0.3,0.1

Type RM Length L Ch R = 1 ,2523    ,115,115,115
BEGIN DESCRIPTION:
Mapping XS 40dee076
END DESCRIPTION:
XS GIS Cut Line= 4
      1964404.57     13546573.05       1963993.1     13546401.17
      1963063.42     13546505.34      1962563.41     13546937.63
#Sta/Elev= 30
  4154.3  633.83    4190  631.27  4290.6  620.16  4396.7  612.95  4425.9  609.88
  4435.6  607.87  4474.3  606.98  4526.6  607.24  4533.1  608.92  4550.4  610.29
  4565.7  609.59  4596.5     606  4628.5  604.41  4763.1   602.9  4763.6   602.4
  4770.6   602.9  4771.9  603.69  4820.1   603.3  4960.6  603.98  5127.6  603.05
  5332.9  604.71  5383.2  604.19  5403.3  605.75  5483.3  606.09  5562.4  610.38
  5576.7  610.34  5598.6  608.07  5647.9     608  5760.9  610.54  6196.7  615.51
#Mann= 5 ,-1 , 0
  4154.3      .1       0  4474.3     .05       0  4763.1     .07       0
  4770.6     .05       0  4820.1      .1       0
Bank Sta=4763.1,4770.6
XS Rating Curve= 0 ,0
Exp/Cntr=0.3,0.1

Type RM Length L Ch R = 1 ,2408    ,61,61,61
BEGIN DESCRIPTION:
Mapping XS 931c154b
END DESCRIPTION:
XS GIS Cut Line= 6
      1964412.37     13546528.77      1964112.89     13546101.69
      1963810.81      13546169.4      1963480.08     13546401.17
        1962928.     13546414.19      1962538.14     13546921.01
#Sta/Elev= 30
  3884.5  632.55  3957.3  626.31  4022.7  619.19  4072.3   616.4  4121.2  612.22
  4201.3  609.79  4243.3  607.68  4266.7  608.36  4406.1  604.56  4434.7  602.81
  4449.7   602.9  4552.7  602.24  4687.2  600.45  4687.7  599.95  4694.7  600.45
  4874.5  601.58  4889.3  602.36  4981.7  602.21  4990.4  601.22  5026.2  602.37
  5082.8  602.71  5304.7  602.47  5368.2  603.17  5544.7  606.45  5564.8  607.61
  5619.9  607.14  5924.9  611.04  5966.5  610.67  6038.7  612.34  6311.2  615.49
#Mann= 7 ,-1 , 0
  3884.5      .1       0  4449.7     .05       0  4552.7      .1       0
  4687.2     .07       0  4694.7      .1       0  5368.2     .05       0
  5619.9      .1       0
Bank Sta=4687.2,4694.7
XS Rating Curve= 0 ,0
Exp/Cntr=0.3,0.1

Type RM Length L Ch R = 1 ,2347    ,805,805,805
BEGIN DESCRIPTION:
Mapping XS 98e2314f
END DESCRIPTION:
XS GIS Cut Line= 6
      1964584.25     13546310.03      1963901.96     13545997.52
      1963589.46     13546263.15      1963477.48     13546330.86
      1962896.75     13546364.71      1962540.01      13546885.5
#Sta/Elev= 30
  3781.3  627.69  3829.7  625.07  3852.7  622.08  3950.2   618.7  4019.2  613.55
  4024.7  614.62  4110.4  610.29  4351.5  602.64  4397.9  601.98    4535  599.62
  4633.8  600.71  4662.3  599.17  4684.3  600.41  4698.4  603.18  4719.5  600.59
    4954  602.51  4990.9  599.67  5012.2  600.11  5014.3  598.72  5014.8  598.22
  5021.8  598.72  5027.8  598.87  5033.6  601.51    5064  600.13  5085.2   601.8
  5105.3  600.54  5297.2  602.63  5584.8  607.37  5682.4  607.13  6286.1  614.98
#Mann= 7 ,-1 , 0
  3781.3      .1       0  4351.5     .05       0  4397.9      .1       0
  5014.3     .07       0  5021.8      .1       0  5297.2     .05       0
  5682.4      .1       0
Bank Sta=5014.3,5021.8
XS Rating Curve= 0 ,0
Exp/Cntr=0.3,0.1

Type RM Length L Ch R = 1 ,1542    ,892,892,892
BEGIN DESCRIPTION:
Mapping XS 5c4fde89
END DESCRIPTION:
XS GIS Cut Line= 4
      1964530.44      13546124.2       1963808.2     13545665.85
      1962884.59     13546030.43      1962496.49     13546851.67
#Sta/Elev= 30
  3587.7   627.9  3685.9  620.73  3795.2   615.6  3952.8  603.93  4032.4  601.09
  4177.2  599.16  4234.9  597.23  4521.8   599.6    4537  599.38  4554.1     597
  4566.8  599.22    4683  598.45  4751.2  597.37    4813  598.93  4945.6  599.74
  4975.3  599.05  4990.5  594.66    4991  594.16    4998  594.66  5008.4  598.12
  5016.3  599.26  5059.3  598.81  5167.4  600.58  5446.7  601.35  5695.5   605.5
  5788.9  605.96  5935.8  609.17  6303.8  614.21  6316.6   612.9  6344.4  614.71
#Mann= 7 ,-1 , 0
  3587.7      .1       0    4683     .05       0  4751.2      .1       0
  4990.5     .07       0    4998      .1       0  5008.4     .05       0
  5788.9      .1       0
Bank Sta=4990.5,4998
XS Rating Curve= 0 ,0
Exp/Cntr=0.3,0.1

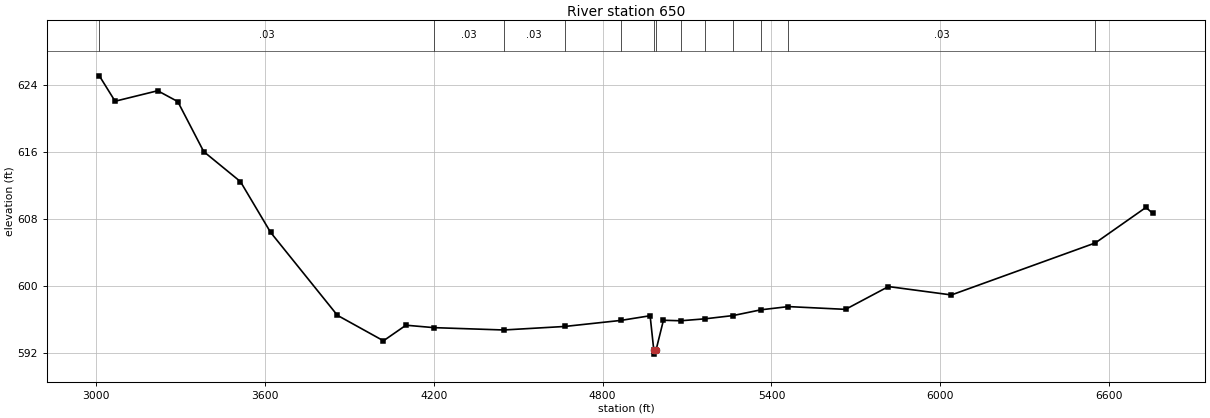
Type RM Length L Ch R = 1 ,650     ,0,0,0
BEGIN DESCRIPTION:
UNT 028 in BCW 1.0
END DESCRIPTION:
XS GIS Cut Line= 4
      1964937.38     13545881.14      1963796.74     13545073.83
      1962775.91     13545214.46      1962538.24     13546508.82
#Sta/Elev= 30
  3011.1  625.07  3067.1  622.04  3218.5  623.29  3289.8     622  3382.1  616.03
  3512.6  612.45  3619.7   606.4  3857.2   596.5  4020.9  593.46  4100.9  595.32
  4200.1  595.03  4448.2  594.75  4664.9  595.17  4864.3  595.89  4968.6  596.45
  4981.6  592.37  4982.1  591.87  4989.8  592.37  5015.9  595.91  5077.5  595.85
  5163.4  596.08  5263.2  596.47  5362.9  597.16  5460.2  597.54  5663.2  597.21
  5815.7  599.93  6039.4  598.93  6551.2  605.14  6730.8  609.37    6755  608.66
#Mann= 13 ,-1 , 0
  3011.1     .03       0  4200.1     .03       0  4448.2     .03       0
  4664.9     .03       0  4864.3     .03       0  4981.6     .03       0
  4989.8     .03       0  5077.5     .03       0  5163.4     .03       0
  5263.2     .03       0  5362.9     .03       0  5460.2     .03       0
  6551.2     .03       0
Bank Sta=4981.6,4989.8
XS Rating Curve= 0 ,0
Exp/Cntr=0.3,0.1
LCMann Table=0

Chan Stop Cuts=-1
Use User Specified Reach Order=0
Composite Channel Slope=5