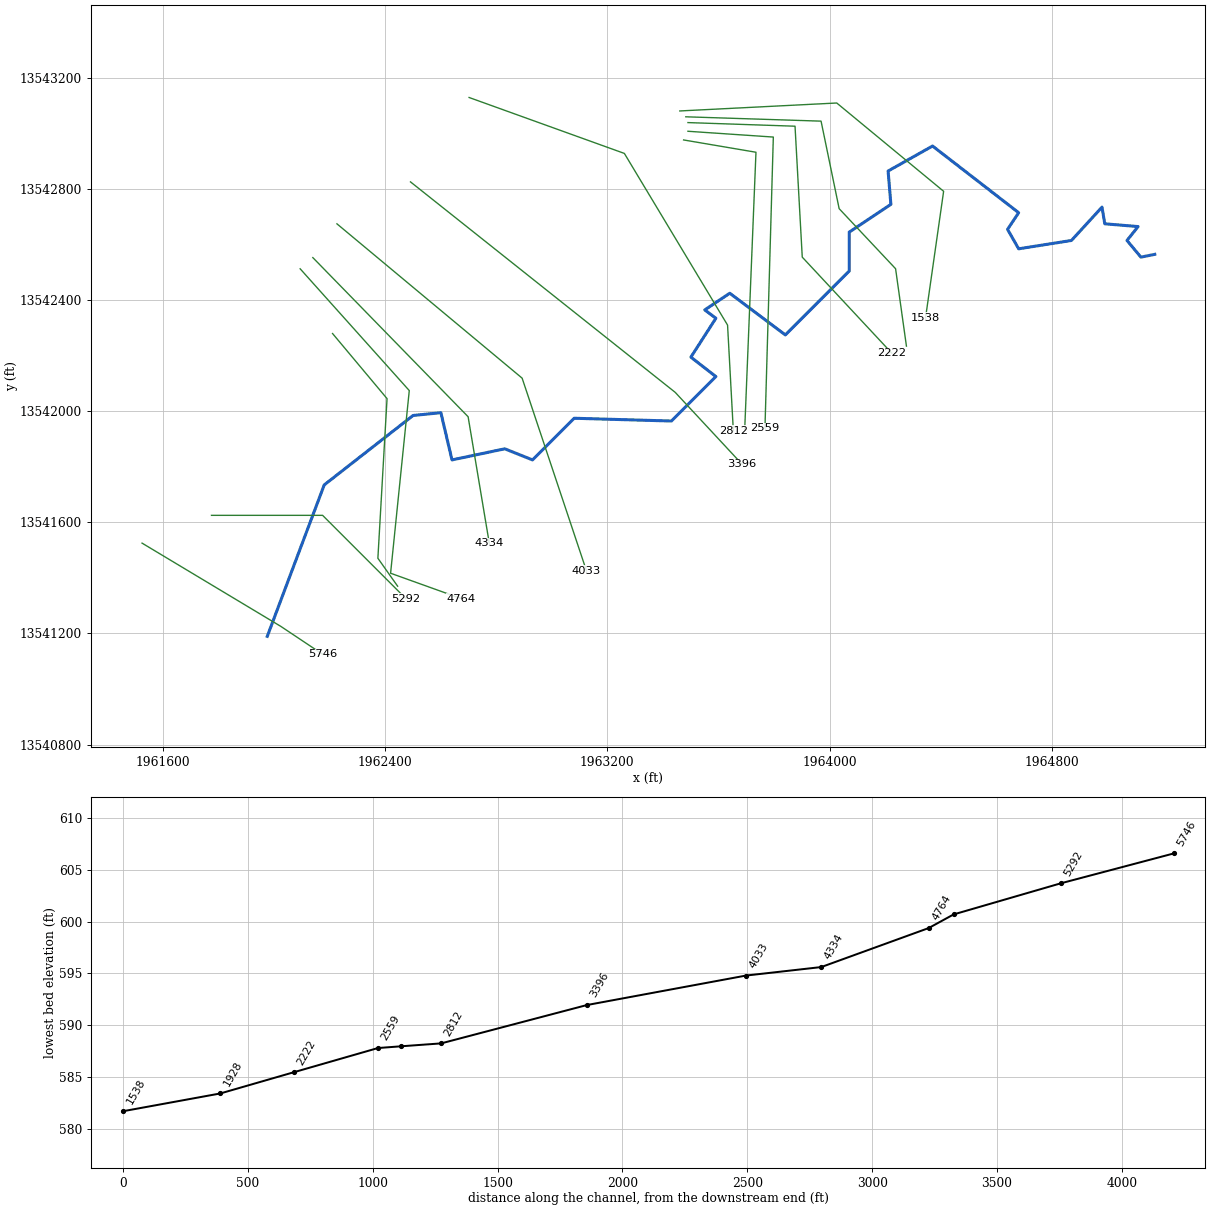
--- UNT 029 in BCW.prj (project) ---

Proj Title=UNT 029 in BCW Base Level Engineering
Current Plan=p01
Default Exp/Contr=0.3,0.1
English Units
Geom File=g01
Flow File=f01
Plan File=p01
BEGIN DESCRIPTION:
UNT 029 in BCW
END DESCRIPTION:

--- UNT 029 in BCW.p01 (plan) ---

Plan Title=Multiple Run
Short Identifier=Multiple
Geom File=g01
Flow File=f01
Subcritical Flow
K Sum by GR= 0
Std Step Tol= 0.01
Critical Tol= 0.01
Num of Std Step Trials= 20
Max Error Tol= 0.3
Flow Tol Ratio= 0.001
Split Flow NTrial= 30
Split Flow Tol= 0.02
Split Flow Ratio= 0.02
Log Output Level= 0
Friction Slope Method= 1
Unsteady Friction Slope Method= 2
Unsteady Bridges Friction Slope Method= 1
Parabolic Critical Depth
Global Vel Dist=  1 , 1 , 1
Global Log Level= 0
CheckData=True
Encroach Param= -1, 0, 0, 0
BEGIN DESCRIPTION:
Multiple Run
END DESCRIPTION:

--- UNT 029 in BCW.f01 (steady flow) ---

Flow Title=Multiple
Number of Profiles=7
Profile Names=10-year,25-year,50-year,1pct_min,100-year,1pct_plu,500-year
River Rch & RM= UNT 029 in BCW,Reach-1,5746
     176     245     302     187     372     743     576
River Rch & RM= UNT 029 in BCW,Reach-1,3396
     185     256     316     195     389     776     600
Boundary for River Rch & Prof#=UNT 029 in BCW,Reach-1,1
Up Type=0
Dn Type=3
Dn Slope=0.005
Boundary for River Rch & Prof#=UNT 029 in BCW,Reach-1,2
Up Type=0
Dn Type=3
Dn Slope=0.005
Boundary for River Rch & Prof#=UNT 029 in BCW,Reach-1,3
Up Type=0
Dn Type=3
Dn Slope=0.005
Boundary for River Rch & Prof#=UNT 029 in BCW,Reach-1,4
Up Type=0
Dn Type=3
Dn Slope=0.005
Boundary for River Rch & Prof#=UNT 029 in BCW,Reach-1,5
Up Type=0
Dn Type=3
Dn Slope=0.005
Boundary for River Rch & Prof#=UNT 029 in BCW,Reach-1,6
Up Type=0
Dn Type=3
Dn Slope=0.005
Boundary for River Rch & Prof#=UNT 029 in BCW,Reach-1,7
Up Type=0
Dn Type=3
Dn Slope=0.005

--- UNT 029 in BCW.g01 (geometry) ---

Geom Title=Existing Conditions

River Reach=UNT 029 in BCW,Reach-1
Reach XY= 30
      1961975.80     13541189.54      1962180.80     13541734.54
      1962500.80     13541984.54      1962600.80     13541994.54
      1962640.80     13541824.54      1962830.80     13541864.54
      1962930.80     13541824.54      1963080.80     13541974.54
      1963430.80     13541964.54      1963590.80     13542124.54
      1963500.80     13542194.54      1963590.80     13542334.54
      1963550.80     13542364.54      1963640.80     13542424.54
      1963840.80     13542274.54      1964070.80     13542504.54
      1964070.80     13542644.54      1964220.80     13542744.54
      1964210.80     13542864.54      1964370.80     13542954.54
      1964680.80     13542714.54      1964640.80     13542654.54
      1964680.80     13542584.54      1964870.80     13542614.54
      1964980.80     13542734.54      1964990.80     13542674.54
      1965110.80     13542664.54      1965070.80     13542614.54
      1965120.80     13542554.54      1965170.80     13542564.54

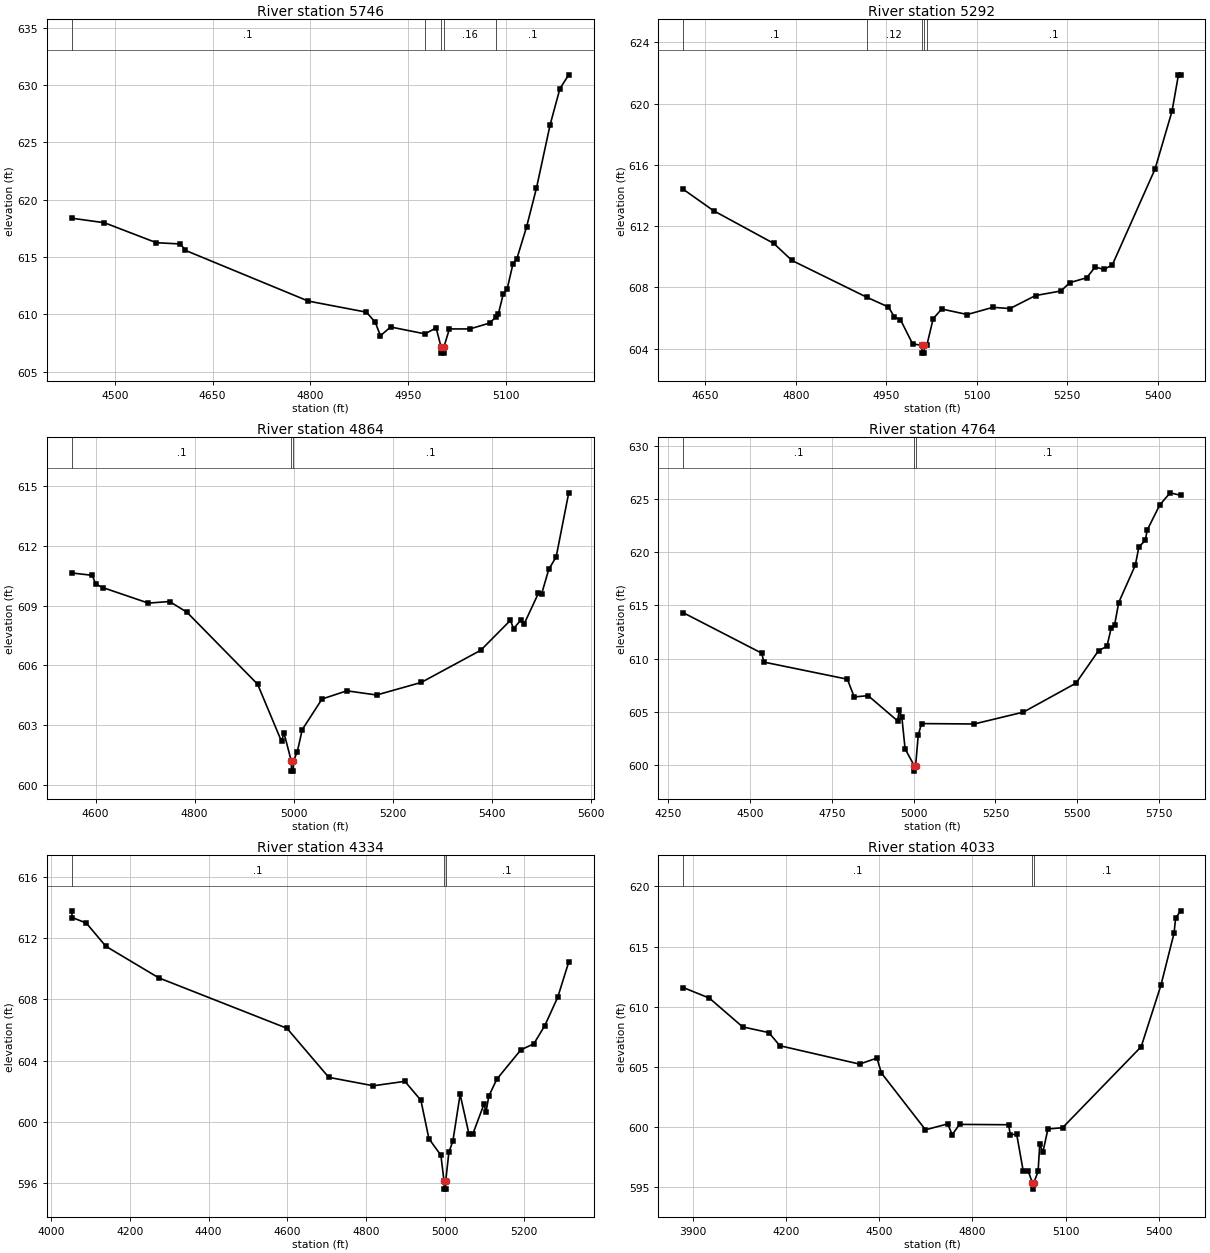
Type RM Length L Ch R = 1,5746,454,454,454
BEGIN DESCRIPTION:
UNT 029 in BCW 7.0
END DESCRIPTION:
XS GIS Cut Line= 3
      1961525.03     13541524.98      1962025.00     13541225.00
      1962174.97     13541125.02
#Sta/Elev= 30
  4433.5  618.38  4484.0  617.98  4563.7  616.24  4600.6  616.13  4608.4  615.57
  4796.9  611.15  4886.3  610.18  4899.9  609.29  4907.7  608.12  4923.3  608.89
  4976.1  608.29  4993.2  608.81  5001.0  607.11  5001.2  606.61  5004.7  606.61
  5005.0  607.11  5013.6  608.72  5045.1  608.72  5075.2  609.23  5085.7  609.79
  5088.7  610.01  5096.2  611.74  5102.2  612.18  5111.2  614.40  5117.2  614.85
  5132.2  617.64  5147.3  621.01  5168.3  626.54  5183.3  629.68  5196.8  630.88
#Mann=5,-1,0
  4433.5     0.1       0  4976.1    0.16       0  5001.0    0.07       0
  5005.0    0.16       0  5085.7     0.1       0
Bank Sta=5001,5005
Exp/Cntr=0.3,0.1

Type RM Length L Ch R = 1,5292,428,428,428
BEGIN DESCRIPTION:
UNT 029 in BCW 6.0
END DESCRIPTION:
XS GIS Cut Line= 3
      1961774.96     13541625.00      1962175.00     13541625.00
      1962475.00     13541325.00
#Sta/Elev= 30
  4613.7  614.40  4663.7  613.01  4763.7  610.87  4793.7  609.76  4917.8  607.36
  4953.7  606.72  4963.7  606.07  4973.7  605.89  4993.7  604.32  5009.2  604.21
  5009.5  603.71  5013.0  603.71  5013.2  604.21  5017.3  604.21  5027.9  605.96
  5042.0  606.59  5084.4  606.23  5126.9  606.70  5155.2  606.62  5197.6  607.47
  5240.0  607.77  5254.2  608.31  5282.4  608.63  5296.6  609.34  5310.7  609.17
  5324.9  609.47  5395.6  615.72  5423.9  619.51  5434.5  621.88  5438.0  621.88
#Mann=5,-1,0
  4613.7     0.1       0  4917.8    0.12       0  5009.2    0.07       0
  5013.2    0.12       0  5017.3     0.1       0
Bank Sta=5009.2,5013.2
Exp/Cntr=0.3,0.1

Type RM Length L Ch R = 1,4864,100,100,100
BEGIN DESCRIPTION:
Mapping XS 2a345bf9
END DESCRIPTION:
XS GIS Cut Line= 4
      1962210.82     13542279.54      1962406.98     13542045.19
      1962374.00     13541470.54      1962445.11     13541369.94
#Sta/Elev= 30
  4551.5  610.63  4593.5  610.51  4600.0  610.08  4614.3  609.90  4706.7  609.12
  4749.6  609.20  4784.8  608.66  4927.4  605.06  4975.7  602.20  4980.7  602.62
  4995.5  601.21  4995.8  600.71  4999.3  600.71  4999.5  601.21  5007.5  601.67
  5017.6  602.79  5057.6  604.32  5107.7  604.73  5167.8  604.52  5258.0  605.15
  5378.2  606.76  5438.2  608.26  5444.4  607.84  5459.1  608.27  5465.3  608.05
  5494.8  609.62  5501.0  609.57  5515.7  610.82  5530.5  611.43  5555.9  614.64
#Mann=3,-1,0
  4551.5     0.1       0  4995.5    0.07       0  4999.5     0.1       0
Bank Sta=4995.5,4999.5
Exp/Cntr=0.3,0.1

Type RM Length L Ch R = 1,4764,430,430,430
BEGIN DESCRIPTION:
UNT 029 in BCW 5.0
END DESCRIPTION:
XS GIS Cut Line= 4
      1962094.23     13542512.54      1962487.03     13542074.17
      1962419.75     13541416.62      1962675.01     13541324.99
#Sta/Elev= 30
  4295.6  614.31  4534.9  610.51  4542.4  609.66  4797.3  608.05  4818.2  606.38
  4860.8  606.50  4951.0  604.12  4956.0  605.13  4963.8  604.51  4973.8  601.49
  5002.0  599.89  5002.3  599.39  5006.0  599.89  5014.1  602.79  5024.1  603.87
  5184.9  603.83  5335.7  604.95  5496.6  607.68  5565.7  610.75  5591.2  611.14
  5603.9  612.83  5614.5  613.14  5627.2  615.27  5678.1  618.80  5688.9  620.51
  5708.8  621.14  5714.1  622.08  5752.6  624.46  5784.5  625.61  5816.4  625.38
#Mann=3,-1,0
  4295.6     0.1       0  5002.0    0.07       0  5006.0     0.1       0
Bank Sta=5002,5006
Exp/Cntr=0.3,0.1

Type RM Length L Ch R = 1,4334,301,301,301
BEGIN DESCRIPTION:
UNT 029 in BCW 4.0
END DESCRIPTION:
XS GIS Cut Line= 3
      1962139.83     13542552.88      1962698.83     13541979.99
      1962774.99     13541525.04
#Sta/Elev= 30
  4052.1  613.77  4054.2  613.33  4089.7  612.97  4139.1  611.46  4273.4  609.40
  4598.7  606.11  4704.9  602.91  4817.9  602.36  4898.1  602.65  4938.7  601.41
  4959.0  598.91  4989.4  597.83  4997.5  596.12  4997.8  595.62  5001.3  595.62
  5001.5  596.12  5009.7  598.03  5019.8  598.75  5038.2  601.80  5060.4  599.24
  5070.5  599.22  5098.9  601.17  5103.9  600.65  5111.1  601.69  5131.3  602.79
  5192.2  604.70  5225.3  605.10  5253.0  606.28  5286.0  608.14  5313.8  610.43
#Mann=3,-1,0
  4052.1     0.1       0  4997.5    0.07       0  5001.5     0.1       0
Bank Sta=4997.5,5001.5
Exp/Cntr=0.3,0.1

Type RM Length L Ch R = 1,4033,637,637,637
BEGIN DESCRIPTION:
UNT 029 in BCW 3.0
END DESCRIPTION:
XS GIS Cut Line= 3
      1962226.60     13542674.44      1962893.28     13542118.88
      1963125.01     13541424.96
#Sta/Elev= 30
  3869.9  611.58  3953.7  610.70  4060.4  608.31  4145.0  607.83  4180.2  606.74
  4436.6  605.21  4492.6  605.71  4506.9  604.47  4648.8  599.74  4720.4  600.23
  4734.7  599.33  4758.3  600.19  4916.3  600.16  4921.5  599.33  4942.1  599.38
  4963.2  596.30  4979.5  596.29  4992.8  595.30  4993.1  594.80  4996.8  595.30
  5011.1  596.28  5016.3  598.53  5026.5  597.88  5042.7  599.81  5089.7  599.91
  5342.7  606.66  5406.0  611.76  5448.2  616.09  5453.5  617.36  5469.3  617.97
#Mann=3,-1,0
  3869.9     0.1       0  4992.8    0.07       0  4996.8     0.1       0
Bank Sta=4992.8,4996.8
Exp/Cntr=0.3,0.1

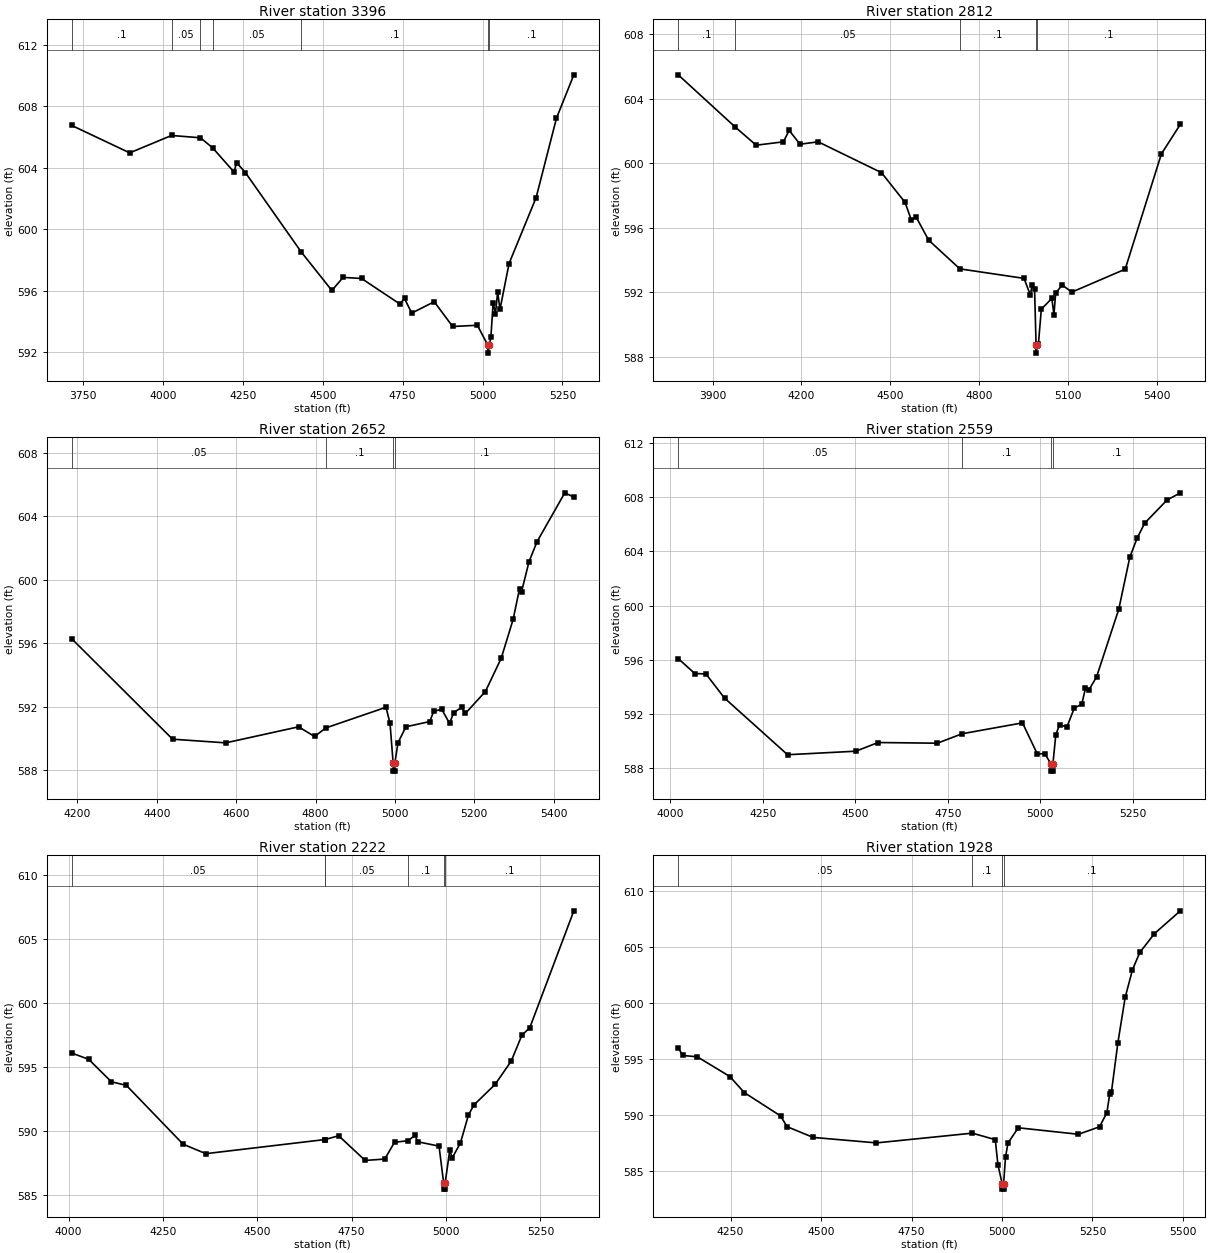
Type RM Length L Ch R = 1,3396,584,584,584
BEGIN DESCRIPTION:
UNT 029 in BCW 2.0
END DESCRIPTION:
XS GIS Cut Line= 3
      1962491.34     13542825.49      1963444.49     13542067.66
      1963685.43     13541808.59
#Sta/Elev= 30
  3714.3  606.74  3895.7  604.96  4026.6  606.09  4117.0  605.94  4155.5  605.28
  4222.4  603.71  4230.0  604.33  4257.7  603.68  4431.9  598.54  4528.4  596.02
  4563.6  596.87  4621.3  596.80  4741.4  595.14  4755.8  595.50  4778.3  594.55
  4848.8  595.29  4906.4  593.68  4983.8  593.76  5016.9  592.45  5017.2  591.95
  5021.0  592.45  5026.3  593.02  5033.1  595.23  5040.5  594.52  5047.3  595.93
  5054.6  594.79  5083.0  597.77  5167.8  602.06  5231.5  607.22  5285.8  610.03
#Mann=7,-1,0
  3714.3     0.1       0  4026.6    0.05       0  4117.0     0.1       0
  4155.5    0.05       0  4431.9     0.1       0  5016.9    0.07       0
  5021.0     0.1       0
Bank Sta=5016.9,5021
Exp/Cntr=0.3,0.1

Type RM Length L Ch R = 1,2812,160,160,160
BEGIN DESCRIPTION:
Mapping XS b05c3c7a
END DESCRIPTION:
XS GIS Cut Line= 4
      1962702.32     13543129.29      1963261.33     13542927.90
      1963632.86     13542309.85      1963653.64     13541928.93
#Sta/Elev= 30
  3783.5  605.48  3975.8  602.25  4046.9  601.12  4138.9  601.33  4158.4  602.04
  4195.0  601.18  4256.4  601.33  4470.4  599.42  4550.0  597.58  4571.4  596.48
  4586.9  596.69  4629.7  595.24  4735.3  593.46  4952.2  592.87  4973.5  591.84
  4979.4  592.44  4987.8  592.22  4992.8  588.74  4993.1  588.24  4997.0  588.74
  5000.8  588.82  5010.5  590.96  5046.1  591.63  5053.2  590.62  5059.0  591.95
  5081.1  592.46  5113.7  592.02  5294.0  593.44  5416.3  600.58  5480.3  602.41
#Mann=5,-1,0
  3783.5     0.1       0  3975.8    0.05       0  4735.3     0.1       0
  4992.8    0.07       0  4997.0     0.1       0
Bank Sta=4992.8,4997
Exp/Cntr=0.3,0.1

Type RM Length L Ch R = 1,2652,93,93,93
BEGIN DESCRIPTION:
Mapping XS 480e93fe
END DESCRIPTION:
XS GIS Cut Line= 3
      1963474.64     13542976.40      1963735.08     13542932.13
      1963694.49     13541932.23
#Sta/Elev= 30
  4185.8  596.29  4439.8  589.97  4573.7  589.74  4757.4  590.75  4797.4  590.14
  4825.8  590.68  4977.5  591.98  4987.6  590.96  4995.5  588.46  4995.8  587.96
  4999.4  587.96  4999.7  588.46  5007.6  589.74  5027.6  590.75  5087.6  591.08
  5097.6  591.72  5117.7  591.86  5137.7  590.96  5147.7  591.64  5167.7  591.97
  5177.7  591.60  5227.8  592.97  5267.8  595.07  5297.8  597.52  5313.9  599.45
  5318.9  599.25  5337.8  601.15  5357.9  602.40  5427.9  605.48  5450.7  605.21
#Mann=4,-1,0
  4185.8    0.05       0  4825.8     0.1       0  4995.5    0.07       0
  4999.7     0.1       0
Bank Sta=4995.5,4999.7
Exp/Cntr=0.3,0.1

Type RM Length L Ch R = 1,2559,337,337,337
BEGIN DESCRIPTION:
Mapping XS 0e946db5
END DESCRIPTION:
XS GIS Cut Line= 3
      1963490.27     13543007.65      1963797.58     13542986.82
      1963767.45     13541938.77
#Sta/Elev= 30
  4021.9  596.09  4066.7  594.99  4096.8  594.96  4146.9  593.18  4317.3  589.00
  4501.8  589.26  4561.8  589.90  4721.9  589.85  4789.3  590.55  4952.0  591.35
  4992.0  589.06  5012.0  589.08  5029.9  588.29  5030.2  587.79  5033.8  587.79
  5034.1  588.29  5042.0  590.47  5052.0  591.21  5072.0  591.05  5092.1  592.45
  5112.1  592.72  5122.1  593.89  5132.1  593.81  5152.1  594.74  5212.1  599.73
  5242.1  603.59  5262.1  605.00  5282.1  606.08  5342.2  607.78  5378.4  608.32
#Mann=4,-1,0
  4021.9    0.05       0  4789.3     0.1       0  5029.9    0.07       0
  5034.1     0.1       0
Bank Sta=5029.9,5034.1
Exp/Cntr=0.3,0.1

Type RM Length L Ch R = 1,2222,294,294,294
BEGIN DESCRIPTION:
Mapping XS 05cdbce0
END DESCRIPTION:
XS GIS Cut Line= 4
      1963490.25     13543038.90      1963875.71     13543025.88
      1963901.75     13542554.52      1964223.79     13542209.11
#Sta/Elev= 30
  4008.5  596.08  4053.3  595.59  4113.3  593.84  4153.3  593.55  4303.4  588.96
  4363.5  588.22  4678.5  589.32  4679.1  589.32  4715.5  589.62  4785.7  587.69
  4837.6  587.80  4863.5  589.11  4898.7  589.23  4917.9  589.64  4924.7  589.15
  4981.4  588.81  4993.5  585.95  4993.7  585.45  4997.4  585.45  4997.7  585.95
  5009.7  588.48  5016.6  587.90  5038.1  589.06  5059.1  591.22  5073.3  592.01
  5129.9  593.63  5172.4  595.44  5200.8  597.47  5221.8  598.06  5338.5  607.19
#Mann=6,-1,0
  4008.5    0.05       0  4678.5     0.1       0  4679.1    0.05       0
  4898.7     0.1       0  4993.5    0.07       0  4997.7     0.1       0
Bank Sta=4993.5,4997.7
Exp/Cntr=0.3,0.1

Type RM Length L Ch R = 1,1928,390,390,390
BEGIN DESCRIPTION:
Mapping XS aff4d8c3
END DESCRIPTION:
XS GIS Cut Line= 5
      1963482.46     13543059.73      1963969.46     13543044.11
      1964034.56     13542729.00      1964237.69     13542512.86
      1964276.75     13542234.20
#Sta/Elev= 30
  4105.6  596.01  4118.1  595.34  4158.2  595.22  4248.2  593.46  4288.2  592.02
  4388.3  589.94  4406.2  588.98  4478.3  588.02  4653.2  587.53  4918.1  588.40
  4981.4  587.82  4988.7  585.59  5000.3  583.90  5000.6  583.40  5004.3  583.40
  5004.5  583.90  5009.7  586.26  5016.6  587.52  5044.9  588.88  5211.2  588.30
  5269.6  588.97  5289.8  590.24  5297.4  591.86  5302.5  592.11  5320.1  596.47
  5340.3  600.53  5360.5  603.00  5380.7  604.54  5421.1  606.22  5492.6  608.26
#Mann=4,-1,0
  4105.6    0.05       0  4918.1     0.1       0  5000.3    0.07       0
  5004.5     0.1       0
Bank Sta=5000.3,5004.5
Exp/Cntr=0.3,0.1

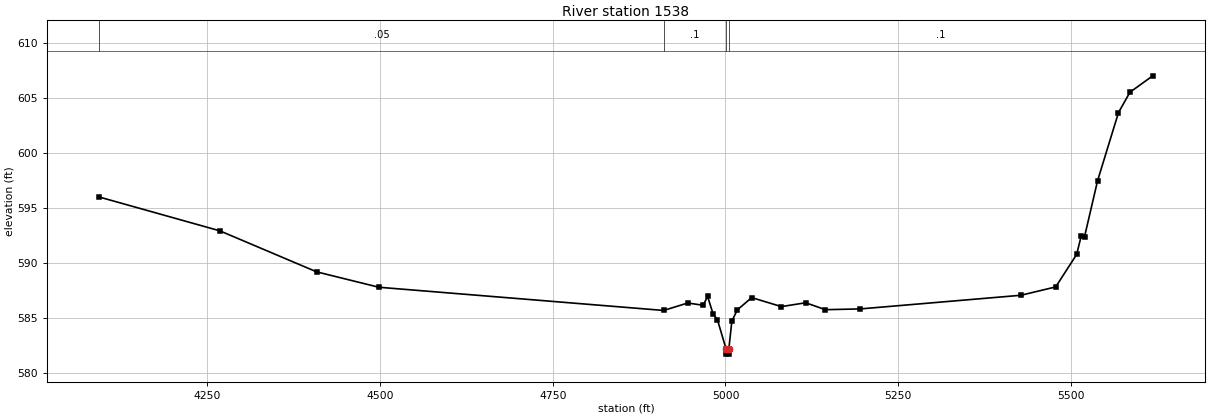
Type RM Length L Ch R = 1,1538,0,0,0
BEGIN DESCRIPTION:
UNT 029 in BCW 1.0
END DESCRIPTION:
XS GIS Cut Line= 4
      1963460.82     13543080.78      1964025.91     13543109.43
      1964410.64     13542791.62      1964345.53     13542335.87
#Sta/Elev= 30
  4093.4  595.96  4267.8  592.89  4408.0  589.16  4498.1  587.76  4910.4  585.65
  4945.4  586.33  4967.6  586.12  4974.1  586.92  4981.9  585.36  4988.4  584.79
  5000.7  582.18  5000.9  581.68  5004.6  581.68  5004.9  582.18  5009.2  584.68
  5017.1  585.70  5037.9  586.82  5080.9  586.00  5116.1  586.35  5144.7  585.72
  5195.2  585.79  5427.6  587.03  5478.1  587.79  5508.4  590.74  5514.9  592.39
  5519.9  592.37  5538.7  597.44  5569.0  603.64  5585.6  605.49  5618.6  606.98
#Mann=4,-1,0
  4093.4    0.05       0  4910.4     0.1       0  5000.7    0.07       0
  5004.9     0.1       0
Bank Sta=5000.7,5004.9
Exp/Cntr=0.3,0.1

Chan Stop Cuts=-1