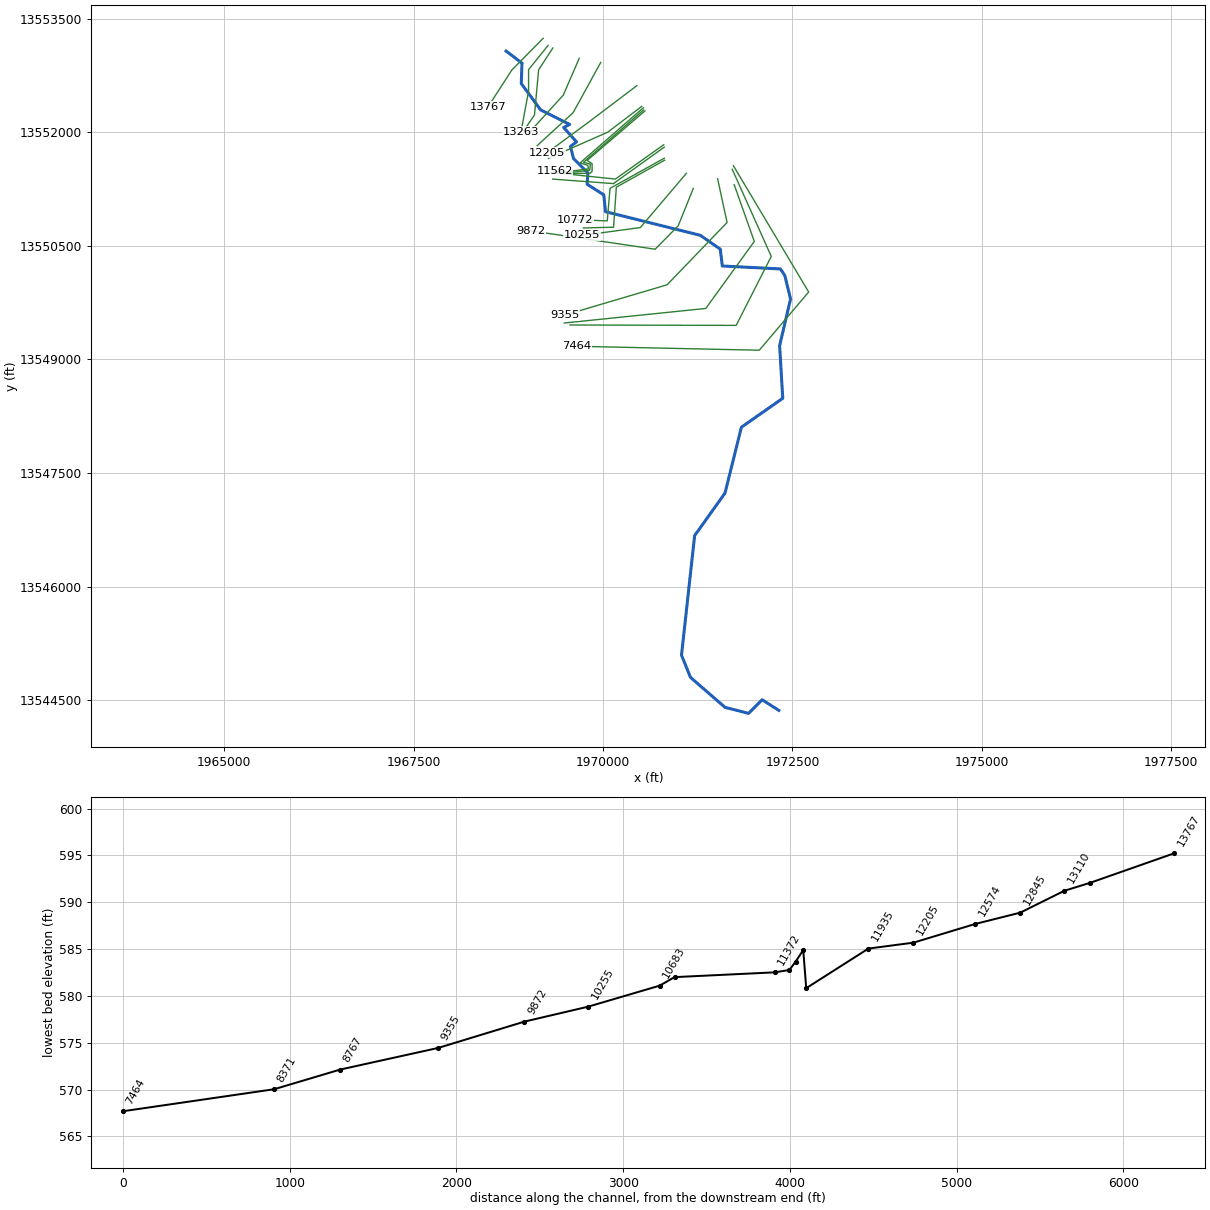
--- UNT 031 in BCW.prj (project) ---

Proj Title=UNT 031 in BCW Base Level Engineering
Current Plan=p01
Default Exp/Contr=0.3,0.1
English Units
Geom File=g01
Flow File=f01
Plan File=p01
BEGIN DESCRIPTION:
UNT 031 in BCW
END DESCRIPTION:

--- UNT 031 in BCW.p01 (plan) ---

Plan Title=Multiple Run
Short Identifier=Multiple
Geom File=g01
Flow File=f01
Subcritical Flow
K Sum by GR= 0
Std Step Tol= 0.01
Critical Tol= 0.01
Num of Std Step Trials= 20
Max Error Tol= 0.3
Flow Tol Ratio= 0.001
Split Flow NTrial= 30
Split Flow Tol= 0.02
Split Flow Ratio= 0.02
Log Output Level= 0
Friction Slope Method= 1
Unsteady Friction Slope Method= 2
Unsteady Bridges Friction Slope Method= 1
Parabolic Critical Depth
Global Vel Dist=  1 , 1 , 1
Global Log Level= 0
CheckData=True
Encroach Param= -1, 0, 0, 0
BEGIN DESCRIPTION:
Multiple Run
END DESCRIPTION:

--- UNT 031 in BCW.f01 (steady flow) ---

Flow Title=Multiple
Number of Profiles=7
Profile Names=10-year,25-year,50-year,1pct_min,100-year,1pct_plu,500-year
River Rch & RM= UNT 031 in BCW,Reach-1,13767
     729    1049    1322     823    1642    3277    2540
River Rch & RM= UNT 031 in BCW,Reach-1,12845
     750    1078    1357     845    1685    3362    2603
River Rch & RM= UNT 031 in BCW,Reach-1,7464
     817    1180    1489     928    1852    3696    2877
Boundary for River Rch & Prof#=UNT 031 in BCW,Reach-1,1
Up Type=0
Dn Type=3
Dn Slope=0.005
Boundary for River Rch & Prof#=UNT 031 in BCW,Reach-1,2
Up Type=0
Dn Type=3
Dn Slope=0.005
Boundary for River Rch & Prof#=UNT 031 in BCW,Reach-1,3
Up Type=0
Dn Type=3
Dn Slope=0.005
Boundary for River Rch & Prof#=UNT 031 in BCW,Reach-1,4
Up Type=0
Dn Type=3
Dn Slope=0.005
Boundary for River Rch & Prof#=UNT 031 in BCW,Reach-1,5
Up Type=0
Dn Type=3
Dn Slope=0.005
Boundary for River Rch & Prof#=UNT 031 in BCW,Reach-1,6
Up Type=0
Dn Type=3
Dn Slope=0.005
Boundary for River Rch & Prof#=UNT 031 in BCW,Reach-1,7
Up Type=0
Dn Type=3
Dn Slope=0.005

--- UNT 031 in BCW.g01 (geometry) ---

Geom Title=Existing Conditions

River Reach=UNT 031 in BCW,Reach-1
Reach XY= 30
      1968720.80     13553074.54      1968930.80     13552914.54
      1968921.36     13552644.81      1969177.44     13552296.50
      1969560.80     13552104.54      1969480.80     13552064.54
      1969650.80     13551874.54      1969570.80     13551814.54
      1969610.80     13551654.54      1969800.80     13551464.54
      1969790.80     13551314.54      1970010.80     13551174.54
      1970032.85     13550952.48      1971285.73     13550639.60
      1971548.31     13550457.31      1971575.44     13550234.87
      1972341.28     13550195.81      1972399.88     13550111.17
      1972475.83     13549798.67      1972331.88     13549181.27
      1972373.11     13548486.82      1971827.32     13548104.88
      1971610.80     13547234.54      1971210.04     13546672.60
      1971036.36     13545092.81      1971155.80     13544799.54
      1971610.80     13544404.54      1971920.80     13544324.54
      1972100.80     13544504.54      1972320.80     13544364.54

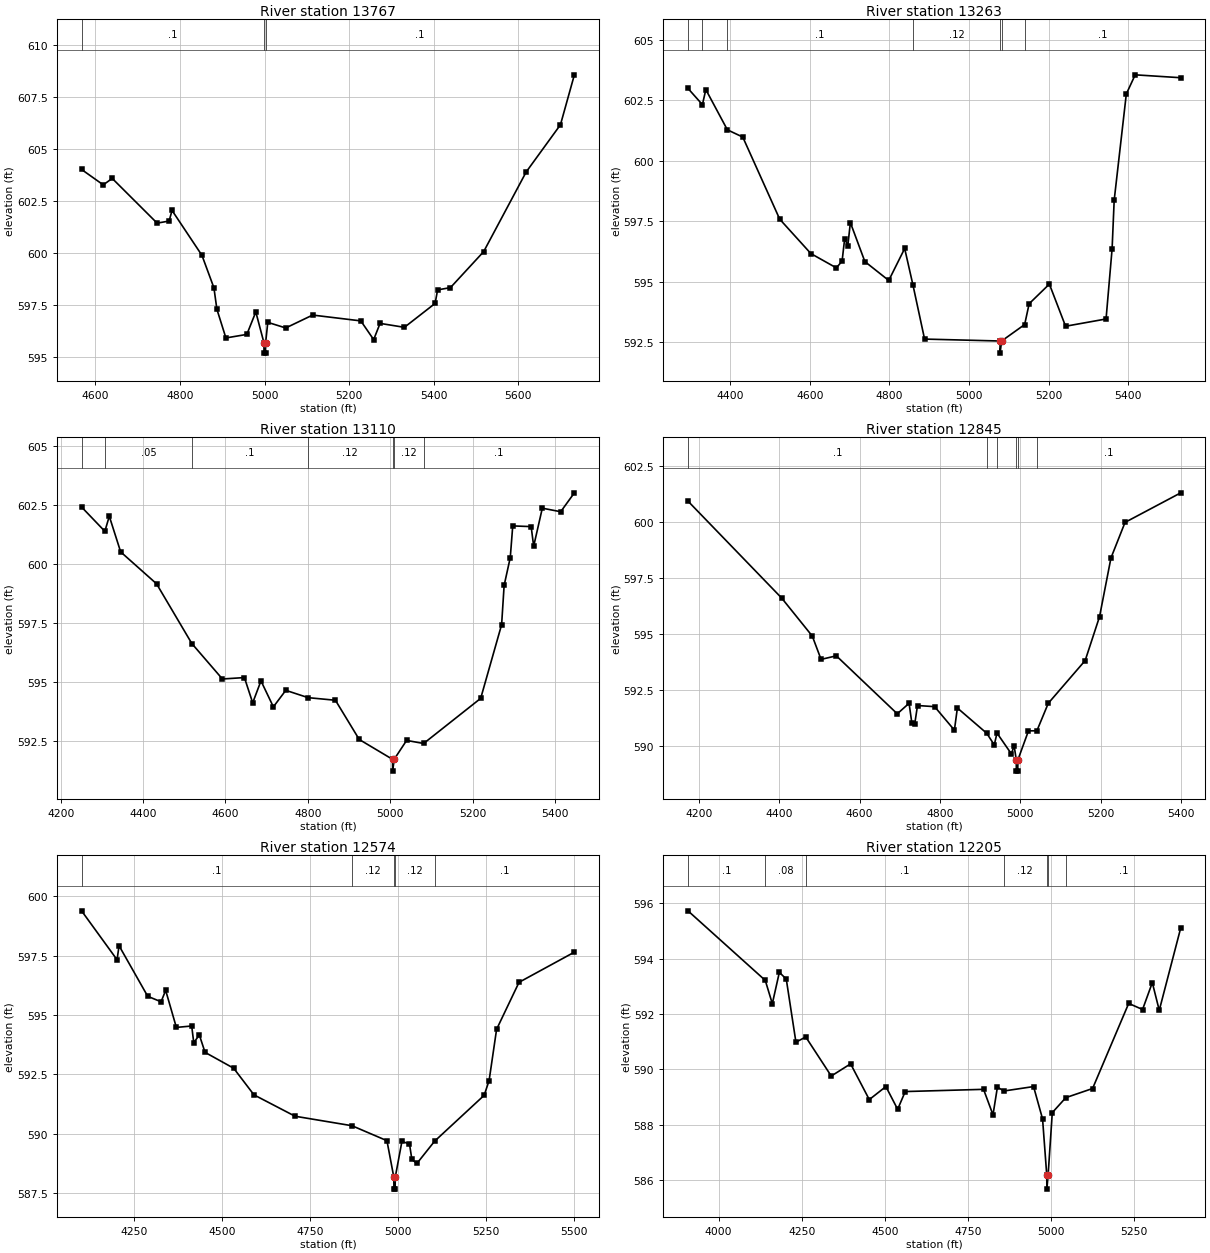
Type RM Length L Ch R = 1,13767,504,504,504
BEGIN DESCRIPTION:
UNT 031 in BCW 6.0
END DESCRIPTION:
XS GIS Cut Line= 3
      1969210.25     13553242.27      1968796.16     13552822.97
      1968484.11     13552339.30
#Sta/Elev= 30
  4567.5  604.04  4618.8  603.30  4640.0  603.61  4746.1  601.46  4774.4  601.56
  4781.4  602.07  4852.1  599.91  4880.4  598.35  4887.4  597.32  4908.7  595.94
  4958.2  596.11  4979.4  597.19  4998.6  595.71  4998.8  595.21  5002.3  595.21
  5002.6  595.71  5007.7  596.69  5050.1  596.42  5113.7  597.04  5227.6  596.76
  5258.0  595.86  5273.1  596.64  5330.6  596.45  5403.2  597.60  5409.1  598.25
  5439.5  598.36  5518.0  600.09  5618.5  603.92  5699.5  606.19  5732.4  608.59
#Mann=3,-1,0
  4567.5     0.1       0  4998.6    0.07       0  5002.6     0.1       0
Bank Sta=4998.6,5002.6
Exp/Cntr=0.3,0.1

Type RM Length L Ch R = 1,13263,153,153,153
BEGIN DESCRIPTION:
UNT 031 in BCW 5.0
END DESCRIPTION:
XS GIS Cut Line= 4
      1969275.34     13553148.51      1969017.51     13552828.18
      1969017.51     13552544.32      1968918.55     13552010.47
#Sta/Elev= 30
  4294.2  602.99  4330.5  602.32  4339.1  602.94  4393.2  601.28  4431.9  600.98
  4524.7  597.59  4603.0  596.17  4667.0  595.58  4681.4  595.86  4687.9  596.79
  4695.8  596.50  4702.2  597.45  4738.6  595.84  4798.6  595.06  4838.6  596.38
  4859.3  594.88  4888.6  592.64  5078.1  592.56  5078.3  592.06  5082.1  592.56
  5140.0  593.24  5151.3  594.10  5202.1  594.91  5242.8  593.17  5344.5  593.47
  5359.7  596.37  5364.9  598.37  5395.4  602.76  5417.7  603.55  5532.2  603.43
#Mann=7,-1,0
  4294.2     0.1       0  4330.5    0.05       0  4393.2     0.1       0
  4859.3    0.12       0  5078.1    0.07       0  5082.1    0.12       0
  5140.0     0.1       0
Bank Sta=5078.1,5082.1
Exp/Cntr=0.3,0.1

Type RM Length L Ch R = 1,13110,265,265,265
BEGIN DESCRIPTION:
Mapping XS 1e851150
END DESCRIPTION:
XS GIS Cut Line= 4
      1969337.81     13553114.62      1969150.32     13552825.57
      1969095.64     13552229.22      1968952.41     13552020.89
#Sta/Elev= 30
  4250.7  602.40  4307.3  601.37  4318.0  602.01  4345.6  600.50  4432.7  599.15
  4518.4  596.62  4592.6  595.12  4646.0  595.18  4666.1  594.11  4686.2  595.04
  4716.3  593.94  4746.4  594.64  4800.7  594.33  4866.9  594.22  4924.7  592.56
  5005.5  591.72  5005.8  591.22  5009.5  591.72  5039.7  592.52  5081.0  592.39
  5219.5  594.30  5270.3  597.42  5276.4  599.08  5291.3  600.26  5297.3  601.60
  5342.0  601.57  5348.1  600.74  5369.1  602.35  5413.7  602.20  5446.9  603.00
#Mann=7,-1,0
  4250.7     0.1       0  4307.3    0.05       0  4518.4     0.1       0
  4800.7    0.12       0  5005.5    0.07       0  5009.5    0.12       0
  5081.0     0.1       0
Bank Sta=5005.5,5009.5
Exp/Cntr=0.3,0.1

Type RM Length L Ch R = 1,12845,271,271,271
BEGIN DESCRIPTION:
Mapping XS bcdfddee
END DESCRIPTION:
XS GIS Cut Line= 3
      1969686.78     13552979.21      1969475.97     13552492.38
      1969007.19     13551976.72
#Sta/Elev= 30
  4172.5  600.94  4405.9  596.61  4482.2  594.91  4504.0  593.87  4542.0  594.03
  4693.8  591.44  4723.2  591.91  4730.0  591.04  4737.4  591.00  4744.2  591.81
  4786.8  591.76  4836.1  590.71  4843.5  591.70  4916.7  590.57  4935.4  590.05
  4942.2  590.58  4978.0  589.65  4984.8  590.02  4990.2  589.38  4990.4  588.88
  4993.9  588.88  4994.2  589.38  5020.6  590.68  5041.5  590.68  5069.9  591.91
  5161.8  593.82  5197.6  595.78  5226.0  598.40  5261.1  599.99  5399.9  601.31
#Mann=6,-1,0
  4172.5     0.1       0  4916.7    0.12       0  4942.2    0.07       0
  4990.2    0.07       0  4994.2    0.07       0  5041.5     0.1       0
Bank Sta=4990.2,4994.2
Exp/Cntr=0.3,0.1

Type RM Length L Ch R = 1,12574,369,369,369
BEGIN DESCRIPTION:
UNT 031 in BCW 4.0
END DESCRIPTION:
XS GIS Cut Line= 3
      1969970.66     13552924.57      1969606.05     13552260.47
      1969132.06     13551825.55
#Sta/Elev= 30
  4100.0  599.39  4200.9  597.33  4206.6  597.92  4288.1  595.79  4326.0  595.56
  4339.1  596.04  4369.5  594.48  4413.1  594.54  4418.9  593.84  4434.9  594.16
  4451.0  593.43  4532.5  592.76  4590.1  591.64  4706.9  590.74  4868.7  590.34
  4968.1  589.71  4987.7  588.17  4987.9  587.67  4991.4  587.67  4991.7  588.17
  5010.7  589.68  5032.2  589.57  5039.0  588.92  5053.2  588.75  5103.7  589.69
  5244.4  591.62  5258.5  592.24  5279.8  594.40  5343.6  596.38  5500.9  597.65
#Mann=5,-1,0
  4100.0     0.1       0  4868.7    0.12       0  4987.7    0.07       0
  4991.7    0.12       0  5103.7     0.1       0
Bank Sta=4987.7,4991.7
Exp/Cntr=0.3,0.1

Type RM Length L Ch R = 1,12205,270,270,270
BEGIN DESCRIPTION:
UNT 031 in BCW 3.0
END DESCRIPTION:
XS GIS Cut Line= 3
      1970447.23     13552617.26      1969803.97     13552130.26
      1969260.41     13551729.74
#Sta/Elev= 30
  3907.9  595.72  4140.4  593.21  4161.6  592.37  4182.7  593.50  4203.5  593.26
  4232.6  590.98  4262.1  591.17  4338.8  589.76  4397.0  590.20  4453.2  588.91
  4503.1  589.38  4538.5  588.56  4561.3  589.20  4796.8  589.28  4825.2  588.36
  4838.5  589.36  4858.0  589.22  4947.2  589.38  4974.3  588.21  4986.9  586.18
  4987.2  585.68  4990.9  586.18  5003.5  588.44  5044.2  588.98  5124.7  589.31
  5233.3  592.38  5275.0  592.16  5304.3  593.13  5325.2  592.13  5389.9  595.11
#Mann=7,-1,0
  3907.9     0.1       0  4140.4    0.08       0  4262.1     0.1       0
  4858.0    0.12       0  4986.9    0.07       0  4990.9    0.12       0
  5044.2     0.1       0
Bank Sta=4986.9,4990.9
Exp/Cntr=0.3,0.1

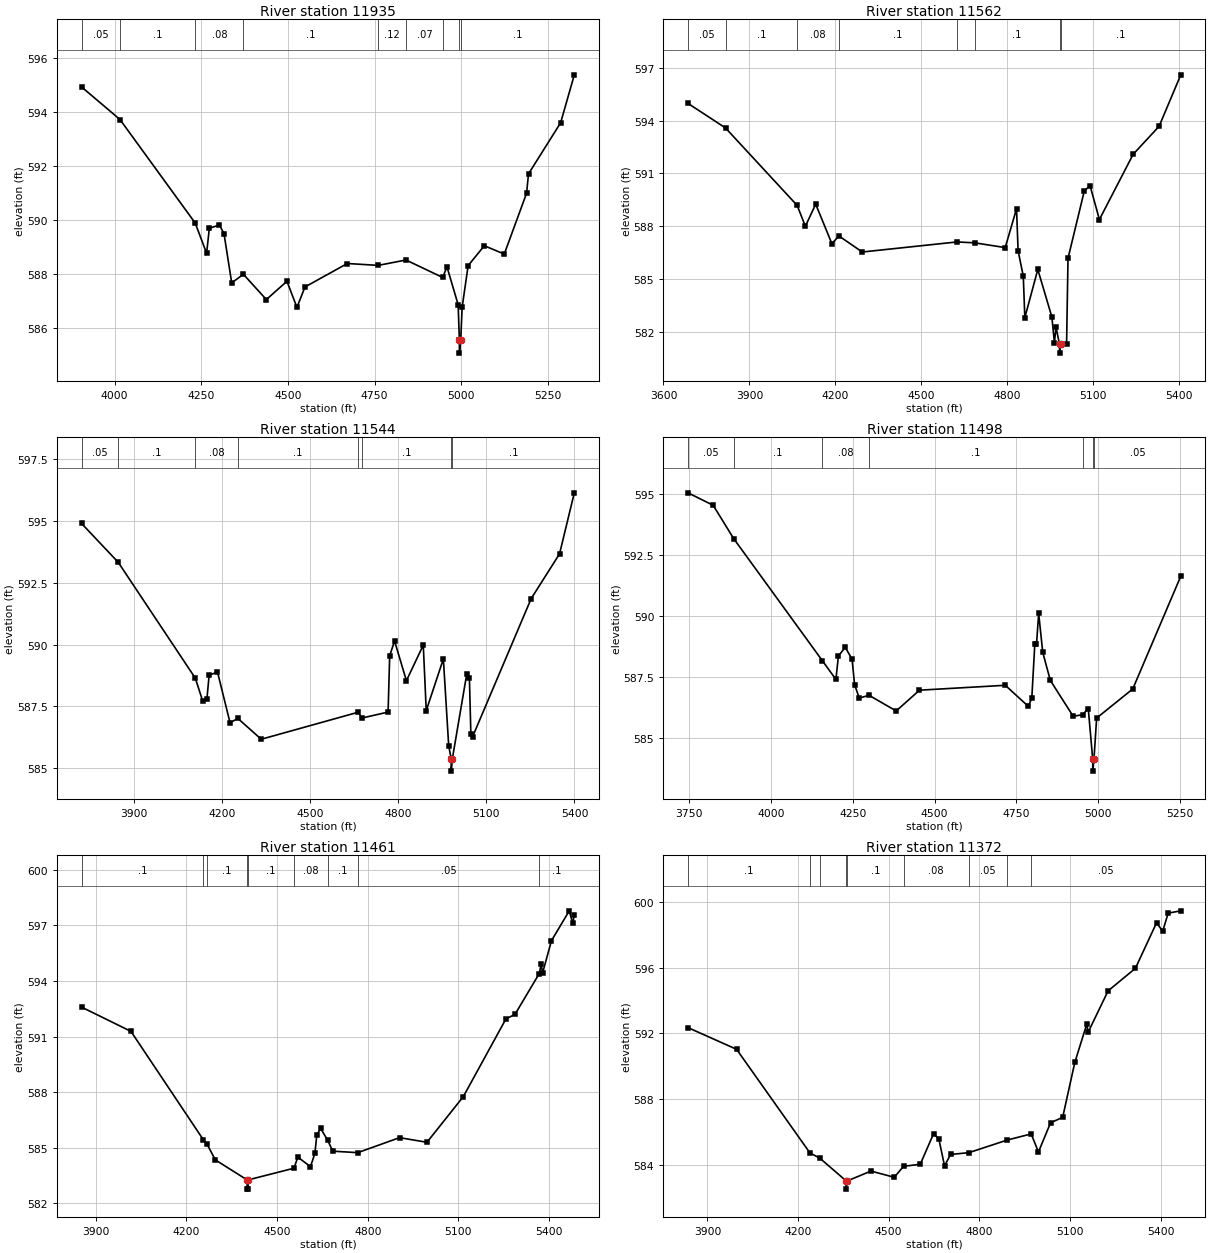
Type RM Length L Ch R = 1,11935,373,373,373
BEGIN DESCRIPTION:
Mapping XS 97e46dae
END DESCRIPTION:
XS GIS Cut Line= 3
      1970512.27     13552343.78      1970062.23     13552002.32
      1969278.98     13551656.77
#Sta/Elev= 30
  3904.8  594.94  4015.6  593.73  4232.7  589.88  4265.4  588.76  4273.3  589.69
  4302.4  589.81  4315.6  589.49  4337.8  587.66  4371.5  587.98  4437.7  587.04
  4497.1  587.72  4525.9  586.75  4549.2  587.51  4671.3  588.38  4760.2  588.31
  4840.4  588.51  4946.4  587.86  4958.5  588.26  4990.8  586.85  4994.3  585.55
  4994.5  585.05  4998.3  585.55  5002.3  586.75  5019.6  588.30  5066.2  589.04
  5123.8  588.73  5188.1  590.99  5193.7  591.71  5286.4  593.61  5325.8  595.39
#Mann=9,-1,0
  3904.8    0.05       0  4015.6     0.1       0  4232.7    0.08       0
  4371.5     0.1       0  4760.2    0.12       0  4840.4    0.07       0
  4946.4     0.1       0  4994.3    0.07       0  4998.3     0.1       0
Bank Sta=4994.3,4998.3
Exp/Cntr=0.3,0.1

Type RM Length L Ch R = 1,11562,18,18,18
BEGIN DESCRIPTION:
Mapping XS 9cb190f0
END DESCRIPTION:
XS GIS Cut Line= 6
      1970533.57     13552325.22      1969697.65     13551596.07
      1969799.21     13551564.82      1969809.63     13551517.94
      1969468.48     13551473.67      1969359.57     13551484.05
#Sta/Elev= 30
  3685.7  594.97  3816.6  593.58  4066.8  589.19  4095.5  588.01  4131.6  589.26
  4188.1  587.02  4212.6  587.46  4294.2  586.55  4624.7  587.12  4686.6  587.07
  4793.4  586.80  4832.9  589.00  4838.4  586.62  4856.5  585.18  4861.9  582.83
  4907.2  585.56  4956.3  582.87  4965.2  581.42  4970.8  582.29  4983.0  581.32
  4983.2  580.82  4987.0  581.32  5007.7  581.33  5012.7  586.19  5069.6  590.01
  5089.7  590.31  5122.3  588.39  5240.3  592.09  5330.7  593.67  5406.5  596.59
#Mann=8,-1,0
  3685.7    0.05       0  3816.6     0.1       0  4066.8    0.08       0
  4212.6     0.1       0  4624.7    0.07       0  4686.6     0.1       0
  4983.0    0.07       0  4987.0     0.1       0
Bank Sta=4983,4987
Exp/Cntr=0.3,0.1

Type RM Length L Ch R = 1,11544,46,46,46
BEGIN DESCRIPTION:
Mapping XS e66e6729
END DESCRIPTION:
XS GIS Cut Line= 6
      1970536.16     13552296.56      1969741.92     13551603.88
      1969833.07     13551580.44      1969825.26     13551499.71
      1969523.17     13551463.26      1969380.02     13551473.67
#Sta/Elev= 30
  3721.5  594.90  3846.3  593.33  4108.9  588.64  4134.4  587.70  4148.3  587.79
  4155.9  588.76  4184.4  588.89  4227.1  586.84  4253.9  587.01  4333.4  586.17
  4662.6  587.26  4677.1  587.03  4765.3  587.27  4770.7  589.54  4787.2  590.15
  4827.7  588.54  4885.1  589.98  4895.2  587.33  4953.5  589.42  4971.7  585.90
  4980.1  585.38  4980.3  584.88  4984.1  585.38  5033.0  588.80  5042.2  588.64
  5047.2  586.37  5053.3  586.28  5252.5  591.86  5349.1  593.67  5399.4  596.14
#Mann=8,-1,0
  3721.5    0.05       0  3846.3     0.1       0  4108.9    0.08       0
  4253.9     0.1       0  4662.6    0.07       0  4677.1     0.1       0
  4980.1    0.07       0  4984.1     0.1       0
Bank Sta=4980.1,4984.1
Exp/Cntr=0.3,0.1

Type RM Length L Ch R = 1,11498,37,37,37
BEGIN DESCRIPTION:
Mapping XS 0f72b448
END DESCRIPTION:
XS GIS Cut Line= 6
      1970554.43     13552283.57      1969791.40     13551629.92
      1969856.51     13551585.65      1969856.51     13551484.09
      1969830.46     13551460.65      1969548.31     13551455.36
#Sta/Elev= 30
  3745.8  595.03  3822.8  594.52  3885.4  593.16  4156.5  588.17  4198.2  587.40
  4205.9  588.36  4226.7  588.71  4247.6  588.23  4255.3  587.19  4269.5  586.64
  4299.7  586.75  4382.6  586.11  4453.9  586.96  4716.3  587.16  4786.7  586.30
  4797.5  586.64  4806.6  588.83  4811.8  588.83  4818.5  590.10  4830.9  588.51
  4854.1  587.36  4924.2  585.89  4952.9  585.96  4970.2  586.21  4983.7  584.15
  4984.0  583.65  4987.7  584.15  4995.8  585.82  5106.3  587.01  5253.2  591.62
#Mann=7,-1,0
  3745.8    0.05       0  3885.4     0.1       0  4156.5    0.08       0
  4299.7     0.1       0  4952.9    0.05       0  4983.7    0.04       0
  4987.7    0.05       0
Bank Sta=4983.7,4987.7
Exp/Cntr=0.3,0.1

Type RM Length L Ch R = 1,11461,89,89,89
BEGIN DESCRIPTION:
Mapping XS cd7e62d8
END DESCRIPTION:
XS GIS Cut Line= 3
      1970801.37     13551835.99      1970163.34     13551382.86
      1969319.84     13551471.38
#Sta/Elev= 30
  3852.9  592.59  4016.4  591.28  4255.8  585.43  4267.8  585.20  4295.6  584.34
  4400.6  583.26  4400.8  582.76  4404.3  582.76  4404.6  583.26  4555.9  583.89
  4568.7  584.49  4610.5  583.97  4625.2  584.70  4631.4  585.68  4643.9  586.04
  4667.8  585.39  4684.1  584.81  4767.0  584.73  4905.3  585.54  4996.0  585.29
  5116.4  587.76  5257.2  591.95  5287.4  592.20  5367.5  594.40  5373.7  594.90
  5378.7  594.44  5408.0  596.18  5466.9  597.79  5478.4  597.11  5483.6  597.58
#Mann=9,-1,0
  3852.9     0.1       0  4255.8    0.05       0  4267.8     0.1       0
  4400.6    0.04       0  4404.6     0.1       0  4555.9    0.08       0
  4667.8     0.1       0  4767.0    0.05       0  5367.5     0.1       0
Bank Sta=4400.6,4404.6
Exp/Cntr=0.3,0.1

Type RM Length L Ch R = 1,11372,600,600,600
BEGIN DESCRIPTION:
UNT 031 in BCW 2.0
END DESCRIPTION:
XS GIS Cut Line= 3
      1970809.18     13551804.74      1970137.30     13551322.97
      1969335.19     13551382.87
#Sta/Elev= 30
  3835.8  592.34  3996.6  591.02  4239.5  584.71  4271.7  584.40  4359.3  583.01
  4359.6  582.51  4363.3  583.01  4441.2  583.61  4518.5  583.23  4549.2  583.90
  4604.5  584.02  4648.7  585.89  4666.2  585.55  4684.9  583.93  4705.0  584.62
  4765.6  584.73  4892.8  585.50  4971.7  585.87  4995.8  584.77  5035.9  586.55
  5076.0  586.88  5116.1  590.22  5155.5  592.54  5160.5  592.07  5226.4  594.58
  5316.7  595.95  5386.9  598.73  5406.9  598.20  5425.2  599.31  5466.9  599.45
#Mann=9,-1,0
  3835.8     0.1       0  4239.5    0.05       0  4271.7     0.1       0
  4359.3    0.04       0  4363.3     0.1       0  4549.2    0.08       0
  4765.6    0.05       0  4892.8     0.1       0  4971.7    0.05       0
Bank Sta=4359.3,4363.3
Exp/Cntr=0.3,0.1

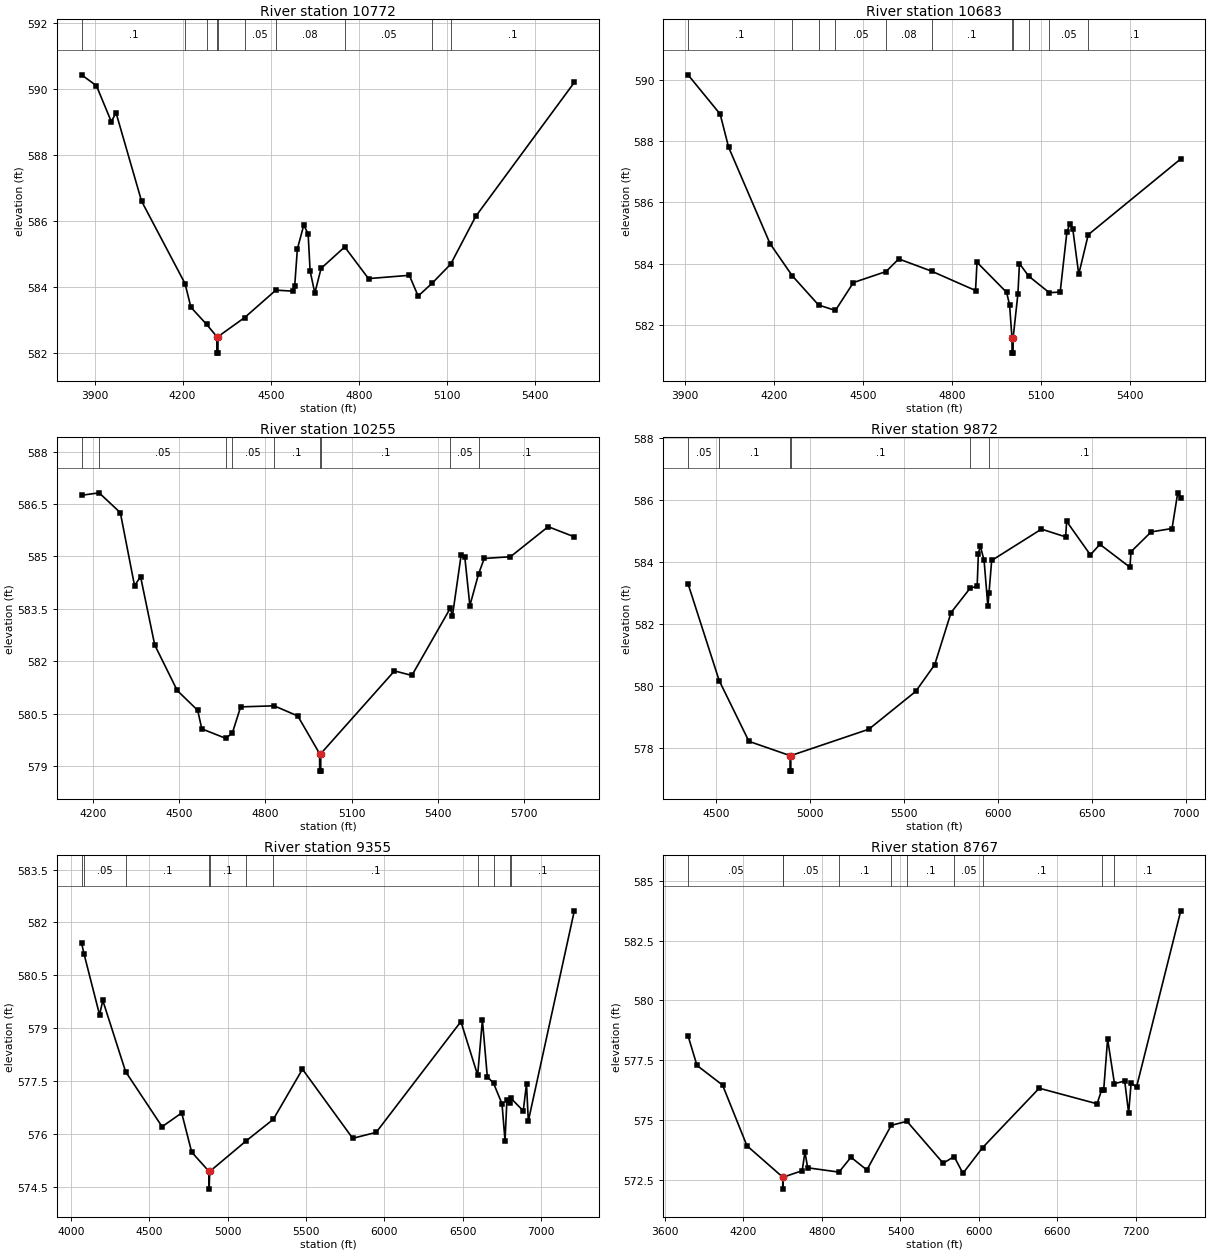
Type RM Length L Ch R = 1,10772,89,89,89
BEGIN DESCRIPTION:
Mapping XS b1a9cdde
END DESCRIPTION:
XS GIS Cut Line= 4
      1970809.20     13551658.92      1970093.03     13551260.47
      1970056.57     13550830.78      1969629.74     13550846.40
#Sta/Elev= 30
  3855.9  590.44  3906.5  590.11  3957.2  589.02  3973.3  589.29  4060.2  586.61
  4208.2  584.11  4228.3  583.39  4281.9  582.87  4316.5  582.50  4316.7  582.00
  4320.2  582.00  4320.5  582.50  4411.5  583.08  4517.5  583.91  4574.8  583.88
  4581.7  584.04  4590.8  585.16  4612.5  585.88  4627.4  585.62  4634.2  584.49
  4650.2  583.82  4671.5  584.57  4752.0  585.22  4833.0  584.26  4972.0  584.36
  5002.1  583.73  5049.6  584.12  5113.0  584.70  5198.3  586.15  5533.8  590.21
#Mann=10,-1,0
  3855.9     0.1       0  4208.2    0.05       0  4281.9     0.1       0
  4316.5    0.04       0  4320.5     0.1       0  4411.5    0.05       0
  4517.5    0.08       0  4752.0    0.05       0  5049.6    0.08       0
  5113.0     0.1       0
Bank Sta=4316.5,4320.5
Exp/Cntr=0.3,0.1

Type RM Length L Ch R = 1,10683,428,428,428
BEGIN DESCRIPTION:
Mapping XS d3c55dd4
END DESCRIPTION:
XS GIS Cut Line= 4
      1970814.35     13551632.85      1970176.36     13551276.09
      1970139.91     13550747.45      1969741.50     13550737.03
#Sta/Elev= 30
  3911.5  590.16  4019.7  588.88  4048.2  587.80  4187.6  584.66  4262.6  583.61
  4350.9  582.66  4407.8  582.48  4468.5  583.39  4578.7  583.75  4621.1  584.16
  4732.0  583.76  4879.7  583.13  4884.7  584.05  4984.4  583.07  4994.4  582.66
  5002.4  581.59  5002.7  581.09  5006.2  581.09  5006.4  581.59  5022.5  583.03
  5027.6  584.01  5058.7  583.60  5128.1  583.06  5164.8  583.08  5187.3  585.03
  5197.3  585.31  5207.3  585.13  5227.3  583.66  5259.3  584.95  5570.9  587.42
#Mann=11,-1,0
  3911.5     0.1       0  4262.6    0.05       0  4350.9     0.1       0
  4407.8    0.05       0  4578.7    0.08       0  4732.0     0.1       0
  5002.4    0.07       0  5006.4     0.1       0  5058.7    0.08       0
  5128.1    0.05       0  5259.3     0.1       0
Bank Sta=5002.4,5006.4
Exp/Cntr=0.3,0.1

Type RM Length L Ch R = 1,10255,383,383,383
BEGIN DESCRIPTION:
Mapping XS db077328
END DESCRIPTION:
XS GIS Cut Line= 3
      1971100.85     13551458.82      1970493.20     13550742.67
      1969724.93     13550638.50
#Sta/Elev= 30
  4160.3  586.75  4221.5  586.82  4295.3  586.25  4344.7  584.16  4365.6  584.42
  4415.0  582.46  4493.2  581.16  4564.4  580.59  4578.7  580.06  4661.9  579.79
  4684.9  579.94  4713.8  580.69  4830.4  580.72  4912.6  580.43  4988.6  579.35
  4988.9  578.85  4992.4  578.85  4992.7  579.35  5249.1  581.72  5309.6  581.59
  5442.9  583.51  5450.9  583.30  5481.2  585.05  5493.9  584.97  5511.4  583.59
  5541.8  584.50  5561.4  584.94  5652.7  584.99  5783.9  585.85  5874.8  585.56
#Mann=9,-1,0
  4160.3     0.1       0  4221.5    0.05       0  4661.9     0.1       0
  4684.9    0.05       0  4830.4     0.1       0  4988.6    0.07       0
  4992.7     0.1       0  5442.9    0.05       0  5541.8     0.1       0
Bank Sta=4988.6,4992.7
Exp/Cntr=0.3,0.1

Type RM Length L Ch R = 1,9872,517,517,517
BEGIN DESCRIPTION:
Mapping XS 21df0e54
END DESCRIPTION:
XS GIS Cut Line= 4
      1971191.98     13551259.14      1970992.34     13550764.37
      1970688.52     13550456.21      1969048.98     13550699.11
#Sta/Elev= 30
  4350.5  583.29  4516.3  580.17  4674.8  578.21  4893.8  577.75  4894.1  577.25
  4897.7  577.25  4897.9  577.75  5313.1  578.60  5562.9  579.82  5664.0  580.68
  5751.0  582.36  5853.1  583.15  5890.0  583.21  5896.5  584.26  5906.7  584.51
  5926.9  584.04  5947.1  582.56  5953.0  582.98  5967.3  584.04  6232.4  585.05
  6361.3  584.80  6366.4  585.30  6493.0  584.22  6543.5  584.56  6703.8  583.82
  6708.8  584.32  6816.5  584.96  6927.7  585.07  6958.0  586.22  6974.2  586.04
#Mann=6,-1,0
  4350.5    0.05       0  4516.3     0.1       0  4893.8    0.07       0
  4897.9     0.1       0  5853.1    0.05       0  5953.0     0.1       0
Bank Sta=4893.8,4897.9
Exp/Cntr=0.3,0.1

Type RM Length L Ch R = 1,9355,588,588,588
BEGIN DESCRIPTION:
Mapping XS 7a8d20e8
END DESCRIPTION:
XS GIS Cut Line= 4
      1971513.23     13551387.54      1971638.23     13550809.41
      1970846.56     13549986.50      1969492.38     13549585.45
#Sta/Elev= 30
  4067.4  581.42  4083.1  581.11  4182.5  579.38  4203.0  579.79  4348.7  577.77
  4581.6  576.21  4706.6  576.60  4770.4  575.49  4881.5  574.94  4881.8  574.44
  4885.6  574.94  5118.8  575.81  5291.8  576.42  5477.6  577.84  5798.4  575.88
  5948.4  576.05  6489.1  579.19  6596.1  577.67  6626.3  579.24  6657.6  577.63
  6697.7  577.44  6751.5  576.86  6770.8  575.81  6782.8  576.96  6801.0  576.87
  6807.4  577.02  6887.1  576.66  6907.9  577.42  6919.5  576.37  7213.1  582.33
#Mann=11,-1,0
  4067.4     0.1       0  4083.1    0.05       0  4348.7     0.1       0
  4881.5    0.07       0  4885.6     0.1       0  5118.8    0.05       0
  5291.8     0.1       0  6596.1    0.08       0  6697.7     0.1       0
  6801.0    0.12       0  6807.4     0.1       0
Bank Sta=4881.5,4885.6
Exp/Cntr=0.3,0.1

Type RM Length L Ch R = 1,8767,396,396,396
BEGIN DESCRIPTION:
Mapping XS f393556f
END DESCRIPTION:
XS GIS Cut Line= 4
      1971731.97     13551309.43      1971997.60     13550559.41
      1971356.98     13549674.00      1969488.61     13549481.44
#Sta/Elev= 30
  3776.2  578.53  3844.6  577.29  4040.3  576.47  4226.5  573.94  4500.2  572.63
  4500.4  572.13  4504.4  572.63  4649.1  572.90  4670.0  573.68  4690.9  573.02
  4930.2  572.84  5021.7  573.46  5143.4  572.93  5329.5  574.79  5449.6  574.96
  5727.0  573.21  5810.2  573.49  5877.8  572.79  6027.8  573.86  6460.9  576.34
  6903.2  575.69  6937.6  576.26  6953.5  576.25  6983.7  578.39  7036.1  576.53
  7114.3  576.64  7144.5  575.30  7163.2  576.55  7204.8  576.39  7543.0  583.74
#Mann=10,-1,0
  3776.2    0.05       0  4500.2    0.07       0  4504.4    0.05       0
  4930.2     0.1       0  5329.5    0.05       0  5449.6     0.1       0
  5810.2    0.05       0  6027.8     0.1       0  6937.6    0.08       0
  7036.1     0.1       0
Bank Sta=4500.2,4504.4
Exp/Cntr=0.3,0.1

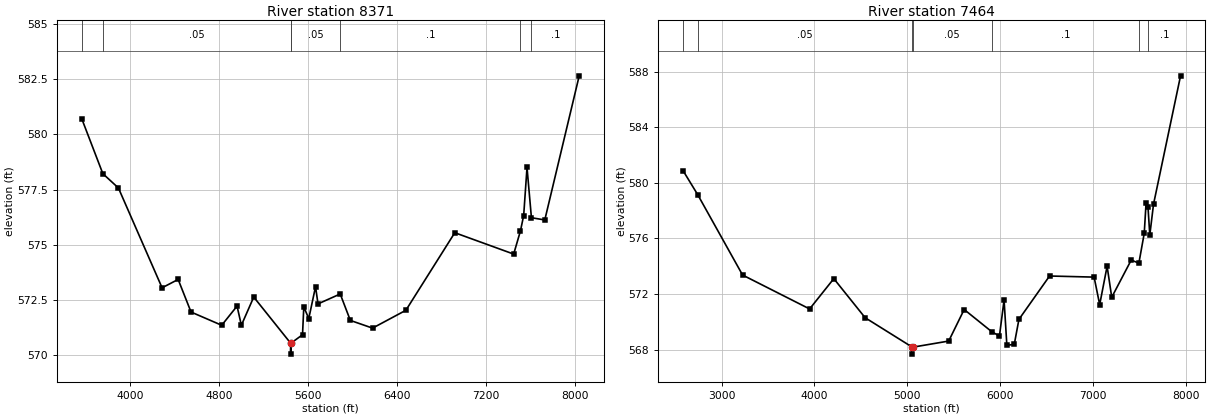
Type RM Length L Ch R = 1,8371,907,907,907
BEGIN DESCRIPTION:
Mapping XS 50b90c61
END DESCRIPTION:
XS GIS Cut Line= 4
      1971705.94     13551512.52      1972221.56     13550361.50
      1971758.02     13549450.04      1969565.32     13549455.25
#Sta/Elev= 30
  3565.5  580.71  3754.9  578.22  3895.2  577.57  4288.1  573.04  4432.7  573.42
  4548.7  571.94  4824.8  571.34  4962.8  572.21  5001.7  571.34  5112.9  572.62
  5444.6  570.53  5444.8  570.03  5448.8  570.53  5552.0  570.91  5563.5  572.18
  5608.1  571.64  5669.1  573.09  5691.4  572.31  5891.2  572.76  5982.3  571.56
  6182.3  571.21  6482.3  572.02  6922.3  575.54  7452.3  574.57  7513.6  575.63
  7542.3  576.32  7572.3  578.50  7612.0  576.22  7732.3  576.12  8042.0  582.66
#Mann=7,-1,0
  3565.5     0.1       0  3754.9    0.05       0  5444.6   0.035       0
  5448.8    0.05       0  5891.2     0.1       0  7513.6    0.08       0
  7612.0     0.1       0
Bank Sta=5444.6,5448.8
Exp/Cntr=0.3,0.1

Type RM Length L Ch R = 1,7464,0,0,0
BEGIN DESCRIPTION:
UNT 031 in BCW 1.0
END DESCRIPTION:
XS GIS Cut Line= 4
      1971721.54     13551559.45      1972715.43     13549891.11
      1972063.01     13549122.08      1969653.81     13549174.00
#Sta/Elev= 30
  2584.7  580.87  2741.9  579.15  3225.4  573.37  3947.7  570.93  4208.5  573.11
  4545.9  570.30  5054.3  568.18  5054.6  567.68  5059.0  568.18  5446.6  568.62
  5613.2  570.89  5911.0  569.29  5993.3  568.98  6043.3  571.57  6073.3  568.31
  6153.3  568.39  6203.3  570.18  6533.4  573.30  7013.5  573.22  7073.5  571.24
  7153.5  574.00  7203.5  571.77  7413.6  574.45  7495.8  574.22  7553.6  576.37
  7573.6  578.57  7594.2  578.25  7613.6  576.25  7653.6  578.46  7944.9  587.70
#Mann=7,-1,0
  2584.7     0.1       0  2741.9    0.05       0  5054.3   0.035       0
  5059.0    0.05       0  5911.0     0.1       0  7495.8    0.08       0
  7594.2     0.1       0
Bank Sta=5054.3,5059
Exp/Cntr=0.3,0.1

Chan Stop Cuts=-1