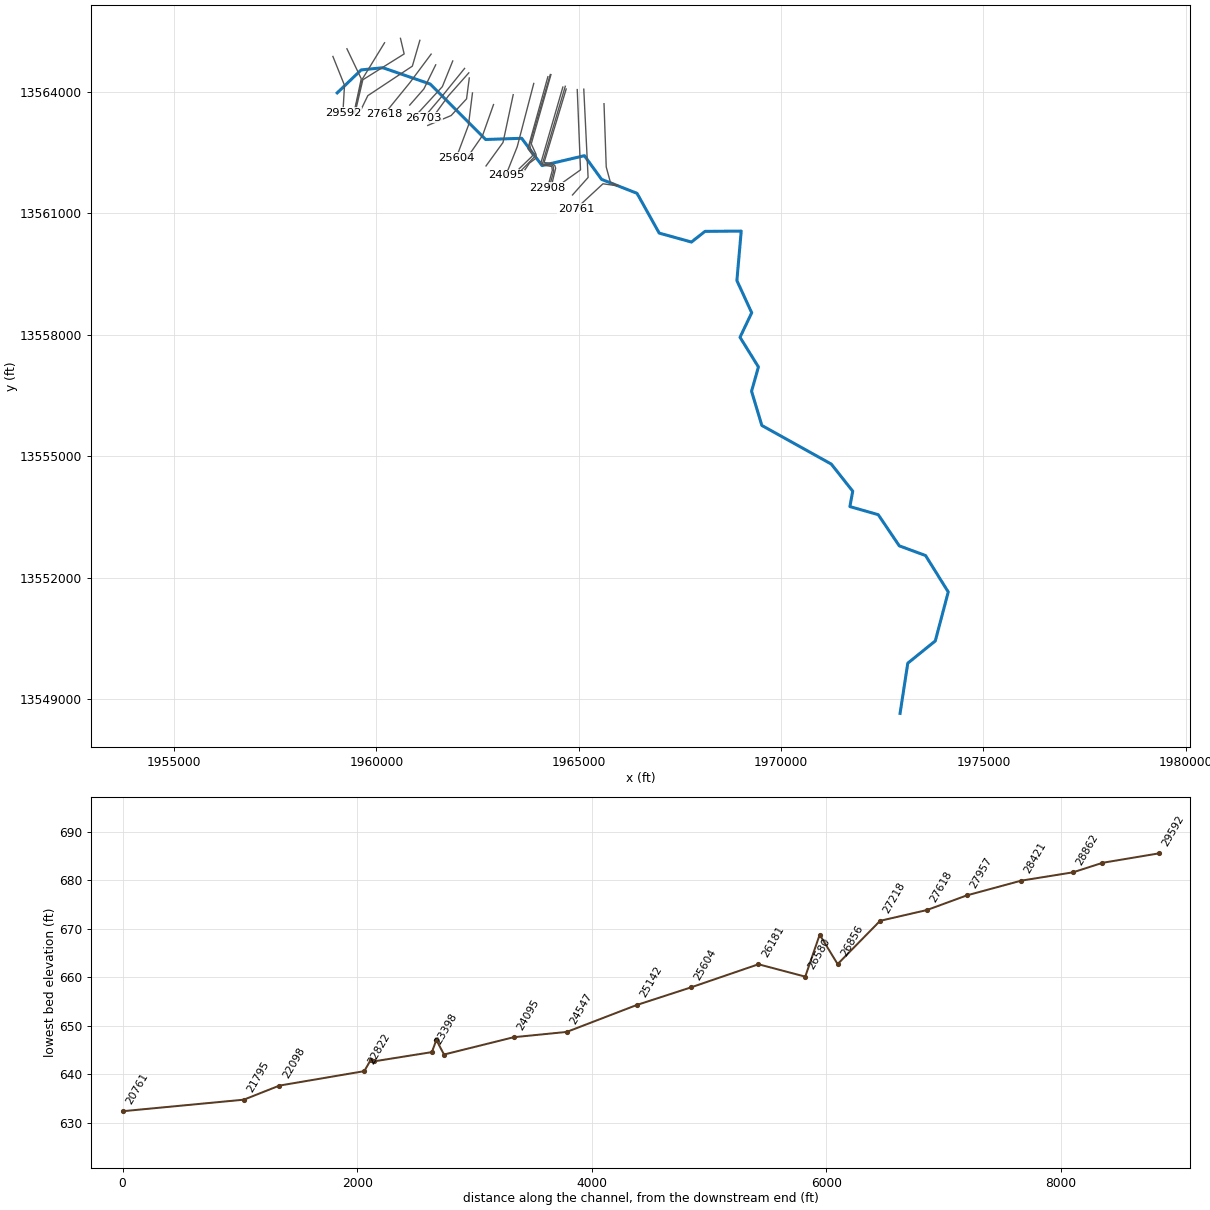
--- UNT 033 in BCW.prj (project) ---

Proj Title=UNT 033 in BCW Base Level Engineering
Current Plan=p02
Default Exp/Contr=0.3,0.1
English Units
Geom File=g01
Flow File=f01
Plan File=p02
Y Axis Title=Elevation
X Axis Title(PF)=Main Channel Distance
X Axis Title(XS)=Station
BEGIN DESCRIPTION:
UNT 033 in BCW
END DESCRIPTION:
DSS Export Rating Curves= 0
DSS Export Rating Curve Sorted= 0
DSS Export Volume Flow Curves= 0
DXF OffsetX= 0
DXF OffsetY= 0
DXF ScaleX= 1
DXF ScaleY= 10

--- UNT 033 in BCW.p02 (plan) ---

Plan Title=Multiple Run
Program Version=5.07
Short Identifier=Multiple Run
Geom File=g01
Flow File=f01
Subcritical Flow
K Sum by GR= 0
Std Step Tol= 0.01
Critical Tol= 0.01
Num of Std Step Trials= 20
Max Error Tol= 0.3
Flow Tol Ratio= 0.001
Split Flow NTrial= 30
Split Flow Tol= 0.02
Split Flow Ratio= 0.02
Log Output Level= 0
Friction Slope Method= 1
Unsteady Friction Slope Method= 2
Unsteady Bridges Friction Slope Method= 1
Parabolic Critical Depth
Global Vel Dist= 1 , 1 , 1
Global Log Level= 0
CheckData=True
Encroach Param=-1 ,0,0, 0
BEGIN DESCRIPTION:
Multiple Run
END DESCRIPTION:
Computation Interval=1MIN
Output Interval=1HOUR
Instantaneous Interval=1HOUR
Mapping Interval=1HOUR
Computation Time Step Use Courant=        0
Computation Time Step Use Time Series=    0
Computation Time Step Count To Double=0
Computation Time Step Max Doubling=0
Computation Time Step Max Halving=0
Computation Time Step Residence Courant=0
Run HTab= 0
Run UNet= 0
Run Sediment= 0
Run PostProcess= 0
Run WQNet= 0
Run RASMapper= 0
UNET Theta= 1
UNET Theta Warmup= 1
UNET ZTol= 0.02
UNET ZSATol= 0.02
UNET MxIter= 20
UNET Max Iter WO Improvement= 0
UNET MaxInSteps= 0
UNET DtIC= 0
UNET DtMin= 0
UNET MaxCRTS= 20
UNET WFStab= 2
UNET SFStab= 1
UNET WFX= 1
UNET SFX= 1
UNET 1D Methodology=Finite Difference
UNET DSS MLevel= 4
UNET Pardiso=0
UNET DZMax Abort= 100
UNET Use Existing IB Tables=-1
UNET Froude Reduction=False
UNET Froude Limit= 0.8
UNET Froude Power= 4
UNET D1 Cores= 0
UNET D2 Coriolis=0
UNET D2 Cores= 0
UNET D2 Theta= 1
UNET D2 Theta Warmup= 1
UNET D2 Z Tol= 0.01
UNET D2 Volume Tol= 0.01
UNET D2 Max Iterations= 20
UNET D2 Equation= 0
UNET D2 RampUpFraction=0.1
UNET D2 TimeSlices= 1
UNET D2 BCVolumeCheck=0
UNET D1D2 MaxIter= 0
UNET D1D2 ZTol=0.01
UNET D1D2 QTol=0.1
UNET D1D2 MinQTol=1
Write IC File= 0
Write IC File at Fixed DateTime=0
Write IC File at Sim End=0
Echo Input=False
Echo Parameters=False
Echo Output=False
Write Detailed= 0
HDF Write Warmup=0
HDF Write Time Slices=0
HDF Flush=0
HDF Face Node Velocities=0
HDF Compression= 1
HDF Chunk Size= 1
HDF Spatial Parts= 1
HDF Use Max Rows=0
HDF Fixed Rows= 1
Calibration Method= 0
Calibration Iterations= 20
Calibration Max Change=0.05
Calibration Tolerance=0.2
Calibration Maximum=1.5
Calibration Minimum=0.5
Calibration Optimization Method= 1
WQ AD Non Conservative
WQ ULTIMATE=-1
WQ Max Comp Step=1HOUR
WQ Output Interval=15MIN
WQ Output Selected Increments= 0
WQ Output face flow=0
WQ Output face velocity=0
WQ Output face area=0
WQ Output face dispersion=0
WQ Output cell volume=0
WQ Output cell surface area=0
WQ Output cell continuity=0
WQ Output cumulative cell continuity=0
WQ Output face conc=0
WQ Output face dconc_dx=0
WQ Output face courant=0
WQ Output face peclet=0
WQ Output face adv mass=0
WQ Output face disp mass=0
WQ Output cell mass=0
WQ Output cell source sink temp=0
WQ Output nsm pathways=0
WQ Output nsm derived pathways=0
WQ Output MaxMinRange=-1
WQ Daily Max Min Mean=-1
WQ Daily Range=0
WQ Daily Time=0
WQ Create Restart=0
WQ Fixed Restart=0
WQ System Summary=0
WQ Write To DSS=0
WQ Use Fixed Temperature=0
Sorting and Armoring Iterations= 10
XS Update Threshold= 0.02
Bed Roughness Predictor= 0
Hydraulics Update Threshold= 0.02
Energy Slope Method= 1
Volume Change Method= 1
Sediment Retention Method= 0
XS Weighting Method= 0
Number of US Weighted Cross Sections= 1
Number of DS Weighted Cross Sections= 1
Upstream XS Weight=0
Main XS Weight=1
Downstream XS Weight=0
Number of DS XS's Weighted with US Boundary= 1
Upstream Boundary Weight= 1
Weight of XSs Associated with US Boundary= 0
Number of US XS's Weighted with DS Boundary= 1
Downstream Boundary Weight= 0.5
Weight of XSs Associated with DS Boundary= 0.5
Percentile Method= 0
Sediment Output Level= 3
Mass or Volume Output= 0
Output Increment Type= 1
Profile and TS Output Increment= 1
XS Output Flag= 0
XS Output Increment= 10
Write Gradation File= 0
Read Gradation Hotstart= 0
Write HDF5 File= 1
Write Binary Output= 1
Write DSS Sediment File= 0
SV Curve= 0
Specific Gage Flag= 0

--- UNT 033 in BCW.f01 (steady flow) ---

Flow Title=Multiple
Program Version=5.05
Number of Profiles= 7
Profile Names=10-year,25-year,50-year,1pct_min,100-year,1pct_plu,500-year
River Rch & RM=UNT 033 in BCW,Reach-1         ,29592
     708    1012    1269     786    1569    3131    2402
River Rch & RM=UNT 033 in BCW,Reach-1         ,28421
     854    1234    1557     970    1935    3861    2997
River Rch & RM=UNT 033 in BCW,Reach-1         ,25604
    1166    1707    2175    1365    2724    5436    4288
River Rch & RM=UNT 033 in BCW,Reach-1         ,19106
    1492    2209    2833    1790    3571    7124    5690
River Rch & RM=UNT 033 in BCW,Reach-1         ,13063
    1564    2320    2979    1883    3758    7498    6001
River Rch & RM=UNT 033 in BCW,Reach-1         ,12548
    1881    2804    3612    2290    4568    9115    7337
Boundary for River Rch & Prof#=UNT 033 in BCW,Reach-1         , 1
Up Type= 0
Dn Type= 3
Dn Slope=0.005
Boundary for River Rch & Prof#=UNT 033 in BCW,Reach-1         , 2
Up Type= 0
Dn Type= 3
Dn Slope=0.005
Boundary for River Rch & Prof#=UNT 033 in BCW,Reach-1         , 3
Up Type= 0
Dn Type= 3
Dn Slope=0.005
Boundary for River Rch & Prof#=UNT 033 in BCW,Reach-1         , 4
Up Type= 0
Dn Type= 3
Dn Slope=0.005
Boundary for River Rch & Prof#=UNT 033 in BCW,Reach-1         , 5
Up Type= 0
Dn Type= 3
Dn Slope=0.005
Boundary for River Rch & Prof#=UNT 033 in BCW,Reach-1         , 6
Up Type= 0
Dn Type= 3
Dn Slope=0.005
Boundary for River Rch & Prof#=UNT 033 in BCW,Reach-1         , 7
Up Type= 0
Dn Type= 3
Dn Slope=0.005
DSS Import GetInterval= 0
DSS Import GetPeak= 0
DSS Import FillOption= 0

--- UNT 033 in BCW.g01 (geometry) ---

Geom Title=Existing Conditions
Program Version=5.05

River Reach=UNT 033 in BCW  ,Reach-1
Reach XY= 30
      1959032.99     13563976.38      1959624.57     13564544.11
       1960160.6     13564597.93       1961330.8     13564194.54
       1962700.8     13562824.54       1963590.8     13562854.54
      1964094.55     13562179.36       1965140.8     13562424.54
       1965565.9     13561838.65       1966440.8     13561494.54
      1966989.03     13560511.69      1967786.26     13560290.86
       1968120.8     13560554.54      1969015.18     13560561.29
      1968908.57     13559339.05      1969274.51     13558543.06
      1968985.88     13557937.59       1969440.8     13557204.54
       1969270.8     13556604.54      1969525.11     13555758.92
       1971240.8     13554804.54       1971770.8     13554134.54
       1971700.8     13553754.54       1972400.8     13553554.54
       1972920.8     13552784.54       1973570.8     13552544.54
       1974130.8     13551644.54       1973810.8     13550434.54
       1973130.8     13549884.54       1972940.8     13548644.54

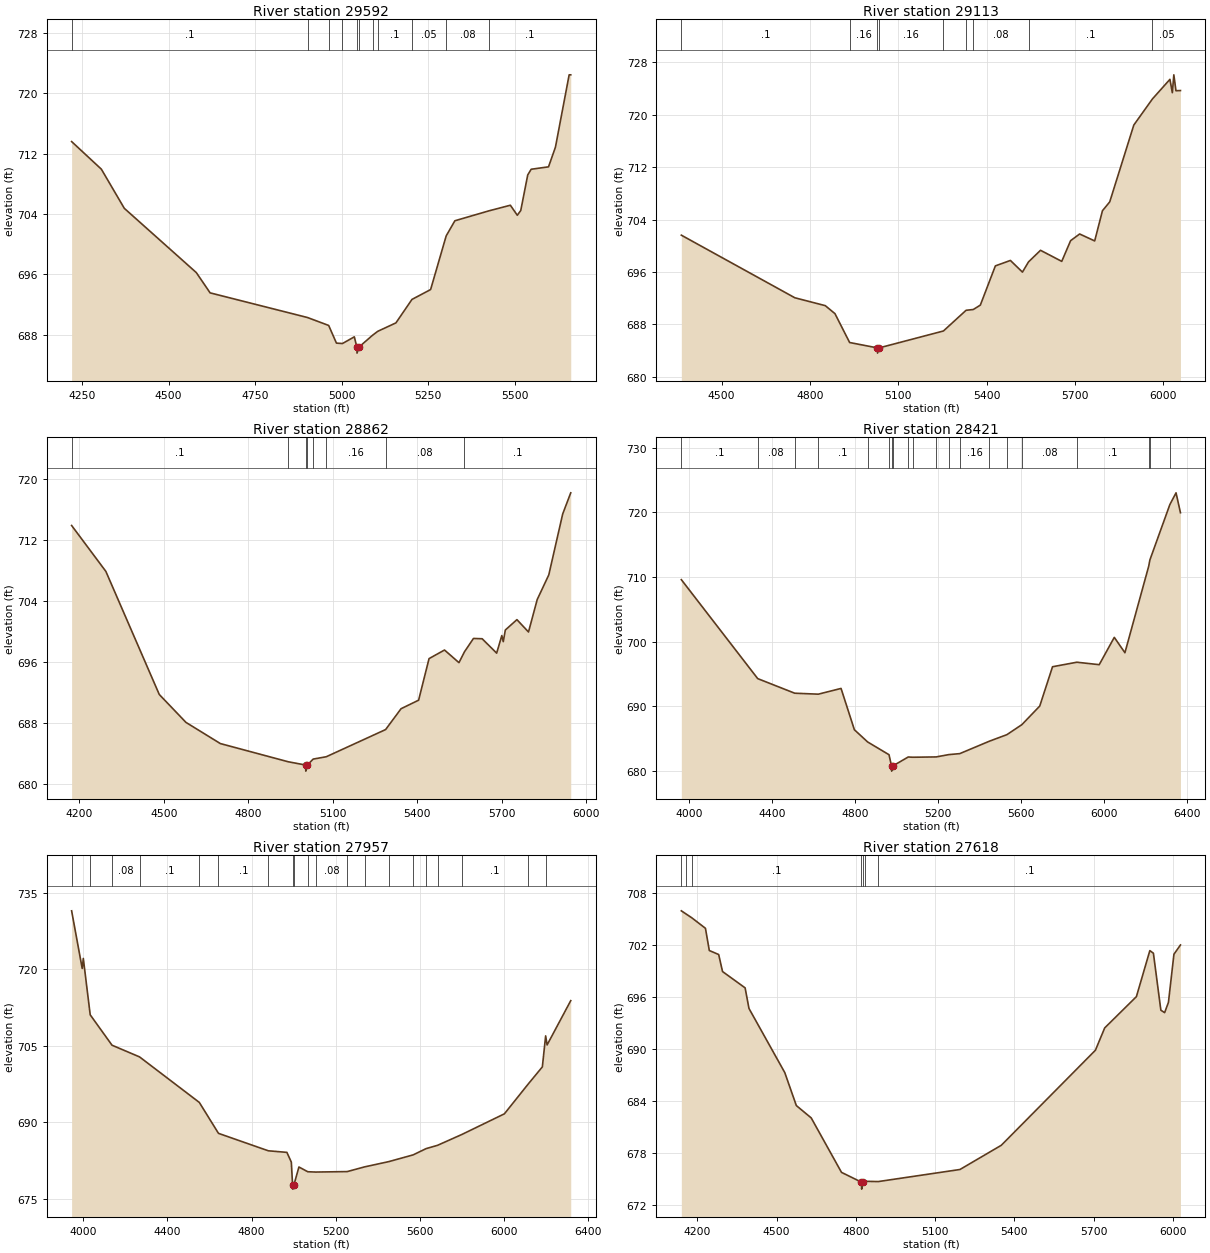
Type RM Length L Ch R = 1 ,29592   ,479,479,479
BEGIN DESCRIPTION:
UNT 033 in BCW 23.0
END DESCRIPTION:
XS GIS Cut Line= 3
      1958926.62     13564876.29       1959213.1     13564162.71
      1959174.04     13563490.88
#Sta/Elev= 30
  4219.8  713.59  4305.7  709.93    4372  704.74    4580  696.22  4619.9  693.53
  4901.3  690.26  4962.4  689.21  4984.8  686.87  5002.1  686.81  5036.5   687.7
  5043.8  686.34  5044.3  685.54  5049.8  686.34  5089.7  687.93  5104.1  688.43
  5156.7  689.55    5203  692.66  5256.9  693.97  5301.9  701.09    5327  703.09
  5424.9   704.4  5487.3  705.15  5507.3  703.82  5517.3  704.45  5537.4  709.16
  5547.4  709.92  5597.5  710.24  5617.5  712.85  5657.1  722.44  5661.7  722.44
#Mann= 11 ,-1 , 0
  4219.8      .1       0  4901.3     .12       0  4962.4     .16       0
  5002.1      .1       0  5043.8     .07       0  5049.8      .1       0
  5089.7     .16       0  5104.1      .1       0    5203     .05       0
  5301.9     .08       0  5424.9      .1       0
Bank Sta=5043.8,5049.8
XS Rating Curve= 0 ,0
Exp/Cntr=0.3,0.1

Type RM Length L Ch R = 1 ,29113   ,251,251,251
BEGIN DESCRIPTION:
UNT 033 in BCW 22.0
END DESCRIPTION:
XS GIS Cut Line= 3
      1959273.01     13565066.33      1959627.16     13564324.17
      1959444.87     13563470.03
#Sta/Elev= 30
    4363  701.61  4748.7  692.05    4852  690.85  4884.9  689.63  4934.8  685.22
  5029.1   684.4  5029.6   683.6  5035.1   684.4  5253.4  686.98  5330.4  690.14
  5354.9  690.26  5378.8  690.93  5429.9  696.92    5481  697.75  5521.9  695.97
  5542.5  697.53  5583.3   699.3  5655.4  697.61  5685.5  700.77  5716.2  701.79
  5767.3  700.73  5793.7  705.34  5818.4  706.69  5900.2  718.42  5963.7  722.42
  6022.9   725.4  6031.1  723.36  6036.2  726.09  6043.4  723.66  6058.7  723.69
#Mann= 9 ,-1 , 0
    4363      .1       0  4934.8     .16       0  5029.1     .07       0
  5035.1     .16       0  5253.4     .08       0  5330.4     .05       0
  5354.9     .08       0  5542.5      .1       0  5963.7     .05       0
Bank Sta=5029.1,5035.1
XS Rating Curve= 0 ,0
Exp/Cntr=0.3,0.1

Type RM Length L Ch R = 1 ,28862   ,441,441,441
BEGIN DESCRIPTION:
Mapping XS 1cf9ff7d
END DESCRIPTION:
XS GIS Cut Line= 3
      1960202.68      13565214.8      1959647.99     13564308.55
      1959484.11      13563619.2
#Sta/Elev= 30
  4173.1  713.91  4294.6  707.88  4484.1  691.71  4578.9  688.04  4700.9  685.26
  4941.7  682.87  5003.5  682.44    5004  681.64  5009.5  682.44  5030.2  683.22
  5076.7  683.53  5287.3   687.1  5342.1  689.84  5404.4  690.96  5441.4  696.42
  5496.3  697.55  5547.6  695.89    5567  697.31    5599  699.07  5629.9  699.03
  5681.3  697.14  5699.6  699.45  5704.8  698.65  5712.1  700.18  5753.2  701.54
  5794.3  699.92  5825.2  704.18  5866.3  707.42  5915.6  715.42  5944.2   718.2
#Mann= 8 ,-1 , 0
  4173.1      .1       0  4941.7     .16       0  5003.5     .07       0
  5009.5     .16       0  5030.2      .1       0  5076.7     .16       0
  5287.3     .08       0    5567      .1       0
Bank Sta=5003.5,5009.5
XS Rating Curve= 0 ,0
Exp/Cntr=0.3,0.1

Type RM Length L Ch R = 1 ,28421   ,464,464,464
BEGIN DESCRIPTION:
Mapping XS be6b516b
END DESCRIPTION:
XS GIS Cut Line= 4
      1960595.91     13565324.16      1960687.05     13564938.75
      1959666.22     13564300.73      1959481.31     13563514.23
#Sta/Elev= 30
  3960.9  709.59  4329.4  694.26  4507.8     692  4621.5  691.85  4731.4  692.74
  4795.7  686.34  4859.6  684.45  4962.8  682.47  4974.8  680.73  4975.3  679.93
  4980.9  680.73  5055.5  682.12  5076.5  682.08  5190.3  682.13  5251.4  682.49
    5304  682.64  5447.3  684.57  5531.5  685.58  5603.7  687.13  5689.9  690.01
  5751.6   696.1  5868.8   696.8  5976.8  696.42  6049.5  700.65  6100.8  698.27
  6215.7  711.69  6221.2  712.64  6317.7  721.23  6347.4  723.04  6368.7  719.96
#Mann= 20 ,-1 , 0
  3960.9      .1       0  4329.4     .08       0  4507.8     .05       0
  4621.5      .1       0  4859.6     .05       0  4962.8      .1       0
  4974.8     .07       0  4980.9      .1       0  5055.5     .08       0
  5076.5     .05       0  5190.3     .16       0  5251.4     .05       0
    5304     .16       0  5447.3     .05       0  5531.5     .16       0
  5603.7     .08       0  5868.8      .1       0  6215.7     .05       0
  6221.2      .1       0  6317.7     .05       0
Bank Sta=4974.8,4980.9
XS Rating Curve= 0 ,0
Exp/Cntr=0.3,0.1

Type RM Length L Ch R = 1 ,27957   ,339,339,339
BEGIN DESCRIPTION:
UNT 033 in BCW 20.0
END DESCRIPTION:
XS GIS Cut Line= 4
        1961075.     13565275.01      1960889.31     13564637.02
      1959789.05     13563907.85      1959619.91     13563560.89
#Sta/Elev= 30
  3945.6  731.48  3995.9  720.17  4001.1  722.14  4033.9  711.08  4137.5  705.12
  4268.1  702.83    4552   693.9  4643.1  687.83  4879.7  684.41  4967.9   684.1
    4989  682.19    4995  677.69  4995.5  676.89  5001.1  677.69  5025.1  681.23
  5067.1   680.3  5105.4  680.24  5254.5  680.33  5336.6  681.25  5452.2  682.29
  5567.7  683.61  5629.3  684.84  5683.3  685.48  5798.9  687.61  6000.9  691.66
  6112.5  697.43  6181.2  700.87  6196.8  706.95  6203.7  705.17    6316  713.86
#Mann= 20 ,-1 , 0
  3945.6      .1       0  4033.9     .05       0  4137.5     .08       0
  4268.1      .1       0    4552     .05       0  4643.1      .1       0
  4879.7     .05       0    4995     .07       0  5001.1      .1       0
  5067.1     .05       0  5105.4     .08       0  5254.5     .05       0
  5336.6     .08       0  5452.2     .08       0  5567.7      .1       0
  5629.3     .05       0  5683.3     .08       0  5798.9      .1       0
  6112.5      .1       0  6196.8     .05       0
Bank Sta=4995,5001.1
XS Rating Curve= 0 ,0
Exp/Cntr=0.3,0.1

Type RM Length L Ch R = 1 ,27618   ,400,400,400
BEGIN DESCRIPTION:
UNT 033 in BCW 19.0
END DESCRIPTION:
XS GIS Cut Line= 3
      1961353.73     13564934.35        1960825.       13564225.
      1960190.53     13563445.62
#Sta/Elev= 30
  4139.3  705.92  4155.5  705.59  4177.9  705.14  4230.6  703.91  4245.2  701.35
  4280.7  700.89  4295.3  698.93  4380.8  697.05  4395.4  694.68  4530.9   687.3
  4574.7   683.5    4631  682.08  4745.7  675.81  4821.4  674.68  4821.9  673.88
  4827.6  674.68  4834.7  674.78  4884.9  674.75  5194.2  676.14  5350.8  678.93
    5707  689.87  5742.2  692.44  5862.2  696.04  5913.1  701.34  5926.6  701.04
  5954.8  694.48  5969.1   694.2  5983.5  695.38  6004.3  700.92    6029  701.99
#Mann= 7 ,-1 , 0
  4139.3     .08       0  4155.5     .05       0  4177.9      .1       0
  4821.4     .07       0  4827.6      .1       0  4834.7     .12       0
  4884.9      .1       0
Bank Sta=4821.4,4827.6
XS Rating Curve= 0 ,0
Exp/Cntr=0.3,0.1

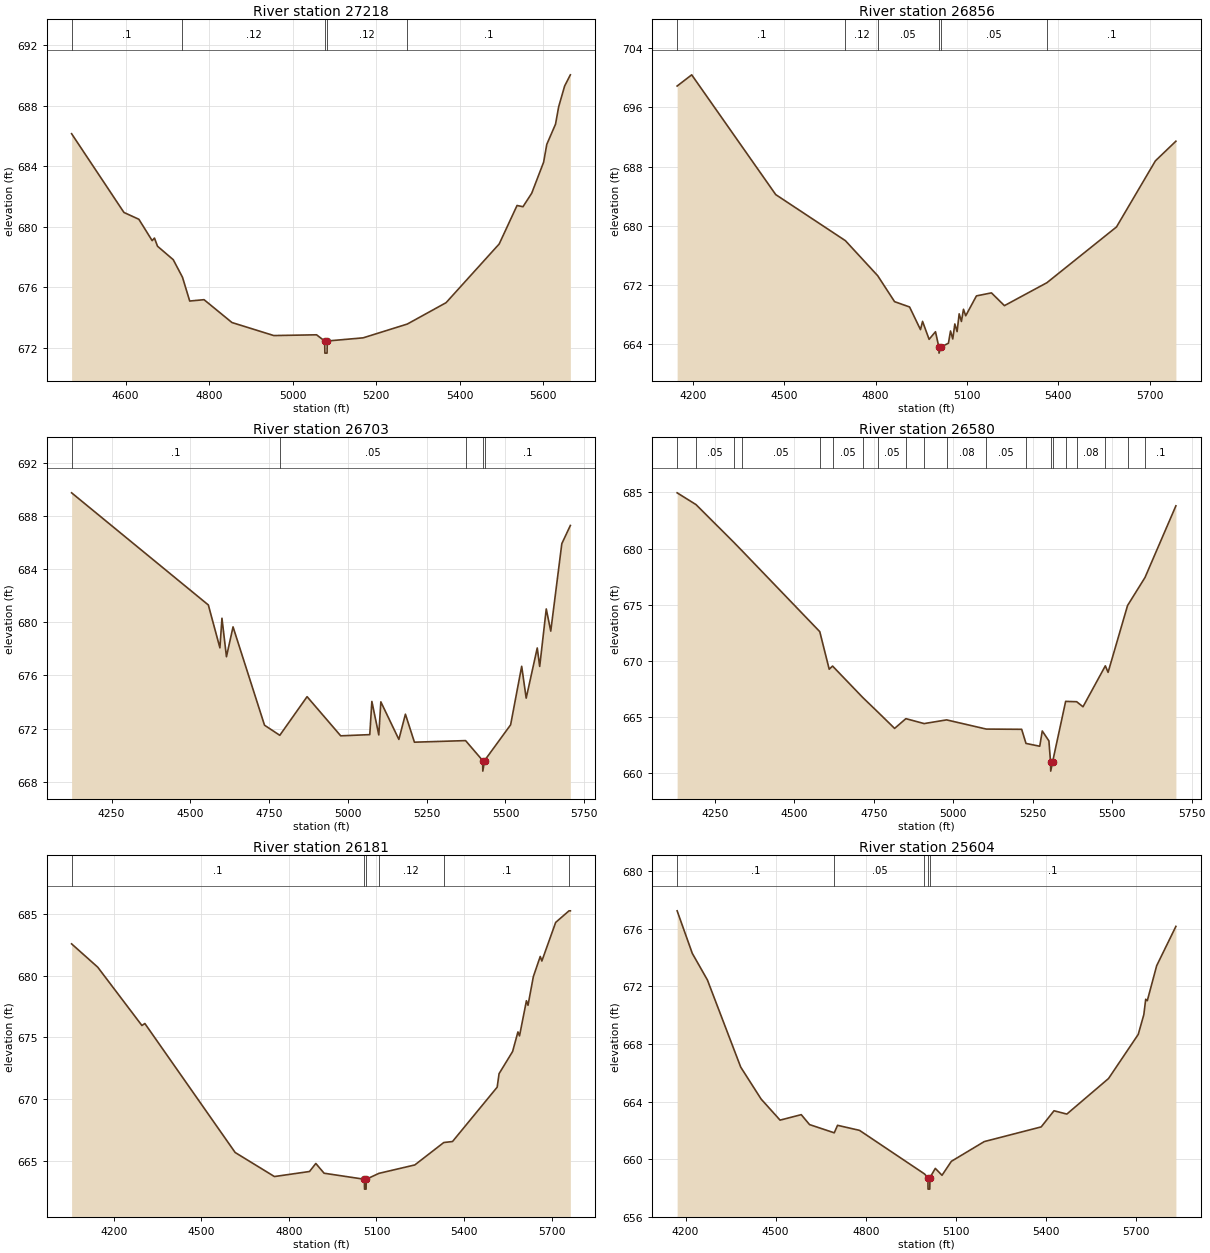
Type RM Length L Ch R = 1 ,27218   ,362,362,362
BEGIN DESCRIPTION:
UNT 033 in BCW 18.0
END DESCRIPTION:
XS GIS Cut Line= 3
      1961466.58     13564669.59        1961175.       13564075.
      1960825.03     13563675.03
#Sta/Elev= 30
  4470.9  686.14  4596.2  680.94  4631.9  680.49  4663.7  679.08  4669.2  679.25
  4676.5  678.71  4714.2  677.82  4736.3  676.66  4753.6  675.09  4787.9  675.18
  4854.7  673.67  4954.9  672.81  5057.2  672.86  5076.6  672.45  5077.1  671.65
  5082.3  671.65  5082.8  672.45  5168.7  672.66  5274.3  673.57  5367.1  674.98
  5494.3  678.86    5537   681.4  5551.2  681.32  5572.1  682.21  5600.6  684.26
  5608.2  685.44  5629.1  686.77  5636.6  687.92  5650.9  689.29  5664.6  690.03
#Mann= 5 ,-1 , 0
  4470.9      .1       0  4736.3     .12       0  5076.6     .07       0
  5082.8     .12       0  5274.3      .1       0
Bank Sta=5076.6,5082.8
XS Rating Curve= 0 ,0
Exp/Cntr=0.3,0.1

Type RM Length L Ch R = 1 ,26856   ,153,153,153
BEGIN DESCRIPTION:
UNT 033 in BCW 17.0
END DESCRIPTION:
XS GIS Cut Line= 3
      1961887.58     13564765.08       1961631.5     13564131.38
       1960985.6     13563429.13
#Sta/Elev= 30
  4148.4   698.9  4196.2  700.42  4472.1   684.2  4700.9  677.96    4807  673.21
  4862.3   669.7  4911.6  668.98  4947.4  665.91  4954.2  667.03  4975.7   664.6
  4996.7  665.63  5007.8  663.53  5008.3  662.73    5014  663.53  5039.2  664.08
    5046  665.73  5053.4  664.65  5060.2  666.68  5067.6  665.64  5074.4  668.05
  5081.8  667.02  5088.6  668.67  5095.9  667.79  5131.1  670.48  5180.4  670.89
    5223  669.16  5362.6  672.27    5591  679.82  5718.7  688.77    5786  691.43
#Mann= 6 ,-1 , 0
  4148.4      .1       0  4700.9     .12       0    4807     .05       0
  5007.8    .033       0    5014     .05       0  5362.6      .1       0
Bank Sta=5007.8,5014
XS Rating Curve= 0 ,0
Exp/Cntr=0.3,0.1

Type RM Length L Ch R = 1 ,26703   ,123,123,123
BEGIN DESCRIPTION:
UNT 033 in BCW 16.0
END DESCRIPTION:
XS GIS Cut Line= 3
      1962180.09       13564581.       1961672.3     13563953.42
      1961169.83     13563362.44
#Sta/Elev= 30
    4123  689.76    4557  681.31  4593.7  678.08  4600.2  680.31  4614.5  677.41
  4635.4  679.66  4735.3  672.25  4783.8  671.49  4870.4   674.4  4977.1  671.45
  5069.4  671.54    5076  674.04    5098  671.52  5104.5  674.01  5161.7  671.18
  5182.5  673.08  5211.1  670.97  5373.4  671.09  5427.6  669.59  5428.1  668.79
  5433.8  669.59  5516.4  672.28  5551.5  676.69  5565.8  674.29  5600.9  678.07
  5608.7  676.68  5629.5  681.01  5643.8  679.34  5678.9  685.93    5706   687.3
#Mann= 5 ,-1 , 0
    4123      .1       0  4783.8     .05       0  5373.4      .1       0
  5427.6    .033       0  5433.8      .1       0
Bank Sta=5427.6,5433.8
XS Rating Curve= 0 ,0
Exp/Cntr=0.3,0.1

Type RM Length L Ch R = 1 ,26580   ,399,399,399
BEGIN DESCRIPTION:
UNT 033 in BCW 15.0
END DESCRIPTION:
XS GIS Cut Line= 3
      1962284.27     13564471.64      1961779.07     13563901.34
      1961303.34     13563248.84
#Sta/Elev= 30
  4131.1  684.97  4190.5  683.92    4309  680.57  4333.7  679.85  4579.9  672.59
  4609.6  669.24  4620.2  669.52  4715.4  666.71  4763.4   665.4  4815.4  663.96
  4850.9  664.83  4908.2  664.39    4979  664.72  5103.9   663.9  5215.2  663.88
  5228.8  662.62  5272.1  662.37    5280  663.73  5300.9  662.85  5306.1  660.95
  5306.6  660.15  5312.3  660.95  5353.6  666.37  5388.3  666.34  5408.2  665.89
  5478.5  669.54  5487.1  668.96  5548.4  674.92  5603.3  677.42  5700.5  683.81
#Mann= 20 ,-1 , 0
  4131.1     .08       0  4190.5     .05       0    4309      .1       0
  4333.7     .05       0  4579.9      .1       0  4620.2     .05       0
  4715.4      .1       0  4763.4     .05       0  4850.9      .1       0
  4908.2     .05       0    4979     .08       0  5103.9     .05       0
  5228.8     .05       0  5306.1     .07       0  5312.3     .05       0
  5353.6      .1       0  5388.3     .08       0  5478.5      .1       0
  5548.4     .08       0  5603.3      .1       0
Bank Sta=5306.1,5312.3
XS Rating Curve= 0 ,0
Exp/Cntr=0.3,0.1

Type RM Length L Ch R = 1 ,26181   ,577,577,577
BEGIN DESCRIPTION:
Mapping XS aac58b26
END DESCRIPTION:
XS GIS Cut Line= 4
      1962296.25     13564343.75      1962228.55     13563828.16
      1961848.34     13563416.71      1961270.17      13563171.9
#Sta/Elev= 30
    4056  682.59  4145.5   680.7  4296.8  675.97  4306.9  676.13  4616.2  665.67
  4750.6  663.72  4870.8  664.13  4892.4  664.78  4920.7  663.99  5058.7   663.5
  5059.2   662.7  5064.5   662.7    5065   663.5  5108.6  663.98  5231.3  664.66
  5330.6  666.48  5360.5  666.56  5513.5  670.97  5519.9  672.06  5566.3  673.86
  5584.6  675.45    5590  675.13  5613.7  677.98  5619.1  677.61  5637.3  679.93
    5661  681.57  5666.5   681.2  5713.8  684.33  5759.5  685.27  5764.1  685.27
#Mann= 6 ,-1 , 0
    4056      .1       0  5058.7     .07       0    5065      .1       0
  5108.6     .12       0  5330.6      .1       0  5759.5     .05       0
Bank Sta=5058.7,5065
XS Rating Curve= 0 ,0
Exp/Cntr=0.3,0.1

Type RM Length L Ch R = 1 ,25604   ,462,462,462
BEGIN DESCRIPTION:
UNT 033 in BCW 14.0
END DESCRIPTION:
XS GIS Cut Line= 3
        1962375.     13563975.02        1962275.       13563175.
      1961975.02     13562375.04
#Sta/Elev= 30
  4171.9  677.24  4222.3  674.29  4272.7  672.44  4383.6  666.39  4451.6  664.17
  4514.6  662.71  4585.1  663.09  4612.8   662.4    4695  661.83    4706  662.35
  4779.1     662  4995.2  658.98  5006.8  658.72  5007.3  657.92  5013.1  657.92
  5013.6  658.72  5031.5  659.36  5053.8  658.88  5084.9  659.85  5194.4  661.22
    5384  662.24  5426.7  663.36  5469.4  663.13  5608.3   665.6  5707.1  668.66
  5725.7  670.03    5732   671.1  5737.3     671  5768.5  673.43  5832.5  676.16
#Mann= 5 ,-1 , 0
  4171.9      .1       0    4695     .05       0  4995.2      .1       0
  5006.8     .07       0  5013.6      .1       0
Bank Sta=5006.8,5013.6
XS Rating Curve= 0 ,0
Exp/Cntr=0.3,0.1

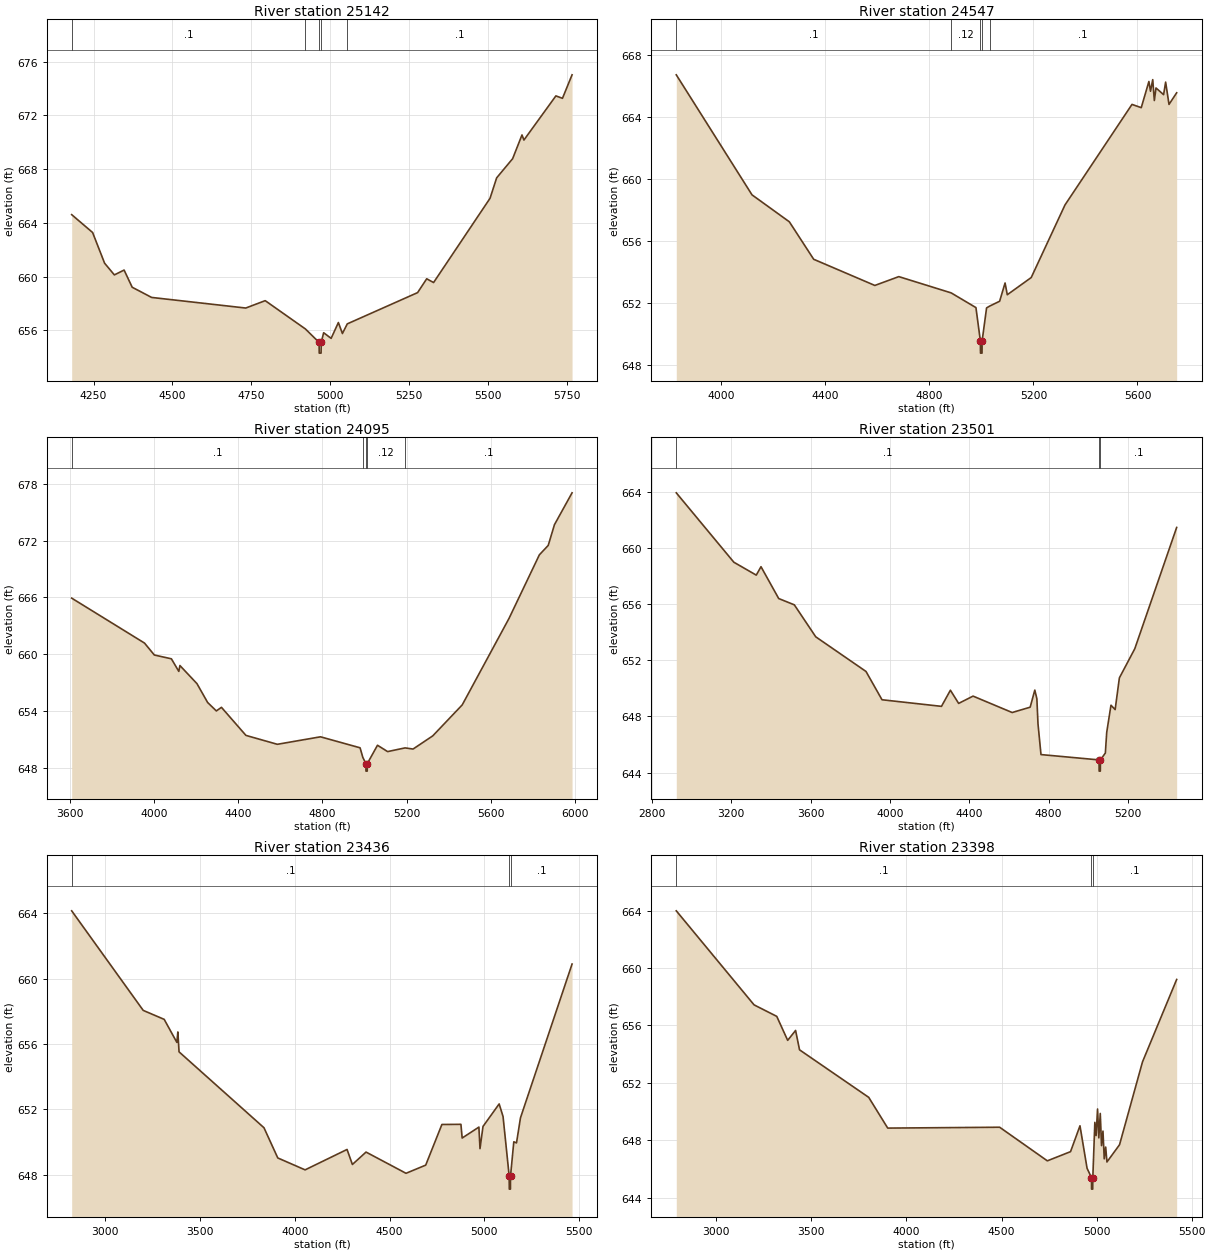
Type RM Length L Ch R = 1 ,25142   ,595,595,595
BEGIN DESCRIPTION:
UNT 033 in BCW 13.0
END DESCRIPTION:
XS GIS Cut Line= 3
       1962895.2      13563687.5        1962625.       13562925.
      1962181.66     13562286.48
#Sta/Elev= 30
  4180.5  664.61  4246.8  663.28  4284.9  660.99  4315.8  660.12  4346.7  660.48
  4372.3   659.2    4434  658.44  4732.3  657.65    4794   658.2  4921.5  656.09
  4964.8  655.09  4965.3  654.29  4971.1  654.29  4971.6  655.09  4979.3  655.81
    5003  655.39    5026  656.57  5038.8  655.75  5054.2  656.47  5277.2   658.8
    5306  659.83  5327.8  659.55  5506.8  665.83  5527.7  667.35  5578.4  668.78
  5608.1  670.55  5614.2  670.17  5715.5  673.46  5736.4  673.28  5766.8  675.03
#Mann= 5 ,-1 , 0
  4180.5      .1       0  4921.5     .12       0  4964.8     .07       0
  4971.6     .12       0  5054.2      .1       0
Bank Sta=4964.8,4971.6
XS Rating Curve= 0 ,0
Exp/Cntr=0.3,0.1

Type RM Length L Ch R = 1 ,24547   ,452,452,452
BEGIN DESCRIPTION:
Mapping XS e5953771
END DESCRIPTION:
XS GIS Cut Line= 3
      1963381.36     13563931.55      1963129.63     13562751.04
      1962709.56     13562170.66
#Sta/Elev= 30
  3827.2  666.73  4118.3  658.98  4261.8  657.24  4355.4  654.82  4590.5  653.13
  4682.6   653.7  4883.8  652.65  4979.1   651.7  4996.1  649.56  4996.6  648.76
  5002.5  648.76    5003  649.56    5020  651.68  5032.3   651.8  5070.2  652.11
  5091.1  653.29  5099.6  652.53  5191.6  653.64  5321.5  658.33    5579  664.82
  5614.6  664.61    5644   666.3  5650.2  665.67  5658.7  666.42  5664.9  665.07
  5671.3  665.88  5700.5  665.45  5708.3  666.26  5721.3  664.82  5750.7  665.57
#Mann= 5 ,-1 , 0
  3827.2      .1       0  4883.8     .12       0  4996.1     .07       0
    5003     .12       0  5032.3      .1       0
Bank Sta=4996.1,5003
XS Rating Curve= 0 ,0
Exp/Cntr=0.3,0.1

Type RM Length L Ch R = 1 ,24095   ,594,594,594
BEGIN DESCRIPTION:
Mapping XS 623f592f
END DESCRIPTION:
XS GIS Cut Line= 3
      1963889.18     13564209.35      1963481.15     13562646.74
      1963199.68     13561940.89
#Sta/Elev= 30
  3610.1  665.92  3955.7  661.18  4002.4  659.92  4083.3  659.52  4118.6  658.19
  4123.8  658.81  4204.7   656.9  4255.4  654.91  4296.7  654.02  4320.9   654.4
  4437.1  651.44  4586.1   650.5    4791  651.29  4978.9  650.13  4991.9  649.12
  5006.4  648.47  5006.9  647.67  5012.8  647.67  5013.3  648.47  5061.5   650.4
  5109.5  649.73  5192.4  650.12  5230.3     650  5323.9  651.39  5463.8  654.66
  5685.8  663.78  5829.9  670.49  5871.8  671.48  5901.5  673.67    5985  677.03
#Mann= 5 ,-1 , 0
  3610.1      .1       0  4991.9     .12       0  5006.4     .07       0
  5013.3     .12       0  5192.4      .1       0
Bank Sta=5006.4,5013.3
XS Rating Curve= 0 ,0
Exp/Cntr=0.3,0.1

Type RM Length L Ch R = 1 ,23501   ,65,65,65
BEGIN DESCRIPTION:
Mapping XS 5b3137c3
END DESCRIPTION:
XS GIS Cut Line= 6
      1964238.58      13564376.5      1963744.17     13562598.13
      1963817.09     13562500.91       1963865.7     13562434.94
      1963830.98     13562393.27      1963529.42     13562102.11
#Sta/Elev= 30
  2922.8  663.95    3213     659  3326.1  658.08  3349.9  658.68  3439.2  656.41
    3518  655.96  3625.9  653.68  3879.2  651.21    3960  649.19  4259.8  648.72
  4304.8  649.87  4346.3  648.93    4419  649.45  4616.2  648.28    4707  648.66
  4730.3  649.88  4740.7  649.27  4746.4  647.47  4761.5  645.28  5054.2   644.9
  5054.7   644.1  5060.7   644.1  5061.2   644.9    5086  645.39  5092.9  646.87
  5114.3   648.8  5135.4  648.49  5156.7  650.75  5234.4  652.83  5445.5  661.48
#Mann= 3 ,-1 , 0
  2922.8      .1       0  5054.2     .07       0  5061.2      .1       0
Bank Sta=5054.2,5061.2
XS Rating Curve= 0 ,0
Exp/Cntr=0.3,0.1

Type RM Length L Ch R = 1 ,23436   ,38,38,38
BEGIN DESCRIPTION:
Mapping XS 49709a14
END DESCRIPTION:
XS GIS Cut Line= 6
      1964297.17     13564428.58      1963789.31     13562695.35
      1963817.09     13562559.94      1963896.95     13562462.71
      1963907.37     13562396.74      1963563.62     13562042.58
#Sta/Elev= 30
  2823.2  664.16  3200.6  658.06  3311.3  657.51  3378.1   656.1  3383.3  656.74
  3389.6  655.52  3837.7  650.87  3910.5  649.02  4054.6  648.29  4275.9  649.54
  4304.1  648.62  4376.1  649.38    4587  648.08  4690.9  648.58  4776.3  651.07
  4876.7  651.08  4883.2  650.24  4971.5  650.91  4977.3  649.59  4993.2  650.95
  5078.4  652.33  5098.9  651.56  5131.3  647.91  5131.8  647.11  5137.8  647.11
  5138.3  647.91  5155.7  650.01  5169.9  649.94  5190.9  651.48    5463   660.9
#Mann= 3 ,-1 , 0
  2823.2      .1       0  5131.3     .07       0  5138.3      .1       0
Bank Sta=5131.3,5138.3
XS Rating Curve= 0 ,0
Exp/Cntr=0.3,0.1

Type RM Length L Ch R = 1 ,23398   ,490,490,490
BEGIN DESCRIPTION:
Mapping XS 5c3b823f
END DESCRIPTION:
XS GIS Cut Line= 6
      1964314.53     13564428.56      1963827.51     13562716.19
      1963945.56     13562459.24      1963949.03     13562365.49
      1963782.37     13562240.49      1963636.51     13562025.18
#Sta/Elev= 30
  2789.4  663.98  3198.6  657.43  3317.9  656.63  3375.3  654.96  3416.9  655.65
  3437.7   654.3  3801.6  650.99  3901.5  648.85  4490.2  648.91    4741  646.57
  4863.1  647.21  4912.7  649.01    4950  646.05  4973.2   645.4  4973.7   644.6
  4979.7   644.6  4980.2   645.4  4990.9  649.25  4997.5  648.33  5005.1  650.18
  5011.8  648.17  5019.4  649.87    5026  647.63  5033.6  648.64  5040.3  646.71
  5047.9  647.53  5054.5  646.49  5120.7  647.69  5241.5  653.46  5421.2   659.2
#Mann= 3 ,-1 , 0
  2789.4      .1       0  4973.2     .07       0  4980.2      .1       0
Bank Sta=4973.2,4980.2
XS Rating Curve= 0 ,0
Exp/Cntr=0.3,0.1

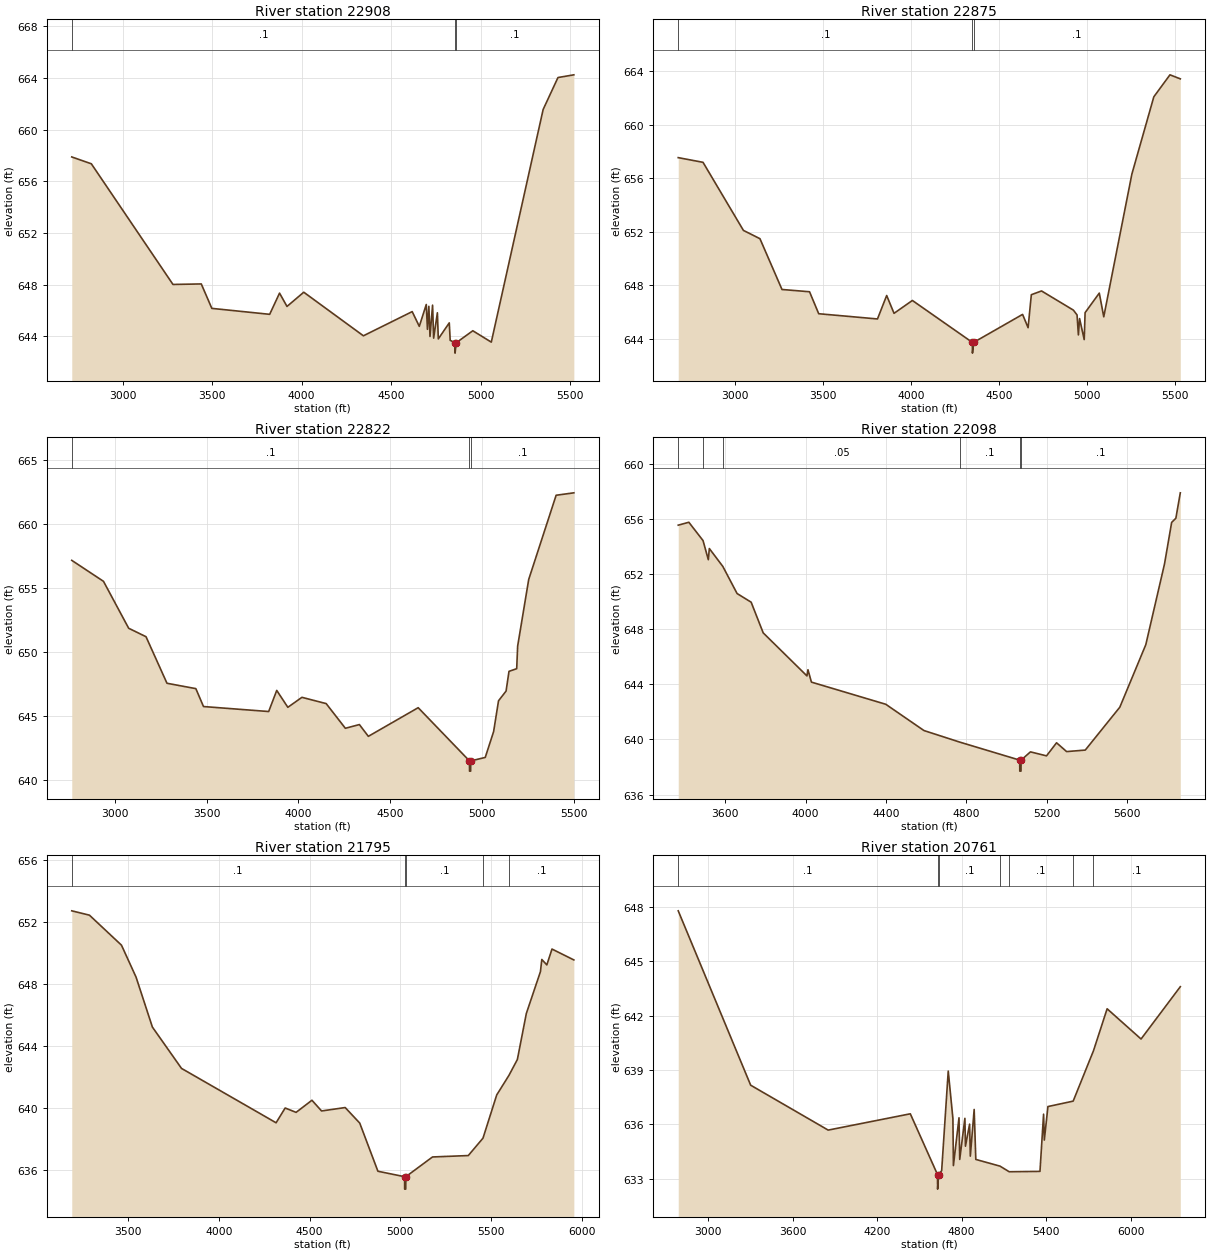
Type RM Length L Ch R = 1 ,22908   ,33,33,33
BEGIN DESCRIPTION:
Mapping XS 1c162e10
END DESCRIPTION:
XS GIS Cut Line= 6
      1964608.24     13564120.04      1964061.37     13562232.03
      1964109.11     13562193.31       1964334.8     13562158.24
      1964347.82     13562062.76      1964230.82     13561629.41
#Sta/Elev= 30
  2715.9  657.88  2825.3  657.35  3281.4  648.02  3439.5  648.06  3498.5  646.17
  3821.7  645.71  3876.8  647.35  3918.4  646.32  4012.1  647.42  4345.3  644.05
  4617.9  645.92  4657.6  644.78  4696.6  646.47  4703.1  644.55    4711  646.33
  4717.4     644  4731.8  646.42  4737.7  643.87  4758.7  645.83  4763.8  643.81
  4825.1  645.05  4830.2   643.7  4856.9  643.51  4857.4  642.71  4863.9  643.51
  4956.6  644.44  5059.9  643.56  5349.6  661.55  5432.4  664.02  5521.1  664.23
#Mann= 3 ,-1 , 0
  2715.9      .1       0  4856.9     .07       0  4863.9      .1       0
Bank Sta=4856.9,4863.9
XS Rating Curve= 0 ,0
Exp/Cntr=0.3,0.1

Type RM Length L Ch R = 1 ,22875   ,53,53,53
BEGIN DESCRIPTION:
UNT 033 in BCW 8.0
END DESCRIPTION:
XS GIS Cut Line= 6
      1964668.26     13564139.93      1964100.43     13562214.67
      1964349.99     13562188.63      1964367.36     13562169.09
      1964382.55     13562047.57      1964265.35     13561620.02
#Sta/Elev= 30
  2679.8  657.53  2820.5  657.18  3049.8   652.1  3143.7  651.48  3268.8  647.69
  3425.2  647.52  3477.3  645.88  3810.9  645.49  3863.1  647.24  3904.8  645.91
    4009  646.87  4349.6  643.74  4350.1  642.94  4356.6  643.74  4634.6  645.83
  4665.9  644.84  4684.3   647.3  4742.2  647.58  4922.9  646.15  4943.8  645.79
  4951.4   644.3  4958.1  645.52  4984.5  643.95  4989.5  645.96  5070.1  647.42
  5095.4  645.65  5255.2  656.31  5379.7  662.07  5471.2  663.71    5530  663.41
#Mann= 3 ,-1 , 0
  2679.8      .1       0  4349.6     .07       0  4356.6      .1       0
Bank Sta=4349.6,4356.6
XS Rating Curve= 0 ,0
Exp/Cntr=0.3,0.1

Type RM Length L Ch R = 1 ,22822   ,724,724,724
BEGIN DESCRIPTION:
Mapping XS 068620ce
END DESCRIPTION:
XS GIS Cut Line= 6
      1964690.71     13564072.33      1964143.83     13562253.73
      1964330.46     13562236.37      1964408.59     13562184.29
      1964430.29     13562114.84      1964317.44     13561646.07
#Sta/Elev= 30
  2765.7  657.16  2938.5  655.52  3075.8  651.85  3170.2  651.19  3284.4  647.55
  3441.7  647.13  3483.4  645.73  3838.5  645.34  3882.4  646.99  3942.9  645.67
  4019.7  646.45  4151.7  645.96  4256.2  644.03  4332.6  644.32  4381.5   643.4
    4653  645.64  4932.3  641.48  4932.8  640.68  4938.8  640.68  4939.3  641.48
  5018.3  641.75  5063.9  643.77  5090.7  646.18  5131.8  646.94  5147.7  648.48
  5189.7  648.69  5194.8  650.45  5255.2  655.67  5404.5  662.25    5501  662.44
#Mann= 3 ,-1 , 0
  2765.7      .1       0  4932.3     .07       0  4939.3      .1       0
Bank Sta=4932.3,4939.3
XS Rating Curve= 0 ,0
Exp/Cntr=0.3,0.1

Type RM Length L Ch R = 1 ,22098   ,303,303,303
BEGIN DESCRIPTION:
UNT 033 in BCW 7.0
END DESCRIPTION:
XS GIS Cut Line= 3
      1964963.83     13564057.89      1965044.52     13562073.82
      1964624.97     13561774.98
#Sta/Elev= 30
  3365.3  655.58  3418.2  655.79  3488.8  654.46  3515.2  653.07  3520.2  653.88
  3587.4  652.58  3658.4  650.61  3728.5  649.98  3788.5  647.75  4006.5  644.62
  4011.5  645.07  4028.7  644.17    4399  642.56  4589.2  640.65  4769.6   639.8
  5066.1   638.5  5066.6   637.7  5072.6   637.7  5073.1   638.5  5119.6   639.1
  5199.7  638.81  5249.7  639.76  5299.8  639.12  5392.7  639.23  5564.9  642.35
  5694.2  646.89  5787.4  652.76    5823  655.78  5843.9  656.08  5866.1  657.93
#Mann= 6 ,-1 , 0
  3365.3     .05       0  3488.8     .08       0  3587.4     .05       0
  4769.6      .1       0  5066.1     .07       0  5073.1      .1       0
Bank Sta=5066.1,5073.1
XS Rating Curve= 0 ,0
Exp/Cntr=0.3,0.1

Type RM Length L Ch R = 1 ,21795   ,1034,1034,1034
BEGIN DESCRIPTION:
UNT 033 in BCW 6.0
END DESCRIPTION:
XS GIS Cut Line= 3
      1965125.29     13564068.32      1965232.02     13561886.32
      1964846.57       13561454.
#Sta/Elev= 30
  3191.2  652.71  3288.6  652.43  3464.8   650.5  3544.9  648.45    3635  645.23
  3795.2  642.57  4315.9  639.07  4365.9  640.02    4426  639.74  4513.4  640.52
  4566.2  639.83  4696.3  640.05  4776.4  639.05  4876.5  635.95  5023.2   635.6
  5023.7   634.8  5029.7   634.8  5030.2   635.6  5176.9  636.87    5374  636.96
  5454.9  638.08  5530.4  640.86  5597.7  642.12  5644.1  643.14  5693.4   646.1
  5771.2   648.8  5778.7  649.58  5806.3  649.23  5834.7  650.25    5955  649.55
#Mann= 5 ,-1 , 0
  3191.2      .1       0  5023.2     .07       0  5030.2      .1       0
  5454.9     .05       0  5597.7      .1       0
Bank Sta=5023.2,5030.2
XS Rating Curve= 0 ,0
Exp/Cntr=0.3,0.1

Type RM Length L Ch R = 1 ,20761   ,34,34,34
BEGIN DESCRIPTION:
Mapping XS 44062390
END DESCRIPTION:
XS GIS Cut Line= 6
      1965625.29     13563708.95      1965679.98     13562146.44
      1965781.85     13561769.31       1966005.8     13561672.96
      1965599.55     13561730.25      1964932.91     13561113.08
#Sta/Elev= 30
  2788.2  647.79  3302.5  638.16  3852.8  635.68    4436  636.58  4629.3  633.22
  4629.8  632.42  4636.4  633.22  4658.6  633.44  4705.3  638.94  4738.4  636.32
    4742  633.72  4781.7  636.36  4786.8  634.06  4823.5  636.33  4827.5  634.79
  4856.9  636.01  4862.1  634.24  4889.3  636.82    4901  634.06  5072.7  633.69
    5138  633.38  5356.6   633.4  5382.2  636.56  5387.5  635.13  5413.1  636.98
  5592.3  637.28  5736.4  640.06  5833.4  642.38  6074.3  640.71    6353   643.6
#Mann= 7 ,-1 , 0
  2788.2      .1       0  4629.3     .07       0  4636.4      .1       0
  5072.7     .05       0    5138      .1       0  5592.3     .05       0
  5736.4      .1       0
Bank Sta=4629.3,4636.4
XS Rating Curve= 0 ,0
Exp/Cntr=0.3,0.1