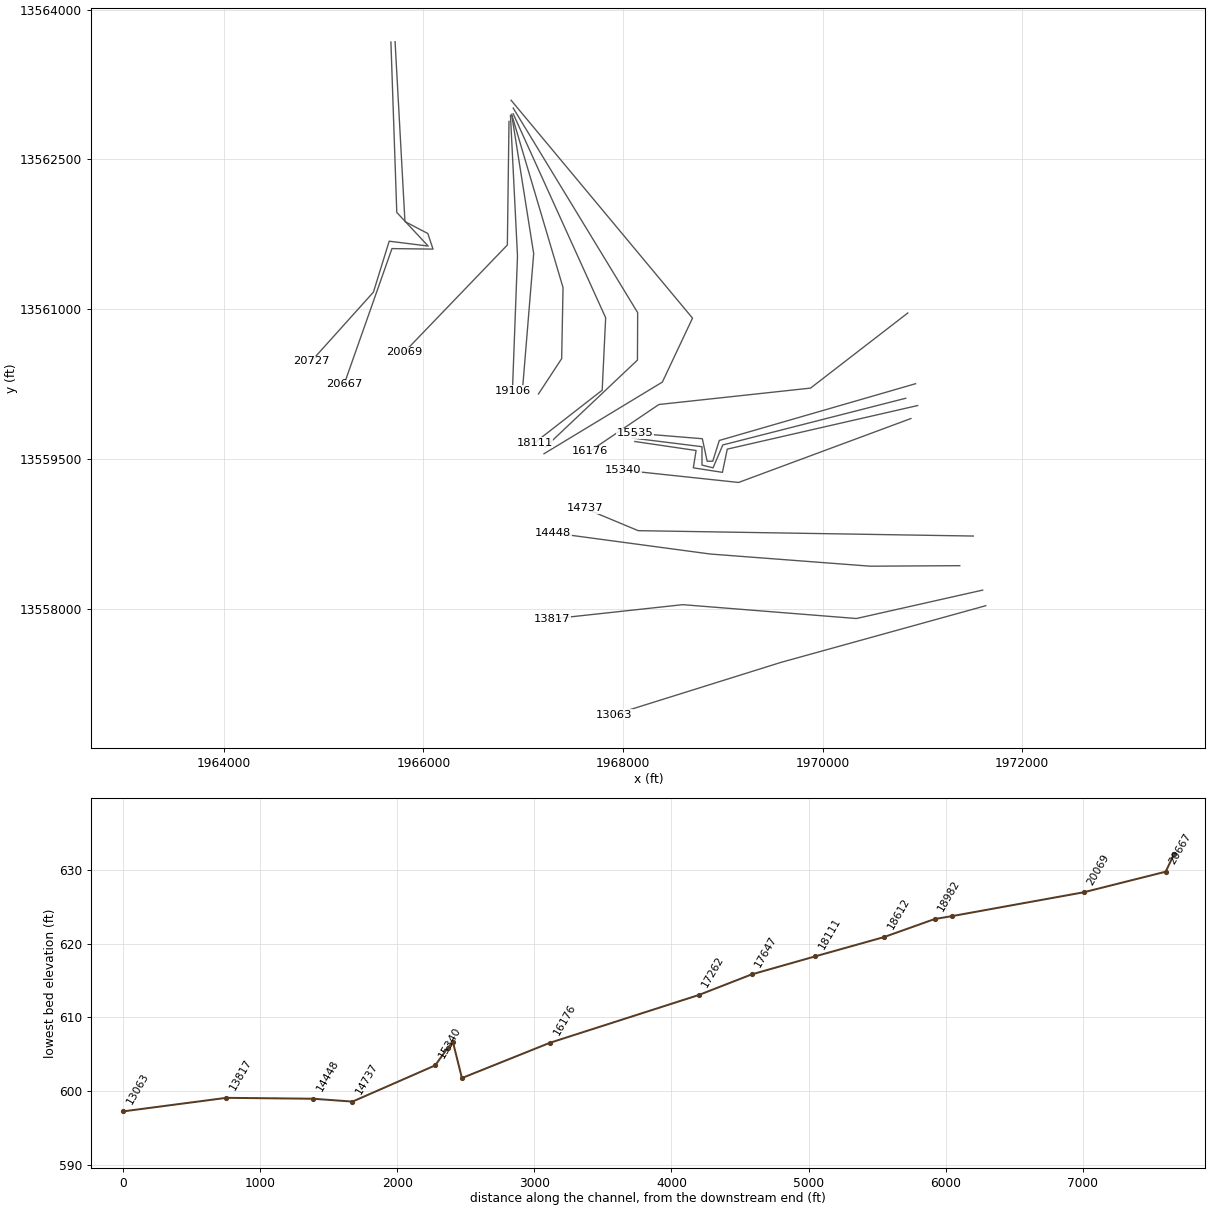
HEC-RAS study UNT 033 in BCW.prj: UNT 033 in BCW Base Level Engineering

--- UNT 033 in BCW.g01 (geometry) --- (continued)

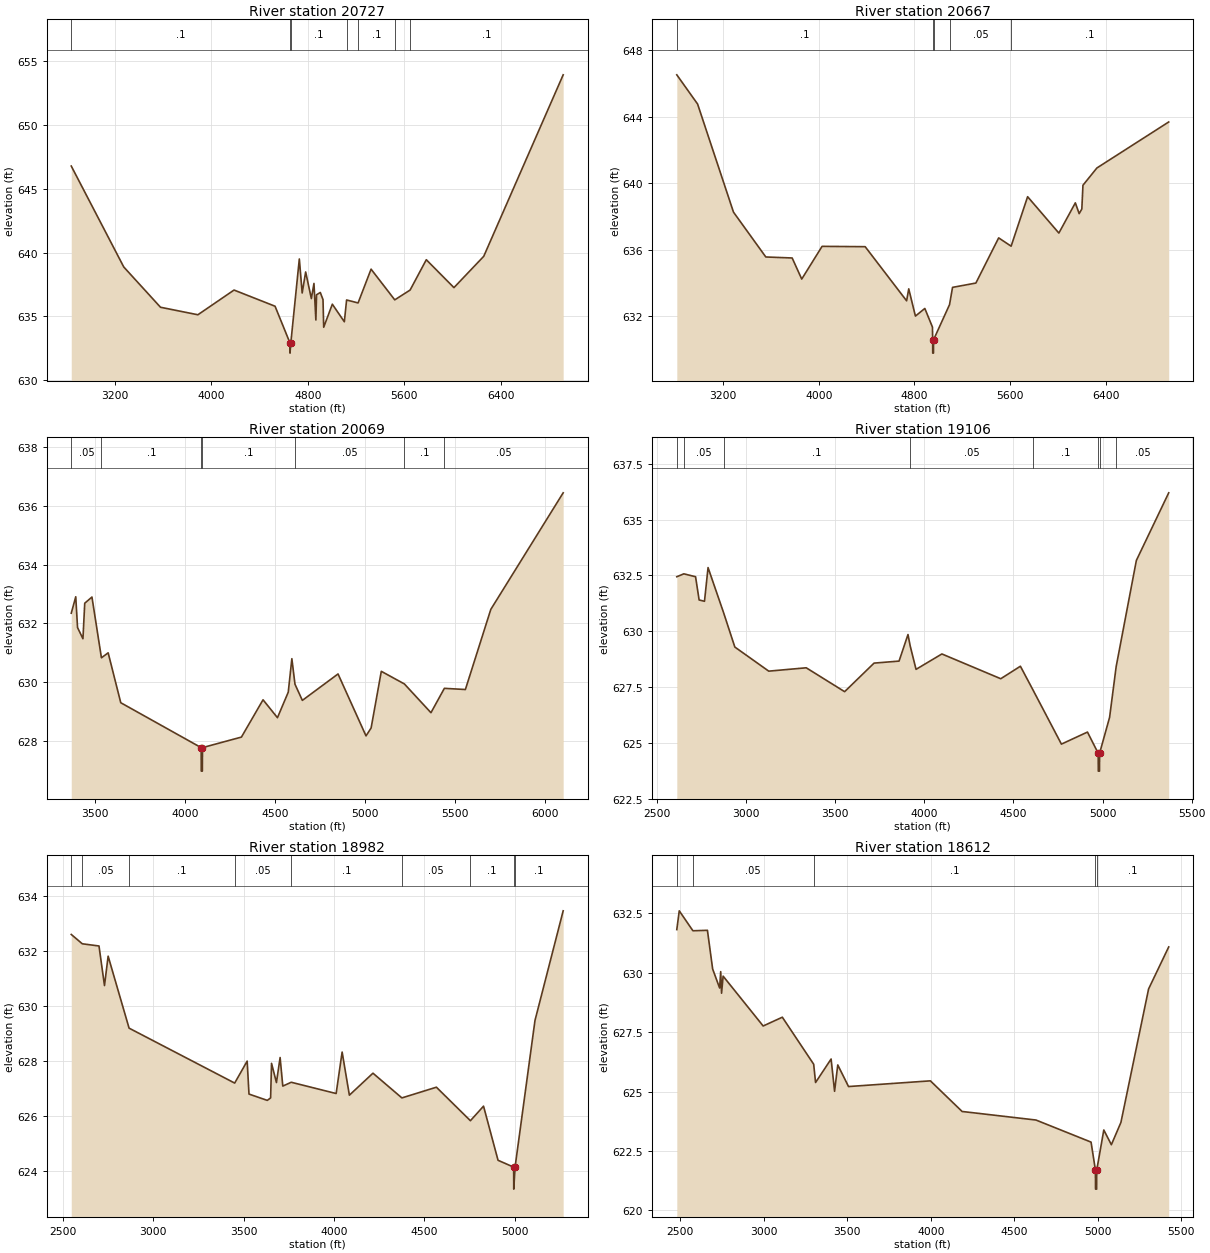
Type RM Length L Ch R = 1 ,20727   ,60,60,60
BEGIN DESCRIPTION:
UNT 033 in BCW 5.0
END DESCRIPTION:
XS GIS Cut Line= 6
        1965675.     13563675.02      1965733.76     13561967.92
      1966048.34     13561631.12      1965657.71     13561679.73
      1965499.73     13561169.31      1964874.98     13560474.98
#Sta/Elev= 30
  2837.3  646.79    3273  638.87  3577.8  635.71  3887.9  635.12  4188.1  637.06
  4528.3  635.79    4652  632.91  4652.5  632.11  4659.1  632.91  4729.7   639.5
  4753.3  636.83  4782.3  638.48  4829.5  636.39  4851.1  637.58    4867  634.71
  4872.7  636.69  4903.6  636.87  4926.2  636.31  4931.9  634.14  5003.6  635.95
  5103.2  634.57  5121.9  636.28  5217.3  636.05    5325   638.7  5521.6  636.29
  5648.9  637.06  5783.3  639.44  6012.7  637.25  6260.1  639.71    6919  653.95
#Mann= 7 ,-1 , 0
  2837.3      .1       0    4652     .07       0  4659.1      .1       0
  5121.9     .05       0  5217.3      .1       0  5521.6     .05       0
  5648.9      .1       0
Bank Sta=4652,4659.1
XS Rating Curve= 0 ,0
Exp/Cntr=0.3,0.1

Type RM Length L Ch R = 1 ,20667   ,598,598,598
BEGIN DESCRIPTION:
Mapping XS f436bab6
END DESCRIPTION:
XS GIS Cut Line= 6
      1965716.74     13563678.71       1965815.7      13561876.6
      1966044.87     13561756.81      1966096.95     13561600.56
      1965685.49     13561605.77      1965206.95     13560248.18
#Sta/Elev= 30
  2811.7  646.52  2985.7  644.76  3286.1  638.25  3556.5  635.55  3776.9  635.49
    3857  634.22  4027.2  636.19  4387.8  636.17  4734.6  632.91  4752.4  633.63
  4808.2  631.99  4886.9  632.45  4950.7  631.33  4952.6  630.56  4953.1  629.76
  4959.2  629.76  4959.7  630.56  5093.7  632.68  5118.8  633.72  5314.1  633.98
  5504.8   636.7    5609   636.2    5747  639.18  6008.5  636.99  6146.3  638.81
  6178.2  638.16  6200.6  638.44    6210  639.87  6326.6  640.91  6927.6  643.68
#Mann= 5 ,-1 , 0
  2811.7      .1       0  4952.6     .07       0  4959.7      .1       0
  5093.7     .05       0    5609      .1       0
Bank Sta=4952.6,4959.7
XS Rating Curve= 0 ,0
Exp/Cntr=0.3,0.1

Type RM Length L Ch R = 1 ,20069   ,963,963,963
BEGIN DESCRIPTION:
UNT 033 in BCW 4.0
END DESCRIPTION:
XS GIS Cut Line= 3
      1966858.34     13562879.92      1966841.87     13561641.82
       1965806.7     13560565.42
#Sta/Elev= 30
  3366.9  632.35  3391.8  632.91  3401.8  631.86  3431.8  631.48  3441.8  632.69
  3481.8   632.9  3534.4  630.83  3571.8     631  3641.8   629.3  4088.3  627.77
  4088.8  626.97  4094.9  626.97  4095.4  627.77  4311.9  628.13  4431.9   629.4
  4511.9  628.79  4571.9  629.66  4591.9   630.8  4609.2  629.93  4650.2  629.38
  4848.3  630.28  5003.7  628.17    5032  628.44  5088.6  630.37  5216.7  629.94
  5364.3  628.96  5438.8  629.79  5555.5  629.75  5696.7  632.48  6098.5  636.45
#Mann= 7 ,-1 , 0
  3366.9     .05       0  3534.4      .1       0  4088.3     .03       0
  4095.4      .1       0  4609.2     .05       0  5216.7      .1       0
  5438.8     .05       0
Bank Sta=4088.3,4095.4
XS Rating Curve= 0 ,0
Exp/Cntr=0.3,0.1

Type RM Length L Ch R = 1 ,19106   ,124,124,124
BEGIN DESCRIPTION:
Mapping XS 3fabe7cb
END DESCRIPTION:
XS GIS Cut Line= 3
      1966873.04     13562940.06      1966943.45     13561530.45
      1966892.95     13560183.66
#Sta/Elev= 30
  2612.2  632.44  2651.6  632.57  2717.4  632.44  2737.4   631.4  2767.5  631.34
  2787.5  632.85  2874.2  630.84  2937.7  629.29  3127.9  628.21  3338.2  628.36
  3553.5  627.29  3718.6  628.57  3858.8  628.66  3908.9  629.85    3921  629.35
  3954.1  628.29  4099.1  628.98  4429.3  627.87  4539.4  628.43  4608.5  627.39
  4769.5  624.94  4915.5  625.48  4975.8  624.53  4976.4  623.73  4982.9  623.73
  4983.6  624.53  5039.7  626.14  5076.5  628.41  5189.8  633.17  5371.3   636.2
#Mann= 8 ,-1 , 0
  2612.2      .1       0  2651.6     .05       0  2874.2      .1       0
    3921     .05       0  4608.5      .1       0  4975.8     .07       0
  4983.6      .1       0  5076.5     .05       0
Bank Sta=4975.8,4983.6
XS Rating Curve= 0 ,0
Exp/Cntr=0.3,0.1

Type RM Length L Ch R = 1 ,18982   ,370,370,370
BEGIN DESCRIPTION:
Mapping XS 66128a51
END DESCRIPTION:
XS GIS Cut Line= 3
      1966886.92     13562936.63      1967105.68     13561555.24
      1966997.11     13560235.71
#Sta/Elev= 30
  2545.4  632.61  2606.5  632.27  2698.9  632.19  2729.3  630.75  2749.5  631.82
  2865.4   629.2  3449.9   627.2    3519     628  3529.1   626.8  3630.4  626.57
  3648.8  626.66  3653.8  627.92    3681  627.22  3701.3  628.13  3716.2  627.09
  3762.8  627.23  4011.4  626.82  4044.6  628.33  4084.7  626.76  4215.2  627.56
  4375.3  626.66  4566.3  627.05  4754.6  625.83  4827.2  626.36  4907.5  624.39
  4993.9  624.14  4994.5  623.34  5001.7  624.14    5112  629.48    5268  633.47
#Mann= 9 ,-1 , 0
  2545.4      .1       0  2606.5     .05       0  2865.4      .1       0
  3449.9     .05       0  3762.8      .1       0  4375.3     .05       0
  4754.6      .1       0  4993.9     .07       0  5001.7      .1       0
Bank Sta=4993.9,5001.7
XS Rating Curve= 0 ,0
Exp/Cntr=0.3,0.1

Type RM Length L Ch R = 1 ,18612   ,501,501,501
BEGIN DESCRIPTION:
Mapping XS 8db6c047
END DESCRIPTION:
XS GIS Cut Line= 4
      1966884.85     13562950.81      1967399.89     13561214.92
      1967386.01     13560503.11      1967153.73      13560149.5
#Sta/Elev= 30
  2478.8  631.82  2493.5  632.61  2575.3  631.77  2662.2  631.79  2693.5  630.16
  2735.2  629.36  2741.7  630.05  2746.9  629.14  2756.1  629.86    2996  627.76
  3110.7  628.13  3298.5  626.15  3309.8  625.38  3402.8  626.37  3423.6  625.01
  3442.7  626.12  3507.1  625.21  3997.3  625.45  4187.3  624.16  4629.5   623.8
  4959.5  622.87  4985.6  621.69  4986.3  620.89  4992.8  620.89  4993.4  621.69
  5035.8  623.38  5081.1  622.76  5138.3   623.7    5304  629.32  5424.5  631.09
#Mann= 5 ,-1 , 0
  2478.8      .1       0  2575.3     .05       0  3298.5      .1       0
  4985.6     .07       0  4993.4      .1       0
Bank Sta=4985.6,4993.4
XS Rating Curve= 0 ,0
Exp/Cntr=0.3,0.1

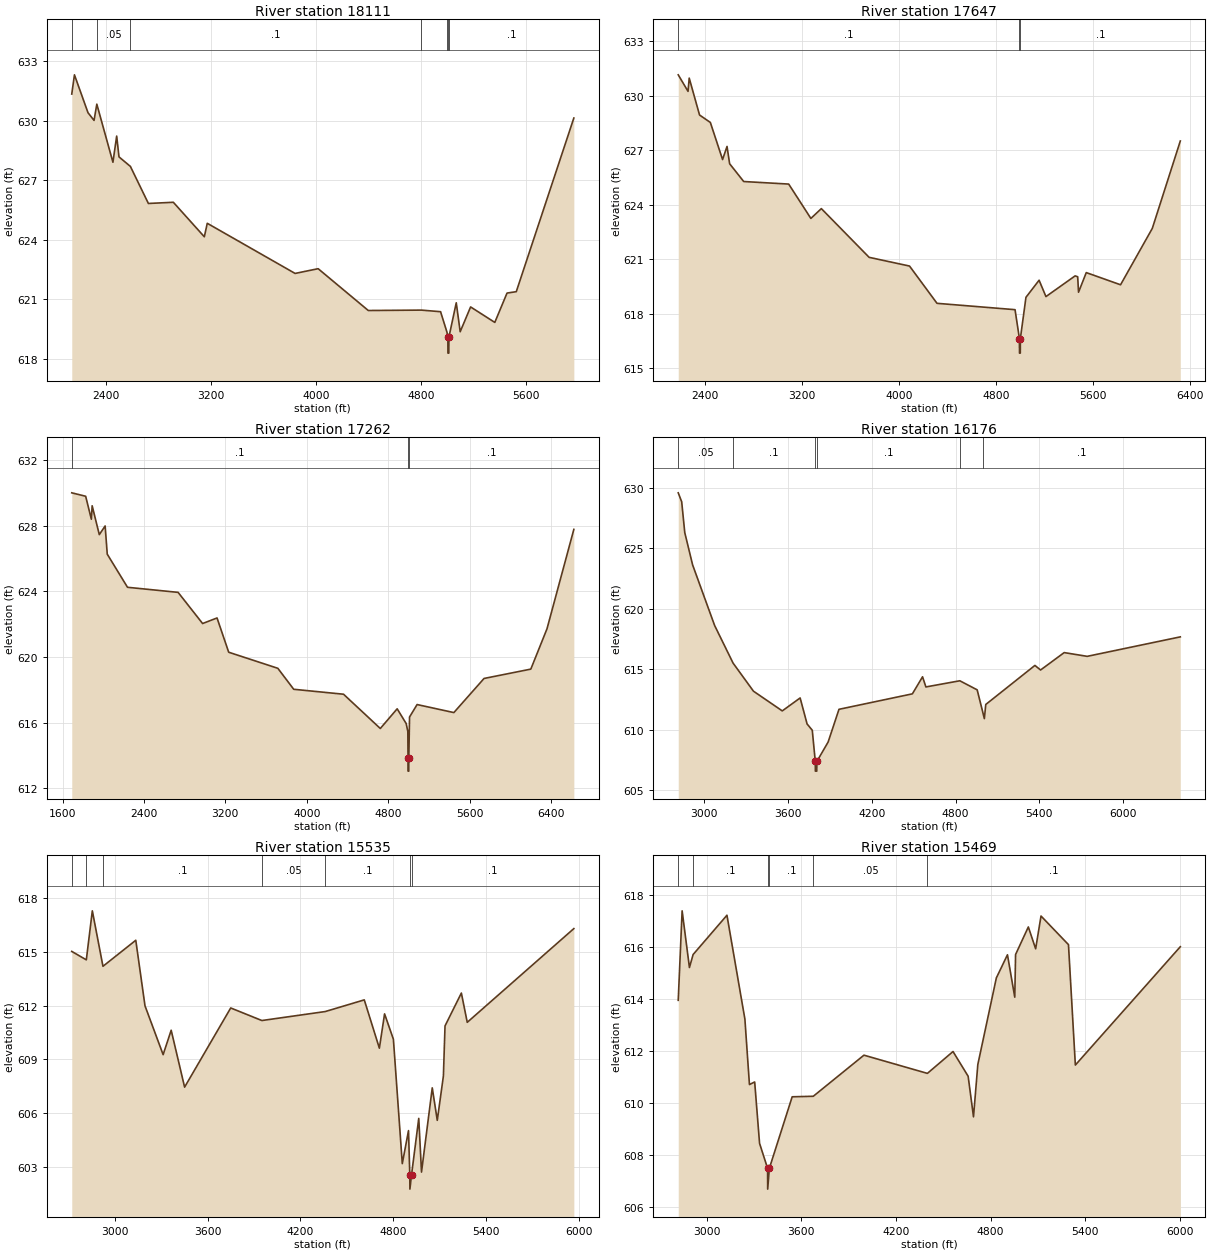
Type RM Length L Ch R = 1 ,18111   ,464,464,464
BEGIN DESCRIPTION:
Mapping XS 89d9033a
END DESCRIPTION:
XS GIS Cut Line= 4
      1966900.46     13562956.06      1967826.98     13560912.83
      1967792.26     13560187.14      1967114.57     13559659.62
#Sta/Elev= 30
  2136.3  631.35  2156.7  632.32    2260  630.41  2306.2  630.02  2327.3  630.84
  2450.2  627.91  2478.8  629.23  2496.4  628.18  2583.3   627.7  2720.6  625.83
  2910.8  625.89  3147.2  624.15  3169.6  624.83  3839.4   622.3  4015.1  622.54
  4397.6  620.43  4803.3  620.45  4948.8  620.37  4997.4  619.34  5004.4  619.08
  5005.1  618.28  5011.6  618.28  5012.2  619.08  5068.4  620.82  5098.4  619.36
  5177.8  620.61  5362.4  619.83  5455.6  621.31  5526.1  621.38  5965.1  630.14
#Mann= 7 ,-1 , 0
  2136.3      .1       0  2327.3     .05       0  2583.3      .1       0
  4803.3     .12       0  4997.4      .1       0  5004.4     .07       0
  5012.2      .1       0
Bank Sta=5004.4,5012.2
XS Rating Curve= 0 ,0
Exp/Cntr=0.3,0.1

Type RM Length L Ch R = 1 ,17647   ,385,385,385
BEGIN DESCRIPTION:
Mapping XS c7c93904
END DESCRIPTION:
XS GIS Cut Line= 4
      1966900.48     13563013.32      1968147.72     13560964.05
      1968145.55     13560488.79      1967224.71     13559618.76
#Sta/Elev= 30
  2181.5  631.14  2262.4  630.23    2272  630.96  2357.3  628.93  2446.4  628.52
  2547.2  626.48    2584   627.2  2605.3  626.25  2721.5  625.27  3092.6  625.13
  3275.5  623.24  3361.9  623.78  3755.9   621.1  4089.2  620.62  4315.8  618.57
  4959.5  618.22  4995.6  616.63  4996.3  615.83  5002.8  615.83  5003.4  616.63
  5049.5   618.9  5157.8  619.84  5214.4  618.94  5455.1  620.08  5476.2  620.03
  5483.1  619.18    5547  620.26  5829.8  619.59  6091.5  622.69  6322.6   627.5
#Mann= 3 ,-1 , 0
  2181.5      .1       0  4995.6     .07       0  5003.4      .1       0
Bank Sta=4995.6,5003.4
XS Rating Curve= 0 ,0
Exp/Cntr=0.3,0.1

Type RM Length L Ch R = 1 ,17262   ,1086,1086,1086
BEGIN DESCRIPTION:
Mapping XS a3c11d74
END DESCRIPTION:
XS GIS Cut Line= 4
      1966879.65     13563091.44      1968697.34     13560909.18
      1968395.26     13560268.55      1967209.01     13559550.56
#Sta/Elev= 30
  1690.4  630.01    1827   629.8    1883   628.4  1890.8  629.22  1961.1  627.46
  2018.4  627.99  2039.2  626.27  2238.3  624.25  2735.6  623.94  2976.4  622.04
  3118.3  622.38  3232.9  620.29  3715.9  619.31  3872.1  618.03  4361.5  617.73
  4723.1  615.64  4888.9  616.84  4977.4  615.94  4993.6  615.46  4995.6  613.84
  4996.2  613.04  5002.8  613.04  5003.4  613.84  5010.5  616.34  5084.7   617.1
    5446  616.61  5742.8  618.69  6202.5  619.26  6361.6  621.72  6625.4  627.78
#Mann= 3 ,-1 , 0
  1690.4      .1       0  4995.6     .07       0  5003.4      .1       0
Bank Sta=4995.6,5003.4
XS Rating Curve= 0 ,0
Exp/Cntr=0.3,0.1

Type RM Length L Ch R = 1 ,16176   ,641,641,641
BEGIN DESCRIPTION:
Mapping XS 8bc35be2
END DESCRIPTION:
XS GIS Cut Line= 4
       1970854.6     13560960.52      1969880.36      13560208.2
      1968360.41     13560043.83      1967668.59     13559576.12
#Sta/Elev= 30
    2814  629.57  2838.8  628.83  2860.8  626.28    2917  623.61  3074.6   618.6
  3206.8  615.49  3352.6  613.17  3558.9  611.54  3686.8  612.61  3736.6  610.46
  3773.7  609.94  3795.3  607.36  3795.9  606.56  3805.9  606.56  3806.6  607.36
  3887.4  608.97  3964.9  611.67  4490.5  612.95  4563.3  614.36  4587.3  613.52
  4830.2  614.03  4954.4  613.28  4993.7  611.47  5005.8   610.9  5015.9  612.07
  5367.9   615.3  5408.2  614.92  5577.4  616.36  5742.2  616.05  6408.8  617.66
#Mann= 6 ,-1 , 0
    2814     .05       0  3206.8      .1       0  3795.3     .07       0
  3806.6      .1       0  4830.2     .12       0  4993.7      .1       0
Bank Sta=3795.3,3806.6
XS Rating Curve= 0 ,0
Exp/Cntr=0.3,0.1

Type RM Length L Ch R = 1 ,15535   ,66,66,66
BEGIN DESCRIPTION:
Mapping XS 7a5b3d28
END DESCRIPTION:
XS GIS Cut Line= 6
      1970932.78     13560252.22      1968965.87     13559683.67
      1968899.89     13559475.33      1968844.34     13559475.33
      1968795.73     13559701.03      1968119.31     13559756.53
#Sta/Elev= 30
  2721.3  615.02  2815.5  614.55  2854.3  617.28  2923.1  614.19  3135.4  615.64
    3195  611.99  3312.3  609.27  3364.4  610.63  3451.2  607.46  3749.5  611.87
  3951.1  611.17  4360.9  611.67  4613.5  612.32  4711.1  609.63  4744.8  611.54
  4801.8  610.13  4859.4   603.2  4899.6  605.04  4907.9  602.58  4908.6  601.78
  4919.2  602.58  4965.9  605.72  4983.7  602.73  5053.2  607.42  5085.7  605.61
  5125.3  608.08  5135.8  610.87  5241.5   612.7  5279.6  611.07  5969.1  616.29
#Mann= 7 ,-1 , 0
  2721.3      .1       0  2815.5     .05       0  2923.1      .1       0
  3951.1     .05       0  4360.9      .1       0  4907.9     .07       0
  4919.2      .1       0
Bank Sta=4907.9,4919.2
XS Rating Curve= 0 ,0
Exp/Cntr=0.3,0.1

Type RM Length L Ch R = 1 ,15469   ,39,39,39
BEGIN DESCRIPTION:
Mapping XS 7e75d2fe
END DESCRIPTION:
XS GIS Cut Line= 6
      1970833.75     13560106.37      1969000.59     13559638.53
      1968903.37     13559409.36      1968792.26     13559437.14
      1968792.26     13559621.17      1968094.37     13559707.97
#Sta/Elev= 30
  2818.7  613.96  2843.4   617.4  2889.8  615.22  2913.1  615.72  3127.7  617.23
  3241.5  613.24  3270.4  610.72  3303.6  610.82  3334.6  608.46  3385.4   607.5
  3386.1   606.7  3396.7   607.5  3541.5  610.25  3675.3  610.27  3996.7  611.85
  4399.2  611.15  4561.7  611.99  4657.6  611.04  4691.6  609.48    4719  611.49
  4836.5  614.82    4907  615.71  4953.4  614.08  4958.5  615.72  5039.4  616.78
  5085.8  615.94  5119.9   617.2    5294   616.1  5337.7  611.47  6003.4  616.02
#Mann= 6 ,-1 , 0
  2818.7     .08       0  2913.1      .1       0  3385.4     .07       0
  3396.7      .1       0  3675.3     .05       0  4399.2      .1       0
Bank Sta=3385.4,3396.7
XS Rating Curve= 0 ,0
Exp/Cntr=0.3,0.1

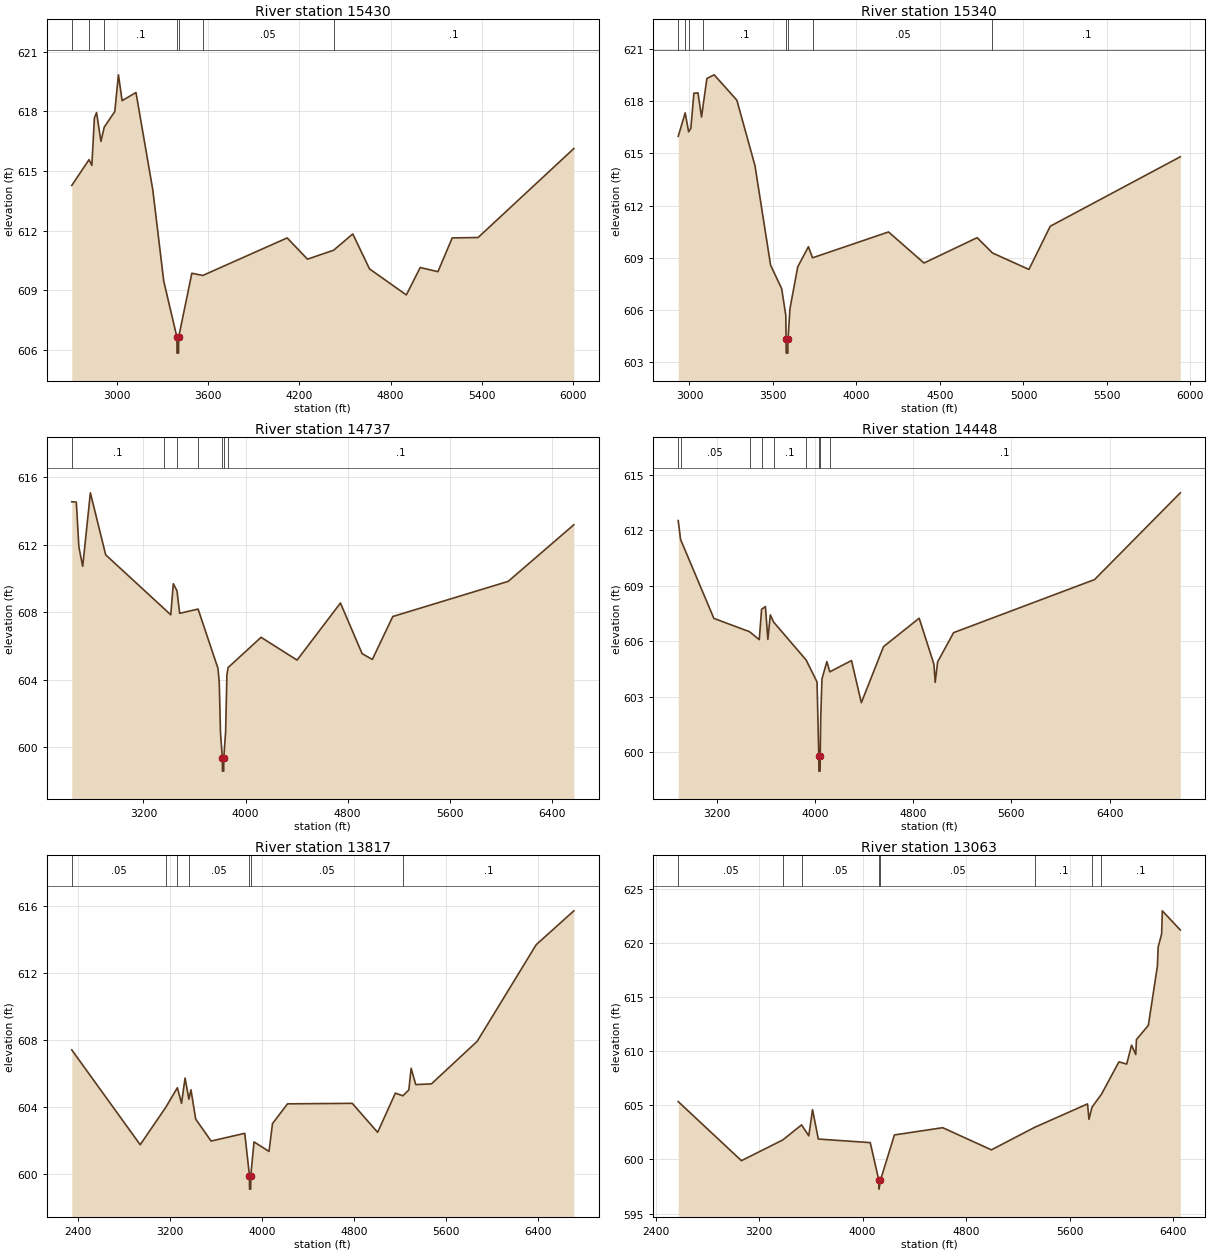
Type RM Length L Ch R = 1 ,15430   ,90,90,90
BEGIN DESCRIPTION:
Mapping XS c495f884
END DESCRIPTION:
XS GIS Cut Line= 6
      1970953.56     13560033.45      1969045.73     13559596.86
      1968997.12     13559364.22      1968705.45     13559409.36
      1968733.23     13559582.97      1968119.29     13559673.15
#Sta/Elev= 30
  2706.1  614.27  2819.4  615.57    2838  615.28  2854.7  617.67  2868.8  617.94
  2897.7  616.49  2919.5  617.21  2988.6  617.99  3012.4  619.84  3036.7  618.54
  3127.7  618.95  3238.1  614.05  3309.9  609.46  3396.6  606.63  3397.2  605.83
  3407.2  605.83  3407.9  606.63  3494.5  609.85  3566.4  609.74  4120.3  611.63
  4253.7  610.56  4425.4  611.01  4551.2  611.83  4661.1  610.07  4902.8  608.76
    4994  610.14  5110.4  609.93  5203.9  611.63    5374  611.65  6002.6  616.13
#Mann= 7 ,-1 , 0
  2706.1      .1       0  2819.4     .08       0  2919.5      .1       0
  3396.6     .07       0  3407.9      .1       0  3566.4     .05       0
  4425.4      .1       0
Bank Sta=3396.6,3407.9
XS Rating Curve= 0 ,0
Exp/Cntr=0.3,0.1

Type RM Length L Ch R = 1 ,15340   ,603,603,603
BEGIN DESCRIPTION:
Mapping XS c89973d4
END DESCRIPTION:
XS GIS Cut Line= 3
      1970885.92     13559903.27      1969158.97     13559262.89
      1968000.58     13559386.21
#Sta/Elev= 30
  2932.6  615.99  2974.2  617.34  2994.9  616.25  3008.2  616.45  3026.3  618.47
  3050.9  618.49  3072.2   617.1  3081.6  617.76  3104.2  619.32  3147.8  619.53
  3283.7  618.07  3392.2   614.3  3485.7  608.57  3552.2  607.21  3576.8  605.67
  3578.5   604.3  3579.2   603.5  3589.2   603.5  3589.8   604.3  3601.9  606.07
  3648.2  608.47  3712.2  609.63  3736.8  608.99  4192.1  610.48  4404.5  608.69
  4722.6  610.15  4814.4  609.27  5032.7  608.32  5160.6  610.81  5939.4  614.81
#Mann= 8 ,-1 , 0
  2932.6      .1       0  2974.2     .08       0  2994.9     .05       0
  3081.6      .1       0  3578.5     .07       0  3589.8      .1       0
  3736.8     .05       0  4814.4      .1       0
Bank Sta=3578.5,3589.8
XS Rating Curve= 0 ,0
Exp/Cntr=0.3,0.1

Type RM Length L Ch R = 1 ,14737   ,289,289,289
BEGIN DESCRIPTION:
Mapping XS 857befe7
END DESCRIPTION:
XS GIS Cut Line= 3
      1971510.84     13558726.17      1968153.24     13558779.99
      1967620.24     13559002.22
#Sta/Elev= 30
  2637.8  614.53  2673.6  614.51  2693.6  611.85  2723.6  610.71  2783.7  615.06
  2903.7  611.39  3363.9  608.19  3413.7  607.84  3433.7  609.68  3462.3  609.27
  3483.7  607.93  3628.1  608.18  3783.8  604.67  3793.8  603.86  3803.8  600.83
  3818.1  599.39  3818.8  598.59  3828.8  598.59  3829.5  599.39  3843.8  600.93
  3853.8  604.29  3863.3  604.72  4121.8  606.51  4403.9  605.16  4743.8  608.54
  4913.9  605.54  4993.9   605.2    5154  607.74  6058.9  609.82  6573.3  613.17
#Mann= 7 ,-1 , 0
  2637.8      .1       0  3363.9     .08       0  3462.3      .1       0
  3628.1     .16       0  3818.1     .07       0  3829.5     .16       0
  3863.3      .1       0
Bank Sta=3818.1,3829.5
XS Rating Curve= 0 ,0
Exp/Cntr=0.3,0.1

Type RM Length L Ch R = 1 ,14448   ,631,631,631
BEGIN DESCRIPTION:
Mapping XS 8edb3ff5
END DESCRIPTION:
XS GIS Cut Line= 4
      1971375.49     13558429.29      1970479.63     13558424.09
      1968875.59     13558545.93      1967302.58     13558757.41
#Sta/Elev= 30
    2885  612.53    2904  611.51  3175.5  607.24  3465.9  606.52  3545.5  606.09
  3564.2  607.73  3595.5  607.88  3615.5   606.1  3635.5  607.43  3662.5  607.04
  3927.2  604.99  4016.2   603.8  4030.5  599.78  4031.2  598.98  4041.2  598.98
  4041.9  599.78  4046.3  601.91  4056.3  603.97  4096.4   604.9  4120.1  604.35
    4297  604.96  4377.2  602.68  4557.7  605.71  4848.6  607.25  4968.9  604.76
  4978.9  603.78    4999  604.89  5129.4  606.47  6278.1  609.34  6976.7  614.03
#Mann= 9 ,-1 , 0
    2885      .1       0    2904     .05       0  3465.9      .1       0
  3564.2     .08       0  3662.5      .1       0  3927.2     .16       0
  4030.5     .07       0  4041.9     .16       0  4120.1      .1       0
Bank Sta=4030.5,4041.9
XS Rating Curve= 0 ,0
Exp/Cntr=0.3,0.1

Type RM Length L Ch R = 1 ,13817   ,754,754,754
BEGIN DESCRIPTION:
Mapping XS cf3ba813
END DESCRIPTION:
XS GIS Cut Line= 4
      1971604.68     13558184.51      1970339.15     13557899.89
      1968599.42     13558038.67      1967290.42     13557896.43
#Sta/Elev= 30
  2348.7  607.41  2942.9  601.75  3165.4  603.99  3265.5  605.15  3301.6  604.22
  3332.3  605.73  3365.6  604.47  3383.6  605.03  3424.6  603.28  3558.6  601.97
  3850.6  602.43  3891.6   599.9  3892.2   599.1  3902.3   599.1    3903   599.9
  3930.9  601.92  4061.3  601.35  4091.4  603.01  4221.8  604.19  4783.8  604.22
  5004.3  602.49  5158.1  604.83  5223.3  604.67  5275.1  605.02  5295.2  606.31
  5335.3  605.34  5471.2  605.38  5868.3  607.92  6381.3  613.69  6707.8  615.71
#Mann= 7 ,-1 , 0
  2348.7     .05       0  3165.4      .1       0  3265.5     .08       0
  3365.6     .05       0  3891.6    .035       0    3903     .05       0
  5223.3      .1       0
Bank Sta=3891.6,3903
XS Rating Curve= 0 ,0
Exp/Cntr=0.3,0.1

Type RM Length L Ch R = 1 ,13063   ,515,515,515
BEGIN DESCRIPTION:
Mapping XS bb4ffef4
END DESCRIPTION:
XS GIS Cut Line= 3
      1971635.89     13558028.26       1969583.8     13557460.54
      1967911.02     13556937.22
#Sta/Elev= 30
  2574.3  605.35  3062.9  599.89    3383  601.81  3527.9   603.2  3583.6  602.19
  3612.7  604.61  3657.4  601.89  4058.9  601.56  4125.9  598.06  4126.5  597.26
  4137.3  598.06  4245.7  602.27  4619.2  602.94  4995.6  600.89  5329.6  602.97
  5738.9  605.14    5750  603.71  5773.1  604.83  5846.8  606.04  5981.9  609.03
  6041.6  608.82  6079.3  610.57  6111.7   609.7    6117  611.09  6209.1   612.4
  6279.3  617.89  6284.5  619.61  6311.8  620.86    6317  622.99  6456.2  621.22
#Mann= 8 ,-1 , 0
  2574.3     .05       0    3383      .1       0  3527.9     .05       0
  4125.9    .035       0  4137.3     .05       0  5329.6      .1       0
  5773.1     .16       0  5846.8      .1       0
Bank Sta=4125.9,4137.3
XS Rating Curve= 0 ,0
Exp/Cntr=0.3,0.1