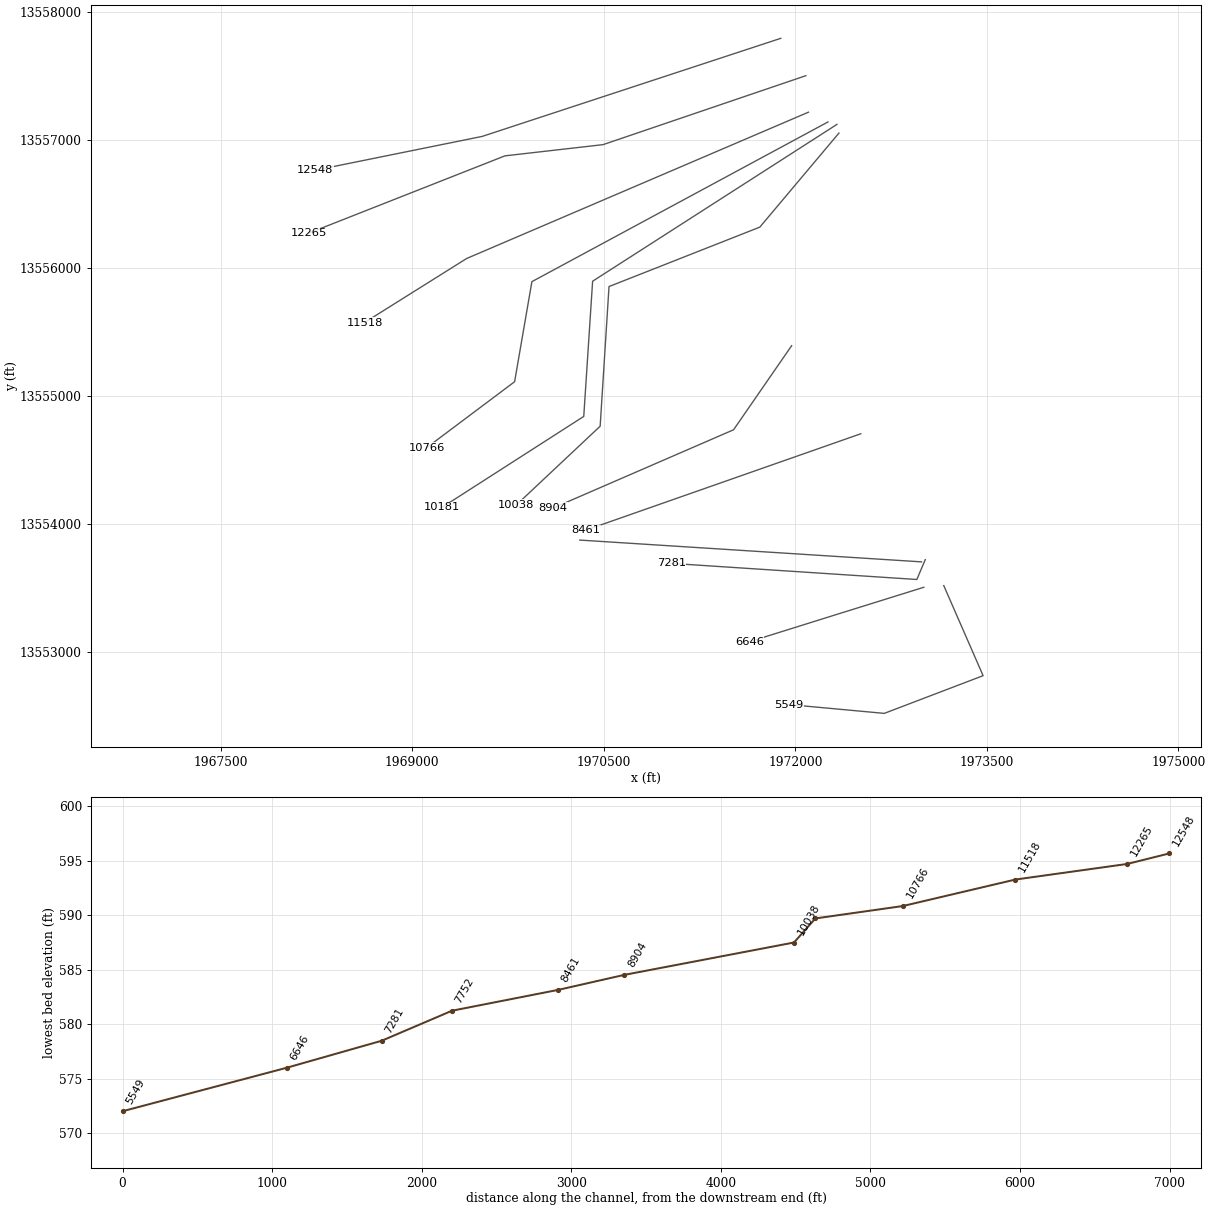
HEC-RAS study UNT 033 in BCW.prj: UNT 033 in BCW Base Level Engineering

--- UNT 033 in BCW.g01 (geometry) --- (continued)

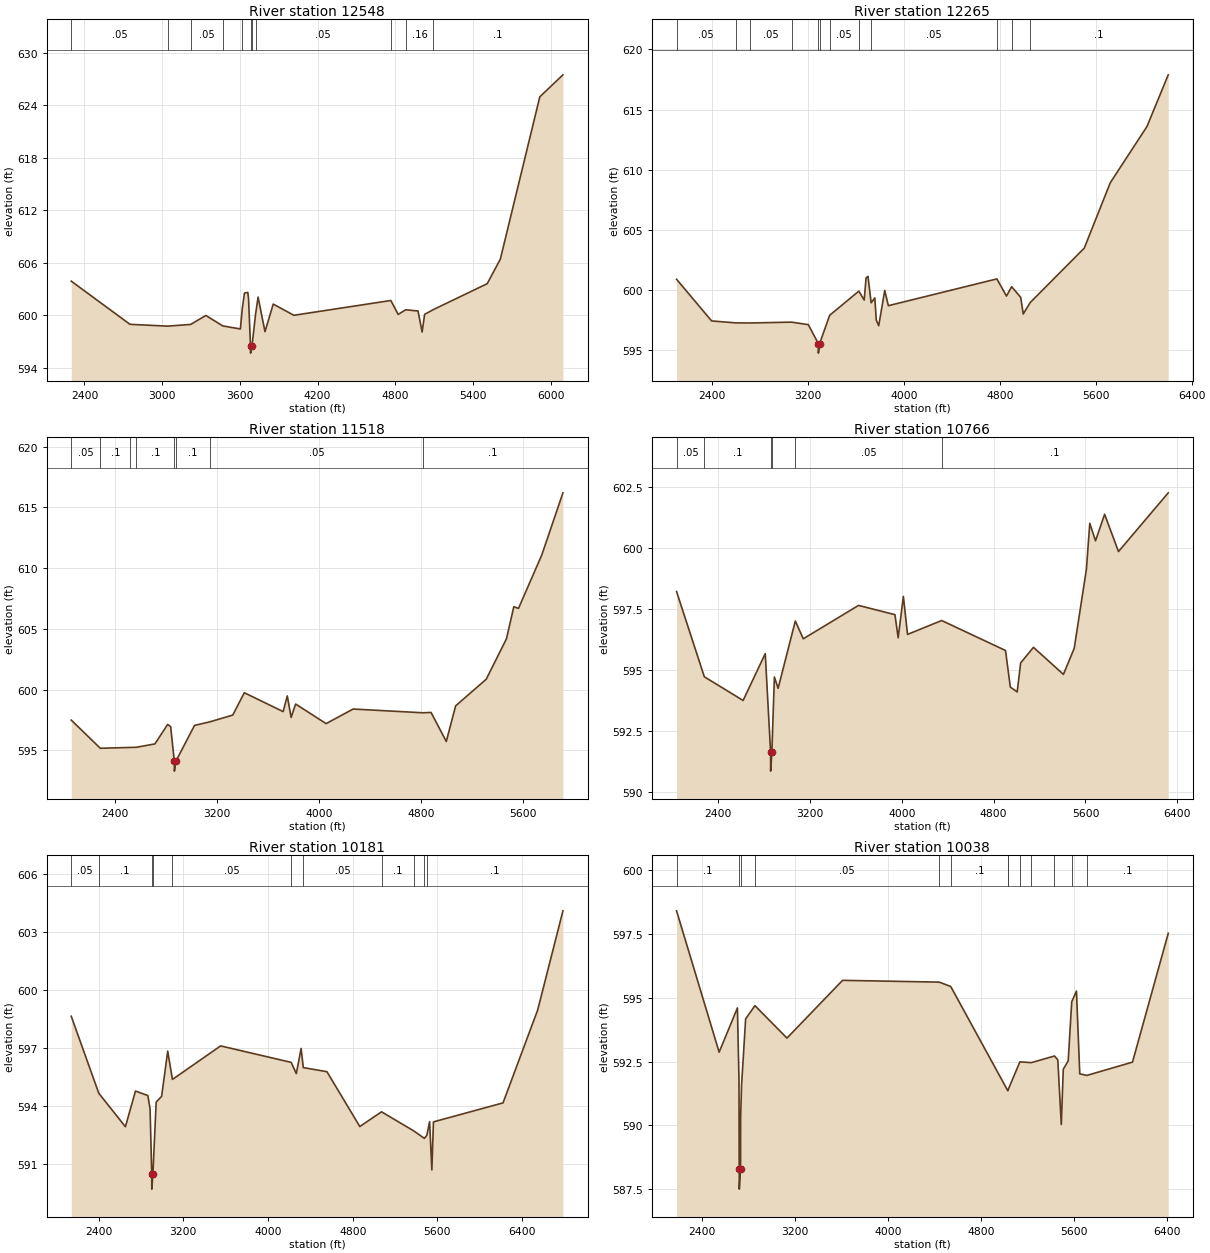
Type RM Length L Ch R = 1 ,12548   ,283,283,283
BEGIN DESCRIPTION:
Mapping XS 885c6fd6
END DESCRIPTION:
XS GIS Cut Line= 3
      1971885.92     13557793.89      1969547.32     13557028.37
      1968238.26     13556763.96
#Sta/Elev= 30
    2298  603.91  2751.4  598.98  3043.2  598.77  3220.4  598.97  3337.3  599.99
  3467.5   598.8  3603.7  598.45  3618.7  600.81  3635.3  602.55  3661.1  602.62
  3666.8  601.93    3682  596.49  3682.6  595.69  3693.4  596.49  3721.1  600.13
  3740.5  602.09  3793.8  598.14  3857.5  601.29  4016.7  600.01  4765.3   601.7
  4822.3  600.11  4879.7  600.64  4975.3   600.5    5007   598.1  5026.3  600.12
  5093.5  600.66  5509.5  603.62    5611  606.43  5915.6  624.96  6094.2  627.47
#Mann= 11 ,-1 , 0
    2298     .05       0  3043.2      .1       0  3220.4     .05       0
  3467.5      .1       0  3618.7     .08       0    3682     .07       0
  3693.4     .08       0  3721.1     .05       0  4765.3      .1       0
  4879.7     .16       0  5093.5      .1       0
Bank Sta=3682,3693.4
XS Rating Curve= 0 ,0
Exp/Cntr=0.3,0.1

Type RM Length L Ch R = 1 ,12265   ,747,747,747
BEGIN DESCRIPTION:
Mapping XS c216b188
END DESCRIPTION:
XS GIS Cut Line= 4
       1972082.1     13557502.22      1970493.76     13556963.96
      1969725.27     13556876.46      1968189.45     13556273.41
#Sta/Elev= 30
  2104.2  600.87  2396.8   597.4    2597  597.24  2718.6  597.23  3063.4   597.3
  3203.1  597.09  3286.3  595.52    3287  594.72  3297.7  595.52  3381.1  597.87
  3624.3  599.88    3669  599.14  3684.9  600.99  3700.5  601.11  3727.1  598.91
    3758  599.32  3769.4  597.48  3790.1     597  3840.4  599.94  3870.6  598.67
  4775.7   600.9  4855.8  599.47  4898.6  600.25    4974  599.37  4995.5  597.98
  5053.5  598.93  5504.2  603.46  5721.1   608.9  6027.4  613.59  6204.7  617.89
#Mann= 12 ,-1 , 0
  2104.2     .05       0    2597      .1       0  2718.6     .05       0
  3063.4      .1       0  3286.3     .07       0  3297.7      .1       0
  3381.1     .05       0  3624.3     .08       0  3727.1     .05       0
  4775.7      .1       0  4898.6     .16       0  5053.5      .1       0
Bank Sta=3286.3,3297.7
XS Rating Curve= 0 ,0
Exp/Cntr=0.3,0.1

Type RM Length L Ch R = 1 ,11518   ,752,752,752
BEGIN DESCRIPTION:
UNT 033 in BCW 2.0
END DESCRIPTION:
XS GIS Cut Line= 3
      1972102.93      13557217.5        1969425.       13556075.
      1968624.96     13555574.98
#Sta/Elev= 30
    2060  597.49  2287.9  595.17  2523.5  595.24  2569.2  595.25  2715.9  595.53
  2815.7  597.13  2839.4  596.95  2868.1  594.09  2868.8  593.29  2879.5  594.09
  3026.4  597.05  3147.7  597.35  3326.1   597.9  3416.8  599.74  3721.2  598.19
  3753.8  599.48  3783.7  597.71    3819  598.81  4058.2   597.2  4270.4   598.4
    4818  598.09  4880.7  598.12  5000.4  595.73  5073.5  598.66  5313.4  600.85
  5472.1  604.18  5529.8  606.82  5566.4  606.68  5749.2  611.08  5914.9  616.19
#Mann= 8 ,-1 , 0
    2060     .05       0  2287.9      .1       0  2523.5     .05       0
  2569.2      .1       0  2868.1     .07       0  2879.5      .1       0
  3147.7     .05       0    4818      .1       0
Bank Sta=2868.1,2879.5
XS Rating Curve= 0 ,0
Exp/Cntr=0.3,0.1

Type RM Length L Ch R = 1 ,10766   ,585,585,585
BEGIN DESCRIPTION:
Mapping XS 7832316f
END DESCRIPTION:
XS GIS Cut Line= 4
      1972255.66     13557141.09      1969936.32     13555894.33
       1969800.9     13555113.08      1969113.91     13554599.58
#Sta/Elev= 30
  2037.2  598.23  2279.4  594.73    2617  593.76    2810  595.68  2856.4  591.66
  2857.1  590.86  2867.8  591.66  2889.7  594.72  2922.2  594.26    3072  597.02
  3141.3  596.29  3622.6  597.66    3940  597.28    3968  596.33  4013.4  598.03
  4049.5  596.47  4347.1  597.04  4903.2  595.81  4945.2  594.31  5004.9  594.11
  5035.1   595.3  5146.7  595.94  5407.8  594.83  5501.9   595.9  5608.2  599.15
  5637.4  601.03  5687.4  600.31  5766.6   601.4  5887.5  599.87    6321  602.28
#Mann= 6 ,-1 , 0
  2037.2     .05       0  2279.4      .1       0  2856.4     .07       0
  2867.8      .1       0    3072     .05       0  4347.1      .1       0
Bank Sta=2856.4,2867.8
XS Rating Curve= 0 ,0
Exp/Cntr=0.3,0.1

Type RM Length L Ch R = 1 ,10181   ,143,143,143
BEGIN DESCRIPTION:
Mapping XS e8996490
END DESCRIPTION:
XS GIS Cut Line= 4
      1972325.99     13557122.15      1970412.01     13555897.81
      1970342.57     13554842.25      1969234.91      13554133.9
#Sta/Elev= 30
  2141.4  598.64  2401.2  594.67    2653  592.94    2748  594.78  2864.9  594.55
  2886.1  593.86  2901.5  590.52  2902.2  589.72  2912.9  590.52  2943.6  594.21
  2995.2  594.51  3052.7  596.84  3097.3  595.38  3552.5  597.11  4218.9  596.26
  4267.5  595.68  4312.8  596.98  4333.4  595.99  4556.6  595.78  4867.3  592.95
  5072.3  593.71  5375.2  592.73    5477  592.34  5500.6   592.5  5526.5   593.2
  5547.7  590.71  5562.9  593.19  6220.1  594.17  6547.3  598.96  6786.1  604.08
#Mann= 11 ,-1 , 0
  2141.4     .05       0  2401.2      .1       0  2901.5    .035       0
  2912.9      .1       0  3097.3     .05       0  4218.9     .08       0
  4333.4     .05       0  5072.3      .1       0  5375.2     .05       0
    5477     .08       0  5500.6      .1       0
Bank Sta=2901.5,2912.9
XS Rating Curve= 0 ,0
Exp/Cntr=0.3,0.1

Type RM Length L Ch R = 1 ,10038   ,1134,1134,1134
BEGIN DESCRIPTION:
Mapping XS 3606e446
END DESCRIPTION:
XS GIS Cut Line= 5
      1972341.61     13557054.44      1971721.82     13556320.06
      1970540.48     13555856.14      1970471.04     13554765.86
       1969814.8     13554151.29
#Sta/Elev= 30
  2185.5   598.4  2551.2  592.87  2708.2   594.6  2721.5  591.79  2723.5  588.31
  2724.2  587.51  2734.9  588.31  2735.8  590.33  2743.5  591.56  2778.7  594.17
  2858.7  594.69  3133.6  593.42    3611  595.68  4440.6  595.61  4539.5  595.44
  5029.7  591.36  5034.4  591.42  5133.4  592.49  5232.3  592.46  5430.3  592.72
  5458.9  592.57  5488.9  590.04    5506   592.2  5548.3  592.53  5578.5  594.84
  5619.1  595.26  5647.5  592.02  5709.4  591.96  6100.3  592.48  6407.2  597.52
#Mann= 13 ,-1 , 0
  2185.5      .1       0  2723.5     .07       0  2734.9      .1       0
  2858.7     .05       0  4440.6     .08       0  4539.5      .1       0
  5029.7     .05       0  5034.4     .08       0  5133.4     .05       0
  5232.3     .08       0  5430.3      .1       0  5578.5     .05       0
  5709.4      .1       0
Bank Sta=2723.5,2734.9
XS Rating Curve= 0 ,0
Exp/Cntr=0.3,0.1

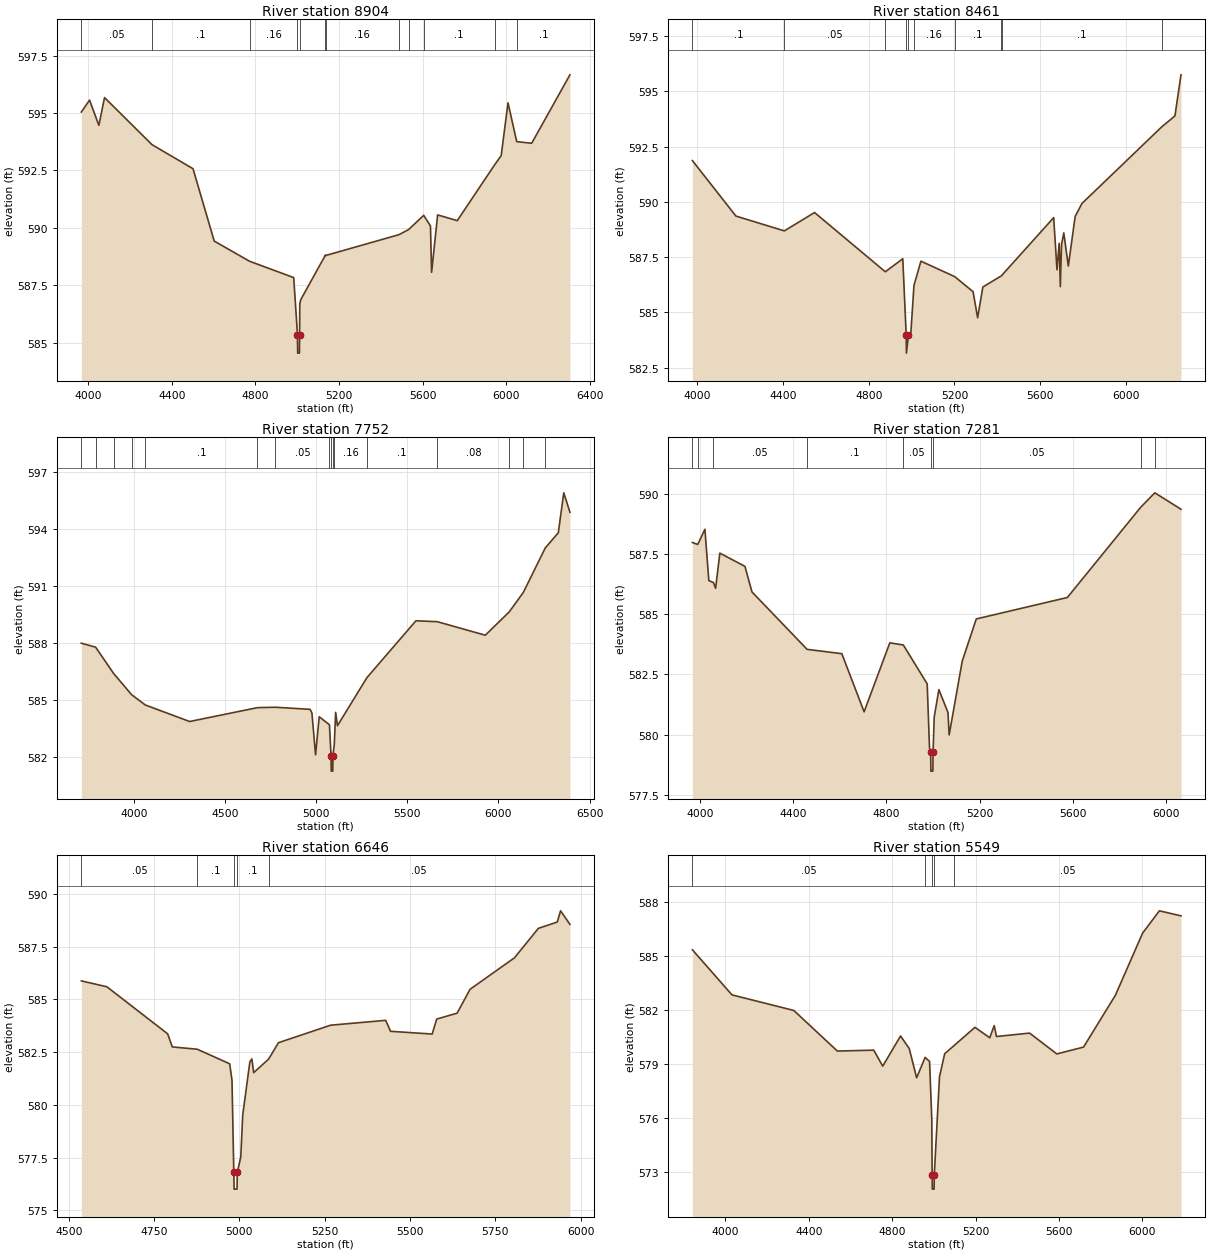
Type RM Length L Ch R = 1 ,8904    ,443,443,443
BEGIN DESCRIPTION:
Mapping XS dde6cbfe
END DESCRIPTION:
XS GIS Cut Line= 3
      1971971.02     13555394.31      1971516.18     13554738.08
      1970102.99     13554126.98
#Sta/Elev= 30
  3966.9  595.04  4006.2  595.56  4050.8  594.46  4077.8  595.67  4304.9  593.62
  4501.4  592.57  4602.7  589.42  4772.1  588.54  4983.2  587.83  5001.2  585.34
  5002.1  584.54  5010.5  584.54  5011.4  585.34  5012.1  586.69  5017.6  586.88
    5135  588.81  5135.6  588.79  5487.3   589.7  5532.8  589.92  5605.3  590.54
  5637.6  590.08    5643  588.06  5671.9  590.56  5765.9  590.31  5944.6  592.74
    5976  593.14  6008.7  595.44  6050.4  593.75    6122  593.68    6305  596.66
#Mann= 12 ,-1 , 0
  3966.9     .05       0  4304.9      .1       0  4772.1     .16       0
  5001.2     .07       0  5011.4     .16       0    5135      .1       0
  5135.6     .16       0  5487.3      .1       0  5532.8     .16       0
  5605.3      .1       0  5944.6     .08       0  6050.4      .1       0
Bank Sta=5001.2,5011.4
XS Rating Curve= 0 ,0
Exp/Cntr=0.3,0.1

Type RM Length L Ch R = 1 ,8461    ,709,709,709
BEGIN DESCRIPTION:
Mapping XS 605c25eb
END DESCRIPTION:
XS GIS Cut Line= 2
      1972512.72     13554706.84      1970358.27     13553953.99
#Sta/Elev= 30
  3976.2  591.87  4179.6  589.36  4405.6  588.69  4546.8  589.52  4877.3  586.84
  4958.9  587.43    4975  583.96  4975.9  583.16  4985.2  583.96  4996.7  584.09
  5011.2  586.23  5043.7  587.32  5201.5  586.62  5287.3  585.94  5308.5  584.76
  5332.9  586.15    5420  586.66  5422.5  586.69  5663.8  589.29  5679.2  586.93
  5689.5  588.13  5694.8  586.17  5700.4  588.07    5711   588.6  5732.2   587.1
    5764  589.34  5795.8  589.93  6168.9   593.4  6230.1  593.89  6258.4  595.75
#Mann= 10 ,-1 , 0
  3976.2      .1       0  4405.6     .05       0  4877.3      .1       0
    4975     .07       0  4985.2      .1       0  5011.2     .16       0
  5201.5      .1       0    5420     .16       0  5422.5      .1       0
  6168.9     .05       0
Bank Sta=4975,4985.2
XS Rating Curve= 0 ,0
Exp/Cntr=0.3,0.1

Type RM Length L Ch R = 1 ,7752    ,471,471,471
BEGIN DESCRIPTION:
Mapping XS ea396abe
END DESCRIPTION:
XS GIS Cut Line= 2
       1972988.4     13553706.83       1970311.3     13553876.97
#Sta/Elev= 30
  3709.8  587.98  3788.2  587.77  3886.9  586.39  3985.7  585.27    4061  584.73
  4304.4  583.86  4676.9  584.59  4775.7  584.61  4965.7   584.5  4975.7  584.31
  4995.8  582.11  5015.8  584.11  5071.9  583.69  5080.8  582.05  5081.8  581.25
  5090.2  581.25  5091.1  582.05  5098.7  582.67    5106  584.34    5116  583.64
  5277.9  586.17  5546.9  589.16  5664.4  589.11  5927.7   588.4  6059.4  589.63
  6136.4  590.65  6256.9  592.99  6328.5  593.79  6358.5  595.89  6392.3  594.87
#Mann= 16 ,-1 , 0
  3709.8     .08       0  3788.2     .05       0  3886.9     .08       0
  3985.7     .05       0    4061      .1       0  4676.9     .08       0
  4775.7     .05       0  5071.9     .08       0  5080.8     .04       0
  5091.1     .08       0  5098.7     .16       0  5277.9      .1       0
  5664.4     .08       0  6059.4     .05       0  6136.4      .1       0
  6256.9     .05       0
Bank Sta=5080.8,5091.1
XS Rating Curve= 0 ,0
Exp/Cntr=0.3,0.1

Type RM Length L Ch R = 1 ,7281    ,635,635,635
BEGIN DESCRIPTION:
Mapping XS 47e953ab
END DESCRIPTION:
XS GIS Cut Line= 3
      1973017.86     13553724.42      1972951.71     13553569.21
      1971028.63     13553694.95
#Sta/Elev= 30
  3967.5  587.97  3990.5  587.89  4021.2  588.52    4038  586.39  4057.7  586.31
  4067.1  586.07  4085.3  587.53    4193  586.98  4223.1  585.92  4459.4  583.54
  4608.5  583.36  4704.1  580.95  4814.4  583.81  4872.3  583.72  4974.7  582.11
  4984.7  579.44  4989.6  579.29  4990.5  578.49    4999  578.49  4999.9  579.29
  5004.8  580.73  5024.8  581.87  5063.9  580.92  5068.9  579.99    5125  583.05
  5185.2   584.8    5576  585.69  5890.5  589.43  5951.2  590.03  6063.4  589.35
#Mann= 9 ,-1 , 0
  3967.5     .05       0  3990.5     .08       0  4057.7     .05       0
  4459.4      .1       0  4872.3     .05       0  4989.6     .04       0
  4999.9     .05       0  5890.5     .08       0  5951.2     .05       0
Bank Sta=4989.6,4999.9
XS Rating Curve= 0 ,0
Exp/Cntr=0.3,0.1

Type RM Length L Ch R = 1 ,6646    ,1097,1097,1097
BEGIN DESCRIPTION:
Mapping XS c4ef4fae
END DESCRIPTION:
XS GIS Cut Line= 3
      1973006.54     13553508.41      1972307.74     13553291.39
      1971639.66     13553083.16
#Sta/Elev= 30
  4536.9  585.88  4611.8   585.6  4789.8  583.37  4803.4  582.75  4876.6  582.64
  4971.5  581.95  4978.3  581.17  4983.6  576.81  4984.5  576.01    4993  576.01
  4993.9  576.81    5004  577.53  5009.7  579.52  5030.7  582.05  5036.6  582.18
  5041.8  581.53  5085.5  582.17  5114.4  582.95  5267.4  583.78  5428.6  584.01
  5442.8  583.49  5564.8  583.36  5578.1  584.07  5637.9  584.35  5675.7  585.48
  5805.7  586.97    5876  588.37  5931.4  588.67    5941   589.2  5968.4  588.56
#Mann= 5 ,-1 , 0
  4536.9     .05       0  4876.6      .1       0  4983.6     .07       0
  4993.9      .1       0  5085.5     .05       0
Bank Sta=4983.6,4993.9
XS Rating Curve= 0 ,0
Exp/Cntr=0.3,0.1

Type RM Length L Ch R = 1 ,5549    ,0,0,0
BEGIN DESCRIPTION:
UNT 033 in BCW 1.0
END DESCRIPTION:
XS GIS Cut Line= 4
      1973162.77     13553521.43      1973470.93      13552818.3
      1972696.62     13552524.03       1971951.8     13552592.61
#Sta/Elev= 30
  3841.7  585.35  4031.5  582.84  4328.4  581.97  4537.2  579.71  4711.9  579.76
  4754.8  578.87  4840.4  580.55    4882  579.85  4917.4  578.22  4958.4  579.36
  4979.5  579.13  4990.2   575.9  4991.9  572.82  4992.8  572.02  5001.3  572.02
  5002.2  572.82  5027.2  578.28    5052  579.56  5098.5  580.03  5197.2  581.03
  5268.3  580.45  5289.7  581.13  5300.4  580.52  5459.4  580.71    5590  579.55
  5718.2  579.93  5871.2  582.82  6001.7  586.28  6082.1  587.52  6185.7  587.24
#Mann= 5 ,-1 , 0
  3841.7     .05       0  4958.4      .1       0  4991.9     .07       0
  5002.2      .1       0  5098.5     .05       0
Bank Sta=4991.9,5002.2
XS Rating Curve= 0 ,0
Exp/Cntr=0.3,0.1
LCMann Table=0

Chan Stop Cuts=-1
Use User Specified Reach Order=0
Composite Channel Slope=5