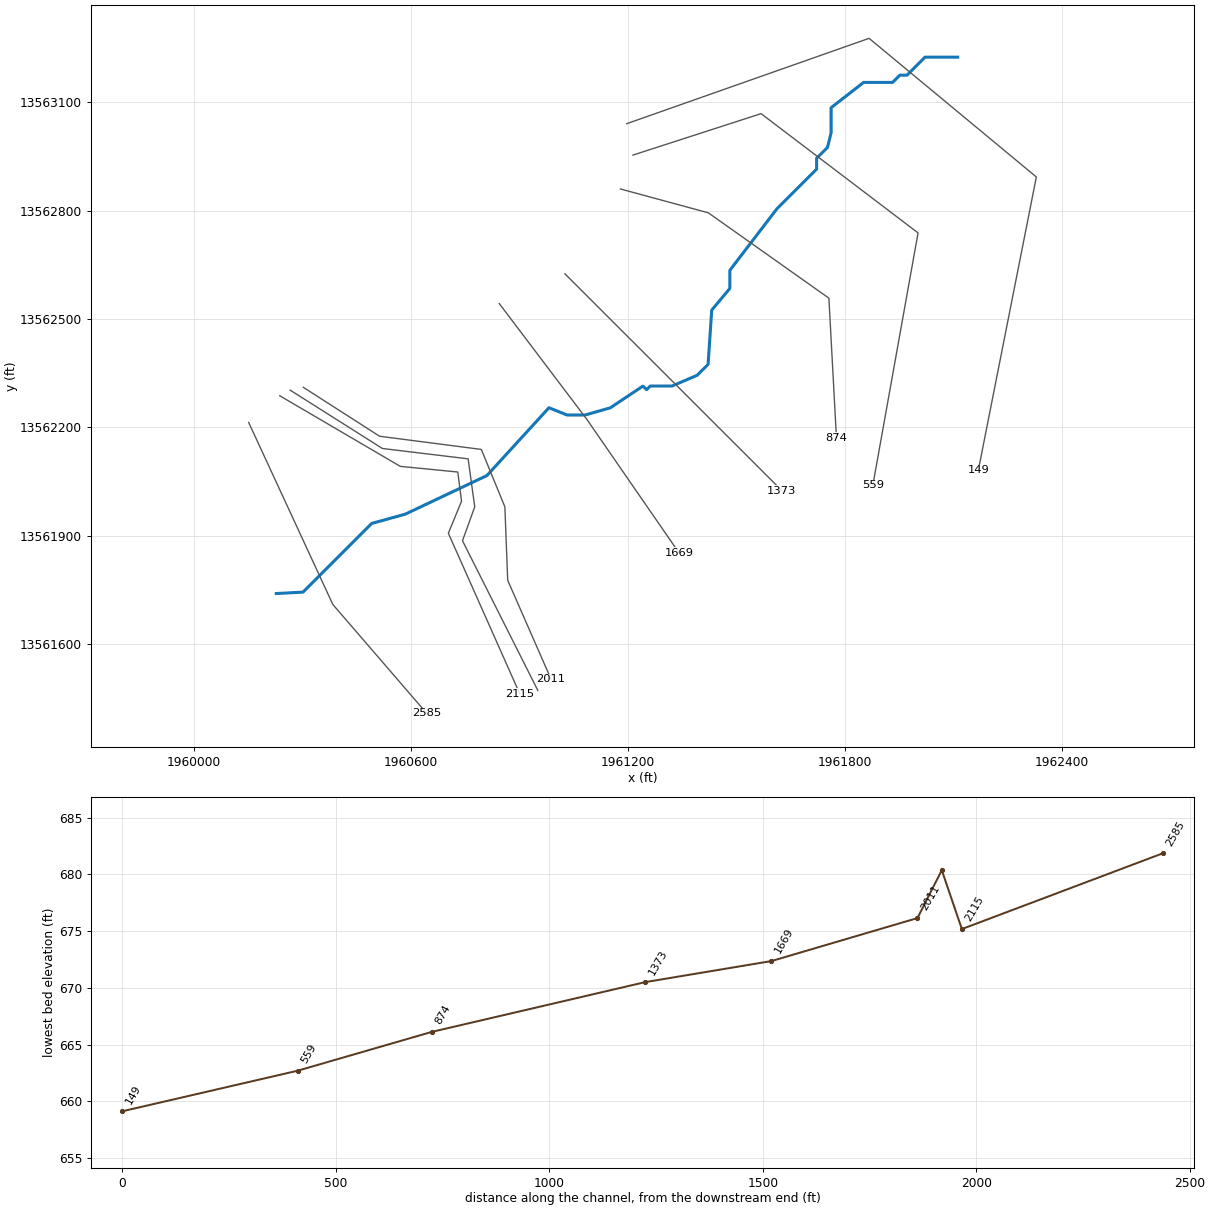
--- UNT 034 in BCW.prj (project) ---

Proj Title=UNT 034 in BCW Base Level Engineering
Current Plan=p01
Default Exp/Contr=0.3,0.1
English Units
Geom File=g01
Flow File=f01
Plan File=p01
Y Axis Title=Elevation
X Axis Title(PF)=Main Channel Distance
X Axis Title(XS)=Station
BEGIN DESCRIPTION:
UNT 034 in BCW
END DESCRIPTION:
DSS Export Rating Curves= 0
DSS Export Rating Curve Sorted= 0
DSS Export Volume Flow Curves= 0
DXF OffsetX= 0
DXF OffsetY= 0
DXF ScaleX= 1
DXF ScaleY= 10

--- UNT 034 in BCW.p01 (plan) ---

Plan Title=Multiple Run
Short Identifier=Multiple
Geom File=g01
Flow File=f01
Subcritical Flow
K Sum by GR= 0
Std Step Tol= 0.01
Critical Tol= 0.01
Num of Std Step Trials= 20
Max Error Tol= 0.3
Flow Tol Ratio= 0.001
Split Flow NTrial= 30
Split Flow Tol= 0.02
Split Flow Ratio= 0.02
Log Output Level= 0
Friction Slope Method= 1
Unsteady Friction Slope Method= 2
Unsteady Bridges Friction Slope Method= 1
Parabolic Critical Depth
Global Vel Dist=  1 , 1 , 1
Global Log Level= 0
CheckData=True
Encroach Param= -1, 0, 0, 0
BEGIN DESCRIPTION:
Multiple Run
END DESCRIPTION:

--- UNT 034 in BCW.f01 (steady flow) ---

Flow Title=Multiple
Number of Profiles=7
Profile Names=10-year,25-year,50-year,1pct_min,100-year,1pct_plu,500-year
River Rch & RM= UNT 034 in BCW,Reach-1,2585
     544     771     961     593    1184    2362    1798
Boundary for River Rch & Prof#=UNT 034 in BCW,Reach-1,1
Up Type=0
Dn Type=3
Dn Slope=0.005
Boundary for River Rch & Prof#=UNT 034 in BCW,Reach-1,2
Up Type=0
Dn Type=3
Dn Slope=0.005
Boundary for River Rch & Prof#=UNT 034 in BCW,Reach-1,3
Up Type=0
Dn Type=3
Dn Slope=0.005
Boundary for River Rch & Prof#=UNT 034 in BCW,Reach-1,4
Up Type=0
Dn Type=3
Dn Slope=0.005
Boundary for River Rch & Prof#=UNT 034 in BCW,Reach-1,5
Up Type=0
Dn Type=3
Dn Slope=0.005
Boundary for River Rch & Prof#=UNT 034 in BCW,Reach-1,6
Up Type=0
Dn Type=3
Dn Slope=0.005
Boundary for River Rch & Prof#=UNT 034 in BCW,Reach-1,7
Up Type=0
Dn Type=3
Dn Slope=0.005

--- UNT 034 in BCW.g01 (geometry) ---

Geom Title=Existing Conditions
Program Version=5.05

River Reach=UNT 034 in BCW  ,Reach-1
Reach XY= 30
      1960226.91     13561740.65       1960300.8     13561744.54
       1960490.8     13561934.54      1960583.48     13561960.17
      1960809.17     13562066.94       1960980.8     13562254.54
       1961030.8     13562234.54       1961080.8     13562234.54
       1961150.8     13562254.54       1961240.8     13562314.54
       1961250.8     13562304.54       1961260.8     13562314.54
       1961320.8     13562314.54       1961390.8     13562344.54
       1961420.8     13562374.54       1961430.8     13562524.54
       1961480.8     13562584.54       1961480.8     13562634.54
       1961610.8     13562804.54       1961720.8     13562914.54
       1961720.8     13562944.54       1961750.8     13562974.54
       1961760.8     13563014.54       1961760.8     13563084.54
       1961850.8     13563154.54       1961930.8     13563154.54
       1961950.8     13563174.54       1961970.8     13563174.54
       1962020.8     13563224.54       1962110.8     13563224.54

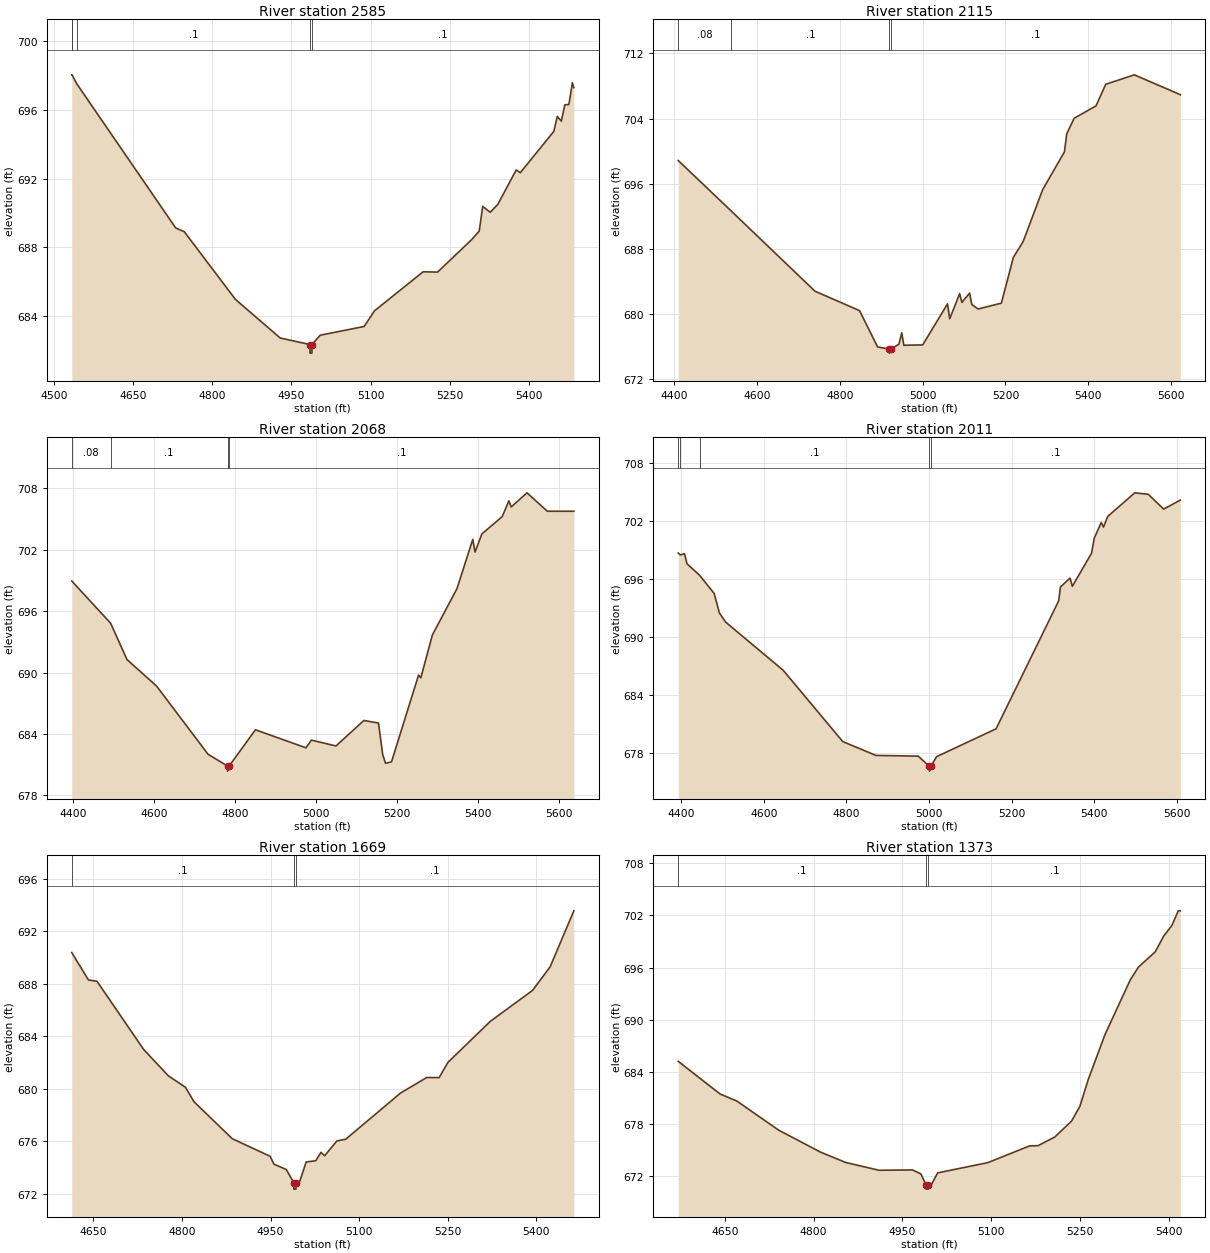
Type RM Length L Ch R = 1 ,2585    ,470,470,470
BEGIN DESCRIPTION:
UNT 034 in BCW 4.0
END DESCRIPTION:
XS GIS Cut Line= 3
      1960150.61      13562213.9      1960383.23     13561710.46
      1960642.98     13561409.15
#Sta/Elev= 30
  4533.2  698.03  4533.7  698.03  4543.1  697.49  4730.3  689.13  4746.6  688.91
  4843.8  684.97  4928.6  682.73  4984.9  682.35  4985.2  681.85  4988.7  681.85
  4988.9  682.35  5004.4  682.89  5087.8   683.4  5107.5  684.31  5199.7  686.58
  5227.1  686.56  5291.8  688.45  5306.1  688.94  5312.7  690.38    5327  690.04
  5341.2  690.49  5376.3   692.5    5384  692.34  5447.6  694.74  5454.2  695.61
  5461.9  695.34  5468.5  696.29  5476.2   696.3  5482.8  697.57  5485.6  697.28
#Mann= 5 ,-1 , 0
  4533.2     .05       0  4533.7     .08       0  4543.1      .1       0
  4984.9     .07       0  4988.9      .1       0
Bank Sta=4984.9,4988.9
XS Rating Curve= 0 ,0
Exp/Cntr=0.3,0.1

Type RM Length L Ch R = 1 ,2115    ,47,47,47
BEGIN DESCRIPTION:
Mapping XS c7b052dc
END DESCRIPTION:
XS GIS Cut Line= 6
       1960236.5     13562287.73      1960569.87      13562092.4
      1960728.72     13562076.78      1960739.14     13561996.05
      1960702.68      13561907.5       1960900.3     13561462.89
#Sta/Elev= 30
  4409.8  698.84  4538.2  692.62    4740  682.79  4847.7   680.4  4891.4  675.94
  4919.4  675.68  4919.6  675.18  4923.4  675.68  4942.8  676.27  4949.7  677.68
  4954.6  676.15  5000.3  676.19  5060.2  681.23  5065.6  679.41  5089.6  682.49
    5095  681.41  5113.5  682.55  5118.9  681.16    5134   680.6  5190.3  681.32
  5219.3  686.95  5242.9  688.88  5290.1  695.27  5342.6   699.9  5348.2  702.13
  5366.2  704.04  5418.8  705.55  5442.4  708.21  5511.4  709.37  5622.5  706.93
#Mann= 4 ,-1 , 0
  4409.8     .08       0  4538.2      .1       0  4919.4     .07       0
  4923.4      .1       0
Bank Sta=4919.4,4923.4
XS Rating Curve= 0 ,0
Exp/Cntr=0.3,0.1

Type RM Length L Ch R = 1 ,2068    ,57,57,57
BEGIN DESCRIPTION:
Mapping XS 2b7a8731
END DESCRIPTION:
XS GIS Cut Line= 6
      1960265.19     13562303.33      1960520.39     13562141.88
      1960757.37     13562113.23       1960775.6     13561980.42
      1960741.74     13561886.67      1960950.04     13561472.67
#Sta/Elev= 30
  4395.9  698.95  4491.9  694.83  4532.4  691.27  4605.3  688.69  4732.6  682.02
  4780.7  680.87    4781  680.37  4784.7  680.87  4849.7  684.41  4974.5  682.65
  4987.9   683.4  5048.7  682.83  5117.7  685.32  5153.7  685.07  5164.1     682
  5171.2  681.13  5185.9  681.28  5252.8  689.76  5258.4  689.49  5286.8  693.67
  5347.7  698.21  5386.7  703.02  5392.3  701.78  5409.1  703.55  5459.3  705.24
    5476  706.79  5481.6  706.19  5520.7  707.57  5570.9  705.77  5636.4  705.77
#Mann= 4 ,-1 , 0
  4395.9     .08       0  4491.9      .1       0  4780.7     .07       0
  4784.7      .1       0
Bank Sta=4780.7,4784.7
XS Rating Curve= 0 ,0
Exp/Cntr=0.3,0.1

Type RM Length L Ch R = 1 ,2011    ,342,342,342
BEGIN DESCRIPTION:
Mapping XS 42836c8d
END DESCRIPTION:
XS GIS Cut Line= 6
      1960301.67     13562311.13      1960512.57     13562175.73
      1960793.82     13562139.28      1960858.93     13561980.42
      1960866.74      13561777.3      1960986.52     13561503.89
#Sta/Elev= 30
  4392.5  698.66  4397.8  698.47  4407.7   698.6  4413.7  697.56  4444.4  696.36
  4479.6  694.49  4492.3  692.47  4507.5  691.53  4646.8  686.56  4791.1   679.2
  4871.5  677.77  4973.8   677.7  5000.9  676.65  5001.1  676.15  5004.9  676.65
  5018.3  677.64  5162.5  680.52  5314.3  693.74  5318.3  695.15  5341.7  696.08
  5347.2  695.23  5393.9  698.66  5400.2  700.18  5417.3  701.82  5422.8  701.34
  5432.9  702.44  5498.4  704.88  5531.2  704.73  5568.5   703.2  5608.8  704.13
#Mann= 5 ,-1 , 0
  4392.5     .05       0  4397.8     .08       0  4444.4      .1       0
  5000.9     .07       0  5004.9      .1       0
Bank Sta=5000.9,5004.9
XS Rating Curve= 0 ,0
Exp/Cntr=0.3,0.1

Type RM Length L Ch R = 1 ,1669    ,296,296,296
BEGIN DESCRIPTION:
UNT 034 in BCW 3.0
END DESCRIPTION:
XS GIS Cut Line= 3
      1960843.31     13562542.91      1961085.49     13562222.61
      1961340.32     13561853.36
#Sta/Elev= 30
  4613.4  690.37  4641.6  688.29  4656.2  688.18  4735.2  682.99  4776.9  680.99
    4806  680.11  4820.5  679.01  4885.1   676.2  4949.3  674.86  4955.8  674.26
  4976.7  673.85  4989.2  672.86  4989.5  672.36    4993  672.36  4993.2  672.86
  4999.4  672.95  5010.4  674.43  5026.6  674.52  5035.4  675.16  5041.5   674.9
  5062.4  676.03  5077.3  676.16    5170  679.67  5214.5  680.86  5235.5  680.85
  5250.4  682.01    5322  685.13  5393.7  687.49  5423.5  689.29  5463.6  693.55
#Mann= 3 ,-1 , 0
  4613.4      .1       0  4989.2     .07       0  4993.2      .1       0
Bank Sta=4989.2,4993.2
XS Rating Curve= 0 ,0
Exp/Cntr=0.3,0.1

Type RM Length L Ch R = 1 ,1373    ,499,499,499
BEGIN DESCRIPTION:
UNT 034 in BCW 2.0
END DESCRIPTION:
XS GIS Cut Line= 3
      1961024.99     13562625.01        1961325.       13562325.
      1961624.97     13562025.03
#Sta/Elev= 30
  4571.3  685.21    4642  681.45  4670.3  680.64    4741  677.29  4811.7  674.76
  4854.2  673.57  4910.7  672.67  4967.3  672.71  4981.4  672.25    4990     671
  4990.3   670.5  4993.8   670.5    4994     671  4999.1     671  5009.7  672.37
  5094.6  673.55  5165.3  675.48  5179.4   675.5  5207.7   676.5    5236  678.33
  5250.1  680.03  5264.3  683.13  5292.6   688.3    5335  694.55  5349.1  696.06
  5377.4  697.81  5391.6  699.61  5405.7  700.86  5416.3  702.53  5419.8  702.53
#Mann= 3 ,-1 , 0
  4571.3      .1       0    4990     .07       0    4994      .1       0
Bank Sta=4990,4994
XS Rating Curve= 0 ,0
Exp/Cntr=0.3,0.1

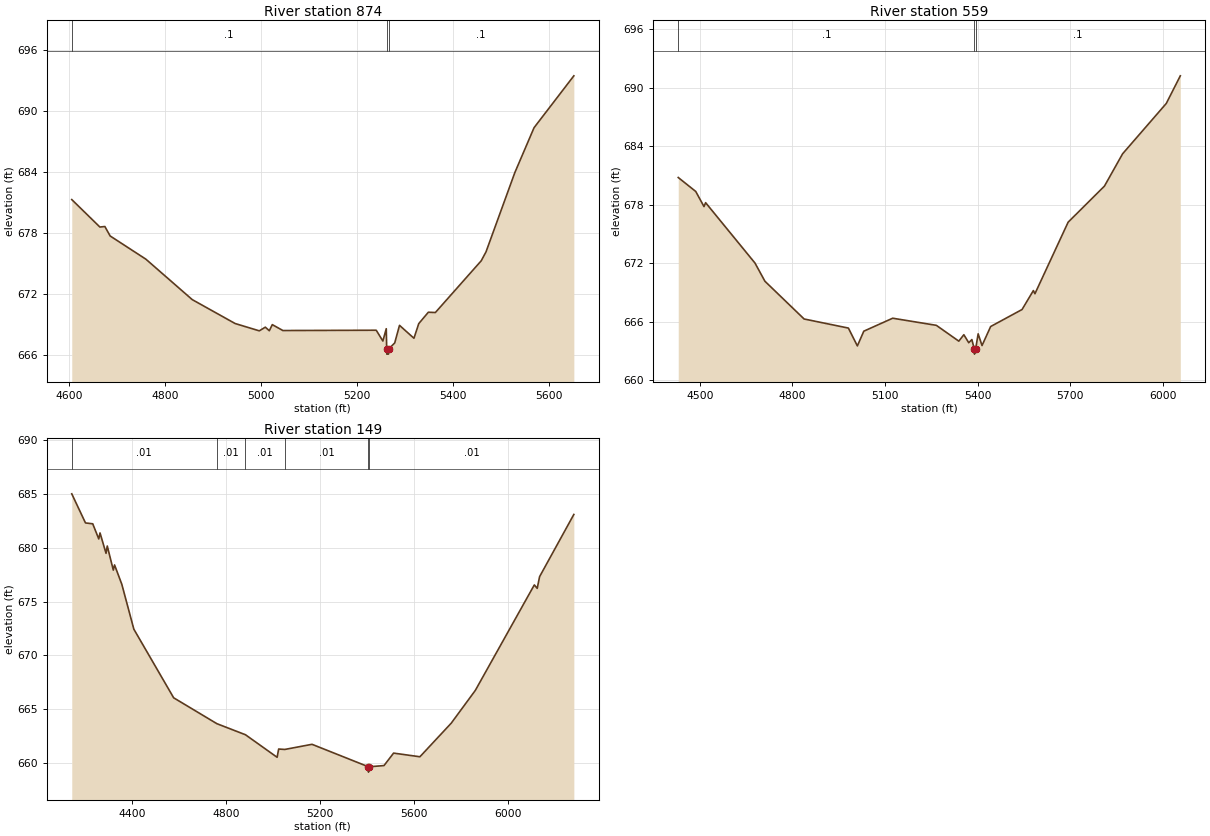
Type RM Length L Ch R = 1 ,874     ,315,315,315
BEGIN DESCRIPTION:
Mapping XS d9293f0c
END DESCRIPTION:
XS GIS Cut Line= 4
       1961178.4     13562859.75      1961421.43     13562793.79
      1961754.76     13562557.68       1961775.6     13562172.25
#Sta/Elev= 30
  4605.7  681.32  4664.3  678.62  4674.7  678.67  4685.7  677.74  4760.1  675.46
  4856.8  671.48  4946.1  669.13  4996.5  668.41    5009  668.77  5017.4  668.42
  5023.6  669.02  5045.7  668.44  5240.2  668.47    5254  667.41  5261.1  668.62
    5262  666.62  5262.2  666.12  5265.7  666.12    5266  666.62  5278.7  667.22
  5288.7  668.95  5318.8  667.68  5328.8  669.12  5348.8  670.24  5363.4  670.21
    5459   675.3    5469  676.18  5529.1  683.98  5569.1  688.39    5652  693.49
#Mann= 3 ,-1 , 0
  4605.7      .1       0    5262     .07       0    5266      .1       0
Bank Sta=5262,5266
XS Rating Curve= 0 ,0
Exp/Cntr=0.3,0.1

Type RM Length L Ch R = 1 ,559     ,410,410,410
BEGIN DESCRIPTION:
Mapping XS 555ffa58
END DESCRIPTION:
XS GIS Cut Line= 4
      1961213.09     13562953.51      1961567.26     13563068.09
      1962001.29     13562738.23      1961876.29     13562040.34
#Sta/Elev= 30
    4430  680.79  4486.7  679.36  4513.5  677.81  4518.7  678.21  4678.7  672.02
  4710.8  670.16  4837.8  666.29  4981.2  665.36  5010.3  663.53  5031.1  665.04
  5124.7  666.37  5266.1  665.64  5338.9  664.02  5355.2  664.68    5371  663.86
  5381.2  664.18  5389.3  663.19  5389.6  662.69  5393.3  663.19  5401.5  664.77
  5414.1  663.57  5442.1  665.52  5543.7  667.26  5580.4   669.2  5585.5  668.88
    5693  676.21  5810.7  679.91  5869.5  683.22    6011  688.38  6056.4  691.21
#Mann= 3 ,-1 , 0
    4430      .1       0  5389.3     .07       0  5393.3      .1       0
Bank Sta=5389.3,5393.3
XS Rating Curve= 0 ,0
Exp/Cntr=0.3,0.1

Type RM Length L Ch R = 1 ,149     ,0,0,0
BEGIN DESCRIPTION:
UNT 034 in BCW 1.0
END DESCRIPTION:
XS GIS Cut Line= 4
      1961195.73     13563040.32      1961865.87     13563276.43
      1962328.32     13562892.95      1962167.95     13562081.94
#Sta/Elev= 30
  4142.6  685.03    4201  682.32  4231.9  682.24  4257.6  680.83  4262.9  681.39
  4288.5  679.49  4293.8  680.17  4319.5  677.93  4324.8  678.41  4355.7  676.61
  4406.9  672.43  4576.5  666.04  4760.6  663.63  4882.3   662.6  5017.1   660.5
  5023.6  661.27  5049.6  661.23  5165.6  661.71  5405.8  659.62  5406.1  659.12
  5409.8  659.62  5472.2  659.73    5513  660.89  5625.1  660.55  5758.6  663.68
  5861.1  666.73  6112.3  676.55  6124.6  676.23  6134.8  677.32  6280.6  683.11
#Mann= 6 ,-1 , 0
  4142.6     .01       0  4760.6     .01       0  4882.3     .01       0
  5049.6     .01       0  5405.8     .01       0  5409.8     .01       0
Bank Sta=5405.8,5409.8
XS Rating Curve= 0 ,0
Exp/Cntr=0.3,0.1
LCMann Table=0

Chan Stop Cuts=-1
Use User Specified Reach Order=0
Composite Channel Slope=5