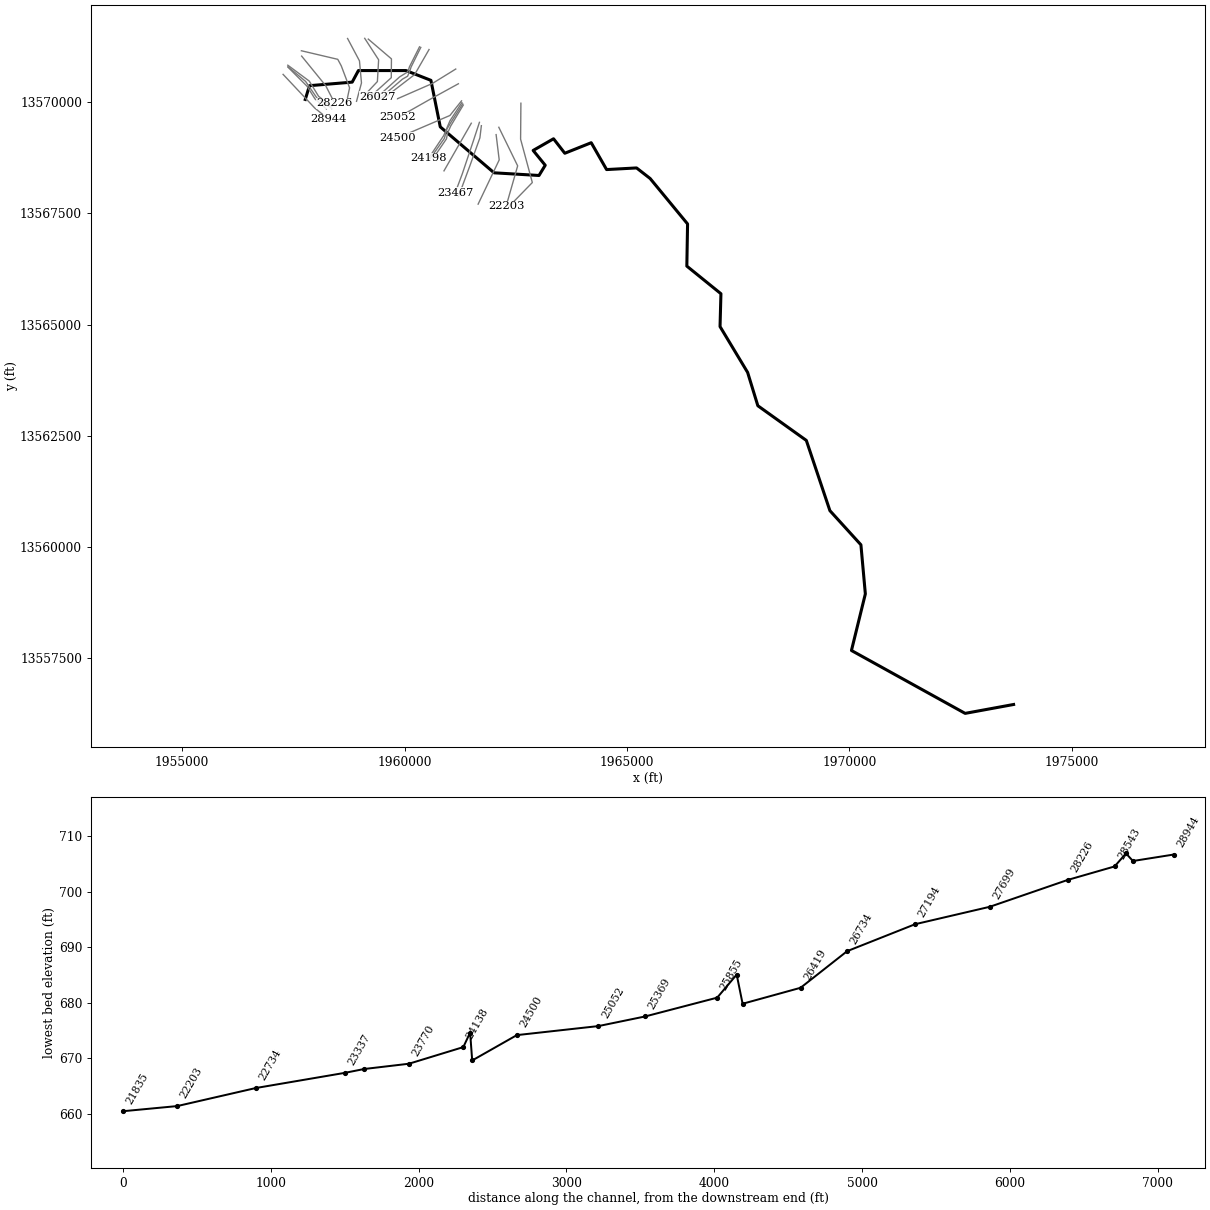
--- UNT 035 in BCW.prj (project) ---

Proj Title=UNT 035 in BCW Base Level Engineering
Current Plan=p01
Default Exp/Contr=0.3,0.1
English Units
Geom File=g01
Flow File=f01
Plan File=p01
Y Axis Title=Elevation
X Axis Title(PF)=Main Channel Distance
X Axis Title(XS)=Station
BEGIN DESCRIPTION:
UNT 035 in BCW
END DESCRIPTION:
DSS Export Rating Curves= 0
DSS Export Rating Curve Sorted= 0
DSS Export Volume Flow Curves= 0
DXF OffsetX= 0
DXF OffsetY= 0
DXF ScaleX= 1
DXF ScaleY= 10

--- UNT 035 in BCW.p01 (plan) ---

Plan Title=Multiple Run
Program Version=5.05
Short Identifier=3
Geom File=g01
Flow File=f01
Subcritical Flow
K Sum by GR= 0
Std Step Tol= 0.01
Critical Tol= 0.01
Num of Std Step Trials= 20
Max Error Tol= 0.3
Flow Tol Ratio= 0.001
Split Flow NTrial= 30
Split Flow Tol= 0.02
Split Flow Ratio= 0.02
Log Output Level= 0
Friction Slope Method= 1
Unsteady Friction Slope Method= 2
Unsteady Bridges Friction Slope Method= 1
Parabolic Critical Depth
Global Vel Dist= 1 , 1 , 1
Global Log Level= 0
CheckData=True
Encroach Param=-1 ,0,0, 0
BEGIN DESCRIPTION:
Multiple Run
END DESCRIPTION:
Computation Interval=1MIN
Output Interval=1HOUR
Instantaneous Interval=1HOUR
Mapping Interval=1HOUR
Computation Time Step Use Courant=        0
Computation Time Step Use Time Series=    0
Computation Time Step Count To Double=0
Computation Time Step Max Doubling=0
Computation Time Step Max Halving=0
Computation Time Step Residence Courant=0
Run HTab= 0
Run UNet= 0
Run Sediment= 0
Run PostProcess= 0
Run WQNet= 0
Run RASMapper= 0
UNET Theta= 1
UNET Theta Warmup= 1
UNET ZTol= 0.02
UNET ZSATol= 0.02
UNET MxIter= 20
UNET Max Iter WO Improvement= 0
UNET MaxInSteps= 0
UNET DtIC= 0
UNET DtMin= 0
UNET MaxCRTS= 20
UNET WFStab= 2
UNET SFStab= 1
UNET WFX= 1
UNET SFX= 1
UNET 1D Methodology=Finite Difference
UNET DSS MLevel= 4
UNET Pardiso=0
UNET DZMax Abort= 100
UNET Use Existing IB Tables=-1
UNET Froude Reduction=False
UNET Froude Limit= 0.8
UNET Froude Power= 4
UNET D1 Cores= 0
UNET D2 Coriolis=0
UNET D2 Cores= 0
UNET D2 Theta= 1
UNET D2 Theta Warmup= 1
UNET D2 Z Tol= 0.01
UNET D2 Volume Tol= 0.01
UNET D2 Max Iterations= 20
UNET D2 Equation= 0
UNET D2 RampUpFraction=0.1
UNET D2 TimeSlices= 1
UNET D2 BCVolumeCheck=0
UNET D1D2 MaxIter= 0
UNET D1D2 ZTol=0.01
UNET D1D2 QTol=0.1
UNET D1D2 MinQTol=1
Write IC File= 0
Write IC File at Fixed DateTime=0
Write IC File at Sim End=0
Echo Input=False
Echo Parameters=False
Echo Output=False
Write Detailed= 0
HDF Write Warmup=0
HDF Write Time Slices=0
HDF Flush=0
HDF Face Node Velocities=0
HDF Compression= 1
HDF Chunk Size= 1
HDF Spatial Parts= 1
HDF Use Max Rows=0
HDF Fixed Rows= 1
Calibration Method= 0
Calibration Iterations= 20
Calibration Max Change=0.05
Calibration Tolerance=0.2
Calibration Maximum=1.5
Calibration Minimum=0.5
Calibration Optimization Method= 1
WQ AD Non Conservative
WQ ULTIMATE=-1
WQ Max Comp Step=1HOUR
WQ Output Interval=15MIN
WQ Output Selected Increments= 0
WQ Output face flow=0
WQ Output face velocity=0
WQ Output face area=0
WQ Output face dispersion=0
WQ Output cell volume=0
WQ Output cell surface area=0
WQ Output cell continuity=0
WQ Output cumulative cell continuity=0
WQ Output face conc=0
WQ Output face dconc_dx=0
WQ Output face courant=0
WQ Output face peclet=0
WQ Output face adv mass=0
WQ Output face disp mass=0
WQ Output cell mass=0
WQ Output cell source sink temp=0
WQ Output nsm pathways=0
WQ Output nsm derived pathways=0
WQ Output MaxMinRange=-1
WQ Daily Max Min Mean=-1
WQ Daily Range=0
WQ Daily Time=0
WQ Create Restart=0
WQ Fixed Restart=0
WQ System Summary=0
WQ Write To DSS=0
WQ Use Fixed Temperature=0
Sorting and Armoring Iterations= 10
XS Update Threshold= 0.02
Bed Roughness Predictor= 0
Hydraulics Update Threshold= 0.02
Energy Slope Method= 1
Volume Change Method= 1
Sediment Retention Method= 0
XS Weighting Method= 0
Number of US Weighted Cross Sections= 1
Number of DS Weighted Cross Sections= 1
Upstream XS Weight=0
Main XS Weight=1
Downstream XS Weight=0
Number of DS XS's Weighted with US Boundary= 1
Upstream Boundary Weight= 1
Weight of XSs Associated with US Boundary= 0
Number of US XS's Weighted with DS Boundary= 1
Downstream Boundary Weight= 0.5
Weight of XSs Associated with DS Boundary= 0.5
Percentile Method= 0
Sediment Output Level= 3
Mass or Volume Output= 0
Output Increment Type= 1
Profile and TS Output Increment= 1
XS Output Flag= 0
XS Output Increment= 10
Write Gradation File= 0
Read Gradation Hotstart= 0
Write HDF5 File= 1
Write Binary Output= 1
Write DSS Sediment File= 0
SV Curve= 0
Specific Gage Flag= 0

--- UNT 035 in BCW.f01 (steady flow) ---

Flow Title=Multiple
Program Version=5.05
Number of Profiles= 7
Profile Names=10-year,25-year,50-year,1pct_min,100-year,1pct_plu,500-year
River Rch & RM=UNT 035 in BCW,Reach-1         ,28944
     575     811    1008     619    1236    2466    1860
River Rch & RM=UNT 035 in BCW,Reach-1         ,27699
     741    1061    1333     827    1651    3294    2536
River Rch & RM=UNT 035 in BCW,Reach-1         ,26027
    1107    1619    2062    1296    2585    5158    4072
River Rch & RM=UNT 035 in BCW,Reach-1         ,24198
    1283    1886    2408    1516    3025    6035    4784
River Rch & RM=UNT 035 in BCW,Reach-1         ,20557
    1405    2071    2650    1671    3334    6653    5291
River Rch & RM=UNT 035 in BCW,Reach-1         ,17717
    2173    3252    4203    2672    5330   10636    8599
River Rch & RM=UNT 035 in BCW,Reach-1         ,14369
    2436    3657    4734    3014    6013   11998    9731
River Rch & RM=UNT 035 in BCW,Reach-1         ,13105
    2436    3657    4734    3014    6013   11998    9731
River Rch & RM=UNT 035 in BCW,Reach-1         ,8562
    2419    3620    4676    2970    5927   11826    9553
Boundary for River Rch & Prof#=UNT 035 in BCW,Reach-1         , 1
Up Type= 0
Dn Type= 3
Dn Slope=0.005
Boundary for River Rch & Prof#=UNT 035 in BCW,Reach-1         , 2
Up Type= 0
Dn Type= 3
Dn Slope=0.005
Boundary for River Rch & Prof#=UNT 035 in BCW,Reach-1         , 3
Up Type= 0
Dn Type= 3
Dn Slope=0.005
Boundary for River Rch & Prof#=UNT 035 in BCW,Reach-1         , 4
Up Type= 0
Dn Type= 3
Dn Slope=0.005
Boundary for River Rch & Prof#=UNT 035 in BCW,Reach-1         , 5
Up Type= 0
Dn Type= 3
Dn Slope=0.005
Boundary for River Rch & Prof#=UNT 035 in BCW,Reach-1         , 6
Up Type= 0
Dn Type= 3
Dn Slope=0.005
Boundary for River Rch & Prof#=UNT 035 in BCW,Reach-1         , 7
Up Type= 0
Dn Type= 3
Dn Slope=0.005
DSS Import GetInterval= 0
DSS Import GetPeak= 0
DSS Import FillOption= 0

--- UNT 035 in BCW.g01 (geometry) ---

Geom Title=Geom 01
Program Version=5.05

River Reach=UNT 035 in BCW  ,Reach-1
Reach XY= 30
       1957765.8     13570064.54       1957860.8     13570374.54
       1958820.8     13570454.54       1958960.8     13570714.54
       1960030.8     13570714.54       1960590.8     13570494.54
      1960800.85      13569448.1       1962010.8     13568414.54
       1963020.8     13568354.54       1963160.8     13568584.54
      1962889.39     13568917.71      1963347.63      13569180.2
       1963600.8     13568854.54      1964194.85     13569091.66
      1964540.33      13568487.5       1965214.2     13568524.23
       1965519.5     13568286.11       1966360.8     13567264.54
       1966344.3     13566315.62       1967110.8     13565694.54
      1967090.72     13564955.45       1967710.8     13563924.54
       1967940.8     13563174.54       1969030.8     13562394.54
       1969560.8     13560814.54      1970257.82      13560046.9
      1970357.65      13558942.3      1970045.22     13557669.15
       1972600.8     13556254.54       1973690.8     13556454.54

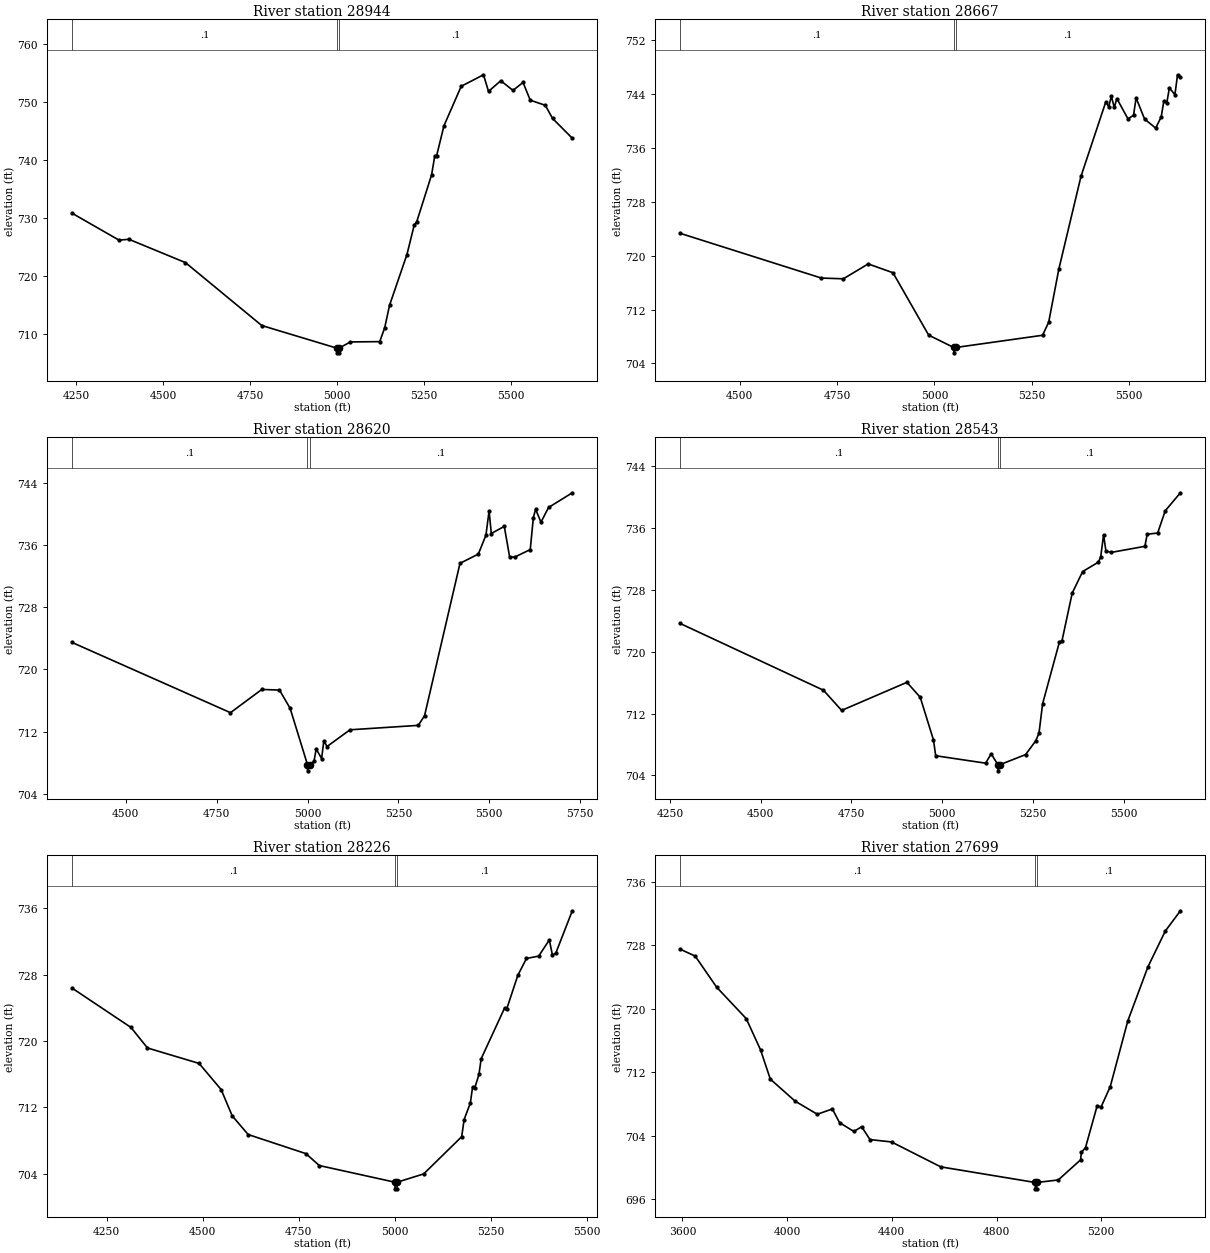
Type RM Length L Ch R = 1 ,28944   ,277,277,277
BEGIN DESCRIPTION:
UNT 035 in BCW 49.0
END DESCRIPTION:
XS GIS Cut Line= 3
       1957267.5     13570628.77      1957981.98     13569868.44
      1958290.95     13569621.79
#Sta/Elev= 30
  4237.7  730.81    4373  726.16  4401.3  726.31    4564  722.29  4783.3  711.45
  4999.6  707.54  5000.1  706.74  5005.1  706.74  5005.6  707.54  5038.2  708.62
  5122.7  708.67  5136.9  711.06  5151.1  714.98  5200.9  723.68  5221.9  728.78
  5229.2  729.36  5271.7   737.4    5281   740.7  5286.2   740.7  5307.4  745.88
    5357  752.68    5421  754.66  5435.5   751.8  5470.7  753.63  5505.9  751.97
  5534.7  753.34  5555.5  750.28  5598.8   749.4  5619.6  747.14  5676.4  743.72
#Mann= 3 ,-1 , 0
  4237.7      .1       0  4999.6     .07       0  5005.6      .1       0
Bank Sta=4999.6,5005.6
XS Rating Curve= 0 ,0
Exp/Cntr=0.3,0.1

Type RM Length L Ch R = 1 ,28667   ,47,47,47
BEGIN DESCRIPTION:
Mapping XS 0c88b849
END DESCRIPTION:
XS GIS Cut Line= 4
      1957377.84     13570790.29      1957804.89     13570363.23
      1957984.58     13570076.78      1958241.18     13569851.28
#Sta/Elev= 30
  4347.3  723.33  4709.7  716.68  4766.2  716.57  4829.9  718.78  4893.5  717.47
  4985.1   708.2  5049.2  706.37  5049.7  705.57  5055.2  706.37  5277.3  708.18
    5293  710.11    5319  717.99  5375.9  731.79  5439.5  742.84  5447.1  742.13
  5453.8  743.69  5461.3  742.04    5468  743.34  5496.5  740.33  5510.7  740.86
  5517.3  743.44  5539.1  740.31  5567.6  738.95  5581.8  740.64  5588.5  742.97
  5596.1  742.71  5602.7  744.93    5617  743.93  5623.6  746.88    5631   746.5
#Mann= 3 ,-1 , 0
  4347.3      .1       0  5049.2     .07       0  5055.2      .1       0
Bank Sta=5049.2,5055.2
XS Rating Curve= 0 ,0
Exp/Cntr=0.3,0.1

Type RM Length L Ch R = 1 ,28620   ,77,77,77
BEGIN DESCRIPTION:
Mapping XS 80152cc1
END DESCRIPTION:
XS GIS Cut Line= 4
      1957376.85     13570800.68      1957772.69     13570470.81
      1958029.63     13570095.81      1958361.31     13569860.87
#Sta/Elev= 30
  4352.1  723.46  4788.1  714.42  4874.3  717.41  4922.9  717.33  4952.1  714.99
  4999.9  707.74  5000.4  706.94  5005.9  707.74  5017.8  708.16  5023.9  709.75
  5038.8  708.52  5044.9   710.8  5053.7  710.07  5116.9  712.22  5304.8  712.79
    5322  714.04  5419.5  733.64  5469.9  734.82  5490.8  737.25  5499.5  740.39
  5505.6  737.47  5541.3  738.39  5556.1  734.43  5570.8  734.46  5612.7   735.4
  5621.3  739.52  5627.4  740.59  5642.2  738.93  5663.1  740.82  5728.4  742.71
#Mann= 3 ,-1 , 0
  4352.1      .1       0  4999.9     .07       0  5005.9      .1       0
Bank Sta=4999.9,5005.9
XS Rating Curve= 0 ,0
Exp/Cntr=0.3,0.1

Type RM Length L Ch R = 1 ,28543   ,317,317,317
BEGIN DESCRIPTION:
Mapping XS 149c42f4
END DESCRIPTION:
XS GIS Cut Line= 4
      1957373.41     13570835.37      1957856.02     13570477.75
      1958064.36     13570137.48      1958359.47     13569901.38
#Sta/Elev= 30
  4278.3  723.64    4673  715.01  4723.1   712.4  4902.8  716.03  4939.5   714.1
    4976  708.58  4982.1  706.54  5119.5  705.58  5134.9  706.79  5153.2  705.39
  5153.7  704.59  5159.2  705.39  5229.7  706.69  5257.4  708.46  5266.5  709.45
  5276.5  713.26  5322.8  721.25    5330  721.43    5358  727.57  5386.8  730.35
    5430  731.56  5436.4  732.24  5444.4  735.09  5450.8  733.01  5465.2  732.82
  5558.1  733.61  5564.5  735.17  5593.3  735.33  5614.1   738.2  5655.9  740.53
#Mann= 3 ,-1 , 0
  4278.3      .1       0  5153.2     .07       0  5159.2      .1       0
Bank Sta=5153.2,5159.2
XS Rating Curve= 0 ,0
Exp/Cntr=0.3,0.1

Type RM Length L Ch R = 1 ,28226   ,527,527,527
BEGIN DESCRIPTION:
UNT 035 in BCW 48.0
END DESCRIPTION:
XS GIS Cut Line= 3
      1957684.14     13571040.26        1958225.       13570375.
      1958428.39     13569978.83
#Sta/Elev= 30
  4159.5  726.38    4313  721.63  4356.1  719.15  4490.4  717.29  4547.9  714.13
  4576.6  710.97  4618.2  708.71  4768.4  706.41  4803.5  704.97  5000.2  702.96
  5000.7  702.16  5005.7  702.16  5006.2  702.96  5075.2  703.96  5174.2  708.45
  5180.5  710.51  5196.7  712.51  5202.7  714.48  5208.3  714.34  5219.2  715.97
  5224.9  717.85  5285.8  723.96  5291.4  723.85  5320.4  727.92  5342.9  729.95
  5374.6  730.23  5402.4  732.18  5410.3   730.4  5418.9  730.55  5462.2   735.7
#Mann= 3 ,-1 , 0
  4159.5      .1       0  5000.2     .07       0  5006.2      .1       0
Bank Sta=5000.2,5006.2
XS Rating Curve= 0 ,0
Exp/Cntr=0.3,0.1

Type RM Length L Ch R = 1 ,27699   ,505,505,505
BEGIN DESCRIPTION:
UNT 035 in BCW 47.0
END DESCRIPTION:
XS GIS Cut Line= 5
      1957678.91     13571160.05      1958496.65     13570967.34
      1958574.77      13570821.5      1958762.27     13570326.71
      1958684.47     13569958.44
#Sta/Elev= 30
  3591.3  727.53  3648.9  726.66  3731.1  722.73  3844.1  718.77  3898.7  714.83
  3935.9  711.15  4030.8  708.37  4115.5  706.72  4172.9  707.39  4200.2  705.67
  4255.1  704.55  4284.9  705.15  4316.7  703.53  4398.9  703.23    4587  700.09
  4947.8  698.12  4948.3  697.32  4953.3  697.32  4953.8  698.12  5035.9  698.44
    5121  700.97  5124.2  701.91    5140  702.53  5184.7  707.82  5199.3  707.63
  5234.4   710.2  5301.5  718.49  5378.5  725.31  5444.6  729.81  5502.4  732.37
#Mann= 3 ,-1 , 0
  3591.3      .1       0  4947.8     .07       0  4953.8      .1       0
Bank Sta=4947.8,4953.8
XS Rating Curve= 0 ,0
Exp/Cntr=0.3,0.1

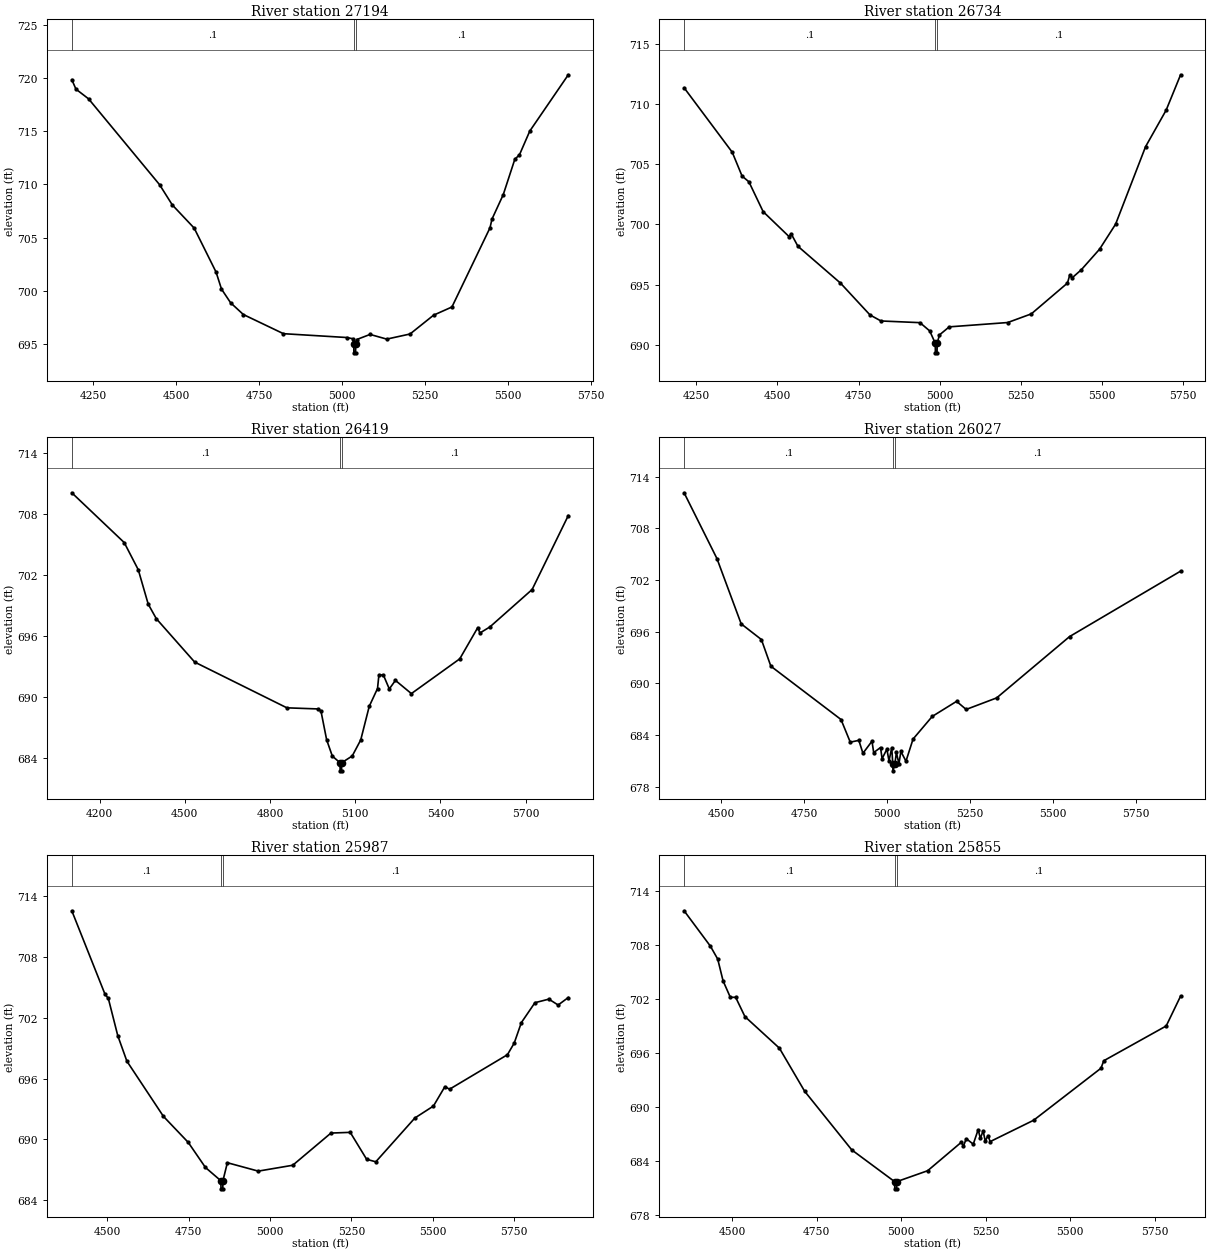
Type RM Length L Ch R = 1 ,27194   ,460,460,460
BEGIN DESCRIPTION:
Mapping XS d00eab1b
END DESCRIPTION:
XS GIS Cut Line= 4
      1958717.14     13571436.07      1958984.49     13570932.61
      1959029.63     13570436.09      1958918.52     13570022.88
#Sta/Elev= 30
    4185  719.85  4197.5  718.96  4235.5  718.05  4449.6  709.98  4487.9  708.08
  4553.9   705.9  4619.8  701.77  4636.2  700.17  4663.8  698.88  4702.1  697.78
  4822.9  695.98  5013.7  695.62  5032.8   695.5  5034.8  694.98  5035.3  694.18
  5040.3  694.18  5040.8  694.98  5043.8  695.43    5084  695.91  5134.2  695.47
  5204.5  695.95  5275.5  697.72  5330.8  698.49  5445.5  705.93  5451.5  706.75
  5485.5  709.05  5520.3  712.37  5534.3  712.79  5565.4  715.02  5681.5  720.31
#Mann= 3 ,-1 , 0
    4185      .1       0  5034.8     .07       0  5040.8      .1       0
Bank Sta=5034.8,5040.8
XS Rating Curve= 0 ,0
Exp/Cntr=0.3,0.1

Type RM Length L Ch R = 1 ,26734   ,315,315,315
BEGIN DESCRIPTION:
UNT 035 in BCW 46.0
END DESCRIPTION:
XS GIS Cut Line= 4
      1959102.55     13571439.56      1959415.05     13570956.92
      1959387.27     13570467.34      1959068.91     13570128.21
#Sta/Elev= 30
  4212.3  711.36  4360.7     706    4391  704.02  4412.1  703.54    4456  701.06
  4536.1  698.98  4542.1  699.23  4563.2  698.18  4694.3  695.12  4785.4  692.47
  4819.2  691.97  4939.4  691.83  4969.5  691.14  4986.5  690.12    4987  689.32
    4992  689.32  4992.5  690.12  4999.5  690.81  5029.6  691.48  5209.9  691.84
  5282.7  692.56    5394  695.12  5401.3   695.8  5408.2  695.55  5436.5  696.22
  5493.1  697.94  5542.5  700.02  5634.8  706.46  5698.3   709.5  5742.8  712.44
#Mann= 3 ,-1 , 0
  4212.3      .1       0  4986.5     .07       0  4992.5      .1       0
Bank Sta=4986.5,4992.5
XS Rating Curve= 0 ,0
Exp/Cntr=0.3,0.1

Type RM Length L Ch R = 1 ,26419   ,392,392,392
BEGIN DESCRIPTION:
UNT 035 in BCW 45.0
END DESCRIPTION:
XS GIS Cut Line= 4
      1959182.42     13571422.19      1959703.24     13570977.75
      1959699.77     13570554.14      1959224.99     13570124.99
#Sta/Elev= 30
  4102.1  710.08  4286.7  705.18  4336.1  702.51  4371.2  699.12  4399.7  697.69
  4534.8  693.42  4859.5  688.92  4969.5  688.81  4979.5   688.6  4999.5  685.77
  5019.5  684.17  5046.5  683.52    5047  682.72    5052  682.72  5052.5  683.52
  5089.5  684.18  5119.5  685.76  5149.5  689.07  5178.6  690.82  5183.6  692.18
  5199.5  692.13  5220.1  690.78  5241.7  691.62  5297.8  690.32  5468.2  693.74
  5531.7  696.82  5539.1  696.28  5574.3  696.88    5723  700.56  5850.4  707.84
#Mann= 3 ,-1 , 0
  4102.1      .1       0  5046.5     .07       0  5052.5      .1       0
Bank Sta=5046.5,5052.5
XS Rating Curve= 0 ,0
Exp/Cntr=0.3,0.1

Type RM Length L Ch R = 1 ,26027   ,40,40,40
BEGIN DESCRIPTION:
Mapping XS ce8e4e59
END DESCRIPTION:
XS GIS Cut Line= 6
       1960334.4     13571248.63      1960105.24     13570792.92
      1960084.41      13570717.4      1960050.55     13570673.13
      1959886.49     13570571.57      1959397.55     13570129.44
#Sta/Elev= 30
  4388.2  712.13  4487.2  704.49  4560.2  696.91  4621.1  695.09  4649.7  691.99
  4861.1   685.8    4889  683.17  4914.8  683.38  4927.2  681.88  4954.4  683.28
  4959.6  681.96  4980.2  682.55  4984.9  681.25  4999.4  682.36  5005.7  680.98
    5014  682.54  5017.1  680.64  5017.6  679.84  5023.5  680.64    5028  681.97
  5035.7  680.67  5041.5  682.09  5056.9  680.96  5078.2  683.53  5136.1  686.16
  5209.4  687.91  5238.3  686.97  5330.2  688.31  5549.9  695.43  5884.5  703.03
#Mann= 3 ,-1 , 0
  4388.2      .1       0  5017.1     .07       0  5023.5      .1       0
Bank Sta=5017.1,5023.5
XS Rating Curve= 0 ,0
Exp/Cntr=0.3,0.1

Type RM Length L Ch R = 1 ,25987   ,132,132,132
BEGIN DESCRIPTION:
Mapping XS 4e493336
END DESCRIPTION:
XS GIS Cut Line= 6
      1960363.05     13571235.62       1960144.3     13570792.92
      1960118.26     13570709.59      1960066.18     13570587.19
      1959951.59     13570522.09      1959436.36     13570079.71
#Sta/Elev= 30
  4391.1  712.57    4493  704.33  4503.3  703.91  4532.3  700.23  4560.3  697.71
  4672.5  692.26  4748.7  689.69  4801.6  687.21  4848.9   685.9  4849.4   685.1
  4854.8   685.1  4855.3   685.9  4868.9  687.68  4963.8  686.85  5069.7  687.43
  5187.1  690.61  5246.3  690.68  5296.7  688.02  5324.8  687.77  5444.9   692.1
  5501.9  693.28  5537.1   695.2  5551.3  694.94  5729.1  698.35    5750   699.5
  5771.9  701.52  5813.6  703.49  5856.4  703.84  5884.9  703.26  5916.1     704
#Mann= 3 ,-1 , 0
  4391.1      .1       0  4848.9     .07       0  4855.3      .1       0
Bank Sta=4848.9,4855.3
XS Rating Curve= 0 ,0
Exp/Cntr=0.3,0.1

Type RM Length L Ch R = 1 ,25855   ,486,486,486
BEGIN DESCRIPTION:
UNT 035 in BCW 44.0
END DESCRIPTION:
XS GIS Cut Line= 3
      1960548.71     13571187.79        1960225.       13570625.
        1959575.       13570125.
#Sta/Elev= 30
  4357.8  711.79  4435.7  707.86  4457.3  706.43  4473.1  704.02  4494.6  702.19
  4510.4  702.19  4537.8  700.05  4639.8  696.55  4714.5  691.77    4854  685.26
  4980.8  681.74  4981.3  680.94  4986.7  680.94  4987.2  681.74  5078.6  682.95
  5178.3  686.11  5184.6  685.69  5192.8   686.5  5213.6   685.9  5228.1  687.51
  5234.5  686.53  5242.7  687.38    5249  686.24  5257.2  686.85  5263.5  686.18
  5392.2  688.55  5591.5  694.32  5599.7  695.15  5784.5  699.01  5827.1  702.32
#Mann= 3 ,-1 , 0
  4357.8      .1       0  4980.8     .07       0  4987.2      .1       0
Bank Sta=4980.8,4987.2
XS Rating Curve= 0 ,0
Exp/Cntr=0.3,0.1

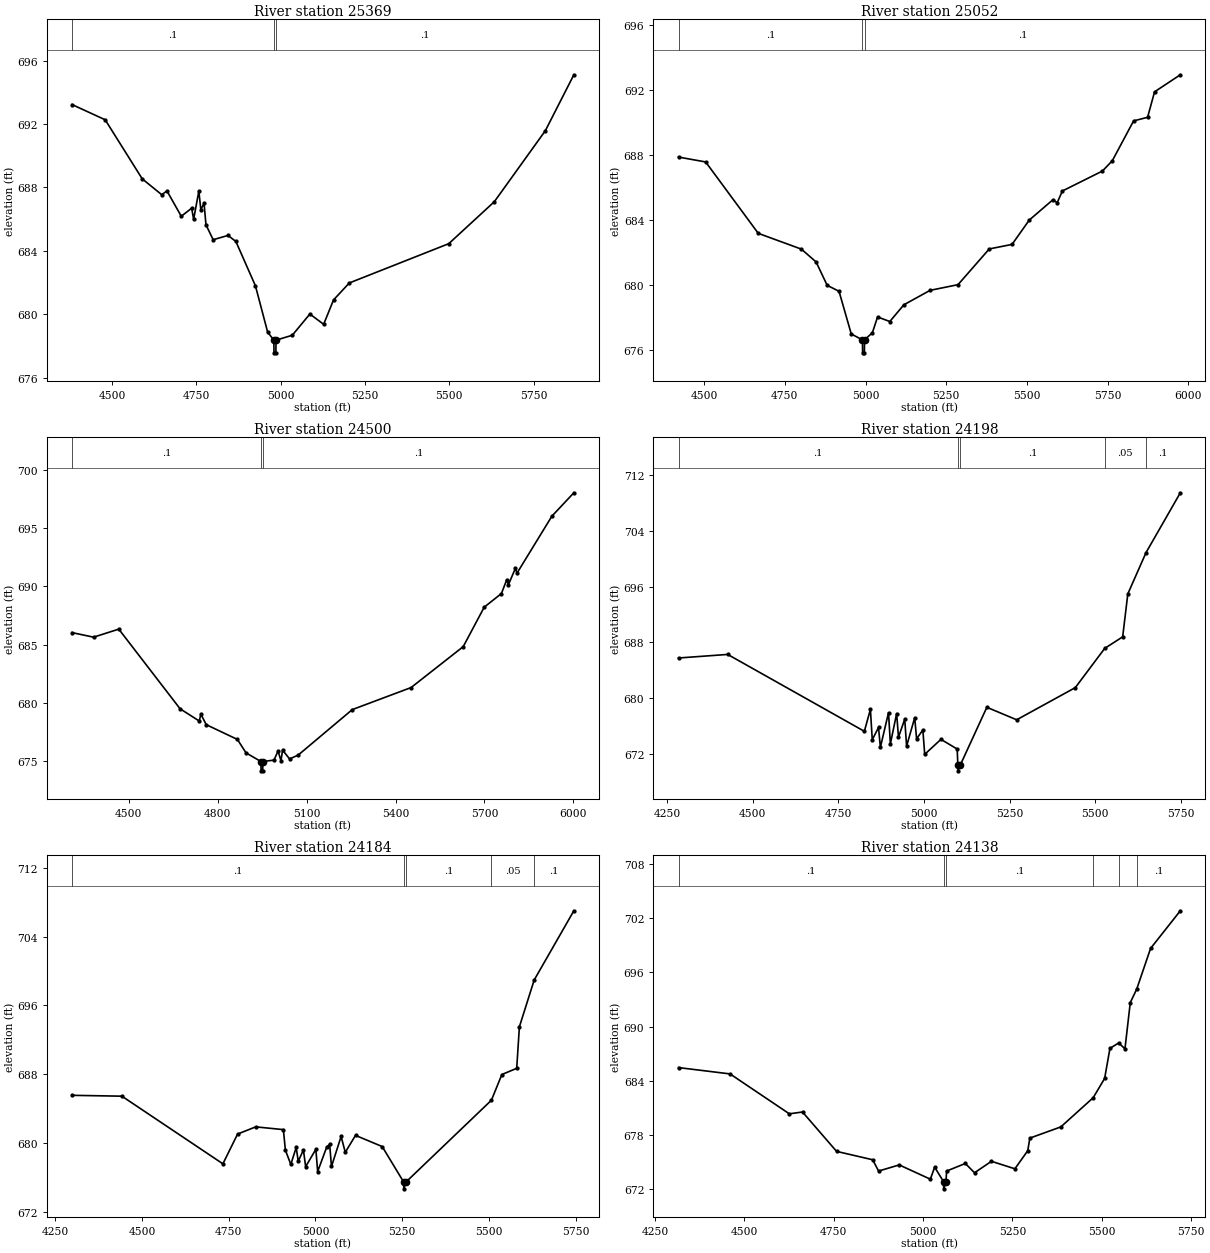
Type RM Length L Ch R = 1 ,25369   ,317,317,317
BEGIN DESCRIPTION:
UNT 035 in BCW 43.0
END DESCRIPTION:
XS GIS Cut Line= 3
      1961148.54     13570748.57        1960625.       13570425.
      1959824.97     13570074.99
#Sta/Elev= 30
    4381  693.23  4479.2  692.27  4589.2  688.54  4647.1  687.54  4662.5  687.78
    4705  686.18  4735.8  686.69  4741.7  685.99  4757.1  687.77    4763   686.6
  4772.5     687  4778.3  685.64  4799.6   684.7  4843.6  684.97    4867  684.59
    4925  681.79  4961.2  678.87  4979.6  678.36  4980.1  677.56  4985.6  677.56
  4986.1  678.36  5034.3  678.67  5086.5  680.01  5127.4  679.36  5156.7   680.9
  5203.5  681.97  5498.6  684.45  5633.8   687.1  5785.1  691.58  5869.7  695.11
#Mann= 3 ,-1 , 0
    4381      .1       0  4979.6     .07       0  4986.1      .1       0
Bank Sta=4979.6,4986.1
XS Rating Curve= 0 ,0
Exp/Cntr=0.3,0.1

Type RM Length L Ch R = 1 ,25052   ,552,552,552
BEGIN DESCRIPTION:
UNT 035 in BCW 42.0
END DESCRIPTION:
XS GIS Cut Line= 3
      1961208.43     13570417.84       1960549.6     13570055.88
      1959851.66     13569660.03
#Sta/Elev= 30
  4420.8  687.88  4504.8  687.58  4667.8  683.18  4801.2  682.21  4846.8  681.42
  4881.1  679.98  4917.9  679.61  4955.8  676.98  4990.4  676.62  4990.9  675.82
  4996.4  675.82  4996.9  676.62  5021.2  677.06  5037.2  678.03  5075.1  677.75
  5118.7  678.78  5199.9  679.67  5286.4  680.02  5383.1  682.22  5453.7   682.5
  5507.1     684  5580.2  685.25  5593.6  685.07  5609.5  685.79  5733.6  687.02
  5764.1  687.65  5830.2  690.11  5873.5  690.33  5895.1   691.9  5974.9  692.95
#Mann= 3 ,-1 , 0
  4420.8      .1       0  4990.4     .07       0  4996.9      .1       0
Bank Sta=4990.4,4996.9
XS Rating Curve= 0 ,0
Exp/Cntr=0.3,0.1

Type RM Length L Ch R = 1 ,24500   ,302,302,302
BEGIN DESCRIPTION:
UNT 035 in BCW 41.0
END DESCRIPTION:
XS GIS Cut Line= 3
      1961278.74      13570032.4      1961018.35     13569704.32
      1959848.28     13569202.49
#Sta/Elev= 30
  4309.4  686.04    4382  685.65  4466.9  686.34  4673.6  679.51  4738.3  678.46
  4743.7  679.05  4761.8  678.15    4867  676.88    4896  675.73  4946.2  674.99
  4946.7  674.19  4952.3  674.19  4952.8  674.99  4990.3  675.11  5003.9  675.89
  5013.8  675.06  5019.3  675.97  5042.8  675.21  5071.8  675.54  5254.2  679.44
  5452.5  681.33  5628.4  684.84  5699.1  688.22  5757.1  689.39  5775.2  690.58
  5780.6  690.14  5804.2  691.55  5809.7  691.14  5927.5  696.03  6001.4  698.03
#Mann= 3 ,-1 , 0
  4309.4      .1       0  4946.2     .07       0  4952.8      .1       0
Bank Sta=4946.2,4952.8
XS Rating Curve= 0 ,0
Exp/Cntr=0.3,0.1

Type RM Length L Ch R = 1 ,24198   ,14,14,14
BEGIN DESCRIPTION:
Mapping XS 9ce01a76
END DESCRIPTION:
XS GIS Cut Line= 4
       1961286.6     13569993.41      1961018.35     13569584.52
      1960877.72     13569251.19      1960537.19     13568739.08
#Sta/Elev= 30
    4283  685.78  4426.6  686.29  4825.8  675.28  4843.5  678.42  4848.9  674.08
  4867.2  675.83  4872.6  672.99  4896.4  677.95  4901.8  673.49  4920.1  677.82
  4925.5  674.44  4943.8  677.02  4949.2  673.16  4972.9  677.23  4978.4  674.21
  4996.7  675.47  5002.1  671.98  5049.5  674.13    5097  672.74  5098.9  670.42
  5099.4  669.62  5105.8  670.42  5183.6  678.72  5270.8  676.93  5442.1  681.54
  5527.8  687.15  5580.4  688.81  5595.4  694.96  5648.7  700.88  5748.8  709.44
#Mann= 5 ,-1 , 0
    4283      .1       0  5098.9     .07       0  5105.8      .1       0
  5527.8     .05       0  5648.7      .1       0
Bank Sta=5098.9,5105.8
XS Rating Curve= 0 ,0
Exp/Cntr=0.3,0.1

Type RM Length L Ch R = 1 ,24184   ,46,46,46
BEGIN DESCRIPTION:
Mapping XS a6826141
END DESCRIPTION:
XS GIS Cut Line= 5
      1961304.82     13569964.75      1961039.18     13569548.07
      1960950.64     13569399.63      1960893.35     13569188.69
      1960570.45     13568730.39
#Sta/Elev= 30
  4298.6  685.53  4442.2  685.43  4733.3  677.56  4775.6  681.02  4827.8  681.86
  4907.6  681.54  4913.4  679.16    4929  677.49  4944.6  679.47  4950.4  677.86
  4965.4  679.17  4971.8  677.23  5001.2  679.25  5006.4  676.66  5032.6  679.52
    5041  679.82  5046.2  677.25    5074  680.74    5086   678.9  5115.5  680.87
  5192.4  679.57  5254.2  675.45  5254.7  674.65  5261.1  675.45  5507.2  684.96
  5537.3  687.95  5580.1  688.67  5587.8   693.5  5630.5  698.95  5744.8     707
#Mann= 5 ,-1 , 0
  4298.6      .1       0  5254.2     .07       0  5261.1      .1       0
  5507.2     .05       0  5630.5      .1       0
Bank Sta=5254.2,5261.1
XS Rating Curve= 0 ,0
Exp/Cntr=0.3,0.1

Type RM Length L Ch R = 1 ,24138   ,368,368,368
BEGIN DESCRIPTION:
Mapping XS 4ba22c2c
END DESCRIPTION:
XS GIS Cut Line= 5
      1961317.84      13569938.7      1961033.97     13569464.73
      1960963.66     13569303.27      1960940.22     13569178.27
      1960630.34     13568725.16
#Sta/Elev= 30
  4315.4  685.46  4459.6  684.76  4625.6  680.34  4662.5  680.54  4757.8  676.18
  4858.9  675.25  4875.4     674  4933.2  674.68  5020.3   673.1  5032.4  674.43
  5057.2  672.83  5057.7  672.03  5064.1  672.83  5065.8     674  5118.3  674.84
    5144  673.81  5191.3  675.08    5257  674.25  5292.9  676.25  5298.9  677.65
  5385.6  678.89  5476.1  682.12  5508.2  684.26  5523.1  687.59  5547.6  688.19
  5565.1  687.54    5580  692.66  5598.1  694.16  5636.8  698.66  5720.1  702.83
#Mann= 6 ,-1 , 0
  4315.4      .1       0  5057.2     .07       0  5064.1      .1       0
  5476.1     .08       0  5547.6     .05       0  5598.1      .1       0
Bank Sta=5057.2,5064.1
XS Rating Curve= 0 ,0
Exp/Cntr=0.3,0.1

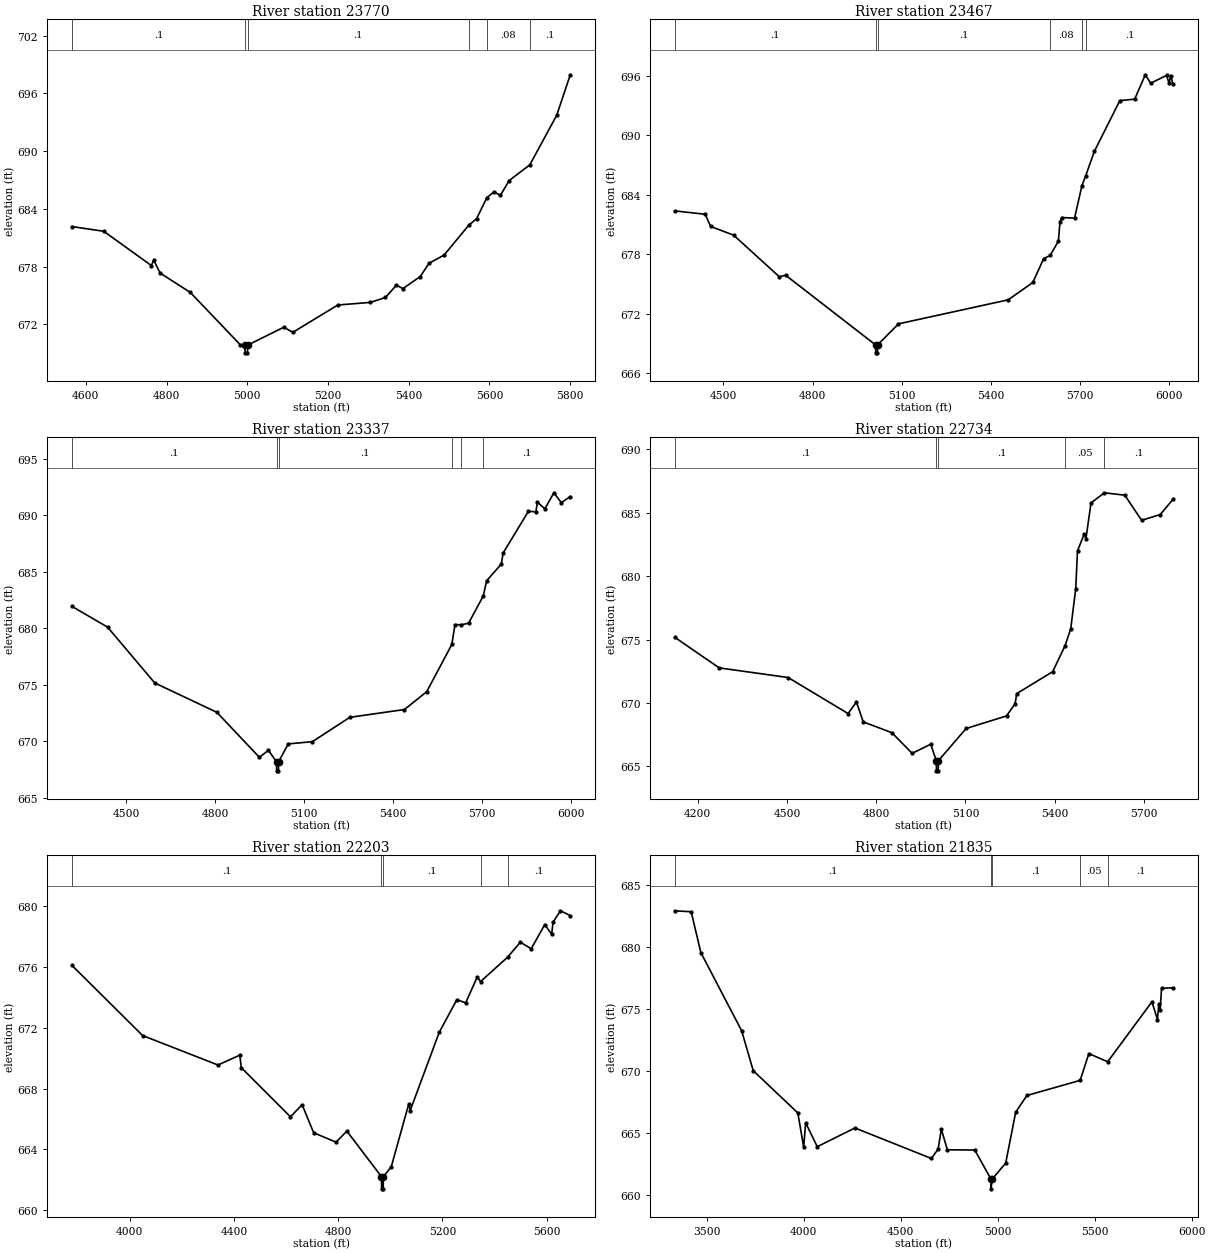
Type RM Length L Ch R = 1 ,23770   ,303,303,303
BEGIN DESCRIPTION:
Mapping XS 116c5ca4
END DESCRIPTION:
XS GIS Cut Line= 2
      1961498.45     13569529.87      1960884.75      13568458.5
#Sta/Elev= 30
  4565.5  682.15  4644.4  681.66  4762.4   678.1  4768.2  678.67    4784  677.32
  4858.8  675.31  4982.6  669.87  4994.1  669.83  4994.6  669.03  5000.5  669.03
    5001  669.83  5090.5  671.69  5112.8  671.16  5224.3     674  5304.9  674.27
  5342.3  674.78  5369.6  676.07  5385.4   675.7  5428.6  676.96  5450.2  678.33
  5487.6  679.19  5548.9   682.3  5568.2  682.97  5593.5  685.16  5611.3  685.75
  5627.1  685.39  5648.7  686.93  5699.9  688.56  5766.7  693.72  5800.2  697.92
#Mann= 6 ,-1 , 0
  4565.5      .1       0  4994.1     .07       0    5001      .1       0
  5548.9     .05       0  5593.5     .08       0  5699.9      .1       0
Bank Sta=4994.1,5001
XS Rating Curve= 0 ,0
Exp/Cntr=0.3,0.1

Type RM Length L Ch R = 1 ,23467   ,130,130,130
BEGIN DESCRIPTION:
UNT 035 in BCW 40.0
END DESCRIPTION:
XS GIS Cut Line= 4
      1961681.56     13569549.84      1961545.34     13569134.07
      1961295.34     13568389.28      1961136.48     13567964.77
#Sta/Elev= 30
  4335.6  682.38  4438.8  682.04  4456.4  680.82  4534.3  679.93    4688  675.74
    4709   675.9  5011.5  668.88    5012  668.08    5018  668.08  5018.5  668.88
  5088.6     671  5457.8  673.42  5540.5  675.17  5576.7  677.56  5599.1   677.9
  5626.5  679.34  5631.9  681.28  5638.1  681.71  5680.8  681.65  5705.6  684.91
  5718.5  685.93  5747.7  688.39  5833.2  693.49  5883.1  693.63  5918.7  696.09
    5937  695.24  5990.4  696.03  5998.9  695.23  6004.2  696.01    6012  695.13
#Mann= 6 ,-1 , 0
  4335.6      .1       0  5011.5     .07       0  5018.5      .1       0
  5599.1     .08       0  5705.6     .05       0  5718.5      .1       0
Bank Sta=5011.5,5018.5
XS Rating Curve= 0 ,0
Exp/Cntr=0.3,0.1

Type RM Length L Ch R = 1 ,23337   ,603,603,603
BEGIN DESCRIPTION:
UNT 035 in BCW 39.0
END DESCRIPTION:
XS GIS Cut Line= 4
        1961725.     13569474.97      1961691.96     13569200.84
        1961468.     13568575.84      1961209.91     13567880.21
#Sta/Elev= 30
  4316.5  681.93  4437.1  680.09    4596  675.16  4805.9  672.56  4949.1  668.59
  4979.9   669.2  5007.1  668.19  5007.6  667.39  5013.6  667.39  5014.1  668.19
  5046.7  669.77  5128.3  669.97  5254.3  672.12  5438.8  672.81  5514.1  674.39
  5598.7  678.56  5609.4  680.32  5629.9   680.3  5655.3  680.44    5705  682.86
  5716.1  684.19  5766.2  685.68  5771.5  686.63  5857.3  690.34  5882.3  690.28
  5887.6  691.14  5912.7  690.55  5943.1  691.97  5968.1   691.1  5998.5  691.63
#Mann= 6 ,-1 , 0
  4316.5      .1       0  5007.1     .07       0  5014.1      .1       0
  5598.7     .08       0  5629.9     .05       0    5705      .1       0
Bank Sta=5007.1,5014.1
XS Rating Curve= 0 ,0
Exp/Cntr=0.3,0.1

Type RM Length L Ch R = 1 ,22734   ,531,531,531
BEGIN DESCRIPTION:
UNT 035 in BCW 38.0
END DESCRIPTION:
XS GIS Cut Line= 3
      1962056.54     13569273.77      1962125.99     13568704.32
      1961652.16      13567709.8
#Sta/Elev= 30
  4122.5  675.19  4272.4  672.77  4504.1  672.01  4705.5  669.17  4733.8  670.08
  4756.5  668.51  4852.8  667.66  4920.9  666.03  4983.4  666.75  5002.1  665.45
  5002.6  664.65  5008.6  664.65  5009.1  665.45  5102.5  667.99  5238.2  668.98
    5267  669.94  5272.5  670.74  5393.3  672.47    5435  674.52  5454.1  675.86
  5470.8  679.02  5476.8  681.99  5499.5  683.34  5505.1  682.95  5522.2  685.78
  5567.1  686.58  5635.7  686.39  5692.3  684.41  5754.8  684.86  5797.8  686.06
#Mann= 5 ,-1 , 0
  4122.5      .1       0  5002.1     .07       0  5009.1      .1       0
    5435     .05       0  5567.1      .1       0
Bank Sta=5002.1,5009.1
XS Rating Curve= 0 ,0
Exp/Cntr=0.3,0.1

Type RM Length L Ch R = 1 ,22203   ,368,368,368
BEGIN DESCRIPTION:
UNT 035 in BCW 37.0
END DESCRIPTION:
XS GIS Cut Line= 3
       1962117.3      13569438.7      1962540.92     13568570.63
       1962280.5     13567660.89
#Sta/Elev= 30
  3778.1  676.11  4049.3  671.49  4338.6  669.55  4422.4   670.2  4427.9  669.38
  4616.8  666.14  4661.3  666.94  4705.8  665.09  4791.5  664.47  4833.1   665.2
  4965.9   662.2  4966.4   661.4  4972.5   661.4    4973   662.2  5003.2  662.84
  5070.8     667    5076  666.55  5187.7  671.71  5255.2  673.85    5289  673.64
  5333.2  675.34    5346  675.04  5449.5  676.64  5498.8  677.63  5540.4   677.2
  5592.4  678.79  5618.9  678.15  5624.1  678.95  5652.7   679.7  5690.3  679.38
#Mann= 5 ,-1 , 0
  3778.1      .1       0  4965.9     .07       0    4973      .1       0
    5346     .05       0  5449.5      .1       0
Bank Sta=4965.9,4973
XS Rating Curve= 0 ,0
Exp/Cntr=0.3,0.1

Type RM Length L Ch R = 1 ,21835   ,1278,1278,1278
BEGIN DESCRIPTION:
Mapping XS 34284928
END DESCRIPTION:
XS GIS Cut Line= 4
      1962613.84      13569980.4      1962606.89     13569171.33
      1962870.78     13568195.63      1962347.74     13567658.74
#Sta/Elev= 30
  3334.4   682.9  3419.8  682.82  3469.8  679.52  3679.8  673.23  3739.8     670
  3969.8  666.59  3999.8  663.82  4009.8   665.8  4069.8  663.87    4264  665.38
  4658.1  662.92  4692.8  663.67  4709.5  665.28  4740.5  663.62  4881.8   663.6
  4964.9  661.27  4965.4  660.47    4972  661.27  5041.2  662.54  5092.8  666.65
  5150.5     668  5425.1  669.22    5470  671.38  5567.1  670.72  5795.3  675.56
  5823.6  674.12  5830.6  675.36  5837.7   674.9  5844.7  676.64  5903.8  676.69
#Mann= 5 ,-1 , 0
  3334.4      .1       0  4964.9     .07       0    4972      .1       0
  5425.1     .05       0  5567.1      .1       0
Bank Sta=4964.9,4972
XS Rating Curve= 0 ,0
Exp/Cntr=0.3,0.1