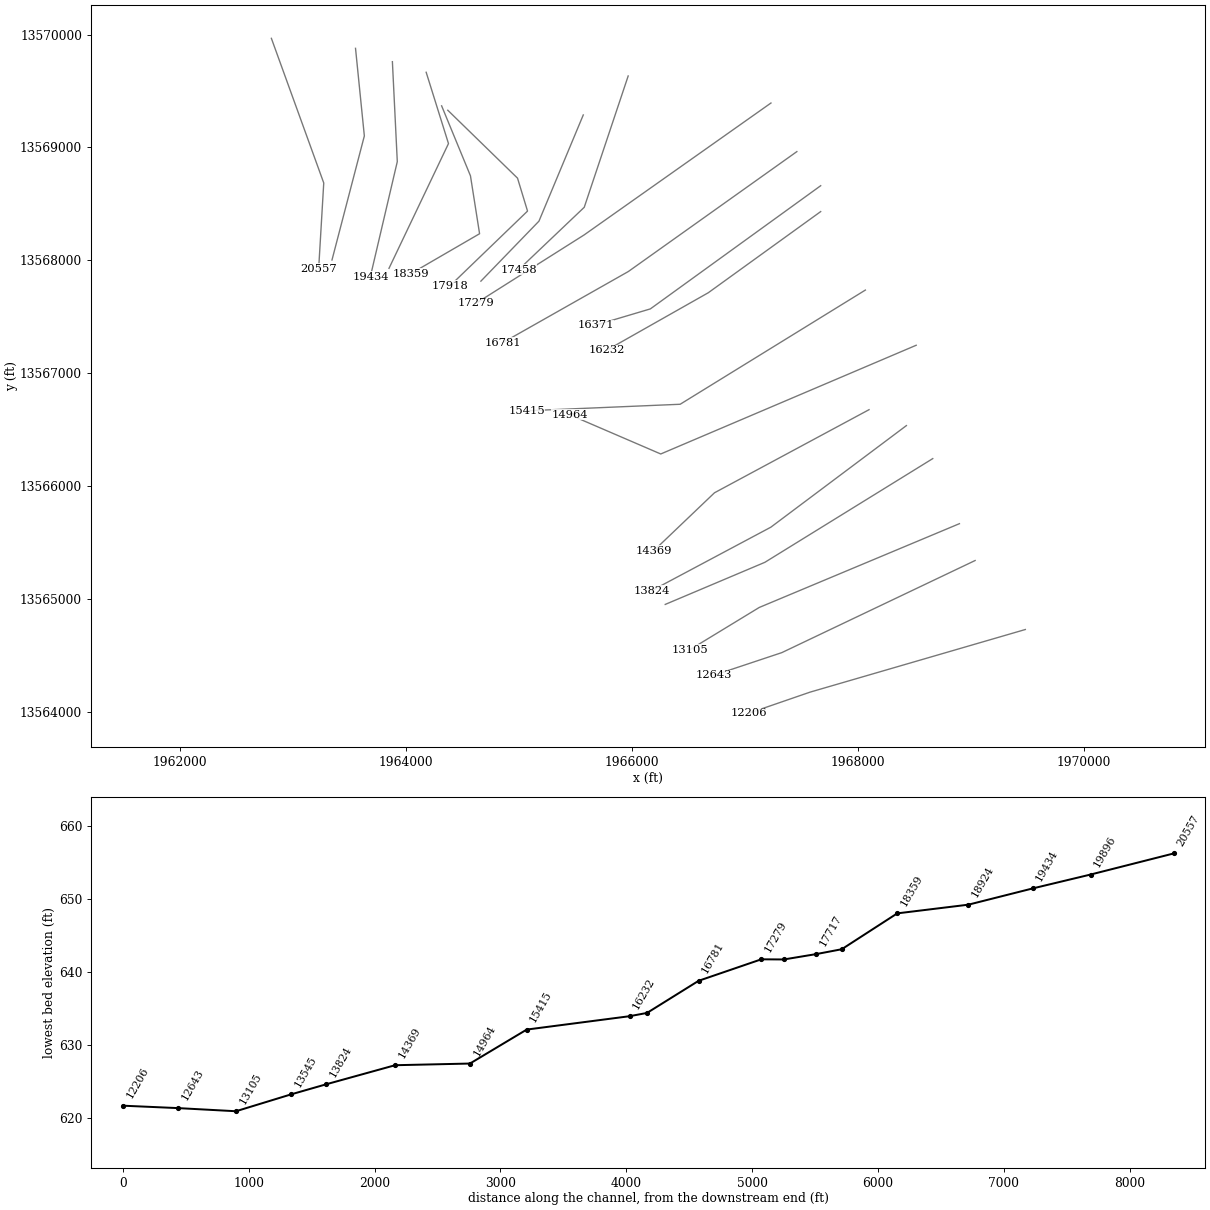
HEC-RAS study UNT 035 in BCW.prj: UNT 035 in BCW Base Level Engineering

--- UNT 035 in BCW.g01 (geometry) --- (continued)

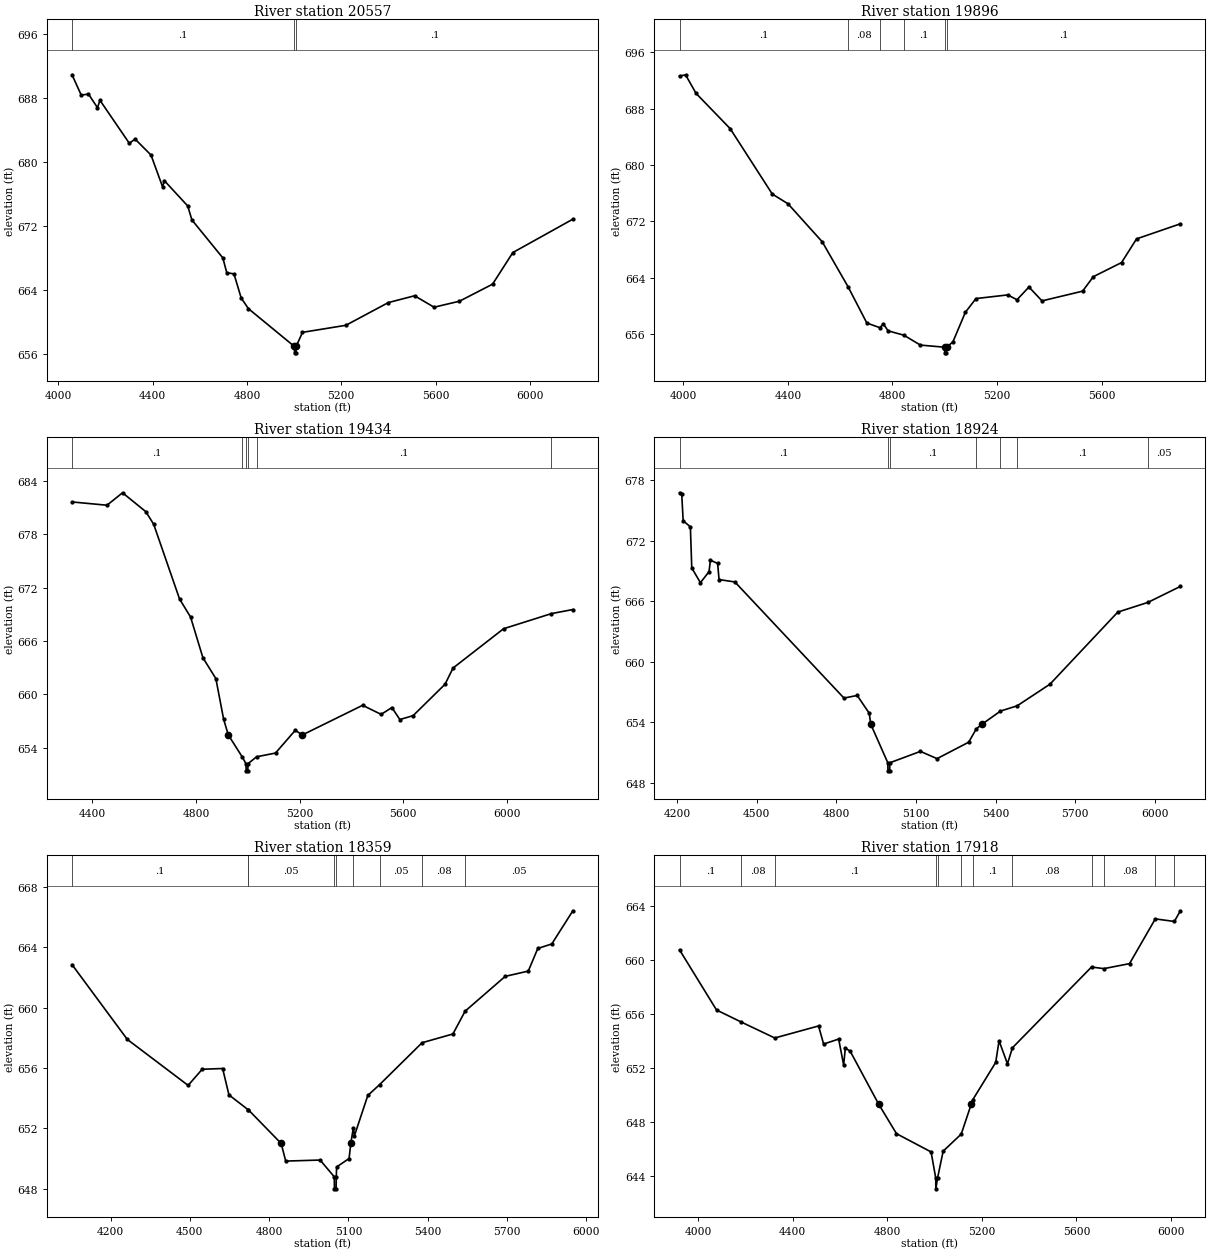
Type RM Length L Ch R = 1 ,20557   ,661,661,661
BEGIN DESCRIPTION:
UNT 035 in BCW 36.0
END DESCRIPTION:
XS GIS Cut Line= 3
      1962806.55     13569966.45      1963270.09     13568685.22
        1963225.     13567924.96
#Sta/Elev= 30
  4058.1  690.94  4097.2   688.4  4127.9  688.53    4166  686.83  4176.6  687.75
  4301.1  682.38  4325.5  682.91  4393.1  680.91  4442.5  676.91  4449.1  677.73
  4548.8  674.55  4566.4  672.81  4697.7  668.06  4714.3  666.22  4744.9  666.06
  4775.6  663.05  4806.2  661.72  5001.1     657  5001.7   656.2    5008   656.2
  5008.6     657  5035.5  658.76  5219.3  659.64  5399.6  662.48    5511  663.33
  5593.5   661.9  5701.3  662.65  5841.6  664.78  5927.7  668.73  6182.2   672.9
#Mann= 3 ,-1 , 0
  4058.1      .1       0  5001.1     .07       0  5008.6      .1       0
Bank Sta=5001.1,5008.6
XS Rating Curve= 0 ,0
Exp/Cntr=0.3,0.1

Type RM Length L Ch R = 1 ,19896   ,462,462,462
BEGIN DESCRIPTION:
UNT 035 in BCW 35.0
END DESCRIPTION:
XS GIS Cut Line= 3
      1963551.34     13569877.91      1963629.46     13569101.88
      1963343.01     13568002.95
#Sta/Elev= 30
  3985.6  692.61  4008.6  692.81  4048.8  690.17  4179.5  685.15  4340.3  675.87
  4400.6  674.48  4531.3  669.09    4630  662.71  4702.1  657.54  4751.6  656.89
  4765.5  657.42    4783  656.44  4843.3  655.82    4907  654.41  4999.4  654.11
    5000  653.31  5006.4  653.31    5007  654.11    5031  654.85    5079  659.08
  5119.5  661.02    5241  661.54  5276.3  660.85    5322  662.66    5372  660.69
  5527.1  662.07  5568.4  664.13  5676.1  666.13  5733.7   669.5  5901.2  671.64
#Mann= 6 ,-1 , 0
  3985.6      .1       0    4630     .08       0  4751.6     .05       0
  4843.3      .1       0  4999.4     .07       0    5007      .1       0
Bank Sta=4999.4,5007
XS Rating Curve= 0 ,0
Exp/Cntr=0.3,0.1

Type RM Length L Ch R = 1 ,19434   ,510,510,510
BEGIN DESCRIPTION:
UNT 035 in BCW 34.0
END DESCRIPTION:
XS GIS Cut Line= 3
      1963877.73     13569759.83      1963921.13     13568874.45
       1963682.4     13567854.45
#Sta/Elev= 30
    4321  681.64    4456  681.27  4516.1  682.67  4606.2  680.54  4636.2  679.14
  4736.3  670.72  4778.7   668.7  4826.4  664.12  4876.5  661.77  4906.5  657.19
 4924.56655.4335  4979.2  652.92  4992.8   652.2  4993.4   651.4  4999.8   651.4
  5000.4   652.2  5033.7  652.98  5106.8   653.4  5183.1  655.96 5210.17655.4331
  5443.1  658.77  5514.7  657.75  5556.1  658.52  5586.9  657.17  5638.2  657.61
  5761.5  661.14  5792.3  662.96  5987.4  667.38  6171.9  669.08    6255  669.54
#Mann= 6 ,-1 , 0
    4321      .1       0  4979.2     .05       0  4992.8     .04       0
  5000.4     .05       0  5033.7      .1       0  6171.9     .08       0
Bank Sta=4924.56,5210.17
XS Rating Curve= 0 ,0
Exp/Cntr=0.3,0.1

Type RM Length L Ch R = 1 ,18924   ,565,565,565
BEGIN DESCRIPTION:
UNT 035 in BCW 33.0
END DESCRIPTION:
XS GIS Cut Line= 3
      1964176.76     13569665.72      1964374.25     13569034.18
      1963847.74      13567929.1
#Sta/Elev= 30
  4209.7  676.77  4218.1   676.6  4223.4  673.99  4250.6  673.39  4255.8  669.31
  4288.3  667.85  4320.8  668.94    4326  670.08  4353.2  669.76  4358.5  668.16
  4418.2  667.92  4828.8   656.4  4878.7  656.66  4924.1  654.89  4929.6  653.81
  4993.9  649.98  4994.5  649.18  5000.9  649.18  5001.5  649.98  5116.8  651.11
  5179.3  650.39  5298.4  652.02  5327.3  653.35 5348.82653.8107  5418.2  655.11
  5480.9  655.63  5604.6  657.78  5859.8  664.93    5973  665.89  6095.5  667.48
#Mann= 7 ,-1 , 0
  4209.7      .1       0  4993.9     .07       0  5001.5      .1       0
  5327.3     .08       0  5418.2     .05       0  5480.9      .1       0
    5973     .05       0
Bank Sta=4929.6,5348.82
XS Rating Curve= 0 ,0
Exp/Cntr=0.3,0.1

Type RM Length L Ch R = 1 ,18359   ,441,441,441
BEGIN DESCRIPTION:
UNT 035 in BCW 32.0
END DESCRIPTION:
XS GIS Cut Line= 4
      1964313.57     13569368.44      1964568.78     13568748.65
      1964649.51     13568235.63      1964039.16     13567881.02
#Sta/Elev= 30
    4054  662.86  4263.2   657.9  4493.4  654.85  4546.7  655.92    4624  655.97
  4647.9  654.22    4721  653.23  4721.5  653.23 4845.52651.0004  4862.7  649.83
  4992.8   649.9  5046.5  648.79  5047.1  647.99  5053.5  647.99  5054.2  648.79
  5055.4  649.44  5102.5     650 5109.06651.0002  5118.7  652.04    5123  651.52
  5173.4  654.18    5218   654.9  5378.9  657.68  5495.6  658.26  5541.6  659.77
  5693.4  662.08  5780.8  662.43  5816.7  663.93  5869.7  664.23  5949.5  666.43
#Mann= 9 ,-1 , 0
    4054      .1       0    4721     .08       0  4721.5     .05       0
  5046.5     .04       0  5054.2     .05       0  5118.7     .08       0
    5218     .05       0  5378.9     .08       0  5541.6     .05       0
Bank Sta=4845.52,5109.06
XS Rating Curve= 0 ,0
Exp/Cntr=0.3,0.1

Type RM Length L Ch R = 1 ,17918   ,201,201,201
BEGIN DESCRIPTION:
UNT 035 in BCW 31.0
END DESCRIPTION:
XS GIS Cut Line= 4
      1964368.28     13569329.36      1964985.45     13568727.82
      1965073.99     13568436.15      1964389.94     13567776.42
#Sta/Elev= 30
  3922.2  660.76  4078.6  656.31    4183  655.42  4324.8  654.24  4509.9  655.13
  4531.2  653.79  4594.8  654.16  4615.9  652.24  4623.1  653.51  4644.2  653.24
  4763.9649.3444  4839.3  647.16  4985.5  645.81  5005.1  643.88  5005.7  643.08
  5012.8  643.88  5036.6  645.87  5112.9  647.13 5155.32649.3453    5162  649.68
  5258.6  652.43  5272.8  654.03  5308.3  652.33  5329.6  653.52  5663.7  659.49
  5715.9  659.37  5824.3  659.74  5933.3  663.05  6013.8  662.86  6039.2  663.65
#Mann= 12 ,-1 , 0
  3922.2      .1       0    4183     .08       0  4324.8      .1       0
  5005.1     .07       0  5012.8      .1       0  5112.9     .05       0
    5162      .1       0  5329.6     .08       0  5663.7     .05       0
  5715.9     .08       0  5933.3      .1       0  6013.8     .08       0
Bank Sta=4763.9,5155.32
XS Rating Curve= 0 ,0
Exp/Cntr=0.3,0.1

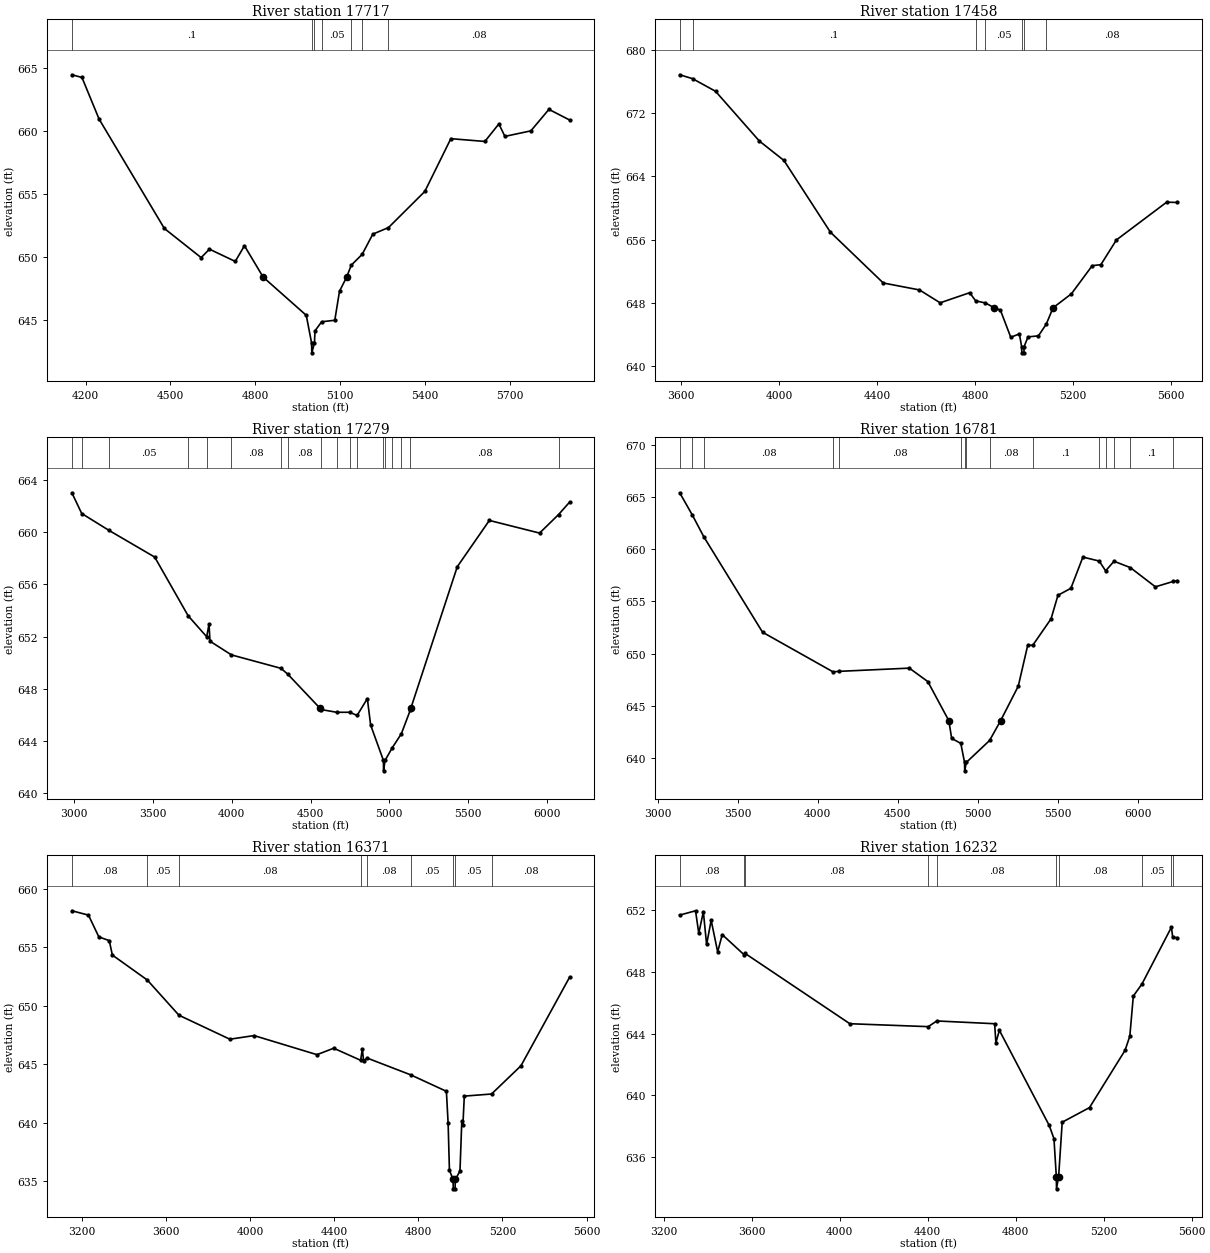
Type RM Length L Ch R = 1 ,17717   ,259,259,259
BEGIN DESCRIPTION:
Mapping XS f51f83fd
END DESCRIPTION:
XS GIS Cut Line= 3
      1965567.39     13569287.84      1965175.04      13568346.9
      1964661.14     13567815.65
#Sta/Elev= 30
  4151.5  664.44  4187.1  664.23  4247.7  660.93  4478.3  652.27  4608.3  649.96
  4637.6  650.63  4728.8  649.66  4761.3   650.9 4827.42648.4169  4979.8  645.39
  4998.4  643.22  4999.4  642.42  5008.8  643.22  5010.5  644.16  5034.1  644.88
  5080.5     645  5097.2   647.3 5122.44648.4168  5138.7  649.36  5177.3  650.22
  5214.9  651.82  5270.3  652.34  5398.6   655.2  5490.6  659.38  5610.8  659.16
  5660.4  660.55  5681.5  659.56  5773.4     660  5837.2   661.7  5910.1  660.86
#Mann= 7 ,-1 , 0
  4151.5      .1       0  4998.4     .07       0  5008.8      .1       0
  5034.1     .05       0  5138.7      .1       0  5177.3     .05       0
  5270.3     .08       0
Bank Sta=4827.42,5122.44
XS Rating Curve= 0 ,0
Exp/Cntr=0.3,0.1

Type RM Length L Ch R = 1 ,17458   ,179,179,179
BEGIN DESCRIPTION:
UNT 035 in BCW 30.0
END DESCRIPTION:
XS GIS Cut Line= 3
      1965964.95      13569633.1      1965576.07     13568469.94
      1964993.17     13567915.24
#Sta/Elev= 30
  3594.6  676.87    3647  676.38  3740.9  674.78  3919.5  668.49  4019.9  666.03
  4209.4  656.96  4425.3  650.52  4573.2  649.64  4657.5  648.01    4778  649.29
  4802.3  648.26  4842.5  647.99 4878.33647.3806  4903.2   647.1  4945.7  643.65
  4980.9  644.08  4989.9  642.48  4990.8  641.68  4999.3  641.68  5000.3  642.48
  5016.1   643.7  5058.6  643.83  5090.5  645.31 5118.31647.3806  5193.2  649.15
  5278.1  652.71  5313.4  652.84  5376.9  655.97    5582  660.75  5625.7  660.71
#Mann= 7 ,-1 , 0
  3594.6     .05       0    3647      .1       0  4802.3     .08       0
  4842.5     .05       0  4989.9     .04       0  5000.3     .05       0
  5090.5     .08       0
Bank Sta=4878.33,5118.31
XS Rating Curve= 0 ,0
Exp/Cntr=0.3,0.1

Type RM Length L Ch R = 1 ,17279   ,498,498,498
BEGIN DESCRIPTION:
UNT 035 in BCW 29.0
END DESCRIPTION:
XS GIS Cut Line= 3
      1967228.83     13569393.53        1965575.       13568225.
      1964617.76     13567619.26
#Sta/Elev= 30
  2985.5  663.02  3048.1  661.43  3220.5  660.14    3511  658.09  3723.2  653.59
    3841  651.98  3855.8  652.95  3861.9  651.64  3997.9  650.59  4312.2  649.56
  4355.5  649.11 4561.37646.4805  4566.6   646.4  4665.7  646.19  4748.3  646.19
  4795.4  645.95  4860.3  647.24  4881.2  645.21  4962.2   642.5  4963.1   641.7
  4972.6   642.5  5018.9  643.48  5075.9  644.54    5133  646.36  5135.7646.4802
  5430.9  657.35  5634.4   660.9  5953.1  659.93  6073.5  661.35  6143.3   662.3
#Mann= 18 ,-1 , 0
  2985.5     .05       0  3048.1     .08       0  3220.5     .05       0
  3723.2     .08       0    3841     .05       0  3997.9     .08       0
  4312.2     .05       0  4355.5     .08       0  4566.6     .05       0
  4665.7     .08       0  4748.3      .1       0  4795.4     .08       0
  4962.2     .07       0  4972.6     .08       0  5018.9      .1       0
  5075.9     .05       0    5133     .08       0  6073.5     .05       0
Bank Sta=4561.37,5135.7
XS Rating Curve= 0 ,0
Exp/Cntr=0.3,0.1

Type RM Length L Ch R = 1 ,16781   ,410,410,410
BEGIN DESCRIPTION:
UNT 035 in BCW 28.0
END DESCRIPTION:
XS GIS Cut Line= 3
      1967458.02       13568963.      1965966.67     13567901.04
      1964853.82     13567270.27
#Sta/Elev= 30
  3138.1   665.4  3216.6  663.28  3288.9  661.18  3655.9  652.04  4096.6  648.24
    4131  648.29  4573.1   648.6  4688.6  647.31  4820.2643.5546  4837.4  641.87
  4894.7  641.39  4918.2  639.56  4919.1  638.76  4928.7  639.56  5074.6  641.67
 5143.05643.5542  5253.7  646.87  5312.9   650.8  5344.3  650.79  5458.5  653.32
  5501.8  655.58  5582.6  656.25  5657.6  659.24  5759.3  658.86  5799.7  657.92
  5852.1  658.84  5954.2  658.23  6110.6  656.39  6223.1  656.91  6248.1  656.98
#Mann= 15 ,-1 , 0
  3138.1     .08       0  3216.6     .05       0  3288.9     .08       0
  4096.6     .05       0    4131     .08       0  4894.7     .05       0
  4918.2     .04       0  4928.7     .05       0  5074.6     .08       0
  5344.3      .1       0  5759.3     .08       0  5799.7      .1       0
  5852.1     .08       0  5954.2      .1       0  6223.1     .15       0
Bank Sta=4820.2,5143.05
XS Rating Curve= 0 ,0
Exp/Cntr=0.3,0.1

Type RM Length L Ch R = 1 ,16371   ,139,139,139
BEGIN DESCRIPTION:
UNT 035 in BCW 27.0
END DESCRIPTION:
XS GIS Cut Line= 3
      1967668.96     13568660.92      1966161.14     13567569.77
      1965674.96     13567424.99
#Sta/Elev= 30
  3150.7  658.11  3229.7  657.74    3279  655.88  3328.7  655.56  3343.4  654.33
  3509.4   652.2  3660.2  649.19  3902.6  647.14  4017.8  647.45  4317.1  645.82
  4396.8  646.37    4525  645.34  4532.9  646.31  4539.1   645.3  4555.9  645.53
    4764  644.09  4933.1  642.69  4941.3  639.96  4947.5  635.95  4964.9  635.16
  4965.8  634.36  4974.5  634.36  4975.4  635.16  4997.7  635.88  5006.3  640.13
  5011.7  639.83  5018.3  642.28  5147.9  642.46  5287.9  644.87  5519.2  652.43
#Mann= 9 ,-1 , 0
  3150.7     .08       0  3509.4     .05       0  3660.2     .08       0
    4525     .05       0  4555.9     .08       0    4764     .05       0
  4964.9     .04       0  4975.4     .05       0  5147.9     .08       0
Bank Sta=4964.9,4975.4
XS Rating Curve= 0 ,0
Exp/Cntr=0.3,0.1

Type RM Length L Ch R = 1 ,16232   ,817,817,817
BEGIN DESCRIPTION:
UNT 035 in BCW 26.0
END DESCRIPTION:
XS GIS Cut Line= 3
      1967668.94     13568431.73      1966674.17       13567713.
      1965773.14     13567202.59
#Sta/Elev= 30
  3272.5   651.7  3344.5  651.98  3359.2  650.52  3380.1  651.91  3394.8  649.79
  3415.6  651.36  3445.1  649.31  3465.9  650.43  3565.4  649.12  3569.7  649.21
  4046.1  644.64  4402.4  644.45  4441.6  644.82  4704.3  644.64  4710.1  643.41
    4726  644.21  4952.5  638.03  4974.1  637.17  4984.8  634.71  4985.7  633.91
  4995.3  634.71  5011.6  638.24  5135.7  639.19  5297.3  642.91    5319  643.83
  5334.9  646.44  5374.1  647.22  5508.1  650.91  5514.1  650.25  5535.3  650.23
#Mann= 10 ,-1 , 0
  3272.5     .08       0  3565.4     .05       0  3569.7     .08       0
  4402.4      .1       0  4441.6     .08       0  4984.8     .07       0
  4995.3     .08       0  5374.1     .05       0  5508.1     .08       0
  5514.1      .1       0
Bank Sta=4984.8,4995.3
XS Rating Curve= 0 ,0
Exp/Cntr=0.3,0.1

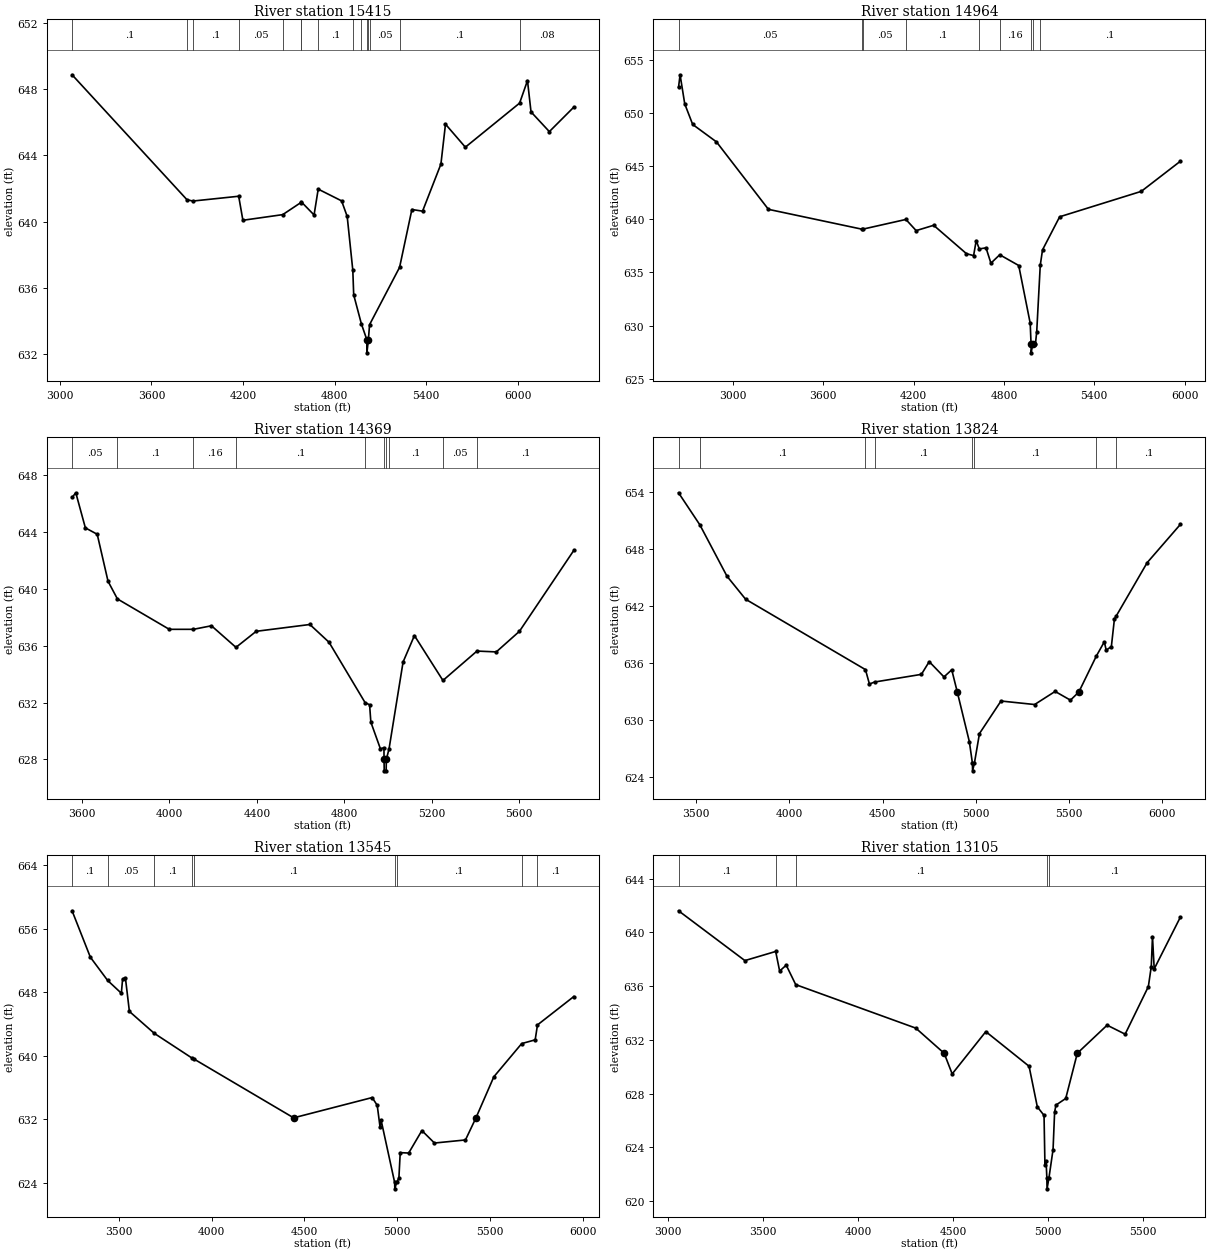
Type RM Length L Ch R = 1 ,15415   ,451,451,451
BEGIN DESCRIPTION:
UNT 035 in BCW 25.0
END DESCRIPTION:
XS GIS Cut Line= 3
      1968064.54     13567736.62        1966425.       13566725.
      1965064.54     13566667.17
#Sta/Elev= 30
  3080.3  648.86  3833.3  641.32  3871.6  641.24  4172.2  641.53  4199.7  640.08
  4460.7  640.42  4579.8  641.15  4580.4  641.21  4666.1   640.4  4693.2  641.96
  4846.6  641.25  4883.2  640.31    4920  637.06  4925.8  635.58  4976.1  633.83
  5011.6  632.88  5012.4  632.08  5022.1  632.88  5029.8  633.78  5226.5  637.24
  5307.1  640.73  5377.1  640.63  5497.3  643.47  5527.3  645.88  5657.4  644.49
    6013  647.15  6064.6  648.51  6087.8  646.62  6207.9  645.43  6368.5  646.91
#Mann= 15 ,-1 , 0
  3080.3      .1       0  3833.3     .05       0  3871.6      .1       0
  4172.2     .05       0  4460.7      .1       0  4579.8     .08       0
  4580.4     .05       0  4693.2      .1       0    4920     .05       0
  4976.1     .08       0  5011.6     .07       0  5022.1     .08       0
  5029.8     .05       0  5226.5      .1       0    6013     .08       0
Bank Sta=5011.6,5022.1
XS Rating Curve= 0 ,0
Exp/Cntr=0.3,0.1

Type RM Length L Ch R = 1 ,14964   ,595,595,595
BEGIN DESCRIPTION:
UNT 035 in BCW 24.0
END DESCRIPTION:
XS GIS Cut Line= 3
      1968514.43     13567247.71      1966253.19     13566284.65
      1965448.82     13566631.36
#Sta/Elev= 30
  2638.3   652.4  2648.6  653.57  2679.6  650.83  2732.3   648.9  2890.4  647.26
  3235.5  640.92  3854.9  639.06  3866.7  639.07  4148.8  639.97  4216.9  638.92
  4333.3  639.42  4551.3  636.75  4598.6  636.57  4615.9  637.98  4636.3   637.2
  4681.1   637.3  4713.7  635.86  4772.2  636.65  4898.4  635.64  4974.6  630.22
  4980.4  628.23  4981.2  627.43  4990.9  628.23  5009.2  628.24    5018  629.42
  5041.4  635.66  5056.5  637.11  5170.3  640.22  5712.6  642.61    5972  645.44
#Mann= 9 ,-1 , 0
  2638.3     .05       0  3854.9      .1       0  3866.7     .05       0
  4148.8      .1       0  4636.3     .05       0  4772.2     .16       0
  4980.4     .07       0  4990.9     .16       0  5041.4      .1       0
Bank Sta=4980.4,4990.9
XS Rating Curve= 0 ,0
Exp/Cntr=0.3,0.1

Type RM Length L Ch R = 1 ,14369   ,545,545,545
BEGIN DESCRIPTION:
UNT 035 in BCW 23.0
END DESCRIPTION:
XS GIS Cut Line= 3
      1968096.98     13566677.03      1966728.89      13565940.9
      1966190.69     13565427.01
#Sta/Elev= 30
  3553.9  646.44    3571  646.77  3614.8   644.3  3669.1  643.85  3718.6  640.54
  3761.5   639.3    3999  637.16  4109.7  637.16  4192.1  637.41  4304.4  635.89
    4397  637.02  4642.8   637.5  4730.5  636.25  4895.7     632  4916.3  631.85
    4922  630.63  4965.8  628.75    4982  628.83  4982.4     628  4983.3   627.2
  4992.1   627.2  4992.9     628  5005.5  628.76  5069.6  634.86  5121.5  636.72
  5252.1  633.56    5408  635.63  5496.4  635.57  5602.4  637.02  5851.6  642.72
#Mann= 10 ,-1 , 0
  3553.9     .05       0  3761.5      .1       0  4109.7     .16       0
  4304.4      .1       0  4895.7     .12       0  4982.4     .07       0
  4992.9     .12       0  5005.5      .1       0  5252.1     .05       0
    5408      .1       0
Bank Sta=4982.4,4992.9
XS Rating Curve= 0 ,0
Exp/Cntr=0.3,0.1

Type RM Length L Ch R = 1 ,13824   ,279,279,279
BEGIN DESCRIPTION:
UNT 035 in BCW 22.0
END DESCRIPTION:
XS GIS Cut Line= 3
      1968427.76      13566536.1      1967227.78     13565636.11
      1966175.04     13565075.02
#Sta/Elev= 30
    3405  653.91  3519.1  650.54  3664.9  645.12  3764.9  642.69  4408.1  635.27
  4429.5  633.75  4456.7  633.96  4708.4  634.77  4750.3  636.11  4829.5   634.5
  4871.2  635.25 4901.01632.9035  4965.5  627.69  4982.2   625.4    4983   624.6
  4992.7   625.4    5020  628.53  5135.5  631.96  5316.1  631.59    5426  632.97
  5508.2  632.05 5553.11632.9044  5647.2   636.7    5690   638.2  5700.1  637.32
  5727.8   637.7  5744.1  640.59  5755.1  640.96  5919.8  646.54  6097.9  650.57
#Mann= 8 ,-1 , 0
    3405     .05       0  3519.1      .1       0  4408.1     .16       0
  4456.7      .1       0  4982.2     .07       0  4992.7      .1       0
  5647.2     .05       0  5755.1      .1       0
Bank Sta=4901.01,5553.11
XS Rating Curve= 0 ,0
Exp/Cntr=0.3,0.1

Type RM Length L Ch R = 1 ,13545   ,440,440,440
BEGIN DESCRIPTION:
UNT 035 in BCW 21.0
END DESCRIPTION:
XS GIS Cut Line= 3
      1968661.02     13566243.64        1967175.       13565325.
      1966292.97     13564951.98
#Sta/Elev= 30
  3248.4  658.25    3347   652.4  3440.2  649.47  3514.1  647.86  3520.8  649.68
  3536.2  649.74  3557.4  645.57  3691.5  642.81  3895.2  639.69  3905.1  639.58
 4442.73632.1647    4866  634.72  4893.2  633.74  4908.6  630.98  4914.4  631.84
  4987.2  624.02  4988.1  623.22  4997.7  624.02    5010  624.57  5017.2  627.78
  5062.8  627.73  5133.9  630.56  5201.7  628.99  5368.9  629.38 5425.39632.1644
  5521.9  637.34    5672  641.52  5744.6  641.99    5757  643.87  5953.1  647.45
#Mann= 9 ,-1 , 0
  3248.4      .1       0  3440.2     .05       0  3691.5      .1       0
  3895.2     .05       0  3905.1      .1       0  4987.2     .07       0
  4997.7      .1       0    5672     .05       0    5757      .1       0
Bank Sta=4442.73,5425.39
XS Rating Curve= 0 ,0
Exp/Cntr=0.3,0.1

Type RM Length L Ch R = 1 ,13105   ,462,462,462
BEGIN DESCRIPTION:
UNT 035 in BCW 20.0
END DESCRIPTION:
XS GIS Cut Line= 3
      1968897.14     13565667.26        1967125.       13564925.
      1966509.81     13564550.15
#Sta/Elev= 30
  3055.7  641.61    3405   637.9  3567.1  638.58    3588  637.12  3622.6  637.56
  3672.6  636.11  4304.8  632.87 4454.19630.9965  4496.3  629.46  4673.4  632.61
  4901.1  630.03  4944.5  627.01  4979.9  626.37  4984.7  622.65  4990.6  622.98
  4994.8   621.7  4995.7   620.9  5005.6   621.7  5027.4  623.83  5035.6  626.62
  5042.8  627.14  5094.1  627.63 5155.01630.9966    5312  633.09  5406.9  632.42
    5529  635.96  5544.4  637.45  5550.8  639.69  5559.9  637.28  5697.4  641.13
#Mann= 5 ,-1 , 0
  3055.7      .1       0  3567.1     .05       0  3672.6      .1       0
  4994.8     .07       0  5005.6      .1       0
Bank Sta=4454.19,5155.01
XS Rating Curve= 0 ,0
Exp/Cntr=0.3,0.1

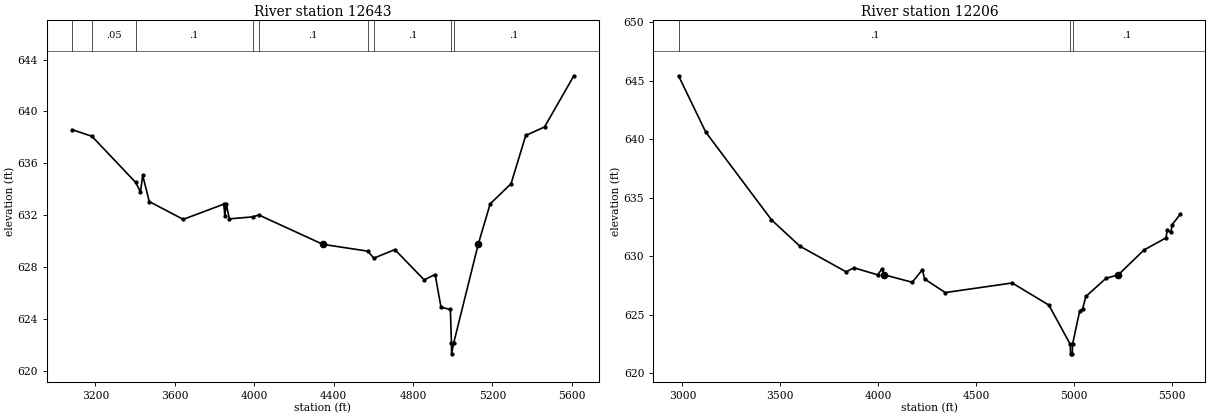
Type RM Length L Ch R = 1 ,12643   ,437,437,437
BEGIN DESCRIPTION:
UNT 035 in BCW 19.0
END DESCRIPTION:
XS GIS Cut Line= 3
      1969036.05     13565340.88        1967325.       13564525.
      1966724.97     13564324.99
#Sta/Elev= 30
  3082.4   638.6  3182.3  638.09  3403.2  634.53    3427   633.8  3438.3  635.08
  3471.3  633.06  3642.5  631.69  3846.8  632.86  3852.3  631.91  3859.1  632.89
    3875  631.73  3992.9  631.88    4023  632.03 4346.07629.7653  4572.2  629.24
  4602.6   628.7  4708.7  629.36  4856.1  627.03  4911.5  627.44  4941.2  624.92
  4988.5  624.75  4993.7  622.13  4994.5  621.33  5004.5  622.13 5128.61629.7652
  5188.8  632.88  5294.2  634.44    5368  638.15  5462.9  638.81  5610.5  642.75
#Mann= 9 ,-1 , 0
  3082.4      .1       0  3182.3     .05       0  3403.2      .1       0
  3992.9     .05       0    4023      .1       0  4572.2     .05       0
  4602.6      .1       0  4993.7     .07       0  5004.5      .1       0
Bank Sta=4346.07,5128.61
XS Rating Curve= 0 ,0
Exp/Cntr=0.3,0.1

Type RM Length L Ch R = 1 ,12206   ,477,477,477
BEGIN DESCRIPTION:
UNT 035 in BCW 18.0
END DESCRIPTION:
XS GIS Cut Line= 3
      1969480.46     13564729.75        1967575.       13564175.
      1967029.51     13563986.85
#Sta/Elev= 30
  2980.3  645.44  3119.3  640.62  3454.7  633.12  3600.5  630.86  3836.4  628.67
  3875.1  629.02  3996.3  628.42  4019.6  628.92 4031.02628.4155  4173.3  627.78
  4225.4  628.86  4236.3  628.06    4342   626.9  4683.7  627.72  4870.7  625.83
  4980.5  622.46  4981.3  621.66  4990.8  621.66  4991.5  622.46  5028.3  625.34
  5042.9  625.51  5060.1  626.57  5162.4  628.12 5225.04628.4154  5356.3  630.54
  5469.1  631.58  5474.4  632.22  5493.8  632.06  5500.3  632.71  5541.9  633.61
#Mann= 3 ,-1 , 0
  2980.3      .1       0  4980.5     .07       0  4991.5      .1       0
Bank Sta=4031.02,5225.04
XS Rating Curve= 0 ,0
Exp/Cntr=0.3,0.1