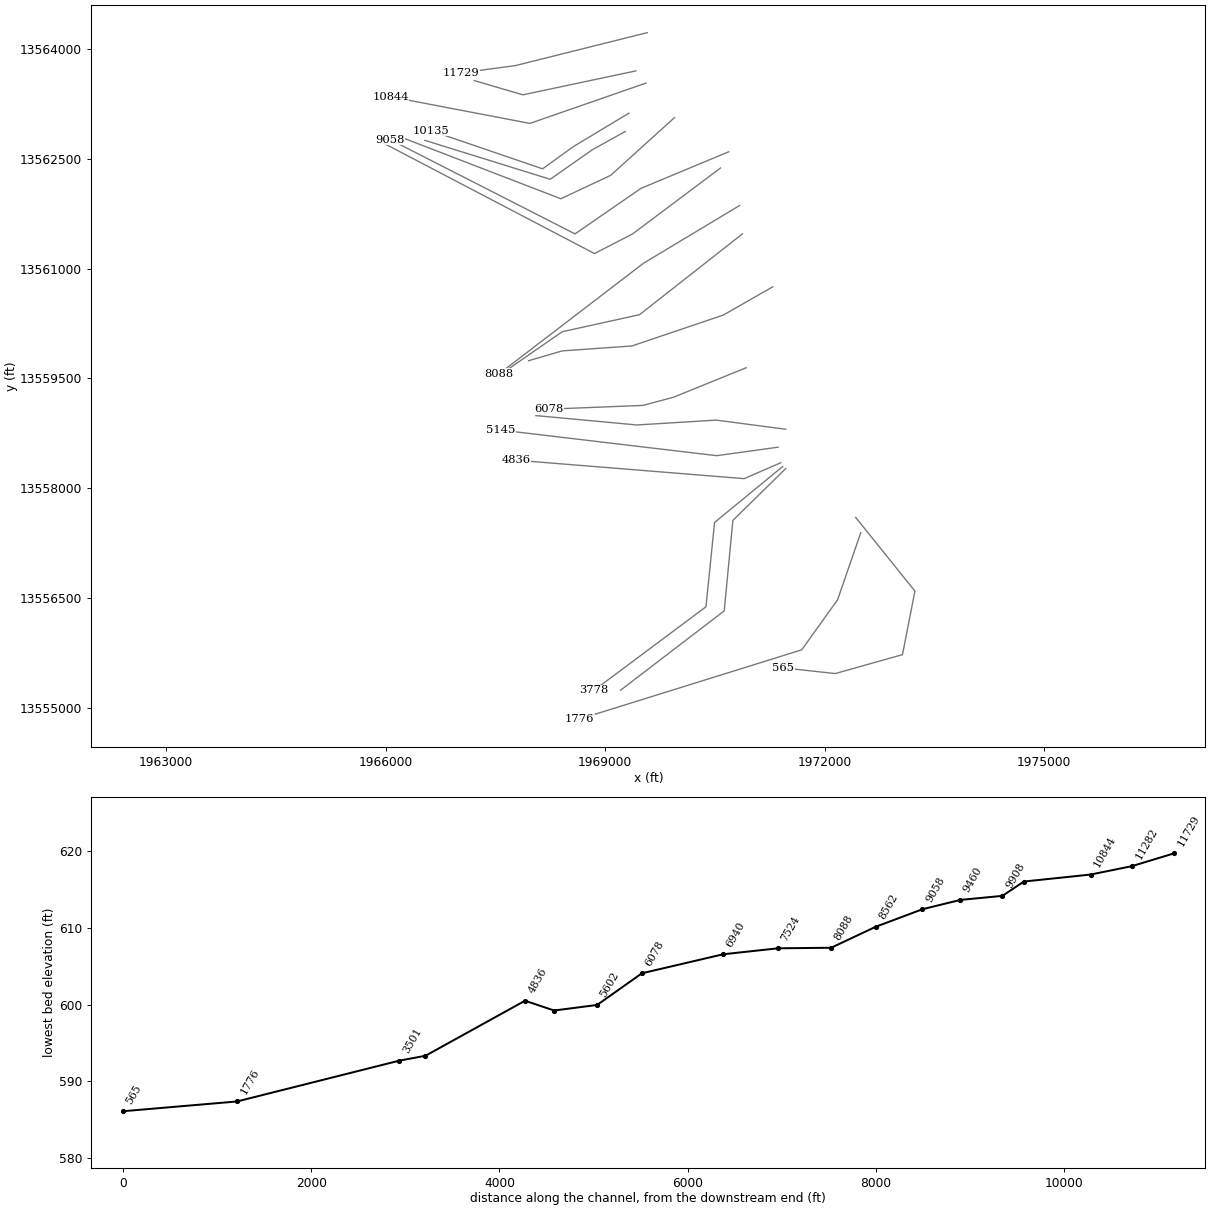
HEC-RAS study UNT 035 in BCW.prj: UNT 035 in BCW Base Level Engineering

--- UNT 035 in BCW.g01 (geometry) --- (continued)

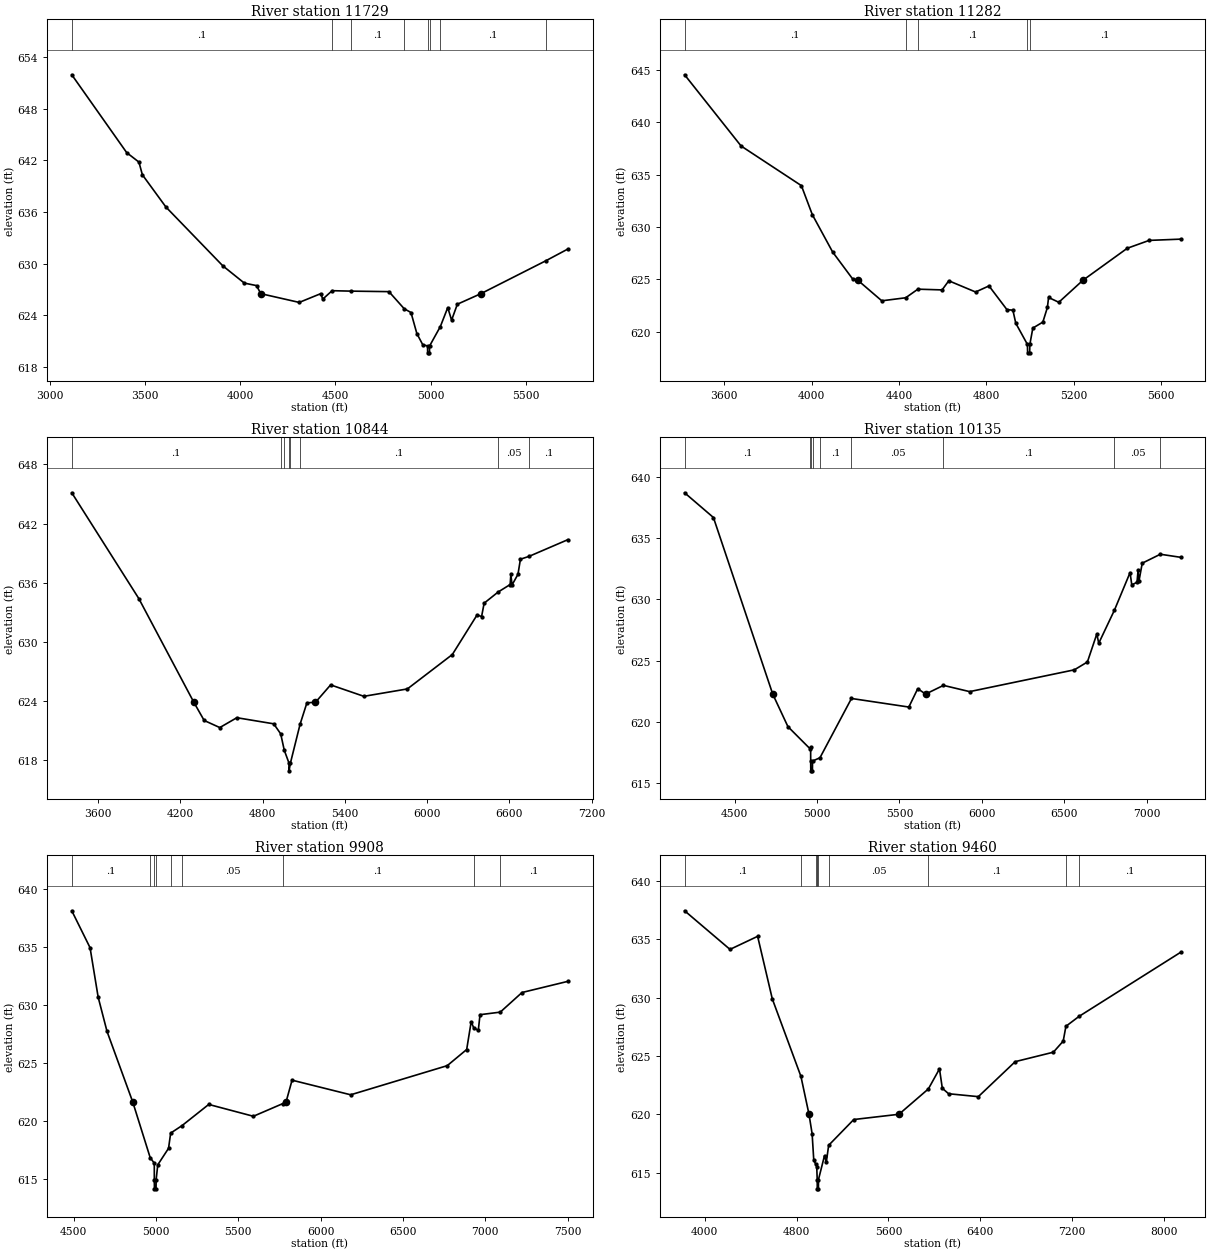
Type RM Length L Ch R = 1 ,11729   ,447,447,447
BEGIN DESCRIPTION:
UNT 035 in BCW 17.0
END DESCRIPTION:
XS GIS Cut Line= 3
      1969574.99       13564225.        1967775.       13563775.
      1967029.56     13563674.27
#Sta/Elev= 30
  3113.8  651.92  3402.4  642.89  3466.8  641.79  3484.9  640.32  3608.6  636.58
  3907.5  629.76  4020.9  627.75  4085.3  627.46 4107.03626.5266  4309.5  625.51
  4422.9  626.53  4433.2  625.89  4482.4  626.87  4580.7  626.82  4781.1  626.76
  4861.6  624.77    4897  624.34    4928  621.89  4958.9   620.6  4983.9  620.46
  4984.6  619.66  4994.1  619.66  4994.9  620.46  5051.4  622.71  5090.3  624.91
  5110.5  623.45  5140.7   625.3 5264.65626.5264  5605.8  630.34  5721.4   631.7
#Mann= 8 ,-1 , 0
  3113.8      .1       0  4482.4     .05       0  4580.7      .1       0
  4861.6     .12       0  4983.9     .07       0  4994.9     .12       0
  5051.4      .1       0  5605.8     .05       0
Bank Sta=4107.03,5264.65
XS Rating Curve= 0 ,0
Exp/Cntr=0.3,0.1

Type RM Length L Ch R = 1 ,11282   ,438,438,438
BEGIN DESCRIPTION:
UNT 035 in BCW 16.0
END DESCRIPTION:
XS GIS Cut Line= 3
      1969417.96     13563701.98        1967875.       13563375.
      1967209.91     13563569.96
#Sta/Elev= 30
  3418.4  644.51    3677  637.72    3953  633.94  4002.9  631.18  4096.1  627.61
  4188.1  625.03 4211.55624.9171    4321  622.96  4430.3  623.25  4486.2  624.07
    4597     624  4627.6  624.87  4750.3   623.8  4811.6  624.38  4893.4  622.13
  4921.1  622.06  4934.3  620.82  4987.6   618.8  4988.3     618  4997.8     618
  4998.6   618.8  5012.3  620.36  5058.1  620.93    5079  622.33  5084.3  623.28
  5131.1  622.82 5241.44624.9171  5444.5  627.97  5544.7  628.72  5688.7  628.84
#Mann= 5 ,-1 , 0
  3418.4      .1       0  4430.3     .05       0  4486.2      .1       0
  4987.6     .07       0  4998.6      .1       0
Bank Sta=4211.55,5241.44
XS Rating Curve= 0 ,0
Exp/Cntr=0.3,0.1

Type RM Length L Ch R = 1 ,10844   ,709,709,709
BEGIN DESCRIPTION:
UNT 035 in BCW 15.0
END DESCRIPTION:
XS GIS Cut Line= 3
      1969556.91     13563535.33      1967970.68     13562984.52
      1966065.41      13563348.7
#Sta/Elev= 30
  3407.4  645.12  3896.4  634.39 4297.93623.8645  4373.3  622.02  4487.2   621.3
  4611.7   622.3  4880.8  621.68  4931.7  620.66  4957.7     619  4991.8  617.71
  4992.5  616.91  5002.8  617.71  5073.1  621.64  5122.9  623.81 5185.48623.8644
  5295.9  625.63  5538.5  624.47  5855.9  625.22  6183.9  628.71    6365  632.74
  6397.3  632.56  6415.9  633.92  6517.9  635.05  6605.7  635.81  6610.8  636.83
  6619.5  635.77  6662.8  636.85  6680.6  638.38  6743.8  638.67  7026.3  640.36
#Mann= 8 ,-1 , 0
  3407.4      .1       0  4931.7     .07       0  4957.7     .12       0
  4991.8     .07       0  5002.8     .12       0  5073.1      .1       0
  6517.9     .05       0  6743.8      .1       0
Bank Sta=4297.93,5185.48
XS Rating Curve= 0 ,0
Exp/Cntr=0.3,0.1

Type RM Length L Ch R = 1 ,10135   ,227,227,227
BEGIN DESCRIPTION:
UNT 035 in BCW 14.0
END DESCRIPTION:
XS GIS Cut Line= 4
      1969325.04     13563125.02      1968563.81     13562667.26
      1968144.16     13562363.82      1966624.47     13562883.12
#Sta/Elev= 30
    4195  638.71  4370.1  636.69 4730.17622.2689  4822.5  619.61  4957.7  617.79
  4960.4  617.96  4960.7   616.8  4961.4     616  4971.2     616  4971.9   616.8
  5017.1  617.07  5208.3  621.91  5556.7  621.21  5610.8  622.71 5658.35622.2688
    5767  622.98    5926  622.47  6561.9  624.25    6641  624.89  6698.3  627.18
  6709.9  626.42  6805.1  629.12  6900.1  632.19  6910.6  631.19  6942.3   631.4
  6948.8  632.37  6954.1  631.49    6974  632.96    7084  633.69  7207.1  633.44
#Mann= 9 ,-1 , 0
    4195      .1       0  4957.7     .12       0  4960.7     .07       0
  4971.9     .12       0  5017.1      .1       0  5208.3     .05       0
    5767      .1       0  6805.1     .05       0    7084      .1       0
Bank Sta=4730.17,5658.35
XS Rating Curve= 0 ,0
Exp/Cntr=0.3,0.1

Type RM Length L Ch R = 1 ,9908    ,448,448,448
BEGIN DESCRIPTION:
UNT 035 in BCW 13.0
END DESCRIPTION:
XS GIS Cut Line= 4
      1969275.04     13562875.02        1968825.       13562625.
      1968248.41      13562220.9      1966535.87     13562752.93
#Sta/Elev= 30
  4489.1  638.09  4600.1  634.91  4649.3  630.65  4703.1   627.7 4859.46621.6163
  4965.4  616.82  4990.2  616.35  4990.3  614.94    4991  614.14  5000.8  614.14
  5001.5  614.94  5011.3  616.21  5076.7  617.63  5089.6  618.94    5159  619.59
  5320.8  621.41  5591.9  620.39  5770.4  621.48 5790.19 621.616  5826.8   623.5
  6182.8  622.24  6769.2  624.75  6887.2  626.14  6914.5  628.53  6929.3  628.03
  6957.7  627.78  6968.2  629.14  7091.1  629.36  7223.2  631.05  7501.3  632.01
#Mann= 9 ,-1 , 0
  4489.1      .1       0  4965.4     .12       0  4990.3     .07       0
  5001.5     .12       0  5089.6     .16       0    5159     .05       0
  5770.4      .1       0  6929.3     .05       0  7091.1      .1       0
Bank Sta=4859.46,5790.19
XS Rating Curve= 0 ,0
Exp/Cntr=0.3,0.1

Type RM Length L Ch R = 1 ,9460    ,402,402,402
BEGIN DESCRIPTION:
UNT 035 in BCW 12.0
END DESCRIPTION:
XS GIS Cut Line= 4
      1969945.76     13563063.09        1969075.       13562275.
      1968393.31       13561955.      1966160.89     13562815.43
#Sta/Elev= 30
  3824.7  637.44  4220.2  634.13  4460.8  635.25  4588.5  629.89  4837.8  623.25
 4908.17620.0004  4935.3  618.34  4949.5   616.1  4966.8  615.71  4975.5  615.52
  4979.7  614.41  4980.4  613.61  4990.2  613.61  4990.9  614.41  5043.3  616.46
  5058.9  615.89  5079.4  617.34  5298.1  619.55 5691.59619.9999  5947.6  622.17
  6044.6  623.89  6069.3  622.23  6123.9  621.76  6382.9  621.51  6704.2  624.51
  7036.4  625.32  7122.2  626.27  7145.7  627.54  7260.2  628.39  8144.7  633.88
#Mann= 10 ,-1 , 0
  3824.7      .1       0  4837.8     .12       0  4966.8     .16       0
  4975.5     .12       0  4979.7     .07       0  4990.9     .12       0
  5079.4     .05       0  5947.6      .1       0  7145.7     .05       0
  7260.2      .1       0
Bank Sta=4908.17,5691.59
XS Rating Curve= 0 ,0
Exp/Cntr=0.3,0.1

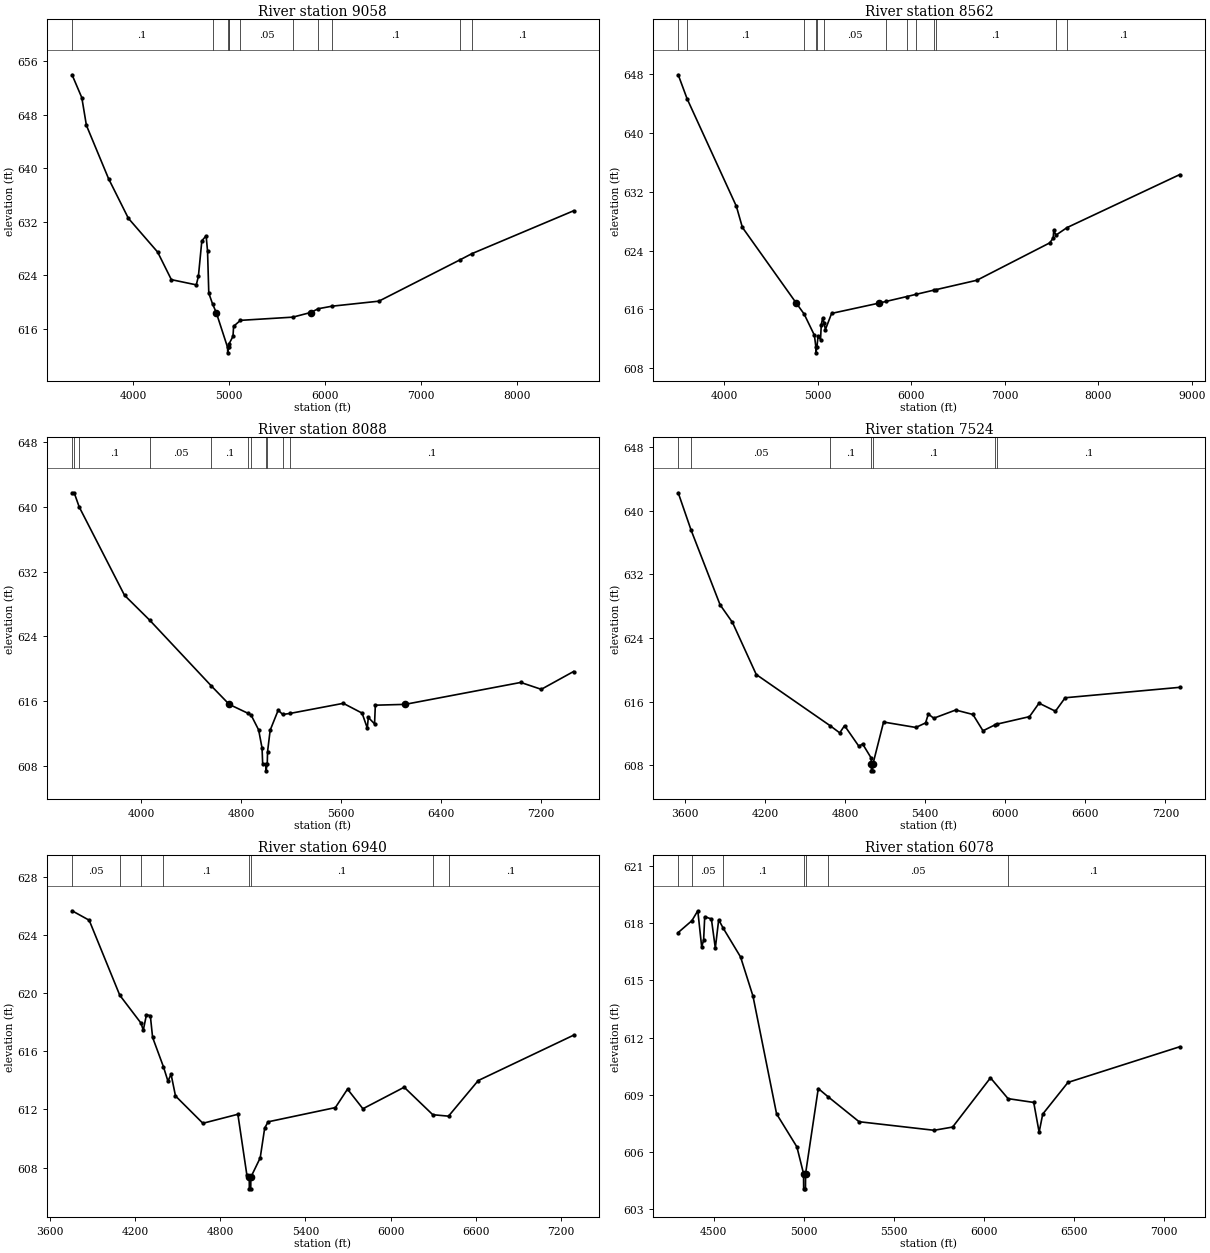
Type RM Length L Ch R = 1 ,9058    ,496,496,496
BEGIN DESCRIPTION:
UNT 035 in BCW 11.0
END DESCRIPTION:
XS GIS Cut Line= 4
      1970688.88     13562597.22      1969488.89     13562097.22
      1968587.52     13561474.66      1966061.95     13562763.33
#Sta/Elev= 30
  3361.6     654  3463.5  650.57  3511.2  646.44    3742  638.47  3948.9  632.53
  4254.1  627.48  4397.4  623.35  4657.4  622.57  4679.4  623.85  4715.2  629.16
  4759.9  629.91  4774.7  627.64  4787.8  621.33  4826.7  619.73 4865.64618.4313
  4984.1   613.2  4984.8   612.4  4995.3   613.2  5000.9  613.79  5040.4  614.88
  5046.5  616.37  5117.9  617.26  5664.3  617.74 5849.15618.4316  5929.6     619
  6073.5  619.38  6561.7  620.13  7412.8  626.35  7532.3  627.24  8592.4  633.65
#Mann= 11 ,-1 , 0
  3361.6      .1       0  4826.7     .07       0  4984.1     .07       0
  4995.3     .07       0  5000.9      .1       0  5117.9     .05       0
  5664.3      .1       0  5929.6     .05       0  6073.5      .1       0
  7412.8     .05       0  7532.3      .1       0
Bank Sta=4865.64,5849.15
XS Rating Curve= 0 ,0
Exp/Cntr=0.3,0.1

Type RM Length L Ch R = 1 ,8562    ,474,474,474
BEGIN DESCRIPTION:
UNT 035 in BCW 10.0
END DESCRIPTION:
XS GIS Cut Line= 4
      1970575.04     13562375.03        1969375.       13561475.
      1968853.77     13561206.02      1965948.66      13562726.2
#Sta/Elev= 30
  3507.2  647.84  3601.8   644.6  4129.1  630.01  4193.7  627.14 4770.26616.8643
  4854.1  615.39  4964.5   612.5  4979.7  610.92  4980.4  610.12    4991  610.92
  5004.1  612.39  5029.8  611.92  5037.7  613.94  5052.3  614.82  5066.4  614.22
    5082  613.28  5148.4  615.47 5654.68616.8643  5732.5   617.1  5951.3  617.75
  6050.1  618.05    6247  618.64  6264.8  618.69  6703.2  619.97  7480.9  625.03
  7519.3  625.69    7525   626.8  7547.7  626.08    7667  627.11  8872.6   634.3
#Mann= 13 ,-1 , 0
  3507.2     .16       0  3601.8      .1       0  4854.1     .12       0
  4979.7     .07       0    4991     .12       0  5066.4     .05       0
  5732.5      .1       0  5951.3     .05       0  6050.1      .1       0
    6247     .05       0  6264.8      .1       0  7547.7     .05       0
    7667      .1       0
Bank Sta=4770.26,5654.68
XS Rating Curve= 0 ,0
Exp/Cntr=0.3,0.1

Type RM Length L Ch R = 1 ,8088    ,564,564,564
BEGIN DESCRIPTION:
UNT 035 in BCW 9.0
END DESCRIPTION:
XS GIS Cut Line= 3
      1970834.68     13561861.72        1969525.       13561075.
      1967552.52     13559564.69
#Sta/Elev= 30
  3446.3  641.74  3463.9  641.72  3503.4  639.99  3865.9  629.08  4068.1  625.99
  4559.2   617.9 4703.61615.6002  4854.8  614.49  4878.3  614.29  4939.1  612.44
  4966.3   610.2  4971.2  608.29  4996.5  608.19  4997.2  607.39  5007.8  608.19
  5010.4  609.77  5031.2  612.41  5095.6  614.89  5131.4  614.35    5193  614.49
  5616.4  615.73  5766.6  614.52  5808.2  612.67  5816.4  613.99  5866.3  613.19
  5872.6   615.5  6109.6   615.6  7035.9  618.31    7200  617.46  7458.4  619.66
#Mann= 11 ,-1 , 0
  3446.3      .1       0  3463.9     .05       0  3503.4      .1       0
  4068.1     .05       0  4559.2      .1       0  4854.8     .12       0
  4878.3      .1       0  4996.5     .07       0  5007.8      .1       0
  5131.4     .05       0    5193      .1       0
Bank Sta=4703.61,6109.6
XS Rating Curve= 0 ,0
Exp/Cntr=0.3,0.1

Type RM Length L Ch R = 1 ,7524    ,584,584,584
BEGIN DESCRIPTION:
UNT 035 in BCW 8.0
END DESCRIPTION:
XS GIS Cut Line= 4
      1970875.01     13561475.01      1969469.35     13560370.87
      1968411.92     13560137.63      1967682.74     13559632.41
#Sta/Elev= 30
  3550.2  642.25  3647.1  637.54  3863.8  628.18  3956.9  625.96  4134.9  619.42
  4686.7  613.01  4760.4  612.09  4796.4     613  4903.2  610.42  4932.1  610.69
  4996.3  608.92    4997  608.12  4997.7  607.32  5007.7  607.32  5008.3  608.12
  5088.9  613.45  5330.5  612.77  5403.5  613.34    5424  614.45    5465  613.93
  5628.8  614.96  5758.2   614.4  5833.6  612.35  5924.9  613.11  5941.9   613.2
  6182.1  614.13  6253.5  615.82  6376.4  614.81  6449.3   616.5  7307.6  617.81
#Mann= 7 ,-1 , 0
  3550.2     .08       0  3647.1     .05       0  4686.7      .1       0
    4997     .07       0  5008.3      .1       0  5924.9     .12       0
  5941.9      .1       0
Bank Sta=4997,5008.3
XS Rating Curve= 0 ,0
Exp/Cntr=0.3,0.1

Type RM Length L Ch R = 1 ,6940    ,862,862,862
BEGIN DESCRIPTION:
UNT 035 in BCW 7.0
END DESCRIPTION:
XS GIS Cut Line= 5
      1971290.34     13560752.31      1970612.42     13560365.18
      1969365.55     13559943.44      1968412.01     13559876.01
       1967953.6      13559741.8
#Sta/Elev= 30
  3756.8  625.67  3877.4  625.02  4092.7  619.86  4242.2  617.94  4258.1  617.45
  4280.6  618.52  4307.9  618.45  4323.8  616.96  4400.4  614.93  4431.8  613.95
  4453.9  614.42    4485  612.93  4677.9  611.05  4924.1  611.67    4987  607.52
  5004.1  607.34  5004.8  606.54  5014.8  606.54  5015.4  607.34  5081.3  608.67
  5112.7  610.71  5136.5  611.15  5610.5  612.13    5696   613.4  5804.4  612.05
  6094.9  613.53  6296.2  611.64  6406.9  611.54  6616.2  613.99  7287.3  617.11
#Mann= 8 ,-1 , 0
  3756.8     .05       0  4092.7      .1       0  4242.2     .05       0
  4400.4      .1       0  5004.1     .07       0  5015.4      .1       0
  6296.2     .12       0  6406.9      .1       0
Bank Sta=5004.1,5015.4
XS Rating Curve= 0 ,0
Exp/Cntr=0.3,0.1

Type RM Length L Ch R = 1 ,6078    ,476,476,476
BEGIN DESCRIPTION:
UNT 035 in BCW 5.0
END DESCRIPTION:
XS GIS Cut Line= 4
      1970925.78     13559645.55      1969932.74     13559242.78
        1969514.     13559131.12       1968234.8     13559080.33
#Sta/Elev= 30
  4303.8  617.51  4379.7  618.13  4412.6  618.65  4434.1  616.76  4444.9   617.1
    4451  618.34  4488.1  618.22  4509.9  616.69  4528.6  618.18  4552.9  617.75
    4650  616.23  4718.9  614.18  4850.1     608  4962.9  606.27  4999.8  604.87
  5000.5  604.07  5010.5  604.07  5011.2  604.87  5081.6  609.33  5135.9   608.9
  5308.3  607.59    5725  607.14  5827.8  607.31    6038  609.89  6135.6   608.8
  6278.2   608.6  6308.2  607.04  6328.2  607.99  6468.3  609.65    7089  611.52
#Mann= 7 ,-1 , 0
  4303.8      .1       0  4379.7     .05       0  4552.9      .1       0
  4999.8     .07       0  5011.2      .1       0  5135.9     .05       0
  6135.6      .1       0
Bank Sta=4999.8,5011.2
XS Rating Curve= 0 ,0
Exp/Cntr=0.3,0.1

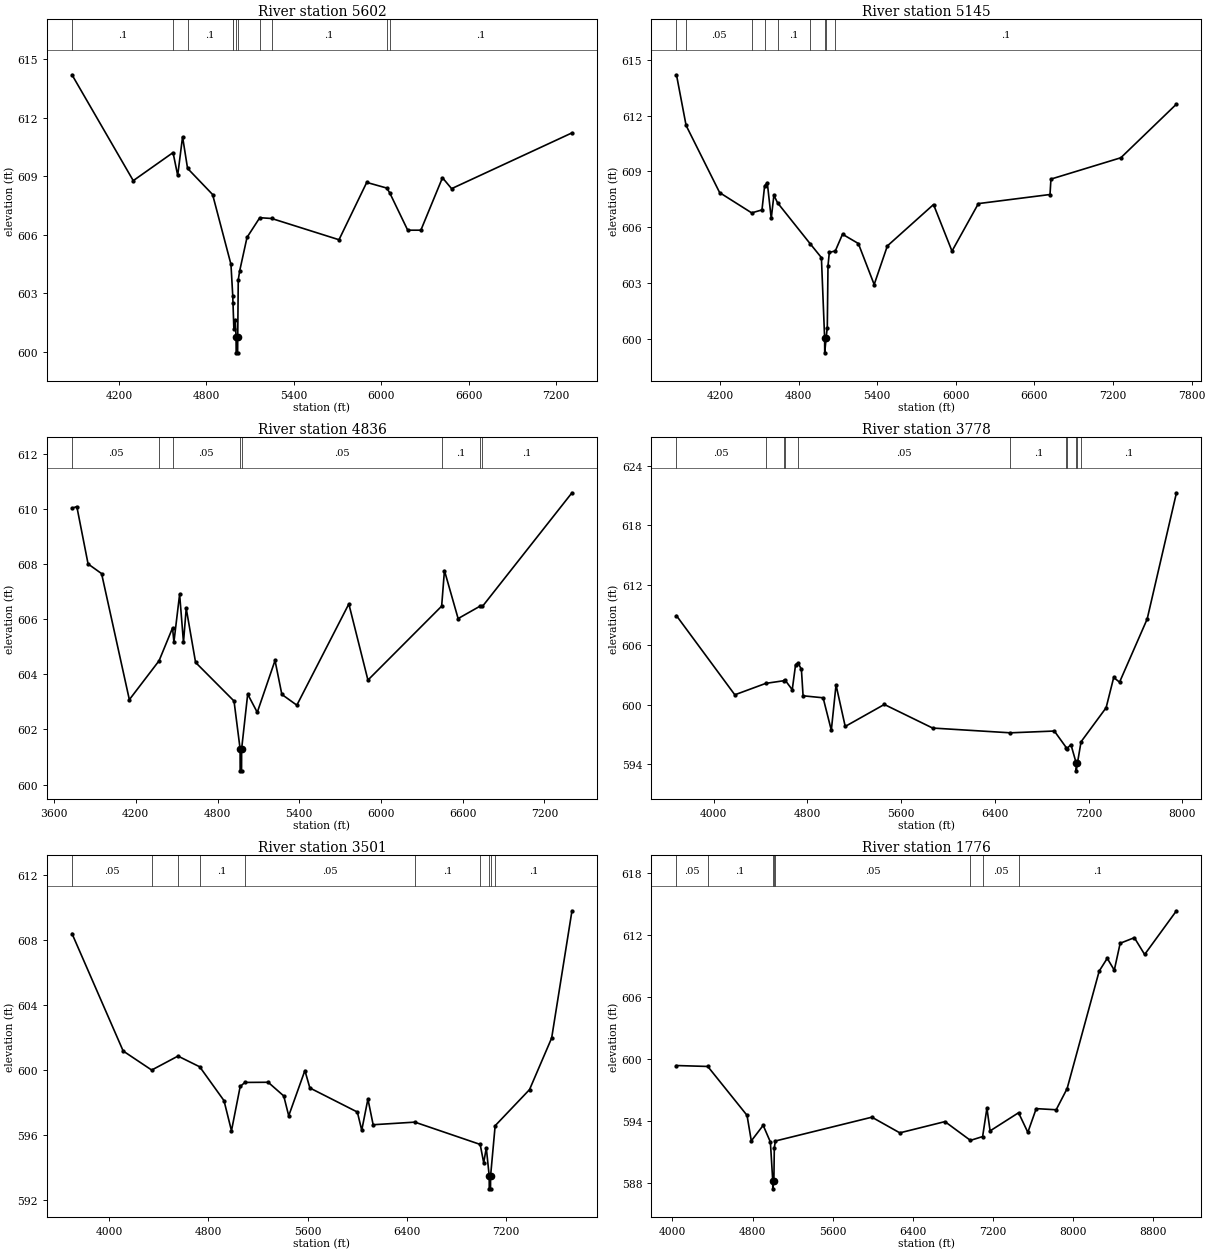
Type RM Length L Ch R = 1 ,5602    ,457,457,457
BEGIN DESCRIPTION:
Mapping XS 5ac6aa11
END DESCRIPTION:
XS GIS Cut Line= 4
      1971467.44     13558805.28      1970516.07     13558930.28
      1969432.94     13558863.83      1968052.57     13558991.79
#Sta/Elev= 30
  3877.6  614.21  4298.1  608.78  4571.1  610.22    4603  609.05  4636.5  611.03
  4670.7  609.41  4842.5  608.07  4968.5  604.49  4980.8  602.88  4982.5   602.5
  4988.5  601.17  4998.5  601.61  5003.6  600.75  5004.3  599.95  5014.3  599.95
    5015  600.75  5018.6  603.69  5028.6  604.16  5078.7  605.87  5166.2  606.88
  5247.7  606.84  5709.9  605.75  5900.2  608.69    6038   608.4  6057.6  608.16
  6181.4  606.24  6271.7  606.24  6419.9  608.93  6482.6  608.37  7308.6  611.23
#Mann= 11 ,-1 , 0
  3877.6      .1       0  4571.1     .08       0  4670.7      .1       0
  4980.8     .16       0  4982.5      .1       0  5003.6     .07       0
    5015      .1       0  5166.2     .05       0  5247.7      .1       0
    6038     .05       0  6057.6      .1       0
Bank Sta=5003.6,5015
XS Rating Curve= 0 ,0
Exp/Cntr=0.3,0.1

Type RM Length L Ch R = 1 ,5145    ,309,309,309
BEGIN DESCRIPTION:
UNT 035 in BCW 4.0
END DESCRIPTION:
XS GIS Cut Line= 3
       1971361.7     13558560.11      1970523.01     13558444.17
      1967573.33     13558793.88
#Sta/Elev= 30
  3867.1  614.21  3940.6  611.48  4196.9  607.86  4441.3  606.77  4519.9  606.93
  4540.2  608.23  4560.3   608.4  4590.6  606.47  4610.8  607.72    4639  607.31
  4886.4  605.12  4973.6  604.36  4998.1  600.03  4998.8  599.23  5009.5  600.03
  5018.5  600.59  5023.9  603.92    5034  604.64  5079.7  604.72  5134.7  605.62
  5255.5  605.12  5376.4  602.91  5477.1  604.99  5829.5  607.22  5970.5  604.71
  6171.9  607.27  6718.8  607.76  6725.8  608.59  7259.5  609.74  7684.1  612.63
#Mann= 9 ,-1 , 0
  3867.1      .1       0  3940.6     .05       0  4441.3      .1       0
  4540.2     .08       0    4639      .1       0  4886.4     .16       0
  4998.1     .07       0  5009.5     .16       0  5079.7      .1       0
Bank Sta=4998.1,5009.5
XS Rating Curve= 0 ,0
Exp/Cntr=0.3,0.1

Type RM Length L Ch R = 1 ,4836    ,1058,1058,1058
BEGIN DESCRIPTION:
UNT 035 in BCW 3.0
END DESCRIPTION:
XS GIS Cut Line= 3
      1971397.69     13558347.42       1970898.6     13558130.42
      1967781.69     13558382.42
#Sta/Elev= 30
  3731.4  610.02    3767  610.08  3849.6     608  3948.8  607.65  4152.7  603.08
  4370.8  604.49  4469.8  605.68  4479.9  605.17  4521.8   606.9  4550.1  605.16
  4570.2  606.39    4639  604.43  4921.3  603.03  4965.8   601.3  4966.4   600.5
  4976.5   600.5  4977.2   601.3  5021.6  603.28  5091.9  602.62  5222.3   604.5
  5272.5  603.27  5382.5  602.88  5764.3  606.55  5904.5  603.79  6445.8  606.47
  6466.3  607.76  6566.7  606.02  6727.8  606.47  6745.2  606.46  7402.7  610.58
#Mann= 8 ,-1 , 0
  3731.4     .05       0  4370.8      .1       0  4469.8     .05       0
  4965.8    .035       0  4977.2     .05       0  6445.8      .1       0
  6727.8     .05       0  6745.2      .1       0
Bank Sta=4965.8,4977.2
XS Rating Curve= 0 ,0
Exp/Cntr=0.3,0.1

Type RM Length L Ch R = 1 ,3778    ,277,277,277
BEGIN DESCRIPTION:
Mapping XS 088fac11
END DESCRIPTION:
XS GIS Cut Line= 4
      1971424.96     13558295.89      1970494.39     13557531.98
      1970376.33     13556379.21      1968850.11     13555239.95
#Sta/Elev= 30
    3682  608.93    4180  600.98  4444.7  602.13  4595.8  602.39  4606.3   602.5
  4670.1  601.49  4698.8  604.02  4719.9  604.19  4748.3  603.53  4762.6  600.88
  4933.6  600.68  5003.6  597.42  5043.8  601.97  5122.2   597.8  5455.9  600.01
  5868.1  597.64  6532.3  597.16    6907  597.34  7010.3  595.65  7015.1  595.58
  7048.7  595.98  7093.1  594.14  7093.7  593.34  7104.5  594.14    7135  596.26
  7348.9  599.68  7413.6  602.72  7463.6  602.25  7699.2  608.59  7949.3  621.28
#Mann= 11 ,-1 , 0
    3682     .05       0  4444.7      .1       0  4595.8     .05       0
  4606.3     .08       0  4719.9     .05       0  6532.3      .1       0
  7010.3     .07       0  7015.1     .12       0  7093.1    .035       0
  7104.5     .12       0    7135      .1       0
Bank Sta=7093.1,7104.5
XS Rating Curve= 0 ,0
Exp/Cntr=0.3,0.1

Type RM Length L Ch R = 1 ,3501    ,1725,1725,1725
BEGIN DESCRIPTION:
Mapping XS 86fb57ec
END DESCRIPTION:
XS GIS Cut Line= 4
      1971466.57     13558268.06      1970744.39     13557559.76
      1970626.33     13556323.65      1969210.33     13555239.94
#Sta/Elev= 30
  3697.9   608.4  4111.3  601.18  4341.5  600.01  4553.7  600.87  4729.1  600.21
  4925.2  598.13  4985.5  596.28  5055.8     599  5093.7  599.25  5281.7  599.26
  5407.4  598.42  5447.6   597.2  5578.2  599.98  5618.3  598.91  6001.7  597.43
  6037.1  596.31    6087  598.23  6129.2  596.65  6465.7  596.81  6993.2  595.44
  7021.8  594.31  7042.6  595.23    7066  593.51  7066.6  592.71  7076.7  592.71
  7077.4  593.51  7114.1  596.59  7391.7  598.81  7570.3  601.98  7734.3   609.8
#Mann= 10 ,-1 , 0
  3697.9     .05       0  4341.5      .1       0  4553.7     .05       0
  4729.1      .1       0  5093.7     .05       0  6465.7      .1       0
  6993.2     .07       0    7066     .07       0  7077.4     .07       0
  7114.1      .1       0
Bank Sta=7066,7077.4
XS Rating Curve= 0 ,0
Exp/Cntr=0.3,0.1

Type RM Length L Ch R = 1 ,1776    ,1211,1211,1211
BEGIN DESCRIPTION:
UNT 035 in BCW 2.0
END DESCRIPTION:
XS GIS Cut Line= 4
      1972491.77     13557391.07        1972175.       13556475.
      1971685.36     13555791.42      1968648.58     13554844.93
#Sta/Elev= 30
  4040.8  599.36  4353.3  599.27  4745.1  594.53  4787.9  592.05  4906.3  593.56
  4978.3  591.94  5001.7   588.2  5002.4   587.4  5013.1   588.2  5017.5   591.4
  5028.2  592.04  5991.4  594.35  6270.3  592.83  6720.7  593.92  6975.1   592.1
  7096.9  592.47  7139.7  595.23  7171.4  593.02  7455.5  594.78  7548.2  592.88
  7631.8  595.18    7831  595.07  7940.2  597.12  8260.4  608.52  8340.8  609.76
  8411.1  608.61  8469.9  611.22  8611.4  611.76  8714.2  610.13  9031.8  614.37
#Mann= 8 ,-1 , 0
  4040.8     .05       0  4353.3      .1       0  5001.7     .07       0
  5013.1      .1       0  5028.2     .05       0  6975.1      .1       0
  7096.9     .05       0  7455.5      .1       0
Bank Sta=5001.7,5013.1
XS Rating Curve= 0 ,0
Exp/Cntr=0.3,0.1

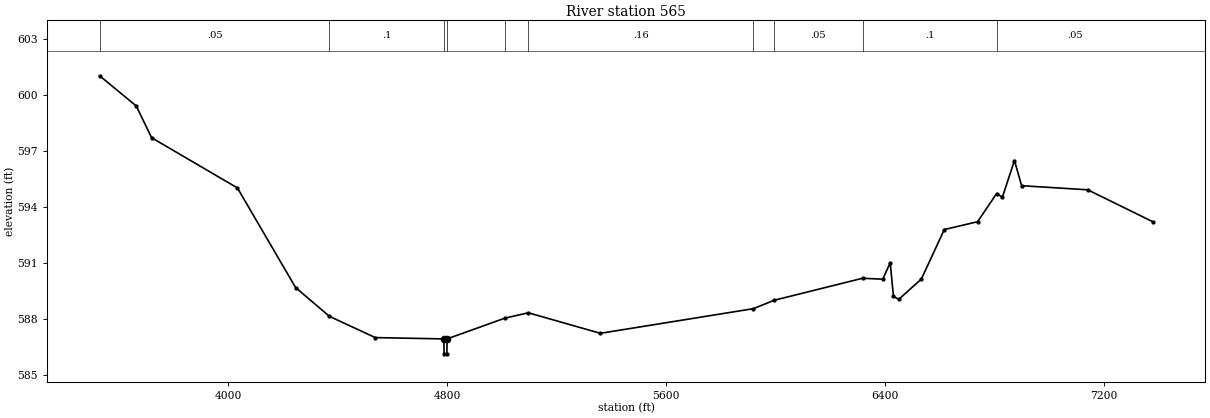
Type RM Length L Ch R = 1 ,565     ,0,0,0
BEGIN DESCRIPTION:
UNT 035 in BCW 1.0
END DESCRIPTION:
XS GIS Cut Line= 5
      1972422.91      13557600.5      1973231.92     13556593.58
      1973061.78     13555725.53        1972143.     13555466.93
      1971428.58     13555545.21
#Sta/Elev= 30
  3530.5  601.03  3664.5  599.41  3720.5  597.71  4034.1  595.02  4246.9  589.68
  4370.4  588.14  4538.1     587  4788.9  586.93  4789.6  586.13  4799.8  586.13
  4800.4  586.93  5011.2  588.04  5097.3  588.33  5360.8  587.23  5919.9  588.55
  5995.9     589  6319.1  590.18  6392.9  590.13  6420.2  591.01  6432.1  589.21
  6451.4  589.05  6534.2  590.14  6617.9  592.79  6739.7  593.21  6809.2  594.72
  6830.2  594.52  6874.3  596.49  6900.6  595.14  7142.1  594.92  7379.9  593.21
#Mann= 10 ,-1 , 0
  3530.5     .05       0  4370.4      .1       0  4788.9     .07       0
  4800.4      .1       0  5011.2     .12       0  5097.3     .16       0
  5919.9      .1       0  5995.9     .05       0  6319.1      .1       0
  6809.2     .05       0
Bank Sta=4788.9,4800.4
XS Rating Curve= 0 ,0
Exp/Cntr=0.3,0.1
LCMann Table=0

Chan Stop Cuts=-1
Use User Specified Reach Order=0
Composite Channel Slope=5