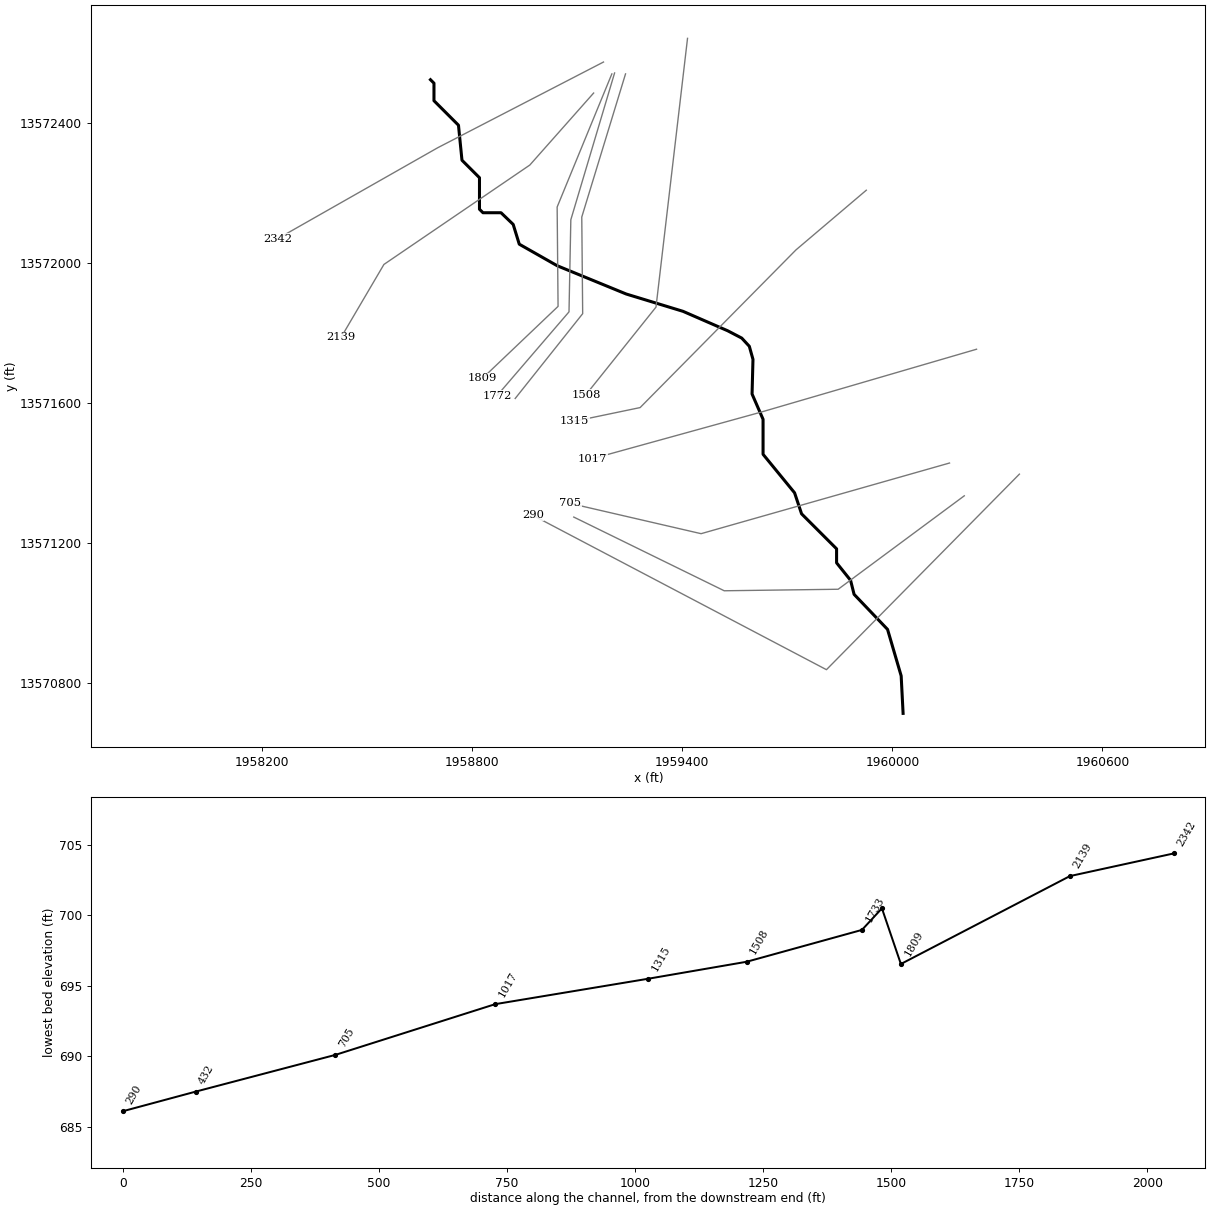
--- UNT 036 in BCW.prj (project) ---

Proj Title=UNT 036 in BCW Base Level Engineering
Current Plan=p01
Default Exp/Contr=0.3,0.1
English Units
Geom File=g01
Flow File=f01
Plan File=p01
BEGIN DESCRIPTION:
UNT 036 in BCW
END DESCRIPTION:

--- UNT 036 in BCW.p01 (plan) ---

Plan Title=Multiple Run
Short Identifier=Multiple
Geom File=g01
Flow File=f01
Subcritical Flow
K Sum by GR= 0
Std Step Tol= 0.01
Critical Tol= 0.01
Num of Std Step Trials= 20
Max Error Tol= 0.3
Flow Tol Ratio= 0.001
Split Flow NTrial= 30
Split Flow Tol= 0.02
Split Flow Ratio= 0.02
Log Output Level= 0
Friction Slope Method= 1
Unsteady Friction Slope Method= 2
Unsteady Bridges Friction Slope Method= 1
Parabolic Critical Depth
Global Vel Dist=  1 , 1 , 1
Global Log Level= 0
CheckData=True
Encroach Param= -1, 0, 0, 0
BEGIN DESCRIPTION:
Multiple Run
END DESCRIPTION:

--- UNT 036 in BCW.f01 (steady flow) ---

Flow Title=Multiple
Number of Profiles=7
Profile Names=10-year,25-year,50-year,1pct_min,100-year,1pct_plu,500-year
River Rch & RM= UNT 036 in BCW,Reach-1,2342
     551     776     963     592    1180    2355    1775
Boundary for River Rch & Prof#=UNT 036 in BCW,Reach-1,1
Up Type=0
Dn Type=3
Dn Slope=0.005
Boundary for River Rch & Prof#=UNT 036 in BCW,Reach-1,2
Up Type=0
Dn Type=3
Dn Slope=0.005
Boundary for River Rch & Prof#=UNT 036 in BCW,Reach-1,3
Up Type=0
Dn Type=3
Dn Slope=0.005
Boundary for River Rch & Prof#=UNT 036 in BCW,Reach-1,4
Up Type=0
Dn Type=3
Dn Slope=0.005
Boundary for River Rch & Prof#=UNT 036 in BCW,Reach-1,5
Up Type=0
Dn Type=3
Dn Slope=0.005
Boundary for River Rch & Prof#=UNT 036 in BCW,Reach-1,6
Up Type=0
Dn Type=3
Dn Slope=0.005
Boundary for River Rch & Prof#=UNT 036 in BCW,Reach-1,7
Up Type=0
Dn Type=3
Dn Slope=0.005

--- UNT 036 in BCW.g01 (geometry) ---

Geom Title=Existing Conditions

River Reach=UNT 036 in BCW,Reach-1
Reach XY= 30
      1958680.80     13572524.54      1958690.80     13572514.54
      1958690.80     13572464.54      1958760.80     13572394.54
      1958770.80     13572294.54      1958820.80     13572244.54
      1958820.80     13572154.54      1958830.80     13572144.54
      1958882.37     13572144.54      1958917.10     13572111.12
      1958934.46     13572054.70      1959042.96     13571993.07
      1959240.01     13571912.34      1959402.34     13571862.86
      1959529.94     13571807.30      1959569.87     13571786.47
      1959591.57     13571763.03      1959601.99     13571725.70
      1959599.39     13571626.75      1959630.80     13571554.54
      1959630.80     13571454.54      1959720.80     13571344.54
      1959740.80     13571284.54      1959840.80     13571184.54
      1959840.80     13571144.54      1959880.80     13571094.54
      1959890.80     13571054.54      1959986.37     13570954.42
      1960025.26     13570821.78      1960030.80     13570714.54

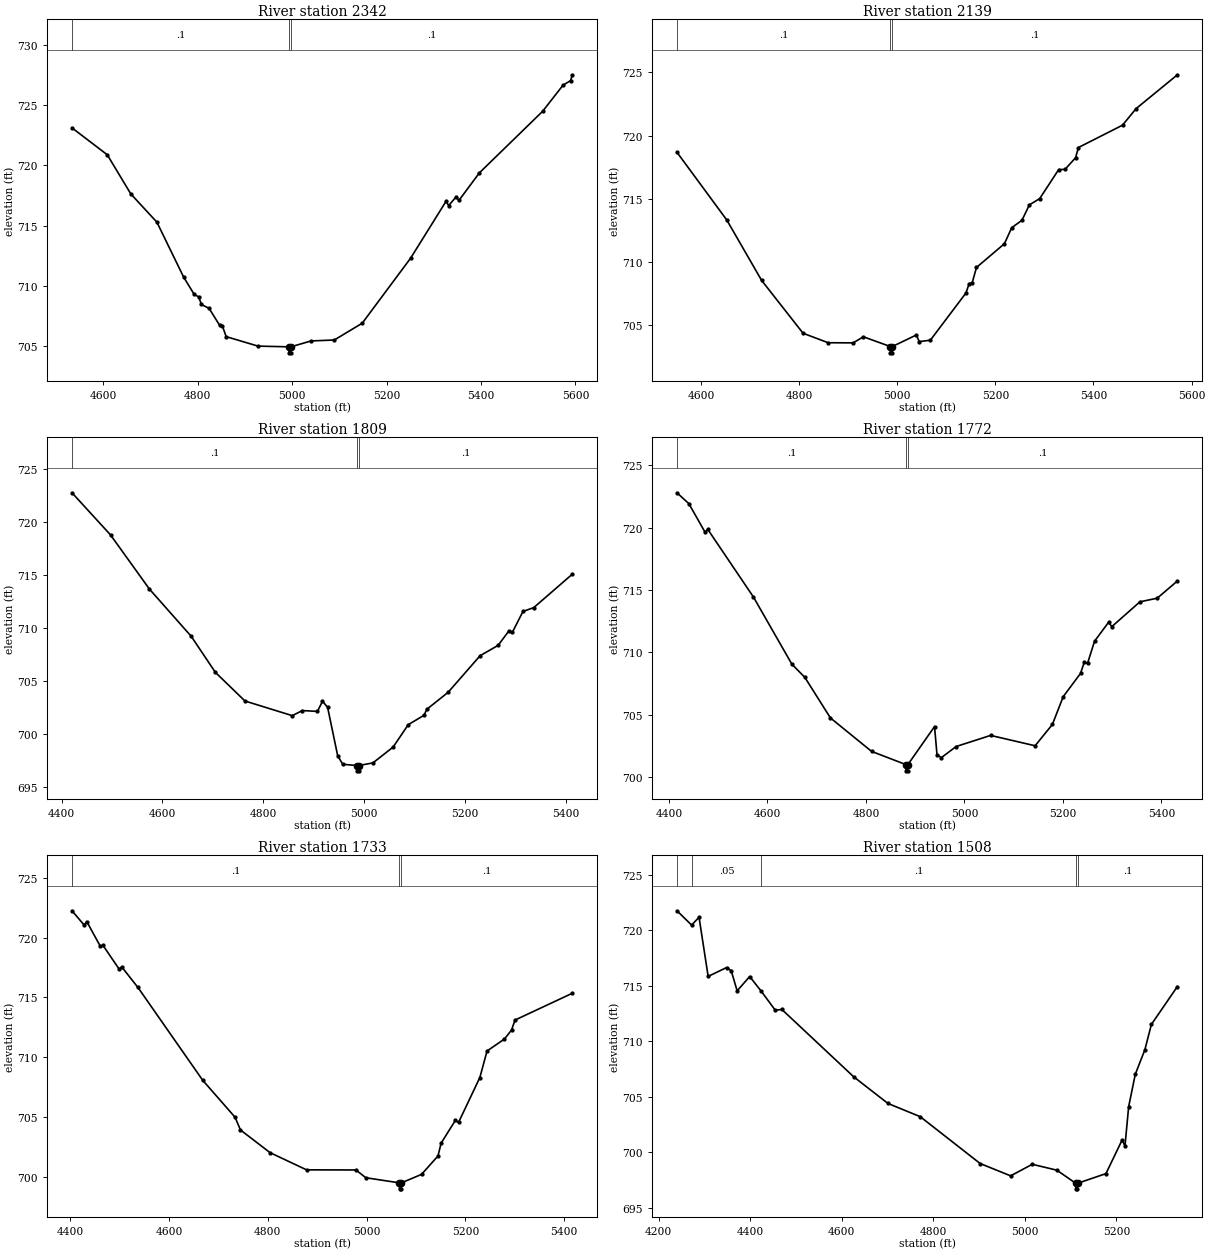
Type RM Length L Ch R = 1,2342,203,203,203
BEGIN DESCRIPTION:
UNT 036 in BCW 4.0
END DESCRIPTION:
XS GIS Cut Line= 3
      1959175.01     13572575.00      1958701.51     13572330.18
      1958243.35     13572069.86
#Sta/Elev= 30
  4533.7  723.13  4608.4  720.89  4658.3  717.63  4713.5  715.28  4770.1  710.71
  4792.6  709.26  4802.1  709.06  4807.7  708.43  4824.2  708.10  4846.4  706.69
  4852.0  706.67  4860.2  705.75  4927.7  704.96  4993.3  704.90  4993.5  704.40
  4997.0  704.40  4997.3  704.90  5040.0  705.39  5089.4  705.47  5148.5  706.87
  5250.9  712.28  5325.9  717.01  5331.6  716.66  5347.5  717.40  5353.3  717.09
  5396.5  719.38  5530.6  724.51  5573.9  726.69  5589.7  727.06  5593.7  727.55
#Mann=3,-1,0
  4533.7     0.1       0  4993.3    0.07       0  4997.3     0.1       0
Bank Sta=4993.3,4997.3
Exp/Cntr=0.3,0.1

Type RM Length L Ch R = 1,2139,330,330,330
BEGIN DESCRIPTION:
Mapping XS 65fb268e
END DESCRIPTION:
XS GIS Cut Line= 4
      1959146.83     13572486.44      1958964.53     13572280.70
      1958547.86     13571996.85      1958425.91     13571789.27
#Sta/Elev= 30
  4551.2  718.67  4652.7  713.31  4723.8  708.52  4808.2  704.34  4859.3  703.59
  4910.2  703.58  4931.1  704.06  4986.0  703.29  4986.3  702.79  4989.8  702.79
  4990.0  703.29  5038.9  704.20  5044.9  703.68  5067.5  703.79  5140.1  707.53
  5146.6  708.27  5152.7  708.32  5161.5  709.55  5218.4  711.43  5233.4  712.70
  5254.3  713.29  5269.3  714.51  5290.3  715.00  5329.0  717.30  5342.0  717.32
  5363.5  718.24  5369.3  719.05  5459.2  720.82  5486.5  722.12  5571.0  724.81
#Mann=3,-1,0
  4551.2     0.1       0  4986.0    0.07       0  4990.0     0.1       0
Bank Sta=4986,4990
Exp/Cntr=0.3,0.1

Type RM Length L Ch R = 1,1809,37,37,37
BEGIN DESCRIPTION:
Mapping XS 7b3d57b9
END DESCRIPTION:
XS GIS Cut Line= 4
      1959198.89     13572541.09      1959042.65     13572160.91
      1959045.26     13571877.06      1958829.55     13571671.74
#Sta/Elev= 30
  4420.6  722.75  4497.0  718.78  4574.3  713.67  4657.0  709.23  4705.0  705.83
  4763.7  703.13  4857.5  701.75  4877.5  702.23  4907.5  702.15  4917.5  703.11
  4927.6  702.54  4947.6  697.98  4957.6  697.17  4985.6  697.05  4985.8  696.55
  4989.3  696.55  4989.6  697.05  5017.6  697.30  5057.6  698.79  5087.6  700.90
  5119.1  701.79  5124.2  702.34  5166.7  703.95  5230.2  707.40  5265.8  708.37
  5286.9  709.71  5294.1  709.60  5315.2  711.57  5336.6  711.93  5413.3  715.09
#Mann=3,-1,0
  4420.6     0.1       0  4985.6    0.07       0  4989.6     0.1       0
Bank Sta=4985.6,4989.6
Exp/Cntr=0.3,0.1

Type RM Length L Ch R = 1,1772,39,39,39
BEGIN DESCRIPTION:
Mapping XS 8a93d8fb
END DESCRIPTION:
XS GIS Cut Line= 4
      1959206.72     13572543.74      1959081.72     13572124.45
      1959076.51     13571861.43      1958870.77     13571621.84
#Sta/Elev= 30
  4416.2  722.79  4440.3  721.92  4473.5  719.61  4478.7  719.86  4571.4  714.44
  4649.7  709.04  4675.8  708.00  4727.9  704.74  4811.4  702.06  4881.2  701.00
  4881.4  700.50  4884.9  700.50  4885.2  701.00  4939.3  704.05  4944.3  701.80
  4953.2  701.56  4983.2  702.45  5053.2  703.34  5143.6  702.51  5178.7  704.22
  5200.7  706.45  5235.8  708.31  5243.5  709.21  5250.0  709.11  5264.3  710.89
  5292.8  712.41  5299.4  712.06  5356.5  714.05  5391.6  714.34  5432.6  715.72
#Mann=3,-1,0
  4416.2     0.1       0  4881.2    0.07       0  4885.2     0.1       0
Bank Sta=4881.2,4885.2
Exp/Cntr=0.3,0.1

Type RM Length L Ch R = 1,1733,225,225,225
BEGIN DESCRIPTION:
Mapping XS a418d8db
END DESCRIPTION:
XS GIS Cut Line= 4
      1959237.96     13572541.11      1959112.97     13572132.27
      1959115.57     13571856.23      1958922.85     13571614.02
#Sta/Elev= 30
  4403.6  722.25  4428.3  721.05  4433.5  721.35  4461.0  719.27  4466.3  719.36
  4499.1  717.36  4504.3  717.55  4537.1  715.83  4668.2  708.06  4733.8  704.96
  4744.6  703.90  4804.6  702.00  4878.4  700.56  4978.4  700.55  4998.4  699.90
  5066.4  699.47  5066.7  698.97  5070.2  698.97  5070.4  699.47  5111.2  700.18
  5144.5  701.72  5150.9  702.80  5179.7  704.70  5186.1  704.53  5229.3  708.29
  5243.8  710.51  5279.0  711.51  5293.4  712.26  5300.4  713.10  5416.7  715.35
#Mann=3,-1,0
  4403.6     0.1       0  5066.4    0.07       0  5070.4     0.1       0
Bank Sta=5066.4,5070.4
Exp/Cntr=0.3,0.1

Type RM Length L Ch R = 1,1508,193,193,193
BEGIN DESCRIPTION:
UNT 036 in BCW 3.0
END DESCRIPTION:
XS GIS Cut Line= 3
      1959415.05     13572642.68      1959325.00     13571875.00
      1959125.00     13571625.00
#Sta/Elev= 30
  4240.1  721.75  4272.1  720.46  4288.3  721.17  4308.2  715.84  4348.5  716.64
  4358.6  716.35  4371.5  714.54  4398.9  715.83  4424.3  714.50  4454.7  712.80
  4469.3  712.86  4626.1  706.80  4700.9  704.40  4771.4  703.21  4902.3  698.99
  4968.9  697.88  5016.2  698.92  5069.9  698.39  5111.1  697.21  5111.3  696.71
  5114.8  696.71  5115.1  697.21  5177.1  698.08  5212.3  701.10  5218.7  700.58
  5226.7  704.11  5241.2  707.03  5262.0  709.22  5276.4  711.52  5333.2  714.93
#Mann=5,-1,0
  4240.1     0.1       0  4272.1    0.05       0  4424.3     0.1       0
  5111.1    0.07       0  5115.1     0.1       0
Bank Sta=5111.1,5115.1
Exp/Cntr=0.3,0.1

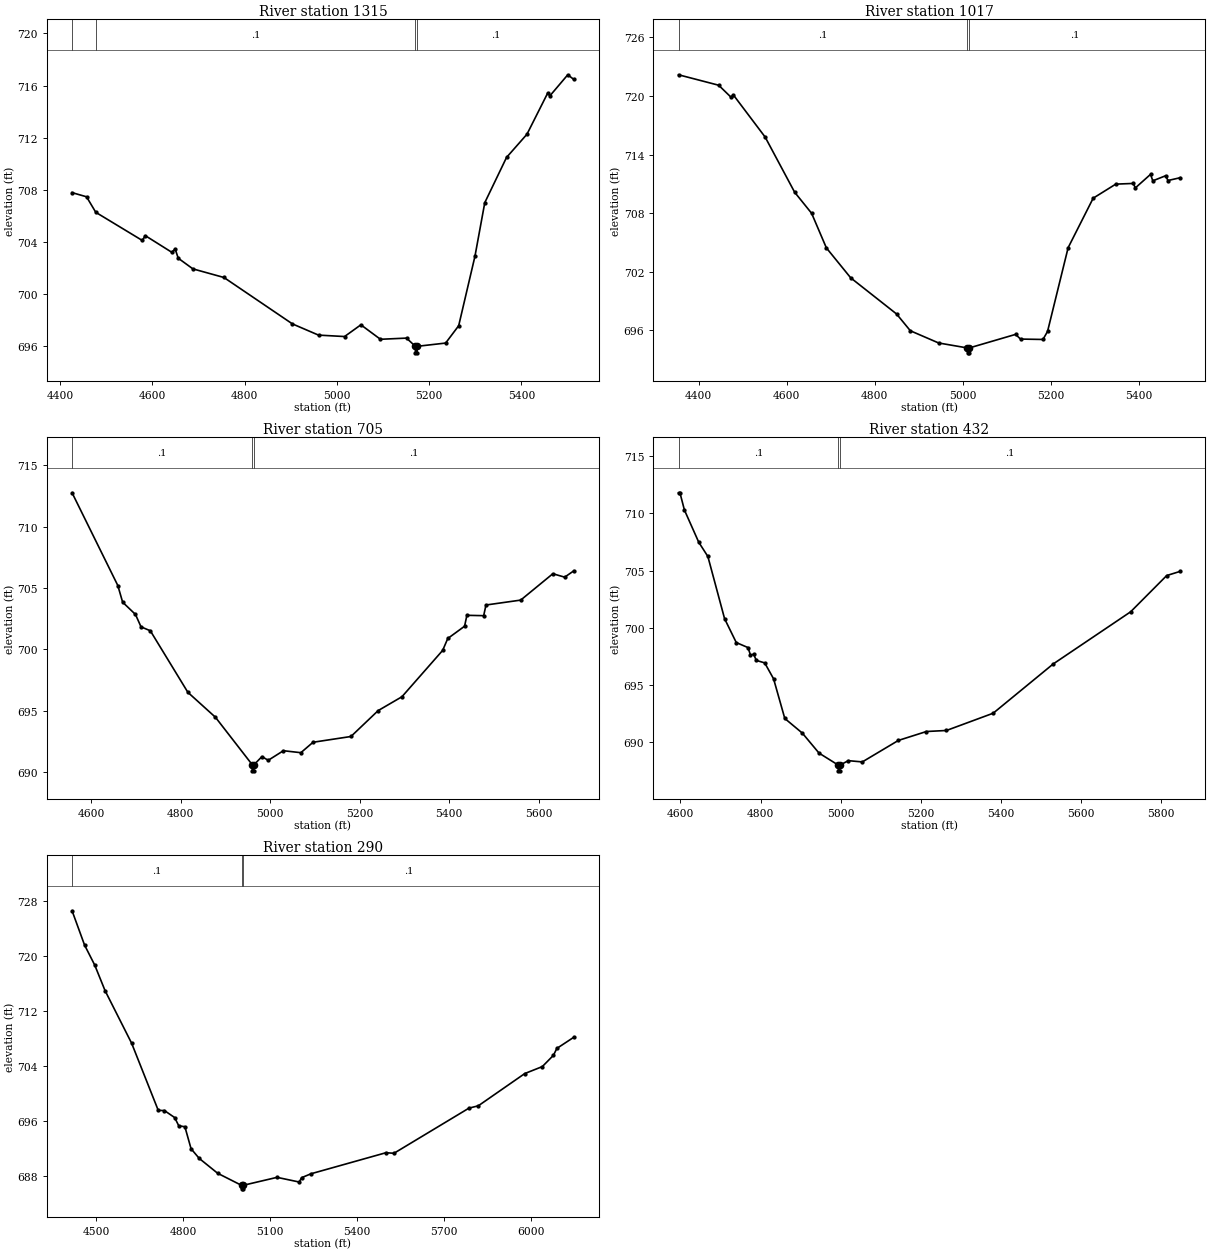
Type RM Length L Ch R = 1,1315,298,298,298
BEGIN DESCRIPTION:
Mapping XS fd3554f9
END DESCRIPTION:
XS GIS Cut Line= 4
      1959925.68     13572208.87      1959724.95     13572038.52
      1959279.63     13571588.00      1959092.10     13571548.93
#Sta/Elev= 30
  4425.6  707.79  4457.0  707.47  4477.0  706.28  4577.9  704.12  4584.4  704.49
  4641.6  703.22  4649.3  703.46  4655.8  702.76  4687.7  701.94  4755.0  701.28
  4903.5  697.72  4960.1  696.86  5016.6  696.75  5052.0  697.65  5094.4  696.54
  5151.0  696.63  5170.1  696.00  5170.4  695.50  5173.9  695.50  5174.1  696.00
  5235.8  696.25  5264.1  697.58  5299.4  702.91  5320.7  707.02  5367.9  710.49
  5412.2  712.27  5457.2  715.43  5462.3  715.23  5500.7  716.83  5513.9  716.47
#Mann=4,-1,0
  4425.6    0.08       0  4477.0     0.1       0  5170.1    0.07       0
  5174.1     0.1       0
Bank Sta=5170.1,5174.1
Exp/Cntr=0.3,0.1

Type RM Length L Ch R = 1,1017,312,312,312
BEGIN DESCRIPTION:
UNT 036 in BCW 2.0
END DESCRIPTION:
XS GIS Cut Line= 3
      1960240.57     13571754.66      1959625.00     13571575.00
      1959144.17     13571442.15
#Sta/Elev= 30
  4354.2  722.18  4445.4  721.11  4473.7  719.87  4478.9  720.11  4551.0  715.80
  4618.0  710.15  4656.6  707.99  4690.1  704.45  4745.4  701.38  4849.6  697.68
  4880.9  695.96  4945.2  694.71  5010.6  694.20  5010.9  693.70  5014.4  693.70
  5014.6  694.20  5120.0  695.59  5131.2  695.11  5182.2  695.07  5192.6  695.89
  5239.4  704.47  5296.3  709.54  5347.6  710.98  5387.1  711.05  5392.3  710.60
  5426.6  711.98  5431.8  711.32  5461.0  711.84  5466.2  711.35  5494.3  711.64
#Mann=3,-1,0
  4354.2     0.1       0  5010.6    0.07       0  5014.6     0.1       0
Bank Sta=5010.6,5014.6
Exp/Cntr=0.3,0.1

Type RM Length L Ch R = 1,705,273,273,273
BEGIN DESCRIPTION:
Mapping XS 8b88a0f0
END DESCRIPTION:
XS GIS Cut Line= 3
      1960163.36     13571429.63      1959453.76     13571227.82
      1959079.19     13571314.42
#Sta/Elev= 30
  4556.7  712.77  4659.0  705.21  4669.8  703.85  4698.5  702.85  4710.9  701.84
  4731.7  701.52  4815.7  696.50  4877.3  694.47  4959.6  690.60  4959.8  690.10
  4963.3  690.10  4963.6  690.60  4981.3  691.26  4995.4  690.96  5029.3  691.74
  5068.4  691.58  5095.6  692.43  5180.4  692.90  5241.2  695.01  5294.4  696.14
  5385.5  699.92  5396.9  700.89  5434.5  701.89  5439.7  702.78  5477.2  702.75
  5482.4  703.62  5560.0  704.02  5631.9  706.17  5658.4  705.89  5678.9  706.41
#Mann=3,-1,0
  4556.7     0.1       0  4959.6    0.07       0  4963.6     0.1       0
Bank Sta=4959.6,4963.6
Exp/Cntr=0.3,0.1

Type RM Length L Ch R = 1,432,142,142,142
BEGIN DESCRIPTION:
Mapping XS 1142bb11
END DESCRIPTION:
XS GIS Cut Line= 4
      1960205.58     13571336.00      1959845.35     13571069.08
      1959519.83     13571064.74      1959090.11     13571275.26
#Sta/Elev= 30
  4595.2  711.81  4598.7  711.81  4609.9  710.30  4645.7  707.48  4668.4  706.24
  4710.1  700.80  4739.3  698.71  4768.6  698.27  4774.8  697.61  4782.6  697.69
  4789.4  697.15  4810.3  696.93  4832.4  695.54  4860.4  692.07  4904.2  690.79
  4945.9  689.04  4994.0  687.99  4994.3  687.49  4997.8  687.49  4998.0  687.99
  5019.0  688.38  5053.9  688.27  5143.9  690.15  5213.9  690.93  5263.9  691.02
  5380.5  692.53  5530.4  696.84  5723.6  701.40  5813.6  704.57  5847.6  704.94
#Mann=3,-1,0
  4595.2     0.1       0  4994.0    0.07       0  4998.0     0.1       0
Bank Sta=4994,4998
Exp/Cntr=0.3,0.1

Type RM Length L Ch R = 1,290,0,0,0
BEGIN DESCRIPTION:
UNT 036 in BCW 1.0
END DESCRIPTION:
XS GIS Cut Line= 3
      1960362.97     13571397.90      1959811.84     13570839.36
      1958972.97     13571280.37
#Sta/Elev= 30
  4416.5  726.52  4459.6  721.54  4494.9  718.61  4530.3  714.92  4622.2  707.26
  4714.1  697.50  4735.3  697.48  4770.7  696.46  4784.9  695.26  4806.0  695.13
  4827.3  691.93  4855.6  690.52  4919.2  688.36  5002.0  686.60  5002.3  686.10
  5005.8  686.10  5006.0  686.60  5124.2  687.77  5200.7  687.09  5208.9  687.72
  5241.3  688.29  5500.2  691.35  5527.9  691.27  5786.7  697.83  5819.0  698.17
  5979.5  702.86  6040.0  703.87  6078.4  705.51  6090.1  706.51  6148.9  708.14
#Mann=3,-1,0
  4416.5     0.1       0  5002.0    0.07       0  5006.0     0.1       0
Bank Sta=5002,5006
Exp/Cntr=0.3,0.1

Chan Stop Cuts=-1