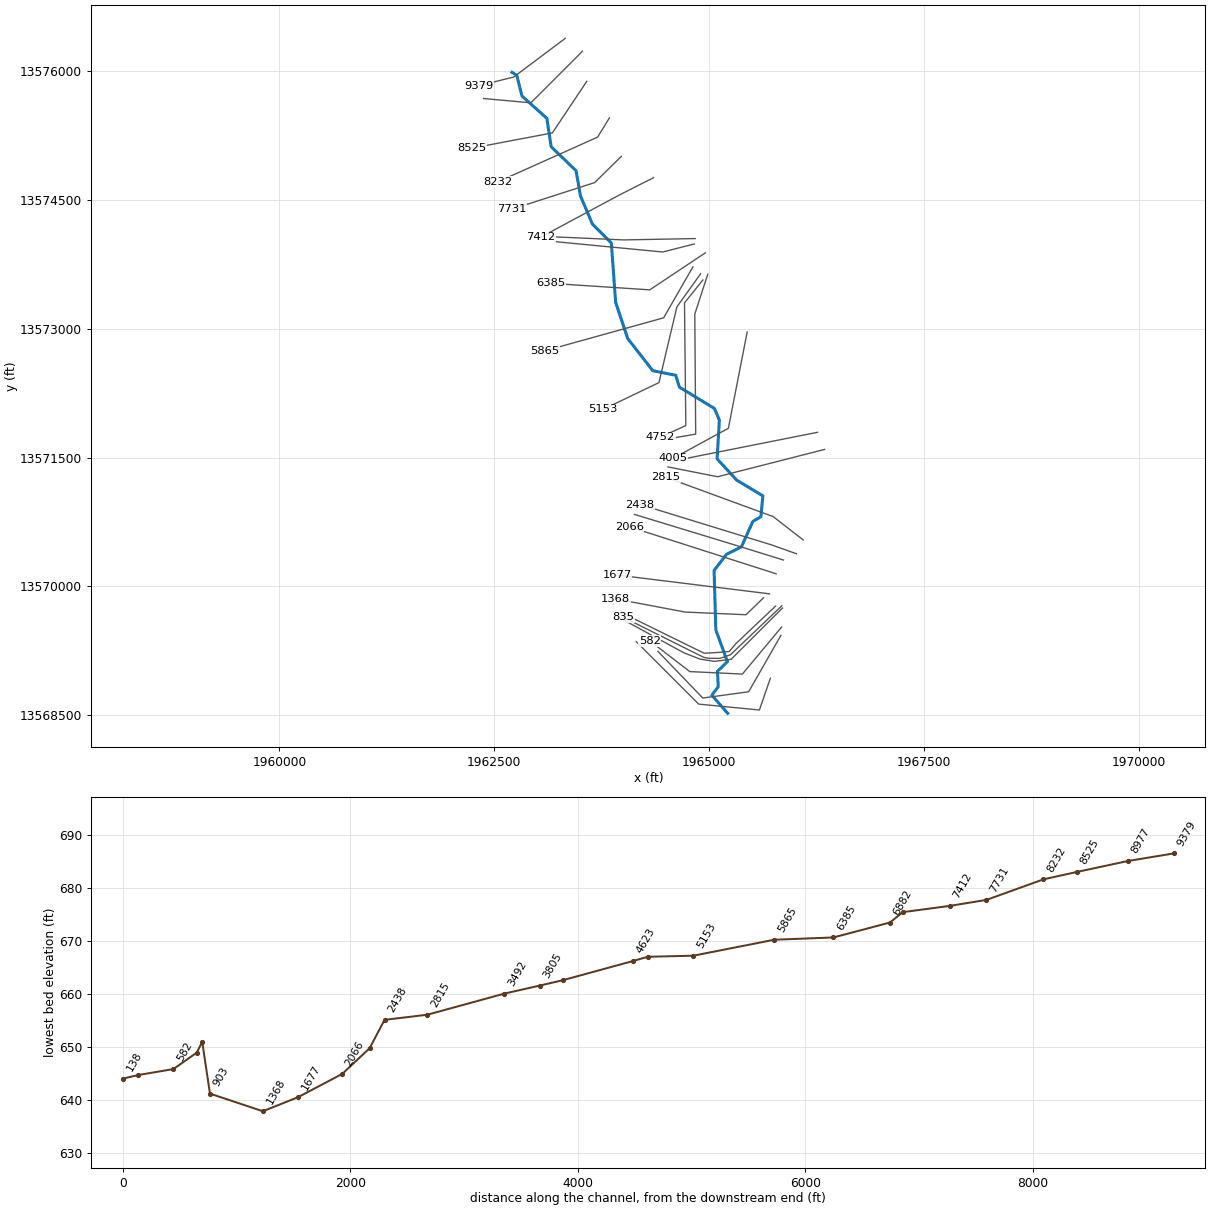
--- UNT 037 in BCW.prj (project) ---

Proj Title=UNT 037 in BCW Base Level Engineering
Current Plan=p01
Default Exp/Contr=0.3,0.1
English Units
Geom File=g01
Flow File=f01
Plan File=p01
BEGIN DESCRIPTION:
UNT 037 in BCW
END DESCRIPTION:

--- UNT 037 in BCW.p01 (plan) ---

Plan Title=Multiple Run
Short Identifier=Multiple
Geom File=g01
Flow File=f01
Subcritical Flow
K Sum by GR= 0
Std Step Tol= 0.01
Critical Tol= 0.01
Num of Std Step Trials= 20
Max Error Tol= 0.3
Flow Tol Ratio= 0.001
Split Flow NTrial= 30
Split Flow Tol= 0.02
Split Flow Ratio= 0.02
Log Output Level= 0
Friction Slope Method= 1
Unsteady Friction Slope Method= 2
Unsteady Bridges Friction Slope Method= 1
Parabolic Critical Depth
Global Vel Dist=  1 , 1 , 1
Global Log Level= 0
CheckData=True
Encroach Param= -1, 0, 0, 0
BEGIN DESCRIPTION:
Multiple Run
END DESCRIPTION:

--- UNT 037 in BCW.f01 (steady flow) ---

Flow Title=Multiple
Number of Profiles=7
Profile Names=10-year,25-year,50-year,1pct_min,100-year,1pct_plu,500-year
River Rch & RM= UNT 037 in BCW,Reach-1,9379
     693     983    1227     756    1509    3010    2285
River Rch & RM= UNT 037 in BCW,Reach-1,8977
     982    1414    1782    1107    2210    4409    3404
River Rch & RM= UNT 037 in BCW,Reach-1,2815
    1212    1764    2237    1398    2790    5566    4349
Boundary for River Rch & Prof#=UNT 037 in BCW,Reach-1,1
Up Type=0
Dn Type=3
Dn Slope=0.005
Boundary for River Rch & Prof#=UNT 037 in BCW,Reach-1,2
Up Type=0
Dn Type=3
Dn Slope=0.005
Boundary for River Rch & Prof#=UNT 037 in BCW,Reach-1,3
Up Type=0
Dn Type=3
Dn Slope=0.005
Boundary for River Rch & Prof#=UNT 037 in BCW,Reach-1,4
Up Type=0
Dn Type=3
Dn Slope=0.005
Boundary for River Rch & Prof#=UNT 037 in BCW,Reach-1,5
Up Type=0
Dn Type=3
Dn Slope=0.005
Boundary for River Rch & Prof#=UNT 037 in BCW,Reach-1,6
Up Type=0
Dn Type=3
Dn Slope=0.005
Boundary for River Rch & Prof#=UNT 037 in BCW,Reach-1,7
Up Type=0
Dn Type=3
Dn Slope=0.005

--- UNT 037 in BCW.g01 (geometry) ---

Geom Title=Existing Conditions
Program Version=5.05

River Reach=UNT 037 in BCW  ,Reach-1
Reach XY= 30
       1962705.8     13575979.54       1962760.8     13575944.54
       1962820.8     13575704.54       1963110.8     13575444.54
       1963160.8     13575114.54       1963450.8     13574834.54
       1963500.8     13574544.54       1963640.8     13574214.54
       1963860.8     13573994.54       1963910.8     13573304.54
       1964050.8     13572884.54      1964342.84     13572509.62
       1964610.2      13572455.8      1964651.87     13572318.65
      1965059.85     13572070.38      1965117.14      13571934.1
       1965090.8     13571484.54      1965318.84     13571236.49
      1965623.22     13571053.89      1965599.78      13570811.7
      1965506.03     13570755.71      1965373.52     13570461.09
       1965200.8     13570374.54       1965055.6     13570186.57
      1965076.21      13569494.3       1965210.8     13569124.54
      1965094.66     13569013.61      1965104.43     13568834.57
      1965029.56     13568735.83       1965214.2     13568524.23

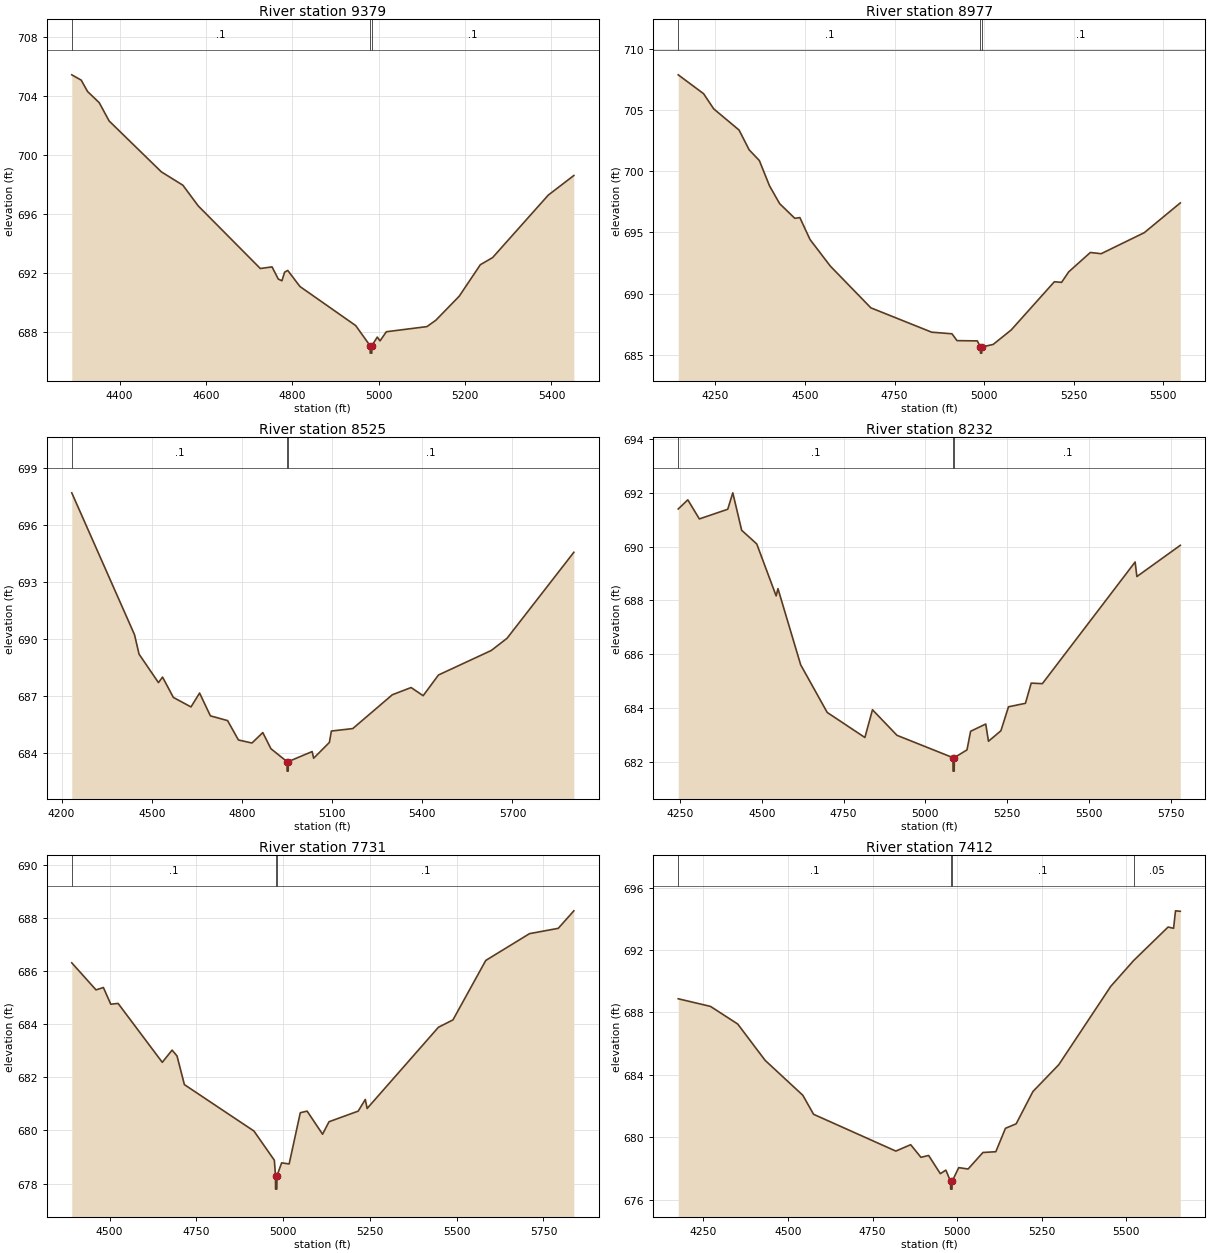
Type RM Length L Ch R = 1 ,9379    ,402,402,402
BEGIN DESCRIPTION:
UNT 037 in BCW 18.0
END DESCRIPTION:
XS GIS Cut Line= 3
      1963325.02     13576375.02        1962725.       13575925.
      1962325.04     13575825.01
#Sta/Elev= 30
  4289.5  705.43  4311.4  705.07    4326   704.3  4353.1  703.54    4376   702.3
  4496.8  698.85  4546.8  697.94  4582.2  696.54    4726  692.29  4753.1   692.4
  4767.7  691.57    4776  691.46  4782.2  692.04  4789.5  692.16  4817.7  691.07
  4946.8  688.42  4980.2  687.05  4980.5  686.55    4984  686.55  4984.2  687.05
  4996.8  687.64  5003.1  687.38  5017.7     688  5111.7  688.35  5132.3  688.78
  5186.4  690.41  5235.4  692.55  5263.7  693.03  5392.6  697.27  5451.8   698.6
#Mann= 3 ,-1 , 0
  4289.5      .1       0  4980.2     .07       0  4984.2      .1       0
Bank Sta=4980.2,4984.2
XS Rating Curve= 0 ,0
Exp/Cntr=0.3,0.1

Type RM Length L Ch R = 1 ,8977    ,452,452,452
BEGIN DESCRIPTION:
UNT 037 in BCW 17.0
END DESCRIPTION:
XS GIS Cut Line= 3
      1963525.01     13576225.01        1962925.       13575625.
      1962375.02       13575675.
#Sta/Elev= 30
  4146.3  707.86    4217  706.32  4245.3  705.08    4316  703.35  4344.3  701.73
  4372.6  700.86  4400.9   698.8  4429.2  697.34  4471.6  696.14  4485.7   696.2
    4514  694.41  4570.6  692.24  4683.7  688.83  4853.4  686.84    4910  686.71
  4924.1  686.15  4980.7  686.13  4989.3  685.63  4989.6  685.13  4993.1  685.13
  4993.3  685.63    5025  685.84  5075.2  687.02  5195.7  690.96  5215.8  690.91
  5235.8  691.77  5296.1  693.35  5326.2  693.25  5446.7  694.97  5547.1   697.4
#Mann= 3 ,-1 , 0
  4146.3      .1       0  4989.3     .07       0  4993.3      .1       0
Bank Sta=4989.3,4993.3
XS Rating Curve= 0 ,0
Exp/Cntr=0.3,0.1

Type RM Length L Ch R = 1 ,8525    ,293,293,293
BEGIN DESCRIPTION:
UNT 037 in BCW 16.0
END DESCRIPTION:
XS GIS Cut Line= 3
        1963575.       13575875.        1963175.       13575275.
      1962242.49     13575098.41
#Sta/Elev= 30
  4233.9   697.7  4442.7  690.23  4457.7  689.21  4522.3  687.71  4535.9     688
  4571.9  686.93  4630.5  686.43  4659.1  687.16  4695.1  685.96  4752.2  685.71
  4788.3  684.69  4833.3  684.53  4869.4  685.08  4896.4  684.23    4950  683.55
  4950.3  683.05  4953.8  683.05    4954  683.55  5033.5  684.08  5038.6  683.73
  5090.9  684.56  5097.5  685.16  5168.7  685.29  5300.2  687.07  5362.7  687.45
  5402.8  687.02  5453.7  688.11  5629.3   689.4  5681.7  690.04  5904.1  694.57
#Mann= 3 ,-1 , 0
  4233.9      .1       0    4950     .07       0    4954      .1       0
Bank Sta=4950,4954
XS Rating Curve= 0 ,0
Exp/Cntr=0.3,0.1

Type RM Length L Ch R = 1 ,8232    ,501,501,501
BEGIN DESCRIPTION:
UNT 037 in BCW 15.0
END DESCRIPTION:
XS GIS Cut Line= 3
      1963838.82     13575449.96      1963700.81     13575226.02
      1962539.67     13574705.32
#Sta/Elev= 30
    4244   691.4  4273.3  691.74  4308.6  691.03  4395.4  691.39  4410.9     692
    4438  690.61  4484.2   690.1  4543.5  688.17    4549  688.44  4618.5  685.61
  4699.7  683.84  4814.9  682.91  4838.1  683.94  4913.1  682.99  5084.3  682.16
  5084.6  681.66  5088.1  681.66  5088.3  682.16  5127.2  682.45  5138.2  683.14
  5184.5  683.41  5192.9  682.77  5230.9  683.16  5254.1  684.05  5305.9  684.18
  5323.6  684.93  5357.7  684.91  5641.4  689.43  5646.8  688.89  5779.6  690.05
#Mann= 3 ,-1 , 0
    4244      .1       0  5084.3     .07       0  5088.3      .1       0
Bank Sta=5084.3,5088.3
XS Rating Curve= 0 ,0
Exp/Cntr=0.3,0.1

Type RM Length L Ch R = 1 ,7731    ,319,319,319
BEGIN DESCRIPTION:
UNT 037 in BCW 14.0
END DESCRIPTION:
XS GIS Cut Line= 3
      1963976.83     13575002.03      1963666.96     13574697.37
      1962703.42     13574387.48
#Sta/Elev= 30
  4390.9  686.32  4460.8   685.3    4482  685.39  4503.3  684.76  4524.4  684.79
  4651.7  682.57    4680  683.03  4694.2  682.81  4715.4  681.73  4915.8  679.98
  4974.6  678.88    4978  678.29  4978.2  677.79  4981.8  677.79  4982.1  678.29
  4995.6  678.78  5017.3  678.74  5049.4  680.67  5069.1  680.73  5113.6  679.86
  5132.1  680.33  5216.2  680.73  5236.7  681.17    5242  680.83  5447.3  683.89
  5489.3  684.17  5583.8  686.41  5709.9  687.42  5792.7  687.62  5837.6  688.28
#Mann= 3 ,-1 , 0
  4390.9      .1       0    4978     .07       0  4982.1      .1       0
Bank Sta=4978,4982.1
XS Rating Curve= 0 ,0
Exp/Cntr=0.3,0.1

Type RM Length L Ch R = 1 ,7412    ,417,417,417
BEGIN DESCRIPTION:
UNT 037 in BCW 13.0
END DESCRIPTION:
XS GIS Cut Line= 3
      1964351.84     13574754.66      1963956.02     13574554.14
      1963039.67     13574062.12
#Sta/Elev= 30
  4175.8  688.88  4271.1  688.39  4351.6  687.26  4432.6  684.93    4544  682.69
  4575.8  681.47  4818.9  679.11  4862.7  679.52  4893.1  678.71  4915.8  678.83
  4950.4  677.66  4966.7  677.89  4980.6  677.17  4980.9  676.67  4984.9  676.67
  4985.2  677.17  5004.8  678.05  5032.4  677.96  5076.3  679.02  5114.4  679.07
  5142.8  680.57  5174.5  680.86    5224  682.93  5300.4  684.65  5453.8  689.67
  5521.6  691.33  5623.5  693.48  5639.7   693.4  5645.4  694.52  5659.6  694.49
#Mann= 4 ,-1 , 0
  4175.8      .1       0  4980.6     .07       0  4985.2      .1       0
  5521.6     .05       0
Bank Sta=4980.6,4985.2
XS Rating Curve= 0 ,0
Exp/Cntr=0.3,0.1

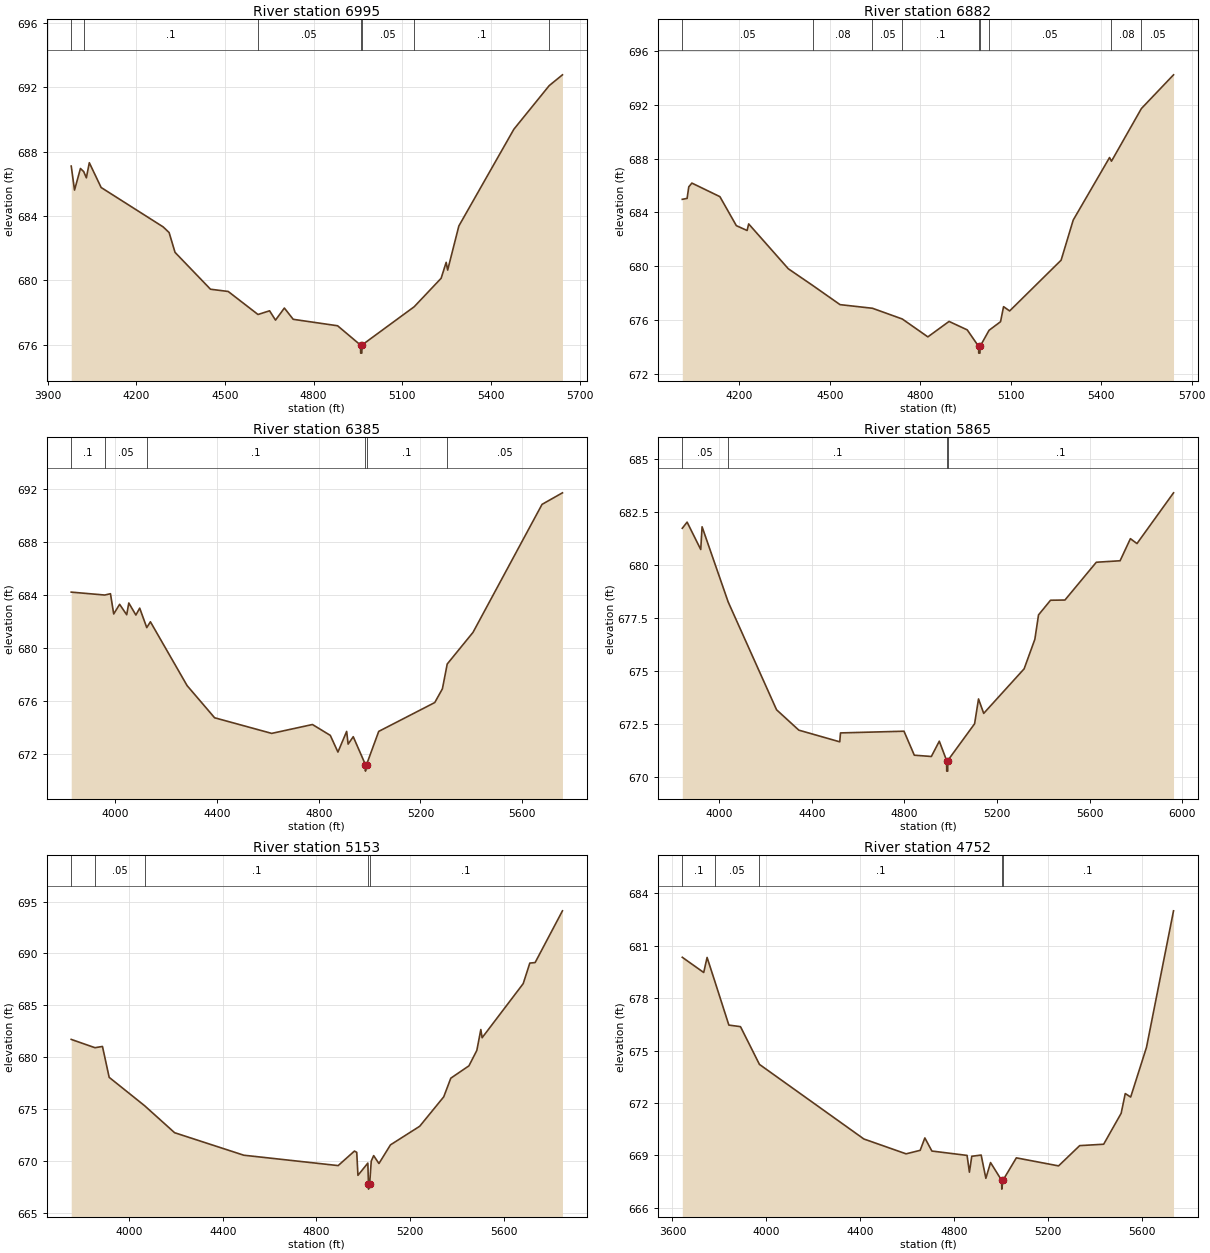
Type RM Length L Ch R = 1 ,6995    ,113,113,113
BEGIN DESCRIPTION:
UNT 037 in BCW 12.0
END DESCRIPTION:
XS GIS Cut Line= 3
       1964836.2     13574046.33       1964005.5      13574030.7
      1963174.75     13574067.16
#Sta/Elev= 30
  3979.8   687.1    3991  685.61    4011  686.95    4022  686.76    4031  686.37
    4041  687.31    4081  685.77  4291.1  683.32  4311.1  682.97  4331.1  681.74
  4451.1  679.45  4511.1  679.31  4611.9  677.88  4651.1  678.11  4671.1  677.53
  4701.1  678.28  4731.1  677.58  4881.2  677.18  4958.9  675.98  4959.3  675.48
  4963.3  675.48  4963.6  675.98  5140.4  678.36  5231.6  680.13  5248.7  681.12
  5253.7  680.64  5291.6  683.38  5477.8  689.39  5597.4   692.1  5642.2  692.77
#Mann= 7 ,-1 , 0
  3979.8     .05       0    4022      .1       0  4611.9     .05       0
  4958.9     .04       0  4963.6     .05       0  5140.4      .1       0
  5597.4     .05       0
Bank Sta=4958.9,4963.6
XS Rating Curve= 0 ,0
Exp/Cntr=0.3,0.1

Type RM Length L Ch R = 1 ,6882    ,497,497,497
BEGIN DESCRIPTION:
UNT 037 in BCW 11.0
END DESCRIPTION:
XS GIS Cut Line= 3
      1964825.81     13573983.83      1964458.63     13573890.08
      1963213.84     13574009.87
#Sta/Elev= 30
  4010.4  684.97  4026.3  685.04  4031.9   685.9  4042.2  686.18  4135.1  685.17
  4189.7  683.01  4225.4  682.65  4230.6  683.14  4362.1   679.8  4442.9  678.56
  4533.7  677.13  4641.2  676.86  4740.3  676.06    4825  674.73  4895.3  675.88
  4955.6  675.25  4993.4  674.02  4993.7  673.52  4997.8  673.52  4998.2  674.02
    5028  675.22  5066.1  675.86  5076.1  676.98  5096.2  676.66    5267  680.44
  5307.2  683.43  5427.6  688.08  5434.1  687.81  5533.3  691.73  5639.9  694.24
#Mann= 9 ,-1 , 0
  4010.4     .05       0  4442.9     .08       0  4641.2     .05       0
  4740.3      .1       0  4993.4     .07       0  4998.2      .1       0
    5028     .05       0  5434.1     .08       0  5533.3     .05       0
Bank Sta=4993.4,4998.2
XS Rating Curve= 0 ,0
Exp/Cntr=0.3,0.1

Type RM Length L Ch R = 1 ,6385    ,520,520,520
BEGIN DESCRIPTION:
UNT 037 in BCW 10.0
END DESCRIPTION:
XS GIS Cut Line= 3
      1964953.46     13573879.69      1964307.59     13573449.98
      1963153.92      13573525.5
#Sta/Elev= 30
  3826.6  684.23  3958.4  684.01  3980.9  684.11  3993.7  682.58  4016.9  683.31
  4044.8  682.52    4053  683.41  4080.9   682.5  4095.9  683.02  4123.7  681.55
    4138  681.99  4282.3  677.17  4390.5  674.74    4615  673.56  4775.3  674.23
  4845.5  673.41  4875.5  672.15  4909.8  673.71  4915.6  672.75  4935.7  673.31
  4983.4  671.21  4983.7  670.71  4988.2  671.21  5035.9  673.71  5256.3  675.89
  5286.4  676.93  5305.3   678.8  5406.7  681.19  5678.3  690.86  5758.5  691.73
#Mann= 6 ,-1 , 0
  3826.6      .1       0  3958.4     .05       0  4123.7      .1       0
  4983.4     .07       0  4988.2      .1       0  5305.3     .05       0
Bank Sta=4983.4,4988.2
XS Rating Curve= 0 ,0
Exp/Cntr=0.3,0.1

Type RM Length L Ch R = 1 ,5865    ,712,712,712
BEGIN DESCRIPTION:
UNT 037 in BCW 9.0
END DESCRIPTION:
XS GIS Cut Line= 3
      1964810.21     13573718.24      1964469.04     13573124.45
      1963082.71     13572739.51
#Sta/Elev= 30
  3839.6  681.72  3860.4  682.01  3919.3  680.72  3925.1  681.79  4037.9  678.25
  4247.1  673.17  4343.4  672.21  4520.3  671.66  4523.5  672.08    4798  672.16
  4842.6  671.03  4916.3  670.97  4950.6  671.69  4982.3  670.78  4982.7  670.28
    4987  670.28  4987.3  670.78  5103.2  672.51  5120.2  673.68  5142.6     673
  5317.4   675.1  5363.7  676.49  5379.6  677.64  5431.5  678.33  5493.8  678.34
  5629.4  680.12  5732.2  680.19  5776.8  681.23  5805.2     681  5963.2  683.39
#Mann= 4 ,-1 , 0
  3839.6     .05       0  4037.9      .1       0  4982.3     .07       0
  4987.3      .1       0
Bank Sta=4982.3,4987.3
XS Rating Curve= 0 ,0
Exp/Cntr=0.3,0.1

Type RM Length L Ch R = 1 ,5153    ,401,401,401
BEGIN DESCRIPTION:
Mapping XS 62914c42
END DESCRIPTION:
XS GIS Cut Line= 4
        1964899.     13573636.84      1964622.96     13573251.42
      1964414.62     13572371.21      1963764.89     13572059.34
#Sta/Elev= 30
  3752.1  681.71  3853.5  680.91  3885.6  681.03  3914.3  678.05  4065.4  675.32
    4194  672.71  4489.7  670.54  4892.9  669.54  4962.4  670.94  4972.3  670.82
  4977.4   668.6  5019.7  669.78  5022.3  667.77  5022.7  667.27  5027.4  667.77
  5034.3  669.98  5044.6   670.5  5067.1  669.74  5116.5  671.54  5241.2  673.33
    5344  676.17  5374.3  677.97  5451.7  679.16  5485.5  680.65  5502.6  682.66
  5508.1  681.87  5683.7  687.09  5711.9  689.07  5734.6  689.12  5851.4  694.11
#Mann= 5 ,-1 , 0
  3752.1      .1       0  3853.5     .05       0  4065.4      .1       0
  5022.3     .07       0  5027.4      .1       0
Bank Sta=5022.3,5027.4
XS Rating Curve= 0 ,0
Exp/Cntr=0.3,0.1

Type RM Length L Ch R = 1 ,4752    ,129,129,129
BEGIN DESCRIPTION:
Mapping XS 0c9bcd5d
END DESCRIPTION:
XS GIS Cut Line= 4
      1964925.03     13573563.91       1964711.5     13573298.29
      1964727.12     13571871.21      1964430.22     13571735.78
#Sta/Elev= 30
    3642  680.34  3733.3  679.47  3747.7  680.33  3780.1  678.99  3840.5  676.46
  3890.1  676.37  3970.9  674.21  4416.1  669.94  4596.1  669.09  4656.1  669.29
  4676.1     670  4706.1  669.25  4856.1     669  4866.1  668.04  4876.1  668.95
  4916.2  669.02  4936.2  667.69  4956.2  668.59  5003.6  667.57    5004  667.07
  5008.8  667.57  5066.2  668.86  5246.2   668.4  5336.2  669.56  5438.4  669.64
    5513  671.41  5530.5  672.54  5553.6  672.34  5621.1  675.19  5736.3     683
#Mann= 5 ,-1 , 0
    3642      .1       0  3780.1     .05       0  3970.9      .1       0
  5003.6     .07       0  5008.8      .1       0
Bank Sta=5003.6,5008.8
XS Rating Curve= 0 ,0
Exp/Cntr=0.3,0.1

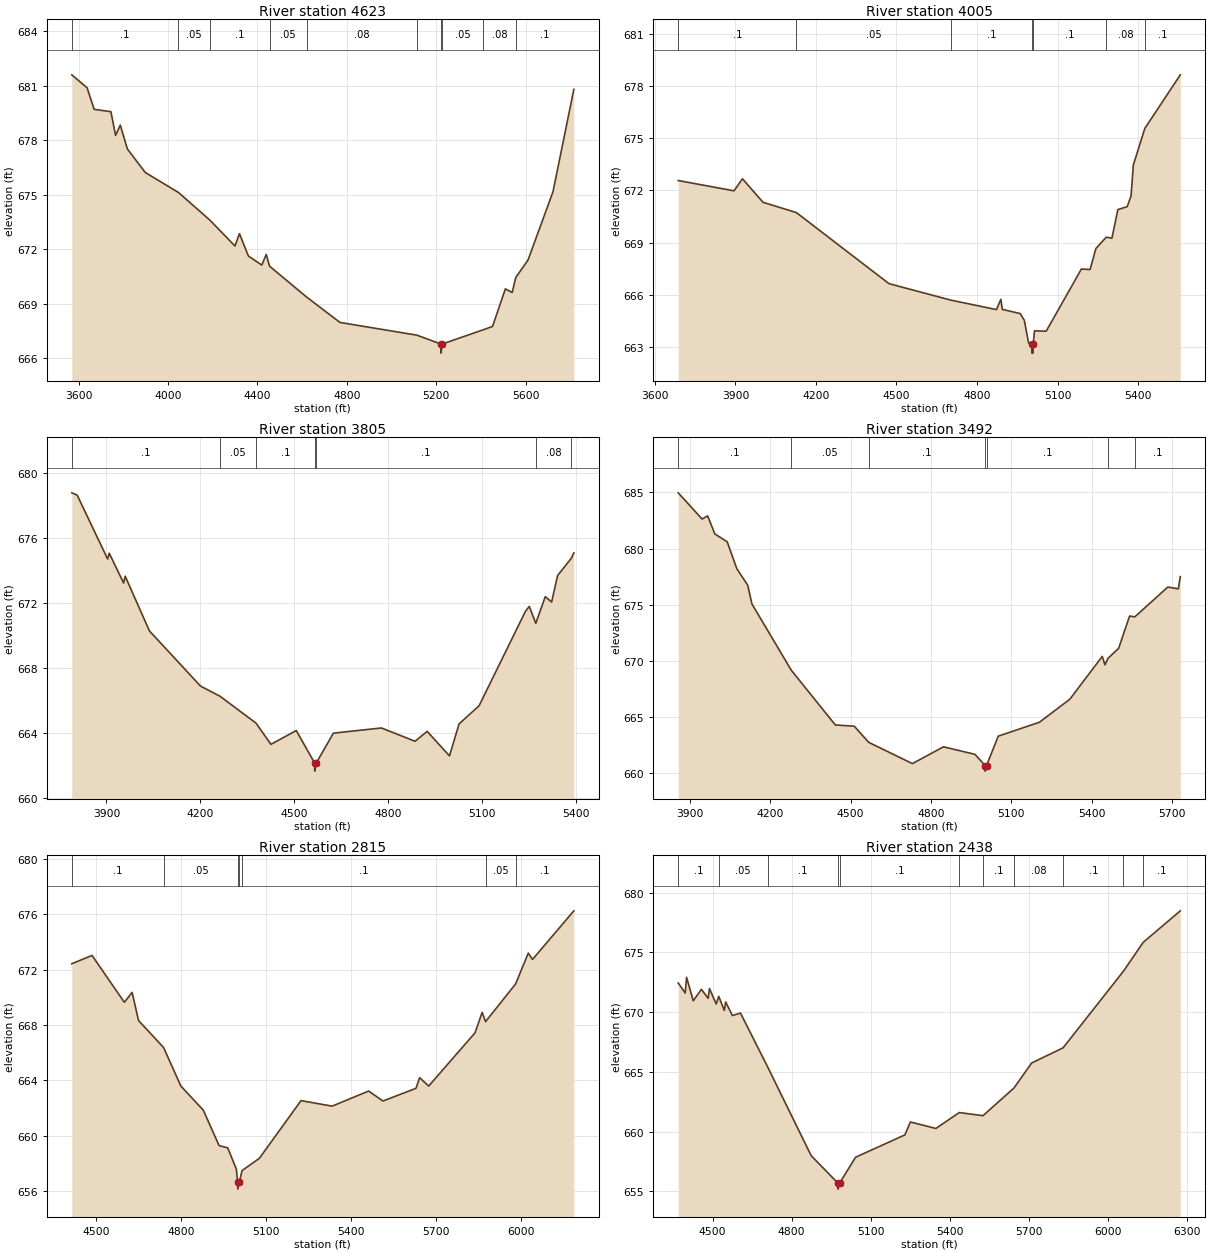
Type RM Length L Ch R = 1 ,4623    ,618,618,618
BEGIN DESCRIPTION:
Mapping XS d4262688
END DESCRIPTION:
XS GIS Cut Line= 4
      1964982.32      13573631.6      1964831.29     13573168.09
      1964841.71     13571772.25      1964483.06     13571709.88
#Sta/Elev= 30
  3568.9   681.6  3637.3  680.89  3669.2   679.7  3744.1  679.57    3765  678.26
  3786.2  678.83  3817.7  677.52  3897.9  676.22  4046.5  675.12  4186.8   673.6
  4299.5  672.17  4319.5  672.85  4359.5  671.62  4419.5  671.12  4439.5  671.71
  4454.2  671.06    4621  669.35  4769.5  667.96  5113.7  667.26  5221.6  666.77
    5222  666.27  5226.8  666.77  5409.3  667.55  5452.3  667.74  5509.8  669.81
  5540.3  669.61  5556.1  670.43  5611.3   671.4    5723  675.16  5816.3   680.8
#Mann= 10 ,-1 , 0
  3568.9      .1       0  4046.5     .05       0  4186.8      .1       0
  4454.2     .05       0    4621     .08       0  5113.7     .05       0
  5221.6     .07       0  5226.8     .05       0  5409.3     .08       0
  5556.1      .1       0
Bank Sta=5221.6,5226.8
XS Rating Curve= 0 ,0
Exp/Cntr=0.3,0.1

Type RM Length L Ch R = 1 ,4005    ,200,200,200
BEGIN DESCRIPTION:
Mapping XS 7ce470d7
END DESCRIPTION:
XS GIS Cut Line= 3
      1965440.66     13572959.71      1965221.91     13571839.96
      1964581.31     13571491.01
#Sta/Elev= 30
    3687  672.56  3894.8  671.97  3926.2  672.66    4003  671.31  4127.2  670.72
    4472  666.64  4703.4  665.69  4872.6  665.15  4888.8  665.74  4894.5  665.16
  4961.1  664.92  4976.2  664.54  4992.3  663.23    5004  663.15  5004.4  662.65
  5008.9  662.65  5009.3  663.15  5014.1  663.93  5057.8  663.91  5188.9  667.48
  5221.2  667.45    5243  668.66  5281.7  669.31  5302.7  669.25  5324.7  670.89
  5359.6  671.06    5374  671.68  5382.4  673.45  5425.1  675.55  5557.4  678.63
#Mann= 7 ,-1 , 0
    3687      .1       0  4127.2     .05       0  4703.4      .1       0
    5004     .07       0  5009.3      .1       0  5281.7     .08       0
  5425.1      .1       0
Bank Sta=5004,5009.3
XS Rating Curve= 0 ,0
Exp/Cntr=0.3,0.1

Type RM Length L Ch R = 1 ,3805    ,313,313,313
BEGIN DESCRIPTION:
Mapping XS 171c1e74
END DESCRIPTION:
XS GIS Cut Line= 2
      1966258.39     13571793.09      1964685.43     13571480.58
#Sta/Elev= 30
  3789.2   678.8  3806.5  678.66  3903.7  674.72  3908.8  675.08  3954.8  673.24
  3959.9  673.66  4037.3  670.29  4200.5  666.89  4262.3  666.27  4377.7  664.61
  4425.4   663.3  4506.3  664.15  4564.9  662.15  4565.3  661.65  4570.2  662.15
  4624.9  663.99  4778.3  664.31  4885.7  663.49  4924.3   664.1  4995.7  662.59
  5026.3  664.56  5090.3  665.68  5238.6  671.51  5250.6   671.8  5271.4  670.76
  5301.6   672.4    5322  672.07  5340.9   673.7    5385  674.77  5392.9   675.1
#Mann= 7 ,-1 , 0
  3789.2      .1       0  4262.3     .05       0  4377.7      .1       0
  4564.9     .07       0  4570.2      .1       0  5271.4     .08       0
    5385      .1       0
Bank Sta=4564.9,4570.2
XS Rating Curve= 0 ,0
Exp/Cntr=0.3,0.1

Type RM Length L Ch R = 1 ,3492    ,677,677,677
BEGIN DESCRIPTION:
UNT 037 in BCW 5.0
END DESCRIPTION:
XS GIS Cut Line= 3
      1966341.43     13571594.07      1965096.65     13571276.36
      1964519.26      13571390.8
#Sta/Elev= 30
    3857  684.97  3946.2  682.63  3966.8  682.91  3993.7   681.3  4039.7   680.6
  4075.4  678.21  4116.3  676.72    4132  675.05  4278.7  669.14  4443.2  664.25
  4513.8  664.14  4567.6   662.7  4730.6   660.8  4846.6   662.3    4964  661.63
  5002.2  660.63  5002.6  660.13  5007.5  660.63  5050.9  663.25  5204.5  664.49
  5318.2  666.55    5439  670.37  5449.2  669.62  5460.6   670.2  5500.2  671.09
    5541  673.97  5560.6   673.9  5683.7  676.56  5722.8   676.4  5730.3  677.49
#Mann= 7 ,-1 , 0
    3857      .1       0  4278.7     .05       0  4567.6      .1       0
  5002.2     .07       0  5007.5      .1       0  5460.6     .08       0
  5560.6      .1       0
Bank Sta=5002.2,5007.5
XS Rating Curve= 0 ,0
Exp/Cntr=0.3,0.1

Type RM Length L Ch R = 1 ,2815    ,377,377,377
BEGIN DESCRIPTION:
UNT 037 in BCW 4.0
END DESCRIPTION:
XS GIS Cut Line= 3
      1966091.46     13570541.98      1965742.48     13570812.82
       1964494.1     13571270.56
#Sta/Elev= 30
  4413.4  672.42  4484.9  673.02  4598.8  669.64  4626.3  670.35    4649  668.32
  4737.4  666.37  4798.3  663.59  4877.5  661.85  4933.2  659.29  4963.7  659.13
  4994.2  657.59  4998.5  656.65    4999  656.15  5004.6  656.65  5014.2  657.49
  5075.1  658.37  5222.3  662.54  5331.8  662.14  5460.9  663.23  5511.3  662.51
    5628  663.43  5640.6   664.2  5672.6  663.59  5836.1  667.43  5861.3  668.91
  5873.3  668.24  5979.3  670.96  6024.1  673.19    6039  672.73  6184.8  676.24
#Mann= 7 ,-1 , 0
  4413.4      .1       0  4737.4     .05       0  4998.5    .035       0
  5004.6     .05       0  5014.2      .1       0  5873.3     .05       0
  5979.3      .1       0
Bank Sta=4998.5,5004.6
XS Rating Curve= 0 ,0
Exp/Cntr=0.3,0.1

Type RM Length L Ch R = 1 ,2438    ,130,130,130
BEGIN DESCRIPTION:
UNT 037 in BCW 3.0
END DESCRIPTION:
XS GIS Cut Line= 3
      1966013.28     13570380.54      1965737.27     13570479.49
      1964195.59     13570953.45
#Sta/Elev= 30
  4369.5  672.44  4395.9   671.6  4401.2  672.91  4426.6  670.95  4457.4  671.91
  4482.8  671.16  4488.1  671.97  4513.6  670.68  4523.3  671.32  4544.3  670.14
  4549.6  670.85  4575.1  669.71  4605.8  669.92    4709  665.41  4874.3  657.98
  4975.8  655.68  4976.3  655.18    4982  655.68  5042.9  657.85    5230  659.72
  5250.9   660.8  5347.7  660.26  5436.4  661.59  5526.5  661.33  5644.3  663.65
  5711.3  665.74  5830.6  667.01  6059.9  673.43  6134.7  675.84  6275.6  678.48
#Mann= 11 ,-1 , 0
  4369.5      .1       0  4523.3     .05       0    4709      .1       0
  4975.8     .07       0    4982      .1       0  5436.4     .05       0
  5526.5      .1       0  5644.3     .08       0  5830.6      .1       0
  6059.9     .08       0  6134.7      .1       0
Bank Sta=4975.8,4982
XS Rating Curve= 0 ,0
Exp/Cntr=0.3,0.1

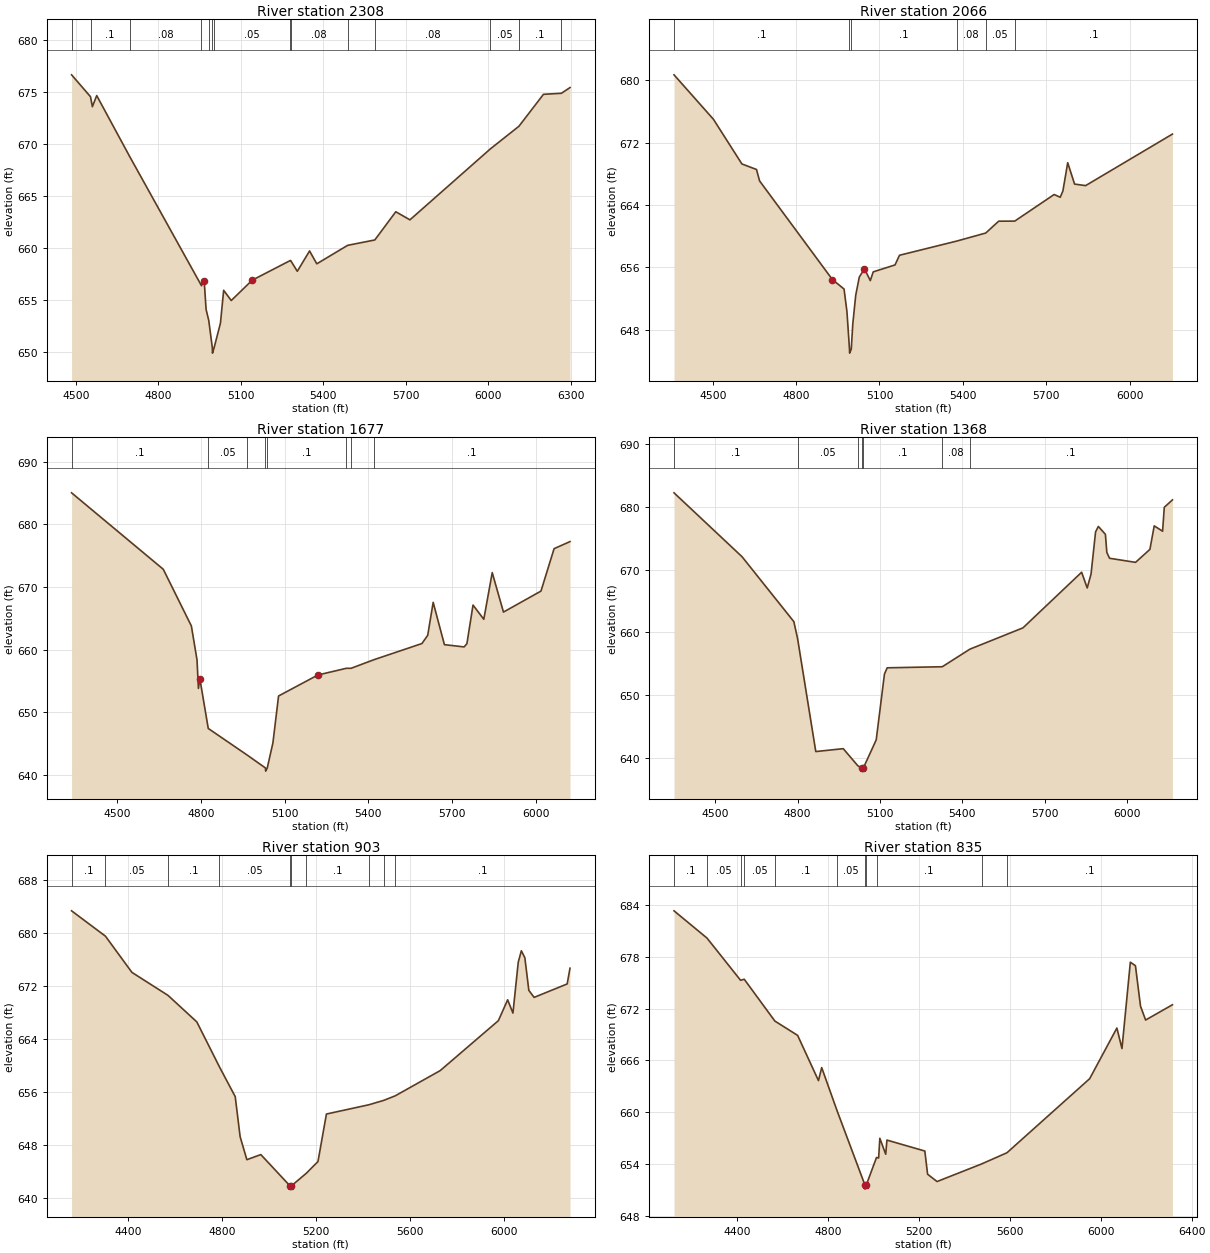
Type RM Length L Ch R = 1 ,2308    ,242,242,242
BEGIN DESCRIPTION:
UNT 037 in BCW 2.0
END DESCRIPTION:
XS GIS Cut Line= 3
      1965862.28     13570307.61      1965409.15     13570448.24
      1964128.97     13570838.54
#Sta/Elev= 30
  4484.4  676.69  4553.2  674.58    4560  673.62  4575.8  674.69  4695.2  668.84
  4956.9  656.36  4966.7  656.85  4973.6  654.08  4983.3  653.01  4996.4  650.36
  4996.9  649.86  5002.6  650.36  5025.9  652.76  5037.5  655.92  5065.1  654.93
  5141.2  656.89    5280  658.79  5281.1  658.79  5305.4  657.75    5350  659.71
  5376.3  658.47  5488.4  660.25  5587.3  660.77  5663.6  663.49    5715  662.71
  6007.6  669.55  6111.4  671.73  6200.7  674.81  6265.9  674.91  6297.2  675.46
#Mann= 14 ,-1 , 0
  4484.4     .08       0  4553.2      .1       0  4695.2     .08       0
  4956.9      .1       0  4983.3     .05       0  4996.4     .04       0
  5002.6     .05       0    5280      .1       0  5281.1     .08       0
  5488.4      .1       0  5587.3     .08       0  6007.6     .05       0
  6111.4      .1       0  6265.9     .05       0
Bank Sta=4966.7,5141.2
XS Rating Curve= 0 ,0
Exp/Cntr=0.3,0.1

Type RM Length L Ch R = 1 ,2066    ,389,389,389
BEGIN DESCRIPTION:
Mapping XS 06594139
END DESCRIPTION:
XS GIS Cut Line= 2
      1965777.67     13570147.63      1964069.65     13570694.41
#Sta/Elev= 30
  4360.7  680.68  4502.5  674.98    4605  669.25  4657.5  668.54  4668.5  667.08
  4930.9  654.41  4972.5  653.21    4983  650.29  4992.1  645.49  4992.6  644.99
  4998.4  645.49    5004  648.75  5014.5  652.41  5027.4  654.75    5046   655.8
    5067  654.29  5077.5  655.41  5155.9   656.3    5172  657.54    5378  659.36
  5482.3  660.39    5529  661.91  5586.6  661.92  5728.5  665.33  5750.4  664.98
    5760  665.79  5777.3  669.41    5802  666.67  5841.6  666.47  6154.1  673.08
#Mann= 6 ,-1 , 0
  4360.7      .1       0  4992.1     .07       0  4998.4      .1       0
    5378     .08       0  5482.3     .05       0  5586.6      .1       0
Bank Sta=4930.9,5046
XS Rating Curve= 0 ,0
Exp/Cntr=0.3,0.1

Type RM Length L Ch R = 1 ,1677    ,309,309,309
BEGIN DESCRIPTION:
Mapping XS 637dec23
END DESCRIPTION:
XS GIS Cut Line= 2
      1965701.09     13569914.38      1963928.41     13570132.93
#Sta/Elev= 30
  4336.5  685.01  4665.1  672.81  4765.8  663.76    4786  658.35    4791   653.8
  4796.1  655.36  4826.3  647.41  4965.9  643.16  5031.4   641.1  5031.9   640.6
  5037.7   641.1    5058  645.11  5078.2  652.59  5219.2  655.94  5321.2  657.01
  5338.1  657.01  5420.7  658.39    5592  660.96  5612.7  662.27  5632.3  667.53
  5672.6  660.78  5743.2  660.42  5753.2  660.94  5775.1   667.1  5813.7  664.83
  5843.9  672.28  5884.2  665.98  6018.6  669.33  6065.6   676.1  6122.6  677.23
#Mann= 8 ,-1 , 0
  4336.5      .1       0  4826.3     .05       0  4965.9      .1       0
  5031.4     .07       0  5037.7      .1       0  5321.2     .05       0
  5338.1     .08       0  5420.7      .1       0
Bank Sta=4796.1,5219.2
XS Rating Curve= 0 ,0
Exp/Cntr=0.3,0.1

Type RM Length L Ch R = 1 ,1368    ,465,465,465
BEGIN DESCRIPTION:
Mapping XS a2b1b624
END DESCRIPTION:
XS GIS Cut Line= 4
      1965631.63     13569869.25      1965426.77     13569671.33
      1964718.44     13569702.58      1963909.71      13569855.3
#Sta/Elev= 30
  4349.4  682.19  4597.5  672.03  4786.2  661.72  4799.8  659.04  4866.2  641.07
  4966.3  641.53  5019.3  638.82  5033.3  638.46  5033.8  637.96  5039.6  638.46
  5086.5  642.93  5116.5  653.39  5126.5  654.38  5327.4  654.55  5427.8  657.34
  5621.5  660.73  5835.3  669.57  5855.6  667.07  5869.6  669.28  5886.1  675.98
  5896.3  676.85    5922  675.59  5927.1  672.73    5937  671.79  6031.8  671.14
  6084.2   673.2  6099.9  676.94  6130.4  676.09  6136.6  679.89  6166.3  681.07
#Mann= 7 ,-1 , 0
  4349.4      .1       0  4799.8     .05       0  5019.3      .1       0
  5033.3    .033       0  5039.6      .1       0  5327.4     .08       0
  5427.8      .1       0
Bank Sta=5033.3,5039.6
XS Rating Curve= 0 ,0
Exp/Cntr=0.3,0.1

Type RM Length L Ch R = 1 ,903     ,68,68,68
BEGIN DESCRIPTION:
Mapping XS 1557a574
END DESCRIPTION:
XS GIS Cut Line= 6
      1965770.53     13569772.03      1965305.24     13569331.05
      1965232.32     13569244.25      1965117.74     13569233.83
      1964940.66     13569223.41      1963979.43     13569695.35
#Sta/Elev= 30
  4161.6  683.34  4305.5  679.51  4417.9  674.04  4571.3  670.56  4693.8  666.55
  4789.8  659.76  4856.9  655.26  4877.7  649.21  4906.3  645.73  4965.7   646.5
  5089.3  641.78  5089.8  641.28  5095.9  641.78  5159.3  643.69  5208.5  645.45
  5244.4  652.63  5424.9  654.03  5487.7  654.69  5536.2  655.37  5727.7  659.19
    5975  666.74  6014.4  669.89  6036.9  667.89  6059.4  675.57  6072.6   677.3
  6087.5  676.25  6104.4  671.32  6126.9  670.26  6267.3  672.29  6279.3  674.67
#Mann= 10 ,-1 , 0
  4161.6      .1       0  4305.5     .05       0  4571.3      .1       0
  4789.8     .05       0  5089.3    .033       0  5095.9     .05       0
  5159.3      .1       0  5424.9     .05       0  5487.7     .08       0
  5536.2      .1       0
Bank Sta=5089.3,5095.9
XS Rating Curve= 0 ,0
Exp/Cntr=0.3,0.1

Type RM Length L Ch R = 1 ,835     ,47,47,47
BEGIN DESCRIPTION:
Mapping XS f8ed087f
END DESCRIPTION:
XS GIS Cut Line= 6
      1965843.45     13569775.51      1965246.21     13569206.05
      1965124.69     13569164.38      1964999.69     13569164.38
      1964937.19      13569174.8      1963996.22     13569643.55
#Sta/Elev= 30
  4122.1  683.35  4267.2  680.19    4415  675.29  4431.2  675.41  4565.9  670.56
    4666   668.9  4757.8  663.65    4772  665.16  4839.9  660.14  4961.9  651.56
  4962.4  651.06  4968.5  651.56  5013.2  654.73  5022.5  654.67  5027.8  656.96
  5053.7  655.11    5059  656.75  5225.8  655.48    5238  652.79  5279.6  651.94
  5475.6  653.98  5587.2  655.28  5951.1  663.87    6071  669.75  6093.3  667.37
  6130.2  677.39  6152.6  676.98    6175  672.28  6197.4  670.68  6315.4  672.45
#Mann= 11 ,-1 , 0
  4122.1      .1       0  4267.2     .05       0    4415      .1       0
  4431.2     .05       0  4565.9      .1       0  4839.9     .05       0
  4961.9    .033       0  4968.5     .05       0  5013.2      .1       0
  5475.6     .05       0  5587.2      .1       0
Bank Sta=4961.9,4968.5
XS Rating Curve= 0 ,0
Exp/Cntr=0.3,0.1

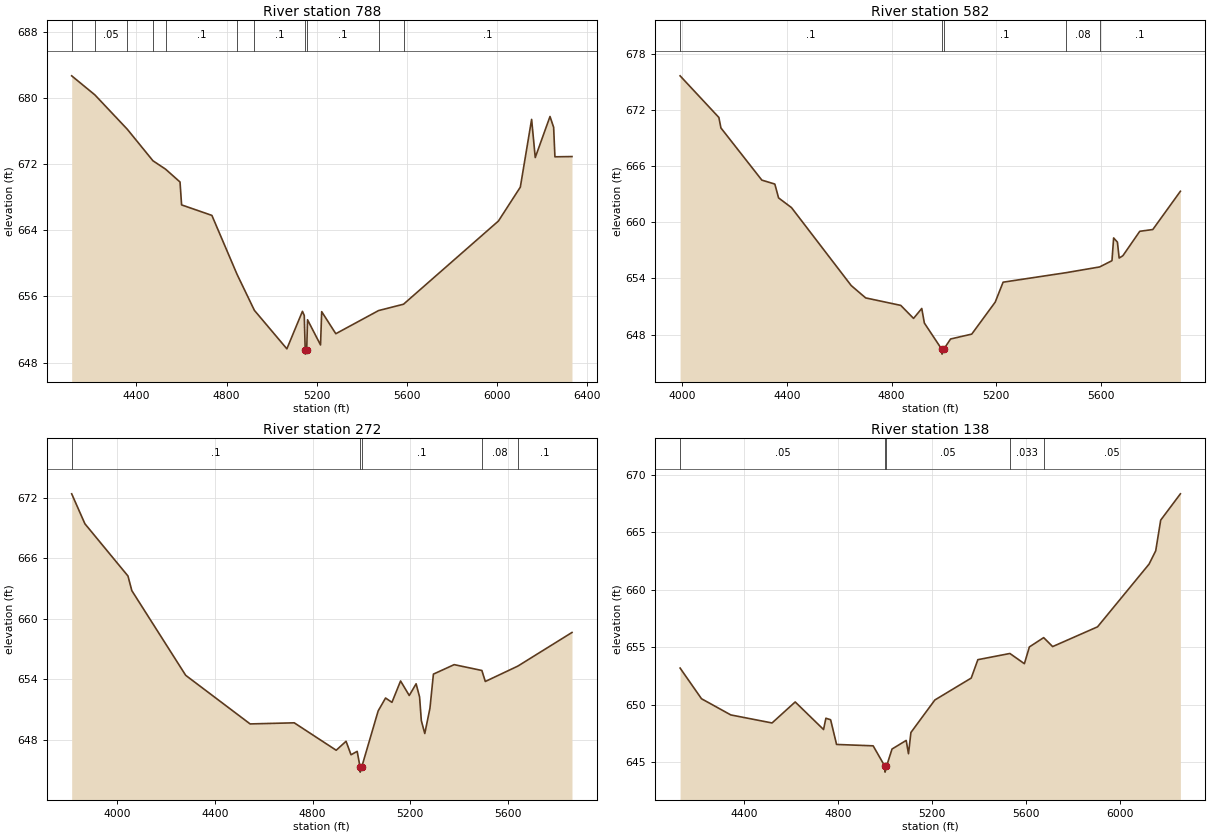
Type RM Length L Ch R = 1 ,788     ,206,206,206
BEGIN DESCRIPTION:
Mapping XS cf378213
END DESCRIPTION:
XS GIS Cut Line= 6
      1965850.57     13569749.21      1965254.21     13569152.85
      1965058.89     13569129.41      1964892.23     13569155.45
      1964704.73     13569228.37      1963993.79     13569616.39
#Sta/Elev= 30
  4112.9   682.7  4215.6   680.4  4359.5  676.24  4473.5  672.42  4529.2  671.41
  4593.6  669.85  4600.6  667.08    4735  665.81  4846.6  658.68  4923.6  654.32
  5067.7  649.66  5136.8   654.2  5144.9   653.7  5149.1  649.52  5149.6  649.02
  5155.7  649.52  5159.4  653.18  5217.1  650.13  5222.2  654.16  5284.9  651.49
  5474.5  654.29  5585.3  655.06  6006.5  665.13  6103.6  669.23  6153.7  677.43
  6169.8  672.81  6235.3  677.78  6251.4  676.47  6257.1   672.9  6332.8  672.93
#Mann= 11 ,-1 , 0
  4112.9      .1       0  4215.6     .05       0  4359.5      .1       0
  4473.5     .05       0  4529.2      .1       0  4846.6     .05       0
  4923.6      .1       0  5149.1     .07       0  5155.7      .1       0
  5474.5     .05       0  5585.3      .1       0
Bank Sta=5149.1,5155.7
XS Rating Curve= 0 ,0
Exp/Cntr=0.3,0.1

Type RM Length L Ch R = 1 ,582     ,310,310,310
BEGIN DESCRIPTION:
Mapping XS 23c00e30
END DESCRIPTION:
XS GIS Cut Line= 4
      1965840.84     13569528.34      1965385.11     13568981.45
      1964773.13      13569010.1       1964309.8      13569366.7
#Sta/Elev= 30
  3993.2  675.66  4141.2  671.21    4149  670.09  4305.2  664.51  4354.7  664.09
    4369  662.61  4418.4  661.57  4646.2  653.24  4701.3  651.92  4835.3  651.12
  4884.1  649.73  4915.4  650.79  4925.4  649.23  4992.2  646.41  4992.7  645.91
  4998.8  646.41  5025.5  647.53  5106.2  648.05  5195.7  651.47  5225.8   653.6
  5466.9  654.62  5594.2  655.23  5641.3   655.9  5647.6  658.33  5662.1  657.88
  5668.7  656.18  5682.9  656.43  5747.3  659.04  5797.1  659.23  5902.4  663.32
#Mann= 5 ,-1 , 0
  3993.2      .1       0  4992.2     .07       0  4998.8      .1       0
  5466.9     .08       0  5594.2      .1       0
Bank Sta=4992.2,4998.8
XS Rating Curve= 0 ,0
Exp/Cntr=0.3,0.1

Type RM Length L Ch R = 1 ,272     ,134,134,134
BEGIN DESCRIPTION:
Mapping XS 62b52eb2
END DESCRIPTION:
XS GIS Cut Line= 4
      1965833.01     13569431.95      1965458.02     13568775.72
      1964924.17     13568702.81      1964403.31      13569244.5
#Sta/Elev= 30
  3814.9  672.38    3869  669.41  4045.1  664.23  4060.9  662.78  4281.2  654.38
  4544.7  649.56  4725.1  649.67  4896.7  646.95  4937.1  647.84  4957.3   646.5
  4982.5  646.84  4994.4  645.28  4994.9  644.78    5001  645.28  5068.3  650.85
  5098.6  652.13  5124.7   651.7    5160  653.82  5195.5  652.38  5223.5  653.54
  5237.7  652.24  5244.9  649.88    5259  648.61  5280.1  651.11  5294.3   654.5
  5379.2  655.44  5492.5  654.86  5506.5  653.77  5639.2  655.29    5861  658.63
#Mann= 5 ,-1 , 0
  3814.9      .1       0  4994.4     .07       0    5001      .1       0
  5492.5     .08       0  5639.2      .1       0
Bank Sta=4994.4,5001
XS Rating Curve= 0 ,0
Exp/Cntr=0.3,0.1

Type RM Length L Ch R = 1 ,138     ,0,0,0
BEGIN DESCRIPTION:
UNT 037 in BCW 1.0
END DESCRIPTION:
XS GIS Cut Line= 4
      1965710.64     13568933.31      1965583.02     13568563.48
       1964876.6     13568632.02      1964150.03     13569358.59
#Sta/Elev= 30
  4129.2  653.18  4220.2  650.51    4345   649.1  4520.4   648.4  4618.9  650.23
  4739.5  647.83  4749.5  648.81  4769.6  648.68  4794.9  646.53  4950.5  646.41
  5000.6  644.62  5001.1  644.12  5007.3  644.62  5030.8  646.13  5091.1  646.88
  5100.9  645.72  5111.2  647.57    5213   650.4  5367.8  652.31    5396  653.91
  5532.3  654.45    5594  653.56  5615.2  655.02    5676  655.83  5714.2  655.05
  5905.2  656.77  6124.4  662.23  6152.7  663.39  6173.9  666.06  6257.7  668.35
#Mann= 5 ,-1 , 0
  4129.2     .05       0  5000.6    .033       0  5007.3     .05       0
  5532.3    .033       0    5676     .05       0
Bank Sta=5000.6,5007.3
XS Rating Curve= 0 ,0
Exp/Cntr=0.3,0.1
LCMann Table=0

Chan Stop Cuts=-1
Use User Specified Reach Order=0
Composite Channel Slope=5