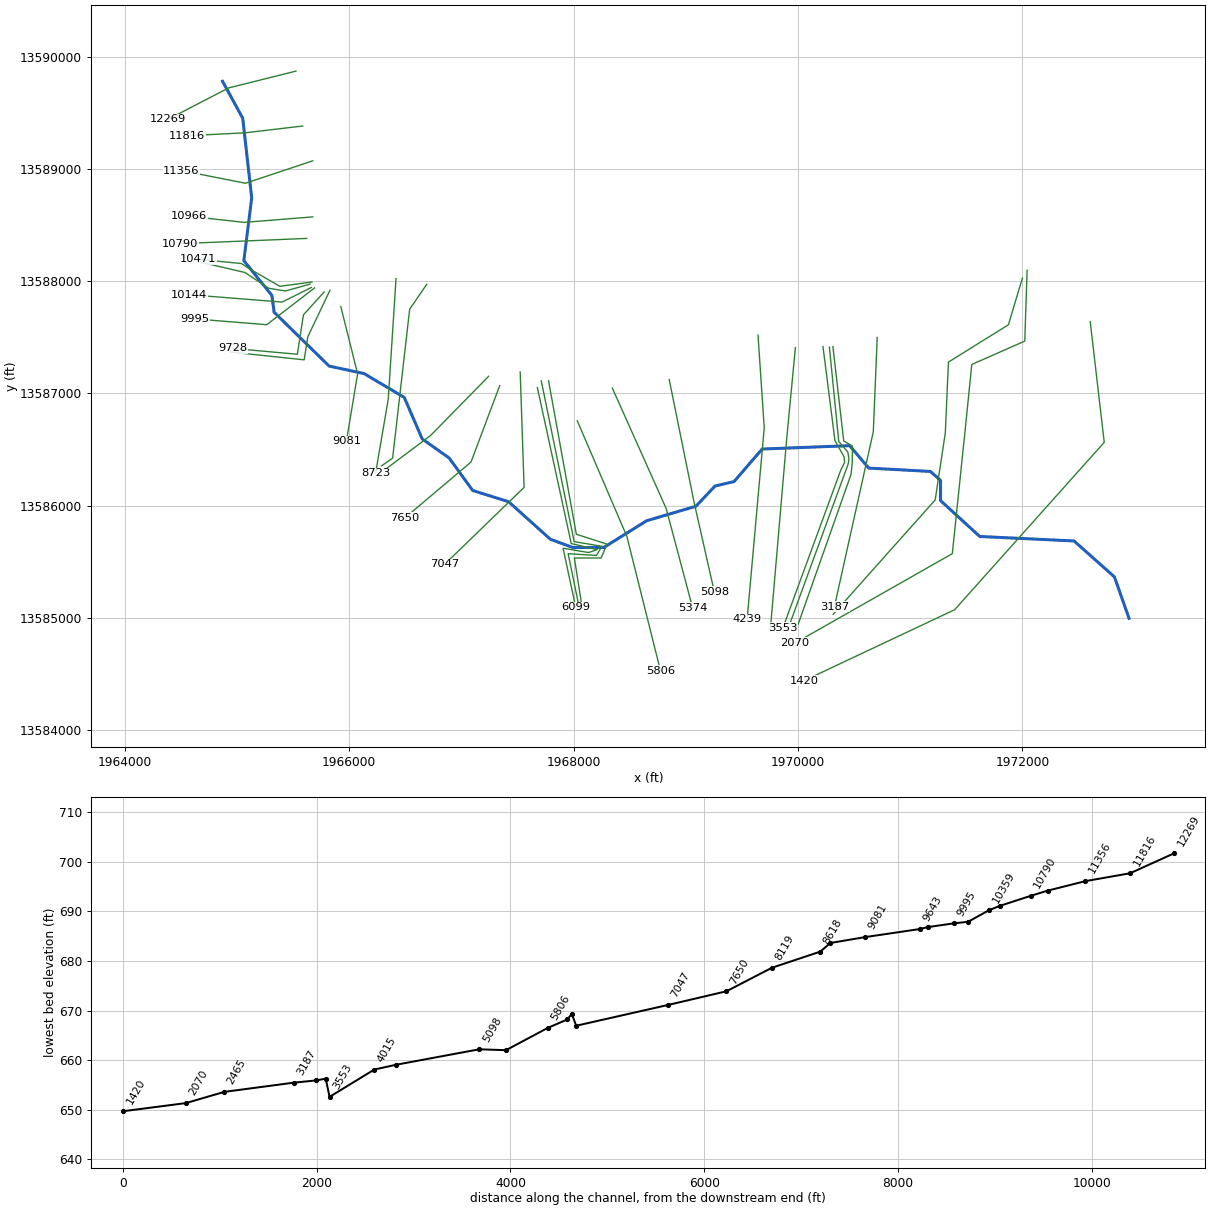
--- UNT 038 in BCW.prj (project) ---

Proj Title=UNT 038 in BCW Base Level Engineering
Current Plan=p01
Default Exp/Contr=0.3,0.1
English Units
Geom File=g01
Flow File=f01
Plan File=p01
Y Axis Title=Elevation
X Axis Title(PF)=Main Channel Distance
X Axis Title(XS)=Station
BEGIN DESCRIPTION:
UNT 038 in BCW
END DESCRIPTION:
DSS Export Rating Curves= 0
DSS Export Rating Curve Sorted= 0
DSS Export Volume Flow Curves= 0
DXF OffsetX= 0
DXF OffsetY= 0
DXF ScaleX= 1
DXF ScaleY= 10

--- UNT 038 in BCW.p01 (plan) ---

Plan Title=Multiple Run
Short Identifier=Multiple
Geom File=g01
Flow File=f01
Subcritical Flow
K Sum by GR= 0
Std Step Tol= 0.01
Critical Tol= 0.01
Num of Std Step Trials= 20
Max Error Tol= 0.3
Flow Tol Ratio= 0.001
Split Flow NTrial= 30
Split Flow Tol= 0.02
Split Flow Ratio= 0.02
Log Output Level= 0
Friction Slope Method= 1
Unsteady Friction Slope Method= 2
Unsteady Bridges Friction Slope Method= 1
Parabolic Critical Depth
Global Vel Dist=  1 , 1 , 1
Global Log Level= 0
CheckData=True
Encroach Param= -1, 0, 0, 0
BEGIN DESCRIPTION:
Multiple Run
END DESCRIPTION:

--- UNT 038 in BCW.f01 (steady flow) ---

Flow Title=Multiple
Program Version=5.05
Number of Profiles= 7
Profile Names=10-year,25-year,50-year,1pct_min,100-year,1pct_plu,500-year
River Rch & RM=UNT 038 in BCW,Reach-1         ,12269
     493     684     840     511    1019    2033    1499
River Rch & RM=UNT 038 in BCW,Reach-1         ,9081
     957    1382    1743    1085    2165    4321    3347
River Rch & RM=UNT 038 in BCW,Reach-1         ,8723
     957    1382    1743    1085    2165    4321    3347
River Rch & RM=UNT 038 in BCW,Reach-1         ,6099
    1549    2287    2929    1848    3687    7357    5859
Boundary for River Rch & Prof#=UNT 038 in BCW,Reach-1         , 1
Up Type= 0
Dn Type= 3
Dn Slope=0.005
Boundary for River Rch & Prof#=UNT 038 in BCW,Reach-1         , 2
Up Type= 0
Dn Type= 3
Dn Slope=0.005
Boundary for River Rch & Prof#=UNT 038 in BCW,Reach-1         , 3
Up Type= 0
Dn Type= 3
Dn Slope=0.005
Boundary for River Rch & Prof#=UNT 038 in BCW,Reach-1         , 4
Up Type= 0
Dn Type= 3
Dn Slope=0.005
Boundary for River Rch & Prof#=UNT 038 in BCW,Reach-1         , 5
Up Type= 0
Dn Type= 3
Dn Slope=0.005
Boundary for River Rch & Prof#=UNT 038 in BCW,Reach-1         , 6
Up Type= 0
Dn Type= 3
Dn Slope=0.005
Boundary for River Rch & Prof#=UNT 038 in BCW,Reach-1         , 7
Up Type= 0
Dn Type= 3
Dn Slope=0.005
DSS Import GetInterval= 0
DSS Import GetPeak= 0
DSS Import FillOption= 0

--- UNT 038 in BCW.g01 (geometry) ---

Geom Title=Existing Conditions

River Reach=UNT 038 in BCW,Reach-1
Reach XY= 30
      1964870.80     13589784.54      1965050.80     13589454.54
      1965130.80     13588744.54      1965060.80     13588184.54
      1965310.80     13587874.54      1965330.80     13587724.54
      1965820.80     13587244.54      1966133.22     13587177.15
      1966490.80     13586964.54      1966650.80     13586594.54
      1966890.80     13586424.54      1967100.80     13586134.54
      1967420.80     13586034.54      1967793.12     13585699.79
      1967994.95     13585625.57      1968269.69     13585626.87
      1968650.80     13585864.54      1969090.80     13585994.54
      1969260.80     13586174.54      1969430.80     13586214.54
      1969680.80     13586504.54      1970460.80     13586534.54
      1970630.80     13586334.54      1971180.80     13586304.54
      1971270.80     13586224.54      1971270.80     13586044.54
      1971620.80     13585724.54      1972460.80     13585684.54
      1972820.80     13585364.54      1972950.80     13584994.54

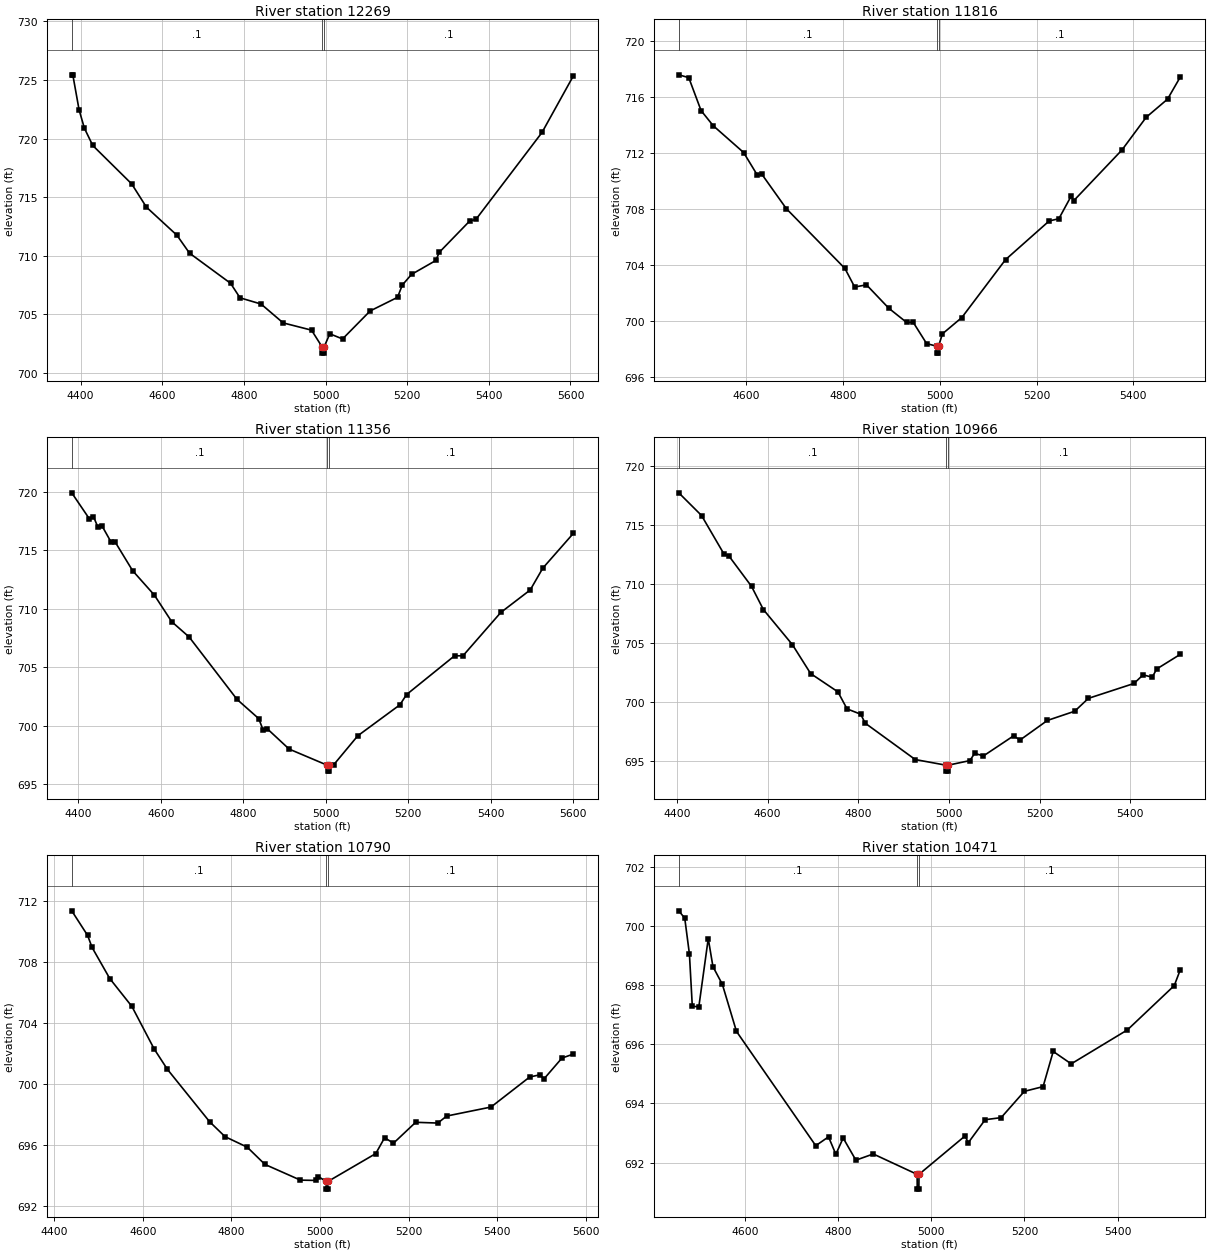
Type RM Length L Ch R = 1,12269,453,453,453
BEGIN DESCRIPTION:
UNT 038 in BCW 19.0
END DESCRIPTION:
XS GIS Cut Line= 3
      1965524.98     13589874.99      1964925.00     13589725.00
      1964383.18     13589443.99
#Sta/Elev= 30
  4378.1  725.44  4380.7  725.44  4396.1  722.45  4409.0  720.89  4429.6  719.41
  4525.0  716.13  4561.0  714.15  4635.8  711.75  4666.7  710.22  4767.2  707.65
  4790.4  706.41  4841.9  705.88  4896.0  704.27  4965.6  703.65  4992.0  702.19
  4992.2  701.69  4995.7  701.69  4996.0  702.19  5010.4  703.34  5041.6  702.90
  5109.2  705.29  5176.2  706.45  5188.0  707.50  5210.6  708.41  5270.3  709.60
  5278.2  710.28  5353.2  712.97  5368.3  713.10  5530.2  720.52  5606.9  725.34
#Mann=3,-1,0
  4378.1     0.1       0  4992.0    0.07       0  4996.0     0.1       0
Bank Sta=4992,4996
Exp/Cntr=0.3,0.1

Type RM Length L Ch R = 1,11816,460,460,460
BEGIN DESCRIPTION:
UNT 038 in BCW 18.0
END DESCRIPTION:
XS GIS Cut Line= 3
      1965585.50     13589385.42      1965075.00     13589325.00
      1964554.64     13589298.61
#Sta/Elev= 30
  4461.7  717.60  4482.3  717.40  4507.7  715.04  4532.7  713.96  4595.5  712.04
  4623.3  710.45  4633.4  710.47  4683.7  708.02  4804.6  703.74  4824.7  702.41
  4849.0  702.57  4895.2  700.89  4931.8  699.88  4945.6  699.88  4973.2  698.36
  4993.8  698.18  4994.0  697.68  4997.5  697.68  4997.8  698.18  5005.8  699.06
  5045.9  700.23  5136.0  704.37  5226.1  707.14  5246.1  707.30  5271.5  708.92
  5276.5  708.58  5376.3  712.22  5426.3  714.56  5470.4  715.86  5496.8  717.45
#Mann=3,-1,0
  4461.7     0.1       0  4993.8    0.07       0  4997.8     0.1       0
Bank Sta=4993.8,4997.8
Exp/Cntr=0.3,0.1

Type RM Length L Ch R = 1,11356,390,390,390
BEGIN DESCRIPTION:
UNT 038 in BCW 17.0
END DESCRIPTION:
XS GIS Cut Line= 3
      1965675.00     13589075.00      1965075.00     13588875.00
      1964502.55     13588988.29
#Sta/Elev= 30
  4384.2  719.94  4426.4  717.74  4436.9  717.90  4447.4  717.02  4458.0  717.08
  4479.1  715.75  4489.6  715.72  4531.8  713.27  4584.5  711.18  4626.6  708.90
  4668.8  707.59  4784.8  702.25  4837.5  700.60  4848.0  699.64  4858.5  699.72
  4911.2  697.99  5004.1  696.60  5004.4  696.10  5007.9  696.10  5008.1  696.60
  5019.2  696.64  5077.8  699.13  5179.8  701.78  5196.0  702.66  5312.3  705.98
  5332.7  705.98  5424.4  709.69  5495.8  711.62  5526.3  713.49  5600.2  716.46
#Mann=3,-1,0
  4384.2     0.1       0  5004.1    0.07       0  5008.1     0.1       0
Bank Sta=5004.1,5008.1
Exp/Cntr=0.3,0.1

Type RM Length L Ch R = 1,10966,176,176,176
BEGIN DESCRIPTION:
UNT 038 in BCW 16.0
END DESCRIPTION:
XS GIS Cut Line= 3
      1965674.99     13588575.00      1965064.64     13588526.04
      1964573.32     13588580.15
#Sta/Elev= 30
  4403.9  717.74  4454.1  715.82  4504.2  712.52  4514.2  712.41  4564.4  709.82
  4590.5  707.86  4654.7  704.88  4694.8  702.44  4755.0  700.89  4775.1  699.45
  4805.2  699.00  4815.2  698.24  4925.6  695.16  4993.8  694.68  4994.0  694.18
  4997.5  694.18  4997.8  694.68  5046.0  695.07  5056.7  695.68  5076.2  695.47
  5142.7  697.17  5156.7  696.81  5217.1  698.47  5277.4  699.25  5307.6  700.34
  5408.2  701.60  5428.3  702.33  5448.4  702.13  5458.5  702.83  5510.5  704.07
#Mann=3,-1,0
  4403.9     0.1       0  4993.8    0.07       0  4997.8     0.1       0
Bank Sta=4993.8,4997.8
Exp/Cntr=0.3,0.1

Type RM Length L Ch R = 1,10790,319,319,319
BEGIN DESCRIPTION:
Mapping XS 8d63797d
END DESCRIPTION:
XS GIS Cut Line= 2
      1965620.82     13588382.88      1964489.39     13588336.02
#Sta/Elev= 30
  4439.5  711.37  4475.3  709.76  4485.4  708.97  4525.4  706.93  4575.4  705.10
  4625.5  702.32  4655.5  700.98  4750.7  697.55  4785.6  696.57  4835.7  695.88
  4875.7  694.75  4955.8  693.72  4991.6  693.70  4996.6  693.95  5013.8  693.63
  5014.1  693.13  5017.6  693.13  5017.8  693.63  5125.9  695.46  5145.9  696.50
  5165.9  696.14  5216.0  697.51  5266.0  697.46  5286.0  697.92  5386.1  698.51
  5473.5  700.48  5496.2  700.62  5506.2  700.37  5546.3  701.72  5571.9  701.98
#Mann=3,-1,0
  4439.5     0.1       0  5013.8    0.07       0  5017.8     0.1       0
Bank Sta=5013.8,5017.8
Exp/Cntr=0.3,0.1

Type RM Length L Ch R = 1,10471,112,112,112
BEGIN DESCRIPTION:
Mapping XS f28a0838
END DESCRIPTION:
XS GIS Cut Line= 5
      1965667.64     13587993.98      1965381.23     13587955.79
      1965099.98     13588118.99      1965039.22     13588158.92
      1964652.02     13588197.12
#Sta/Elev= 30
  4458.5  700.52  4471.3  700.27  4481.3  699.06  4487.5  697.29  4501.5  697.27
  4521.7  699.58  4531.8  698.63  4552.0  698.03  4582.2  696.44  4752.3  692.57
  4779.7  692.87  4795.4  692.28  4811.1  692.83  4838.4  692.08  4875.7  692.29
  4969.8  691.60  4970.0  691.10  4973.5  691.10  4973.8  691.60  5072.6  692.90
  5079.5  692.67  5115.7  693.45  5150.0  693.52  5199.8  694.41  5240.0  694.57
  5261.7  695.76  5300.3  695.34  5420.9  696.49  5521.4  697.99  5534.4  698.53
#Mann=3,-1,0
  4458.5     0.1       0  4969.8    0.07       0  4973.8     0.1       0
Bank Sta=4969.8,4973.8
Exp/Cntr=0.3,0.1

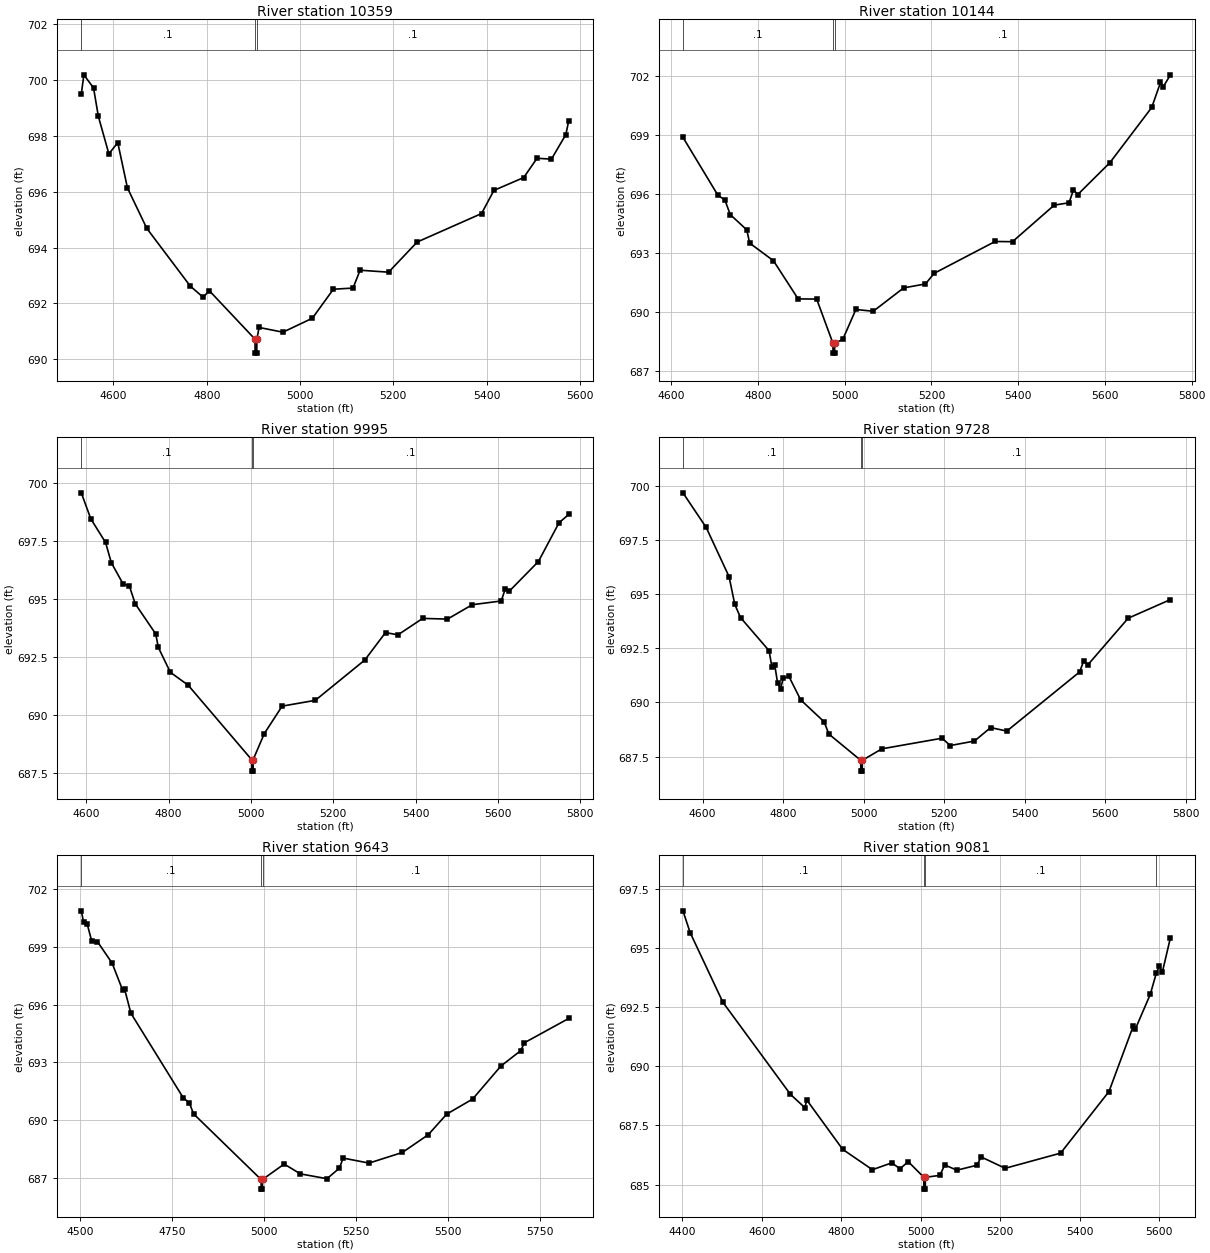
Type RM Length L Ch R = 1,10359,215,215,215
BEGIN DESCRIPTION:
Mapping XS db820e5e
END DESCRIPTION:
XS GIS Cut Line= 5
      1965650.30     13587974.88      1965431.58     13587914.13
      1965282.28     13587938.43      1965070.47     13588079.06
      1964668.82     13588172.55
#Sta/Elev= 30
  4531.1  699.49  4536.6  700.19  4557.4  699.72  4567.7  698.70  4590.2  697.36
  4609.3  697.76  4630.0  696.14  4671.5  694.69  4764.8  692.62  4792.4  692.22
  4805.3  692.46  4903.5  690.72  4903.7  690.22  4907.2  690.22  4907.5  690.72
  4912.2  691.14  4963.3  690.97  5026.4  691.47  5071.5  692.51  5113.6  692.55
  5128.7  693.19  5189.8  693.12  5251.1  694.20  5389.1  695.22  5415.6  696.05
  5479.5  696.51  5508.0  697.20  5538.9  697.17  5569.8  698.05  5576.0  698.55
#Mann=3,-1,0
  4531.1     0.1       0  4903.5    0.07       0  4907.5     0.1       0
Bank Sta=4903.5,4907.5
Exp/Cntr=0.3,0.1

Type RM Length L Ch R = 1,10144,149,149,149
BEGIN DESCRIPTION:
Mapping XS a7a83e45
END DESCRIPTION:
XS GIS Cut Line= 3
      1965662.50     13587945.39      1965402.07     13587815.17
      1964572.16     13587881.15
#Sta/Elev= 30
  4627.3  698.88  4707.4  695.95  4724.2  695.68  4736.3  694.95  4774.5  694.17
  4781.0  693.50  4836.0  692.60  4892.8  690.66  4935.6  690.65  4973.1  688.40
  4973.3  687.90  4976.8  687.90  4977.1  688.40  4995.8  688.60  5025.9  690.12
  5066.0  690.03  5136.2  691.22  5186.4  691.42  5206.4  691.96  5346.9  693.58
  5387.0  693.57  5483.2  695.43  5517.4  695.55  5527.5  696.21  5537.5  695.97
  5611.5  697.59  5708.0  700.40  5728.1  701.67  5734.8  701.46  5751.0  702.06
#Mann=3,-1,0
  4627.3     0.1       0  4973.1    0.07       0  4977.1     0.1       0
Bank Sta=4973.1,4977.1
Exp/Cntr=0.3,0.1

Type RM Length L Ch R = 1,9995,267,267,267
BEGIN DESCRIPTION:
Mapping XS 60666c17
END DESCRIPTION:
XS GIS Cut Line= 3
      1965691.80     13587941.40      1965264.73     13587613.28
      1964621.49     13587665.37
#Sta/Elev= 30
  4587.9  699.57  4611.0  698.45  4646.9  697.43  4660.8  696.56  4689.9  695.63
  4704.4  695.57  4718.9  694.79  4768.7  693.49  4775.0  692.91  4804.1  691.84
  4847.6  691.28  5001.4  688.08  5001.7  687.58  5005.2  687.58  5005.4  688.08
  5032.5  689.20  5075.7  690.38  5156.3  690.63  5276.7  692.37  5326.8  693.55
  5356.9  693.45  5417.1  694.16  5477.3  694.13  5537.5  694.75  5607.8  694.91
  5617.8  695.44  5627.8  695.34  5698.1  696.61  5748.2  698.28  5771.8  698.64
#Mann=3,-1,0
  4587.9     0.1       0  5001.4    0.07       0  5005.4     0.1       0
Bank Sta=5001.4,5005.4
Exp/Cntr=0.3,0.1

Type RM Length L Ch R = 1,9728,85,85,85
BEGIN DESCRIPTION:
Mapping XS f36fa36a
END DESCRIPTION:
XS GIS Cut Line= 4
      1965776.43     13587905.37      1965591.98     13587701.39
      1965537.73     13587349.83      1964960.51     13587401.91
#Sta/Elev= 30
  4551.4  699.68  4609.1  698.08  4665.9  695.81  4680.1  694.53  4694.3  693.92
  4765.3  692.39  4772.0  691.66  4779.5  691.71  4786.2  690.92  4793.7  690.63
  4800.4  691.12  4814.6  691.20  4843.7  690.12  4901.8  689.11  4913.8  688.54
  4992.8  687.33  4993.0  686.83  4996.5  686.83  4996.8  687.33  5045.4  687.86
  5194.9  688.35  5215.0  688.01  5275.2  688.22  5315.4  688.84  5355.6  688.68
  5536.3  691.41  5546.3  691.91  5556.4  691.73  5656.8  693.89  5761.7  694.75
#Mann=3,-1,0
  4551.4     0.1       0  4992.8    0.07       0  4996.8     0.1       0
Bank Sta=4992.8,4996.8
Exp/Cntr=0.3,0.1

Type RM Length L Ch R = 1,9643,562,562,562
BEGIN DESCRIPTION:
UNT 038 in BCW 13.0
END DESCRIPTION:
XS GIS Cut Line= 4
      1965828.54     13587920.60      1965631.04     13587506.08
      1965598.49     13587299.91      1964945.26     13587369.36
#Sta/Elev= 30
  4504.3  700.86  4510.5  700.28  4520.1  700.19  4532.7  699.29  4548.3  699.26
  4588.0  698.15  4616.4  696.76  4622.0  696.80  4639.1  695.55  4780.9  691.18
  4798.1  690.89  4809.6  690.33  4992.9  686.93  4993.2  686.43  4996.7  686.43
  4996.9  686.93  5055.7  687.73  5099.8  687.22  5172.1  686.97  5205.9  687.52
  5215.9  688.04  5286.3  687.78  5376.8  688.33  5447.2  689.25  5497.5  690.32
  5567.9  691.10  5644.6  692.81  5698.6  693.61  5708.7  694.02  5829.1  695.28
#Mann=3,-1,0
  4504.3     0.1       0  4992.9    0.07       0  4996.9     0.1       0
Bank Sta=4992.9,4996.9
Exp/Cntr=0.3,0.1

Type RM Length L Ch R = 1,9081,358,358,358
BEGIN DESCRIPTION:
UNT 038 in BCW 12.0
END DESCRIPTION:
XS GIS Cut Line= 3
      1965924.99     13587775.03      1966075.00     13587175.00
      1965974.99     13586574.97
#Sta/Elev= 30
  4401.2  696.56  4419.3  695.64  4501.7  692.70  4671.8  688.81  4707.9  688.25
  4713.0  688.57  4803.2  686.49  4878.0  685.63  4926.9  685.92  4947.5  685.67
  4968.2  685.97  5007.4  685.31  5007.6  684.81  5011.1  684.81  5011.4  685.31
  5047.6  685.39  5060.2  685.83  5090.7  685.61  5141.3  685.82  5151.5  686.17
  5212.3  685.69  5351.7  686.33  5473.4  688.93  5534.2  691.68  5539.3  691.55
  5577.3  693.03  5592.9  693.95  5600.1  694.22  5607.7  693.97  5628.0  695.42
#Mann=4,-1,0
  4401.2     0.1       0  5007.4    0.07       0  5011.4     0.1       0
  5592.9    0.05       0
Bank Sta=5007.4,5011.4
Exp/Cntr=0.3,0.1

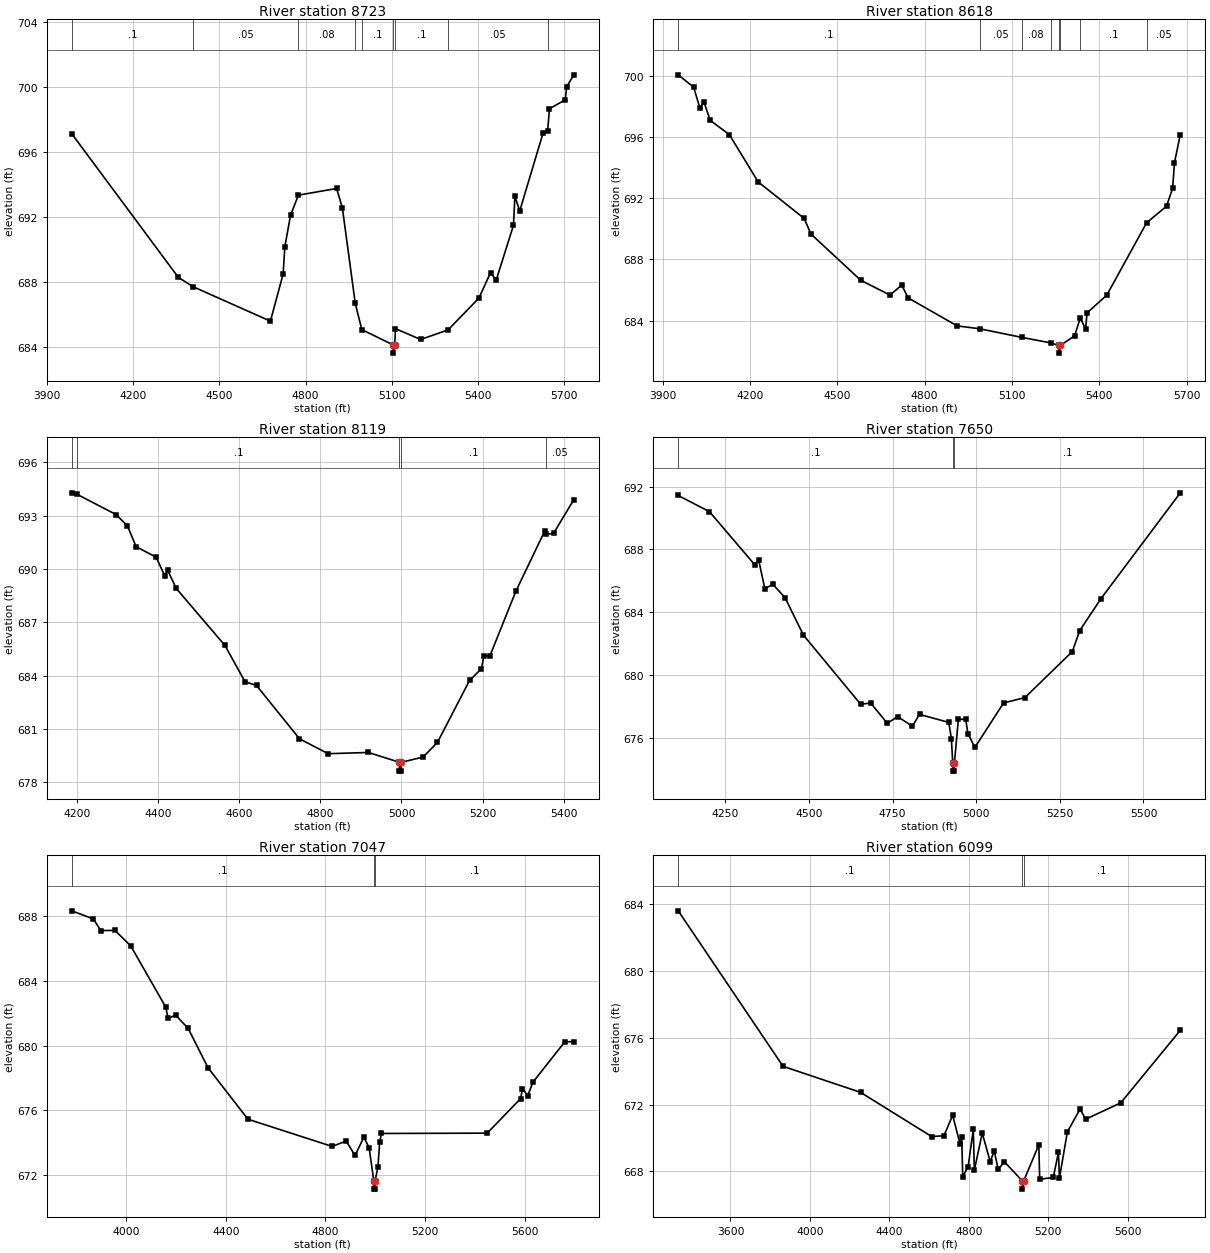
Type RM Length L Ch R = 1,8723,105,105,105
BEGIN DESCRIPTION:
UNT 038 in BCW 11.0
END DESCRIPTION:
XS GIS Cut Line= 3
      1966417.32     13588024.86      1966347.88     13586948.42
      1966235.14     13586289.37
#Sta/Elev= 30
  3986.1  697.14  4356.7  688.30  4408.3  687.72  4677.4  685.60  4721.8  688.51
  4727.5  690.17  4747.5  692.13  4774.8  693.36  4907.9  693.77  4927.9  692.57
  4972.7  686.69  4995.5  685.08  5105.2  684.13  5105.6  683.63  5110.0  684.13
  5112.7  685.14  5200.1  684.47  5295.5  685.06  5403.0  687.02  5443.6  688.59
  5463.1  688.12  5523.2  691.50  5528.3  693.28  5545.1  692.39  5626.2  697.18
  5642.2  697.31  5648.4  698.68  5703.5  699.23  5708.5  700.04  5733.4  700.77
#Mann=9,-1,0
  3986.1     0.1       0  4408.3    0.05       0  4774.8    0.08       0
  4972.7    0.05       0  4995.5     0.1       0  5105.2    0.07       0
  5110.0     0.1       0  5295.5    0.05       0  5642.2     0.1       0
Bank Sta=5105.2,5110
Exp/Cntr=0.3,0.1

Type RM Length L Ch R = 1,8618,499,499,499
BEGIN DESCRIPTION:
Mapping XS d49550f9
END DESCRIPTION:
XS GIS Cut Line= 4
      1966690.74     13587972.69      1966538.85     13587751.38
      1966386.94     13586423.25      1966288.52     13586354.78
#Sta/Elev= 30
  3953.4  700.06  4006.4  699.25  4027.4  697.91  4042.3  698.26  4063.3  697.08
  4128.9  696.16  4228.2  693.06  4386.0  690.68  4409.4  689.66  4580.5  686.64
  4681.2  685.67  4721.4  686.33  4743.1  685.49  4911.7  683.66  4989.4  683.47
  5133.3  682.91  5232.9  682.55  5261.4  682.38  5261.8  681.88  5266.2  682.38
  5315.3  683.01  5334.8  684.17  5353.1  683.47  5358.1  684.51  5426.0  685.67
  5562.5  690.39  5631.2  691.48  5652.1  692.65  5658.4  694.32  5678.5  696.16
#Mann=8,-1,0
  3953.4     0.1       0  4989.4    0.05       0  5133.3    0.08       0
  5232.9    0.05       0  5261.4    0.04       0  5266.2    0.05       0
  5334.8     0.1       0  5562.5    0.05       0
Bank Sta=5261.4,5266.2
Exp/Cntr=0.3,0.1

Type RM Length L Ch R = 1,8119,469,469,469
BEGIN DESCRIPTION:
UNT 038 in BCW 10.0
END DESCRIPTION:
XS GIS Cut Line= 3
      1967241.98     13587152.42      1966725.00     13586625.00
      1966325.03     13586325.02
#Sta/Elev= 30
  4186.7  694.29  4200.2  694.20  4295.8  693.07  4324.1  692.43  4345.4  691.26
  4394.8  690.67  4416.1  689.62  4423.1  689.94  4444.4  688.91  4564.6  685.70
  4614.1  683.66  4642.4  683.45  4748.4  680.45  4819.2  679.61  4918.2  679.68
  4994.7  679.13  4995.0  678.63  4999.2  678.63  4999.6  679.13  5053.4  679.42
  5088.8  680.25  5167.9  683.73  5197.1  684.39  5203.4  685.12  5217.9  685.10
  5282.5  688.77  5353.4  692.14  5356.9  691.95  5375.2  692.01  5425.2  693.91
#Mann=5,-1,0
  4186.7    0.05       0  4200.2     0.1       0  4994.7    0.07       0
  4999.6     0.1       0  5356.9    0.05       0
Bank Sta=4994.7,4999.6
Exp/Cntr=0.3,0.1

Type RM Length L Ch R = 1,7650,603,603,603
BEGIN DESCRIPTION:
UNT 038 in BCW 9.0
END DESCRIPTION:
XS GIS Cut Line= 3
      1967341.81     13587069.97      1967085.72     13586388.53
      1966495.82     13585889.71
#Sta/Elev= 30
  4109.6  691.43  4202.9  690.40  4338.0  687.03  4349.9  687.33  4368.3  685.51
  4392.7  685.77  4428.7  684.93  4483.9  682.54  4654.6  678.15  4684.9  678.22
  4734.5  676.93  4764.9  677.36  4809.3  676.75  4830.7  677.50  4918.2  676.99
  4925.9  675.96  4930.0  674.39  4930.4  673.89  4934.6  673.89  4934.9  674.39
  4946.8  677.19  4968.8  677.19  4975.3  676.27  4996.2  675.40  5081.9  678.23
  5145.7  678.57  5287.4  681.50  5309.4  682.83  5373.1  684.87  5610.1  691.60
#Mann=3,-1,0
  4109.6     0.1       0  4930.0    0.07       0  4934.9     0.1       0
Bank Sta=4930,4934.9
Exp/Cntr=0.3,0.1

Type RM Length L Ch R = 1,7047,948,948,948
BEGIN DESCRIPTION:
UNT 038 in BCW 8.0
END DESCRIPTION:
XS GIS Cut Line= 3
      1967524.09     13587191.51      1967558.82     13586162.83
      1966851.38     13585477.10
#Sta/Elev= 30
  3782.4  688.33  3869.0  687.83  3899.0  687.11  3955.8  687.12  4019.0  686.16
  4159.1  682.39  4169.1  681.69  4199.2  681.88  4249.1  681.07  4329.2  678.63
  4489.3  675.45  4827.0  673.77  4883.6  674.10  4918.9  673.21  4954.3  674.34
  4975.5  673.69  4994.3  671.63  4994.7  671.13  4998.9  671.13  4999.2  671.63
  5010.9  672.49  5017.9  674.06  5025.1  674.57  5449.3  674.59  5583.6  676.73
  5590.8  677.34  5611.9  676.91  5633.2  677.75  5760.5  680.23  5796.9  680.25
#Mann=3,-1,0
  3782.4     0.1       0  4994.3    0.07       0  4999.2     0.1       0
Bank Sta=4994.3,4999.2
Exp/Cntr=0.3,0.1

Type RM Length L Ch R = 1,6099,46,46,46
BEGIN DESCRIPTION:
Mapping XS 02ecefe6
END DESCRIPTION:
XS GIS Cut Line= 6
      1967677.19     13587051.83      1967979.26     13585661.25
      1968210.16     13585607.43      1968133.77     13585581.39
      1967906.34     13585619.59      1968019.19     13585091.79
#Sta/Elev= 30
  3337.3  683.62  3864.9  674.30  4255.0  672.74  4613.2  670.09  4674.7  670.14
  4718.7  671.37  4755.8  669.64  4764.2  670.05  4769.3  667.69  4796.6  668.29
  4822.6  670.53  4827.7  668.07  4867.6  670.30  4907.7  668.58  4927.7  669.24
  4947.9  668.12  4978.7  668.58  5068.7  667.44  5069.2  666.94  5076.3  667.44
  5152.3  669.59  5156.7  667.53  5225.1  667.64  5251.0  669.14  5256.1  667.60
  5295.9  670.37  5360.1  671.74  5387.9  671.13  5564.7  672.11  5864.5  676.46
#Mann=3,-1,0
  3337.3     0.1       0  5068.7    0.07       0  5076.3     0.1       0
Bank Sta=5068.7,5076.3
Exp/Cntr=0.3,0.1

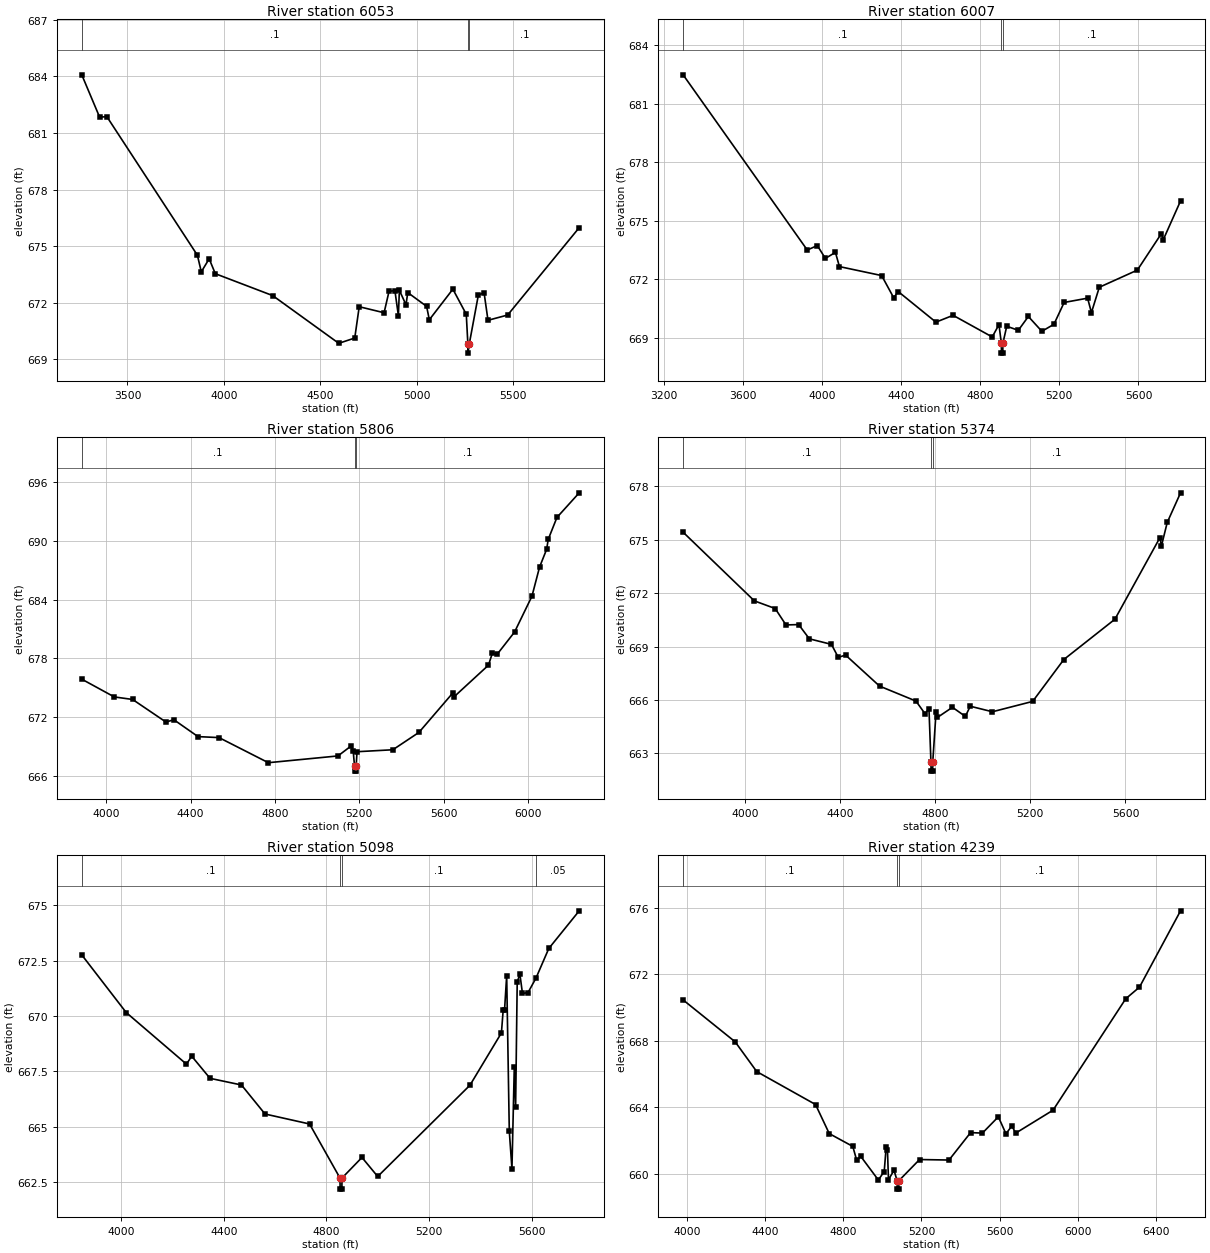
Type RM Length L Ch R = 1,6053,46,46,46
BEGIN DESCRIPTION:
Mapping XS a840dd78
END DESCRIPTION:
XS GIS Cut Line= 6
      1967711.91     13587112.61      1968005.30     13585678.61
      1968253.57     13585636.95      1968203.22     13585555.35
      1967951.48     13585570.98      1968052.17     13585081.43
#Sta/Elev= 30
  3263.1  684.08  3355.5  681.84  3393.4  681.86  3862.9  674.52  3883.3  673.64
  3924.1  674.33  3955.9  673.54  4253.6  672.38  4596.6  669.85  4679.5  670.13
  4702.7  671.79  4831.7  671.47  4857.5  672.61  4887.9  672.64  4905.9  671.32
  4911.1  672.66  4945.5  671.89  4954.5  672.54  5052.3  671.81  5066.5  671.10
  5188.7  672.72  5258.2  671.39  5266.4  669.83  5266.9  669.33  5274.0  669.83
  5320.7  672.40  5350.5  672.54  5370.9  671.07  5473.0  671.35  5844.2  675.98
#Mann=3,-1,0
  3263.1     0.1       0  5266.4    0.07       0  5274.0     0.1       0
Bank Sta=5266.4,5274
Exp/Cntr=0.3,0.1

Type RM Length L Ch R = 1,6007,201,201,201
BEGIN DESCRIPTION:
Mapping XS 56b18764
END DESCRIPTION:
XS GIS Cut Line= 6
      1967777.01     13587112.61      1968024.40     13585744.59
      1968298.70     13585656.04      1968244.89     13585532.78
      1968007.04     13585532.78      1968076.35     13585089.19
#Sta/Elev= 30
  3297.9  682.48  3925.5  673.49  3976.3  673.72  4017.0  673.06  4067.8  673.37
  4088.1  672.64  4301.5  672.18  4362.5  671.04  4385.2  671.36  4575.9  669.79
  4662.8  670.14  4860.5  669.03  4894.6  669.66  4906.8  668.70  4907.3  668.20
  4913.9  668.20  4914.4  668.70  4933.9  669.58  4992.4  669.37  5043.2  670.08
  5111.5  669.32  5172.5  669.68  5224.1  670.80  5342.7  671.02  5362.1  670.28
  5401.9  671.58  5594.2  672.46  5715.6  674.33  5725.7  674.03  5812.6  676.01
#Mann=3,-1,0
  3297.9     0.1       0  4906.8    0.07       0  4914.4     0.1       0
Bank Sta=4906.8,4914.4
Exp/Cntr=0.3,0.1

Type RM Length L Ch R = 1,5806,432,432,432
BEGIN DESCRIPTION:
UNT 038 in BCW 7.0
END DESCRIPTION:
XS GIS Cut Line= 3
      1968032.76     13586756.61      1968475.00     13585725.00
      1968774.99     13584525.04
#Sta/Elev= 30
  3883.8  675.89  4037.9  674.08  4124.9  673.82  4282.8  671.52  4320.8  671.75
  4435.1  670.03  4534.8  669.93  4768.7  667.37  5099.0  668.06  5160.8  669.07
  5171.1  668.55  5177.6  667.01  5178.1  666.51  5184.7  666.51  5185.2  667.01
  5189.2  668.49  5359.3  668.69  5482.9  670.46  5642.7  674.46  5647.9  674.06
  5812.8  677.32  5830.8  678.52  5854.0  678.43  5936.5  680.70  6018.9  684.35
  6055.0  687.32  6088.5  689.13  6096.3  690.16  6137.5  692.39  6243.1  694.90
#Mann=3,-1,0
  3883.8     0.1       0  5177.6    0.07       0  5185.2     0.1       0
Bank Sta=5177.6,5185.2
Exp/Cntr=0.3,0.1

Type RM Length L Ch R = 1,5374,276,276,276
BEGIN DESCRIPTION:
UNT 038 in BCW 6.0
END DESCRIPTION:
XS GIS Cut Line= 3
      1968345.29     13587048.20      1968825.00     13585975.00
      1969060.26     13585091.01
#Sta/Elev= 30
  3741.2  675.41  4040.5  671.56  4128.1  671.13  4173.3  670.21  4226.7  670.23
  4271.7  669.43  4364.5  669.12  4393.2  668.39  4423.8  668.52  4566.6  666.78
  4719.6  665.94  4757.7  665.23  4774.3  665.51  4782.6  662.51  4783.1  662.01
  4789.7  662.01  4790.2  662.51  4804.1  665.34  4809.6  665.02  4872.9  665.59
  4927.1  665.08  4947.8  665.65  5040.9  665.34  5210.0  665.92  5341.0  668.27
  5555.7  670.53  5744.6  675.10  5751.2  674.64  5775.6  675.96  5831.5  677.62
#Mann=3,-1,0
  3741.2     0.1       0  4782.6    0.07       0  4790.2     0.1       0
Bank Sta=4782.6,4790.2
Exp/Cntr=0.3,0.1

Type RM Length L Ch R = 1,5098,859,859,859
BEGIN DESCRIPTION:
UNT 038 in BCW 5.0
END DESCRIPTION:
XS GIS Cut Line= 3
      1968852.22     13587124.63      1969075.00     13586025.00
      1969254.85     13585229.44
#Sta/Elev= 30
  3846.8  672.76  4019.9  670.16  4254.5  667.83  4275.0  668.19  4346.4  667.19
  4468.8  666.89  4560.6  665.58  4734.1  665.13  4852.6  662.69  4853.1  662.19
  4859.9  662.19  4860.4  662.69  4938.2  663.62  4999.5  662.76  5358.9  666.88
  5481.4  669.24  5488.4  670.29  5493.5  670.26  5501.9  671.83  5512.1  664.80
  5522.4  663.11  5531.6  667.72  5536.7  665.91  5542.9  671.52  5553.2  671.91
  5563.4  671.02  5585.0  671.06  5616.3  671.72  5665.9  673.05  5784.4  674.75
#Mann=4,-1,0
  3846.8     0.1       0  4852.6    0.07       0  4860.4     0.1       0
  5616.3    0.05       0
Bank Sta=4852.6,4860.4
Exp/Cntr=0.3,0.1

Type RM Length L Ch R = 1,4239,224,224,224
BEGIN DESCRIPTION:
UNT 038 in BCW 4.0
END DESCRIPTION:
XS GIS Cut Line= 3
      1969643.88     13587520.52      1969699.44     13586694.08
      1969546.67     13584985.80
#Sta/Elev= 30
  3981.4  670.45  4247.5  667.93  4357.8  666.14  4658.4  664.16  4728.6  662.41
  4848.9  661.64  4869.0  660.80  4889.1  661.05  4979.5  659.62  5009.6  660.13
  5019.6  661.60  5026.3  661.40  5031.3  659.64  5059.8  660.20  5075.8  659.57
  5076.3  659.07  5083.5  659.07  5084.0  659.57  5190.3  660.85  5340.9  660.82
  5451.3  662.47  5511.6  662.44  5593.1  663.42  5632.1  662.40  5662.2  662.87
  5682.2  662.44  5873.0  663.82  6244.5  670.52  6314.8  671.22  6524.8  675.81
#Mann=3,-1,0
  3981.4     0.1       0  5075.8    0.07       0  5084.0     0.1       0
Bank Sta=5075.8,5084
Exp/Cntr=0.3,0.1

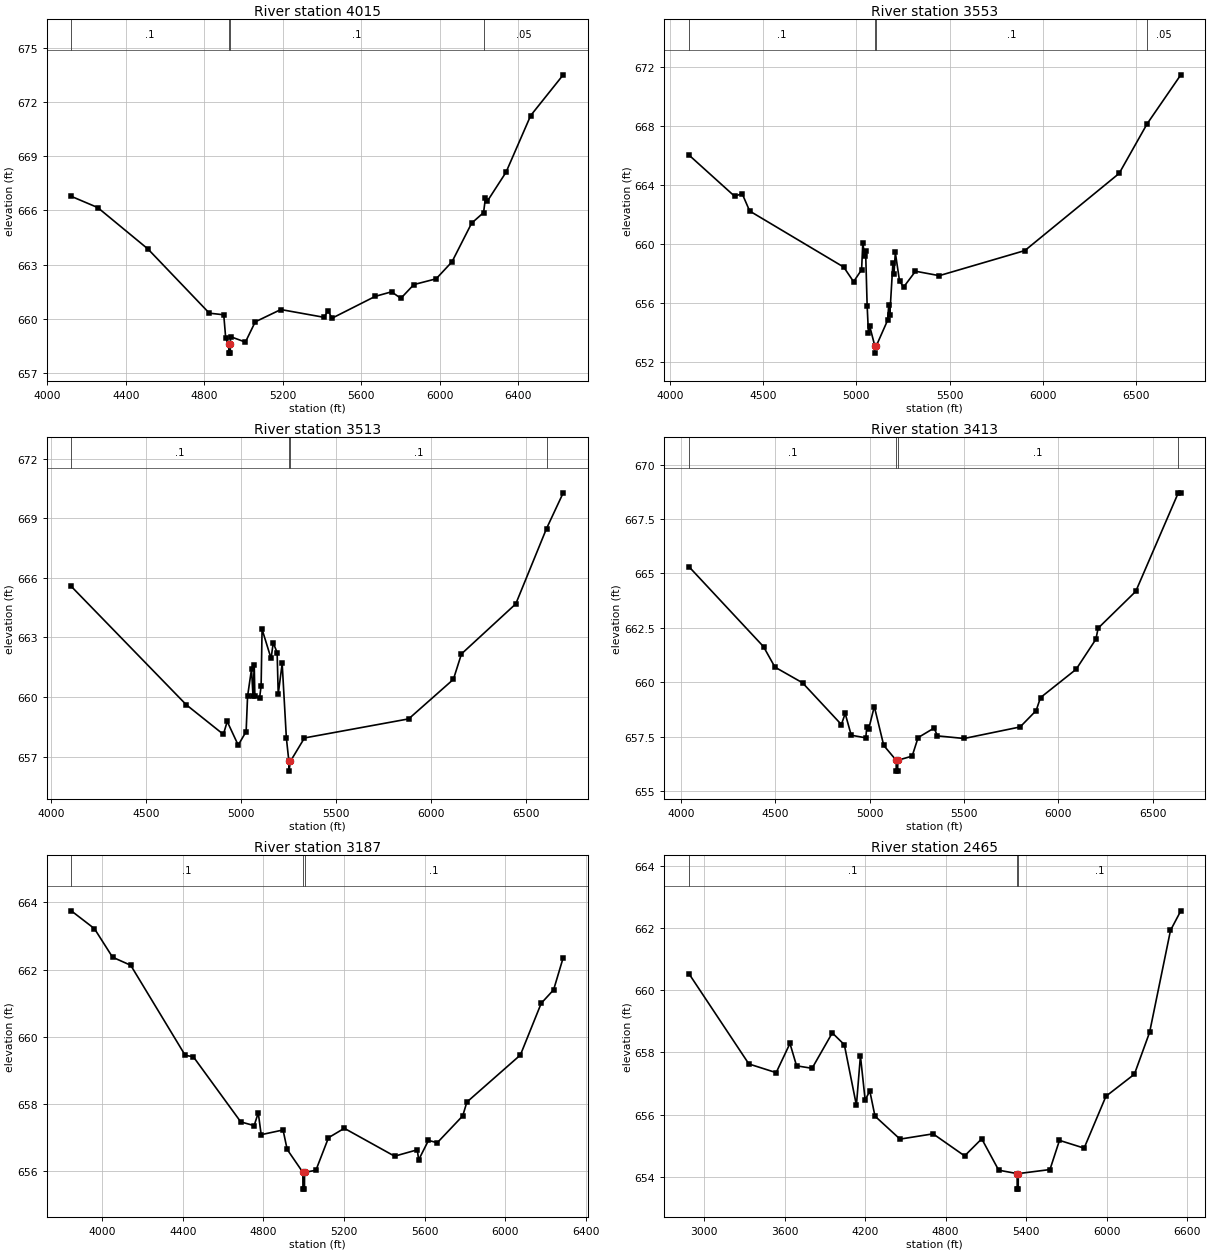
Type RM Length L Ch R = 1,4015,462,462,462
BEGIN DESCRIPTION:
UNT 038 in BCW 3.0
END DESCRIPTION:
XS GIS Cut Line= 3
      1969977.21     13587409.31      1969900.83     13586610.75
      1969755.02     13584909.70
#Sta/Elev= 30
  4121.3  666.78  4256.2  666.16  4512.3  663.87  4825.5  660.32  4899.1  660.23
  4909.2  658.93  4924.6  658.61  4925.1  658.11  4932.4  658.11  4932.9  658.61
  4933.8  659.02  5009.6  658.72  5059.8  659.84  5190.2  660.52  5411.0  660.09
  5431.1  660.46  5451.2  660.04  5672.0  661.25  5755.1  661.50  5802.5  661.14
  5868.8  661.90  5982.6  662.22  6063.4  663.16  6163.8  665.30  6224.4  665.88
  6234.0  666.69  6244.1  666.52  6338.9  668.11  6464.9  671.25  6630.8  673.50
#Mann=4,-1,0
  4121.3     0.1       0  4924.6    0.07       0  4932.9     0.1       0
  6224.4    0.05       0
Bank Sta=4924.6,4932.9
Exp/Cntr=0.3,0.1

Type RM Length L Ch R = 1,3553,40,40,40
BEGIN DESCRIPTION:
Mapping XS ae5222c8
END DESCRIPTION:
XS GIS Cut Line= 6
      1970222.89     13587418.20      1970329.65     13586579.70
      1970410.38     13586436.48      1970415.59     13586384.39
      1970381.74     13586316.68      1969866.11     13584910.44
#Sta/Elev= 30
  4102.3  666.03  4347.5  663.23  4387.8  663.41  4428.1  662.23  4932.1  658.43
  4984.8  657.44  5027.7  658.25  5034.3  660.09  5043.4  659.18  5049.2  659.52
  5057.5  655.80  5064.4  653.98  5070.5  654.46  5098.3  653.10  5098.8  652.60
  5106.8  653.10  5166.9  654.82  5173.1  655.84  5178.7  655.16  5195.5  658.71
  5201.1  657.94  5208.4  659.42  5230.8  657.50  5252.5  657.07  5316.5  658.15
  5443.7  657.85  5902.3  659.55  6407.6  664.78  6557.4  668.14  6737.9  671.46
#Mann=4,-1,0
  4102.3     0.1       0  5098.3    0.07       0  5106.8     0.1       0
  6557.4    0.05       0
Bank Sta=5098.3,5106.8
Exp/Cntr=0.3,0.1

Type RM Length L Ch R = 1,3513,100,100,100
BEGIN DESCRIPTION:
Mapping XS 508ba3ad
END DESCRIPTION:
XS GIS Cut Line= 6
      1970280.17     13587413.08      1970363.51     13586571.89
      1970444.24     13586478.14      1970454.65     13586415.64
      1970446.84     13586368.77      1969928.85     13584949.29
#Sta/Elev= 30
  4105.4  665.57  4711.8  659.61  4907.4  658.12  4927.5  658.77  4985.4  657.58
  5027.2  658.26  5034.8  660.04  5055.7  661.41  5063.4  660.05  5070.0  661.61
  5073.2  660.05  5097.9  659.93  5106.2  660.56  5111.3  663.41  5158.7  661.94
  5170.0  662.73  5190.6  662.24  5196.4  660.14  5217.2  661.69  5239.3  657.94
  5252.5  656.77  5253.0  656.27  5261.0  656.77  5334.7  657.94  5884.1  658.90
  6119.8  660.89  6162.3  662.17  6448.7  664.69  6610.7  668.48  6698.8  670.28
#Mann=4,-1,0
  4105.4     0.1       0  5252.5    0.07       0  5261.0     0.1       0
  6610.7    0.05       0
Bank Sta=5252.5,5261
Exp/Cntr=0.3,0.1

Type RM Length L Ch R = 1,3413,226,226,226
BEGIN DESCRIPTION:
Mapping XS ab3bf4a7
END DESCRIPTION:
XS GIS Cut Line= 6
      1970311.42     13587418.25      1970407.78     13586577.10
      1970485.90     13586530.23      1970483.99     13586378.14
      1970472.88     13586277.62      1970001.54     13584941.73
#Sta/Elev= 30
  4041.7  665.31  4437.5  661.63  4497.9  660.69  4644.1  659.97  4850.2  658.05
  4870.3  658.56  4902.4  657.56  4979.5  657.44  4984.7  657.92  4994.7  657.84
  5024.7  658.88  5074.7  657.09  5140.5  656.41  5141.0  655.91  5148.5  655.91
  5149.0  656.41  5225.3  656.60  5256.7  657.45  5341.5  657.89  5359.5  657.53
  5500.6  657.41  5797.5  657.94  5882.3  658.69  5905.7  659.29  6094.4  660.59
  6199.1  661.97  6211.1  662.48  6410.4  664.17  6634.4  668.67  6649.3  668.70
#Mann=4,-1,0
  4041.7     0.1       0  5140.5    0.07       0  5149.0     0.1       0
  6634.4    0.05       0
Bank Sta=5140.5,5149
Exp/Cntr=0.3,0.1

Type RM Length L Ch R = 1,3187,722,722,722
BEGIN DESCRIPTION:
UNT 038 in BCW 2.0
END DESCRIPTION:
XS GIS Cut Line= 3
      1970706.39     13587499.68      1970671.66     13586659.36
      1970324.80     13585098.48
#Sta/Elev= 30
  3846.7  663.75  3961.5  663.22  4051.6  662.37  4141.6  662.13  4411.9  659.45
  4451.9  659.41  4687.4  657.47  4753.7  657.36  4774.2  657.74  4788.6  657.09
  4897.1  657.23  4917.6  656.65  4995.3  655.97  4995.8  655.47  5003.3  655.47
  5003.8  655.97  5060.0  656.03  5122.5  657.00  5200.9  657.28  5450.3  656.45
  5562.9  656.64  5569.7  656.34  5618.3  656.92  5661.9  656.85  5788.3  657.65
  5808.8  658.06  6074.2  659.46  6177.6  661.00  6239.0  661.40  6286.7  662.36
#Mann=3,-1,0
  3846.7     0.1       0  4995.3    0.07       0  5003.8     0.1       0
Bank Sta=4995.3,5003.8
Exp/Cntr=0.3,0.1

Type RM Length L Ch R = 1,2465,395,395,395
BEGIN DESCRIPTION:
Mapping XS c9207f57
END DESCRIPTION:
XS GIS Cut Line= 6
      1972000.82     13588029.56      1971875.84     13587612.93
      1971341.11     13587279.60      1971313.34     13586647.66
      1971223.06     13586050.43      1970313.49     13585029.82
#Sta/Elev= 30
  2884.5  660.54  3332.2  657.63  3535.7  657.35  3638.6  658.29  3687.9  657.57
  3803.6  657.49  3954.4  658.63  4044.2  658.25  4134.3  656.30  4164.3  657.89
  4199.5  656.47  4234.3  656.76  4272.8  655.95  4459.7  655.21  4706.2  655.38
  4941.5  654.67  5069.1  655.22  5195.5  654.21  5333.1  654.10  5333.6  653.60
  5341.2  653.60  5341.7  654.10  5578.0  654.23  5649.0  655.17  5832.8  654.92
  5995.7  656.59  6207.9  657.30  6321.4  658.65  6477.1  661.93  6554.1  662.56
#Mann=3,-1,0
  2884.5     0.1       0  5333.1    0.07       0  5341.7     0.1       0
Bank Sta=5333.1,5341.7
Exp/Cntr=0.3,0.1

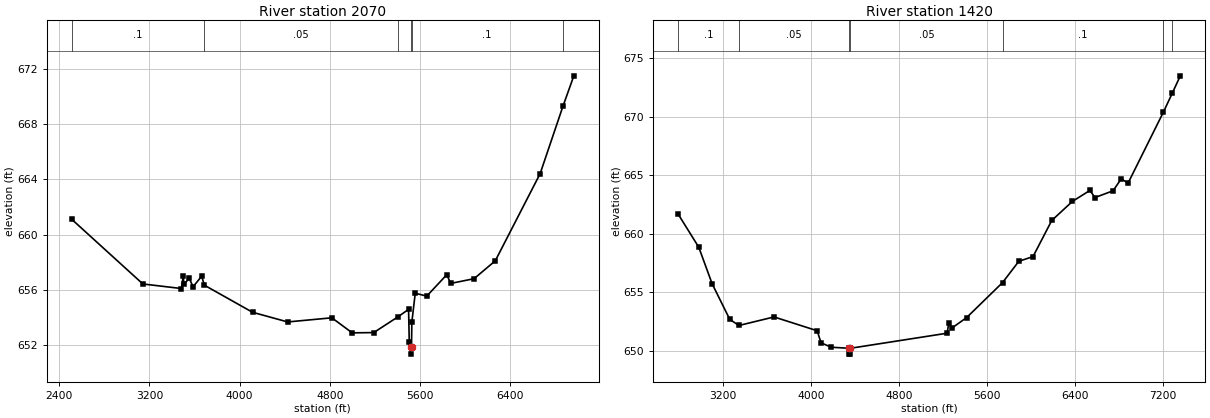
Type RM Length L Ch R = 1,2070,650,650,650
BEGIN DESCRIPTION:
UNT 038 in BCW 1.0
END DESCRIPTION:
XS GIS Cut Line= 6
      1972042.50     13588099.08      1972021.67     13587467.10
      1971549.45     13587258.77      1971493.89     13586710.16
      1971375.84     13585571.27      1969974.99     13584775.00
#Sta/Elev= 30
  2510.3  661.10  3141.2  656.42  3482.8  656.09  3499.7  656.98  3506.1  656.39
  3552.7  656.83  3587.1  656.22  3663.2  656.98  3687.4  656.33  4114.8  654.37
  4426.5  653.67  4818.6  653.97  4999.5  652.88  5190.6  652.90  5401.6  654.02
  5499.6  654.58  5505.7  652.25  5517.0  651.84  5517.5  651.34  5525.6  651.84
  5528.7  653.66  5558.8  655.75  5661.1  655.54  5838.4  657.09  5873.7  656.46
  6080.6  656.80  6269.5  658.10  6667.4  664.41  6869.5  669.28  6966.5  671.49
#Mann=6,-1,0
  2510.3     0.1       0  3687.4    0.05       0  5401.6     0.1       0
  5517.0   0.035       0  5525.6     0.1       0  6869.5    0.05       0
Bank Sta=5517,5525.6
Exp/Cntr=0.3,0.1

Type RM Length L Ch R = 1,1420,0,0,0
BEGIN DESCRIPTION:
UNT 038 in BCW 500.0
END DESCRIPTION:
XS GIS Cut Line= 4
      1972605.01     13587640.68      1972730.00     13586564.32
      1971396.67     13585071.27      1970056.42     13584439.34
#Sta/Elev= 30
  2790.5  661.66  2977.4  658.84  3098.6  655.72  3259.3  652.67  3342.8  652.15
  3662.0  652.88  4054.2  651.70  4089.3  650.67  4181.6  650.29  4347.3  650.20
  4347.8  649.70  4355.8  649.70  4356.3  650.20  5237.1  651.49  5251.4  652.38
  5279.8  651.93  5414.4  652.83  5740.7  655.82  5888.7  657.64  6017.7  658.04
  6188.2  661.13  6376.0  662.76  6535.4  663.70  6581.0  663.09  6746.0  663.67
  6819.9  664.69  6882.7  664.33  7204.4  670.41  7284.1  672.01  7357.6  673.50
#Mann=7,-1,0
  2790.5     0.1       0  3342.8    0.05       0  4347.3   0.035       0
  4356.3    0.05       0  5740.7     0.1       0  7204.4    0.05       0
  7284.1     0.1       0
Bank Sta=4347.3,4356.3
Exp/Cntr=0.3,0.1

Chan Stop Cuts=-1