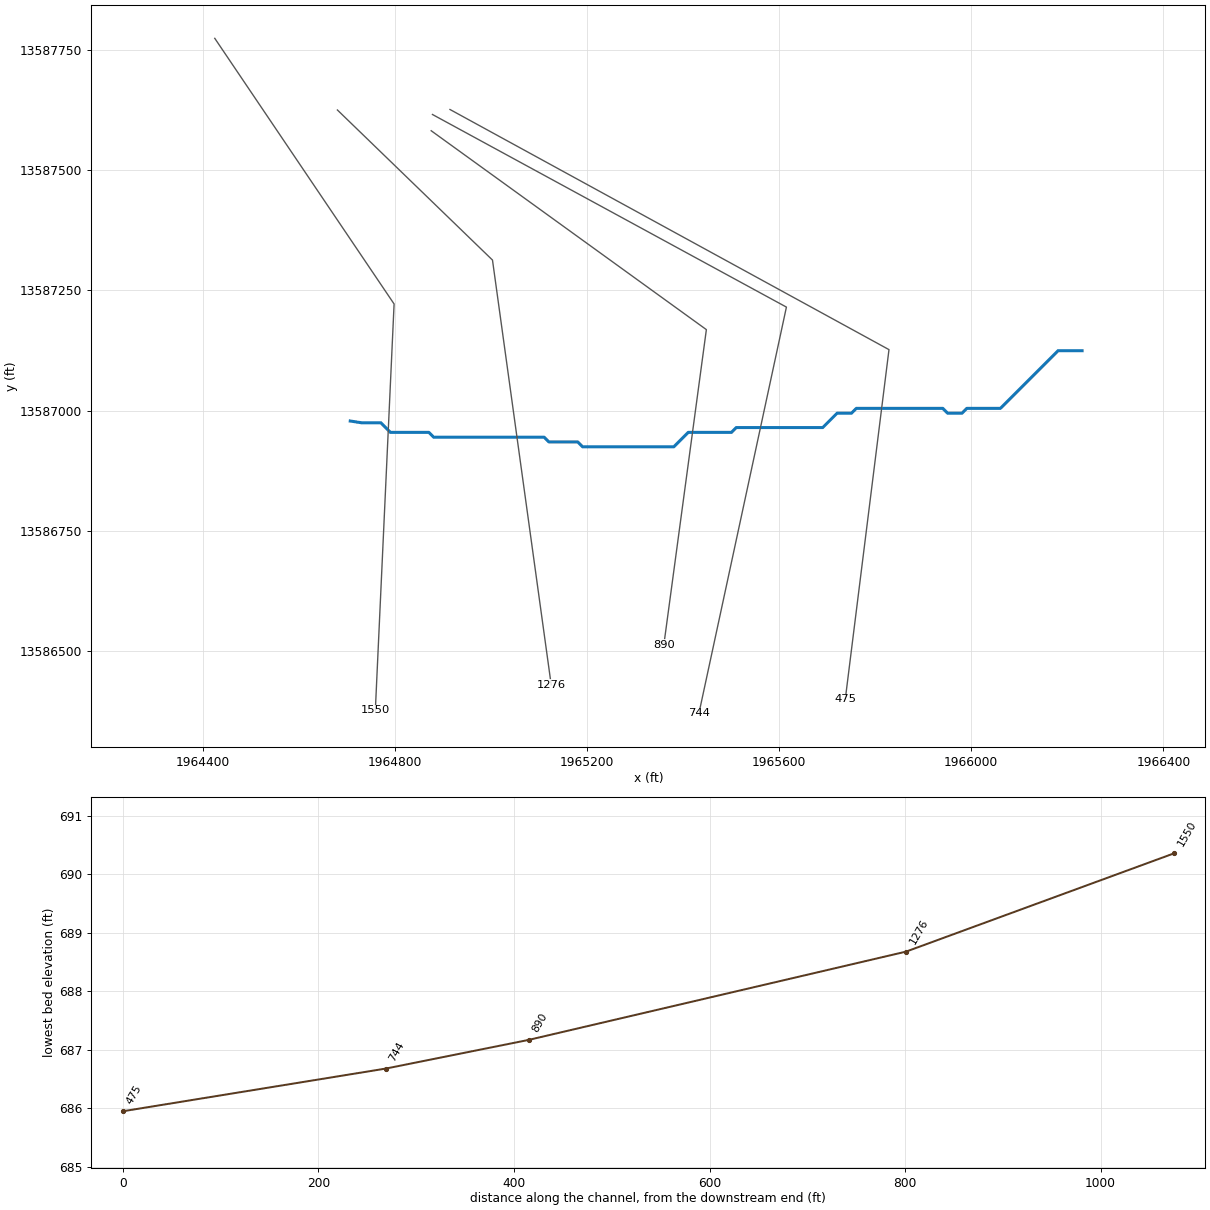
--- UNT 039 in BCW.prj (project) ---

Proj Title=UNT 039 in BCW Base Level Engineering
Current Plan=p01
Default Exp/Contr=0.3,0.1
English Units
Geom File=g01
Flow File=f01
Plan File=p01
BEGIN DESCRIPTION:
UNT 039 in BCW
END DESCRIPTION:

--- UNT 039 in BCW.p01 (plan) ---

Plan Title=Multiple Run
Short Identifier=Multiple
Geom File=g01
Flow File=f01
Subcritical Flow
K Sum by GR= 0
Std Step Tol= 0.01
Critical Tol= 0.01
Num of Std Step Trials= 20
Max Error Tol= 0.3
Flow Tol Ratio= 0.001
Split Flow NTrial= 30
Split Flow Tol= 0.02
Split Flow Ratio= 0.02
Log Output Level= 0
Friction Slope Method= 1
Unsteady Friction Slope Method= 2
Unsteady Bridges Friction Slope Method= 1
Parabolic Critical Depth
Global Vel Dist=  1 , 1 , 1
Global Log Level= 0
CheckData=True
Encroach Param= -1, 0, 0, 0
BEGIN DESCRIPTION:
Multiple Run
END DESCRIPTION:

--- UNT 039 in BCW.f01 (steady flow) ---

Flow Title=Multiple
Number of Profiles=7
Profile Names=10-year,25-year,50-year,1pct_min,100-year,1pct_plu,500-year
River Rch & RM= UNT 039 in BCW,Reach-1,1550
     602     849    1055     649    1294    2582    1949
Boundary for River Rch & Prof#=UNT 039 in BCW,Reach-1,1
Up Type=0
Dn Type=3
Dn Slope=0.005
Boundary for River Rch & Prof#=UNT 039 in BCW,Reach-1,2
Up Type=0
Dn Type=3
Dn Slope=0.005
Boundary for River Rch & Prof#=UNT 039 in BCW,Reach-1,3
Up Type=0
Dn Type=3
Dn Slope=0.005
Boundary for River Rch & Prof#=UNT 039 in BCW,Reach-1,4
Up Type=0
Dn Type=3
Dn Slope=0.005
Boundary for River Rch & Prof#=UNT 039 in BCW,Reach-1,5
Up Type=0
Dn Type=3
Dn Slope=0.005
Boundary for River Rch & Prof#=UNT 039 in BCW,Reach-1,6
Up Type=0
Dn Type=3
Dn Slope=0.005
Boundary for River Rch & Prof#=UNT 039 in BCW,Reach-1,7
Up Type=0
Dn Type=3
Dn Slope=0.005

--- UNT 039 in BCW.g01 (geometry) ---

Geom Title=Existing Conditions

River Reach=UNT 039 in BCW,Reach-1
Reach XY= 25
      1964707.03     13586978.21      1964730.80     13586974.54
      1964770.80     13586974.54      1964790.80     13586954.54
      1964870.80     13586954.54      1964880.80     13586944.54
      1965110.80     13586944.54      1965120.80     13586934.54
      1965180.80     13586934.54      1965190.80     13586924.54
      1965380.80     13586924.54      1965410.80     13586954.54
      1965500.80     13586954.54      1965510.80     13586964.54
      1965690.80     13586964.54      1965720.80     13586994.54
      1965750.80     13586994.54      1965760.80     13587004.54
      1965940.80     13587004.54      1965950.80     13586994.54
      1965980.80     13586994.54      1965990.80     13587004.54
      1966060.80     13587004.54      1966180.80     13587124.54
      1966230.80     13587124.54

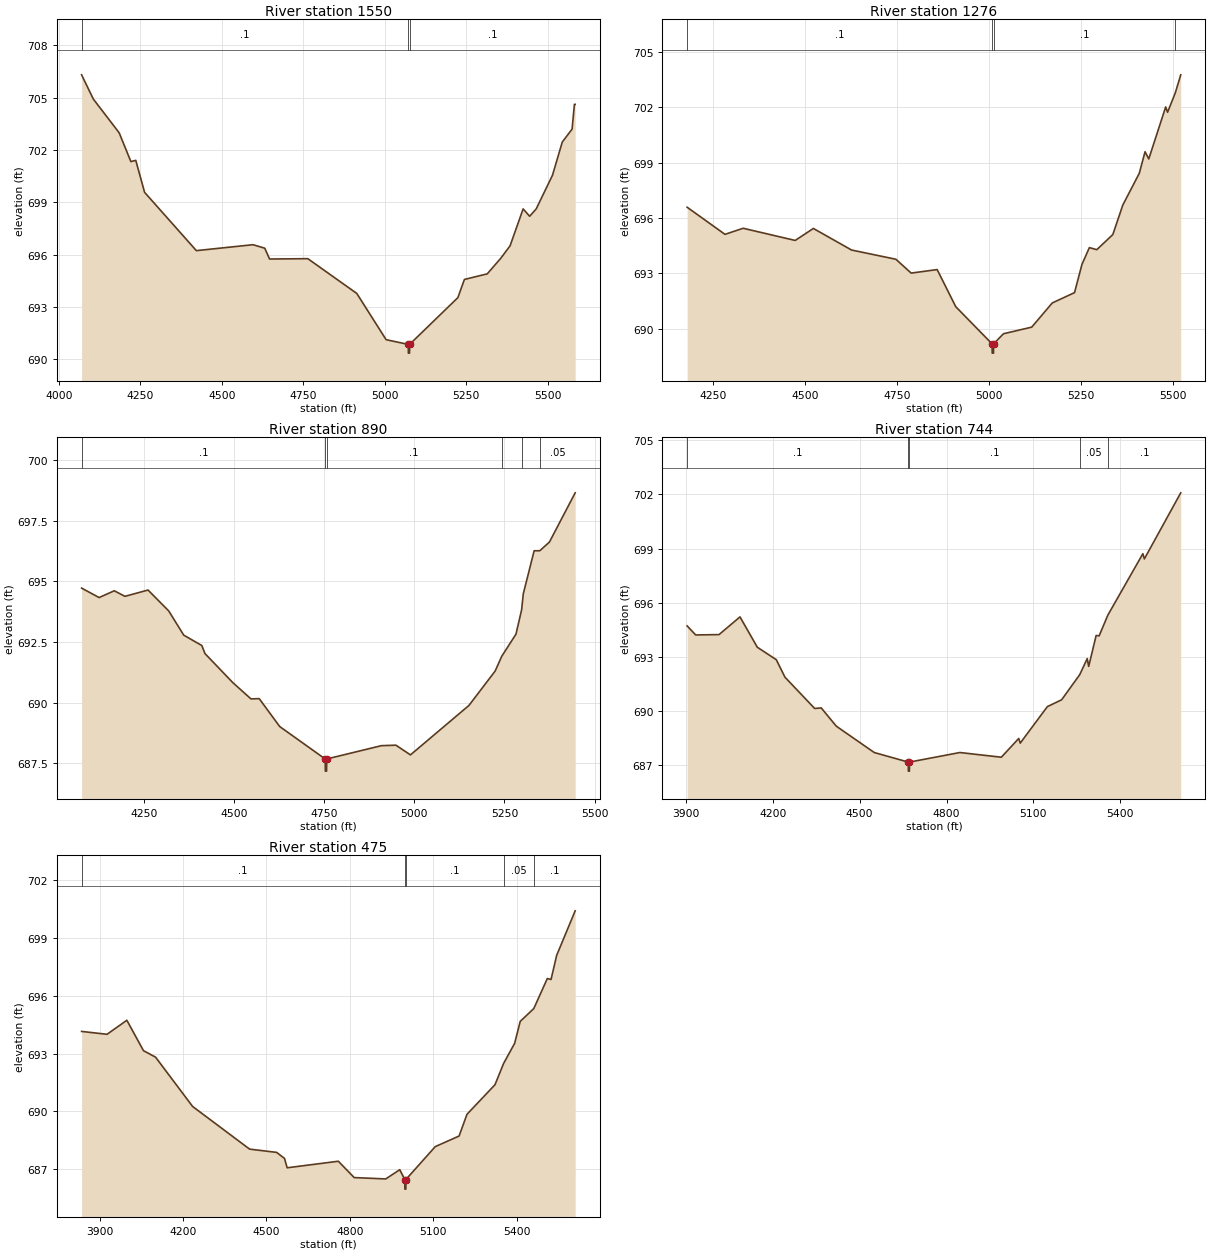
Type RM Length L Ch R = 1,1550,274,274,274
BEGIN DESCRIPTION:
UNT 039 in BCW 1.0
END DESCRIPTION:
XS GIS Cut Line= 3
      1964425.03     13587774.96      1964798.40     13587221.86
      1964759.33     13586375.49
#Sta/Elev= 30
  4069.6  706.30  4105.7  704.91  4184.9  702.98  4220.9  701.33  4235.9  701.40
  4262.9  699.57  4421.8  696.23  4595.6  696.57  4631.6  696.37  4646.5  695.75
  4763.8  695.77  4914.0  693.78  5004.1  691.13  5072.1  690.86  5072.4  690.36
  5075.9  690.36  5076.1  690.86  5224.3  693.54  5244.3  694.58  5314.4  694.90
  5356.2  695.80  5384.5  696.51  5424.5  698.62  5444.5  698.20  5464.6  698.62
  5514.6  700.55  5544.6  702.45  5574.7  703.19  5581.9  704.61  5584.2  704.61
#Mann=3,-1,0
  4069.6     0.1       0  5072.1    0.07       0  5076.1     0.1       0
Bank Sta=5072.1,5076.1
Exp/Cntr=0.3,0.1

Type RM Length L Ch R = 1,1276,386,386,386
BEGIN DESCRIPTION:
UNT 039 in BCW 2.0
END DESCRIPTION:
XS GIS Cut Line= 3
      1964680.36     13587625.77      1965003.27     13587313.28
      1965125.51     13586428.94
#Sta/Elev= 30
  4178.4  696.59  4281.3  695.12  4330.7  695.45  4472.2  694.79  4521.6  695.44
  4625.5  694.27  4746.0  693.77  4787.5  693.02  4858.2  693.21  4908.7  691.20
  5007.6  689.18  5007.9  688.68  5011.4  688.68  5011.6  689.18  5038.5  689.73
  5115.4  690.09  5171.1  691.40  5231.7  691.96  5251.9  693.49  5272.1  694.40
  5292.3  694.29  5335.9  695.11  5363.0  696.71  5407.8  698.43  5423.5  699.60
  5433.6  699.21  5479.6  702.03  5484.7  701.74  5505.7  702.79  5520.5  703.77
#Mann=4,-1,0
  4178.4     0.1       0  5007.6    0.07       0  5011.6     0.1       0
  5505.7    0.05       0
Bank Sta=5007.6,5011.6
Exp/Cntr=0.3,0.1

Type RM Length L Ch R = 1,890,146,146,146
BEGIN DESCRIPTION:
UNT 039 in BCW 5.0
END DESCRIPTION:
XS GIS Cut Line= 3
      1964875.64     13587582.57      1965448.58     13587168.49
      1965360.04     13586512.25
#Sta/Elev= 30
  4077.2  694.72  4125.8  694.33  4167.9  694.61  4197.4  694.38  4261.5  694.64
  4318.8  693.78  4360.5  692.78  4410.8  692.35  4419.4  692.02  4496.7  690.82
  4547.0  690.15  4569.9  690.16  4626.7  689.01  4753.0  687.67  4753.3  687.17
  4756.8  687.17  4757.0  687.67  4908.7  688.22  4949.1  688.24  4989.4  687.84
  5151.7  689.88  5224.4  691.30  5242.7  691.91  5282.1  692.82  5297.8  693.83
  5302.3  694.48  5332.5  696.26  5348.1  696.26  5374.9  696.62  5446.3  698.65
#Mann=6,-1,0
  4077.2     0.1       0  4753.0    0.07       0  4757.0     0.1       0
  5242.7    0.08       0  5297.8     0.1       0  5348.1    0.05       0
Bank Sta=4753,4757
Exp/Cntr=0.3,0.1

Type RM Length L Ch R = 1,744,269,269,269
BEGIN DESCRIPTION:
UNT 039 in BCW 3.0
END DESCRIPTION:
XS GIS Cut Line= 3
      1964878.28     13587616.40      1965615.25     13587215.37
      1965433.06     13586369.48
#Sta/Elev= 30
  3904.4  694.72  3933.9  694.22  4014.5  694.24  4086.8  695.22  4146.7  693.54
  4212.2  692.85  4242.2  691.88  4344.7  690.15  4367.4  690.18  4419.3  689.17
  4550.4  687.71  4668.0  687.18  4668.3  686.68  4671.8  686.68  4672.0  687.18
  4846.1  687.71  4989.3  687.45  5049.4  688.49  5054.5  688.23  5148.1  690.25
  5197.4  690.63  5259.9  692.02  5285.8  692.91  5290.9  692.48  5316.6  694.19
  5326.9  694.17  5357.1  695.32  5478.0  698.72  5483.1  698.43  5608.7  702.09
#Mann=5,-1,0
  3904.4     0.1       0  4668.0    0.07       0  4672.0     0.1       0
  5259.9    0.05       0  5357.1     0.1       0
Bank Sta=4668,4672
Exp/Cntr=0.3,0.1

Type RM Length L Ch R = 1,475,0,0,0
BEGIN DESCRIPTION:
UNT 039 in BCW 4.0
END DESCRIPTION:
XS GIS Cut Line= 3
      1964914.74     13587626.82      1965828.79     13587126.82
      1965737.79     13586398.85
#Sta/Elev= 30
  3834.9  694.15  3926.4  694.00  3997.7  694.73  4057.5  693.15  4101.1  692.81
  4234.1  690.25  4439.3  688.03  4536.5  687.86  4564.7  687.55  4574.4  687.06
  4758.5  687.40  4815.5  686.55  4929.0  686.48  4979.4  686.96  4997.5  686.45
  4997.8  685.95  5001.3  685.95  5001.5  686.45  5107.1  688.16  5192.8  688.71
  5221.2  689.84  5322.0  691.38  5352.8  692.48  5392.6  693.53  5412.7  694.67
  5461.6  695.34  5510.2  696.90  5523.6  696.85  5543.7  698.10  5610.4  700.42
#Mann=5,-1,0
  3834.9     0.1       0  4997.5    0.07       0  5001.5     0.1       0
  5352.8    0.05       0  5461.6     0.1       0
Bank Sta=4997.5,5001.5
Exp/Cntr=0.3,0.1

Chan Stop Cuts=-1