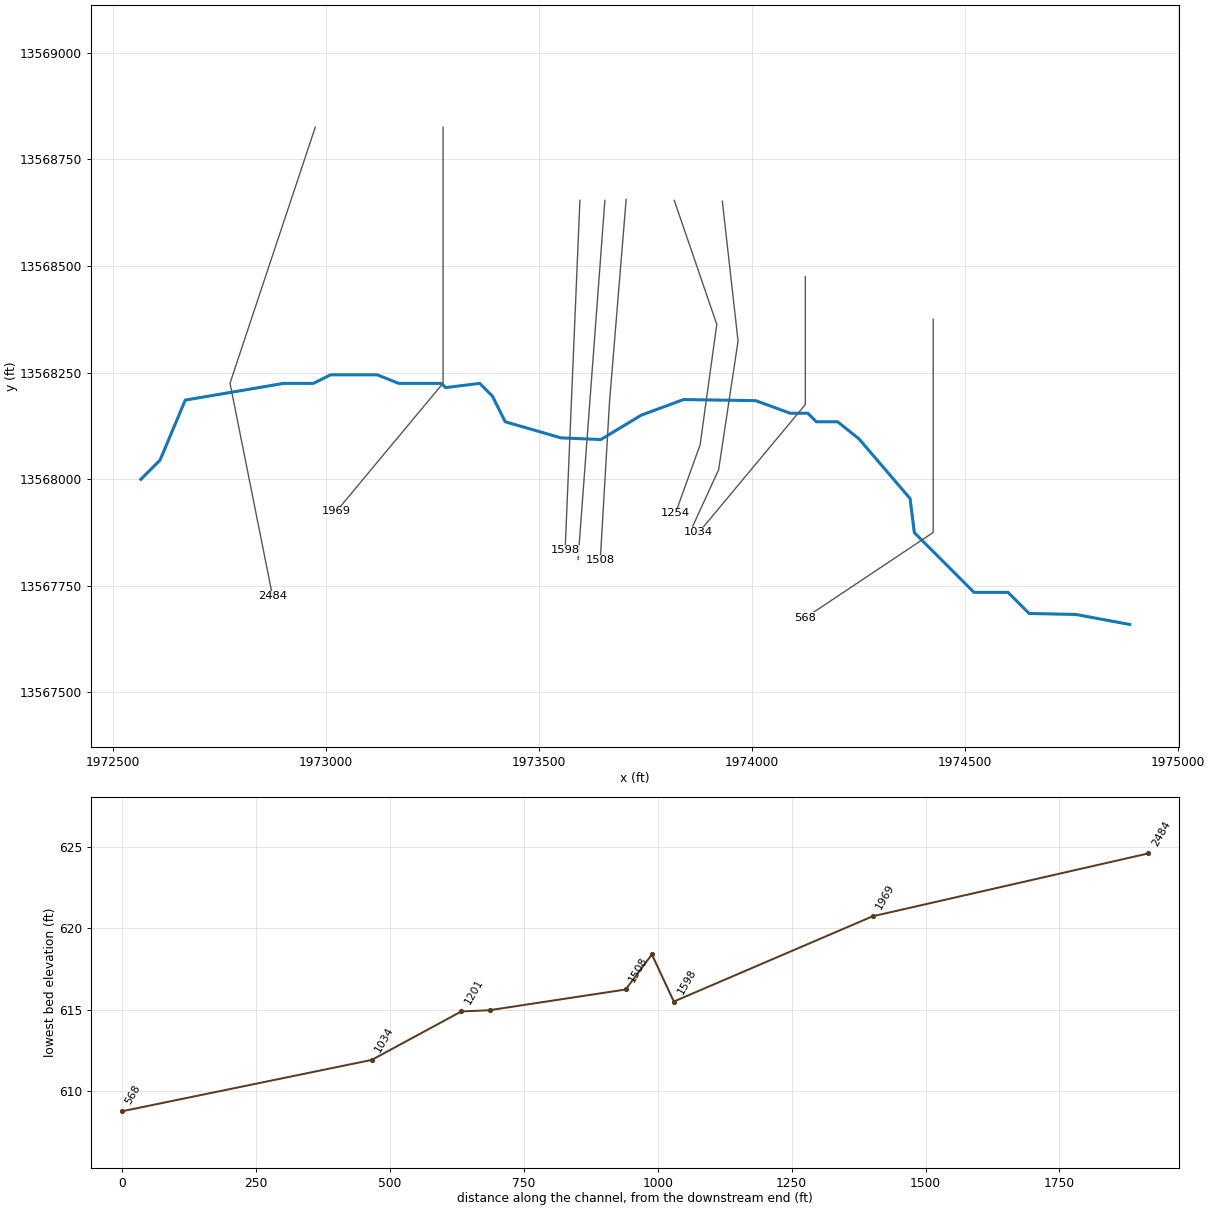
--- UNT 040 in BCW.prj (project) ---

Proj Title=UNT 040 in BCW Base Level Engineering
Current Plan=p01
Default Exp/Contr=0.3,0.1
English Units
Geom File=g01
Flow File=f01
Plan File=p01
BEGIN DESCRIPTION:
UNT 040 in BCW
END DESCRIPTION:

--- UNT 040 in BCW.p01 (plan) ---

Plan Title=Multiple Run
Short Identifier=Multiple
Geom File=g01
Flow File=f01
Subcritical Flow
K Sum by GR= 0
Std Step Tol= 0.01
Critical Tol= 0.01
Num of Std Step Trials= 20
Max Error Tol= 0.3
Flow Tol Ratio= 0.001
Split Flow NTrial= 30
Split Flow Tol= 0.02
Split Flow Ratio= 0.02
Log Output Level= 0
Friction Slope Method= 1
Unsteady Friction Slope Method= 2
Unsteady Bridges Friction Slope Method= 1
Parabolic Critical Depth
Global Vel Dist=  1 , 1 , 1
Global Log Level= 0
CheckData=True
Encroach Param= -1, 0, 0, 0
BEGIN DESCRIPTION:
Multiple Run
END DESCRIPTION:

--- UNT 040 in BCW.f01 (steady flow) ---

Flow Title=Multiple
Number of Profiles=7
Profile Names=10-year,25-year,50-year,1pct_min,100-year,1pct_plu,500-year
River Rch & RM= UNT 040 in BCW,Reach-1,2484
     361     494     601     363     725    1446    1056
Boundary for River Rch & Prof#=UNT 040 in BCW,Reach-1,1
Up Type=0
Dn Type=3
Dn Slope=0.005
Boundary for River Rch & Prof#=UNT 040 in BCW,Reach-1,2
Up Type=0
Dn Type=3
Dn Slope=0.005
Boundary for River Rch & Prof#=UNT 040 in BCW,Reach-1,3
Up Type=0
Dn Type=3
Dn Slope=0.005
Boundary for River Rch & Prof#=UNT 040 in BCW,Reach-1,4
Up Type=0
Dn Type=3
Dn Slope=0.005
Boundary for River Rch & Prof#=UNT 040 in BCW,Reach-1,5
Up Type=0
Dn Type=3
Dn Slope=0.005
Boundary for River Rch & Prof#=UNT 040 in BCW,Reach-1,6
Up Type=0
Dn Type=3
Dn Slope=0.005
Boundary for River Rch & Prof#=UNT 040 in BCW,Reach-1,7
Up Type=0
Dn Type=3
Dn Slope=0.005

--- UNT 040 in BCW.g01 (geometry) ---

Geom Title=Existing Conditions

River Reach=UNT 040 in BCW,Reach-1
Reach XY= 30
      1972565.80     13567999.54      1972610.80     13568044.54
      1972670.01     13568185.34      1972900.80     13568224.54
      1972970.80     13568224.54      1973010.80     13568244.54
      1973120.80     13568244.54      1973170.80     13568224.54
      1973270.80     13568224.54      1973280.80     13568214.54
      1973360.80     13568224.54      1973390.80     13568194.54
      1973420.80     13568134.54      1973551.52     13568096.80
      1973645.27     13568092.89      1973740.32     13568150.18
      1973839.28     13568186.64      1974008.55     13568184.04
      1974089.28     13568154.54      1974130.80     13568154.54
      1974150.80     13568134.54      1974200.80     13568134.54
      1974250.80     13568094.54      1974370.80     13567954.54
      1974380.80     13567874.54      1974520.80     13567734.54
      1974600.80     13567734.54      1974650.24     13567685.10
      1974759.85     13567682.73      1974886.15     13567659.30

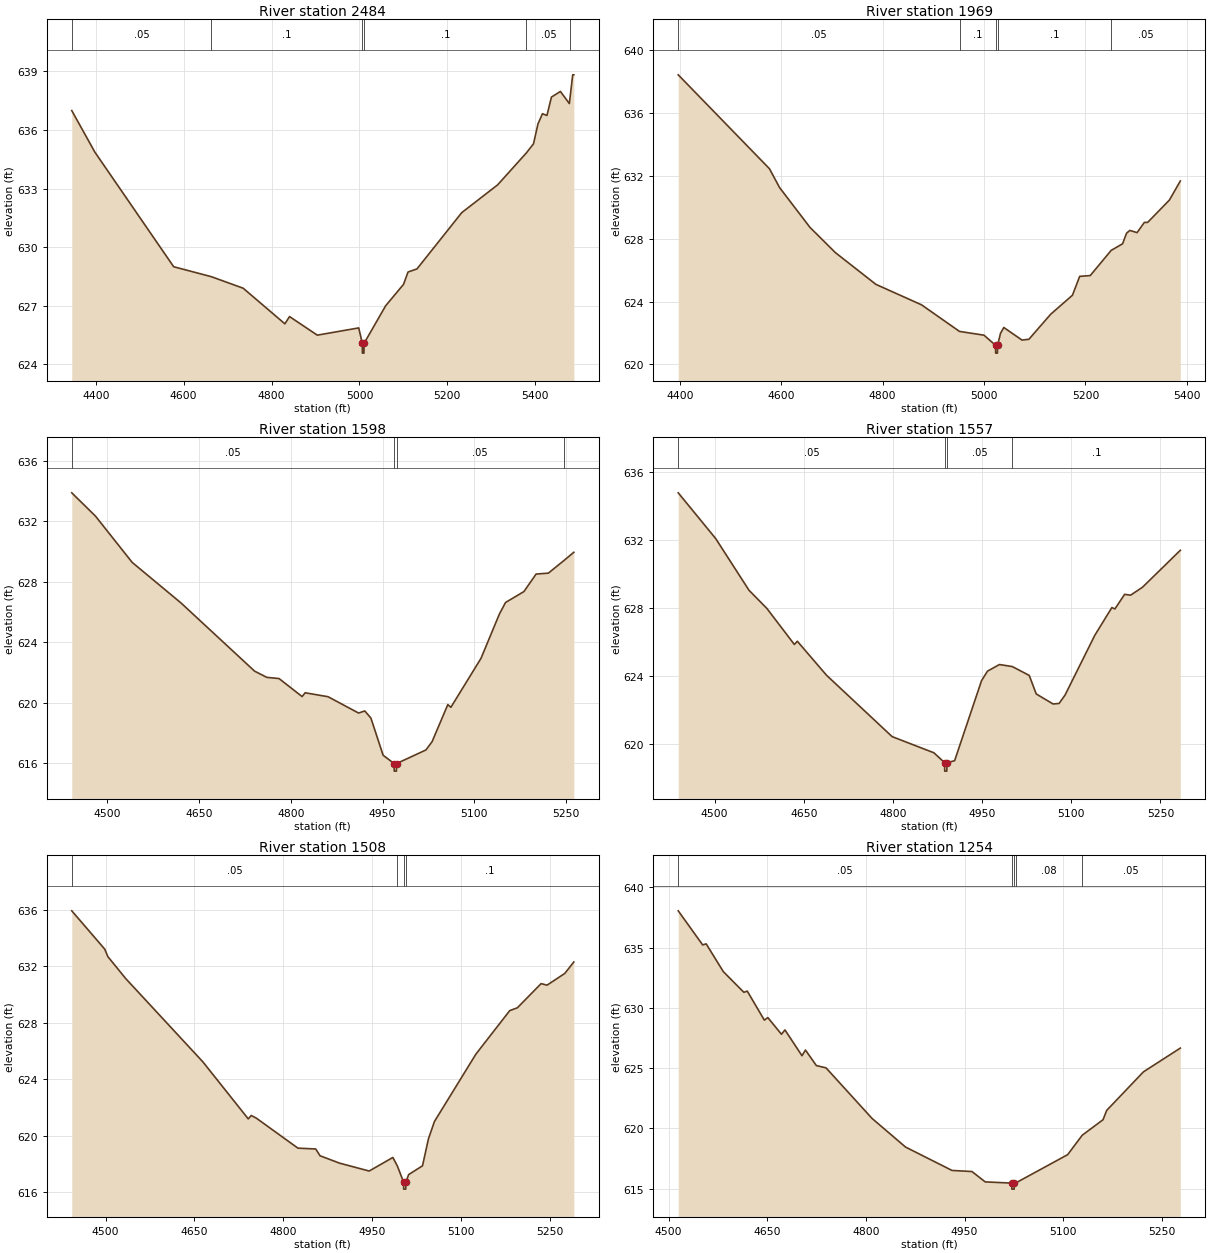
Type RM Length L Ch R = 1,2484,515,515,515
BEGIN DESCRIPTION:
UNT 040 in BCW 5.0
END DESCRIPTION:
XS GIS Cut Line= 3
      1972975.01     13568825.04      1972775.00     13568225.00
      1972875.00     13567725.00
#Sta/Elev= 30
  4345.4  636.99  4398.1  634.86  4577.3  629.00  4663.2  628.49  4735.5  627.90
  4830.3  626.08  4840.9  626.45  4904.1  625.50  4998.3  625.87  5006.5  625.08
  5006.7  624.58  5010.2  624.58  5010.5  625.08  5059.5  627.00  5100.3  628.10
  5110.5  628.73  5130.9  628.89  5232.8  631.77  5314.4  633.19  5380.0  634.83
  5396.0  635.29  5406.2  636.31  5416.4  636.83  5426.6  636.74  5436.8  637.68
  5457.2  637.97  5477.6  637.35  5479.9  637.79  5485.2  638.82  5487.8  638.82
#Mann=6,-1,0
  4345.4    0.05       0  4663.2     0.1       0  5006.5    0.07       0
  5010.5     0.1       0  5380.0    0.05       0  5479.9     0.1       0
Bank Sta=5006.5,5010.5
Exp/Cntr=0.3,0.1

Type RM Length L Ch R = 1,1969,371,371,371
BEGIN DESCRIPTION:
UNT 040 in BCW 4.0
END DESCRIPTION:
XS GIS Cut Line= 3
      1973275.00     13568824.99      1973275.00     13568225.00
      1973025.00     13567925.00
#Sta/Elev= 30
  4396.7  638.41  4576.7  632.44  4596.7  631.24  4656.7  628.71  4706.7  627.11
  4786.7  625.09  4876.7  623.79  4951.6  622.10  4999.9  621.86  5022.7  621.22
  5022.9  620.72  5026.4  620.72  5026.7  621.22  5032.5  621.98  5039.0  622.35
  5074.8  621.55  5088.5  621.60  5131.4  623.19  5174.4  624.40  5188.7  625.60
  5209.5  625.65  5250.8  627.25  5273.3  627.67  5281.1  628.34  5287.6  628.52
  5301.9  628.38  5316.3  629.03  5322.8  629.03  5365.7  630.45  5387.2  631.66
#Mann=5,-1,0
  4396.7    0.05       0  4951.6     0.1       0  5022.7    0.07       0
  5026.7     0.1       0  5250.8    0.05       0
Bank Sta=5022.7,5026.7
Exp/Cntr=0.3,0.1

Type RM Length L Ch R = 1,1598,41,41,41
BEGIN DESCRIPTION:
Mapping XS 0f0e0d4c
END DESCRIPTION:
XS GIS Cut Line= 2
      1973596.04     13568653.73      1973561.32     13567833.36
#Sta/Elev= 30
  4441.7  633.89  4480.5  632.35  4540.5  629.29  4620.6  626.60  4740.7  622.10
  4760.7  621.69  4780.7  621.61  4818.4  620.42  4823.4  620.67  4860.8  620.41
  4910.8  619.33  4920.9  619.47  4930.9  619.00  4950.9  616.54  4968.9  615.99
  4969.1  615.49  4972.6  615.49  4972.9  615.99  5020.9  616.89  5031.0  617.44
  5056.7  619.89  5061.7  619.71  5111.0  622.95  5141.1  625.88  5151.1  626.64
  5181.1  627.36  5201.1  628.52  5221.1  628.58  5246.5  629.41  5262.8  629.96
#Mann=4,-1,0
  4441.7    0.05       0  4968.9   0.035       0  4972.9    0.05       0
  5246.5     0.1       0
Bank Sta=4968.9,4972.9
Exp/Cntr=0.3,0.1

Type RM Length L Ch R = 1,1557,49,49,49
BEGIN DESCRIPTION:
Mapping XS b20fcb10
END DESCRIPTION:
XS GIS Cut Line= 2
      1973654.63     13568653.68      1973591.70     13567811.63
#Sta/Elev= 30
  4439.0  634.75  4502.0  632.06  4558.0  629.02  4588.1  627.95  4634.3  625.83
  4639.3  626.02  4688.4  624.02  4798.7  620.41  4868.9  619.46  4886.9  618.88
  4887.2  618.38  4890.7  618.38  4890.9  618.88  4903.8  618.99  4949.1  623.70
  4959.1  624.26  4979.2  624.65  5000.9  624.53  5029.3  624.01  5041.1  622.92
  5069.4  622.33  5079.5  622.36  5089.5  622.85  5139.6  626.37  5168.3  628.00
  5173.4  627.92  5189.8  628.78  5199.8  628.73  5219.9  629.20  5283.4  631.37
#Mann=4,-1,0
  4439.0    0.05       0  4886.9   0.035       0  4890.9    0.05       0
  5000.9     0.1       0
Bank Sta=4886.9,4890.9
Exp/Cntr=0.3,0.1

Type RM Length L Ch R = 1,1508,254,254,254
BEGIN DESCRIPTION:
UNT 040 in BCW 3.0
END DESCRIPTION:
XS GIS Cut Line= 3
      1973704.54     13568655.83      1973665.48     13568180.59
      1973643.80     13567809.76
#Sta/Elev= 30
  4442.7  635.92  4498.4  633.21  4503.7  632.68  4533.8  631.13  4664.3  625.23
  4740.9  621.20  4745.9  621.44  4754.6  621.25  4824.8  619.13  4854.9  619.07
  4862.2  618.59  4895.0  618.07  4945.2  617.51  4985.2  618.47  4992.8  617.87
  5003.3  616.73  5003.5  616.23  5007.0  616.23  5007.3  616.73  5011.9  617.26
  5035.3  617.88  5045.3  619.78  5055.4  621.01  5125.5  625.78  5182.7  628.86
  5195.6  629.06  5235.7  630.77  5245.7  630.66  5275.7  631.49  5291.0  632.30
#Mann=4,-1,0
  4442.7    0.05       0  4992.8     0.1       0  5003.3    0.07       0
  5007.3     0.1       0
Bank Sta=5003.3,5007.3
Exp/Cntr=0.3,0.1

Type RM Length L Ch R = 1,1254,53,53,53
BEGIN DESCRIPTION:
Mapping XS a0e5f348
END DESCRIPTION:
XS GIS Cut Line= 4
      1973817.39     13568653.70      1973917.22     13568362.89
      1973878.16     13568080.77      1973820.13     13567919.58
#Sta/Elev= 30
  4514.6  638.05  4551.8  635.22  4557.1  635.31  4583.1  633.01  4614.4  631.29
  4619.6  631.39  4645.6  628.98  4650.9  629.19  4671.6  627.81  4676.9  628.17
  4702.8  626.03  4708.1  626.50  4724.7  625.21  4739.4  625.02  4809.3  620.83
  4860.3  618.45  4931.0  616.51  4961.3  616.42  4981.5  615.56  5021.7  615.46
  5022.0  614.96  5025.5  614.96  5025.7  615.46  5027.8  615.47  5106.9  617.82
  5129.0  619.43  5160.7  620.72  5166.2  621.49  5222.1  624.69  5278.2  626.66
#Mann=5,-1,0
  4514.6    0.05       0  5021.7    0.04       0  5025.7    0.05       0
  5027.8    0.08       0  5129.0    0.05       0
Bank Sta=5021.7,5025.7
Exp/Cntr=0.3,0.1

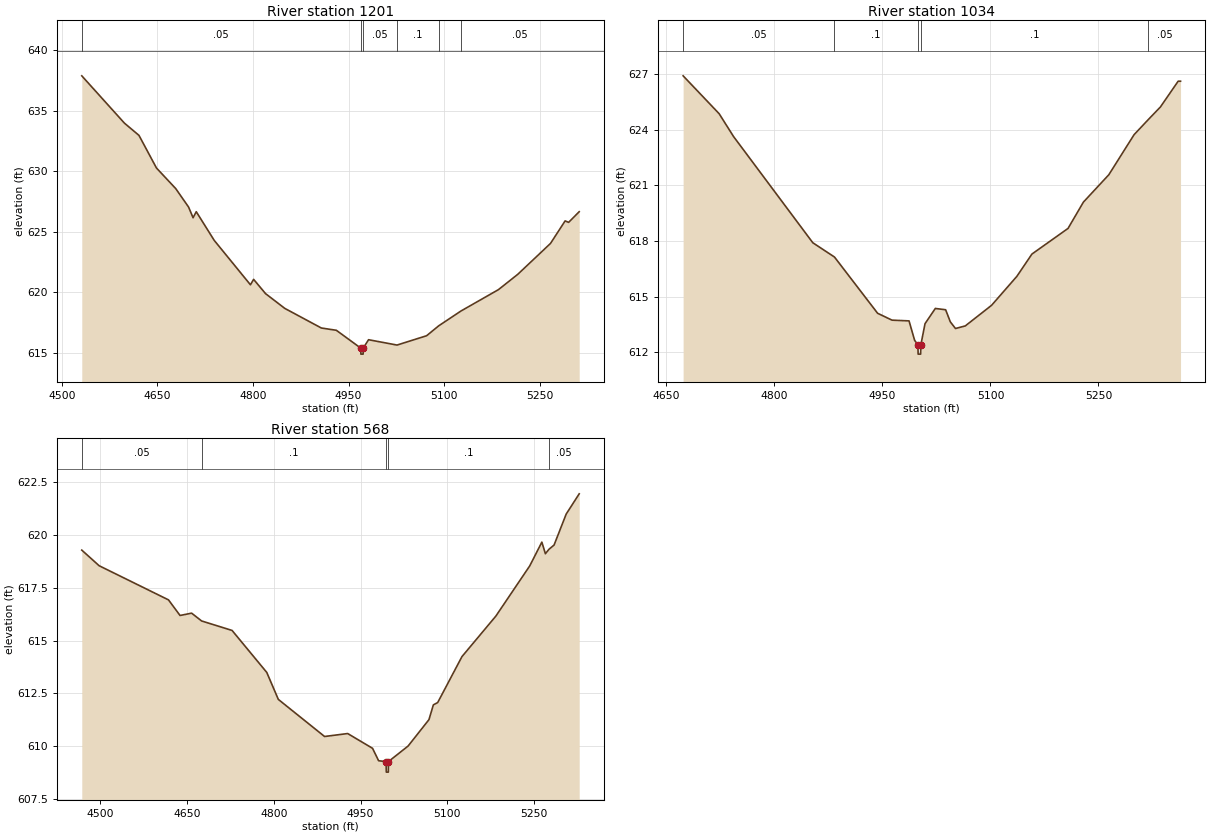
Type RM Length L Ch R = 1,1201,167,167,167
BEGIN DESCRIPTION:
Mapping XS cae30735
END DESCRIPTION:
XS GIS Cut Line= 4
      1973930.24     13568651.51      1973967.13     13568323.82
      1973921.56     13568022.17      1973860.83     13567889.88
#Sta/Elev= 30
  4531.5  637.88  4598.4  633.97  4621.2  632.96  4648.7  630.26  4678.9  628.56
  4699.1  627.03  4706.1  626.15  4711.1  626.65  4739.3  624.28  4796.1  620.61
  4801.1  621.06  4819.8  619.88  4850.0  618.66  4907.3  617.04  4930.9  616.85
  4969.1  615.38  4969.4  614.88  4972.9  614.88  4973.1  615.38  4981.4  616.07
  5026.1  615.63  5072.5  616.40  5091.5  617.22  5126.3  618.44  5185.2  620.21
  5215.4  621.47  5266.9  624.03  5289.8  625.89  5295.3  625.77  5311.9  626.65
#Mann=6,-1,0
  4531.5    0.05       0  4969.1    0.04       0  4973.1    0.05       0
  5026.1     0.1       0  5091.5    0.08       0  5126.3    0.05       0
Bank Sta=4969.1,4973.1
Exp/Cntr=0.3,0.1

Type RM Length L Ch R = 1,1034,466,466,466
BEGIN DESCRIPTION:
UNT 040 in BCW 2.0
END DESCRIPTION:
XS GIS Cut Line= 3
      1974125.00     13568474.96      1974125.00     13568175.00
      1973874.99     13567874.98
#Sta/Elev= 30
  4673.4  626.90  4723.4  624.86  4743.4  623.63  4853.4  617.91  4883.5  617.14
  4943.4  614.11  4963.4  613.74  4987.0  613.70  4994.8  612.65  4999.4  612.41
  4999.6  611.91  5003.1  611.91  5003.4  612.41  5009.2  613.55  5023.5  614.37
  5037.8  614.30  5044.3  613.65  5051.5  613.29  5065.1  613.43  5101.6  614.54
  5136.7  616.10  5157.6  617.30  5207.7  618.68  5229.1  620.10  5264.3  621.57
  5299.4  623.73  5319.3  624.55  5335.9  625.22  5360.6  626.61  5363.9  626.61
#Mann=5,-1,0
  4673.4    0.05       0  4883.5     0.1       0  4999.4    0.07       0
  5003.4     0.1       0  5319.3    0.05       0
Bank Sta=4999.4,5003.4
Exp/Cntr=0.3,0.1

Type RM Length L Ch R = 1,568,0,0,0
BEGIN DESCRIPTION:
UNT 040 in BCW 1.0
END DESCRIPTION:
XS GIS Cut Line= 3
      1974425.00     13568374.99      1974425.00     13567875.00
      1974125.04     13567675.03
#Sta/Elev= 30
  4467.8  619.29  4497.8  618.55  4617.8  616.93  4637.8  616.19  4657.8  616.30
  4675.1  615.93  4727.8  615.48  4787.8  613.49  4807.8  612.21  4887.8  610.45
  4927.8  610.59  4970.8  609.89  4981.3  609.30  4994.3  609.26  4994.6  608.76
  4998.1  608.76  4998.3  609.26  5032.4  610.00  5068.4  611.25  5076.0  611.95
  5083.5  612.06  5125.5  614.24  5184.1  616.16  5242.7  618.54  5263.7  619.67
  5269.8  619.12  5276.0  619.33  5284.8  619.53  5305.8  621.00  5328.3  621.96
#Mann=5,-1,0
  4467.8    0.05       0  4675.1     0.1       0  4994.3    0.07       0
  4998.3     0.1       0  5276.0    0.05       0
Bank Sta=4994.3,4998.3
Exp/Cntr=0.3,0.1

Chan Stop Cuts=-1