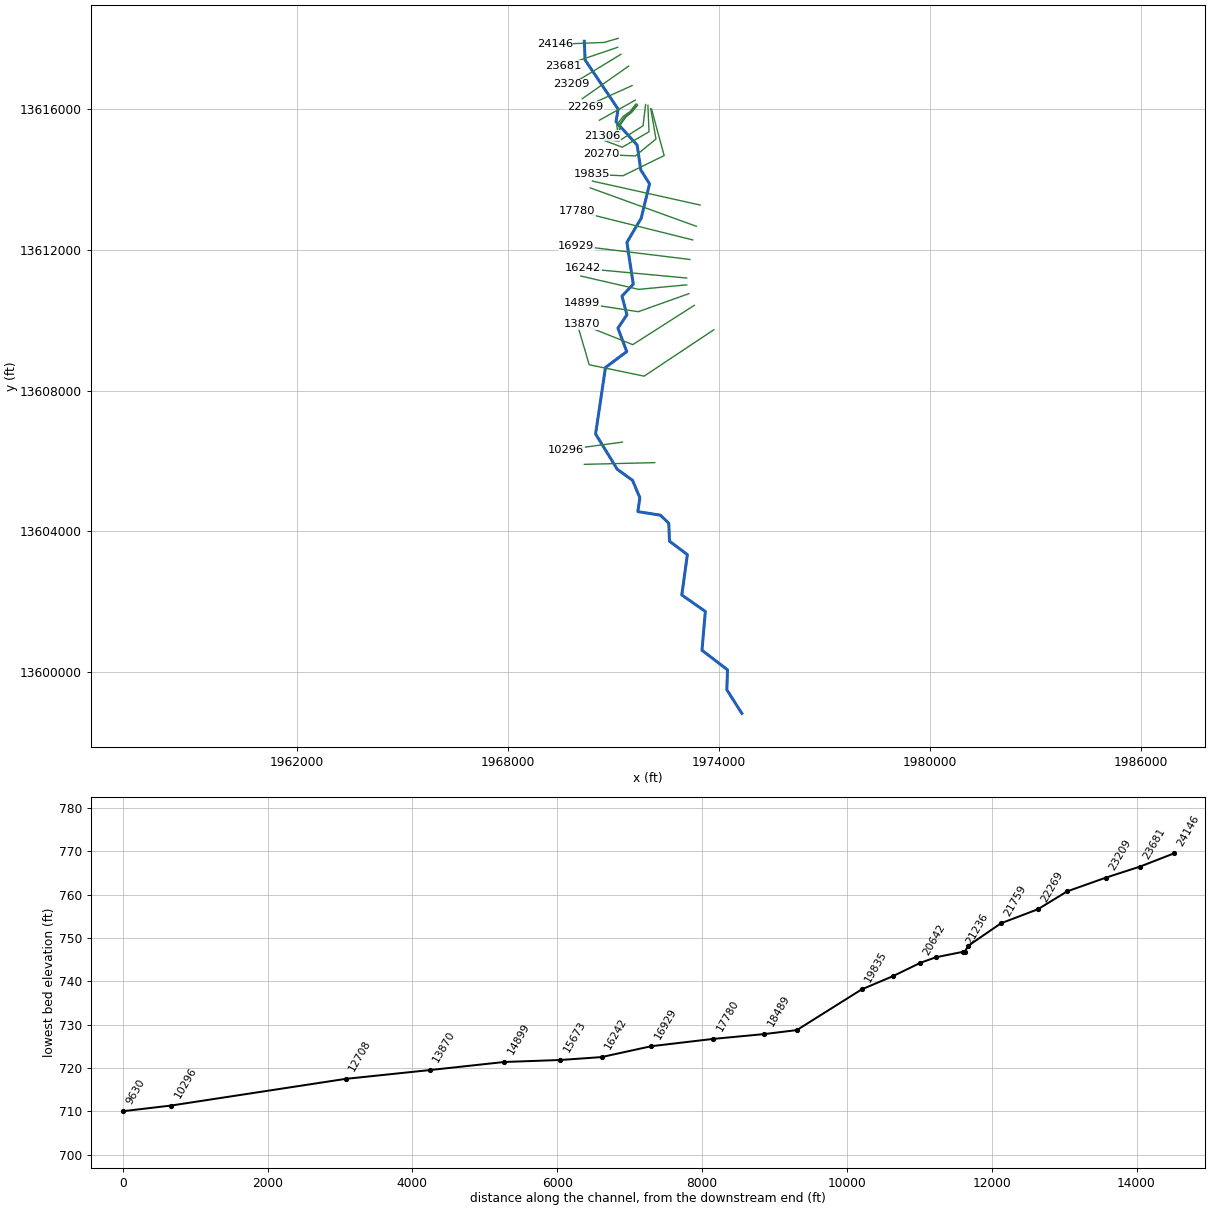
--- UNT 042 in BCW.prj (project) ---

Proj Title=UNT 042 in BCW Base Level Engineering
Current Plan=p01
Default Exp/Contr=0.3,0.1
English Units
Geom File=g01
Flow File=f01
Plan File=p01
Y Axis Title=Elevation
X Axis Title(PF)=Main Channel Distance
X Axis Title(XS)=Station
BEGIN DESCRIPTION:
UNT 042 in BCW
END DESCRIPTION:
DSS Export Rating Curves= 0
DSS Export Rating Curve Sorted= 0
DSS Export Volume Flow Curves= 0
DXF OffsetX= 0
DXF OffsetY= 0
DXF ScaleX= 1
DXF ScaleY= 10

--- UNT 042 in BCW.p01 (plan) ---

Plan Title=Multiple Run
Program Version=5.05
Short Identifier=1
Geom File=g01
Flow File=f01
Subcritical Flow
K Sum by GR= 0
Std Step Tol= 0.01
Critical Tol= 0.01
Num of Std Step Trials= 20
Max Error Tol= 0.3
Flow Tol Ratio= 0.001
Split Flow NTrial= 30
Split Flow Tol= 0.02
Split Flow Ratio= 0.02
Log Output Level= 0
Friction Slope Method= 1
Unsteady Friction Slope Method= 2
Unsteady Bridges Friction Slope Method= 1
Parabolic Critical Depth
Global Vel Dist= 1 , 1 , 1
Global Log Level= 0
CheckData=True
Encroach Param=-1 ,0,0, 0
BEGIN DESCRIPTION:
Multiple Run
END DESCRIPTION:
Computation Interval=1MIN
Output Interval=1HOUR
Instantaneous Interval=1HOUR
Mapping Interval=1HOUR
Computation Time Step Use Courant=        0
Computation Time Step Use Time Series=    0
Computation Time Step Count To Double=0
Computation Time Step Max Doubling=0
Computation Time Step Max Halving=0
Computation Time Step Residence Courant=0
Run HTab= 0
Run UNet= 0
Run Sediment= 0
Run PostProcess= 0
Run WQNet= 0
Run RASMapper= 0
UNET Theta= 1
UNET Theta Warmup= 1
UNET ZTol= 0.02
UNET ZSATol= 0.02
UNET MxIter= 20
UNET Max Iter WO Improvement= 0
UNET MaxInSteps= 0
UNET DtIC= 0
UNET DtMin= 0
UNET MaxCRTS= 20
UNET WFStab= 2
UNET SFStab= 1
UNET WFX= 1
UNET SFX= 1
UNET 1D Methodology=Finite Difference
UNET DSS MLevel= 4
UNET Pardiso=0
UNET DZMax Abort= 100
UNET Use Existing IB Tables=-1
UNET Froude Reduction=False
UNET Froude Limit= 0.8
UNET Froude Power= 4
UNET D1 Cores= 0
UNET D2 Coriolis=0
UNET D2 Cores= 0
UNET D2 Theta= 1
UNET D2 Theta Warmup= 1
UNET D2 Z Tol= 0.01
UNET D2 Volume Tol= 0.01
UNET D2 Max Iterations= 20
UNET D2 Equation= 0
UNET D2 RampUpFraction=0.1
UNET D2 TimeSlices= 1
UNET D2 BCVolumeCheck=0
UNET D1D2 MaxIter= 0
UNET D1D2 ZTol=0.01
UNET D1D2 QTol=0.1
UNET D1D2 MinQTol=1
Write IC File= 0
Write IC File at Fixed DateTime=0
Write IC File at Sim End=0
Echo Input=False
Echo Parameters=False
Echo Output=False
Write Detailed= 0
HDF Write Warmup=0
HDF Write Time Slices=0
HDF Flush=0
HDF Face Node Velocities=0
HDF Compression= 1
HDF Chunk Size= 1
HDF Spatial Parts= 1
HDF Use Max Rows=0
HDF Fixed Rows= 1
Calibration Method= 0
Calibration Iterations= 20
Calibration Max Change=0.05
Calibration Tolerance=0.2
Calibration Maximum=1.5
Calibration Minimum=0.5
Calibration Optimization Method= 1
WQ AD Non Conservative
WQ ULTIMATE=-1
WQ Max Comp Step=1HOUR
WQ Output Interval=15MIN
WQ Output Selected Increments= 0
WQ Output face flow=0
WQ Output face velocity=0
WQ Output face area=0
WQ Output face dispersion=0
WQ Output cell volume=0
WQ Output cell surface area=0
WQ Output cell continuity=0
WQ Output cumulative cell continuity=0
WQ Output face conc=0
WQ Output face dconc_dx=0
WQ Output face courant=0
WQ Output face peclet=0
WQ Output face adv mass=0
WQ Output face disp mass=0
WQ Output cell mass=0
WQ Output cell source sink temp=0
WQ Output nsm pathways=0
WQ Output nsm derived pathways=0
WQ Output MaxMinRange=-1
WQ Daily Max Min Mean=-1
WQ Daily Range=0
WQ Daily Time=0
WQ Create Restart=0
WQ Fixed Restart=0
WQ System Summary=0
WQ Write To DSS=0
WQ Use Fixed Temperature=0
Sorting and Armoring Iterations= 10
XS Update Threshold= 0.02
Bed Roughness Predictor= 0
Hydraulics Update Threshold= 0.02
Energy Slope Method= 1
Volume Change Method= 1
Sediment Retention Method= 0
XS Weighting Method= 0
Number of US Weighted Cross Sections= 1
Number of DS Weighted Cross Sections= 1
Upstream XS Weight=0
Main XS Weight=1
Downstream XS Weight=0
Number of DS XS's Weighted with US Boundary= 1
Upstream Boundary Weight= 1
Weight of XSs Associated with US Boundary= 0
Number of US XS's Weighted with DS Boundary= 1
Downstream Boundary Weight= 0.5
Weight of XSs Associated with DS Boundary= 0.5
Percentile Method= 0
Sediment Output Level= 3
Mass or Volume Output= 0
Output Increment Type= 1
Profile and TS Output Increment= 1
XS Output Flag= 0
XS Output Increment= 10
Write Gradation File= 0
Read Gradation Hotstart= 0
Write HDF5 File= 1
Write Binary Output= 1
Write DSS Sediment File= 0
SV Curve= 0
Specific Gage Flag= 0

--- UNT 042 in BCW.f01 (steady flow) ---

Flow Title=Multiple
Program Version=5.05
Number of Profiles= 7
Profile Names=10-year,25-year,50-year,1pct_min,100-year,1pct_plu,500-year
River Rch & RM=UNT 042 in BCW,Reach-1         ,24146
     429     590     722     438     874    1743    1280
River Rch & RM=UNT 042 in BCW,Reach-1         ,20858
     686     975    1218     754    1504    3000    2298
River Rch & RM=UNT 042 in BCW,Reach-1         ,18489
     872    1250    1569     974    1943    3877    2991
River Rch & RM=UNT 042 in BCW,Reach-1         ,10296
    1846    2734    3510    2220    4430    8839    7082
River Rch & RM=UNT 042 in BCW,Reach-1         ,5006
    1899    2815    3617    2289    4566    9111    7308
Boundary for River Rch & Prof#=UNT 042 in BCW,Reach-1         , 1
Up Type= 0
Dn Type= 3
Dn Slope=0.005
Boundary for River Rch & Prof#=UNT 042 in BCW,Reach-1         , 2
Up Type= 0
Dn Type= 3
Dn Slope=0.005
Boundary for River Rch & Prof#=UNT 042 in BCW,Reach-1         , 3
Up Type= 0
Dn Type= 3
Dn Slope=0.005
Boundary for River Rch & Prof#=UNT 042 in BCW,Reach-1         , 4
Up Type= 0
Dn Type= 3
Dn Slope=0.005
Boundary for River Rch & Prof#=UNT 042 in BCW,Reach-1         , 5
Up Type= 0
Dn Type= 3
Dn Slope=0.005
Boundary for River Rch & Prof#=UNT 042 in BCW,Reach-1         , 6
Up Type= 0
Dn Type= 3
Dn Slope=0.005
Boundary for River Rch & Prof#=UNT 042 in BCW,Reach-1         , 7
Up Type= 0
Dn Type= 3
Dn Slope=0.005
DSS Import GetInterval= 0
DSS Import GetPeak= 0
DSS Import FillOption= 0

--- UNT 042 in BCW.g01 (geometry) ---

Geom Title=Existing Conditions
Program Version=5.05

River Reach=UNT 042 in BCW  ,Reach-1
Reach XY= 30
       1970170.8     13617934.54       1970190.8     13617404.54
       1971130.8     13616004.54      1971069.52      13615645.7
      1971671.57     13614981.45        1971775.       13614275.
      1972024.26     13613878.04      1971785.71     13612898.81
       1971380.8     13612214.54       1971560.8     13611024.54
       1971240.8     13610684.54       1971380.8     13610154.54
      1971124.77     13609771.73      1971376.51     13609108.53
       1970770.8     13608654.54       1970490.8     13606764.54
      1971105.68     13605760.01       1971540.8     13605444.54
      1971749.12     13604949.46       1971690.8     13604554.54
       1972330.8     13604454.54       1972570.8     13604224.54
       1972590.8     13603714.54       1973098.8     13603332.06
       1972940.8     13602184.54      1973609.87      13601715.3
      1973514.51     13600610.83      1974240.08     13600055.22
       1974221.2     13599487.73      1974646.55     13598816.07

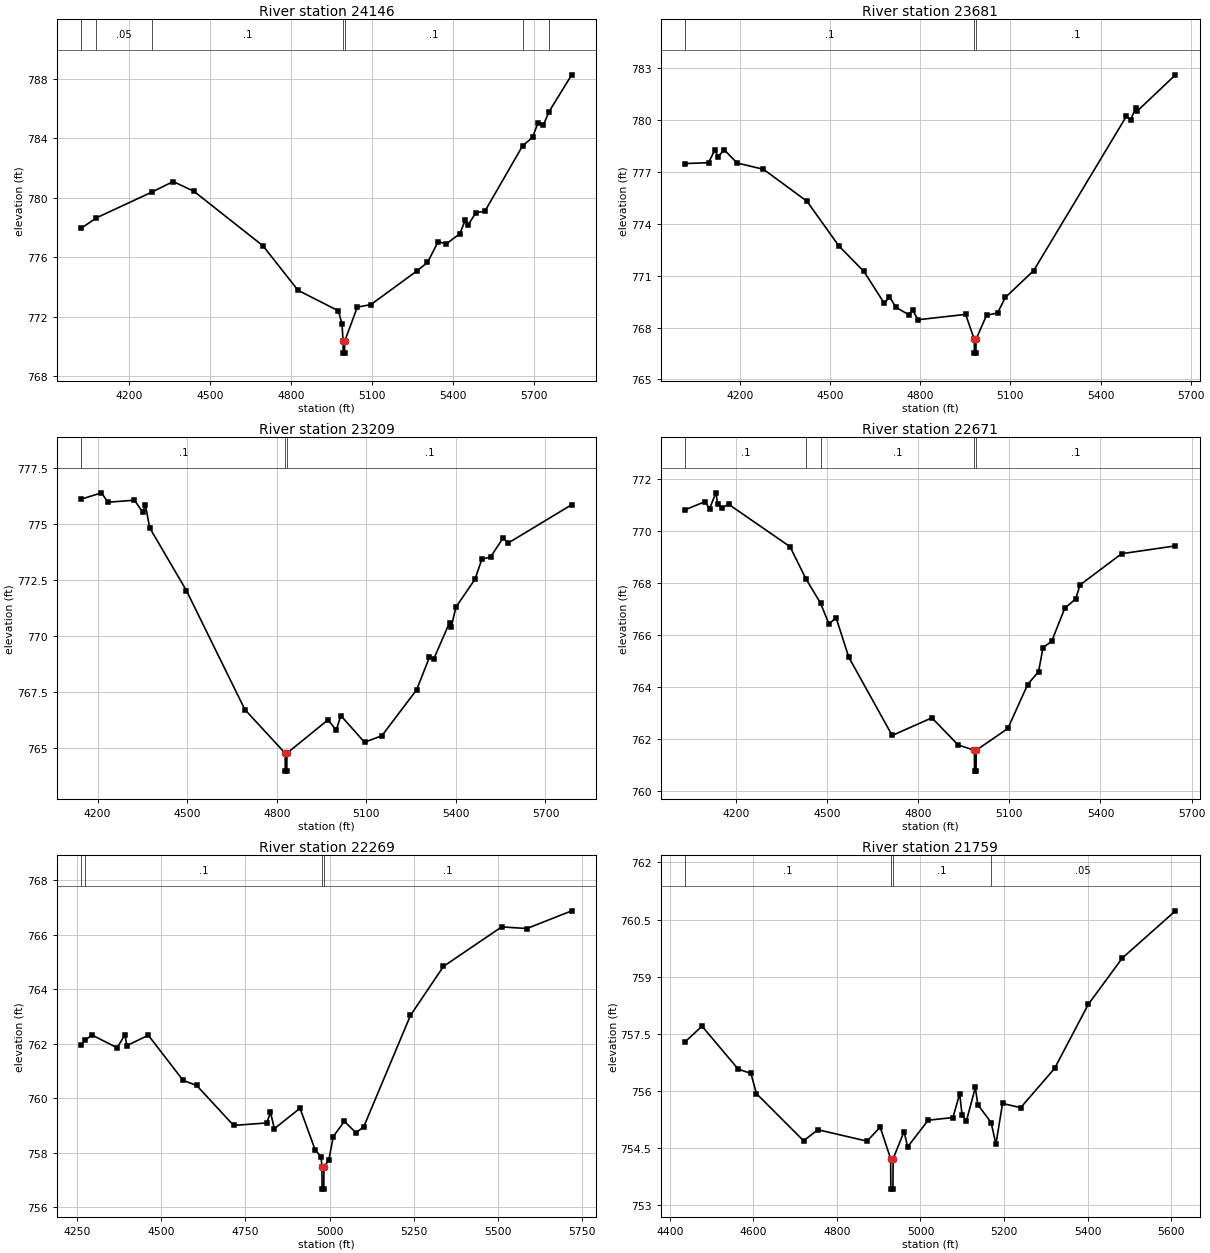
Type RM Length L Ch R = 1 ,24146   ,465,465,465
BEGIN DESCRIPTION:
UNT 042 in BCW 9.0
END DESCRIPTION:
XS GIS Cut Line= 3
      1971131.93     13618017.89      1970730.86      13617900.7
       1969329.9     13617847.75
#Sta/Elev= 30
  4021.7  777.95  4077.3  778.64  4281.8  780.36  4362.3  781.08  4439.5  780.42
  4695.6  776.76  4825.7  773.77  4975.8  772.39  4989.1  771.48  4992.8  770.35
  4993.3  769.55  4998.3  769.55  4998.8  770.35  5045.8  772.64  5095.9  772.81
    5266  775.06    5306  775.64    5346  777.04  5376.1  776.89  5426.1  777.57
  5446.1  778.47  5456.1  778.14  5486.1  778.99  5519.1  779.08  5659.2  783.48
  5696.3  784.05  5716.3  785.03  5736.3  784.88  5757.5  785.78  5841.5  788.25
#Mann= 7 ,-1 , 0
  4021.7      .1       0  4077.3     .05       0  4281.8      .1       0
  4992.8     .07       0  4998.8      .1       0  5659.2     .05       0
  5757.5      .1       0
Bank Sta=4992.8,4998.8
XS Rating Curve= 0 ,0
Exp/Cntr=0.3,0.1

Type RM Length L Ch R = 1 ,23681   ,472,472,472
BEGIN DESCRIPTION:
Mapping XS 02dc3729
END DESCRIPTION:
XS GIS Cut Line= 2
      1971118.86     13617763.01      1969573.77     13617237.86
#Sta/Elev= 30
  4017.4  777.48  4095.4  777.53  4115.6  778.26  4127.1  777.87    4147  778.28
  4190.5  777.51  4277.8  777.15  4422.8   775.3  4528.8  772.72  4612.4  771.24
  4680.5  769.39  4697.4  769.79  4718.6  769.17  4760.8  768.75  4774.6     769
  4792.5  768.45  4950.9  768.76  4979.6  767.32  4980.1  766.52  4985.1  766.52
  4985.6  767.32  5020.4  768.71    5057  768.84  5083.1  769.74  5177.3  771.29
  5485.8  780.21  5500.1     780  5517.2  780.72  5522.4  780.52  5649.3  782.61
#Mann= 3 ,-1 , 0
  4017.4      .1       0  4979.6     .07       0  4985.6      .1       0
Bank Sta=4979.6,4985.6
XS Rating Curve= 0 ,0
Exp/Cntr=0.3,0.1

Type RM Length L Ch R = 1 ,23209   ,538,538,538
BEGIN DESCRIPTION:
Mapping XS 5deafa32
END DESCRIPTION:
XS GIS Cut Line= 2
      1971210.06     13617563.39      1969808.14     13616708.34
#Sta/Elev= 30
  4145.8  776.12    4213   776.4  4234.4  775.98  4323.4  776.07  4350.9  775.54
  4360.1  775.86  4374.3  774.84  4497.6  772.03  4693.2  766.72  4828.1  764.77
  4828.6  763.97  4833.6  763.97  4834.1  764.77  4971.7  766.26  4999.1   765.8
  5014.6  766.45    5094  765.26  5152.1  765.55  5268.3   767.6  5311.3  769.05
  5326.4     769  5378.6   770.6  5384.4   770.4  5399.9  771.29  5463.9  772.54
    5487  773.44  5516.1  773.53  5558.7   774.4  5574.2  774.15  5787.9  775.87
#Mann= 3 ,-1 , 0
  4145.8      .1       0  4828.1     .07       0  4834.1      .1       0
Bank Sta=4828.1,4834.1
XS Rating Curve= 0 ,0
Exp/Cntr=0.3,0.1

Type RM Length L Ch R = 1 ,22671   ,402,402,402
BEGIN DESCRIPTION:
Mapping XS 4acb074e
END DESCRIPTION:
XS GIS Cut Line= 2
      1971431.36     13617229.15       1970111.9     13616300.32
#Sta/Elev= 30
  4033.2  770.83  4098.6  771.14  4113.4  770.87  4134.3  771.48  4140.4  771.05
  4155.2  770.91  4176.2  771.04  4378.2  769.41  4430.3  768.18  4478.6  767.24
  4506.3  766.44  4529.8  766.68  4571.6  765.16  4714.5  762.15  4845.1  762.83
  4931.3  761.79    4985  761.58  4985.5  760.78  4990.5  760.78    4991  761.58
  5095.1  762.42  5160.4  764.11  5196.2  764.61    5211  765.53  5239.4  765.77
  5282.4  767.04  5318.1   767.4  5332.9  767.94  5469.7  769.14  5646.8  769.44
#Mann= 5 ,-1 , 0
  4033.2      .1       0  4430.3     .05       0  4478.6      .1       0
    4985     .07       0    4991      .1       0
Bank Sta=4985,4991
XS Rating Curve= 0 ,0
Exp/Cntr=0.3,0.1

Type RM Length L Ch R = 1 ,22269   ,510,510,510
BEGIN DESCRIPTION:
Mapping XS f75c9136
END DESCRIPTION:
XS GIS Cut Line= 2
      1971526.83     13616673.59      1970199.38     13616074.94
#Sta/Elev= 30
  4262.8  761.97  4273.2  762.12  4294.1  762.32  4368.9  761.85  4392.1  762.33
  4397.6  761.93  4461.5  762.31    4565  760.65  4604.9  760.47  4714.7     759
  4813.3  759.09  4824.3  759.48  4835.9  758.88    4912  759.63    4957   758.1
  4974.7  757.85  4977.1  757.46  4977.6  756.66  4982.6  756.66  4983.1  757.46
  4997.8  757.74  5010.8  758.59  5043.7  759.15  5078.2  758.73  5101.3  758.95
  5240.1  763.04  5338.1  764.84    5511  766.29  5585.9  766.23    5719  766.88
#Mann= 4 ,-1 , 0
  4262.8     .05       0  4273.2      .1       0  4977.1     .07       0
  4983.1      .1       0
Bank Sta=4977.1,4983.1
XS Rating Curve= 0 ,0
Exp/Cntr=0.3,0.1

Type RM Length L Ch R = 1 ,21759   ,453,453,453
BEGIN DESCRIPTION:
Mapping XS 7fb96f9a
END DESCRIPTION:
XS GIS Cut Line= 2
      1971622.34     13616261.27      1970598.07     13615688.38
#Sta/Elev= 30
  4436.8  757.29  4477.1   757.7  4563.9  756.57  4594.2  756.46  4607.3  755.93
  4720.2  754.69  4754.6  754.98  4872.2  754.68  4903.5  755.05  4928.6  754.22
  4929.1  753.42  4934.1  753.42  4934.6  754.22  4960.8  754.93  4969.3  754.53
  5018.4  755.23  5077.8   755.3  5093.8  755.93  5099.5  755.38  5109.7   755.2
  5131.4  756.09  5137.2  755.64  5169.1  755.17  5180.6   754.6  5196.5  755.67
  5239.9  755.56    5321  756.59  5402.1  758.28  5483.2  759.49  5610.4  760.73
#Mann= 4 ,-1 , 0
  4436.8      .1       0  4928.6     .07       0  4934.6      .1       0
  5169.1     .05       0
Bank Sta=4928.6,4934.6
XS Rating Curve= 0 ,0
Exp/Cntr=0.3,0.1

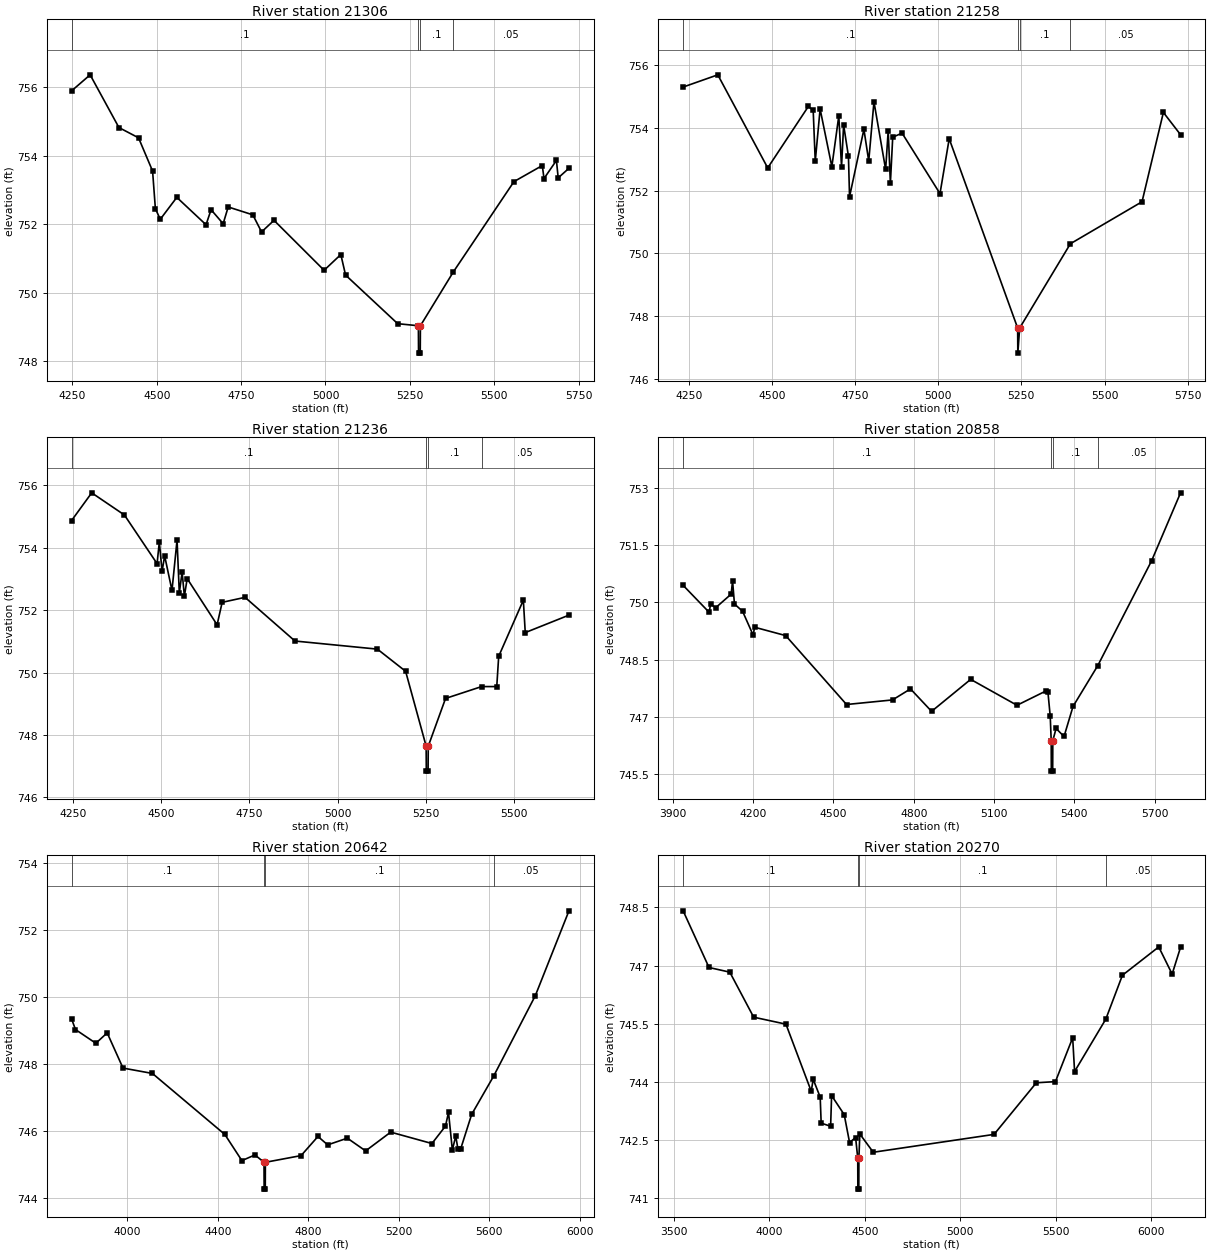
Type RM Length L Ch R = 1 ,21306   ,48,48,48
BEGIN DESCRIPTION:
Mapping XS 4420d23e
END DESCRIPTION:
XS GIS Cut Line= 6
      1971631.85     13616145.88      1971469.07     13615932.31
      1971276.36      13615799.5      1971091.47     13615554.71
      1971118.81     13615345.07       1970690.4      13615242.2
#Sta/Elev= 30
  4247.6  755.89  4302.7  756.36    4388  754.82  4446.1  754.52  4487.7  753.55
    4496  752.45  4510.5  752.14  4559.5  752.78  4646.1  751.98    4661  752.42
  4696.8  752.01  4711.7   752.5  4784.7  752.27  4810.6  751.77  4847.4  752.11
  4995.9  750.65  5045.4  751.11  5059.5  750.51  5213.9  749.09  5275.2  749.03
  5275.7  748.23  5280.7  748.23  5281.2  749.03  5378.6   750.6  5558.3  753.24
  5642.3  753.71  5647.4  753.33  5684.2  753.86  5689.4  753.35  5721.3  753.63
#Mann= 4 ,-1 , 0
  4247.6      .1       0  5275.2     .07       0  5281.2      .1       0
  5378.6     .05       0
Bank Sta=5275.2,5281.2
XS Rating Curve= 0 ,0
Exp/Cntr=0.3,0.1

Type RM Length L Ch R = 1 ,21258   ,22,22,22
BEGIN DESCRIPTION:
Mapping XS 7dfb224d
END DESCRIPTION:
XS GIS Cut Line= 6
      1971660.91     13616145.42      1971491.64     13615918.86
      1971317.16     13615786.05      1971158.31     13615551.67
      1971168.73     13615332.92      1970708.85     13615184.83
#Sta/Elev= 30
  4233.2  755.31  4337.4   755.7  4487.5  752.73  4609.6  754.69  4624.2  754.57
  4630.4  752.94    4645  754.61  4680.3  752.77  4701.2  754.39  4709.4  752.77
  4715.7   754.1  4730.2   753.1  4733.5  751.81  4776.7  753.96  4791.2  752.95
  4806.9  754.84    4842  752.68  4849.7  753.92  4856.3  752.24  4863.3  753.71
  4891.4  753.84  5005.4  751.91  5033.1  753.66  5238.9  747.62  5239.4  746.82
  5244.9  747.62  5397.4  750.31  5612.8  751.65    5677   754.5  5728.6  753.79
#Mann= 4 ,-1 , 0
  4233.2      .1       0  5238.9     .07       0  5244.9      .1       0
  5397.4     .05       0
Bank Sta=5238.9,5244.9
XS Rating Curve= 0 ,0
Exp/Cntr=0.3,0.1

Type RM Length L Ch R = 1 ,21236   ,378,378,378
BEGIN DESCRIPTION:
Mapping XS a41e07da
END DESCRIPTION:
XS GIS Cut Line= 6
      1971683.47     13616117.63      1971520.29     13615914.52
      1971357.09     13615784.31      1971188.69     13615553.41
      1971178.27      13615317.3      1970797.58     13615149.45
#Sta/Elev= 30
  4244.7  754.87    4302  755.76  4394.8  755.05  4487.6  753.49    4494  754.19
  4501.7  753.24  4509.1  753.74  4529.9  752.63  4544.3  754.25  4550.7  752.55
  4558.7  753.22  4565.1  752.45  4573.1  753.01    4658  751.53  4672.4  752.25
  4737.4  752.41  4879.1  751.01  5113.2  750.75  5193.3  750.04  5251.6  747.64
  5252.1  746.84  5257.1  746.84  5257.6  747.64  5306.7  749.17  5409.1  749.55
  5452.1  749.55  5457.6  750.52  5527.6  752.32    5533  751.28  5657.1  751.84
#Mann= 4 ,-1 , 0
  4244.7      .1       0  5251.6     .07       0  5257.6      .1       0
  5409.1     .05       0
Bank Sta=5251.6,5257.6
XS Rating Curve= 0 ,0
Exp/Cntr=0.3,0.1

Type RM Length L Ch R = 1 ,20858   ,216,216,216
BEGIN DESCRIPTION:
Mapping XS 48cce451
END DESCRIPTION:
XS GIS Cut Line= 4
      1971911.78     13616135.45      1971838.86     13615528.67
      1971151.36     13615096.38      1970718.26     13615140.46
#Sta/Elev= 30
  3938.4  750.45  4035.8  749.74  4040.9  749.96  4059.7  749.86    4118  750.22
  4123.1  750.57  4130.2  749.96  4160.4  749.77  4200.2  749.14  4205.3  749.35
  4321.6  749.13  4548.9  747.32  4720.8  747.44  4787.9  747.73  4866.8  747.14
  5012.8  747.98  5185.9   747.3  5295.4  747.68  5301.4  747.65  5310.1  747.01
  5313.7  746.37  5314.2  745.57  5319.2  745.57  5319.7  746.37  5331.9  746.69
  5361.7  746.48  5395.3  747.27  5487.6  748.34  5689.2   751.1    5797  752.88
#Mann= 4 ,-1 , 0
  3938.4      .1       0  5313.7     .07       0  5319.7      .1       0
  5487.6     .05       0
Bank Sta=5313.7,5319.7
XS Rating Curve= 0 ,0
Exp/Cntr=0.3,0.1

Type RM Length L Ch R = 1 ,20642   ,372,372,372
BEGIN DESCRIPTION:
Mapping XS 9e04805d
END DESCRIPTION:
XS GIS Cut Line= 4
       1971977.6     13616112.42      1972008.64     13615359.38
      1971249.09     13614921.01       1970716.1     13615120.34
#Sta/Elev= 30
    3753  749.35  3770.4  749.03  3860.5  748.62  3910.6  748.93  3980.6  747.88
  4110.7  747.72    4431   745.9  4506.4  745.12  4564.1  745.29  4604.2  745.07
  4604.7  744.27  4609.7  744.27  4610.2  745.07  4768.1  745.27  4842.7  745.84
  4885.8  745.59  4972.7  745.79  5053.5  745.41  5164.4  745.97  5346.8  745.63
  5406.7  746.15  5420.1  746.56    5437  745.44  5452.1  745.85  5461.9  745.46
  5473.4  745.46  5522.5   746.5  5619.6  747.64    5804  750.04  5952.7  752.57
#Mann= 4 ,-1 , 0
    3753      .1       0  4604.2     .07       0  4610.2      .1       0
  5619.6     .05       0
Bank Sta=4604.2,4610.2
XS Rating Curve= 0 ,0
Exp/Cntr=0.3,0.1

Type RM Length L Ch R = 1 ,20270   ,435,435,435
BEGIN DESCRIPTION:
Mapping XS ce16b649
END DESCRIPTION:
XS GIS Cut Line= 4
      1972057.25     13616015.74      1972206.55     13615154.66
      1971619.75     13614672.02      1970651.01     13614717.16
#Sta/Elev= 30
  3549.6  748.41  3685.1  746.95  3793.9  746.83  3918.8  745.67  4087.8  745.49
  4220.2  743.76  4230.3  744.07    4267  743.61  4272.1  742.94  4321.6  742.86
  4326.7  743.65  4392.7  743.16  4420.8  742.44  4452.3  742.57  4463.6  742.04
  4464.1  741.24  4469.1  741.24  4469.6  742.04  4474.5  742.66  4544.8  742.19
  5176.9  742.65  5398.3  743.98  5498.4  744.01  5588.5  745.14  5598.5  744.27
    5762  745.62  5848.8  746.75    6039  747.48  6109.1  746.78  6153.1  747.47
#Mann= 4 ,-1 , 0
  3549.6      .1       0  4463.6     .07       0  4469.6      .1       0
    5762     .05       0
Bank Sta=4463.6,4469.6
XS Rating Curve= 0 ,0
Exp/Cntr=0.3,0.1

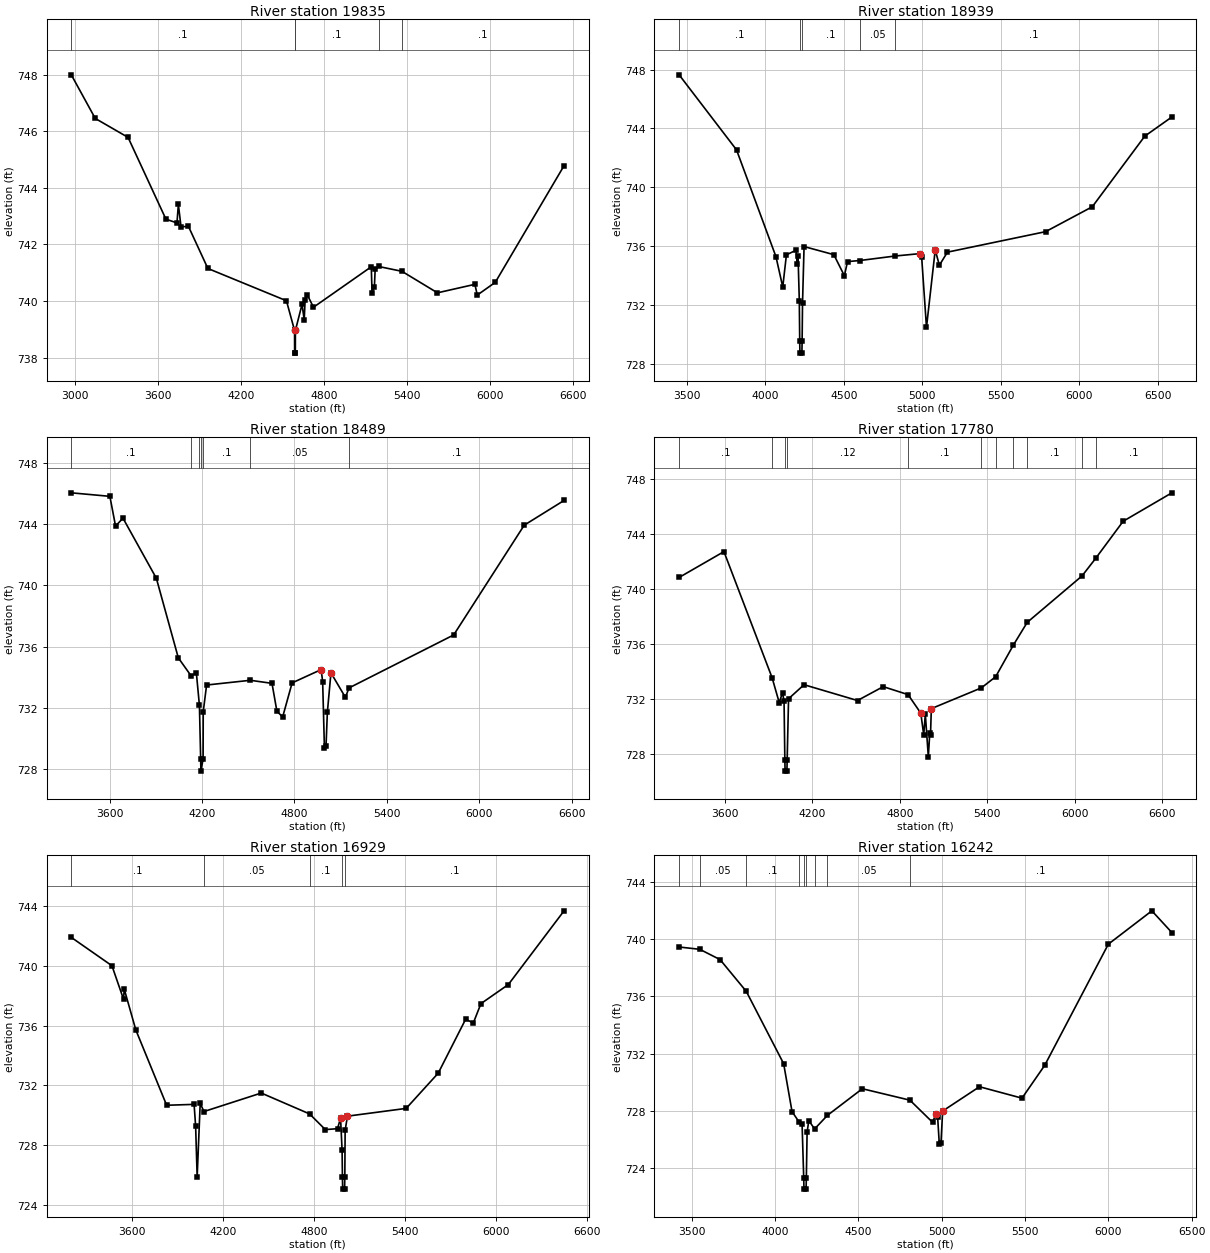
Type RM Length L Ch R = 1 ,19835   ,896,896,896
BEGIN DESCRIPTION:
Mapping XS 2496817f
END DESCRIPTION:
XS GIS Cut Line= 4
      1972081.54     13616001.93      1972439.19     13614682.44
      1971269.05     13614109.52      1970378.34     13614147.65
#Sta/Elev= 30
  2974.3  747.99  3147.3  746.45  3384.6  745.78  3658.3  742.89    3738  742.76
  3748.2  743.41  3767.4  742.62  3820.7  742.64  3961.4  741.15  4529.3  740.01
    4588  738.96  4588.5  738.16  4593.5  738.16    4594  738.96  4641.9  739.88
  4657.8  739.34  4664.4  740.05  4680.1  740.22  4724.6  739.78  5142.5  741.21
  5148.1   740.3    5165   740.5  5170.6  741.12  5195.7  741.22  5363.9  741.05
  5620.7  740.29  5891.4  740.59  5908.6  740.21  6038.7  740.66  6535.8  744.78
#Mann= 5 ,-1 , 0
  2974.3      .1       0    4588     .07       0    4594      .1       0
  5195.7     .05       0  5363.9      .1       0
Bank Sta=4588,4594
XS Rating Curve= 0 ,0
Exp/Cntr=0.3,0.1

Type RM Length L Ch R = 1 ,18939   ,450,450,450
BEGIN DESCRIPTION:
Mapping XS 0e308dbb
END DESCRIPTION:
XS GIS Cut Line= 2
      1973461.55     13613276.32      1970400.75     13613957.14
#Sta/Elev= 30
  3452.2  747.64  3817.5  742.55  4068.2  735.31  4111.7  733.25    4135  735.43
  4196.5  735.74  4203.8  734.81    4209  735.36    4217  732.32  4219.6  729.56
    4221  728.76  4233.5  728.76  4234.9  729.56  4237.5  732.16  4247.3  735.99
  4436.8  735.44  4503.8  734.01  4523.8  734.97  4600.2  735.04  4828.3  735.35
  4984.6  735.51  4995.6  735.27  5026.3  730.51  5081.9  735.76  5108.3  734.72
  5159.5  735.61  5784.4     737  6081.5  738.69  6415.6  743.48  6587.8  744.78
#Mann= 5 ,-1 , 0
  3452.2      .1       0  4219.6     .07       0  4234.9      .1       0
  4600.2     .05       0  4828.3      .1       0
Bank Sta=4984.6,5081.9
XS Rating Curve= 0 ,0
Exp/Cntr=0.3,0.1

Type RM Length L Ch R = 1 ,18489   ,709,709,709
BEGIN DESCRIPTION:
Mapping XS 33c15bfd
END DESCRIPTION:
XS GIS Cut Line= 2
       1973350.5     13612672.14      1970341.74     13613762.69
#Sta/Elev= 30
  3351.1  746.07  3601.6  745.84  3638.5  743.89  3686.7  744.41  3903.6  740.47
  4046.1  735.26  4129.3  734.08  4163.3  734.28  4183.2  732.15  4191.3  728.64
  4192.9  727.84  4207.1  728.64  4207.9  731.73  4229.8  733.48  4513.7  733.79
  4654.6  733.59  4686.5  731.76  4723.9  731.39  4785.2  733.62  4973.7  734.49
  4983.6  733.71    4995  729.38  5005.6  729.51  5014.2   731.7  5037.5  734.28
  5131.4  732.67  5154.7  733.29  5834.6  736.76  6292.7  743.95  6551.4  745.57
#Mann= 7 ,-1 , 0
  3351.1      .1       0  4129.3     .12       0  4183.2      .1       0
  4191.3     .03       0  4207.1      .1       0  4513.7     .05       0
  5154.7      .1       0
Bank Sta=4973.7,5037.5
XS Rating Curve= 0 ,0
Exp/Cntr=0.3,0.1

Type RM Length L Ch R = 1 ,17780   ,851,851,851
BEGIN DESCRIPTION:
Mapping XS be5319b9
END DESCRIPTION:
XS GIS Cut Line= 2
      1973253.25     13612283.26      1969974.44      13613100.4
#Sta/Elev= 30
  3286.7  740.82  3594.1   742.7  3924.3  733.52  3973.2  731.71    3996  732.44
  4006.3  731.79  4011.8  727.52  4013.4  726.72    4026  726.72  4027.6  727.52
  4037.2  731.99  4143.5  733.01    4510  731.86  4686.5  732.87  4856.7  732.29
  4944.1  730.94  4964.1  729.36  4975.1  730.86  4995.7  727.77  5005.4  729.46
  5010.6  729.33  5016.3  731.27  5359.3  732.78  5457.3  733.59  5579.7  735.91
  5673.9  737.55  6049.7  740.93  6143.4  742.21  6331.8  744.91  6665.8  746.98
#Mann= 11 ,-1 , 0
  3286.7      .1       0  3924.3     .12       0  4011.8     .07       0
  4027.6     .12       0  4856.7      .1       0  5359.3     .05       0
  5457.3      .1       0  5579.7     .05       0  5673.9      .1       0
  6049.7     .05       0  6143.4      .1       0
Bank Sta=4944.1,5016.3
XS Rating Curve= 0 ,0
Exp/Cntr=0.3,0.1

Type RM Length L Ch R = 1 ,16929   ,687,687,687
BEGIN DESCRIPTION:
Mapping XS df597657
END DESCRIPTION:
XS GIS Cut Line= 2
      1973169.86     13611727.71      1969940.22     13612124.25
#Sta/Elev= 30
  3197.5  741.91  3465.9  740.01  3542.2  737.77  3547.2  738.44  3623.5  735.71
  3827.1  730.66  4008.4  730.72  4018.5  729.26  4028.6  725.86  4048.7  730.79
  4073.5  730.24  4451.9  731.48    4771  730.08  4874.9  729.03  4955.5  729.09
  4975.6   729.8  4985.7  727.64  4987.9  725.84  4989.5  725.04  5002.1  725.04
  5003.7  725.84  5005.8  728.98  5021.2  729.93  5408.8  730.45  5620.4  732.81
  5801.8  736.43  5852.1  736.17  5902.5  737.47  6083.6  738.75  6451.4  743.69
#Mann= 5 ,-1 , 0
  3197.5      .1       0  4073.5     .05       0    4771      .1       0
  4987.9     .07       0  5003.7      .1       0
Bank Sta=4975.6,5021.2
XS Rating Curve= 0 ,0
Exp/Cntr=0.3,0.1

Type RM Length L Ch R = 1 ,16242   ,569,569,569
BEGIN DESCRIPTION:
Mapping XS 8735e7a4
END DESCRIPTION:
XS GIS Cut Line= 2
      1973079.65     13611199.93      1970135.51     13611473.21
#Sta/Elev= 30
  3424.4  739.46  3548.2   739.3  3670.1  738.58  3827.3  736.36  4051.7   731.3
    4102  727.95  4143.9  727.23  4162.2   727.1    4172  723.33  4173.6  722.53
  4186.2  722.53  4187.9  723.33  4192.3  726.49  4202.4  727.32  4237.5  726.74
  4314.6  727.69  4523.8  729.55  4809.4  728.75  4945.6   727.2  4965.7  727.81
  4975.7  727.57  4985.7  725.67  4995.8  725.77  5005.8  727.99  5226.8  729.69
  5481.9  728.89  5618.4  731.19  6000.1  739.66  6261.2  741.99  6381.2  740.47
#Mann= 9 ,-1 , 0
  3424.4      .1       0  3548.2     .05       0  3827.3      .1       0
  4143.9     .12       0    4172     .07       0  4187.9     .12       0
  4237.5      .1       0  4314.6     .05       0  4809.4      .1       0
Bank Sta=4965.7,5005.8
XS Rating Curve= 0 ,0
Exp/Cntr=0.3,0.1

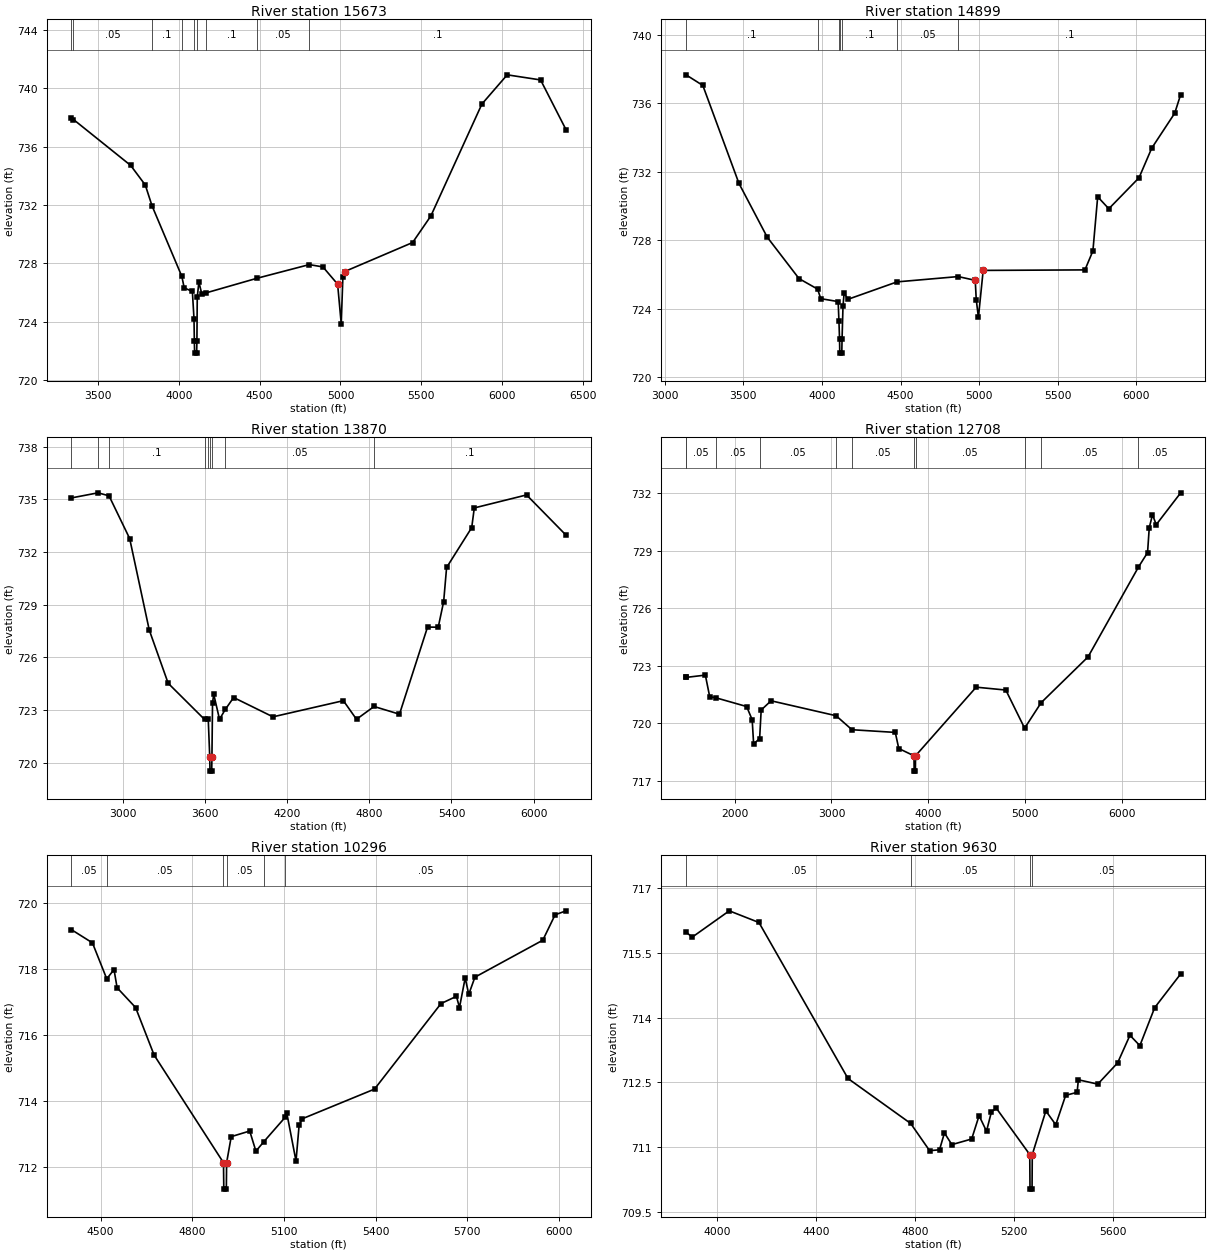
Type RM Length L Ch R = 1 ,15673   ,774,774,774
BEGIN DESCRIPTION:
Mapping XS a955626e
END DESCRIPTION:
XS GIS Cut Line= 3
      1973079.66     13611005.49      1971714.64     13610877.59
      1970070.47     13611256.19
#Sta/Elev= 30
  3336.4  737.94  3349.3  737.85  3702.7  734.71  3793.1  733.37    3835  731.94
  4019.3  727.11  4033.7  726.33  4084.3  726.08  4094.4  724.22  4096.5  722.66
  4098.1  721.86  4110.7  721.86  4112.4  722.66  4114.5  725.68  4124.5  726.73
  4142.6  725.91  4167.6  725.98  4482.4  726.98  4807.1  727.92  4891.5  727.76
  4982.3  726.58  5004.6  723.87  5014.9  727.09  5025.1  727.44  5445.9  729.43
  5558.8  731.25  5874.3  738.91  6030.8  740.91  6237.2  740.56  6394.6  737.15
#Mann= 9 ,-1 , 0
  3336.4      .1       0  3349.3     .05       0    3835      .1       0
  4019.3     .12       0  4096.5     .07       0  4112.4     .12       0
  4167.6      .1       0  4482.4     .05       0  4807.1      .1       0
Bank Sta=4982.3,5025.1
XS Rating Curve= 0 ,0
Exp/Cntr=0.3,0.1

Type RM Length L Ch R = 1 ,14899   ,1029,1029,1029
BEGIN DESCRIPTION:
Mapping XS 4b761814
END DESCRIPTION:
XS GIS Cut Line= 3
      1973142.08     13610755.48      1971704.62      13610241.6
      1970102.98     13610485.79
#Sta/Elev= 30
  3135.5  737.65  3242.4  737.03  3472.2  731.31  3652.1  728.17  3854.5  725.75
  3972.3  725.14  3992.6  724.58  4103.2  724.41  4108.2  723.28  4112.1   722.2
  4113.7   721.4  4126.3   721.4    4128   722.2    4134  724.13  4141.3  724.92
  4164.8  724.54  4477.9  725.56  4866.8  725.87  4975.3  725.65  4981.7  724.52
  4995.5  723.49  5025.8  726.23  5673.2  726.26  5723.8  727.37  5754.2  730.53
    5825  729.83  6017.2  731.64  6098.1  733.37  6244.3  735.41  6282.2   736.5
#Mann= 7 ,-1 , 0
  3135.5      .1       0  3972.3     .12       0  4108.2      .1       0
  4112.1     .07       0    4128      .1       0  4477.9     .05       0
  4866.8      .1       0
Bank Sta=4975.3,5025.8
XS Rating Curve= 0 ,0
Exp/Cntr=0.3,0.1

Type RM Length L Ch R = 1 ,13870   ,1162,1162,1162
BEGIN DESCRIPTION:
Mapping XS 11fe06d1
END DESCRIPTION:
XS GIS Cut Line= 3
      1973294.86     13610422.13      1971546.58     13609304.84
      1970113.84     13609878.15
#Sta/Elev= 30
    2620  735.08  2814.7  735.37  2895.2   735.2  3046.1  732.77  3189.5  727.56
  3327.8  724.53  3594.1  722.47  3620.8  722.51  3631.9  720.33  3633.6  719.53
  3646.2  719.53  3647.9  720.33  3652.3  723.42  3661.1   723.9  3703.4  722.48
  3745.5  723.04  3806.6  723.72  4094.2  722.62  4609.3  723.54  4705.3  722.48
  4833.7  723.21  5019.6  722.77  5224.9  727.73    5303  727.72  5342.8  729.18
  5364.3  731.12    5548  733.39  5566.8  734.51  5949.1  735.25    6238  732.96
#Mann= 9 ,-1 , 0
    2620      .1       0  2814.7     .05       0  2895.2      .1       0
  3594.1     .12       0  3620.8      .1       0  3631.9     .05       0
  3647.9      .1       0  3745.5     .05       0  4833.7      .1       0
Bank Sta=3631.9,3647.9
XS Rating Curve= 0 ,0
Exp/Cntr=0.3,0.1

Type RM Length L Ch R = 1 ,12708   ,2412,2412,2412
BEGIN DESCRIPTION:
Mapping XS ee220f2d
END DESCRIPTION:
XS GIS Cut Line= 4
      1973850.48     13609727.73      1971869.84     13608408.25
      1970308.72     13608733.19      1969989.27     13609823.47
#Sta/Elev= 30
  1497.5  722.41    1499  722.39  1697.1  722.51  1742.2  721.38  1803.4  721.33
  2123.8  720.87  2180.9  720.18  2195.9  718.92  2257.9   719.2    2274  720.69
  2376.2  721.17  3047.8  720.39  3211.8  719.66  3659.4  719.52  3695.4  718.68
  3852.7   718.3  3854.4   717.5    3867   717.5  3868.7   718.3  4495.2  721.88
  4801.6  721.73  4995.6  719.74  5166.2  721.07    5651  723.46  6172.2  728.15
  6265.8   728.9  6283.4   730.2  6316.9  730.88  6355.5  730.36  6608.1  732.02
#Mann= 11 ,-1 , 0
  1497.5     .05       0    1499     .05       0  1803.4     .05       0
  2257.9     .05       0  3047.8     .05       0  3211.8     .05       0
  3852.7     .05       0  3868.7     .05       0  4995.6     .05       0
  5166.2     .05       0  6172.2     .05       0
Bank Sta=3852.7,3868.7
XS Rating Curve= 0 ,0
Exp/Cntr=0.3,0.1

Type RM Length L Ch R = 1 ,10296   ,666,666,666
BEGIN DESCRIPTION:
Mapping XS 7fcb933a
END DESCRIPTION:
XS GIS Cut Line= 2
      1971253.16      13606531.8      1969649.54      13606316.6
#Sta/Elev= 30
  4404.6   719.2  4473.4   718.8  4520.2  717.71    4544  717.99  4554.1  717.44
  4614.6  716.84  4675.2   715.4  4902.1  712.14  4903.1  711.34  4911.4  711.34
  4912.3  712.14  4927.4  712.93  4987.9   713.1  5008.1  712.49  5033.4  712.77
  5103.3  713.51    5109  713.65  5139.3  712.19  5149.4  713.27  5159.5  713.47
  5396.1  714.37  5613.5  716.96    5664  717.18    5674  716.84  5692.7  717.74
  5704.3  717.24  5724.5  717.76  5946.5  718.88  5986.8  719.65  6022.6  719.77
#Mann= 6 ,-1 , 0
  4404.6     .05       0  4520.2     .05       0  4902.1     .05       0
  4912.3     .05       0  5033.4     .05       0  5103.3     .05       0
Bank Sta=4902.1,4912.3
XS Rating Curve= 0 ,0
Exp/Cntr=0.3,0.1

Type RM Length L Ch R = 1 ,9630    ,150,150,150
BEGIN DESCRIPTION:
Mapping XS afe8ad30
END DESCRIPTION:
XS GIS Cut Line= 2
      1972169.82     13605948.47      1970169.91     13605899.86
#Sta/Elev= 30
  3873.1  715.98  3897.9  715.86    4048  716.47    4168   716.2  4528.1  712.59
  4781.6  711.55  4858.2  710.92  4898.2  710.94  4918.2  711.33  4948.2  711.06
  5028.3  711.19  5058.3  711.73  5088.3  711.37  5108.3  711.82  5128.3   711.9
  5263.2  710.83  5264.2  710.03  5272.5  710.03  5273.4  710.83  5328.3  711.84
  5368.4  711.52  5408.4   712.2  5454.8  712.27  5459.8  712.56  5538.4  712.46
  5618.4  712.95  5668.4  713.59  5708.5  713.35  5768.5  714.23  5873.6  715.01
#Mann= 4 ,-1 , 0
  3873.1     .05       0  4781.6     .05       0  5263.2     .05       0
  5273.4     .05       0
Bank Sta=5263.2,5273.4
XS Rating Curve= 0 ,0
Exp/Cntr=0.3,0.1