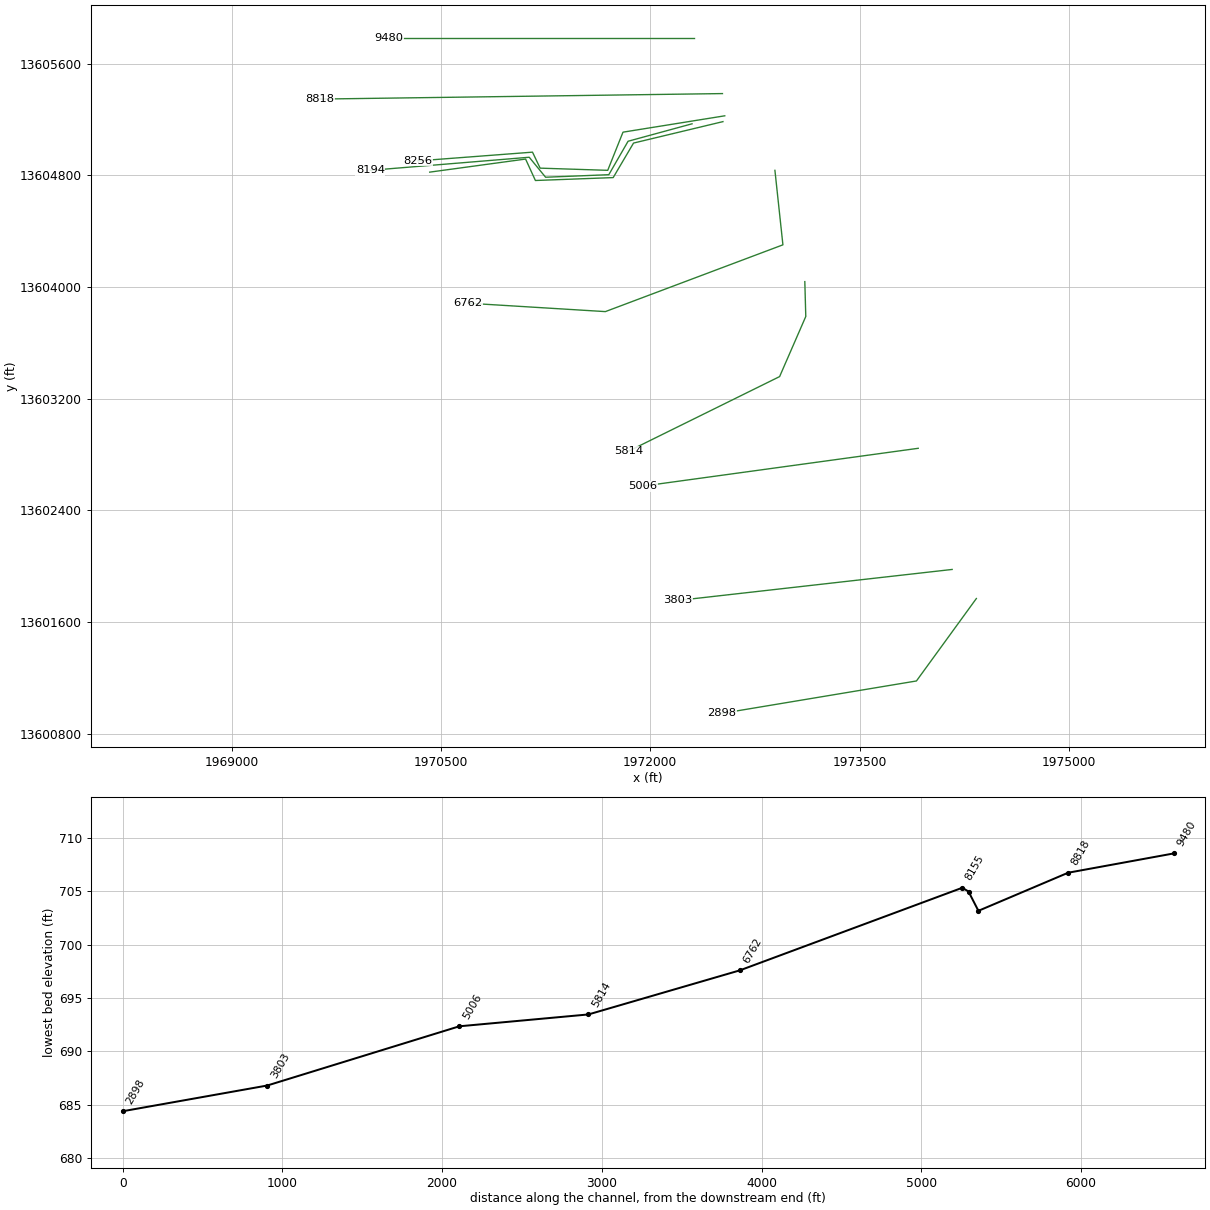
HEC-RAS study UNT 042 in BCW.prj: UNT 042 in BCW Base Level Engineering

--- UNT 042 in BCW.g01 (geometry) --- (continued)

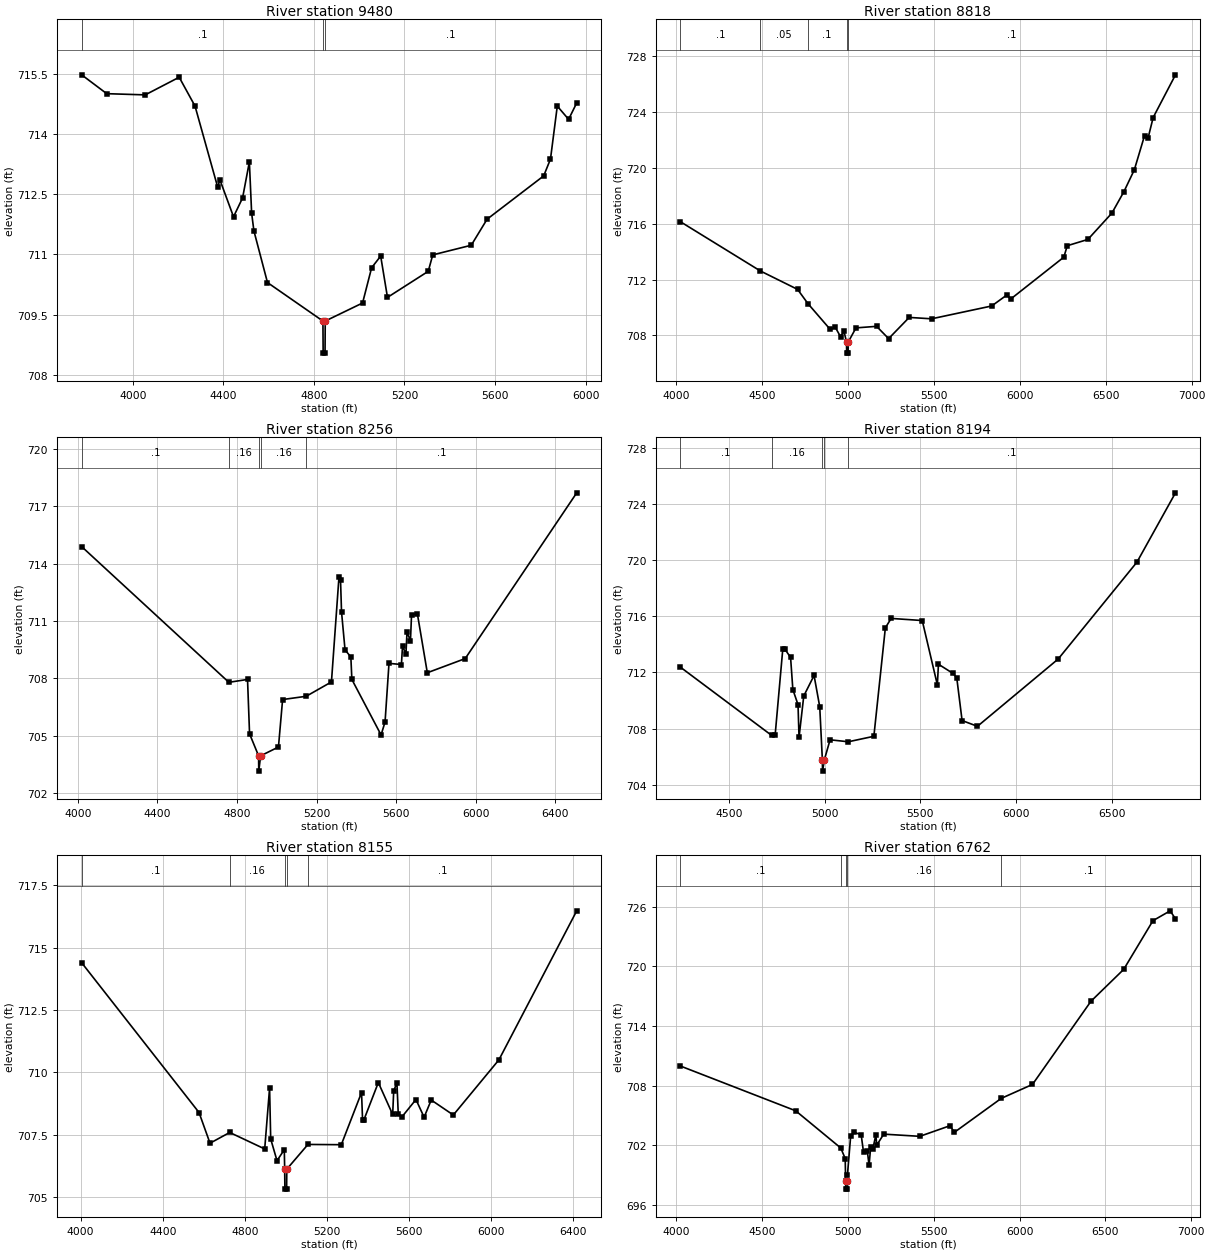
Type RM Length L Ch R = 1 ,9480    ,662,662,662
BEGIN DESCRIPTION:
Mapping XS 54aa93c1
END DESCRIPTION:
XS GIS Cut Line= 2
      1972315.71      13605781.8      1970129.11      13605781.8
#Sta/Elev= 30
  3774.3  715.48    3885  715.01    4055  714.98    4205  715.42    4275   714.7
    4375  712.68    4385  712.86    4445  711.94    4485  712.41    4515  713.31
    4525  712.03    4535  711.59    4595   710.3  4839.9  709.34  4840.9  708.54
  4849.2  708.54  4850.1  709.34    5015  709.79    5055  710.67    5095  710.96
    5125  709.93    5305  710.58    5325  710.99    5495  711.23    5565  711.88
    5815  712.96    5845  713.38    5875   714.7    5925  714.37  5960.9  714.78
#Mann= 3 ,-1 , 0
  3774.3      .1       0  4839.9     .07       0  4850.1      .1       0
Bank Sta=4839.9,4850.1
XS Rating Curve= 0 ,0
Exp/Cntr=0.3,0.1

Type RM Length L Ch R = 1 ,8818    ,562,562,562
BEGIN DESCRIPTION:
Mapping XS ca7e06e2
END DESCRIPTION:
XS GIS Cut Line= 2
      1972517.01     13605385.97      1969635.08     13605346.67
#Sta/Elev= 30
  4023.7  716.15  4489.1  712.62  4705.8   711.3    4766  710.28  4895.8  708.43
  4925.8  708.57  4955.8  707.91  4975.8   708.3  4990.7  707.53  4991.6  706.73
  4999.9  706.73  5000.9  707.53  5045.8  708.54  5165.8  708.65  5235.8  707.77
  5355.8  709.29  5485.8  709.19  5835.9  710.11  5924.5   710.9  5945.9   710.6
  6255.9  713.61  6275.9  714.43  6395.9  714.88  6535.9  716.77  6605.9  718.31
  6666.3  719.87    6726  722.33    6746  722.13    6776  723.62  6905.9  726.68
#Mann= 5 ,-1 , 0
  4023.7      .1       0  4489.1     .05       0    4766      .1       0
  4990.7     .07       0  5000.9      .1       0
Bank Sta=4990.7,5000.9
XS Rating Curve= 0 ,0
Exp/Cntr=0.3,0.1

Type RM Length L Ch R = 1 ,8256    ,62,62,62
BEGIN DESCRIPTION:
Mapping XS eb96a7da
END DESCRIPTION:
XS GIS Cut Line= 6
      1972533.75     13605226.69      1971804.55      13605109.5
      1971695.17     13604836.06       1971210.8     13604851.69
      1971156.11     13604966.27      1970335.79     13604903.77
#Sta/Elev= 30
  4018.7  714.89  4758.9   707.8  4852.8  707.95    4863  705.11  4908.4  703.96
  4909.3  703.16  4918.7  703.96  5008.3  704.42  5029.2   706.9  5147.7  707.07
  5274.8  707.82  5312.5  713.28  5320.4  713.17  5325.5  711.48  5343.1   709.5
  5372.4  709.12  5377.5  707.95  5524.4  705.05  5544.4  705.73  5564.2  708.79
  5626.7  708.73  5632.2  709.69  5649.4  709.28  5654.9  710.44  5672.1  709.96
  5677.6  711.32  5706.8  711.39  5756.9   708.3  5947.5  709.04  6508.3   717.7
#Mann= 5 ,-1 , 0
  4018.7      .1       0  4758.9     .16       0  4908.4     .07       0
  4918.7     .16       0  5147.7      .1       0
Bank Sta=4908.4,4918.7
XS Rating Curve= 0 ,0
Exp/Cntr=0.3,0.1

Type RM Length L Ch R = 1 ,8194    ,39,39,39
BEGIN DESCRIPTION:
Mapping XS fa234dcd
END DESCRIPTION:
XS GIS Cut Line= 6
      1972299.32     13605169.39      1971841.01      13605044.4
      1971702.99     13604804.81      1971249.86     13604786.58
      1971132.67     13604929.81      1969994.63     13604836.06
#Sta/Elev= 30
    4247  712.37  4722.6  707.52  4741.5  707.53  4781.6  713.68  4791.6  713.67
  4822.2  713.06    4834  710.78    4861   709.7  4866.3  707.37    4891  710.32
  4944.8  711.78  4974.4  709.55  4988.1  705.77  4989.1  704.97  4998.4  705.77
  5028.3   707.2  5123.7  707.06    5257  707.45    5317  715.17  5347.2  715.84
  5509.5  715.69  5588.5  711.11  5594.1  712.58  5670.8  711.92  5689.8  711.61
  5717.6  708.57  5797.8  708.16  6219.3  712.95  6630.7  719.85  6831.7  724.78
#Mann= 5 ,-1 , 0
    4247      .1       0  4722.6     .16       0  4988.1     .07       0
  4998.4     .16       0  5123.7      .1       0
Bank Sta=4988.1,4998.4
XS Rating Curve= 0 ,0
Exp/Cntr=0.3,0.1

Type RM Length L Ch R = 1 ,8155    ,1393,1393,1393
BEGIN DESCRIPTION:
Mapping XS 6dc87e15
END DESCRIPTION:
XS GIS Cut Line= 6
      1972520.66     13605185.01      1971880.07     13605031.38
      1971734.24     13604783.98      1971176.94     13604763.15
      1971106.63     13604916.79      1970419.59      13604823.1
#Sta/Elev= 30
  4005.4  714.39  4576.8  708.39  4630.3  707.16  4726.3  707.59  4896.6  706.93
  4920.4  709.37  4925.8  707.33  4956.5  706.46    4992   706.9  4993.9  706.12
  4994.9  705.32  5003.3  705.32  5004.2  706.12  5107.2  707.11  5269.6   707.1
  5368.1  709.19  5373.1   708.1  5379.8   708.1  5449.9  709.59  5519.7  708.31
  5524.7  709.25  5540.4  709.59  5546.9  708.33  5565.3  708.22  5633.1  708.91
  5672.8   708.2  5707.4  708.89    5815  708.29    6037   710.5  6415.9  716.47
#Mann= 5 ,-1 , 0
  4005.4      .1       0  4726.3     .16       0  4993.9     .07       0
  5004.2     .16       0  5107.2      .1       0
Bank Sta=4993.9,5004.2
XS Rating Curve= 0 ,0
Exp/Cntr=0.3,0.1

Type RM Length L Ch R = 1 ,6762    ,948,948,948
BEGIN DESCRIPTION:
Mapping XS 00089f98
END DESCRIPTION:
XS GIS Cut Line= 4
      1972893.09     13604836.05      1972950.38     13604302.21
      1971678.25     13603823.76      1970694.13       13603884.
#Sta/Elev= 30
  4025.5  709.96  4696.4  705.46  4958.8  701.72  4984.8  700.66  4987.3  698.38
  4988.2  697.58  4996.7  697.58  4997.6  698.38  4997.8  699.01  5016.9  702.97
  5038.2  703.29  5077.8  703.04  5091.7  701.27  5113.4  701.45  5123.7  699.96
  5132.9  701.79  5145.1  701.59  5163.2  703.02  5168.5  702.01  5209.2  703.11
  5419.2  702.89  5595.2  703.96  5620.1  703.29  5893.5  706.71  6075.1  708.11
  6415.7  716.48  6606.1  719.68  6776.4  724.58  6876.6  725.57  6907.5  724.76
#Mann= 5 ,-1 , 0
  4025.5      .1       0  4958.8     .16       0  4987.3     .07       0
  4997.6     .16       0  5893.5      .1       0
Bank Sta=4987.3,4997.6
XS Rating Curve= 0 ,0
Exp/Cntr=0.3,0.1

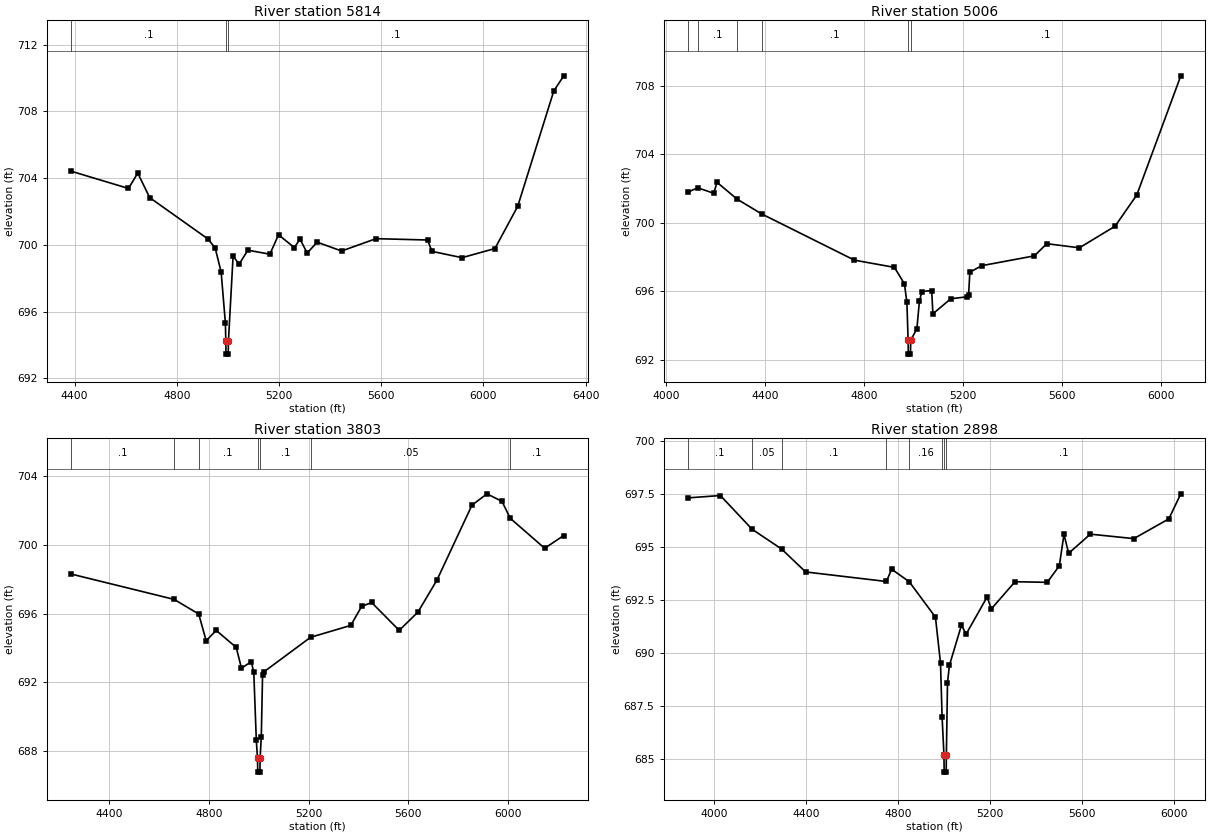
Type RM Length L Ch R = 1 ,5814    ,808,808,808
BEGIN DESCRIPTION:
Mapping XS e9b1708e
END DESCRIPTION:
XS GIS Cut Line= 4
      1973107.33      13604038.7      1973114.27     13603788.74
      1972926.77     13603358.19      1971843.42     13602823.45
#Sta/Elev= 30
    4387  704.41  4610.8  703.38  4647.2   704.3    4694  702.83  4921.3  700.36
  4950.1  699.82  4973.6  698.37  4990.2  695.32  4991.8  694.25  4992.7  693.45
  5001.3  693.45  5002.2  694.25  5020.4  699.33  5043.9  698.84  5078.2  699.68
  5164.4  699.44  5198.2   700.6    5260  699.84  5282.4  700.34  5310.4  699.51
  5349.7  700.16  5445.1  699.63  5579.8  700.37  5781.8  700.29  5798.7  699.61
  5916.5  699.23  6045.4  699.78  6134.6  702.31  6275.7  709.22  6314.8  710.13
#Mann= 3 ,-1 , 0
    4387      .1       0  4991.8     .07       0  5002.2      .1       0
Bank Sta=4991.8,5002.2
XS Rating Curve= 0 ,0
Exp/Cntr=0.3,0.1

Type RM Length L Ch R = 1 ,5006    ,1203,1203,1203
BEGIN DESCRIPTION:
Mapping XS 00c9acdd
END DESCRIPTION:
XS GIS Cut Line= 2
      1973919.84      13602844.3      1971948.84     13602573.64
#Sta/Elev= 30
  4089.7   701.8  4127.9  702.04  4192.6  701.72  4205.6  702.36  4286.6  701.38
  4385.5  700.52  4760.8  697.82  4922.3   697.4  4962.7  696.44  4972.7  695.36
  4977.6  693.14  4978.5  692.34  4987.2  692.34    4988  693.14  5013.1  693.83
  5023.2  695.42  5033.3  695.99  5072.8  696.05  5077.8  694.69  5149.9  695.57
    5215  695.68    5222   695.8    5227  697.12  5275.6   697.5  5487.5  698.07
    5538  698.78  5669.6  698.54  5813.7   699.8  5901.4  701.62  6079.2  708.57
#Mann= 6 ,-1 , 0
  4089.7     .05       0  4127.9      .1       0  4286.6     .05       0
  4385.5      .1       0  4977.6     .07       0    4988      .1       0
Bank Sta=4977.6,4988
XS Rating Curve= 0 ,0
Exp/Cntr=0.3,0.1

Type RM Length L Ch R = 1 ,3803    ,905,905,905
BEGIN DESCRIPTION:
Mapping XS 33b4d55c
END DESCRIPTION:
XS GIS Cut Line= 2
      1974162.89     13601976.25      1972198.81     13601754.16
#Sta/Elev= 30
  4247.7  698.29  4660.5  696.82  4759.2  695.97    4789  694.42  4829.3  695.02
  4909.8  694.03  4930.6  692.83  4970.2   693.2  4980.2  692.58  4990.3  688.65
  4995.1  687.59    4996  686.79  5004.7  686.79  5005.6  687.59  5010.3  688.84
  5015.4  692.41  5020.5  692.61  5208.2  694.62  5369.5  695.31    5413  696.41
  5453.2  696.64  5563.9  695.02  5638.9  696.08  5714.9  697.93  5855.8  702.29
  5916.2  702.95  5976.5  702.51  6009.4  701.53  6147.6  699.79  6224.3  700.53
#Mann= 7 ,-1 , 0
  4247.7      .1       0  4660.5     .08       0  4759.2      .1       0
  4995.1     .07       0  5005.6      .1       0  5208.2     .05       0
  6009.4      .1       0
Bank Sta=4995.1,5005.6
XS Rating Curve= 0 ,0
Exp/Cntr=0.3,0.1

Type RM Length L Ch R = 1 ,2898    ,0,0,0
BEGIN DESCRIPTION:
UNT 042 in BCW 8.0
END DESCRIPTION:
XS GIS Cut Line= 3
      1974336.51     13601767.93      1973907.16     13601177.26
      1972513.61       13600945.
#Sta/Elev= 30
  3887.8   697.3  4027.4  697.41  4165.4  695.82  4293.7  694.89  4398.3  693.81
  4749.9  693.36  4772.3  693.94  4849.1  693.35  4963.1  691.68  4985.2  689.52
  4992.1  686.98  5000.2  685.18  5001.1  684.38  5009.9  684.38  5010.7  685.18
  5015.6  688.59  5023.9  689.41  5076.4   691.3  5096.7  690.88  5187.9  692.63
  5206.4  692.07  5309.6  693.35  5449.7  693.32  5502.2   694.1  5522.5  695.58
  5542.8  694.69  5637.3  695.59  5826.6  695.38  5978.7  696.31  6030.8  697.49
#Mann= 8 ,-1 , 0
  3887.8      .1       0  4165.4     .05       0  4293.7      .1       0
  4749.9     .08       0  4849.1     .16       0  4992.1      .1       0
  5000.2     .07       0  5010.7      .1       0
Bank Sta=5000.2,5010.7
XS Rating Curve= 0 ,0
Exp/Cntr=0.3,0.1
LCMann Table=0

Chan Stop Cuts=-1
Use User Specified Reach Order=0
Composite Channel Slope=5