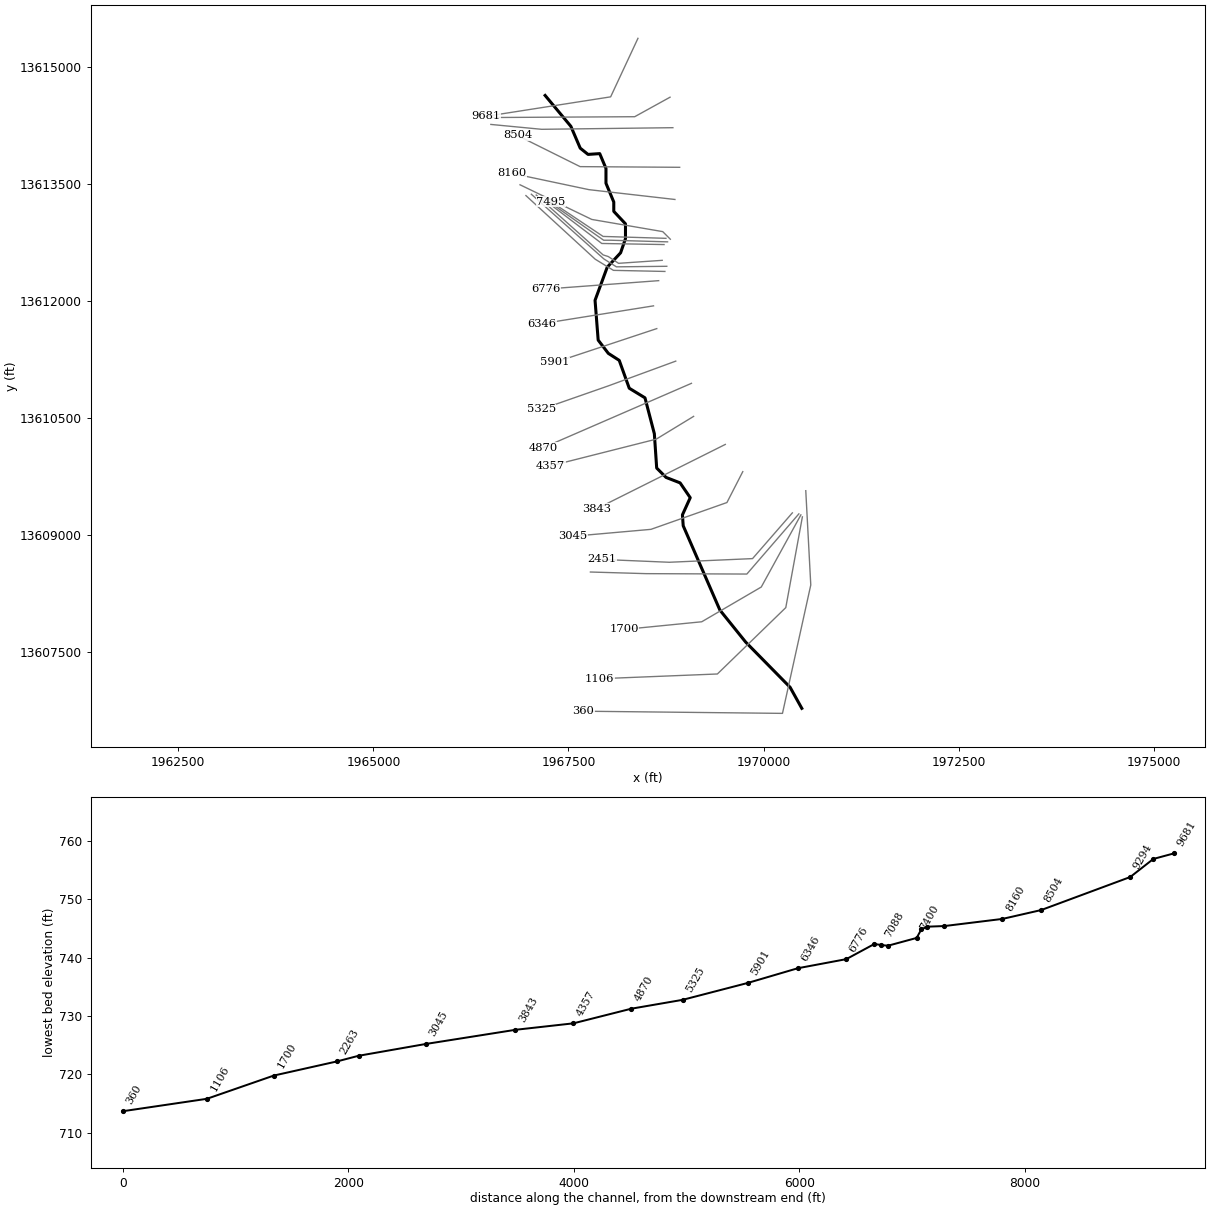
--- UNT 043 in BCW.prj (project) ---

Proj Title=UNT 043 in BCW Base Level Engineering
Current Plan=p01
Default Exp/Contr=0.3,0.1
English Units
Geom File=g01
Flow File=f01
Plan File=p01
BEGIN DESCRIPTION:
UNT 043 in BCW
END DESCRIPTION:

--- UNT 043 in BCW.p01 (plan) ---

Plan Title=Multiple Run
Short Identifier=Multiple
Geom File=g01
Flow File=f01
Subcritical Flow
K Sum by GR= 0
Std Step Tol= 0.01
Critical Tol= 0.01
Num of Std Step Trials= 20
Max Error Tol= 0.3
Flow Tol Ratio= 0.001
Split Flow NTrial= 30
Split Flow Tol= 0.02
Split Flow Ratio= 0.02
Log Output Level= 0
Friction Slope Method= 1
Unsteady Friction Slope Method= 2
Unsteady Bridges Friction Slope Method= 1
Parabolic Critical Depth
Global Vel Dist=  1 , 1 , 1
Global Log Level= 0
CheckData=True
Encroach Param= -1, 0, 0, 0
BEGIN DESCRIPTION:
Multiple Run
END DESCRIPTION:

--- UNT 043 in BCW.f01 (steady flow) ---

Flow Title=Multiple
Number of Profiles=7
Profile Names=10-year,25-year,50-year,1pct_min,100-year,1pct_plu,500-year
River Rch & RM= UNT 043 in BCW,Reach-1,9681
     548     765     945     577    1152    2298    1713
River Rch & RM= UNT 043 in BCW,Reach-1,7025
     859    1234    1551     964    1923    3838    2960
River Rch & RM= UNT 043 in BCW,Reach-1,5325
     927    1334    1680    1046    2086    4162    3219
River Rch & RM= UNT 043 in BCW,Reach-1,3843
    1117    1620    2050    1281    2555    5099    3976
Boundary for River Rch & Prof#=UNT 043 in BCW,Reach-1,1
Up Type=0
Dn Type=3
Dn Slope=0.005
Boundary for River Rch & Prof#=UNT 043 in BCW,Reach-1,2
Up Type=0
Dn Type=3
Dn Slope=0.005
Boundary for River Rch & Prof#=UNT 043 in BCW,Reach-1,3
Up Type=0
Dn Type=3
Dn Slope=0.005
Boundary for River Rch & Prof#=UNT 043 in BCW,Reach-1,4
Up Type=0
Dn Type=3
Dn Slope=0.005
Boundary for River Rch & Prof#=UNT 043 in BCW,Reach-1,5
Up Type=0
Dn Type=3
Dn Slope=0.005
Boundary for River Rch & Prof#=UNT 043 in BCW,Reach-1,6
Up Type=0
Dn Type=3
Dn Slope=0.005
Boundary for River Rch & Prof#=UNT 043 in BCW,Reach-1,7
Up Type=0
Dn Type=3
Dn Slope=0.005

--- UNT 043 in BCW.g01 (geometry) ---

Geom Title=Existing Conditions

River Reach=UNT 043 in BCW,Reach-1
Reach XY= 30
      1967200.92     13614630.16      1967530.80     13614234.54
      1967650.80     13613954.54      1967750.80     13613874.54
      1967900.80     13613884.54      1967980.80     13613694.54
      1967980.80     13613504.54      1968080.80     13613264.54
      1968080.80     13613144.54      1968230.80     13612984.54
      1968230.80     13612794.54      1968168.37     13612613.67
      1967996.93     13612429.21      1967840.80     13612004.54
      1967880.80     13611494.54      1968010.80     13611324.54
      1968150.80     13611234.54      1968279.21     13610877.47
      1968480.80     13610754.54      1968600.80     13610294.54
      1968630.80     13609854.54      1968750.80     13609734.54
      1968930.80     13609664.54      1969060.80     13609474.54
      1968960.80     13609254.54      1968970.80     13609114.54
      1969440.80     13608034.54      1969770.80     13607624.54
      1970340.80     13607044.54      1970490.80     13606774.54

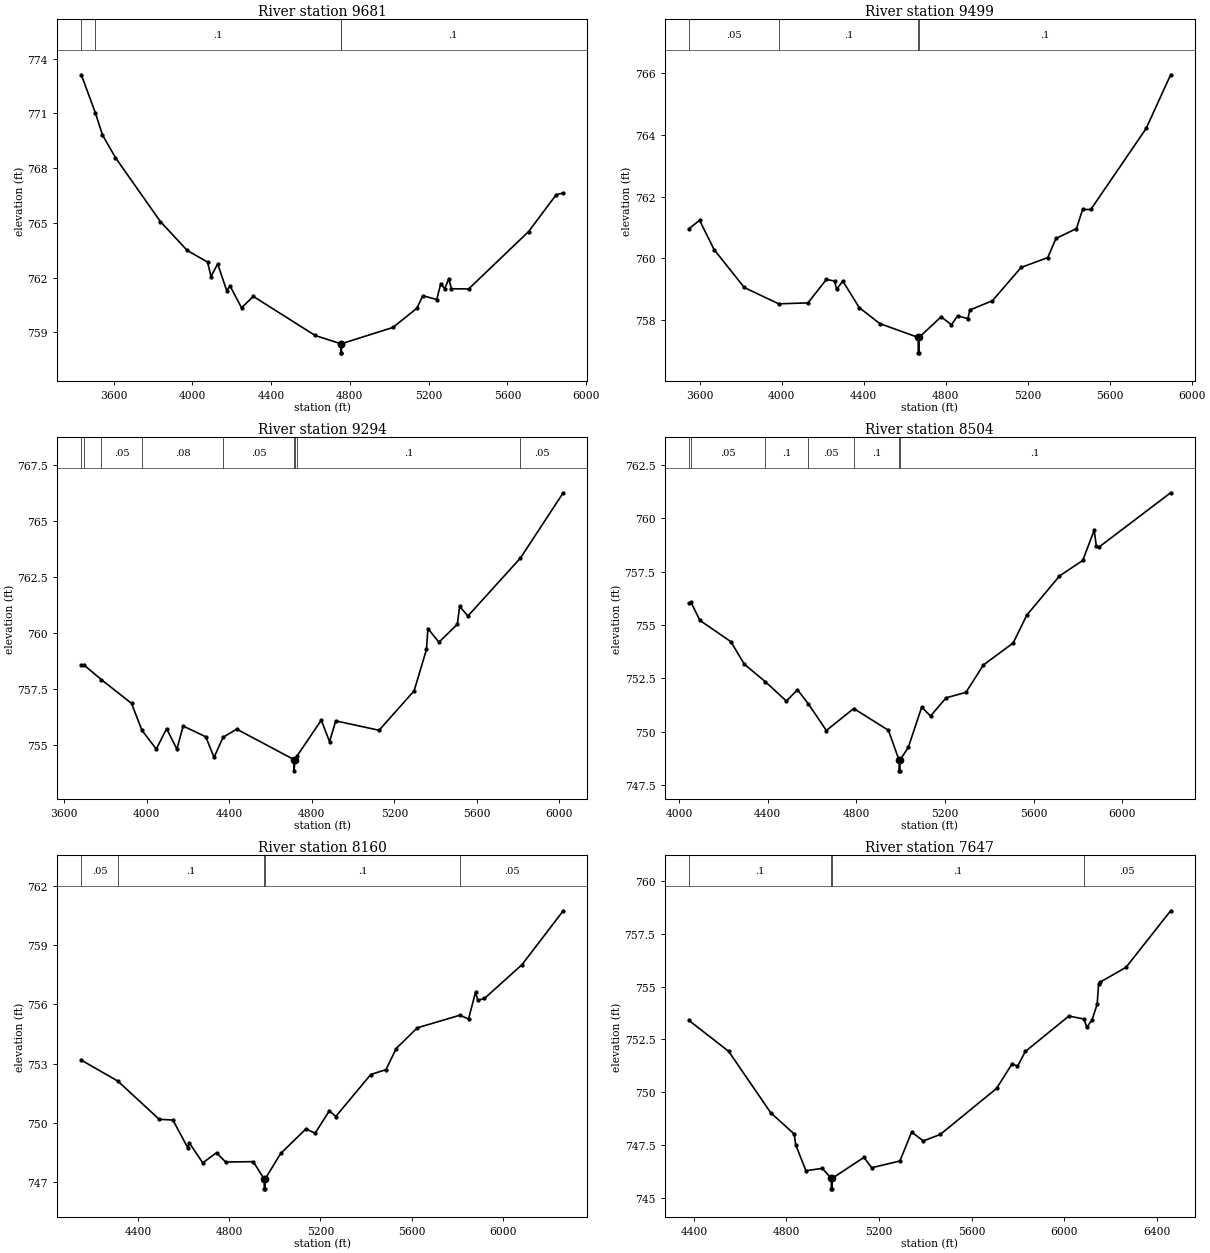
Type RM Length L Ch R = 1,9681,182,182,182
BEGIN DESCRIPTION:
UNT 043 in BCW 4.0
END DESCRIPTION:
XS GIS Cut Line= 3
      1968390.63     13615362.17      1968040.63     13614612.15
      1966440.61     13614362.15
#Sta/Elev= 30
  3436.3  773.11  3507.1  771.04  3543.5  769.82  3609.7  768.57  3837.9  765.07
  3973.9  763.49  4077.5  762.85  4094.8  762.06  4128.7  762.75  4174.5  761.29
  4191.8  761.54  4249.8  760.35  4310.1  760.97  4623.9  758.83  4753.5  758.38
  4753.7  757.88  4757.2  757.88  4757.5  758.38  5018.6  759.27  5140.1  760.32
  5170.5  761.01  5241.3  760.80  5261.6  761.67  5281.8  761.39  5302.0  761.93
  5315.8  761.39  5403.2  761.38  5707.5  764.52  5848.6  766.55  5883.4  766.63
#Mann=4,-1,0
  3436.3    0.05       0  3507.1     0.1       0  4753.5    0.07       0
  4757.5     0.1       0
Bank Sta=4753.5,4757.5
Exp/Cntr=0.3,0.1

Type RM Length L Ch R = 1,9499,205,205,205
BEGIN DESCRIPTION:
Mapping XS 9c83eafe
END DESCRIPTION:
XS GIS Cut Line= 3
      1968802.01     13614607.62      1968348.92     13614357.64
      1966515.63     13614347.22
#Sta/Elev= 30
  3546.6  760.95  3599.2  761.23  3670.2  760.28  3817.3  759.05  3985.3  758.52
  4128.0  758.55  4218.0  759.31  4258.0  759.26  4268.0  758.99  4298.0  759.26
  4378.0  758.40  4478.0  757.88  4666.0  757.43  4666.3  756.93  4669.8  756.93
  4670.0  757.43  4778.0  758.10  4828.0  757.84  4858.0  758.13  4908.0  758.04
  4918.0  758.32  5028.0  758.62  5168.0  759.70  5298.0  760.02  5338.0  760.64
  5438.0  760.96  5468.0  761.58  5508.0  761.58  5778.0  764.21  5897.4  765.95
#Mann=4,-1,0
  3546.6    0.05       0  3985.3     0.1       0  4666.0    0.07       0
  4670.0     0.1       0
Bank Sta=4666,4670
Exp/Cntr=0.3,0.1

Type RM Length L Ch R = 1,9294,790,790,790
BEGIN DESCRIPTION:
Mapping XS ed0fa14b
END DESCRIPTION:
XS GIS Cut Line= 3
      1968838.50     13614217.01      1967156.21     13614196.18
      1966505.12     13614258.69
#Sta/Elev= 30
  3682.2  758.54  3692.9  758.57  3779.4  757.90  3925.7  756.84  3976.1  755.64
  4045.7  754.80  4095.7  755.71  4145.7  754.80  4175.7  755.83  4285.7  755.35
  4325.7  754.43  4369.6  755.33  4435.8  755.69  4713.8  754.33  4714.0  753.83
  4717.8  754.33  4729.3  754.51  4845.8  756.09  4885.8  755.13  4915.8  756.06
  5125.8  755.64  5295.8  757.40  5355.8  759.25  5362.7  760.18  5416.1  759.57
  5505.3  760.37  5516.5  761.17  5556.7  760.74  5811.6  763.33  6018.7  766.24
#Mann=9,-1,0
  3682.2     0.1       0  3692.9    0.08       0  3779.4    0.05       0
  3976.1    0.08       0  4369.6    0.05       0  4713.8    0.07       0
  4717.8    0.05       0  4729.3     0.1       0  5811.6    0.05       0
Bank Sta=4713.8,4717.8
Exp/Cntr=0.3,0.1

Type RM Length L Ch R = 1,8504,344,344,344
BEGIN DESCRIPTION:
Mapping XS 5e9954cf
END DESCRIPTION:
XS GIS Cut Line= 3
      1968925.31     13613709.20      1967649.27     13613717.88
      1966846.34     13614117.17
#Sta/Elev= 30
  4044.3  756.02  4054.7  756.05  4094.6  755.21  4234.6  754.21  4294.6  753.16
  4390.3  752.33  4484.6  751.43  4534.6  751.96  4584.2  751.29  4664.6  750.05
  4788.2  751.08  4944.6  750.06  4992.6  748.66  4992.9  748.16  4996.4  748.16
  4996.6  748.66  5034.6  749.27  5094.6  751.14  5134.6  750.73  5204.6  751.58
  5294.6  751.84  5372.7  753.12  5507.1  754.15  5568.7  755.46  5716.0  757.29
  5820.7  758.02  5872.4  759.43  5882.3  758.68  5894.7  758.65  6217.1  761.19
#Mann=7,-1,0
  4044.3     0.1       0  4054.7    0.05       0  4390.3     0.1       0
  4584.2    0.05       0  4788.2     0.1       0  4992.6    0.07       0
  4996.6     0.1       0
Bank Sta=4992.6,4996.6
Exp/Cntr=0.3,0.1

Type RM Length L Ch R = 1,8160,513,513,513
BEGIN DESCRIPTION:
Mapping XS 19015eb9
END DESCRIPTION:
XS GIS Cut Line= 3
      1968864.52     13613296.88      1967762.11     13613422.74
      1966778.43     13613630.75
#Sta/Elev= 30
  4150.8  753.17  4310.7  752.11  4492.5  750.17  4552.9  750.13  4618.7  748.71
  4623.7  748.99  4683.8  747.96  4744.1  748.47  4784.4  748.00  4905.2  748.02
  4953.5  747.14  4953.8  746.64  4957.3  746.64  4957.5  747.14  5026.0  748.44
  5136.7  749.68  5176.9  749.46  5239.3  750.60  5267.6  750.31  5421.0  752.44
  5488.1  752.69  5532.7  753.76  5625.4  754.81  5812.3  755.45  5850.2  755.26
  5880.9  756.61  5891.1  756.21  5920.3  756.30  6085.3  758.02  6265.8  760.75
#Mann=5,-1,0
  4150.8    0.05       0  4310.7     0.1       0  4953.5    0.07       0
  4957.5     0.1       0  5812.3    0.05       0
Bank Sta=4953.5,4957.5
Exp/Cntr=0.3,0.1

Type RM Length L Ch R = 1,7647,152,152,152
BEGIN DESCRIPTION:
Mapping XS e18eaebb
END DESCRIPTION:
XS GIS Cut Line= 4
      1968805.53     13612787.60      1968708.29     13612884.84
      1967798.57     13613041.09      1966879.25     13613485.14
#Sta/Elev= 30
  4378.0  753.41  4550.2  751.94  4731.9  749.03  4833.4  748.02  4839.9  747.51
  4884.1  746.28  4954.8  746.39  4993.7  745.92  4994.0  745.42  4997.5  745.42
  4997.7  745.92  5134.7  746.91  5168.2  746.42  5290.0  746.74  5340.7  748.11
  5391.4  747.69  5464.7  748.00  5707.7  750.18  5775.5  751.36  5797.9  751.22
  5831.8  751.93  6020.0  753.61  6084.8  753.47  6097.5  753.08  6120.0  753.43
  6142.2  754.17  6148.3  755.13  6153.8  755.21  6266.8  755.92  6459.5  758.60
#Mann=4,-1,0
  4378.0     0.1       0  4993.7    0.07       0  4997.7     0.1       0
  6084.8    0.05       0
Bank Sta=4993.7,4997.7
Exp/Cntr=0.3,0.1

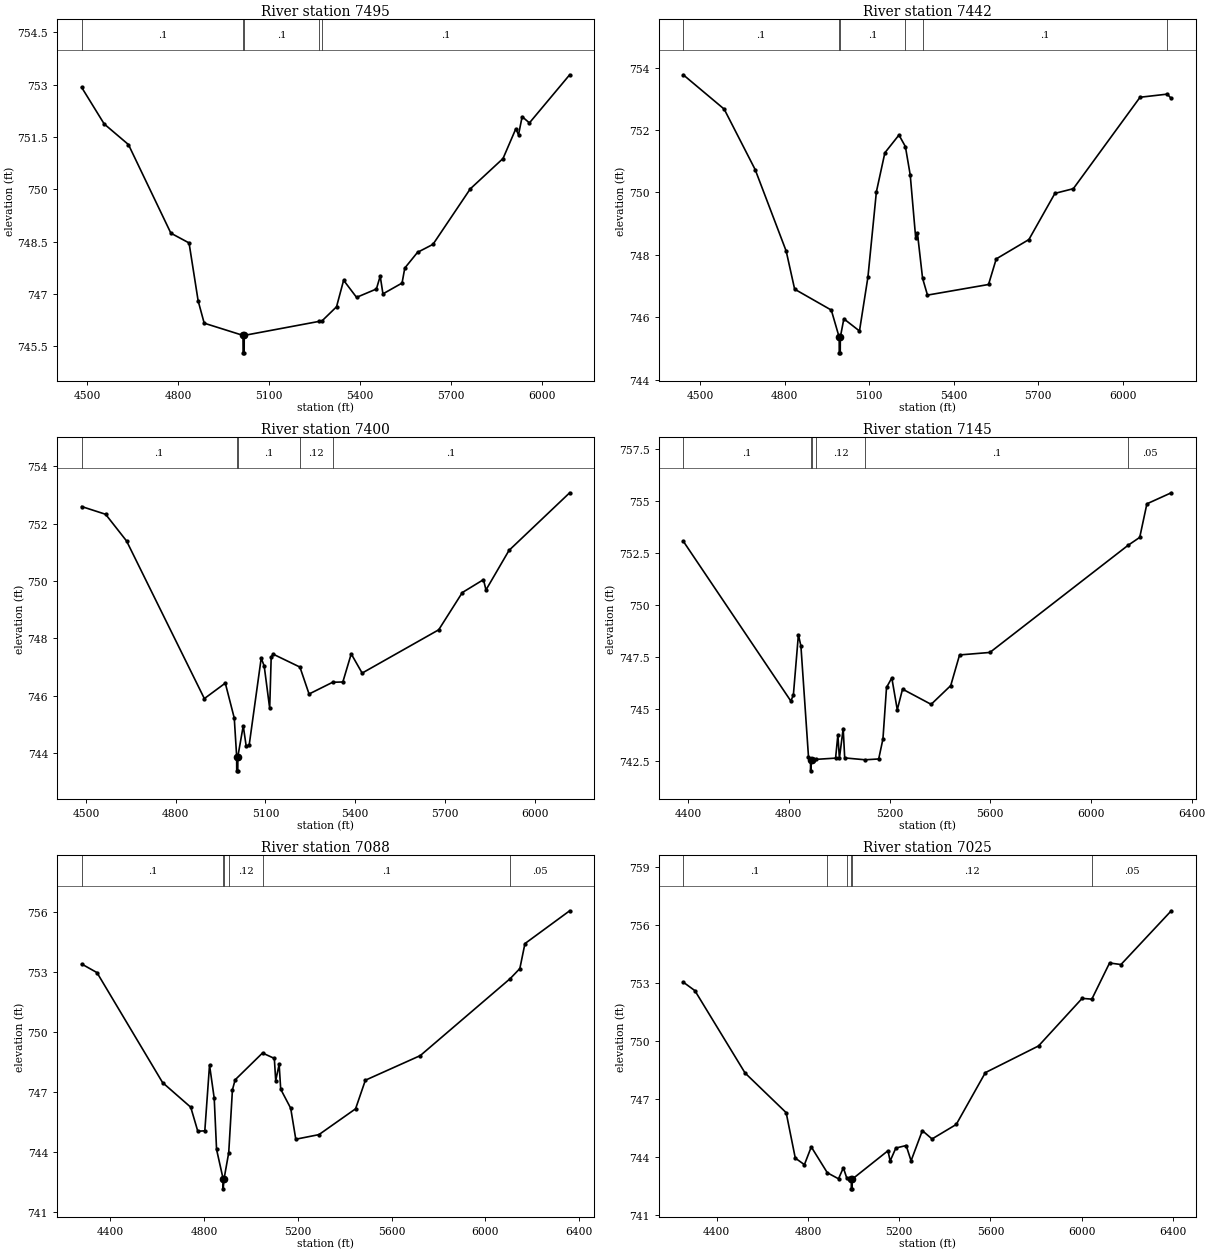
Type RM Length L Ch R = 1,7495,53,53,53
BEGIN DESCRIPTION:
Mapping XS 9dba1659
END DESCRIPTION:
XS GIS Cut Line= 3
      1968749.46     13612798.87      1967943.92     13612823.18
      1967274.58     13613270.56
#Sta/Elev= 30
  4481.1  752.92  4555.6  751.87  4635.6  751.28  4775.7  748.74  4835.7  748.46
  4865.7  746.80  4885.7  746.16  5013.8  745.81  5014.1  745.31  5017.6  745.31
  5017.8  745.81  5263.9  746.21  5275.1  746.23  5322.5  746.63  5345.9  747.39
  5388.6  746.90  5454.1  747.14  5466.7  747.51  5475.7  747.00  5538.8  747.31
  5547.8  747.74  5589.8  748.19  5640.9  748.42  5764.0  750.01  5872.1  750.88
  5914.2  751.73  5923.2  751.56  5935.2  752.08  5959.2  751.90  6092.1  753.28
#Mann=5,-1,0
  4481.1     0.1       0  5013.8    0.07       0  5017.8     0.1       0
  5263.9    0.12       0  5275.1     0.1       0
Bank Sta=5013.8,5017.8
Exp/Cntr=0.3,0.1

Type RM Length L Ch R = 1,7442,42,42,42
BEGIN DESCRIPTION:
Mapping XS d9826b54
END DESCRIPTION:
XS GIS Cut Line= 4
      1968770.27     13612753.73      1968041.14     13612774.57
      1967950.86     13612774.57      1967204.30     13613298.90
#Sta/Elev= 30
  4440.3  753.77  4585.6  752.67  4695.7  750.73  4805.7  748.12  4835.7  746.90
  4965.8  746.23  4993.8  745.36  4994.0  744.86  4997.5  744.86  4997.8  745.36
  5010.3  745.95  5065.8  745.56  5095.8  747.29  5125.8  750.02  5155.9  751.27
  5205.9  751.84  5228.7  751.47  5245.9  750.56  5265.3  748.54  5271.4  748.70
  5289.7  747.25  5307.1  746.71  5523.8  747.05  5551.1  747.87  5667.0  748.49
  5759.4  749.97  5824.7  750.12  6061.5  753.05  6158.1  753.15  6172.3  753.01
#Mann=6,-1,0
  4440.3     0.1       0  4993.8    0.07       0  4997.8     0.1       0
  5228.7    0.12       0  5289.7     0.1       0  6158.1    0.05       0
Bank Sta=4993.8,4997.8
Exp/Cntr=0.3,0.1

Type RM Length L Ch R = 1,7400,255,255,255
BEGIN DESCRIPTION:
Mapping XS 83fd336f
END DESCRIPTION:
XS GIS Cut Line= 3
      1968725.12     13612719.01      1967926.56     13612732.90
      1967263.39     13613236.35
#Sta/Elev= 30
  4485.6  752.60  4565.7  752.33  4635.7  751.40  4895.8  745.90  4965.8  746.44
  4995.8  745.22  5003.8  743.88  5004.0  743.38  5007.5  743.38  5007.8  743.88
  5025.8  744.95  5035.8  744.23  5045.8  744.29  5085.8  747.31  5095.8  747.04
  5114.2  745.56  5119.2  747.35  5125.8  747.45  5215.2  747.00  5245.8  746.06
  5324.7  746.47  5358.7  746.48  5386.7  747.46  5423.2  746.79  5679.1  748.30
  5758.1  749.60  5828.8  750.05  5837.1  749.69  5914.1  751.07  6116.9  753.08
#Mann=5,-1,0
  4485.6     0.1       0  5003.8    0.07       0  5007.8     0.1       0
  5215.2    0.12       0  5324.7     0.1       0
Bank Sta=5003.8,5007.8
Exp/Cntr=0.3,0.1

Type RM Length L Ch R = 1,7145,57,57,57
BEGIN DESCRIPTION:
Mapping XS afbd93df
END DESCRIPTION:
XS GIS Cut Line= 5
      1968701.35     13612516.78      1968142.32     13612478.59
      1968010.38     13612565.39      1967944.41     13612586.23
      1967086.75     13613353.61
#Sta/Elev= 30
  4380.5  753.06  4807.8  745.39  4817.9  745.67  4837.9  748.57  4847.9  748.03
  4878.0  742.71  4886.0  742.54  4886.3  742.04  4890.0  742.54  4906.9  742.59
  4985.6  742.65  4994.7  743.77  5000.7  742.64  5015.8  744.07  5021.8  742.66
  5103.2  742.57  5156.8  742.61  5173.7  743.57  5187.9  746.04  5208.9  746.50
  5230.6  744.97  5251.5  745.96  5365.1  745.23  5442.9  746.13  5478.0  747.60
  5598.4  747.72  6147.2  752.86  6193.5  753.24  6222.0  754.85  6318.8  755.38
#Mann=6,-1,0
  4380.5     0.1       0  4886.0    0.07       0  4890.0     0.1       0
  4906.9    0.12       0  5103.2     0.1       0  6147.2    0.05       0
Bank Sta=4886,4890
Exp/Cntr=0.3,0.1

Type RM Length L Ch R = 1,7088,63,63,63
BEGIN DESCRIPTION:
Mapping XS a3c3ac94
END DESCRIPTION:
XS GIS Cut Line= 4
      1968760.42     13612440.39      1968114.54     13612433.45
      1967954.82     13612534.14      1967024.24     13613364.03
#Sta/Elev= 30
  4277.5  753.40  4342.9  752.97  4622.9  747.47  4742.9  746.24  4772.9  745.04
  4802.9  745.06  4823.0  748.35  4843.0  746.69  4853.0  744.13  4881.0  742.66
  4881.2  742.16  4885.0  742.66  4904.9  743.97  4920.7  747.11  4932.2  747.61
  5049.0  748.95  5099.4  748.68  5105.3  747.57  5119.9  748.38  5126.6  747.14
  5169.2  746.19  5190.9  744.64  5289.6  744.87  5445.9  746.16  5487.7  747.59
  5721.8  748.82  6105.5  752.67  6146.5  753.17  6168.3  754.42  6359.1  756.06
#Mann=6,-1,0
  4277.5     0.1       0  4881.0    0.07       0  4885.0     0.1       0
  4904.9    0.12       0  5049.0     0.1       0  6105.5    0.05       0
Bank Sta=4881,4885
Exp/Cntr=0.3,0.1

Type RM Length L Ch R = 1,7025,249,249,249
BEGIN DESCRIPTION:
Mapping XS 8ba82113
END DESCRIPTION:
XS GIS Cut Line= 4
      1968736.06     13612374.42      1968076.35     13612388.31
      1967843.71     13612530.67      1966954.83     13613346.63
#Sta/Elev= 30
  4253.2  753.03  4304.3  752.59  4524.3  748.33  4704.4  746.28  4744.4  743.93
  4784.4  743.59  4814.4  744.51  4884.9  743.17  4933.8  742.86  4955.1  743.43
  4970.0  742.90  4989.9  742.84  4990.1  742.34  4993.6  742.34  4993.9  742.84
  5150.6  744.31  5160.2  743.78  5185.1  744.45  5230.4  744.58  5251.9  743.79
  5301.3  745.35  5343.8  744.92  5449.9  745.67  5577.5  748.35  5810.6  749.73
  6001.7  752.19  6044.2  752.15  6121.9  754.02  6171.9  753.94  6392.4  756.72
#Mann=6,-1,0
  4253.2     0.1       0  4884.9    0.16       0  4970.0    0.12       0
  4989.9    0.07       0  4993.9    0.12       0  6044.2    0.05       0
Bank Sta=4989.9,4993.9
Exp/Cntr=0.3,0.1

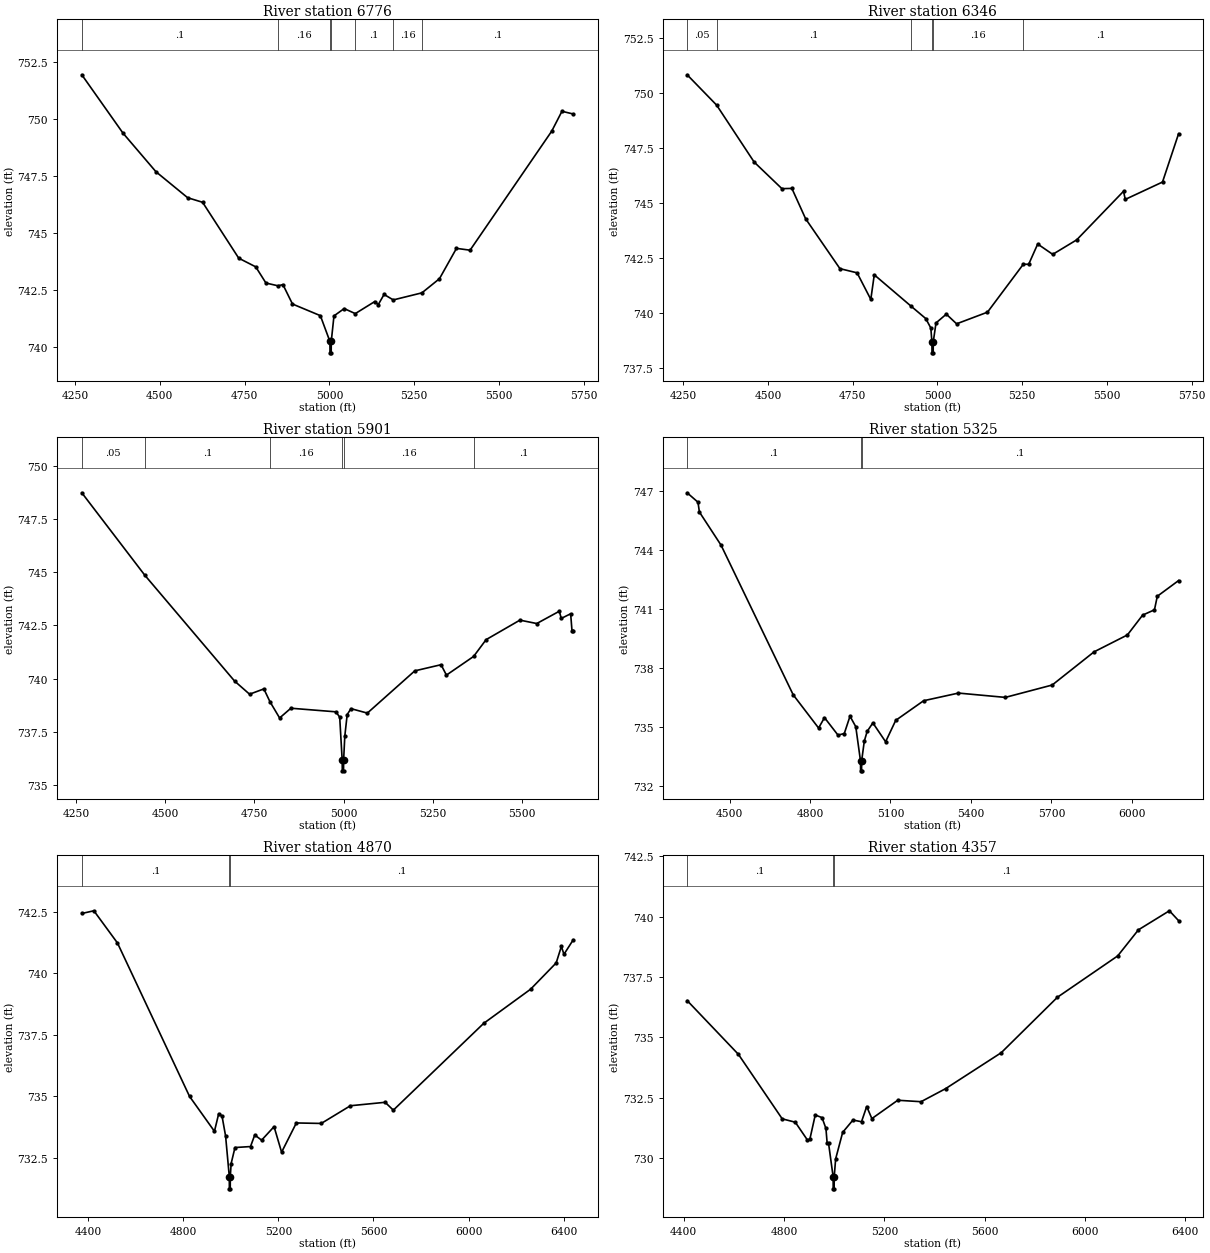
Type RM Length L Ch R = 1,6776,430,430,430
BEGIN DESCRIPTION:
Mapping XS 1f1da08f
END DESCRIPTION:
XS GIS Cut Line= 2
      1968656.17     13612256.36      1967211.78     13612148.73
#Sta/Elev= 30
  4270.2  751.93  4391.7  749.37  4488.7  747.68  4582.2  746.54  4626.2  746.34
  4732.7  743.89  4782.8  743.51  4812.9  742.80  4848.1  742.68  4863.0  742.73
  4891.1  741.88  4973.3  741.37  5001.4  740.24  5001.7  739.74  5005.2  739.74
  5005.4  740.24  5013.4  741.36  5043.5  741.68  5076.2  741.46  5133.8  741.99
  5143.8  741.85  5161.0  742.30  5188.2  742.06  5272.6  742.37  5324.3  742.99
  5374.4  744.32  5414.5  744.24  5655.2  749.46  5685.3  750.33  5718.6  750.21
#Mann=7,-1,0
  4270.2     0.1       0  4848.1    0.16       0  5001.4    0.07       0
  5005.4    0.16       0  5076.2     0.1       0  5188.2    0.16       0
  5272.6     0.1       0
Bank Sta=5001.4,5005.4
Exp/Cntr=0.3,0.1

Type RM Length L Ch R = 1,6346,445,445,445
BEGIN DESCRIPTION:
Mapping XS e1e67724
END DESCRIPTION:
XS GIS Cut Line= 2
      1968590.24     13611933.45      1967158.11     13611704.59
#Sta/Elev= 30
  4261.3  750.83  4348.3  749.45  4459.0  746.86  4540.9  745.65  4570.4  745.66
  4610.9  744.28  4712.2  742.01  4762.8  741.82  4803.3  740.61  4813.5  741.73
  4922.3  740.30  4965.4  739.74  4980.4  739.31  4983.6  738.68  4983.9  738.18
  4987.4  738.18  4987.6  738.68  4995.7  739.54  5026.1  739.94  5056.5  739.50
  5147.6  740.03  5253.3  742.21  5269.2  742.21  5295.8  743.13  5340.1  742.66
  5410.9  743.32  5549.1  745.53  5554.2  745.16  5664.1  745.95  5711.6  748.15
#Mann=6,-1,0
  4261.3    0.05       0  4348.3     0.1       0  4922.3    0.16       0
  4983.6    0.07       0  4987.6    0.16       0  5253.3     0.1       0
Bank Sta=4983.6,4987.6
Exp/Cntr=0.3,0.1

Type RM Length L Ch R = 1,5901,576,576,576
BEGIN DESCRIPTION:
Mapping XS 470bd36b
END DESCRIPTION:
XS GIS Cut Line= 2
      1968631.89     13611641.78      1967322.87     13611207.75
#Sta/Elev= 30
  4265.5  748.75  4442.1  744.87  4694.2  739.88  4736.3  739.26  4776.4  739.51
  4793.4  738.91  4820.6  738.14  4852.2  738.60  4978.6  738.43  4989.2  738.18
  4996.2  736.15  4996.5  735.65  5000.0  735.65  5000.2  736.15  5003.5  737.28
  5010.2  738.30  5020.8  738.58  5066.8  738.37  5199.9  740.36  5273.6  740.65
  5288.7  740.16  5365.0  741.04  5400.0  741.83  5494.9  742.75  5542.2  742.59
  5605.6  743.17  5610.9  742.83  5637.3  743.05  5641.0  742.26  5644.6  742.26
#Mann=6,-1,0
  4265.5    0.05       0  4442.1     0.1       0  4793.4    0.16       0
  4996.2    0.07       0  5000.2    0.16       0  5365.0     0.1       0
Bank Sta=4996.2,5000.2
Exp/Cntr=0.3,0.1

Type RM Length L Ch R = 1,5325,455,455,455
BEGIN DESCRIPTION:
UNT 043 in BCW 3.0
END DESCRIPTION:
XS GIS Cut Line= 3
      1968875.00     13611225.00      1968011.11     13610907.64
      1967150.04     13610606.95
#Sta/Elev= 30
  4341.9  746.92  4382.3  746.44  4387.6  745.94  4468.4  744.25  4737.4  736.63
  4832.0  734.94  4854.0  735.47  4904.3  734.58  4927.8  734.66  4949.1  735.54
  4970.6  735.01  4988.3  733.26  4988.6  732.76  4992.3  732.76  4992.5  733.26
  5002.4  734.27  5013.1  734.77  5034.4  735.20  5081.9  734.24  5119.6  735.33
  5223.6  736.33  5353.5  736.72  5528.1  736.50  5703.0  737.13  5859.2  738.82
  5983.4  739.68  6040.2  740.69  6084.3  740.96  6094.9  741.65  6174.3  742.45
#Mann=3,-1,0
  4341.9     0.1       0  4988.3    0.07       0  4992.5     0.1       0
Bank Sta=4988.3,4992.5
Exp/Cntr=0.3,0.1

Type RM Length L Ch R = 1,4870,513,513,513
BEGIN DESCRIPTION:
Mapping XS 1b458109
END DESCRIPTION:
XS GIS Cut Line= 2
      1969076.32     13610940.38      1967179.14     13610116.88
#Sta/Elev= 30
  4372.6  742.44  4423.4  742.55  4522.7  741.24  4826.0  735.00  4930.8  733.58
  4948.8  734.30  4962.7  734.20  4977.7  733.39  4993.3  731.74  4993.6  731.24
  4997.3  731.24  4997.5  731.74  5001.1  732.27  5017.2  732.92  5082.6  732.96
  5100.4  733.43  5129.3  733.22  5181.7  733.77  5213.4  732.73  5275.5  733.92
  5380.3  733.90  5503.0  734.62  5649.2  734.76  5683.6  734.44  6063.8  737.97
  6261.3  739.36  6369.0  740.43  6390.8  741.10  6401.7  740.78  6440.8  741.37
#Mann=3,-1,0
  4372.6     0.1       0  4993.3    0.07       0  4997.5     0.1       0
Bank Sta=4993.3,4997.5
Exp/Cntr=0.3,0.1

Type RM Length L Ch R = 1,4357,514,514,514
BEGIN DESCRIPTION:
UNT 043 in BCW 2.0
END DESCRIPTION:
XS GIS Cut Line= 3
      1969104.09     13610516.76      1968625.00     13610225.00
      1967269.72     13609882.20
#Sta/Elev= 30
  4414.1  736.53  4618.6  734.30  4793.0  731.63  4845.2  731.49  4893.7  730.75
  4903.3  730.79  4924.7  731.79  4951.8  731.68  4967.3  731.23  4972.1  730.63
  4977.6  730.63  4996.0  729.23  4996.3  728.73  5000.0  728.73  5000.3  729.23
  5006.0  729.97  5034.0  731.07  5075.0  731.58  5109.1  731.51  5129.8  732.14
  5150.4  731.64  5253.5  732.40  5346.4  732.34  5444.2  732.88  5666.1  734.37
  5890.3  736.67  6130.3  738.38  6212.8  739.46  6336.3  740.25  6373.0  739.84
#Mann=3,-1,0
  4414.1     0.1       0  4996.0    0.07       0  5000.3     0.1       0
Bank Sta=4996,5000.3
Exp/Cntr=0.3,0.1

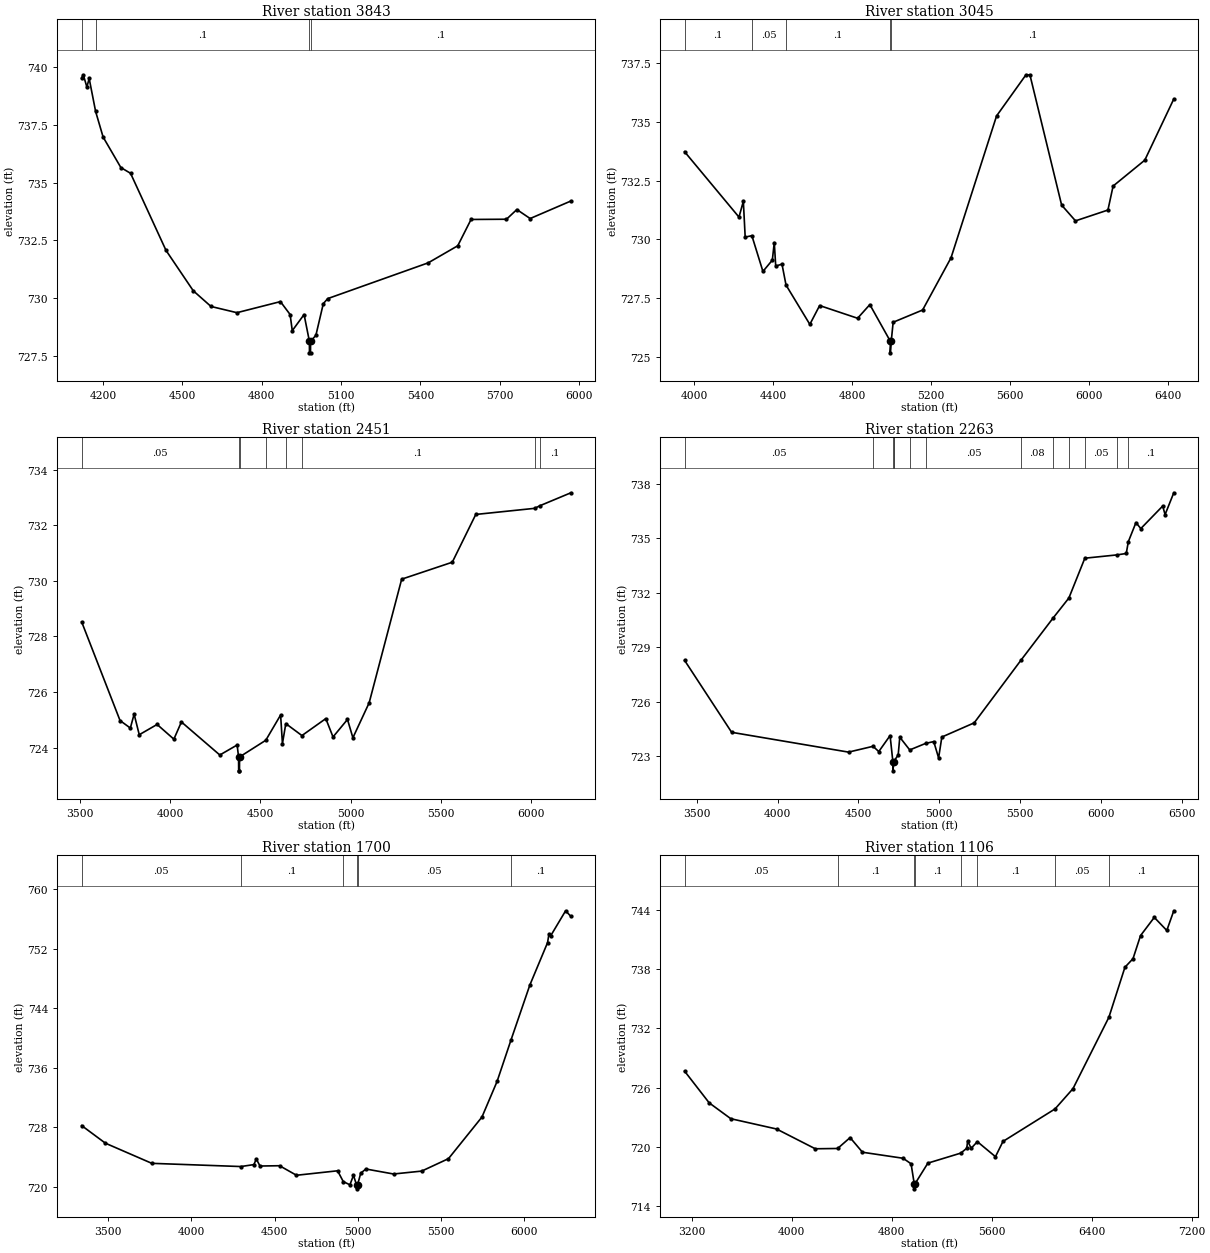
Type RM Length L Ch R = 1,3843,798,798,798
BEGIN DESCRIPTION:
Mapping XS 6e7b9179
END DESCRIPTION:
XS GIS Cut Line= 2
      1969510.34     13610157.39      1967854.84     13609329.64
#Sta/Elev= 30
  4118.7  739.53  4124.7  739.67  4138.3  739.14  4147.0  739.51  4171.4  738.08
  4199.8  736.97  4266.9  735.65  4303.6  735.40  4437.7  732.06  4540.8  730.31
  4607.9  729.63  4706.0  729.36  4870.6  729.84  4907.3  729.28  4915.4  728.58
  4960.1  729.28  4980.2  728.12  4980.5  727.62  4984.4  727.62  4984.7  728.12
  5004.8  728.38  5032.8  729.75  5049.5  729.97  5429.7  731.52  5541.5  732.26
  5591.8  733.40  5725.9  733.41  5765.1  733.83  5815.4  733.44  5969.6  734.20
#Mann=4,-1,0
  4118.7    0.05       0  4171.4     0.1       0  4980.2    0.07       0
  4984.7     0.1       0
Bank Sta=4980.2,4984.7
Exp/Cntr=0.3,0.1

Type RM Length L Ch R = 1,3045,594,594,594
BEGIN DESCRIPTION:
Mapping XS f62e5297
END DESCRIPTION:
XS GIS Cut Line= 4
      1969734.33     13609808.44      1969531.21     13609412.62
      1968557.25     13609068.87      1967558.60     13608980.44
#Sta/Elev= 30
  3950.2  733.73  4226.0  730.95  4248.2  731.62  4257.5  730.10  4291.4  730.16
  4347.5  728.64  4395.1  729.12  4405.0  729.87  4412.3  728.87  4444.1  728.95
  4464.6  728.06  4585.3  726.39  4635.0  727.19  4827.4  726.65  4889.5  727.23
  4992.9  725.68  4993.3  725.18  4998.1  725.68  5007.7  726.48  5157.0  727.00
  5301.1  729.22  5532.0  735.25  5681.2  737.00  5701.3  736.99  5861.9  731.46
  5932.2  730.79  6096.6  731.25  6122.9  732.27  6283.5  733.37  6430.5  735.97
#Mann=5,-1,0
  3950.2     0.1       0  4291.4    0.05       0  4464.6     0.1       0
  4992.9    0.07       0  4998.1     0.1       0
Bank Sta=4992.9,4998.1
Exp/Cntr=0.3,0.1

Type RM Length L Ch R = 1,2451,188,188,188
BEGIN DESCRIPTION:
Mapping XS 3744cd80
END DESCRIPTION:
XS GIS Cut Line= 4
      1970369.69     13609280.16      1969859.34     13608693.87
      1968791.63     13608646.99      1967928.53     13608683.39
#Sta/Elev= 30
  3509.8  728.52  3722.3  724.97  3779.3  724.70  3800.2  725.20  3828.7  724.46
  3927.6  724.83  4020.4  724.30  4062.2  724.92  4274.9  723.73  4370.9  724.09
  4378.8  723.66  4379.3  723.16  4383.8  723.16  4384.2  723.66  4529.5  724.26
  4611.7  725.17  4621.8  724.14  4640.5  724.86  4729.8  724.43  4862.0  725.04
  4902.0  724.38  4982.1  725.01  5012.1  724.35  5102.2  725.61  5282.3  730.06
  5562.6  730.67  5692.8  732.39  6019.1  732.61  6046.6  732.70  6219.7  733.17
#Mann=8,-1,0
  3509.8    0.05       0  4378.8    0.07       0  4384.2    0.05       0
  4529.5     0.1       0  4640.5    0.05       0  4729.8     0.1       0
  6019.1    0.08       0  6046.6     0.1       0
Bank Sta=4378.8,4384.2
Exp/Cntr=0.3,0.1

Type RM Length L Ch R = 1,2263,563,563,563
BEGIN DESCRIPTION:
Mapping XS a8b233b8
END DESCRIPTION:
XS GIS Cut Line= 4
      1970452.97     13609267.07      1969786.42     13608495.95
      1968494.75     13608501.16      1967781.21     13608521.99
#Sta/Elev= 30
  3425.1  728.29  3716.1  724.33  4439.0  723.24  4590.5  723.56  4625.8  723.27
  4695.8  724.15  4713.1  722.71  4713.5  722.21  4718.5  722.71  4718.9  722.73
  4745.8  723.08  4755.8  724.06  4817.3  723.36  4915.7  723.72  4965.8  723.82
  4995.8  722.92  5015.8  724.07  5215.8  724.85  5506.1  728.31  5702.9  730.61
  5801.3  731.72  5899.9  733.91  6096.9  734.09  6156.0  734.17  6168.9  734.82
  6216.0  735.87  6246.0  735.54  6381.4  736.78  6396.1  736.31  6449.9  737.51
#Mann=13,-1,0
  3425.1    0.05       0  4590.5     0.1       0  4713.1   0.035       0
  4718.5     0.1       0  4718.9    0.05       0  4817.3     0.1       0
  4915.7    0.05       0  5506.1    0.08       0  5702.9    0.05       0
  5801.3    0.08       0  5899.9    0.05       0  6096.9    0.08       0
  6168.9     0.1       0
Bank Sta=4713.1,4718.5
Exp/Cntr=0.3,0.1

Type RM Length L Ch R = 1,1700,594,594,594
BEGIN DESCRIPTION:
Mapping XS 02980233
END DESCRIPTION:
XS GIS Cut Line= 4
      1970479.03     13609254.07      1969971.22     13608329.60
      1969208.20     13607884.29      1968213.47     13607785.88
#Sta/Elev= 30
  3341.7  728.25  3484.2  725.89  3762.8  723.19  4297.6  722.76  4375.7  723.02
  4390.3  723.77  4412.5  722.83  4529.9  722.87  4631.6  721.59  4878.4  722.19
  4912.6  720.74  4952.4  720.31  4973.9  721.58  4992.6  720.27  4993.1  719.77
  4998.1  720.27  5017.3  721.87  5048.3  722.43  5214.5  721.76  5383.6  722.15
  5544.4  723.82  5745.4  729.40  5836.1  734.17  5920.5  739.78  6033.1  747.11
  6139.2  752.78  6147.3  753.88  6157.4  753.68  6247.8  757.06  6279.5  756.30
#Mann=6,-1,0
  3341.7    0.05       0  4297.6     0.1       0  4912.6    0.05       0
  4992.6    0.04       0  4998.1    0.05       0  5920.5     0.1       0
Bank Sta=4992.6,4998.1
Exp/Cntr=0.3,0.1

Type RM Length L Ch R = 1,1106,746,746,746
BEGIN DESCRIPTION:
Mapping XS d7c59706
END DESCRIPTION:
XS GIS Cut Line= 4
      1970498.13     13609228.88      1970285.46     13608065.72
      1969408.72     13607215.02      1967899.10     13607154.29
#Sta/Elev= 30
  3141.6  727.68  3338.7  724.47  3511.5  722.87  3877.5  721.83  4187.6  719.83
  4366.6  719.86  4466.2  720.96  4565.3  719.48  4890.6  718.87  4954.2  718.31
  4979.7  716.28  4980.2  715.78  4985.2  716.28  5088.7  718.38  5351.5  719.39
  5399.7  719.88  5406.9  720.61  5435.2  719.88  5484.5  720.55  5629.5  719.03
  5689.5  720.57  6106.4  723.86  6250.0  725.91  6537.1  733.12  6665.5  738.18
  6730.3  739.05  6790.4  741.38  6900.5  743.22  7000.6  741.90  7056.5  743.89
#Mann=8,-1,0
  3141.6    0.05       0  4366.6     0.1       0  4979.7    0.07       0
  4985.2     0.1       0  5351.5    0.05       0  5484.5     0.1       0
  6106.4    0.05       0  6537.1     0.1       0
Bank Sta=4979.7,4985.2
Exp/Cntr=0.3,0.1

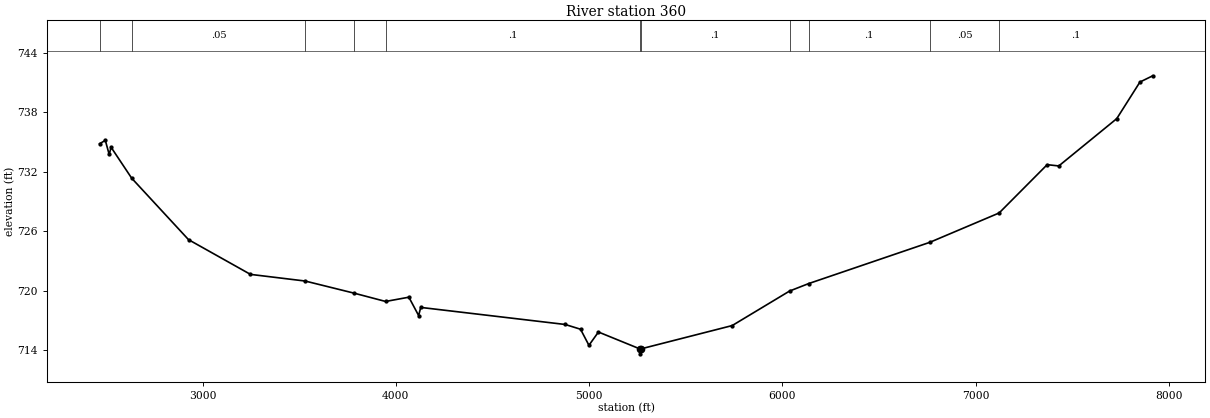
Type RM Length L Ch R = 1,360,0,0,0
BEGIN DESCRIPTION:
UNT 043 in BCW 1.0
END DESCRIPTION:
XS GIS Cut Line= 4
      1970541.62     13609564.36      1970605.77     13608355.65
      1970243.01     13606710.22      1967688.72     13606737.98
#Sta/Elev= 30
  2467.2  734.83  2496.6  735.17  2516.6  733.75  2526.6  734.47  2632.9  731.36
  2927.2  725.16  3247.7  721.66  3530.6  720.99  3783.3  719.77  3947.0  718.93
  4067.4  719.36  4118.0  717.51  4128.8  718.33  4876.4  716.61  4955.8  716.13
  4999.3  714.51  5048.4  715.85  5262.7  714.15  5263.1  713.65  5268.2  714.15
  5740.6  716.50  6037.6  719.98  6136.0  720.73  6763.1  724.89  7122.0  727.85
  7370.7  732.72  7430.7  732.59  7730.7  737.36  7850.7  741.05  7917.0  741.68
#Mann=11,-1,0
  2467.2     0.1       0  2632.9    0.05       0  3530.6     0.1       0
  3783.3    0.05       0  3947.0     0.1       0  5262.7    0.07       0
  5268.2     0.1       0  6037.6    0.08       0  6136.0     0.1       0
  6763.1    0.05       0  7122.0     0.1       0
Bank Sta=5262.7,5268.2
Exp/Cntr=0.3,0.1

Chan Stop Cuts=-1