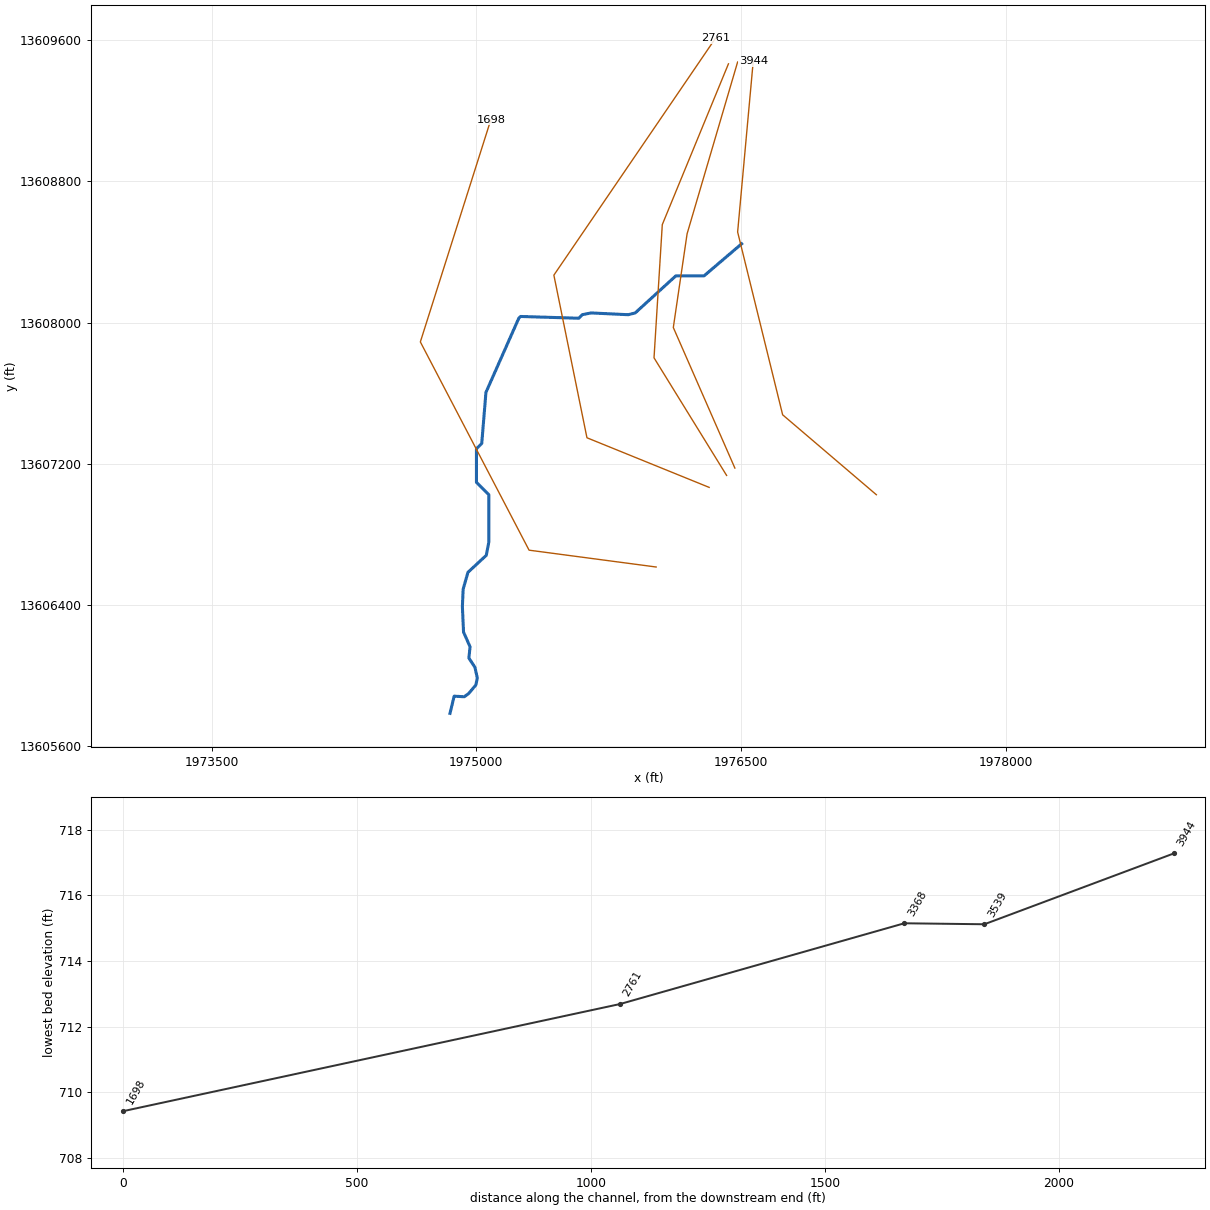
--- UNT 044 in BCW.prj (project) ---

Proj Title=UNT 044 in BCW Base Level Engineering
Current Plan=p01
Default Exp/Contr=0.3,0.1
English Units
Geom File=g01
Flow File=f01
Plan File=p01
BEGIN DESCRIPTION:
UNT 044 in BCW
END DESCRIPTION:

--- UNT 044 in BCW.p01 (plan) ---

Plan Title=Multiple Run
Short Identifier=Multiple
Geom File=g01
Flow File=f01
Subcritical Flow
K Sum by GR= 0
Std Step Tol= 0.01
Critical Tol= 0.01
Num of Std Step Trials= 20
Max Error Tol= 0.3
Flow Tol Ratio= 0.001
Split Flow NTrial= 30
Split Flow Tol= 0.02
Split Flow Ratio= 0.02
Log Output Level= 0
Friction Slope Method= 1
Unsteady Friction Slope Method= 2
Unsteady Bridges Friction Slope Method= 1
Parabolic Critical Depth
Global Vel Dist=  1 , 1 , 1
Global Log Level= 0
CheckData=True
Encroach Param= -1, 0, 0, 0
BEGIN DESCRIPTION:
Multiple Run
END DESCRIPTION:

--- UNT 044 in BCW.f01 (steady flow) ---

Flow Title=Multiple
Number of Profiles=7
Profile Names=10-year,25-year,50-year,1pct_min,100-year,1pct_plu,500-year
River Rch & RM= UNT 044 in BCW,Reach-1,3944
     424     586     720     438     875    1745    1295
River Rch & RM= UNT 044 in BCW,Reach-1,2761
     650     921    1150     710    1417    2827    2160
Boundary for River Rch & Prof#=UNT 044 in BCW,Reach-1,1
Up Type=0
Dn Type=3
Dn Slope=0.005
Boundary for River Rch & Prof#=UNT 044 in BCW,Reach-1,2
Up Type=0
Dn Type=3
Dn Slope=0.005
Boundary for River Rch & Prof#=UNT 044 in BCW,Reach-1,3
Up Type=0
Dn Type=3
Dn Slope=0.005
Boundary for River Rch & Prof#=UNT 044 in BCW,Reach-1,4
Up Type=0
Dn Type=3
Dn Slope=0.005
Boundary for River Rch & Prof#=UNT 044 in BCW,Reach-1,5
Up Type=0
Dn Type=3
Dn Slope=0.005
Boundary for River Rch & Prof#=UNT 044 in BCW,Reach-1,6
Up Type=0
Dn Type=3
Dn Slope=0.005
Boundary for River Rch & Prof#=UNT 044 in BCW,Reach-1,7
Up Type=0
Dn Type=3
Dn Slope=0.005

--- UNT 044 in BCW.g01 (geometry) ---

Geom Title=Existing Conditions

River Reach=UNT 044 in BCW,Reach-1
Reach XY= 30
      1976504.23     13608446.55      1976290.80     13608264.54
      1976130.80     13608264.54      1975900.80     13608054.54
      1975860.80     13608044.54      1975650.80     13608054.54
      1975600.80     13608044.54      1975580.80     13608024.54
      1975250.80     13608034.54      1975240.80     13608024.54
      1975054.53     13607604.05      1975030.80     13607314.54
      1975000.80     13607284.54      1975000.80     13607094.54
      1975070.80     13607024.54      1975070.80     13606755.52
      1975056.70     13606680.65      1974952.54     13606584.08
      1974925.41     13606488.59      1974921.07     13606389.85
      1974927.58     13606245.54      1974964.47     13606161.99
      1974957.96     13606097.97      1974992.68     13606044.80
      1975005.71     13605984.04      1974997.02     13605944.97
      1974956.88     13605897.23      1974931.92     13605878.79
      1974874.41     13605882.04      1974850.80     13605784.54

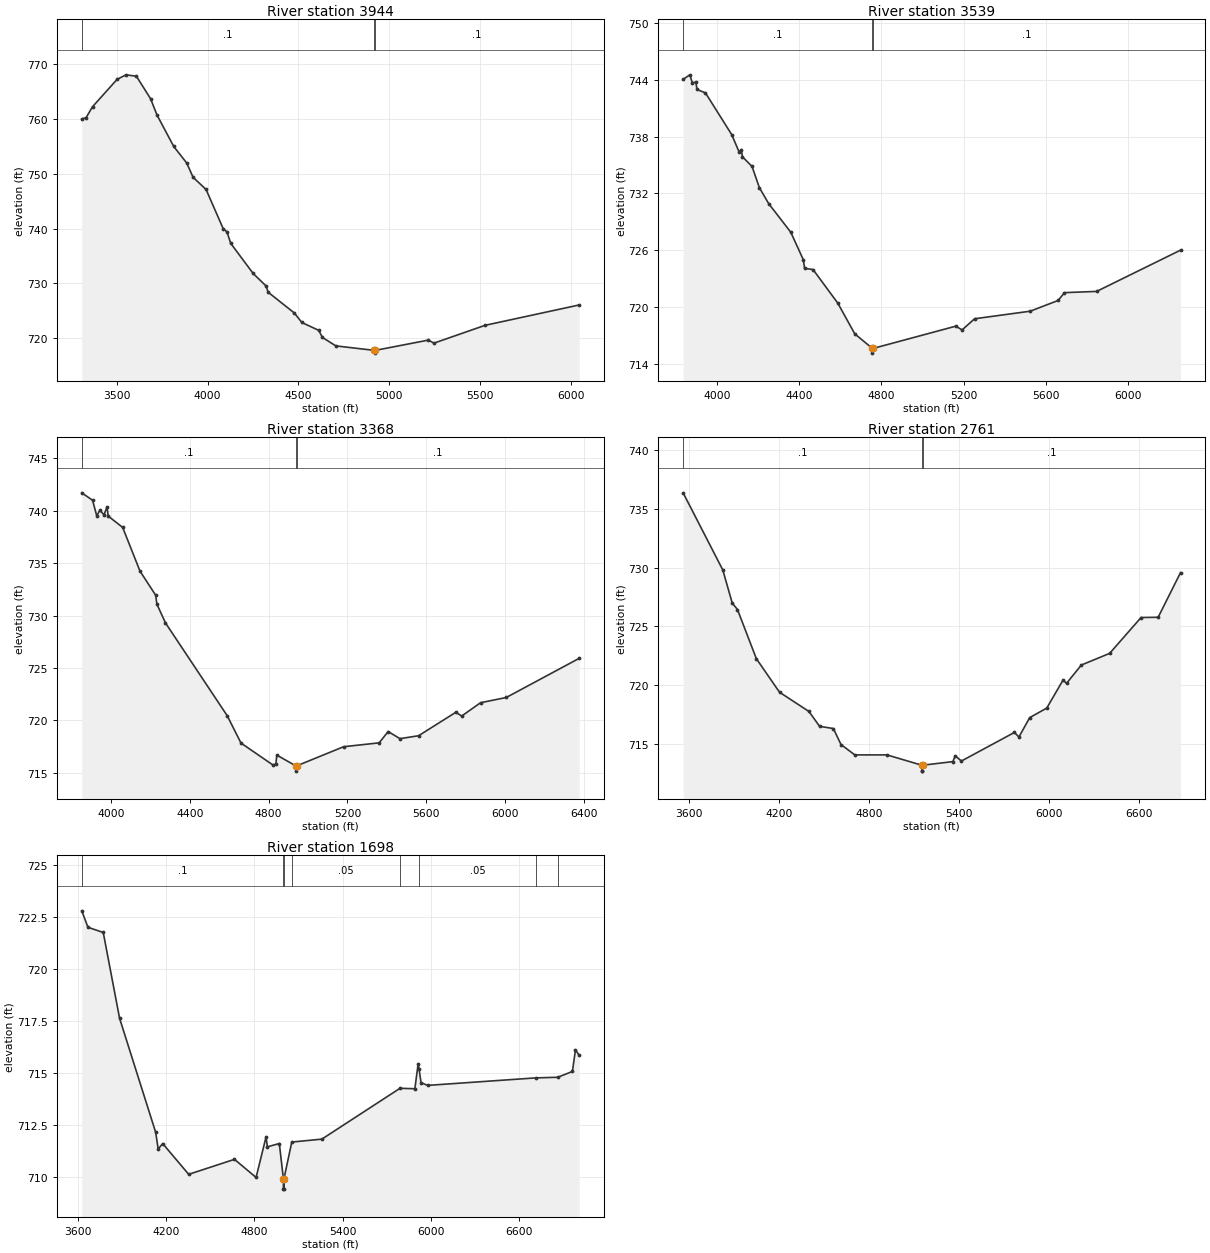
Type RM Length L Ch R = 1,3944,405,405,405
BEGIN DESCRIPTION:
UNT 044 in BCW 2.0
END DESCRIPTION:
XS GIS Cut Line= 4
      1977267.80     13607024.00      1976736.56     13607477.11
      1976481.36     13608513.57      1976569.80     13609481.19
#Sta/Elev= 30
  3308.0  760.00  3332.0  760.27  3367.1  762.24  3502.2  767.23  3551.6  768.06
  3608.7  767.80  3686.7  763.69  3721.8  760.73  3814.0  754.99  3885.4  751.97
  3920.5  749.36  3991.9  747.14  4086.4  739.97  4107.0  739.41  4127.6  737.31
  4251.2  731.81  4322.3  729.52  4333.6  728.39  4477.8  724.60  4519.0  722.87
  4611.7  721.44  4632.3  720.14  4706.2  718.60  4918.6  717.78  4918.9  717.28
  4922.6  717.78  5215.7  719.66  5245.8  719.10  5527.0  722.35  6045.3  726.07
#Mann=3,-1,0
  3308.0     0.1       0  4918.6    0.07       0  4922.6     0.1       0
Bank Sta=4918.6,4922.6
Exp/Cntr=0.3,0.1

Type RM Length L Ch R = 1,3539,171,171,171
BEGIN DESCRIPTION:
UNT 044 in BCW 3.0
END DESCRIPTION:
XS GIS Cut Line= 4
      1976465.73     13607175.04      1976116.77     13607971.90
      1976194.90     13608503.15      1976481.36     13609477.12
#Sta/Elev= 30
  3834.3  744.04  3867.0  744.52  3878.4  743.70  3896.4  743.73  3901.8  742.97
  3943.1  742.61  4071.0  738.20  4107.2  736.35  4117.7  736.62  4123.2  735.86
  4169.9  734.84  4205.4  732.61  4251.0  730.91  4358.3  727.90  4420.1  724.96
  4425.6  724.08  4466.9  723.95  4587.5  720.40  4670.3  717.15  4755.9  715.62
  4756.1  715.12  4759.9  715.62  5162.2  717.97  5192.5  717.57  5253.5  718.75
  5524.5  719.55  5660.0  720.68  5691.3  721.51  5847.7  721.64  6256.4  726.00
#Mann=3,-1,0
  3834.3     0.1       0  4755.9    0.07       0  4759.9     0.1       0
Bank Sta=4755.9,4759.9
Exp/Cntr=0.3,0.1

Type RM Length L Ch R = 1,3368,607,607,607
BEGIN DESCRIPTION:
UNT 044 in BCW 4.0
END DESCRIPTION:
XS GIS Cut Line= 4
      1976418.84     13607133.39      1976007.40     13607800.03
      1976054.27     13608555.24      1976429.26     13609466.66
#Sta/Elev= 30
  3851.4  741.72  3906.2  741.01  3927.5  739.51  3942.9  740.06  3964.2  739.62
  3979.6  740.39  3985.5  739.50  4058.8  738.42  4147.1  734.24  4226.7  731.94
  4232.6  731.10  4276.3  729.30  4589.8  720.44  4659.8  717.83  4820.1  715.76
  4836.7  715.80  4841.7  716.68  4938.3  715.65  4938.6  715.15  4942.3  715.65
  5180.8  717.48  5361.2  717.85  5407.0  718.93  5466.9  718.25  5561.5  718.53
  5750.8  720.77  5780.5  720.41  5876.0  721.68  6006.6  722.18  6377.0  725.92
#Mann=3,-1,0
  3851.4     0.1       0  4938.3    0.07       0  4942.3     0.1       0
Bank Sta=4938.3,4942.3
Exp/Cntr=0.3,0.1

Type RM Length L Ch R = 1,2761,1063,1063,1063
BEGIN DESCRIPTION:
UNT 044 in BCW 5.0
END DESCRIPTION:
XS GIS Cut Line= 4
      1976319.86     13607065.67      1975627.19     13607346.90
      1975439.69     13608268.78      1976355.47     13609611.23
#Sta/Elev= 30
  3560.9  736.35  3825.2  729.79  3888.0  726.98  3922.8  726.43  4048.7  722.25
  4202.9  719.40  4399.1  717.76  4469.8  716.50  4561.7  716.31  4612.7  714.95
  4704.5  714.07  4918.8  714.07  5151.5  713.19  5151.8  712.69  5155.3  712.69
  5155.5  713.19  5358.0  713.50  5372.9  713.99  5414.8  713.55  5767.8  715.98
  5797.7  715.59  5869.5  717.24  5983.2  718.05  6092.0  720.44  6114.7  720.15
  6213.6  721.71  6402.0  722.70  6611.3  725.75  6725.1  725.77  6874.3  729.57
#Mann=3,-1,0
  3560.9     0.1       0  5151.5    0.07       0  5155.5     0.1       0
Bank Sta=5151.5,5155.5
Exp/Cntr=0.3,0.1

Type RM Length L Ch R = 1,1698,0,0,0
BEGIN DESCRIPTION:
UNT 044 in BCW 1.0
END DESCRIPTION:
XS GIS Cut Line= 4
      1976019.57     13606614.26      1975299.06     13606709.75
      1974682.74     13607890.30      1975082.06     13609149.03
#Sta/Elev= 30
  3628.7  722.78  3670.5  721.99  3774.5  721.74  3885.5  717.62  4130.9  712.14
  4147.8  711.34  4178.0  711.61  4355.0  710.13  4666.0  710.85  4812.8  709.98
  4880.3  711.92  4889.8  711.45  4970.6  711.61  4998.2  709.92  4998.5  709.42
  5002.1  709.42  5002.3  709.92  5055.2  711.68  5259.6  711.82  5790.3  714.26
  5891.5  714.24  5913.7  715.44  5919.3  715.21  5933.5  714.53  5978.2  714.40
  6712.7  714.76  6862.4  714.79  6961.6  715.07  6982.6  716.11  7007.8  715.84
#Mann=8,-1,0
  3628.7     0.1       0  4998.2    0.07       0  5002.3     0.1       0
  5055.2    0.05       0  5790.3     0.1       0  5919.3    0.05       0
  6712.7     0.1       0  6862.4    0.05       0
Bank Sta=4998.2,5002.3
Exp/Cntr=0.3,0.1

Chan Stop Cuts=-1