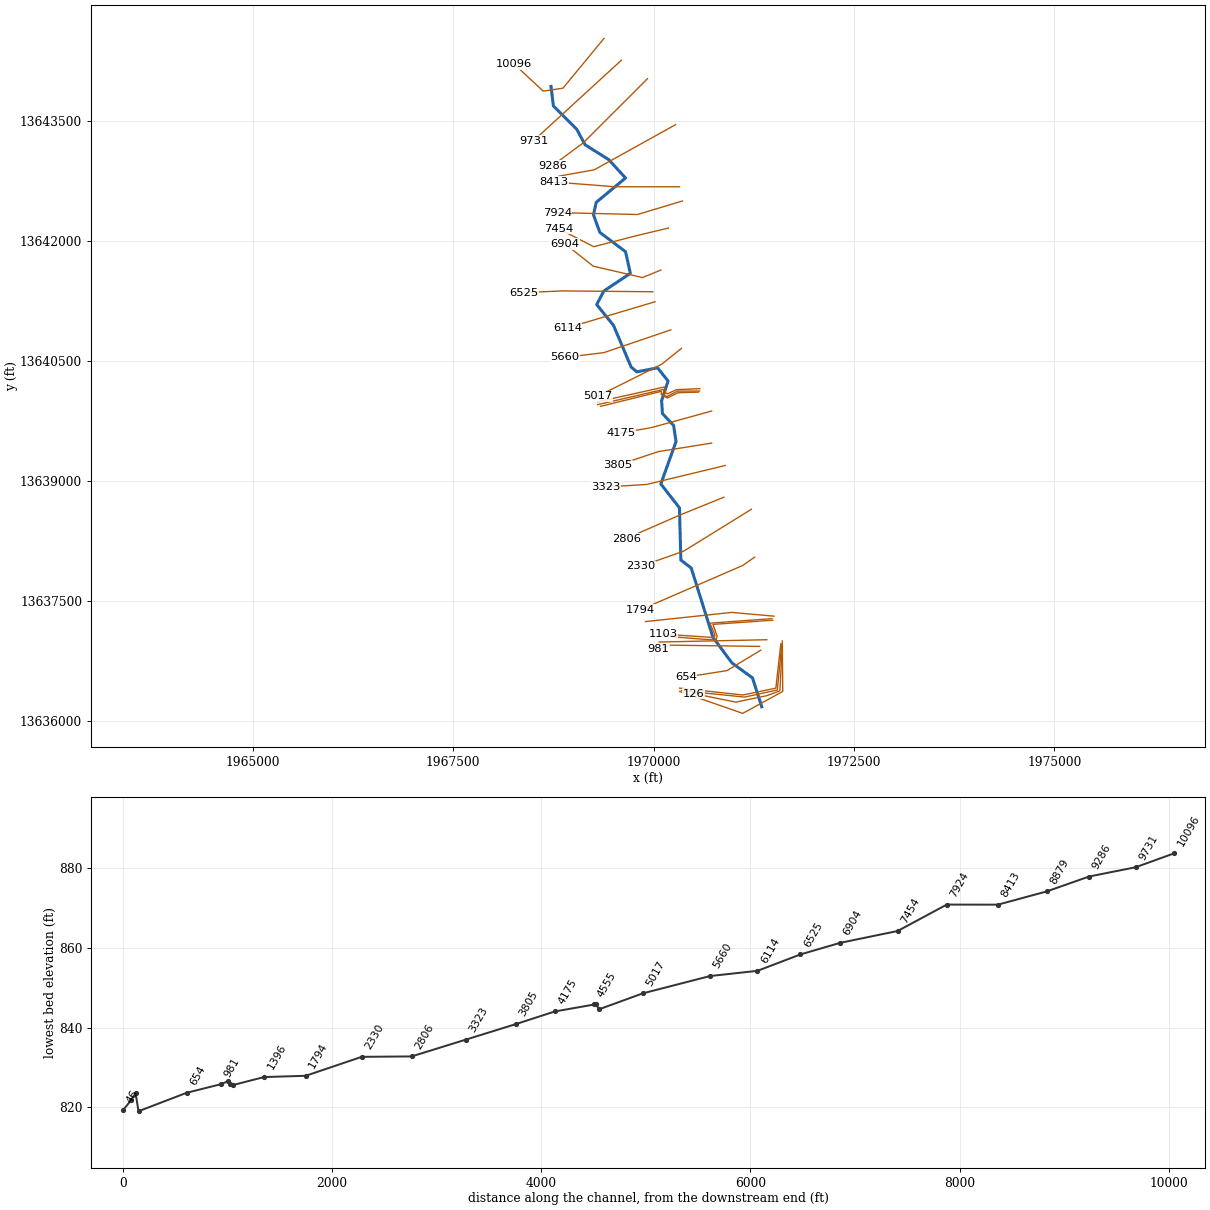
--- UNT 055 in BCW.prj (project) ---

Proj Title=UNT 055 in BCW Base Level Engineering
Current Plan=p01
Default Exp/Contr=0.3,0.1
English Units
Geom File=g01
Flow File=f01
Plan File=p01
Y Axis Title=Elevation
X Axis Title(PF)=Main Channel Distance
X Axis Title(XS)=Station
BEGIN DESCRIPTION:
UNT 055 in BCW
END DESCRIPTION:
DSS Export Rating Curves= 0
DSS Export Rating Curve Sorted= 0
DSS Export Volume Flow Curves= 0
DXF OffsetX= 0
DXF OffsetY= 0
DXF ScaleX= 1
DXF ScaleY= 10

--- UNT 055 in BCW.p01 (plan) ---

Plan Title=Multiple Run
Short Identifier=Multiple
Geom File=g01
Flow File=f01
Subcritical Flow
K Sum by GR= 0
Std Step Tol= 0.01
Critical Tol= 0.01
Num of Std Step Trials= 20
Max Error Tol= 0.3
Flow Tol Ratio= 0.001
Split Flow NTrial= 30
Split Flow Tol= 0.02
Split Flow Ratio= 0.02
Log Output Level= 0
Friction Slope Method= 1
Unsteady Friction Slope Method= 2
Unsteady Bridges Friction Slope Method= 1
Parabolic Critical Depth
Global Vel Dist=  1 , 1 , 1
Global Log Level= 0
CheckData=True
Encroach Param= -1, 0, 0, 0
BEGIN DESCRIPTION:
Multiple Run
END DESCRIPTION:

--- UNT 055 in BCW.f01 (steady flow) ---

Flow Title=Multiple
Program Version=5.05
Number of Profiles= 7
Profile Names=10-year,25-year,50-year,1pct_min,100-year,1pct_plu,500-year
River Rch & RM=UNT 055 in BCW,Reach-1         ,10096
     423     574     694     416     829    1655    1187
River Rch & RM=UNT 055 in BCW,Reach-1         ,9731
     530     730     893     540    1078    2152    1576
River Rch & RM=UNT 055 in BCW,Reach-1         ,6525
    1022    1460    1830    1132    2259    4507    3451
Boundary for River Rch & Prof#=UNT 055 in BCW,Reach-1         , 1
Up Type= 0
Dn Type= 3
Dn Slope=0.005
Boundary for River Rch & Prof#=UNT 055 in BCW,Reach-1         , 2
Up Type= 0
Dn Type= 3
Dn Slope=0.005
Boundary for River Rch & Prof#=UNT 055 in BCW,Reach-1         , 3
Up Type= 0
Dn Type= 3
Dn Slope=0.005
Boundary for River Rch & Prof#=UNT 055 in BCW,Reach-1         , 4
Up Type= 0
Dn Type= 3
Dn Slope=0.005
Boundary for River Rch & Prof#=UNT 055 in BCW,Reach-1         , 5
Up Type= 0
Dn Type= 3
Dn Slope=0.005
Boundary for River Rch & Prof#=UNT 055 in BCW,Reach-1         , 6
Up Type= 0
Dn Type= 3
Dn Slope=0.005
Boundary for River Rch & Prof#=UNT 055 in BCW,Reach-1         , 7
Up Type= 0
Dn Type= 3
Dn Slope=0.005
DSS Import GetInterval= 0
DSS Import GetPeak= 0
DSS Import FillOption= 0

--- UNT 055 in BCW.g01 (geometry) ---

Geom Title=Existing Conditions

River Reach=UNT 055 in BCW,Reach-1
Reach XY= 30
      1968720.69     13643928.03      1968750.80     13643684.54
      1969040.80     13643394.54      1969146.11     13643199.32
      1969440.80     13643014.54      1969650.80     13642784.54
      1969285.00     13642481.00      1969250.80     13642324.54
      1969330.80     13642104.54      1969650.80     13641864.54
      1969710.80     13641594.54      1969379.40     13641373.14
      1969290.80     13641204.54      1969500.80     13640944.54
      1969720.80     13640424.54      1969790.80     13640364.54
      1970050.80     13640414.54      1970181.27     13640250.10
      1970100.97     13640004.87      1970110.80     13639844.54
      1970250.80     13639694.54      1970280.80     13639494.54
      1970090.80     13638964.54      1970323.41     13638666.98
      1970340.80     13638014.54      1970470.80     13637914.54
      1970741.17     13637050.23      1970978.80     13636730.13
      1971234.87     13636543.50      1971349.70     13636183.44

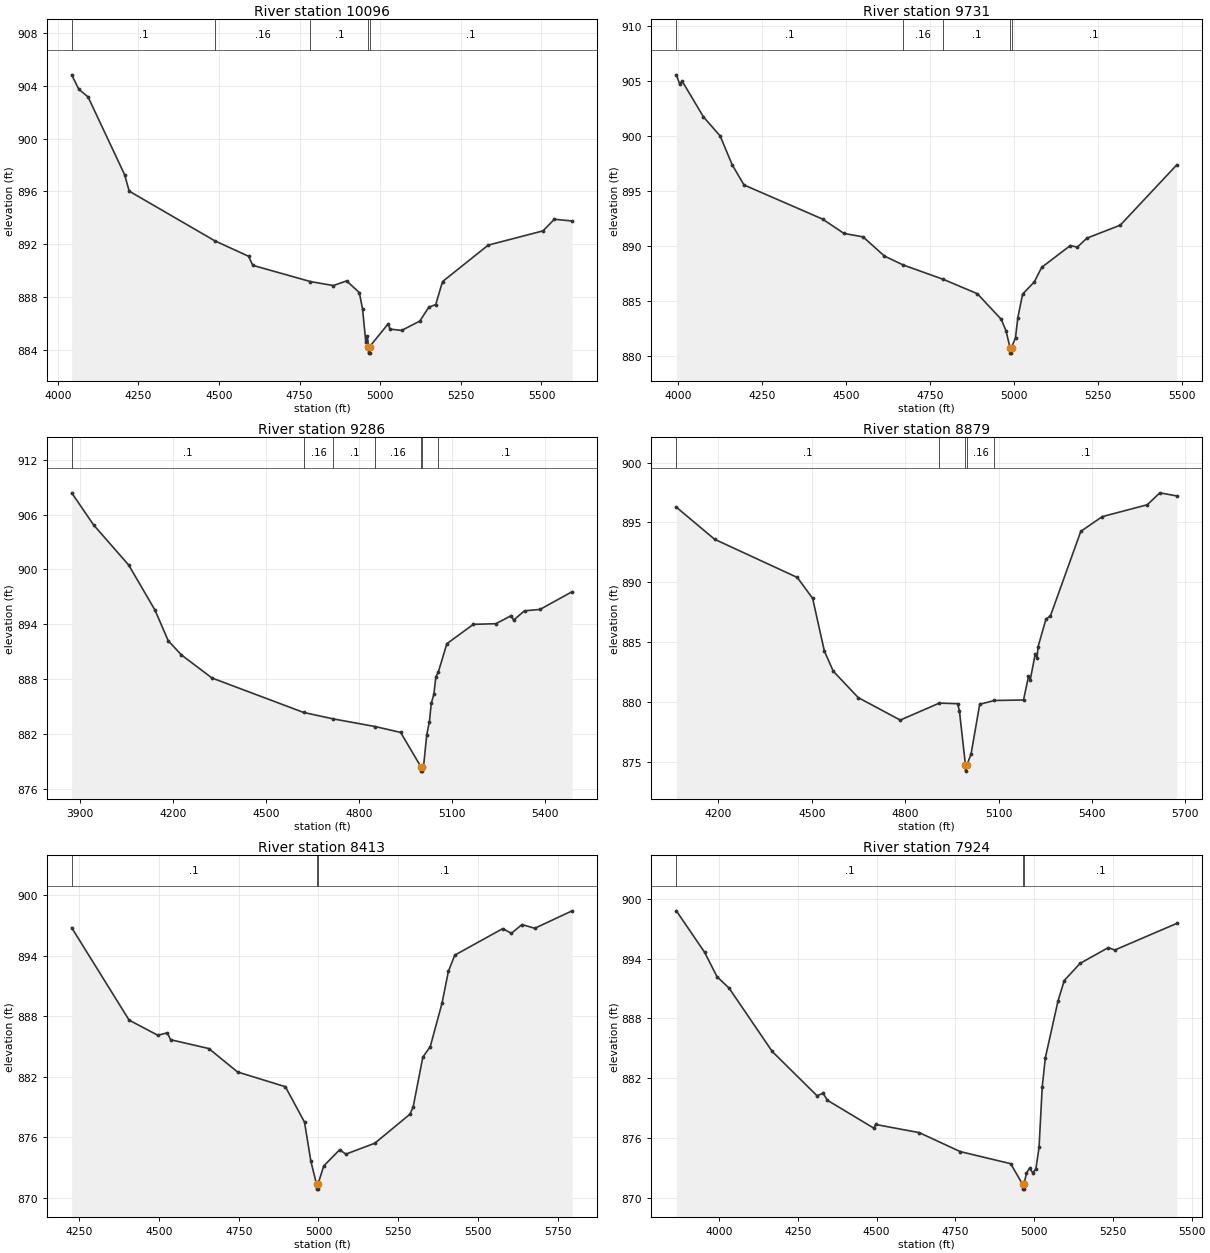
Type RM Length L Ch R = 1,10096,365,365,365
BEGIN DESCRIPTION:
UNT 055 in BCW 21.0
END DESCRIPTION:
XS GIS Cut Line= 4
      1969382.76     13644528.54      1968869.74     13643906.15
      1968622.35     13643869.70      1968260.34     13644208.27
#Sta/Elev= 30
  4042.8  904.83  4064.8  903.74  4093.5  903.16  4206.9  897.27  4221.2  896.02
  4487.3  892.25  4591.3  891.09  4604.6  890.40  4783.4  889.17  4854.3  888.87
  4895.6  889.22  4935.0  888.34  4945.1  887.09  4955.2  884.56  4960.2  885.01
  4963.4  884.25  4963.6  883.75  4967.1  883.75  4967.4  884.25  5024.9  885.98
  5029.9  885.57  5066.4  885.47  5122.8  886.18  5150.6  887.23  5172.1  887.43
  5193.1  889.17  5334.8  891.93  5504.8  893.01  5539.9  893.89  5595.1  893.76
#Mann=5,-1,0
  4042.8     0.1       0  4487.3    0.16       0  4783.4     0.1       0
  4963.4    0.07       0  4967.4     0.1       0
Bank Sta=4963.4,4967.4
Exp/Cntr=0.3,0.1

Type RM Length L Ch R = 1,9731,445,445,445
BEGIN DESCRIPTION:
Mapping XS e1b89a96
END DESCRIPTION:
XS GIS Cut Line= 2
      1969598.90     13644255.11      1968502.57     13643249.92
#Sta/Elev= 30
  3995.9  905.53  4005.7  904.70  4013.1  904.96  4076.6  901.71  4126.0  899.99
  4161.7  897.38  4196.9  895.54  4430.6  892.44  4494.1  891.14  4550.8  890.83
  4614.3  889.09  4670.0  888.28  4789.7  886.97  4890.6  885.67  4961.5  883.35
  4975.7  882.32  4987.6  880.78  4987.9  880.28  4991.8  880.28  4992.1  880.78
  5004.0  881.69  5010.8  883.47  5025.0  885.63  5060.1  886.75  5081.7  888.06
  5166.8  890.04  5187.8  889.90  5216.1  890.71  5315.4  891.89  5483.3  897.36
#Mann=5,-1,0
  3995.9     0.1       0  4670.0    0.16       0  4789.7     0.1       0
  4987.6    0.07       0  4992.1     0.1       0
Bank Sta=4987.6,4992.1
Exp/Cntr=0.3,0.1

Type RM Length L Ch R = 1,9286,407,407,407
BEGIN DESCRIPTION:
UNT 055 in BCW 20.0
END DESCRIPTION:
XS GIS Cut Line= 3
      1969925.00     13644025.00      1969125.00     13643225.00
      1968737.55     13642937.91
#Sta/Elev= 30
  3874.1  908.38  3944.8  904.87  4058.0  900.48  4142.8  895.55  4185.2  892.22
  4227.7  890.66  4326.7  888.13  4621.6  884.37  4717.7  883.66  4853.4  882.82
  4934.8  882.18  4999.7  878.45  5000.0  877.95  5003.9  877.95  5004.2  878.45
  5008.6  878.45  5019.0  881.93  5027.4  883.33  5033.6  885.36  5042.0  886.36
  5048.3  888.24  5056.6  888.81  5083.7  891.88  5169.3  894.00  5241.9  894.07
  5291.7  894.96  5298.7  894.45  5334.2  895.48  5384.2  895.63  5487.7  897.57
#Mann=7,-1,0
  3874.1     0.1       0  4621.6    0.16       0  4717.7     0.1       0
  4853.4    0.16       0  4999.7    0.07       0  5004.2    0.16       0
  5056.6     0.1       0
Bank Sta=4999.7,5004.2
Exp/Cntr=0.3,0.1

Type RM Length L Ch R = 1,8879,466,466,466
BEGIN DESCRIPTION:
Mapping XS 0cba3077
END DESCRIPTION:
XS GIS Cut Line= 3
      1970275.56     13643450.91      1969259.97     13642886.69
      1968821.58     13642808.56
#Sta/Elev= 30
  4065.2  896.28  4188.3  893.59  4453.7  890.40  4502.9  888.65  4540.6  884.24
  4569.2  882.56  4649.3  880.35  4784.3  878.47  4909.6  879.89  4968.5  879.84
  4974.2  879.26  4993.7  874.70  4994.0  874.20  4998.2  874.70  5011.9  875.66
  5039.4  879.79  5086.8  880.11  5180.1  880.15  5196.1  882.12  5201.8  881.84
  5217.9  884.02  5223.6  883.67  5227.0  884.62  5252.4  886.93  5266.4  887.17
  5364.1  894.26  5433.1  895.49  5577.4  896.48  5618.0  897.48  5672.3  897.22
#Mann=5,-1,0
  4065.2     0.1       0  4909.6    0.16       0  4993.7    0.07       0
  4998.2    0.16       0  5086.8     0.1       0
Bank Sta=4993.7,4998.2
Exp/Cntr=0.3,0.1

Type RM Length L Ch R = 1,8413,489,489,489
BEGIN DESCRIPTION:
UNT 055 in BCW 18.0
END DESCRIPTION:
XS GIS Cut Line= 3
      1970324.96     13642675.00      1969525.00     13642675.00
      1968758.28     13642734.64
#Sta/Elev= 30
  4226.3  896.79  4406.3  887.63  4496.3  886.13  4526.3  886.37  4536.3  885.69
  4656.3  884.81  4746.3  882.49  4896.3  881.03  4956.3  877.52  4976.3  873.63
  4993.9  871.38  4994.2  870.88  4998.3  870.88  4998.7  871.38  5016.3  873.17
  5066.4  874.78  5086.1  874.35  5176.7  875.43  5287.0  878.31  5297.1  879.05
  5327.2  883.96  5350.4  884.99  5387.3  889.29  5407.4  892.47  5427.5  894.07
  5577.9  896.70  5604.7  896.23  5638.1  897.10  5678.2  896.73  5795.3  898.46
#Mann=3,-1,0
  4226.3     0.1       0  4993.9    0.07       0  4998.7     0.1       0
Bank Sta=4993.9,4998.7
Exp/Cntr=0.3,0.1

Type RM Length L Ch R = 1,7924,470,470,470
BEGIN DESCRIPTION:
UNT 055 in BCW 17.0
END DESCRIPTION:
XS GIS Cut Line= 3
      1970360.76     13642498.23      1969800.87     13642328.96
      1968798.08     13642352.79
#Sta/Elev= 30
  3864.8  898.78  3954.4  894.63  3993.9  892.18  4032.1  891.04  4169.1  884.69
  4311.4  880.25  4330.5  880.51  4344.3  879.80  4492.0  877.00  4497.0  877.38
  4635.6  876.56  4765.7  874.66  4925.7  873.45  4963.3  871.40  4963.7  870.90
  4967.8  870.90  4968.1  871.40  4975.7  872.49  4985.7  873.00  4995.7  872.54
  5005.7  872.92  5015.8  875.08  5025.8  881.12  5035.8  884.07  5075.8  889.73
  5095.8  891.80  5145.8  893.51  5235.8  895.10  5255.8  894.85  5452.8  897.52
#Mann=3,-1,0
  3864.8     0.1       0  4963.3    0.07       0  4968.1     0.1       0
Bank Sta=4963.3,4968.1
Exp/Cntr=0.3,0.1

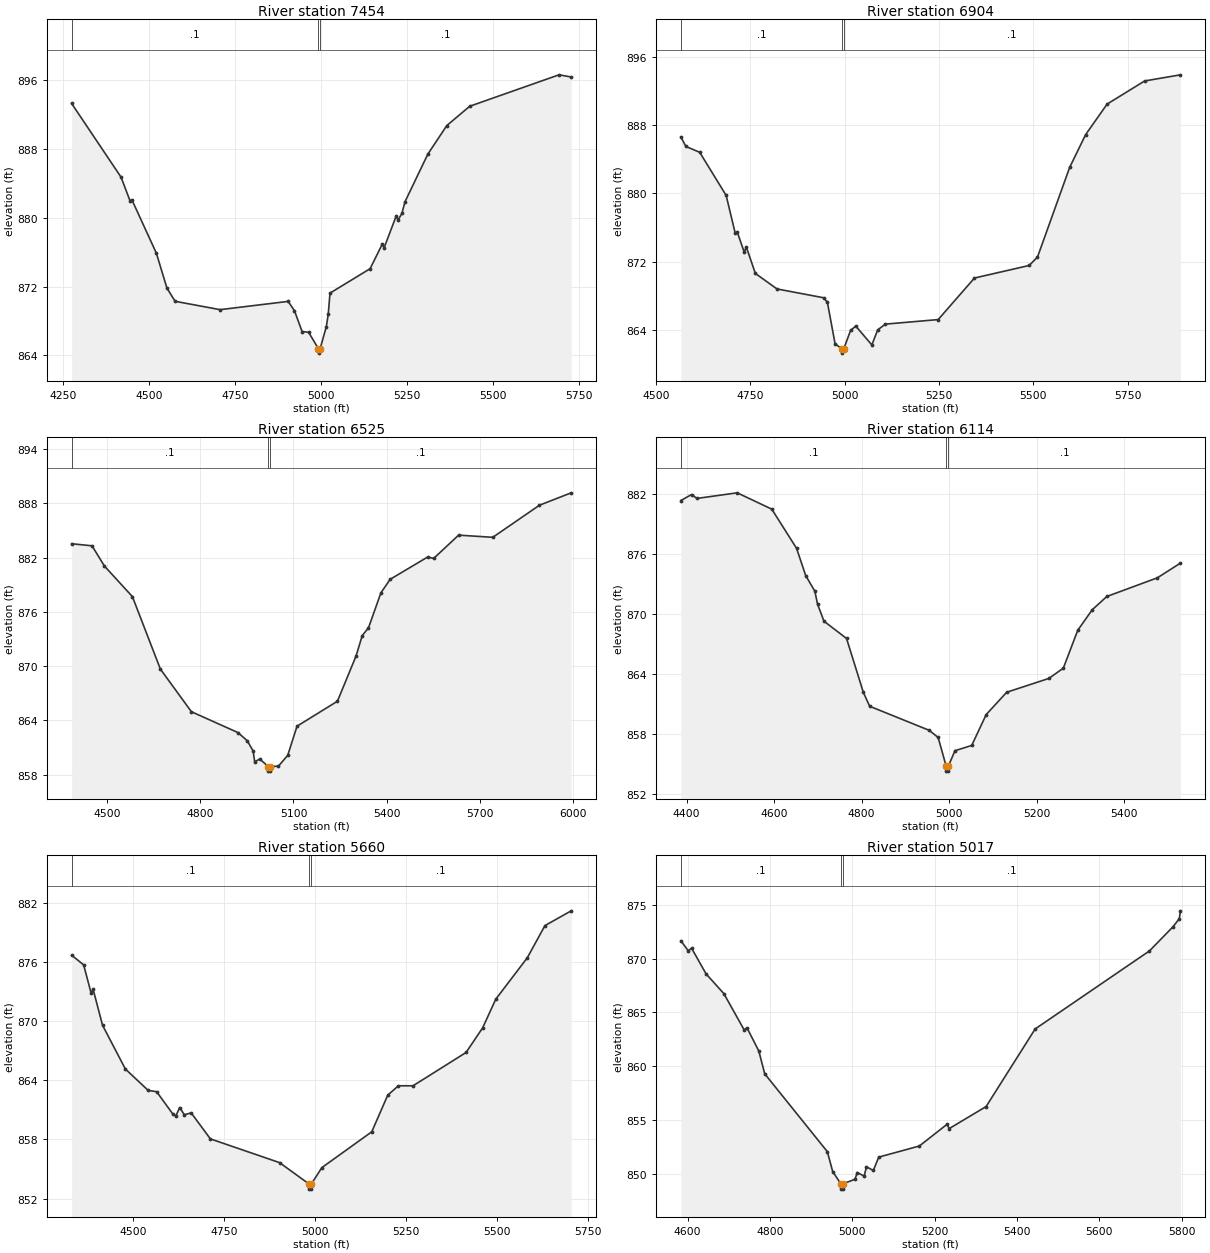
Type RM Length L Ch R = 1,7454,550,550,550
BEGIN DESCRIPTION:
Mapping XS 99e56e87
END DESCRIPTION:
XS GIS Cut Line= 4
      1970184.94     13642159.68      1969778.74     13642062.47
      1969254.43     13641927.05      1968813.42     13642152.77
#Sta/Elev= 30
  4273.8  893.27  4417.7  884.71  4443.9  881.95  4449.0  882.10  4520.5  875.88
  4551.4  871.81  4575.1  870.29  4706.1  869.32  4904.2  870.28  4922.6  869.20
  4944.8  866.78  4963.9  866.69  4992.5  864.77  4992.8  864.27  4997.3  864.77
  5015.5  867.36  5021.0  868.80  5026.1  871.24  5142.9  874.08  5178.4  876.94
  5183.6  876.50  5219.1  880.23  5224.2  879.72  5235.5  880.50  5244.3  881.84
  5311.0  887.39  5366.3  890.71  5433.0  892.95  5692.9  896.60  5728.4  896.35
#Mann=3,-1,0
  4273.8     0.1       0  4992.5    0.07       0  4997.3     0.1       0
Bank Sta=4992.5,4997.3
Exp/Cntr=0.3,0.1

Type RM Length L Ch R = 1,6904,379,379,379
BEGIN DESCRIPTION:
Mapping XS fe52a0f9
END DESCRIPTION:
XS GIS Cut Line= 4
      1970091.21     13641635.38      1969862.07     13641541.64
      1969247.49     13641684.00      1968897.89     13641960.91
#Sta/Elev= 30
  4565.6  886.62  4578.8  885.51  4615.5  884.82  4685.6  879.77  4709.6  875.35
  4715.0  875.49  4733.6  873.11  4739.0  873.74  4763.0  870.63  4820.4  868.81
  4943.8  867.78  4953.9  867.27  4974.4  862.39  4992.5  861.79  4992.8  861.29
  4997.4  861.79  5015.5  863.95  5029.2  864.46  5071.9  862.25  5087.3  864.01
  5107.8  864.69  5247.7  865.22  5343.9  870.09  5488.9  871.56  5511.0  872.54
  5596.3  883.05  5638.6  886.89  5695.6  890.47  5795.0  893.18  5890.0  893.90
#Mann=3,-1,0
  4565.6     0.1       0  4992.5    0.07       0  4997.4     0.1       0
Bank Sta=4992.5,4997.4
Exp/Cntr=0.3,0.1

Type RM Length L Ch R = 1,6525,411,411,411
BEGIN DESCRIPTION:
Mapping XS 494b9f6f
END DESCRIPTION:
XS GIS Cut Line= 3
      1969990.57     13641364.55      1968865.54     13641374.97
      1968382.87     13641354.14
#Sta/Elev= 30
  4385.9  883.54  4451.5  883.31  4491.5  881.07  4581.5  877.69  4671.5  869.68
  4771.5  864.96  4921.5  862.65  4951.5  861.74  4970.2  860.61  4975.2  859.42
  4991.5  859.73  5019.1  858.89  5019.4  858.39  5023.6  858.39  5024.0  858.89
  5051.5  858.94  5081.5  860.13  5111.5  863.36  5241.5  866.12  5301.5  871.12
  5321.5  873.39  5341.5  874.23  5381.5  878.11  5411.5  879.61  5531.5  882.06
  5551.6  881.92  5631.6  884.49  5741.7  884.25  5891.9  887.80  5994.1  889.17
#Mann=3,-1,0
  4385.9     0.1       0  5019.1    0.07       0  5024.0     0.1       0
Bank Sta=5019.1,5024
Exp/Cntr=0.3,0.1

Type RM Length L Ch R = 1,6114,454,454,454
BEGIN DESCRIPTION:
Mapping XS 30adbeee
END DESCRIPTION:
XS GIS Cut Line= 2
      1970018.30     13641239.55      1968924.56     13640913.16
#Sta/Elev= 30
  4386.9  881.34  4411.2  881.94  4423.6  881.55  4515.6  882.11  4594.5  880.48
  4651.2  876.56  4672.1  873.83  4693.0  872.27  4699.1  870.98  4713.8  869.27
  4765.4  867.54  4803.8  862.15  4818.2  860.76  4953.9  858.36  4974.7  857.64
  4993.0  854.77  4993.4  854.27  4997.8  854.27  4998.2  854.77  5013.0  856.31
  5051.4  856.84  5084.5  859.93  5131.3  862.16  5227.5  863.54  5260.7  864.57
  5293.8  868.37  5326.9  870.42  5360.1  871.74  5475.7  873.61  5528.3  875.08
#Mann=3,-1,0
  4386.9     0.1       0  4993.0    0.07       0  4998.2     0.1       0
Bank Sta=4993,4998.2
Exp/Cntr=0.3,0.1

Type RM Length L Ch R = 1,5660,643,643,643
BEGIN DESCRIPTION:
Mapping XS 0a01c850
END DESCRIPTION:
XS GIS Cut Line= 3
      1970216.21     13640888.85      1969379.43     13640604.14
      1968893.29     13640545.11
#Sta/Elev= 30
  4330.3  876.71  4363.3  875.72  4384.0  872.84  4389.3  873.25  4415.3  869.59
  4478.1  865.15  4540.8  862.98  4564.0  862.85  4608.8  860.57  4616.8  860.38
  4627.3  861.24  4640.2  860.51  4659.0  860.70  4711.8  858.06  4902.0  855.65
  4983.9  853.46  4984.3  852.96  4988.7  852.96  4989.1  853.46  5018.2  855.14
  5155.5  858.78  5199.5  862.50  5228.7  863.45  5269.0  863.45  5414.8  866.83
  5460.4  869.33  5496.5  872.24  5583.3  876.45  5631.7  879.71  5703.9  881.21
#Mann=3,-1,0
  4330.3     0.1       0  4983.9    0.07       0  4989.1     0.1       0
Bank Sta=4983.9,4989.1
Exp/Cntr=0.3,0.1

Type RM Length L Ch R = 1,5017,415,415,415
BEGIN DESCRIPTION:
UNT 055 in BCW 10.0
END DESCRIPTION:
XS GIS Cut Line= 3
      1970348.58     13640657.62      1970098.61     13640457.64
      1969299.28     13640057.97
#Sta/Elev= 30
  4583.5  871.65  4601.5  870.72  4609.5  870.96  4644.7  868.58  4687.9  866.75
  4737.6  863.36  4744.0  863.58  4772.8  861.43  4787.2  859.31  4939.3  852.09
  4952.4  850.24  4972.0  849.11  4972.4  848.61  4977.0  848.61  4977.5  849.11
  5006.4  849.52  5012.0  850.15  5028.8  849.82  5034.4  850.68  5051.1  850.34
  5064.2  851.58  5162.9  852.61  5230.0  854.62  5235.6  854.23  5325.1  856.27
  5444.3  863.47  5722.0  870.71  5779.7  872.97  5794.6  873.71  5797.3  874.43
#Mann=3,-1,0
  4583.5     0.1       0  4972.0    0.07       0  4977.5     0.1       0
Bank Sta=4972,4977.5
Exp/Cntr=0.3,0.1

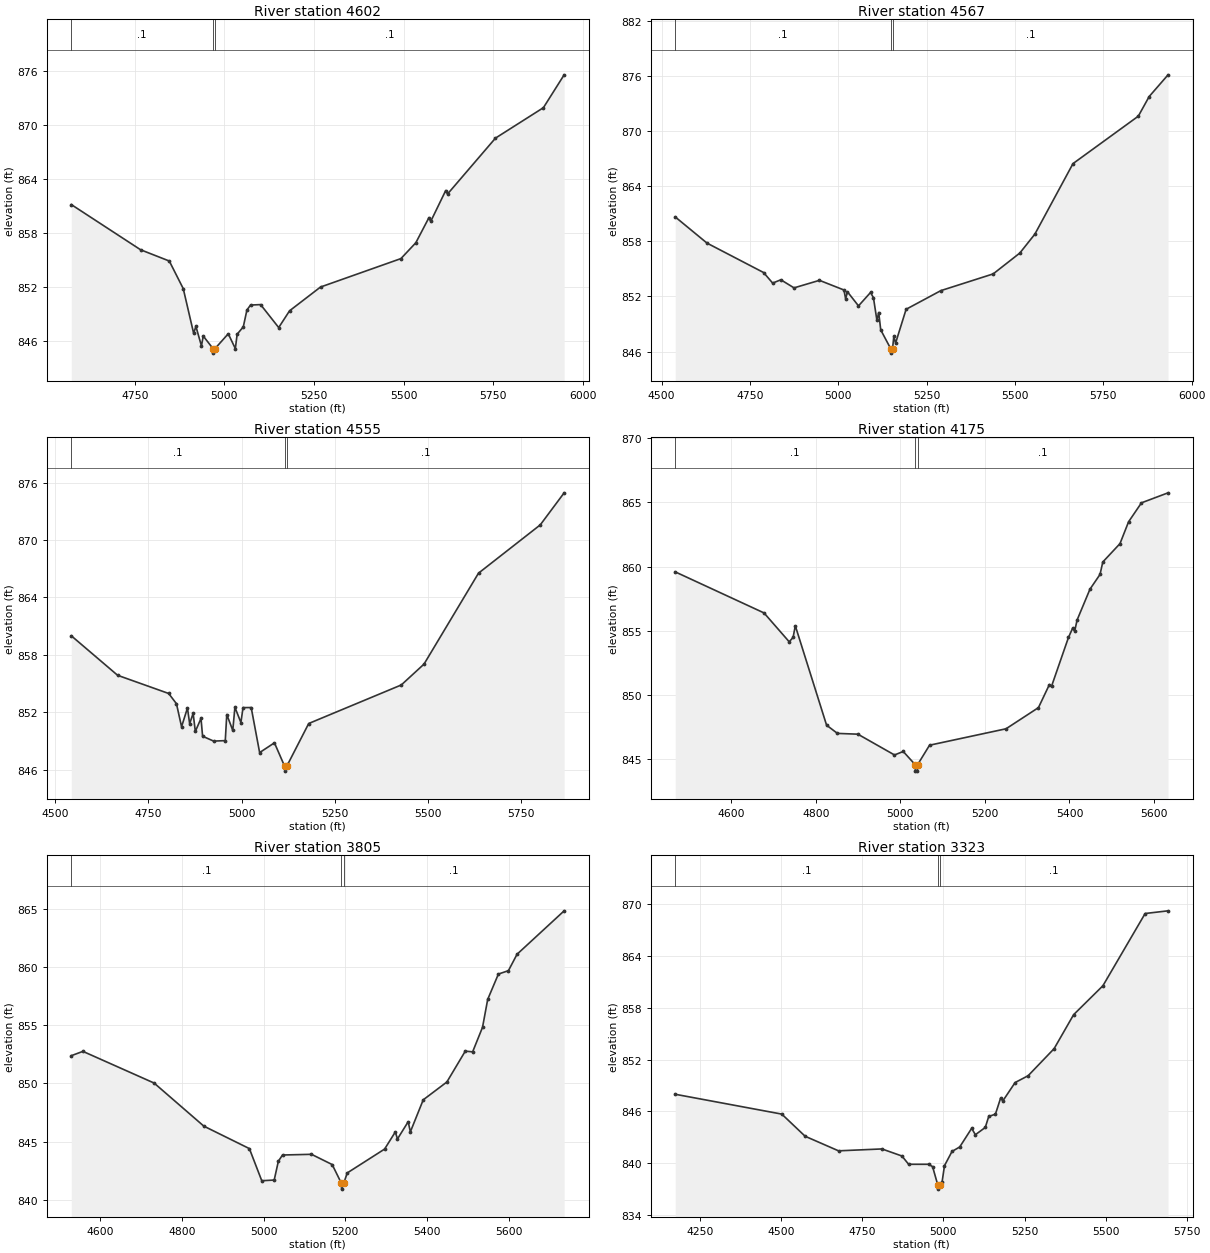
Type RM Length L Ch R = 1,4602,35,35,35
BEGIN DESCRIPTION:
Mapping XS 36c96c05
END DESCRIPTION:
XS GIS Cut Line= 6
      1970578.24     13640154.49      1970286.55     13640142.33
      1970175.44     13640090.25      1970152.87     13640097.19
      1970140.72     13640177.05      1969308.73     13639991.62
#Sta/Elev= 30
  4572.7  861.14  4766.1  856.12  4846.2  854.87  4885.2  851.80  4914.2  846.84
  4920.5  847.61  4936.0  845.44  4941.0  846.54  4968.3  845.14  4968.8  844.64
  4973.8  845.14  5010.8  846.79  5030.6  845.14  5035.6  846.74  5052.8  847.56
  5062.9  849.43  5073.0  849.98  5101.1  850.03  5151.6  847.48  5181.9  849.34
  5268.3  851.98  5492.8  855.14  5534.4  856.90  5571.0  859.69  5576.1  859.28
  5617.8  862.70  5622.9  862.31  5756.7  868.52  5890.5  871.90  5948.4  875.55
#Mann=3,-1,0
  4572.7     0.1       0  4968.3    0.07       0  4973.8     0.1       0
Bank Sta=4968.3,4973.8
Exp/Cntr=0.3,0.1

Type RM Length L Ch R = 1,4567,12,12,12
BEGIN DESCRIPTION:
UNT 055 in BCW 9.0
END DESCRIPTION:
XS GIS Cut Line= 6
      1970575.02     13640125.00      1970298.70     13640124.10
      1970169.36     13640057.26      1970132.90     13640071.15
      1970125.96     13640145.80      1969303.01     13639954.82
#Sta/Elev= 30
  4538.7  860.65  4628.7  857.80  4788.7  854.60  4814.4  853.45  4837.6  853.81
  4874.9  852.93  4946.8  853.75  5016.1  852.70  5020.9  851.74  5026.1  852.50
  5057.3  850.97  5091.4  852.43  5099.6  851.86  5109.4  849.40  5114.5  850.25
  5120.2  848.36  5148.2  846.33  5148.7  845.83  5153.7  846.33  5157.2  847.64
  5162.3  846.93  5192.0  850.60  5290.3  852.63  5438.4  854.45  5513.8  856.72
  5556.4  858.78  5664.2  866.45  5849.0  871.61  5879.8  873.75  5933.2  876.11
#Mann=3,-1,0
  4538.7     0.1       0  5148.2    0.07       0  5153.7     0.1       0
Bank Sta=5148.2,5153.7
Exp/Cntr=0.3,0.1

Type RM Length L Ch R = 1,4555,380,380,380
BEGIN DESCRIPTION:
Mapping XS 99e35874
END DESCRIPTION:
XS GIS Cut Line= 6
      1970559.11     13640111.08      1970305.65     13640104.14
      1970173.70     13640038.17      1970097.31     13640079.83
      1970097.31     13640121.50      1969340.33     13639933.99
#Sta/Elev= 30
  4543.6  859.98  4667.8  855.85  4804.6  853.95  4825.5  852.88  4839.2  850.47
  4855.0  852.43  4860.9  850.79  4870.2  851.87  4876.1  849.98  4891.3  851.34
  4895.6  849.48  4925.1  848.97  4956.4  849.02  4960.4  851.75  4976.5  850.09
  4982.2  852.51  4998.3  850.91  5004.0  852.47  5025.9  852.48  5048.5  847.77
  5088.2  848.79  5115.6  846.33  5116.0  845.83  5121.1  846.33  5180.1  850.81
  5428.3  854.84  5489.2  857.02  5635.3  866.53  5800.9  871.58  5864.9  874.93
#Mann=3,-1,0
  4543.6     0.1       0  5115.6    0.07       0  5121.1     0.1       0
Bank Sta=5115.6,5121.1
Exp/Cntr=0.3,0.1

Type RM Length L Ch R = 1,4175,370,370,370
BEGIN DESCRIPTION:
UNT 055 in BCW 8.0
END DESCRIPTION:
XS GIS Cut Line= 3
      1970724.99     13639875.00      1969970.58     13639667.51
      1969592.97     13639602.40
#Sta/Elev= 30
  4467.5  859.59  4677.5  856.39  4737.1  854.14  4746.3  854.48  4751.5  855.39
  4825.5  847.64  4851.2  847.00  4899.5  846.94  4986.1  845.32  5006.8  845.59
  5035.1  844.56  5035.6  844.06  5040.3  844.06  5040.7  844.56  5069.0  846.08
  5249.9  847.36  5326.6  849.01  5352.5  850.81  5357.5  850.67  5397.6  854.48
  5407.3  855.19  5412.3  854.97  5417.9  855.83  5448.4  858.24  5472.2  859.39
  5478.8  860.36  5519.4  861.79  5539.7  863.49  5570.2  864.97  5633.1  865.75
#Mann=3,-1,0
  4467.5     0.1       0  5035.1    0.07       0  5040.7     0.1       0
Bank Sta=5035.1,5040.7
Exp/Cntr=0.3,0.1

Type RM Length L Ch R = 1,3805,482,482,482
BEGIN DESCRIPTION:
UNT 055 in BCW 7.0
END DESCRIPTION:
XS GIS Cut Line= 3
      1970724.98     13639475.00      1970057.38     13639368.03
      1969555.78     13639199.39
#Sta/Elev= 30
  4529.9  852.37  4558.3  852.74  4732.4  850.02  4854.0  846.32  4965.4  844.39
  4995.7  841.63  5026.1  841.69  5036.3  843.31  5046.4  843.84  5117.3  843.90
  5167.9  843.02  5190.5  841.41  5191.0  840.91  5196.2  841.41  5204.7  842.30
  5296.1  844.35  5322.3  845.82  5327.6  845.22  5353.8  846.70  5359.1  845.83
  5390.6  848.58  5448.4  850.11  5493.4  852.76  5511.4  852.70  5535.6  854.81
  5548.2  857.20  5574.4  859.38  5598.9  859.67  5620.0  861.08  5735.2  864.81
#Mann=3,-1,0
  4529.9     0.1       0  5190.5    0.07       0  5196.2     0.1       0
Bank Sta=5190.5,5196.2
Exp/Cntr=0.3,0.1

Type RM Length L Ch R = 1,3323,517,517,517
BEGIN DESCRIPTION:
Mapping XS 883111ce
END DESCRIPTION:
XS GIS Cut Line= 3
      1970894.22     13639195.29      1969912.42     13638958.30
      1969404.58     13638927.05
#Sta/Elev= 30
  4173.5  847.98  4501.9  845.68  4573.9  843.11  4676.8  841.42  4810.5  841.64
  4872.2  840.82  4892.8  839.86  4954.5  839.86  4966.6  839.59  4982.5  837.48
  4983.0  836.98  4988.3  837.48  4995.7  837.75  5003.3  839.70  5026.5  841.35
  5050.3  841.87  5087.1  844.03  5098.5  843.29  5129.0  844.13  5139.7  845.41
  5160.3  845.67  5176.0  847.50  5183.5  847.23  5221.0  849.34  5261.1  850.13
  5341.2  853.27  5401.3  857.21  5491.5  860.56  5621.7  868.94  5692.3  869.25
#Mann=3,-1,0
  4173.5     0.1       0  4982.5    0.07       0  4988.3     0.1       0
Bank Sta=4982.5,4988.3
Exp/Cntr=0.3,0.1

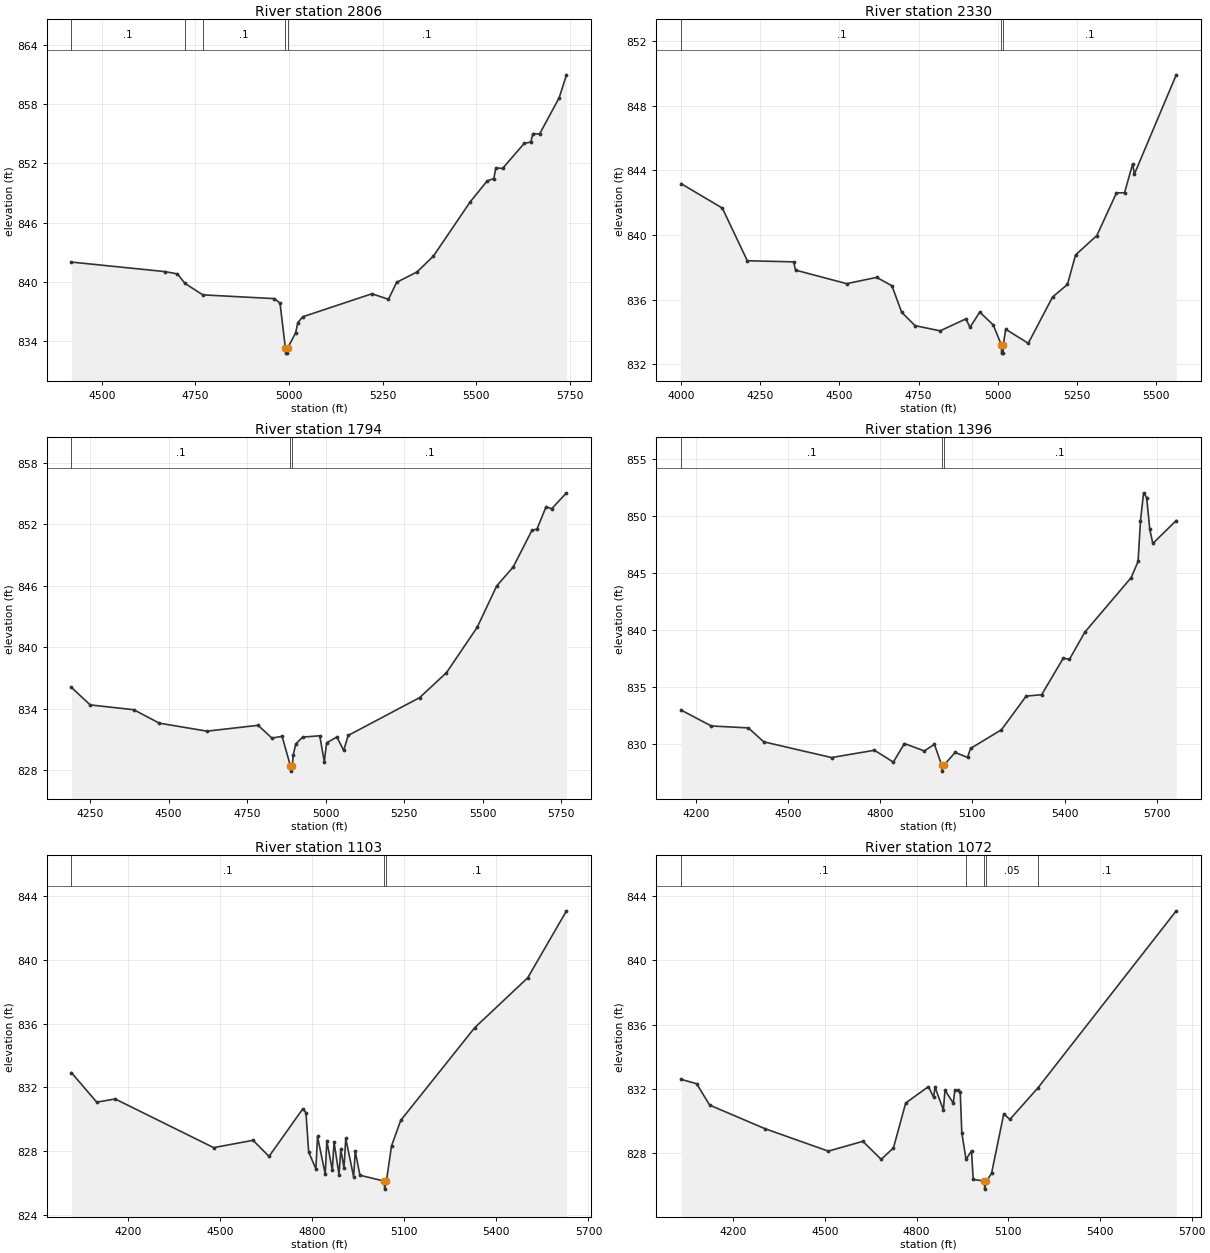
Type RM Length L Ch R = 1,2806,476,476,476
BEGIN DESCRIPTION:
UNT 055 in BCW 6.0
END DESCRIPTION:
XS GIS Cut Line= 3
      1970877.71     13638799.46      1970325.00     13638575.00
      1969659.00     13638283.36
#Sta/Elev= 30
  4418.3  842.00  4669.5  841.03  4701.8  840.80  4721.9  839.84  4769.5  838.68
  4960.9  838.30  4976.0  837.84  4990.4  833.28  4990.9  832.78  4995.7  832.78
  4996.2  833.28  5017.6  834.83  5023.8  835.88  5036.7  836.46  5221.8  838.79
  5265.9  838.23  5287.8  839.95  5342.3  841.00  5386.0  842.60  5484.3  848.09
  5529.7  850.21  5547.6  850.46  5553.0  851.54  5571.0  851.48  5628.6  854.01
  5646.6  854.16  5652.0  855.01  5669.8  854.96  5722.2  858.63  5741.9  860.96
#Mann=5,-1,0
  4418.3     0.1       0  4721.9    0.16       0  4769.5     0.1       0
  4990.4    0.07       0  4996.2     0.1       0
Bank Sta=4990.4,4996.2
Exp/Cntr=0.3,0.1

Type RM Length L Ch R = 1,2330,536,536,536
BEGIN DESCRIPTION:
UNT 055 in BCW 5.0
END DESCRIPTION:
XS GIS Cut Line= 3
      1971220.55     13638648.51      1970375.00     13638125.00
      1969836.06     13637935.75
#Sta/Elev= 30
  3999.4  843.17  4129.5  841.66  4208.6  838.40  4355.2  838.33  4361.1  837.82
  4523.0  836.98  4617.5  837.37  4666.0  836.85  4696.7  835.21  4739.2  834.38
  4818.4  834.06  4899.8  834.80  4912.9  834.28  4943.7  835.22  4986.2  834.43
  5012.1  833.18  5012.6  832.68  5017.6  832.68  5018.1  833.18  5025.7  834.16
  5097.1  833.29  5174.1  836.16  5221.0  836.93  5246.7  838.76  5314.0  839.96
  5376.0  842.60  5401.6  842.61  5427.3  844.40  5432.6  843.76  5565.1  849.91
#Mann=3,-1,0
  3999.4     0.1       0  5012.1    0.07       0  5018.1     0.1       0
Bank Sta=5012.1,5018.1
Exp/Cntr=0.3,0.1

Type RM Length L Ch R = 1,1794,398,398,398
BEGIN DESCRIPTION:
UNT 055 in BCW 4.0
END DESCRIPTION:
XS GIS Cut Line= 3
      1971262.24     13638052.05      1971114.67     13637947.89
      1969834.33     13637392.35
#Sta/Elev= 30
  4190.5  836.09  4250.3  834.38  4389.0  833.91  4470.3  832.60  4622.0  831.82
  4785.0  832.39  4828.6  831.15  4861.3  831.31  4887.9  828.42  4888.4  827.92
  4894.1  828.42  4896.4  829.46  4904.9  830.57  4926.7  831.24  4981.2  831.37
  4995.7  828.83  5003.0  830.68  5035.7  831.25  5057.5  829.94  5071.6  831.40
  5299.1  835.09  5384.5  837.52  5482.6  841.96  5544.6  845.99  5597.0  847.83
  5657.1  851.43  5672.8  851.53  5701.7  853.71  5719.7  853.52  5766.8  855.07
#Mann=3,-1,0
  4190.5     0.1       0  4887.9    0.07       0  4894.1     0.1       0
Bank Sta=4887.9,4894.1
Exp/Cntr=0.3,0.1

Type RM Length L Ch R = 1,1396,293,293,293
BEGIN DESCRIPTION:
Mapping XS bc2494a9
END DESCRIPTION:
XS GIS Cut Line= 3
      1971502.71     13637314.21      1970976.65     13637361.08
      1969899.26     13637246.58
#Sta/Elev= 30
  4152.1  832.95  4250.2  831.56  4370.7  831.39  4420.9  830.17  4641.7  828.79
  4781.3  829.43  4842.8  828.39  4878.9  830.02  4943.4  829.37  4976.5  829.95
  5000.5  828.10  5001.0  827.60  5006.9  828.10  5043.9  829.24  5084.2  828.80
  5094.2  829.59  5194.8  831.23  5275.2  834.18  5325.5  834.30  5395.9  837.50
  5416.0  837.40  5466.3  839.79  5617.1  844.57  5639.5  845.99  5647.3  849.57
  5657.4  852.00  5667.4  851.59  5677.5  848.80  5687.5  847.56  5763.7  849.57
#Mann=3,-1,0
  4152.1     0.1       0  5000.5    0.07       0  5006.9     0.1       0
Bank Sta=5000.5,5006.9
Exp/Cntr=0.3,0.1

Type RM Length L Ch R = 1,1103,31,31,31
BEGIN DESCRIPTION:
Mapping XS c65e6a62
END DESCRIPTION:
XS GIS Cut Line= 6
      1971477.24     13637283.21      1970702.48     13637226.78
      1970754.56     13637111.76      1970765.41     13637072.70
      1970756.73     13637046.66      1970116.54     13637090.06
#Sta/Elev= 30
  4015.2  832.93  4097.7  831.08  4157.8  831.28  4478.7  828.23  4607.0  828.69
  4659.1  827.68  4769.4  830.67  4779.5  830.42  4788.2  827.96  4811.8  826.90
  4817.1  828.93  4842.2  826.57  4847.5  828.64  4865.3  826.82  4871.0  828.58
  4887.2  826.53  4892.9  828.13  4903.4  826.96  4909.1  828.81  4934.8  826.40
  4940.0  828.01  4955.3  826.50  5035.1  826.13  5035.6  825.63  5041.5  826.13
  5058.3  828.34  5088.3  829.94  5329.0  835.74  5501.9  838.87  5628.4  843.07
#Mann=3,-1,0
  4015.2     0.1       0  5035.1    0.07       0  5041.5     0.1       0
Bank Sta=5035.1,5041.5
Exp/Cntr=0.3,0.1

Type RM Length L Ch R = 1,1072,17,17,17
BEGIN DESCRIPTION:
Mapping XS 9dbef116
END DESCRIPTION:
XS GIS Cut Line= 6
      1971488.09     13637263.67      1970741.54     13637211.59
      1970793.62     13637064.02      1970780.60     13637020.62
      1970663.42     13637022.79      1970112.20     13637066.19
#Sta/Elev= 30
  4029.2  832.60  4079.7  832.33  4122.5  831.00  4302.9  829.54  4510.7  828.14
  4623.7  828.75  4683.9  827.63  4724.0  828.34  4764.1  831.13  4838.5  832.15
  4855.1  831.50  4860.3  832.10  4887.4  830.70  4892.7  831.93  4919.8  831.12
  4925.0  831.93  4936.3  831.92  4942.6  831.81  4947.8  829.28  4961.6  827.63
  4979.5  828.16  4985.1  826.38  5021.9  826.28  5022.4  825.78  5028.3  826.28
  5045.1  826.76  5085.1  830.46  5105.1  830.11  5197.3  832.08  5649.6  843.07
#Mann=5,-1,0
  4029.2     0.1       0  4961.6    0.05       0  5021.9    0.04       0
  5028.3    0.05       0  5197.3     0.1       0
Bank Sta=5021.9,5028.3
Exp/Cntr=0.3,0.1

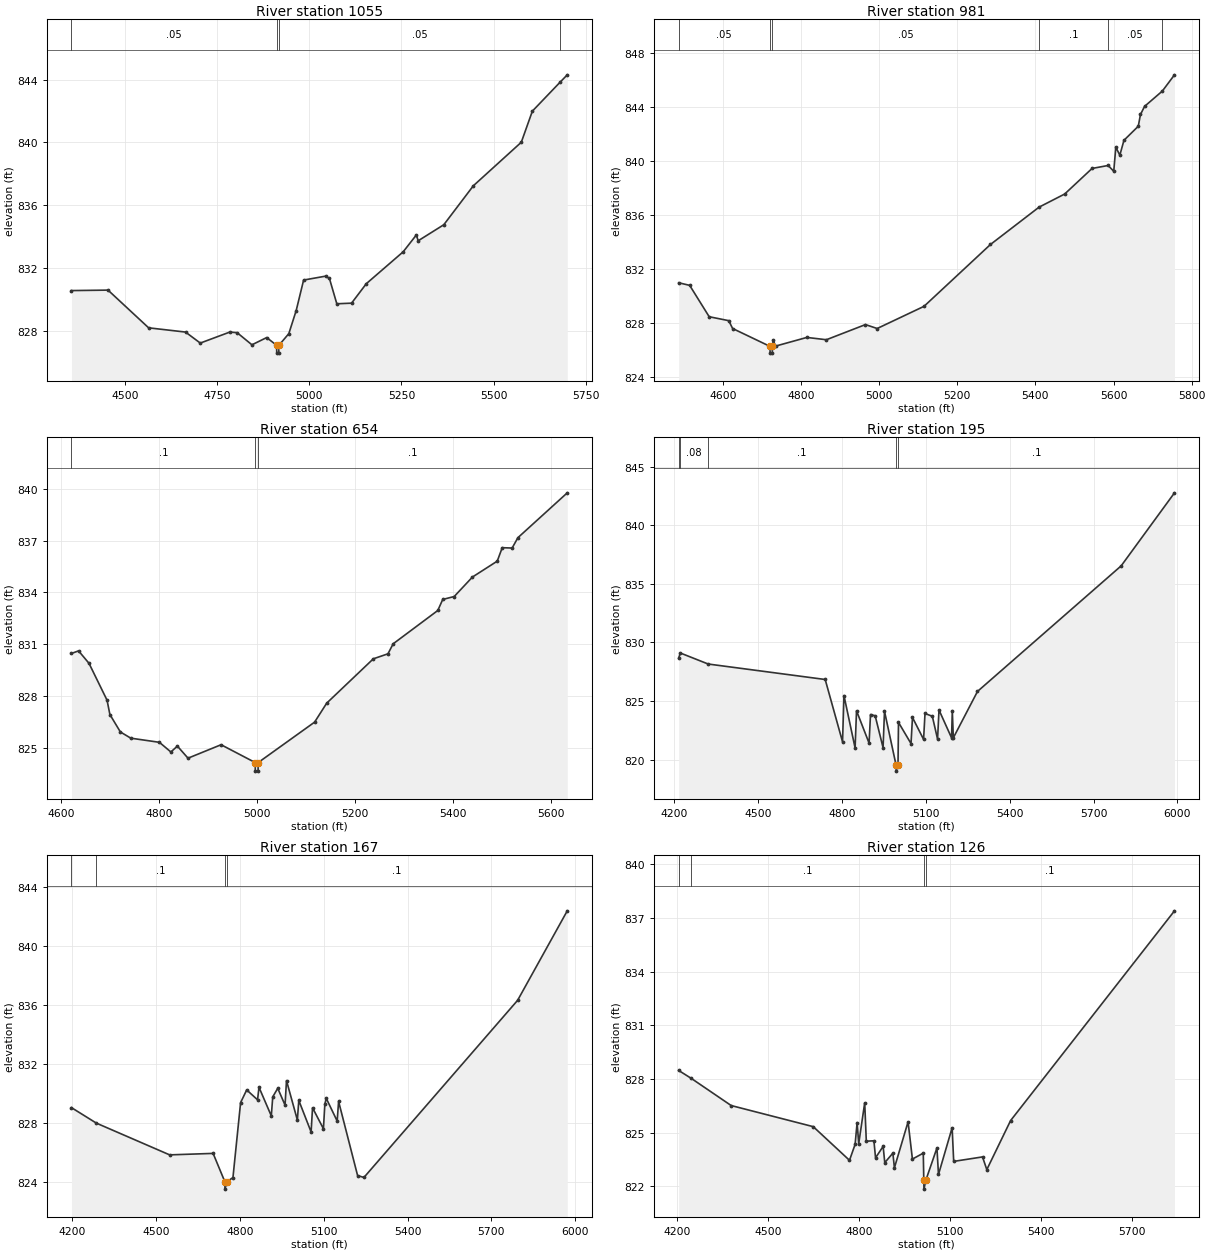
Type RM Length L Ch R = 1,1055,74,74,74
BEGIN DESCRIPTION:
Mapping XS 8becf492
END DESCRIPTION:
XS GIS Cut Line= 2
      1971414.11     13637019.94      1970070.41     13636991.29
#Sta/Elev= 30
  4355.4  830.57  4454.5  830.60  4564.6  828.20  4664.6  827.93  4704.6  827.23
  4784.6  827.93  4804.6  827.89  4844.6  827.12  4884.6  827.58  4911.4  827.09
  4911.9  826.59  4917.3  826.59  4917.8  827.09  4944.6  827.83  4964.6  829.30
  4984.7  831.24  5044.7  831.49  5054.7  831.34  5074.7  829.73  5114.7  829.77
  5154.7  831.01  5254.7  833.04  5290.3  834.11  5295.3  833.74  5364.7  834.76
  5444.8  837.24  5574.8  840.01  5604.8  841.99  5680.3  843.84  5699.4  844.30
#Mann=4,-1,0
  4355.4    0.05       0  4911.4    0.04       0  4917.8    0.05       0
  5680.3     0.1       0
Bank Sta=4911.4,4917.8
Exp/Cntr=0.3,0.1

Type RM Length L Ch R = 1,981,327,327,327
BEGIN DESCRIPTION:
Mapping XS e4636376
END DESCRIPTION:
XS GIS Cut Line= 3
      1971323.05     13636936.60      1970216.24     13636952.23
      1970062.55     13636900.13
#Sta/Elev= 30
  4486.9  831.00  4515.0  830.81  4565.0  828.49  4615.0  828.20  4625.0  827.62
  4720.5  826.30  4721.0  825.80  4726.5  825.80  4727.0  826.30  4728.7  826.77
  4735.0  826.32  4815.0  826.96  4865.0  826.79  4965.0  827.91  4995.0  827.62
  5115.0  829.26  5285.0  833.83  5409.4  836.59  5475.0  837.56  5545.1  839.45
  5586.3  839.67  5600.6  839.24  5605.9  841.02  5616.2  840.43  5626.7  841.53
  5663.4  842.57  5669.0  843.44  5679.6  844.04  5725.0  845.17  5756.1  846.37
#Mann=6,-1,0
  4486.9    0.05       0  4720.5    0.04       0  4727.0    0.05       0
  5409.4     0.1       0  5586.3    0.05       0  5725.0     0.1       0
Bank Sta=4720.5,4727
Exp/Cntr=0.3,0.1

Type RM Length L Ch R = 1,654,459,459,459
BEGIN DESCRIPTION:
Mapping XS 9ede6391
END DESCRIPTION:
XS GIS Cut Line= 3
      1971338.68     13636889.75      1970916.76     13636634.52
      1970403.78     13636553.80
#Sta/Elev= 30
  4621.1  830.46  4635.6  830.61  4656.9  829.89  4693.8  827.75  4699.6  826.92
  4721.0  825.91  4742.3  825.55  4800.7  825.31  4824.1  824.75  4837.4  825.09
  4859.1  824.39  4926.6  825.17  4996.1  824.14  4996.6  823.64  5002.1  823.64
  5002.6  824.14  5117.6  826.48  5142.3  827.58  5237.5  830.15  5267.4  830.44
  5278.0  831.02  5369.1  832.95  5379.2  833.59  5402.6  833.76  5439.9  834.89
  5490.5  835.81  5500.7  836.59  5520.9  836.57  5532.7  837.17  5633.5  839.77
#Mann=3,-1,0
  4621.1     0.1       0  4996.1    0.07       0  5002.6     0.1       0
Bank Sta=4996.1,5002.6
Exp/Cntr=0.3,0.1

Type RM Length L Ch R = 1,195,28,28,28
BEGIN DESCRIPTION:
Mapping XS d2f4c286
END DESCRIPTION:
XS GIS Cut Line= 4
      1971588.64     13636970.48      1971526.13     13636415.77
      1971114.67     13636329.83      1970325.60     13636415.77
#Sta/Elev= 30
  4217.0  828.67  4223.0  829.10  4322.5  828.16  4740.7  826.84  4802.7  821.52
  4807.8  825.47  4847.6  821.00  4852.7  824.17  4897.6  821.41  4902.7  823.85
  4919.4  823.74  4947.6  821.02  4952.7  824.13  4994.2  819.52  4994.7  819.02
  5001.0  819.52  5002.7  823.18  5047.5  821.37  5052.7  823.60  5092.4  821.73
  5097.5  823.94  5123.7  823.70  5142.4  821.75  5147.5  824.24  5192.4  821.86
  5195.1  824.18  5198.7  821.86  5285.1  825.82  5798.8  836.54  5989.3  842.77
#Mann=5,-1,0
  4217.0     0.1       0  4223.0    0.08       0  4322.5     0.1       0
  4994.2    0.07       0  5001.0     0.1       0
Bank Sta=4994.2,5001
Exp/Cntr=0.3,0.1

Type RM Length L Ch R = 1,167,41,41,41
BEGIN DESCRIPTION:
Mapping XS 79a05ae1
END DESCRIPTION:
XS GIS Cut Line= 4
      1971599.05     13636954.88      1971544.36     13636392.33
      1971135.51     13636303.79      1970348.25     13636384.34
#Sta/Elev= 30
  4196.6  829.05  4285.8  828.00  4548.1  825.85  4703.7  825.95  4745.7  824.03
  4746.2  823.53  4752.5  824.03  4774.7  824.31  4802.1  829.39  4823.9  830.25
  4862.8  829.58  4867.9  830.43  4912.0  828.49  4917.2  829.78  4935.1  830.36
  4961.2  829.22  4966.4  830.88  5005.3  828.21  5010.4  829.54  5054.5  827.40
  5059.6  829.04  5098.6  827.62  5103.7  829.29  5109.0  829.67  5147.8  828.14
  5152.9  829.47  5220.9  824.45  5243.6  824.32  5793.8  836.32  5971.5  842.38
#Mann=4,-1,0
  4196.6    0.08       0  4285.8     0.1       0  4745.7    0.07       0
  4752.5     0.1       0
Bank Sta=4745.7,4752.5
Exp/Cntr=0.3,0.1

Type RM Length L Ch R = 1,126,80,80,80
BEGIN DESCRIPTION:
Mapping XS de3cccff
END DESCRIPTION:
XS GIS Cut Line= 5
      1971604.70     13636907.71      1971576.05     13636381.67
      1971414.59     13636321.78      1971026.57     13636241.05
      1970498.98     13636347.61
#Sta/Elev= 30
  4205.0  828.48  4246.3  828.04  4378.0  826.52  4648.4  825.34  4767.8  823.46
  4786.3  824.35  4792.9  825.57  4798.2  824.39  4817.9  826.67  4823.2  824.53
  4848.3  824.55  4853.6  823.60  4878.7  824.24  4884.0  823.33  4910.7  823.86
  4915.8  823.04  4960.8  825.61  4975.1  823.53  5010.9  823.86  5012.6  822.35
  5013.1  821.85  5019.4  822.35  5055.9  824.15  5061.0  822.67  5106.0  825.28
  5111.1  823.40  5206.1  823.65  5220.2  822.94  5298.6  825.68  5838.6  837.40
#Mann=4,-1,0
  4205.0    0.08       0  4246.3     0.1       0  5012.6    0.07       0
  5019.4     0.1       0
Bank Sta=5012.6,5019.4
Exp/Cntr=0.3,0.1

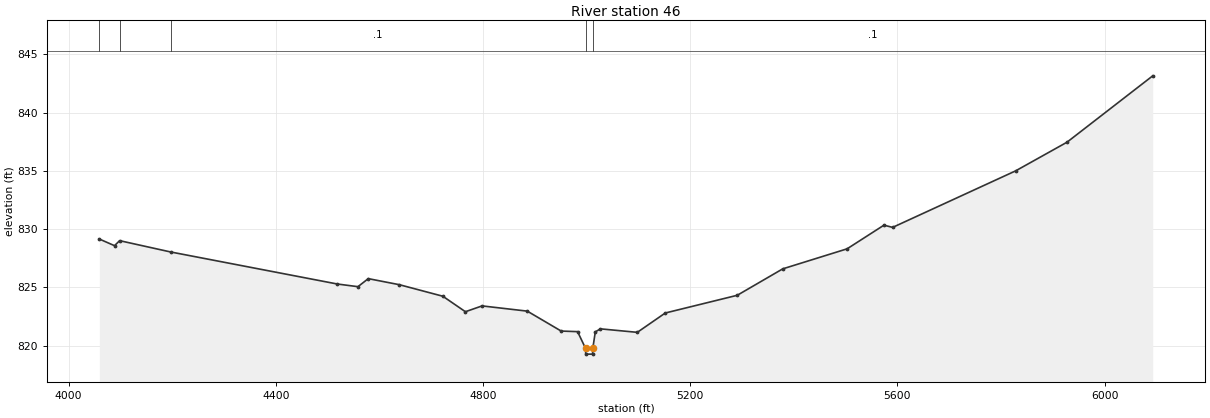
Type RM Length L Ch R = 1,46,0,0,0
BEGIN DESCRIPTION:
UNT 055 in BCW 1.0
END DESCRIPTION:
XS GIS Cut Line= 4
      1971606.86     13637004.32      1971612.07     13636374.10
      1971112.51     13636100.42      1970324.96     13636375.01
#Sta/Elev= 30
  4059.2  829.15  4088.5  828.58  4098.4  829.01  4196.8  828.04  4518.5  825.29
  4558.5  825.06  4578.5  825.75  4638.5  825.23  4722.4  824.24  4766.0  822.91
  4798.2  823.41  4885.5  822.96  4950.9  821.25  4982.6  821.20  4997.9  819.77
  4998.4  819.27  5011.5  819.27  5012.0  819.77  5016.8  821.18  5026.7  821.44
  5097.9  821.14  5151.9  822.80  5290.8  824.32  5378.7  826.59  5503.0  828.31
  5574.1  830.34  5590.9  830.15  5828.3  835.00  5927.5  837.46  6093.1  843.16
#Mann=5,-1,0
  4059.2     0.1       0  4098.4    0.08       0  4196.8     0.1       0
  4997.9    0.07       0  5012.0     0.1       0
Bank Sta=4997.9,5012
Exp/Cntr=0.3,0.1

Chan Stop Cuts=-1