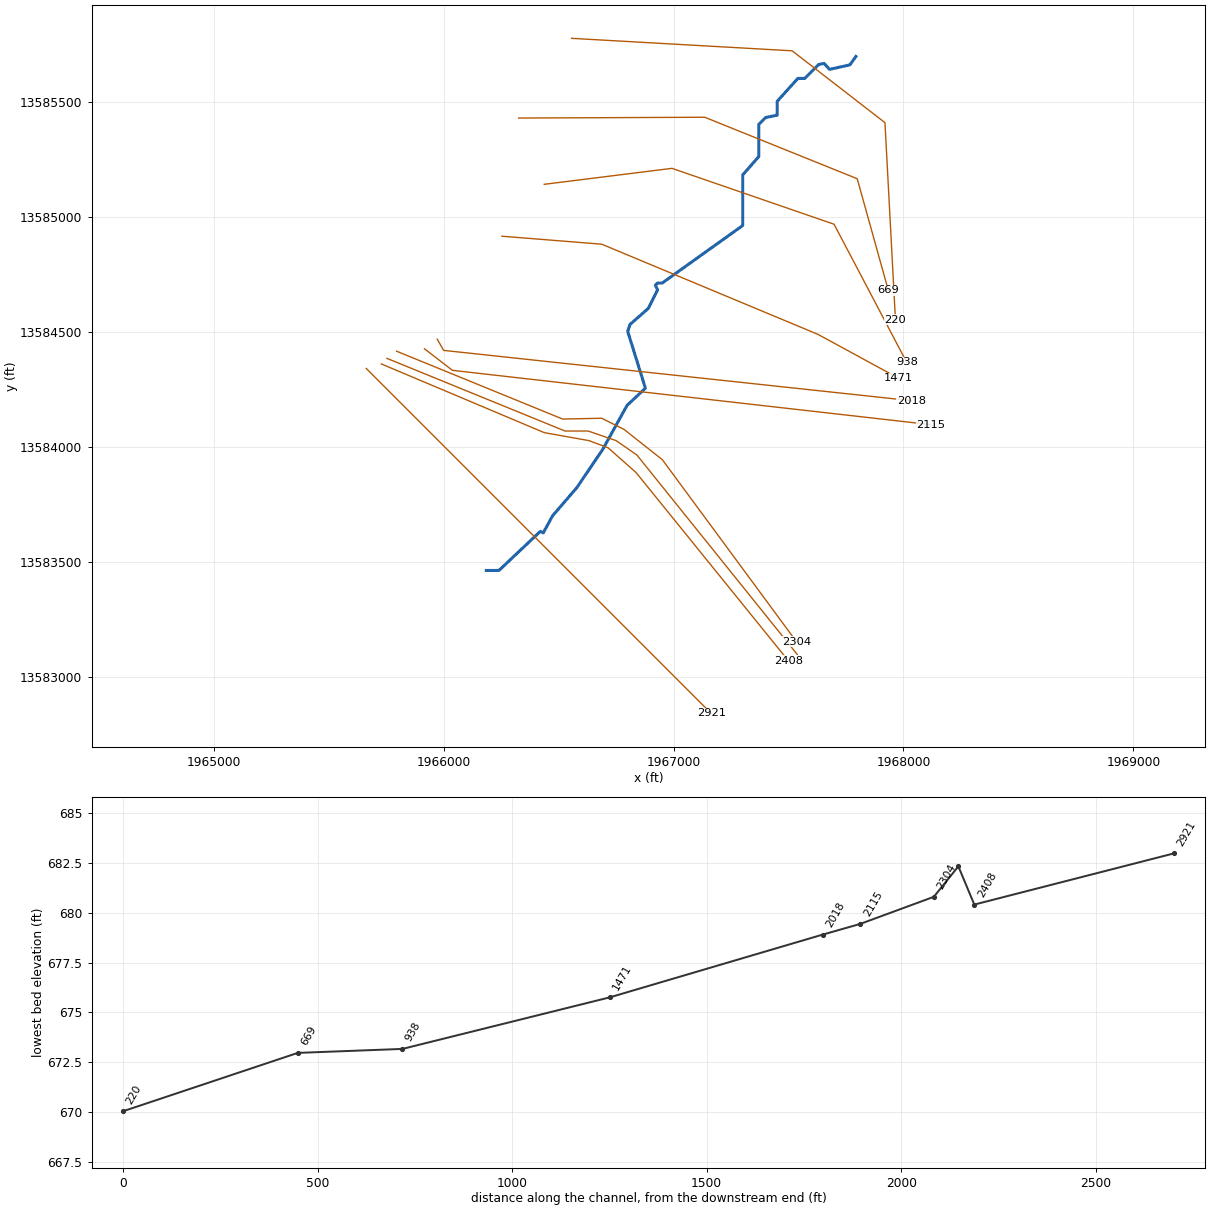
--- UNT 060 in BCW.prj (project) ---

Proj Title=UNT 060 in BCW Base Level Engineering
Current Plan=p01
Default Exp/Contr=0.3,0.1
English Units
Geom File=g01
Flow File=f01
Plan File=p01
Y Axis Title=Elevation
X Axis Title(PF)=Main Channel Distance
X Axis Title(XS)=Station
BEGIN DESCRIPTION:
UNT 060 in BCW
END DESCRIPTION:
DSS Export Rating Curves= 0
DSS Export Rating Curve Sorted= 0
DSS Export Volume Flow Curves= 0
DXF OffsetX= 0
DXF OffsetY= 0
DXF ScaleX= 1
DXF ScaleY= 10

--- UNT 060 in BCW.p01 (plan) ---

Plan Title=Multiple Run
Short Identifier=Multiple
Geom File=g01
Flow File=f01
Subcritical Flow
K Sum by GR= 0
Std Step Tol= 0.01
Critical Tol= 0.01
Num of Std Step Trials= 20
Max Error Tol= 0.3
Flow Tol Ratio= 0.001
Split Flow NTrial= 30
Split Flow Tol= 0.02
Split Flow Ratio= 0.02
Log Output Level= 0
Friction Slope Method= 1
Unsteady Friction Slope Method= 2
Unsteady Bridges Friction Slope Method= 1
Parabolic Critical Depth
Global Vel Dist=  1 , 1 , 1
Global Log Level= 0
CheckData=True
Encroach Param= -1, 0, 0, 0
BEGIN DESCRIPTION:
Multiple Run
END DESCRIPTION:

--- UNT 060 in BCW.f01 (steady flow) ---

Flow Title=Multiple
Number of Profiles=7
Profile Names=10-year,25-year,50-year,1pct_min,100-year,1pct_plu,500-year
River Rch & RM= UNT 060 in BCW,Reach-1,2921
     632     892    1110     682    1361    2716    2051
River Rch & RM= UNT 060 in BCW,Reach-1,2115
     797    1140    1429     885    1765    3521    2697
Boundary for River Rch & Prof#=UNT 060 in BCW,Reach-1,1
Up Type=0
Dn Type=3
Dn Slope=0.005
Boundary for River Rch & Prof#=UNT 060 in BCW,Reach-1,2
Up Type=0
Dn Type=3
Dn Slope=0.005
Boundary for River Rch & Prof#=UNT 060 in BCW,Reach-1,3
Up Type=0
Dn Type=3
Dn Slope=0.005
Boundary for River Rch & Prof#=UNT 060 in BCW,Reach-1,4
Up Type=0
Dn Type=3
Dn Slope=0.005
Boundary for River Rch & Prof#=UNT 060 in BCW,Reach-1,5
Up Type=0
Dn Type=3
Dn Slope=0.005
Boundary for River Rch & Prof#=UNT 060 in BCW,Reach-1,6
Up Type=0
Dn Type=3
Dn Slope=0.005
Boundary for River Rch & Prof#=UNT 060 in BCW,Reach-1,7
Up Type=0
Dn Type=3
Dn Slope=0.005

--- UNT 060 in BCW.g01 (geometry) ---

Geom Title=Existing Conditions
Program Version=5.05

River Reach=UNT 060 in BCW  ,Reach-1
Reach XY= 30
       1966185.8     13583464.54       1966240.8     13583464.54
       1966420.8     13583634.54      1966433.75     13583628.17
      1966474.11     13583702.39      1966579.58     13583824.79
      1966691.56     13583990.15      1966798.33     13584182.86
      1966877.76     13584257.08       1966800.8     13584504.54
       1966810.8     13584534.54       1966890.8     13584604.54
       1966930.8     13584684.54       1966920.8     13584704.54
       1966930.8     13584714.54       1966950.8     13584714.54
       1967300.8     13584964.54       1967300.8     13585184.54
       1967370.8     13585264.54       1967370.8     13585404.54
       1967400.8     13585434.54       1967450.8     13585444.54
       1967450.8     13585504.54       1967540.8     13585604.54
       1967570.8     13585604.54       1967630.8     13585664.54
      1967654.73     13585669.73      1967678.54      13585643.8
      1967767.08     13585663.33      1967793.12     13585699.79

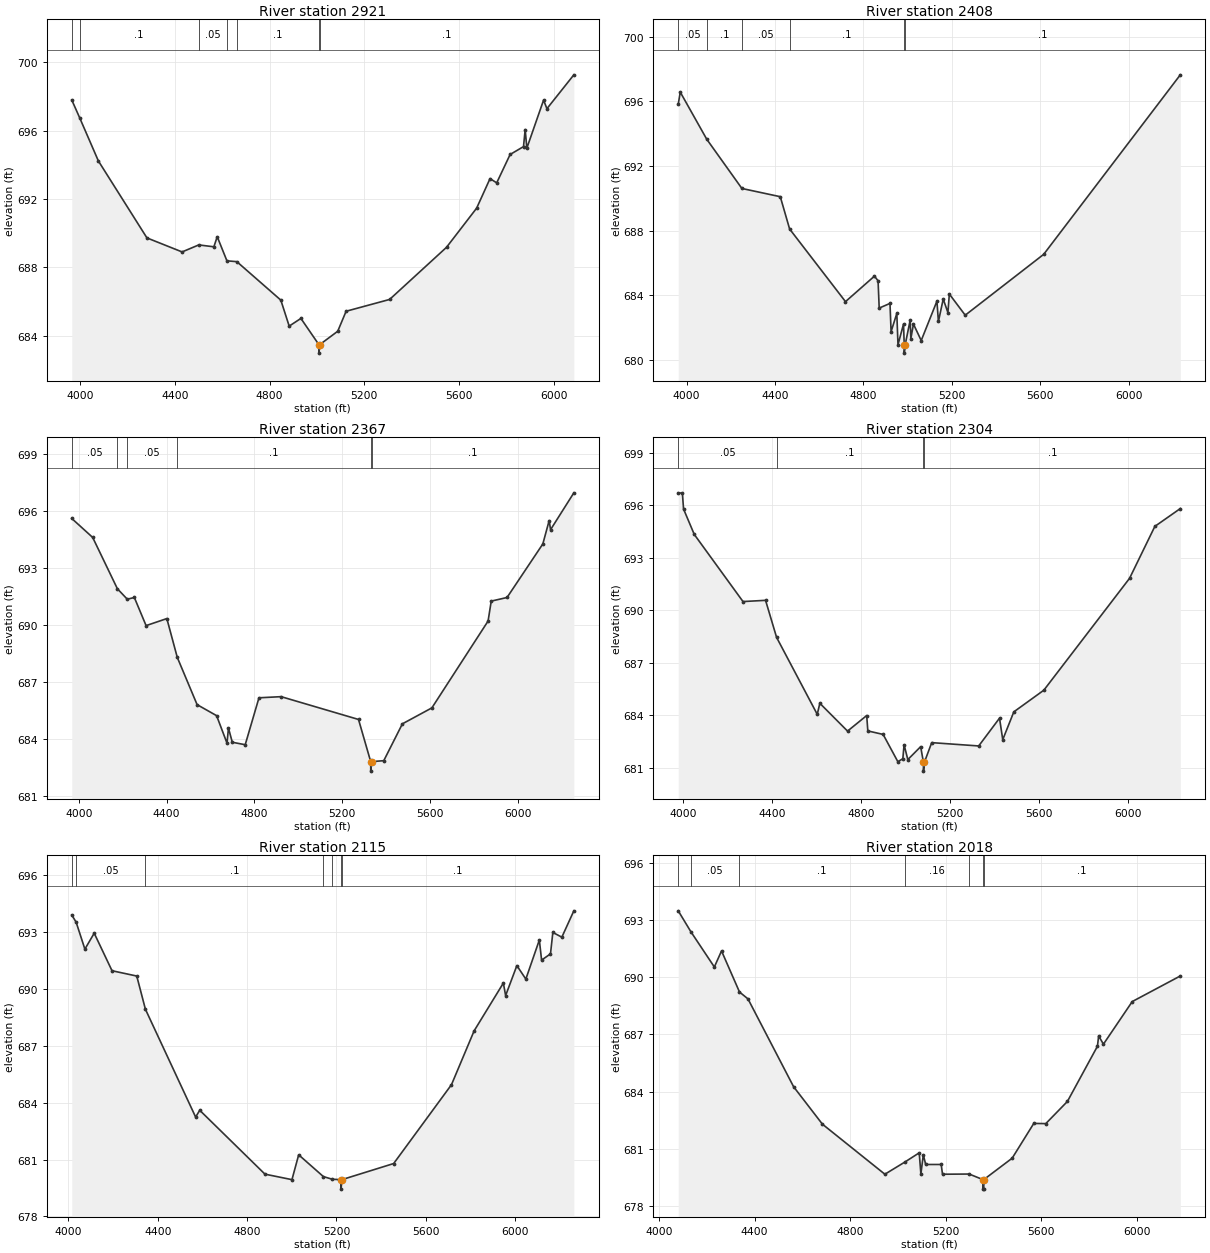
Type RM Length L Ch R = 1 ,2921    ,513,513,513
BEGIN DESCRIPTION:
UNT 060 in BCW 4.0
END DESCRIPTION:
XS GIS Cut Line= 3
       1965663.9     13584343.05      1966263.89     13583743.06
      1967163.88     13582843.06
#Sta/Elev= 30
  3963.8  697.79  3997.4  696.74  4076.3  694.22  4281.4  689.72  4429.9   688.9
  4500.4  689.31  4564.2   689.2  4578.4  689.79  4619.3  688.38  4661.3  688.33
  4847.1  686.08  4882.4  684.56  4931.9  685.01  5007.7  683.48    5008  682.98
  5011.7  683.48  5087.5  684.26  5122.9  685.43  5306.7  686.12  5547.1  689.17
  5674.4  691.46    5731  693.19  5759.2  692.94  5815.8   694.6  5872.4  695.06
  5879.5  696.06  5886.5  694.97  5957.2  697.78  5971.4  697.28  6085.1  699.26
#Mann= 7 ,-1 , 0
  3963.8     .05       0  3997.4      .1       0  4500.4     .05       0
  4619.3     .08       0  4661.3      .1       0  5007.7     .07       0
  5011.7      .1       0
Bank Sta=5007.7,5011.7
XS Rating Curve= 0 ,0
Exp/Cntr=0.3,0.1

Type RM Length L Ch R = 1 ,2408    ,41,41,41
BEGIN DESCRIPTION:
Mapping XS 9b2d0e77
END DESCRIPTION:
XS GIS Cut Line= 6
      1965729.52     13584362.62      1966437.83     13584064.02
      1966632.27      13584029.3      1966715.61     13583998.05
      1966837.14     13583890.41      1967500.19     13583071.14
#Sta/Elev= 30
  3962.2  695.82  3971.3  696.58  4091.2  693.66  4250.2  690.61  4423.9   690.1
  4466.1   688.1  4718.9   683.6  4849.9  685.18  4866.3  684.89  4871.4   683.2
  4920.2  683.49  4925.2  681.74  4951.1  682.87  4956.4  680.93  4981.4  682.21
  4984.7  680.91  4984.9  680.41  4988.7  680.91  5011.6  682.46  5014.6  681.31
  5026.4  682.21  5061.5  681.19  5132.6  683.63  5139.3  682.37  5161.1  683.76
  5182.3  682.92  5188.7  684.07  5260.6  682.76  5615.6  686.53  6233.7  697.65
#Mann= 6 ,-1 , 0
  3962.2     .05       0  4091.2      .1       0  4250.2     .05       0
  4466.1      .1       0  4984.7     .07       0  4988.7      .1       0
Bank Sta=4984.7,4988.7
XS Rating Curve= 0 ,0
Exp/Cntr=0.3,0.1

Type RM Length L Ch R = 1 ,2367    ,63,63,63
BEGIN DESCRIPTION:
Mapping XS a2e2ad03
END DESCRIPTION:
XS GIS Cut Line= 6
      1965753.82     13584386.93      1966528.11     13584070.96
       1966628.8     13584070.96      1966750.33      13584029.3
      1966840.61      13583966.8      1967538.04     13583099.35
#Sta/Elev= 30
  3967.5  695.63  4062.9  694.63  4175.4  691.93  4220.5  691.38  4252.7  691.47
  4306.2  689.99  4400.8  690.36  4448.3  688.32  4538.7  685.83  4627.6  685.25
  4675.1   683.8  4681.6   684.6  4699.1  683.85    4758  683.72  4820.7  686.19
  4921.6  686.25  5274.4  685.05  5329.9  682.83  5330.2  682.33  5333.9  682.83
  5389.5  682.88  5474.4  684.82  5608.8  685.66  5864.9  690.23  5879.3  691.28
  5951.3  691.47  6114.5  694.29  6143.3  695.52  6149.7  695.04  6255.8  696.98
#Mann= 6 ,-1 , 0
  3967.5     .05       0  4175.4      .1       0  4220.5     .05       0
  4448.3      .1       0  5329.9     .07       0  5333.9      .1       0
Bank Sta=5329.9,5333.9
XS Rating Curve= 0 ,0
Exp/Cntr=0.3,0.1

Type RM Length L Ch R = 1 ,2304    ,189,189,189
BEGIN DESCRIPTION:
Mapping XS 71072fbf
END DESCRIPTION:
XS GIS Cut Line= 6
      1965795.51     13584418.17      1966517.69     13584123.05
      1966687.83     13584126.52      1966785.05     13584077.91
      1966951.72     13583945.96      1967535.03     13583154.32
#Sta/Elev= 30
  3979.4  696.72    3998   696.7  4003.4  695.79  4051.5  694.34  4270.6   690.5
  4372.1  690.57  4421.7  688.45  4604.5  684.05  4616.2  684.68  4740.8  683.09
  4826.9  683.98    4832   683.1  4900.8   682.9    4967  681.34  4989.4  681.51
    4995  682.31  5011.8  681.46  5069.6   682.2  5082.1   681.3  5082.3   680.8
  5086.1   681.3  5119.3  682.43  5330.6  682.24  5424.2  683.83  5438.7   682.6
  5488.5  684.19  5623.5  685.43    6009  691.83  6122.7   694.8  6237.2  695.82
#Mann= 4 ,-1 , 0
  3979.4     .05       0  4421.7      .1       0  5082.1     .07       0
  5086.1      .1       0
Bank Sta=5082.1,5086.1
XS Rating Curve= 0 ,0
Exp/Cntr=0.3,0.1

Type RM Length L Ch R = 1 ,2115    ,97,97,97
BEGIN DESCRIPTION:
Mapping XS 0a46808d
END DESCRIPTION:
XS GIS Cut Line= 3
      1965917.01     13584428.59      1966038.52     13584334.85
       1968118.4     13584098.74
#Sta/Elev= 30
  4015.5   693.9  4035.1  693.52  4074.2   692.1  4115.9  692.94  4195.6  690.96
  4306.3  690.68    4345  688.93  4569.8  683.24  4588.1   683.6    4880  680.23
  5000.8  679.94  5030.9  681.25  5141.6   680.1  5181.8  679.96  5220.2  679.94
  5220.4  679.44  5224.2  679.94  5455.9  680.79  5714.7  684.95    5816  687.79
  5946.8  690.31  5956.9  689.65  6007.2  691.23  6047.4  690.52  6107.8  692.58
  6117.9  691.52  6157.7  691.85  6168.2  692.98  6208.5  692.73  6262.2  694.12
#Mann= 7 ,-1 , 0
  4015.5      .1       0  4035.1     .05       0    4345      .1       0
  5141.6     .16       0  5181.8      .1       0  5220.2     .07       0
  5224.2      .1       0
Bank Sta=5220.2,5224.2
XS Rating Curve= 0 ,0
Exp/Cntr=0.3,0.1

Type RM Length L Ch R = 1 ,2018    ,547,547,547
BEGIN DESCRIPTION:
Mapping XS 731d4c7a
END DESCRIPTION:
XS GIS Cut Line= 3
      1965972.57     13584470.25      1966000.33     13584421.66
      1968035.04     13584202.91
#Sta/Elev= 30
  4080.2  693.47  4132.9  692.38  4231.4  690.53  4261.5  691.37  4336.7  689.22
  4372.2  688.86  4563.3  684.26    4684   682.3  4945.5  679.68  5028.2  680.31
  5089.3   680.8  5096.3  679.69  5106.4   680.7  5116.4  680.19  5181.3  680.19
  5186.9  679.68  5298.5  679.69  5355.8   679.4  5356.1   678.9  5359.6   678.9
  5359.8   679.4  5478.5  680.52    5569  682.34  5619.3  682.33  5709.8  683.49
  5835.6  686.38  5840.6  686.92  5860.7  686.49  5981.4  688.72  6182.6  690.06
#Mann= 7 ,-1 , 0
  4080.2      .1       0  4132.9     .05       0  4336.7      .1       0
  5028.2     .16       0  5298.5      .1       0  5355.8     .07       0
  5359.8      .1       0
Bank Sta=5355.8,5359.8
XS Rating Curve= 0 ,0
Exp/Cntr=0.3,0.1

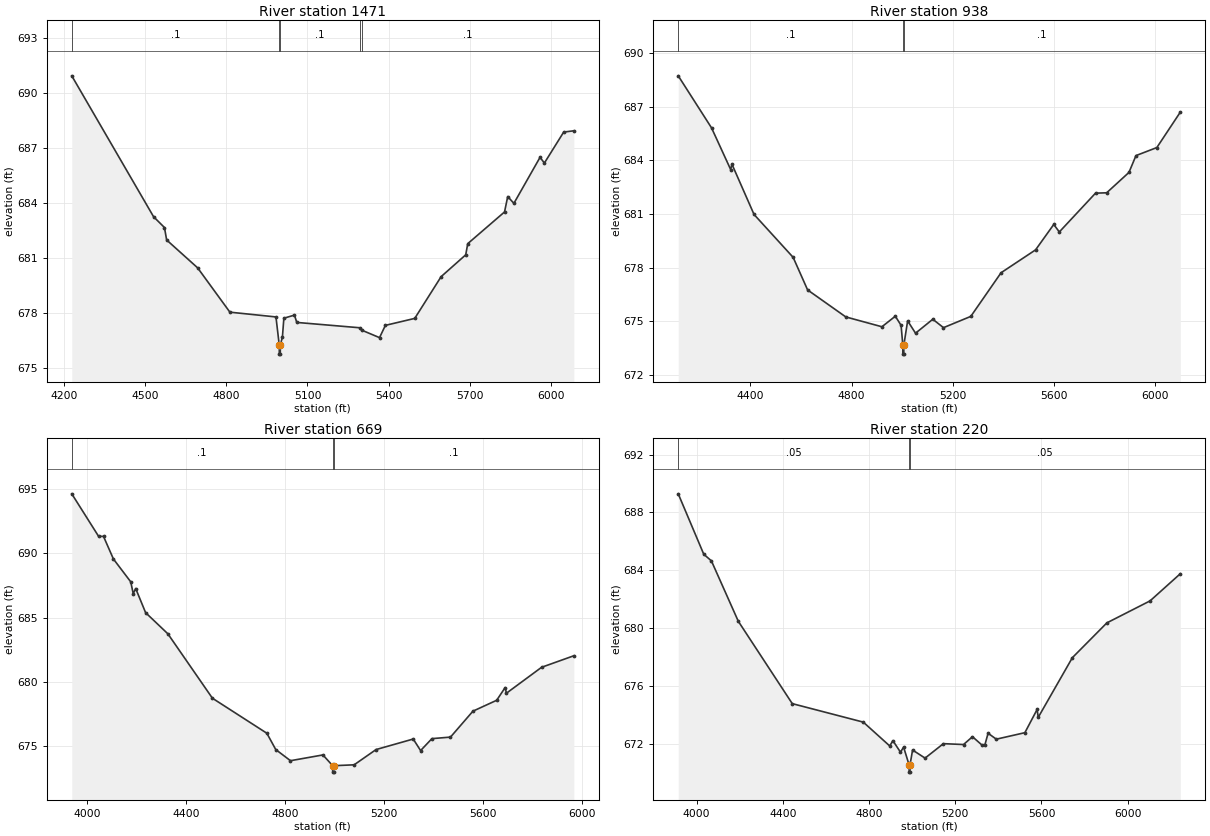
Type RM Length L Ch R = 1 ,1471    ,533,533,533
BEGIN DESCRIPTION:
Mapping XS 19c6db25
END DESCRIPTION:
XS GIS Cut Line= 4
      1966253.81     13584918.19      1966687.83     13584883.46
       1967628.8      13584491.1      1967979.48     13584300.14
#Sta/Elev= 30
  4229.6  690.94  4531.7  683.25  4571.9  682.66    4580  681.98  4694.4  680.46
  4813.6  678.04  4983.7  677.78  4995.8  676.25  4996.1  675.75  4999.6  675.75
  4999.8  676.25  5007.5  676.68  5012.9  677.71    5052  677.88  5060.6  677.48
  5292.3  677.19  5300.2  677.06  5366.2  676.65  5387.8  677.32  5496.2   677.7
  5593.7  679.98  5684.5  681.17    5692  681.78  5827.8  683.51  5839.6  684.35
  5862.4  683.98  5958.9  686.49    5975  686.18  6046.3  687.87  6083.8  687.94
#Mann= 5 ,-1 , 0
  4229.6      .1       0  4995.8     .07       0  4999.8      .1       0
  5292.3     .16       0  5300.2      .1       0
Bank Sta=4995.8,4999.8
XS Rating Curve= 0 ,0
Exp/Cntr=0.3,0.1

Type RM Length L Ch R = 1 ,938     ,269,269,269
BEGIN DESCRIPTION:
Mapping XS 1e3c0a6b
END DESCRIPTION:
XS GIS Cut Line= 4
      1966437.79     13585143.88      1966993.39     13585213.33
      1967698.25     13584970.27      1968014.11     13584369.79
#Sta/Elev= 30
  4114.9  688.72  4246.5  685.81  4322.1  683.48  4327.1  683.78  4414.4  680.97
    4569  678.57  4626.1  676.75    4777  675.24  4919.8  674.69  4972.7  675.28
  4995.5  674.77  5002.4  673.66  5002.7  673.16  5006.2  673.16  5006.4  673.66
  5021.4  675.02  5052.6  674.33  5120.8  675.11  5163.1  674.64    5271  675.27
  5390.6  677.71    5527  678.99  5598.8  680.41  5620.8  679.99  5763.8  682.16
  5807.9  682.18    5896  683.32  5923.7  684.26  6006.2  684.71  6098.9  686.69
#Mann= 3 ,-1 , 0
  4114.9      .1       0  5002.4     .07       0  5006.4      .1       0
Bank Sta=5002.4,5006.4
XS Rating Curve= 0 ,0
Exp/Cntr=0.3,0.1

Type RM Length L Ch R = 1 ,669     ,449,449,449
BEGIN DESCRIPTION:
Mapping XS 36584e8a
END DESCRIPTION:
XS GIS Cut Line= 4
      1966326.69     13585432.08      1967135.75     13585435.55
      1967798.94     13585168.19      1967934.35     13584682.12
#Sta/Elev= 30
  3937.5  694.65  4045.8  691.34  4065.8  691.33  4105.8  689.57  4175.8  687.79
  4185.8  686.87  4195.8  687.27  4235.8  685.39  4325.8  683.74  4505.8  678.72
  4725.8  675.99  4761.7  674.72  4821.2  673.85  4952.3   674.3  4991.7  673.46
  4991.9  672.96  4995.5  672.96  4995.8  673.46  5078.5  673.53  5167.1  674.72
  5317.2  675.54    5347  674.64  5392.7  675.57  5467.8  675.69  5558.4  677.71
  5654.4  678.56  5688.6  679.55  5693.8  679.11  5835.8  681.13  5966.2  682.03
#Mann= 3 ,-1 , 0
  3937.5      .1       0  4991.7     .07       0  4995.8      .1       0
Bank Sta=4991.7,4995.8
XS Rating Curve= 0 ,0
Exp/Cntr=0.3,0.1

Type RM Length L Ch R = 1 ,220     ,0,0,0
BEGIN DESCRIPTION:
UNT 060 in BCW 1.0
END DESCRIPTION:
XS GIS Cut Line= 4
      1966556.77     13585778.72      1967515.95     13585724.47
       1967919.6     13585411.97      1967965.17     13584554.77
#Sta/Elev= 30
  3914.7  689.29  4033.1  685.11  4068.6  684.65  4193.4  680.47  4443.8  674.77
  4773.4  673.49  4896.1  671.84  4910.6  672.21  4945.9  671.41  4960.4  671.76
  4985.9  670.53  4986.2  670.03  4989.9  670.03  4990.2  670.53    5002  671.56
    5060     671  5145.1     672  5238.4  671.94    5280  672.48  5323.5  671.91
    5338  671.94  5352.4  672.72  5390.6  672.31  5523.1  672.76    5580  674.37
    5585  673.82  5743.4  677.95  5903.6  680.36  6103.9  681.88  6244.3  683.76
#Mann= 3 ,-1 , 0
  3914.7     .05       0  4985.9     .03       0  4990.2     .05       0
Bank Sta=4985.9,4990.2
XS Rating Curve= 0 ,0
Exp/Cntr=0.3,0.1
LCMann Table=0

Chan Stop Cuts=-1
Use User Specified Reach Order=0
Composite Channel Slope=5