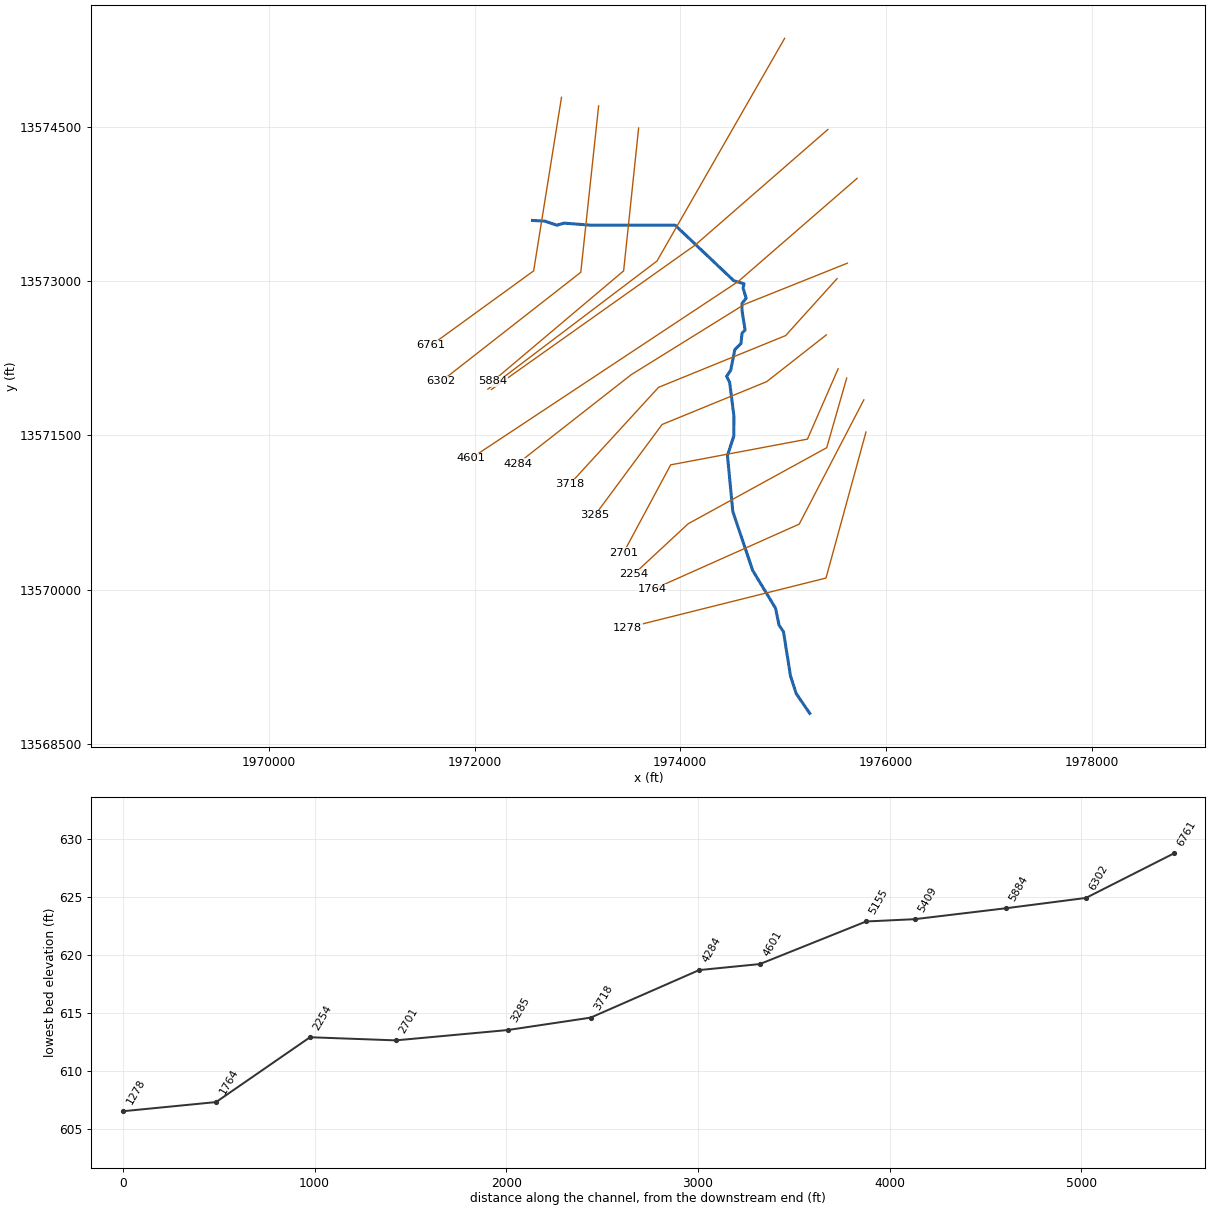
--- UNT 061 in BCW.prj (project) ---

Proj Title=UNT 061 in BCW Base Level Engineering
Current Plan=p01
Default Exp/Contr=0.3,0.1
English Units
Geom File=g01
Flow File=f01
Plan File=p01
BEGIN DESCRIPTION:
UNT 061 in BCW
END DESCRIPTION:

--- UNT 061 in BCW.p01 (plan) ---

Plan Title=Multiple Run
Short Identifier=Multiple
Geom File=g01
Flow File=f01
Subcritical Flow
K Sum by GR= 0
Std Step Tol= 0.01
Critical Tol= 0.01
Num of Std Step Trials= 20
Max Error Tol= 0.3
Flow Tol Ratio= 0.001
Split Flow NTrial= 30
Split Flow Tol= 0.02
Split Flow Ratio= 0.02
Log Output Level= 0
Friction Slope Method= 1
Unsteady Friction Slope Method= 2
Unsteady Bridges Friction Slope Method= 1
Parabolic Critical Depth
Global Vel Dist=  1 , 1 , 1
Global Log Level= 0
CheckData=True
Encroach Param= -1, 0, 0, 0
BEGIN DESCRIPTION:
Multiple Run
END DESCRIPTION:

--- UNT 061 in BCW.f01 (steady flow) ---

Flow Title=Multiple
Number of Profiles=7
Profile Names=10-year,25-year,50-year,1pct_min,100-year,1pct_plu,500-year
River Rch & RM= UNT 061 in BCW,Reach-1,6761
     630     893    1113     687    1370    2734    2080
River Rch & RM= UNT 061 in BCW,Reach-1,5409
     863    1247    1576     984    1963    3916    3056
River Rch & RM= UNT 061 in BCW,Reach-1,5155
    1229    1811    2318    1465    2923    5831    4666
River Rch & RM= UNT 061 in BCW,Reach-1,4601
    1429    2117    2719    1723    3437    6858    5520
Boundary for River Rch & Prof#=UNT 061 in BCW,Reach-1,1
Up Type=0
Dn Type=3
Dn Slope=0.005
Boundary for River Rch & Prof#=UNT 061 in BCW,Reach-1,2
Up Type=0
Dn Type=3
Dn Slope=0.005
Boundary for River Rch & Prof#=UNT 061 in BCW,Reach-1,3
Up Type=0
Dn Type=3
Dn Slope=0.005
Boundary for River Rch & Prof#=UNT 061 in BCW,Reach-1,4
Up Type=0
Dn Type=3
Dn Slope=0.005
Boundary for River Rch & Prof#=UNT 061 in BCW,Reach-1,5
Up Type=0
Dn Type=3
Dn Slope=0.005
Boundary for River Rch & Prof#=UNT 061 in BCW,Reach-1,6
Up Type=0
Dn Type=3
Dn Slope=0.005
Boundary for River Rch & Prof#=UNT 061 in BCW,Reach-1,7
Up Type=0
Dn Type=3
Dn Slope=0.005

--- UNT 061 in BCW.g01 (geometry) ---

Geom Title=Existing Conditions

River Reach=UNT 061 in BCW,Reach-1
Reach XY= 30
      1972564.70     13573590.63      1972680.80     13573584.54
      1972800.80     13573544.54      1972870.80     13573564.54
      1973130.80     13573544.54      1973950.80     13573544.54
      1974520.80     13573004.54      1974620.80     13572974.54
      1974610.80     13572934.54      1974640.80     13572834.54
      1974600.80     13572784.54      1974600.80     13572714.54
      1974630.80     13572524.54      1974600.80     13572494.54
      1974590.80     13572394.54      1974530.80     13572334.54
      1974490.80     13572134.54      1974450.80     13572074.54
      1974480.80     13572014.54      1974522.18     13571687.13
      1974520.80     13571494.54      1974459.25     13571305.18
      1974511.33     13570760.48      1974704.48     13570187.56
      1974926.91     13569819.72      1974960.80     13569655.88
      1975003.95     13569590.77      1975072.31     13569161.09
      1975127.65     13568990.73      1975258.95     13568797.59

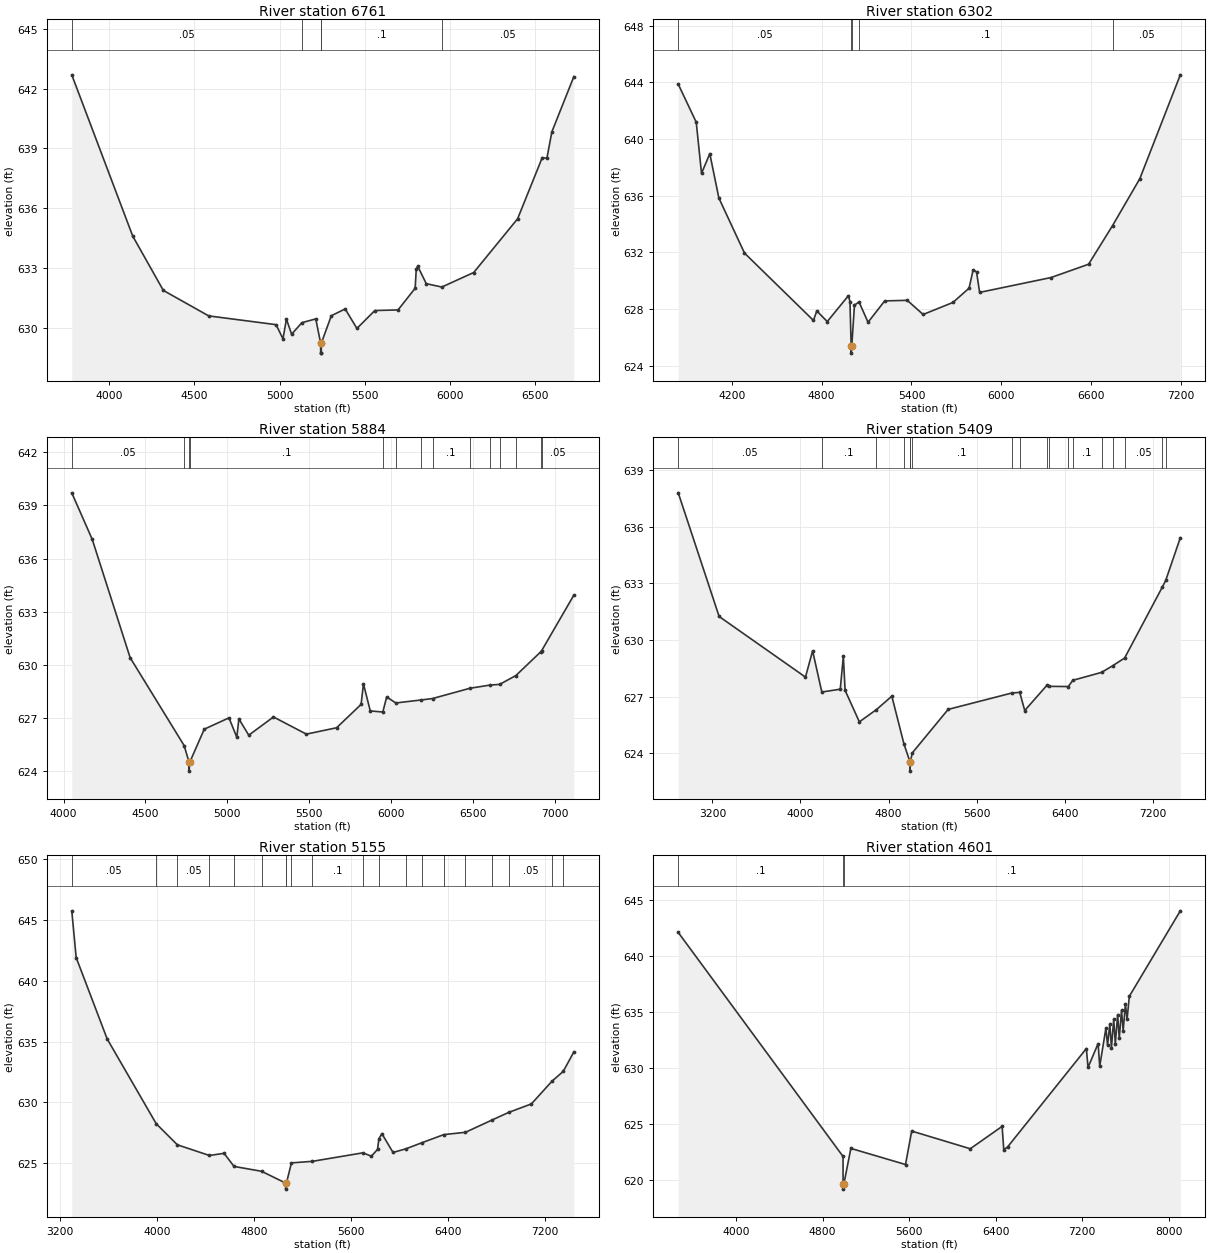
Type RM Length L Ch R = 1,6761,459,459,459
BEGIN DESCRIPTION:
UNT 061 in BCW 12.0
END DESCRIPTION:
XS GIS Cut Line= 3
      1972845.45     13574787.84      1972574.62     13573100.35
      1971575.04     13572375.03
#Sta/Elev= 30
  3781.3  642.70  4138.7  634.60  4318.2  631.87  4584.3  630.59  4979.3  630.15
  5019.8  629.44  5040.0  630.43  5070.4  629.67  5130.7  630.25  5212.2  630.44
  5240.6  629.22  5240.9  628.72  5244.4  628.72  5244.6  629.22  5303.4  630.60
  5384.4  630.94  5453.3  629.96  5558.5  630.86  5694.5  630.89  5795.0  631.98
  5801.2  632.93  5809.7  633.09  5860.0  632.21  5951.2  632.04  6138.3  632.77
  6395.7  635.47  6540.1  638.54  6567.3  638.51  6596.7  639.84  6725.4  642.61
#Mann=5,-1,0
  3781.3    0.05       0  5130.7     0.1       0  5240.6   0.035       0
  5244.6     0.1       0  5951.2    0.05       0
Bank Sta=5240.6,5244.6
Exp/Cntr=0.3,0.1

Type RM Length L Ch R = 1,6302,418,418,418
BEGIN DESCRIPTION:
UNT 061 in BCW 11.0
END DESCRIPTION:
XS GIS Cut Line= 3
      1973206.57     13574704.54      1973032.95     13573086.46
      1971675.04     13572025.03
#Sta/Elev= 30
  3843.4  643.88  3963.6  641.19  3998.8  637.58  4054.1  638.97  4114.5  635.84
  4285.5  631.95  4745.8  627.19  4768.2  627.86  4838.0  627.11  4979.4  628.94
  4989.5  628.52  4997.5  625.38  4997.8  624.88  5001.5  625.38  5019.7  628.28
  5050.3  628.49  5110.2  627.06  5221.5  628.57  5371.7  628.61  5477.9  627.61
  5676.9  628.46  5784.5  629.47  5811.6  630.76  5834.2  630.62  5855.0  629.17
  6331.6  630.22  6582.1  631.16  6742.2  633.89  6923.9  637.20  7194.3  644.54
#Mann=5,-1,0
  3843.4    0.05       0  4997.5   0.035       0  5001.5    0.05       0
  5050.3     0.1       0  6742.2    0.05       0
Bank Sta=4997.5,5001.5
Exp/Cntr=0.3,0.1

Type RM Length L Ch R = 1,5884,475,475,475
BEGIN DESCRIPTION:
UNT 061 in BCW 10.0
END DESCRIPTION:
XS GIS Cut Line= 3
      1973595.45     13574489.24      1973449.62     13573100.35
      1972174.98     13572024.98
#Sta/Elev= 30
  4050.1  639.71  4175.0  637.08  4406.3  630.40  4736.1  625.43  4766.0  624.49
  4766.2  623.99  4770.0  624.49  4858.8  626.36  5009.6  627.00  5057.4  625.90
  5069.9  626.94  5130.3  626.02  5281.1  627.05  5481.8  626.08  5666.4  626.44
  5815.9  627.76  5830.2  628.92  5871.9  627.39  5948.5  627.33  5972.0  628.18
  6027.9  627.84  6182.6  628.01  6251.8  628.09  6479.8  628.67  6602.0  628.85
  6661.5  628.89  6760.8  629.39  6913.5  630.74  6917.6  630.79  7114.3  633.93
#Mann=14,-1,0
  4050.1    0.05       0  4736.1     0.1       0  4766.0    0.07       0
  4770.0     0.1       0  5948.5    0.08       0  6027.9     0.1       0
  6182.6    0.08       0  6251.8     0.1       0  6479.8    0.08       0
  6602.0     0.1       0  6661.5    0.08       0  6760.8    0.05       0
  6913.5    0.08       0  6917.6    0.05       0
Bank Sta=4766,4770
Exp/Cntr=0.3,0.1

Type RM Length L Ch R = 1,5409,254,254,254
BEGIN DESCRIPTION:
Mapping XS 63ac044b
END DESCRIPTION:
XS GIS Cut Line= 3
      1975015.13     13575361.46      1973773.81     13573195.66
      1972129.40     13571950.42
#Sta/Elev= 30
  2889.9  637.79  3261.3  631.24  4045.3  628.03  4110.1  629.42  4193.7  627.24
  4361.2  627.39  4389.2  629.14  4405.0  627.33  4534.5  625.66  4689.8  626.31
  4829.4  627.02  4939.5  624.49  4993.8  623.55  4994.2  623.05  4998.7  623.55
  5014.3  624.01  5340.9  626.32  5921.0  627.19  5990.8  627.22  6036.2  626.26
  6236.8  627.59  6253.2  627.54  6432.1  627.53  6472.8  627.86  6733.7  628.28
  6834.4  628.63  6943.2  629.04  7283.9  632.78  7316.4  633.15  7448.9  635.41
#Mann=18,-1,0
  2889.9    0.05       0  4193.7     0.1       0  4689.8    0.05       0
  4939.5    0.08       0  4993.8    0.07       0  4998.7    0.08       0
  5014.3     0.1       0  5921.0    0.08       0  5990.8     0.1       0
  6236.8    0.08       0  6253.2     0.1       0  6432.1    0.05       0
  6472.8     0.1       0  6733.7    0.08       0  6834.4     0.1       0
  6943.2    0.05       0  7283.9    0.08       0  7316.4    0.05       0
Bank Sta=4993.8,4998.7
Exp/Cntr=0.3,0.1

Type RM Length L Ch R = 1,5155,554,554,554
BEGIN DESCRIPTION:
UNT 061 in BCW 9.0
END DESCRIPTION:
XS GIS Cut Line= 3
      1975435.76     13574475.37      1974144.07     13573350.35
      1972164.91     13571947.58
#Sta/Elev= 30
  3299.7  645.77  3336.1  641.92  3591.5  635.22  3996.2  628.23  4170.2  626.50
  4434.9  625.62  4555.1  625.80  4637.3  624.72  4864.1  624.32  5062.5  623.35
  5063.0  622.85  5069.2  623.35  5110.5  625.01  5283.6  625.14  5700.2  625.84
  5769.7  625.56  5820.2  626.12  5831.4  626.99  5855.9  627.42  5948.1  625.87
  6054.0  626.17  6188.2  626.68  6366.6  627.34  6545.0  627.53  6761.6  628.53
  6901.8  629.17  7088.8  629.87  7258.6  631.74  7351.3  632.55  7438.5  634.15
#Mann=20,-1,0
  3299.7    0.05       0  3996.2     0.1       0  4170.2    0.05       0
  4434.9    0.08       0  4637.3     0.1       0  4864.1     0.1       0
  5062.5    0.07       0  5069.2     0.1       0  5110.5    0.05       0
  5283.6     0.1       0  5700.2     0.1       0  5831.4    0.08       0
  6054.0     0.1       0  6188.2    0.05       0  6366.6    0.05       0
  6545.0    0.05       0  6761.6    0.08       0  6901.8    0.05       0
  7258.6    0.08       0  7351.3    0.05       0
Bank Sta=5062.5,5069.2
Exp/Cntr=0.3,0.1

Type RM Length L Ch R = 1,4601,317,317,317
BEGIN DESCRIPTION:
UNT 061 in BCW 8.0
END DESCRIPTION:
XS GIS Cut Line= 3
      1975719.99     13574000.34      1974563.74     13572996.88
      1971967.93     13571279.06
#Sta/Elev= 30
  3464.8  642.13  4989.2  622.10  4989.3  619.68  4989.8  619.18  4997.5  619.68
  5061.4  622.82  5566.9  621.38  5624.1  624.37  6165.7  622.79  6460.5  624.79
  6475.6  622.70  6511.7  622.96  7239.8  631.75  7254.9  630.06  7348.2  632.19
  7363.2  630.17  7420.4  633.57  7435.4  632.04  7456.5  633.93  7471.5  631.84
  7492.6  634.36  7507.6  632.18  7528.7  634.78  7543.7  632.67  7564.8  635.17
  7579.9  633.34  7600.9  635.73  7616.0  634.36  7637.0  636.42  8108.5  644.06
#Mann=3,-1,0
  3464.8     0.1       0  4989.3    0.07       0  4997.5     0.1       0
Bank Sta=4989.3,4997.5
Exp/Cntr=0.3,0.1

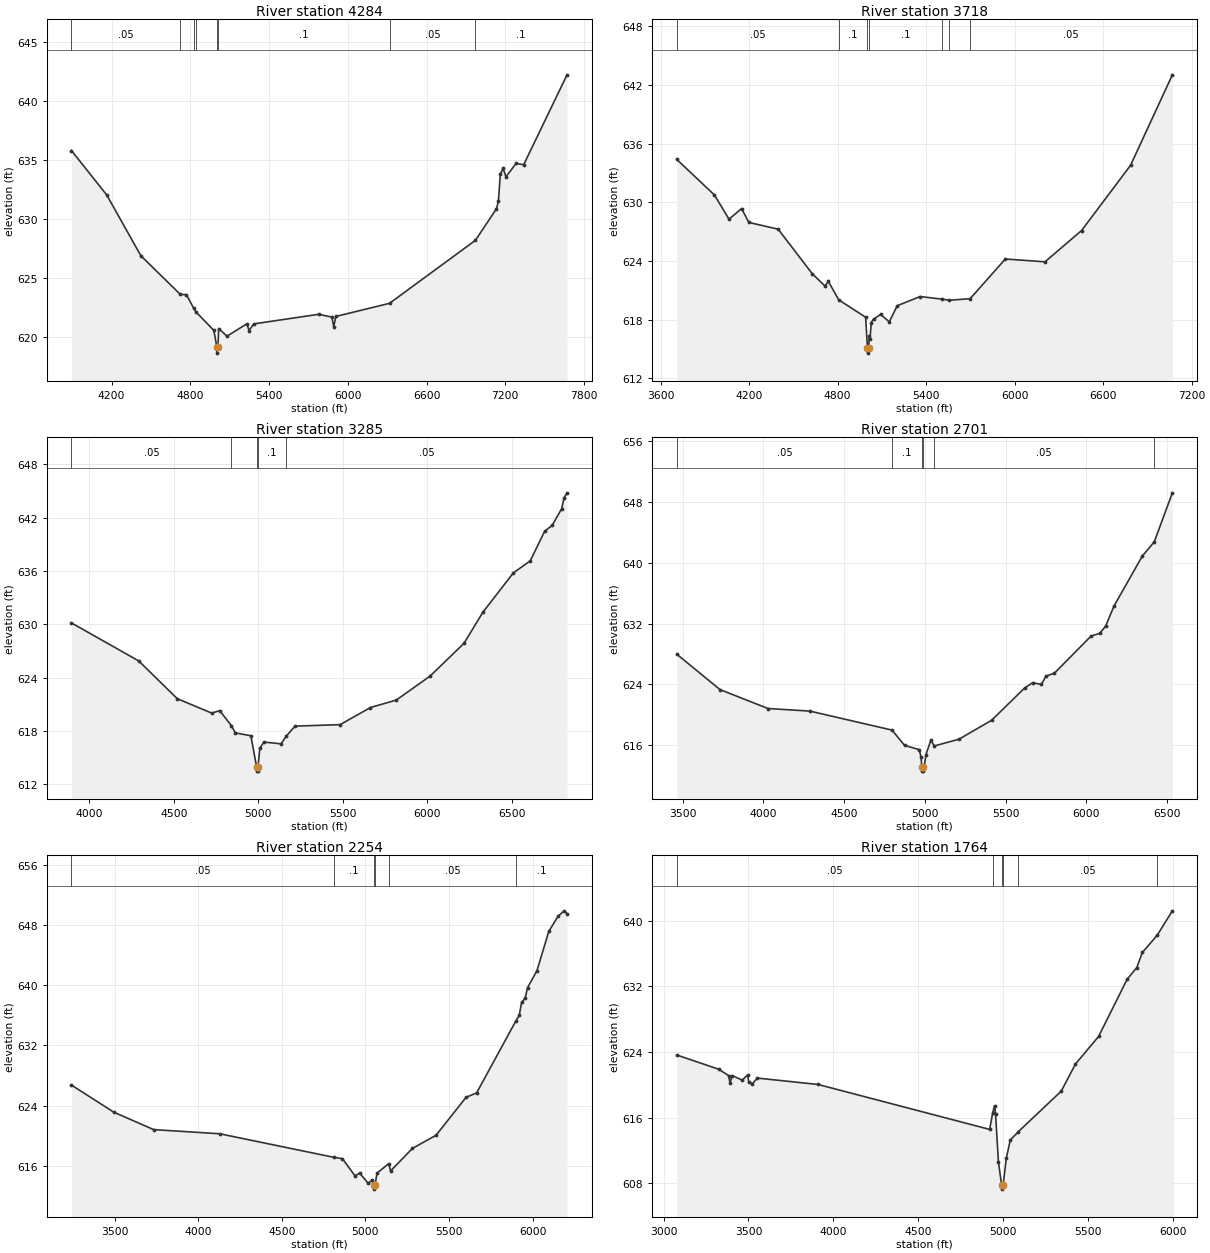
Type RM Length L Ch R = 1,4284,566,566,566
BEGIN DESCRIPTION:
UNT 061 in BCW 7.0
END DESCRIPTION:
XS GIS Cut Line= 4
      1975624.98     13573174.99      1974625.00     13572775.00
      1973523.27     13572090.95      1972419.59     13571226.75
#Sta/Elev= 30
  3894.5  635.83  4163.7  632.06  4423.6  626.91  4724.8  623.63  4770.9  623.62
  4824.5  622.49  4841.7  622.17  4979.2  620.59  5002.7  619.16  5003.2  618.66
  5010.9  619.16  5015.8  620.74  5079.6  620.10  5231.9  621.15  5247.3  620.57
  5283.9  621.14  5777.5  621.95  5877.9  621.72  5893.2  620.90  5908.6  621.77
  6317.8  622.88  6972.1  628.22  7132.8  630.90  7147.3  631.53  7161.8  633.81
  7182.6  634.32  7205.1  633.61  7282.2  634.74  7339.9  634.63  7670.1  642.25
#Mann=8,-1,0
  3894.5    0.05       0  4724.8     0.1       0  4824.5    0.12       0
  4841.7     0.1       0  5002.7    0.07       0  5010.9     0.1       0
  6317.8    0.05       0  6972.1     0.1       0
Bank Sta=5002.7,5010.9
Exp/Cntr=0.3,0.1

Type RM Length L Ch R = 1,3718,433,433,433
BEGIN DESCRIPTION:
UNT 061 in BCW 6.0
END DESCRIPTION:
XS GIS Cut Line= 4
      1975525.02     13573025.02      1975025.00     13572471.16
      1973788.89     13571967.69      1972925.03     13571025.03
#Sta/Elev= 30
  3709.4  634.37  3964.6  630.74  4063.3  628.26  4148.5  629.35  4197.8  627.93
  4396.5  627.24  4628.3  622.67  4714.7  621.42  4736.3  621.91  4807.0  620.01
  4989.5  618.23  5002.1  615.06  5002.6  614.56  5010.4  615.06  5013.5  616.34
  5018.9  616.01  5027.9  617.69  5043.0  618.04  5091.1  618.52  5150.0  617.76
  5203.5  619.41  5358.6  620.35  5508.7  620.08  5557.1  619.97  5698.1  620.13
  5936.5  624.19  6205.4  623.90  6453.2  627.10  6785.6  633.78  7068.9  643.03
#Mann=7,-1,0
  3709.4    0.05       0  4807.0     0.1       0  5002.1    0.07       0
  5010.4     0.1       0  5508.7    0.05       0  5557.1     0.1       0
  5698.1    0.05       0
Bank Sta=5002.1,5010.4
Exp/Cntr=0.3,0.1

Type RM Length L Ch R = 1,3285,584,584,584
BEGIN DESCRIPTION:
Mapping XS d5c02b78
END DESCRIPTION:
XS GIS Cut Line= 4
      1975420.80     13572478.07      1974840.98     13572023.24
      1973823.62     13571606.58      1973170.81     13570724.59
#Sta/Elev= 30
  3894.1  630.16  4292.6  625.88  4520.4  621.64  4724.0  620.02  4772.0  620.29
  4840.2  618.62  4864.4  617.79  4956.2  617.47  4989.9  613.99  4990.4  613.49
  4997.8  613.49  4998.3  613.99  5009.6  616.08  5033.6  616.76  5134.6  616.56
  5166.7  617.44  5217.8  618.55  5484.8  618.72  5663.6  620.64  5816.9  621.48
  6017.3  624.18  6217.6  627.86  6330.3  631.38  6509.8  635.78  6610.0  637.14
  6695.6  640.48  6739.5  641.12  6795.8  642.99  6810.4  644.23  6827.7  644.79
#Mann=5,-1,0
  3894.1    0.05       0  4840.2     0.1       0  4989.9    0.07       0
  4998.3     0.1       0  5166.7    0.05       0
Bank Sta=4989.9,4998.3
Exp/Cntr=0.3,0.1

Type RM Length L Ch R = 1,2701,447,447,447
BEGIN DESCRIPTION:
Mapping XS 6d335ae9
END DESCRIPTION:
XS GIS Cut Line= 4
      1975535.42     13572148.25      1975236.81     13571464.21
      1973906.95     13571214.21      1973449.32     13570361.36
#Sta/Elev= 30
  3464.4  627.97  3731.6  623.32  4028.9  620.83  4288.3  620.49  4797.1  617.99
  4874.0  615.98  4965.6  615.42  4975.7  614.45  4981.7  613.10  4982.2  612.60
  4989.6  612.60  4990.1  613.10  4996.3  613.21  5006.3  614.76  5036.8  616.65
  5058.5  615.91  5211.4  616.80  5413.3  619.29  5617.5  623.53  5667.0  624.22
  5721.5  623.99  5749.1  625.09  5801.4  625.47  6028.4  630.35  6082.8  630.72
  6119.1  631.68  6170.5  634.30  6346.1  640.88  6419.6  642.73  6531.8  649.18
#Mann=6,-1,0
  3464.4    0.05       0  4797.1     0.1       0  4981.7    0.07       0
  4990.1     0.1       0  5058.5    0.05       0  6419.6     0.1       0
Bank Sta=4981.7,4990.1
Exp/Cntr=0.3,0.1

Type RM Length L Ch R = 1,2254,490,490,490
BEGIN DESCRIPTION:
Mapping XS a3059fb7
END DESCRIPTION:
XS GIS Cut Line= 4
      1975618.75     13572057.96      1975424.31     13571380.88
      1974077.09     13570641.30      1973546.81     13570149.14
#Sta/Elev= 30
  3241.4  626.72  3494.9  623.11  3733.5  620.79  4127.6  620.24  4812.1  617.10
  4862.7  616.92  4937.5  614.64  4966.0  615.00  5017.4  613.62  5040.2  614.12
  5048.8  613.37  5049.3  612.87  5057.6  613.37  5069.3  614.99  5139.5  616.26
  5150.8  615.30  5281.5  618.29  5422.7  620.04  5601.9  625.08  5665.4  625.68
  5900.9  635.28  5920.5  636.01  5934.7  637.75  5955.6  638.26  5969.8  639.67
  6026.5  641.95  6097.4  647.19  6154.1  649.23  6189.2  649.91  6206.2  649.54
#Mann=6,-1,0
  3241.4    0.05       0  4812.1     0.1       0  5048.8    0.07       0
  5057.6     0.1       0  5139.5    0.05       0  5900.9     0.1       0
Bank Sta=5048.8,5057.6
Exp/Cntr=0.3,0.1

Type RM Length L Ch R = 1,1764,486,486,486
BEGIN DESCRIPTION:
UNT 061 in BCW 2.0
END DESCRIPTION:
XS GIS Cut Line= 3
      1975785.44     13571846.19      1975156.95     13570637.83
      1973733.35     13570002.42
#Sta/Elev= 30
  3077.6  623.63  3324.5  621.90  3383.3  621.12  3390.8  620.26  3405.8  621.12
  3462.8  620.57  3495.7  621.20  3501.4  620.33  3523.5  620.13  3552.4  620.82
  3910.2  620.04  4921.6  614.56  4939.6  616.58  4950.3  617.45  4956.5  616.43
  4973.5  610.57  4992.2  607.78  4992.7  607.28  5001.1  607.78  5019.9  611.05
  5043.1  613.26  5091.6  614.30  5343.7  619.23  5427.3  622.53  5563.6  625.89
  5731.6  632.85  5789.0  634.30  5821.6  636.13  5909.6  638.24  5998.6  641.21
#Mann=6,-1,0
  3077.6    0.05       0  4939.6     0.1       0  4992.2    0.07       0
  5001.1     0.1       0  5091.6    0.05       0  5909.6     0.1       0
Bank Sta=4992.2,5001.1
Exp/Cntr=0.3,0.1

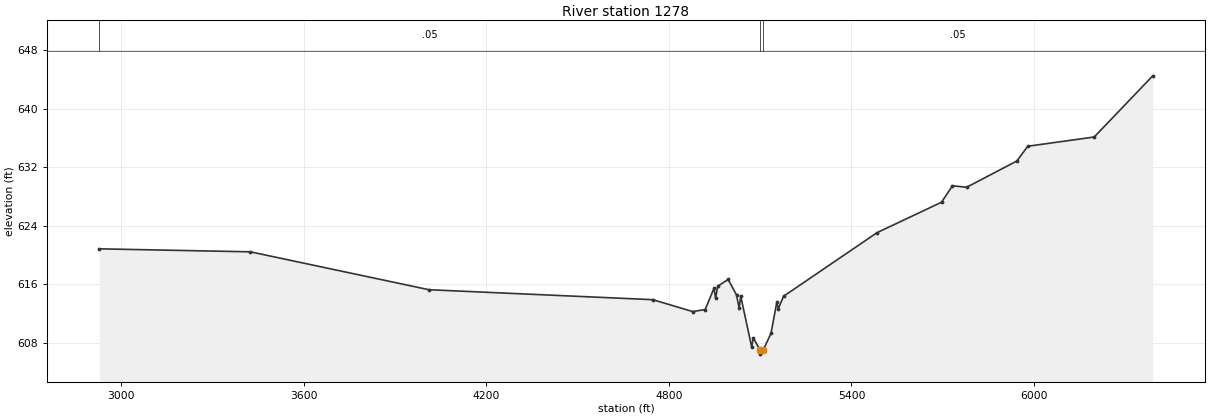
Type RM Length L Ch R = 1,1278,0,0,0
BEGIN DESCRIPTION:
UNT 061 in BCW 1.0
END DESCRIPTION:
XS GIS Cut Line= 3
      1975806.25     13571533.63      1975417.37     13570113.52
      1973488.42     13569631.28
#Sta/Elev= 30
  2929.1  620.86  3425.3  620.45  4012.0  615.28  4747.5  613.92  4878.1  612.30
  4919.3  612.57  4948.5  615.48  4953.7  614.11  4960.5  615.75  4994.9  616.68
  5022.4  614.57  5031.0  612.79  5036.2  614.40  5072.2  607.47  5077.4  608.71
  5100.4  606.99  5100.9  606.49  5109.4  606.99  5135.8  609.34  5154.7  613.58
  5159.9  612.70  5177.0  614.39  5484.6  623.08  5695.9  627.22  5731.9  629.47
  5778.3  629.26  5943.2  632.84  5979.3  634.86  6197.5  636.12  6389.8  644.47
#Mann=3,-1,0
  2929.1    0.05       0  5100.4   0.035       0  5109.4    0.05       0
Bank Sta=5100.4,5109.4
Exp/Cntr=0.3,0.1

Chan Stop Cuts=-1