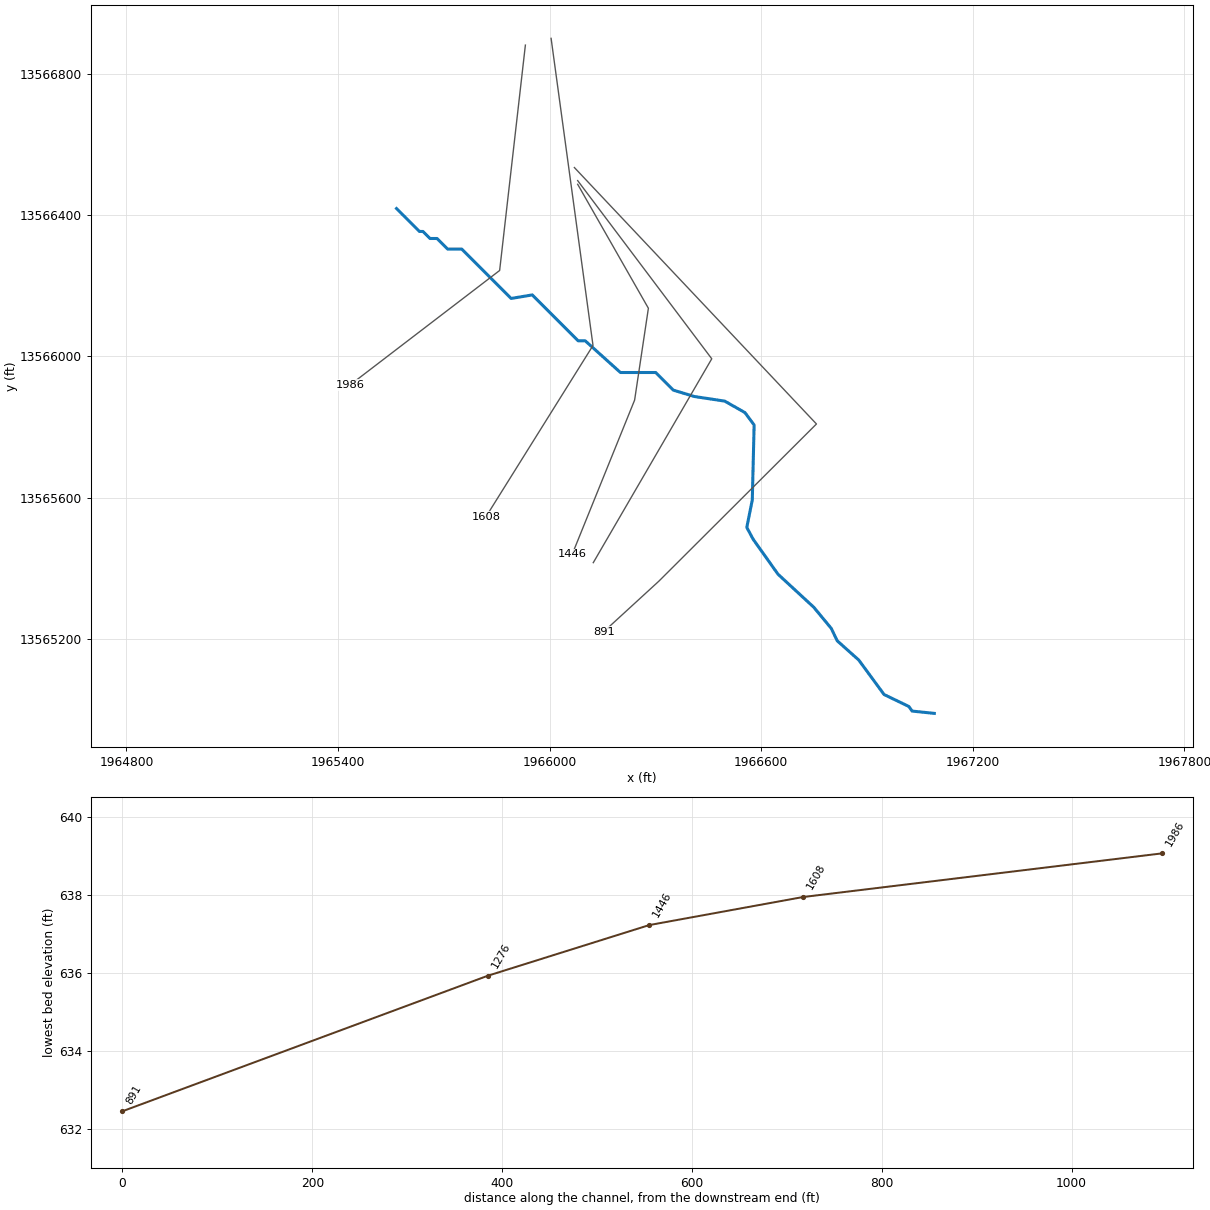
--- UNT 063 in BCW.prj (project) ---

Proj Title=UNT 063 in BCW Base Level Engineering
Current Plan=p01
Default Exp/Contr=0.3,0.1
English Units
Geom File=g01
Flow File=f01
Plan File=p01
Y Axis Title=Elevation
X Axis Title(PF)=Main Channel Distance
X Axis Title(XS)=Station
BEGIN DESCRIPTION:
UNT 063 in BCW
END DESCRIPTION:
DSS Export Rating Curves= 0
DSS Export Rating Curve Sorted= 0
DSS Export Volume Flow Curves= 0
DXF OffsetX= 0
DXF OffsetY= 0
DXF ScaleX= 1
DXF ScaleY= 10

--- UNT 063 in BCW.p01 (plan) ---

Plan Title=Multiple Run
Short Identifier=Multiple
Geom File=g01
Flow File=f01
Subcritical Flow
K Sum by GR= 0
Std Step Tol= 0.01
Critical Tol= 0.01
Num of Std Step Trials= 20
Max Error Tol= 0.3
Flow Tol Ratio= 0.001
Split Flow NTrial= 30
Split Flow Tol= 0.02
Split Flow Ratio= 0.02
Log Output Level= 0
Friction Slope Method= 1
Unsteady Friction Slope Method= 2
Unsteady Bridges Friction Slope Method= 1
Parabolic Critical Depth
Global Vel Dist=  1 , 1 , 1
Global Log Level= 0
CheckData=True
Encroach Param= -1, 0, 0, 0
BEGIN DESCRIPTION:
Multiple Run
END DESCRIPTION:

--- UNT 063 in BCW.f01 (steady flow) ---

Flow Title=Multiple
Program Version=5.05
Number of Profiles= 7
Profile Names=10-year,25-year,50-year,1pct_min,100-year,1pct_plu,500-year
River Rch & RM=UNT 063 in BCW,Reach-1         ,1986
     443     614     754     458     914    1825    1346
Boundary for River Rch & Prof#=UNT 063 in BCW,Reach-1         , 1
Up Type= 0
Dn Type= 3
Dn Slope=0.005
Boundary for River Rch & Prof#=UNT 063 in BCW,Reach-1         , 2
Up Type= 0
Dn Type= 3
Dn Slope=0.005
Boundary for River Rch & Prof#=UNT 063 in BCW,Reach-1         , 3
Up Type= 0
Dn Type= 3
Dn Slope=0.005
Boundary for River Rch & Prof#=UNT 063 in BCW,Reach-1         , 4
Up Type= 0
Dn Type= 3
Dn Slope=0.005
Boundary for River Rch & Prof#=UNT 063 in BCW,Reach-1         , 5
Up Type= 0
Dn Type= 3
Dn Slope=0.005
Boundary for River Rch & Prof#=UNT 063 in BCW,Reach-1         , 6
Up Type= 0
Dn Type= 3
Dn Slope=0.005
Boundary for River Rch & Prof#=UNT 063 in BCW,Reach-1         , 7
Up Type= 0
Dn Type= 3
Dn Slope=0.005
DSS Import GetInterval= 0
DSS Import GetPeak= 0
DSS Import FillOption= 0

--- UNT 063 in BCW.g01 (geometry) ---

Geom Title=Existing Conditions

River Reach=UNT 063 in BCW,Reach-1
Reach XY= 30
      1965565.80     13566419.54      1965630.80     13566354.54
      1965640.80     13566354.54      1965660.80     13566334.54
      1965680.80     13566334.54      1965710.80     13566304.54
      1965750.80     13566304.54      1965890.80     13566164.54
      1965950.80     13566174.54      1966080.80     13566044.54
      1966100.80     13566044.54      1966200.80     13565954.54
      1966300.80     13565954.54      1966350.80     13565904.54
      1966410.60     13565886.44      1966496.53     13565873.42
      1966553.83     13565840.87      1966579.87     13565805.71
      1966574.66     13565593.47      1966559.03     13565515.35
      1966577.26     13565481.49      1966647.58     13565382.53
      1966749.14     13565288.78      1966798.62     13565228.89
      1966815.54     13565193.73      1966876.74     13565139.04
      1966948.36     13565041.39      1967018.67     13565007.53
      1967027.78     13564994.51      1967090.72     13564988.00

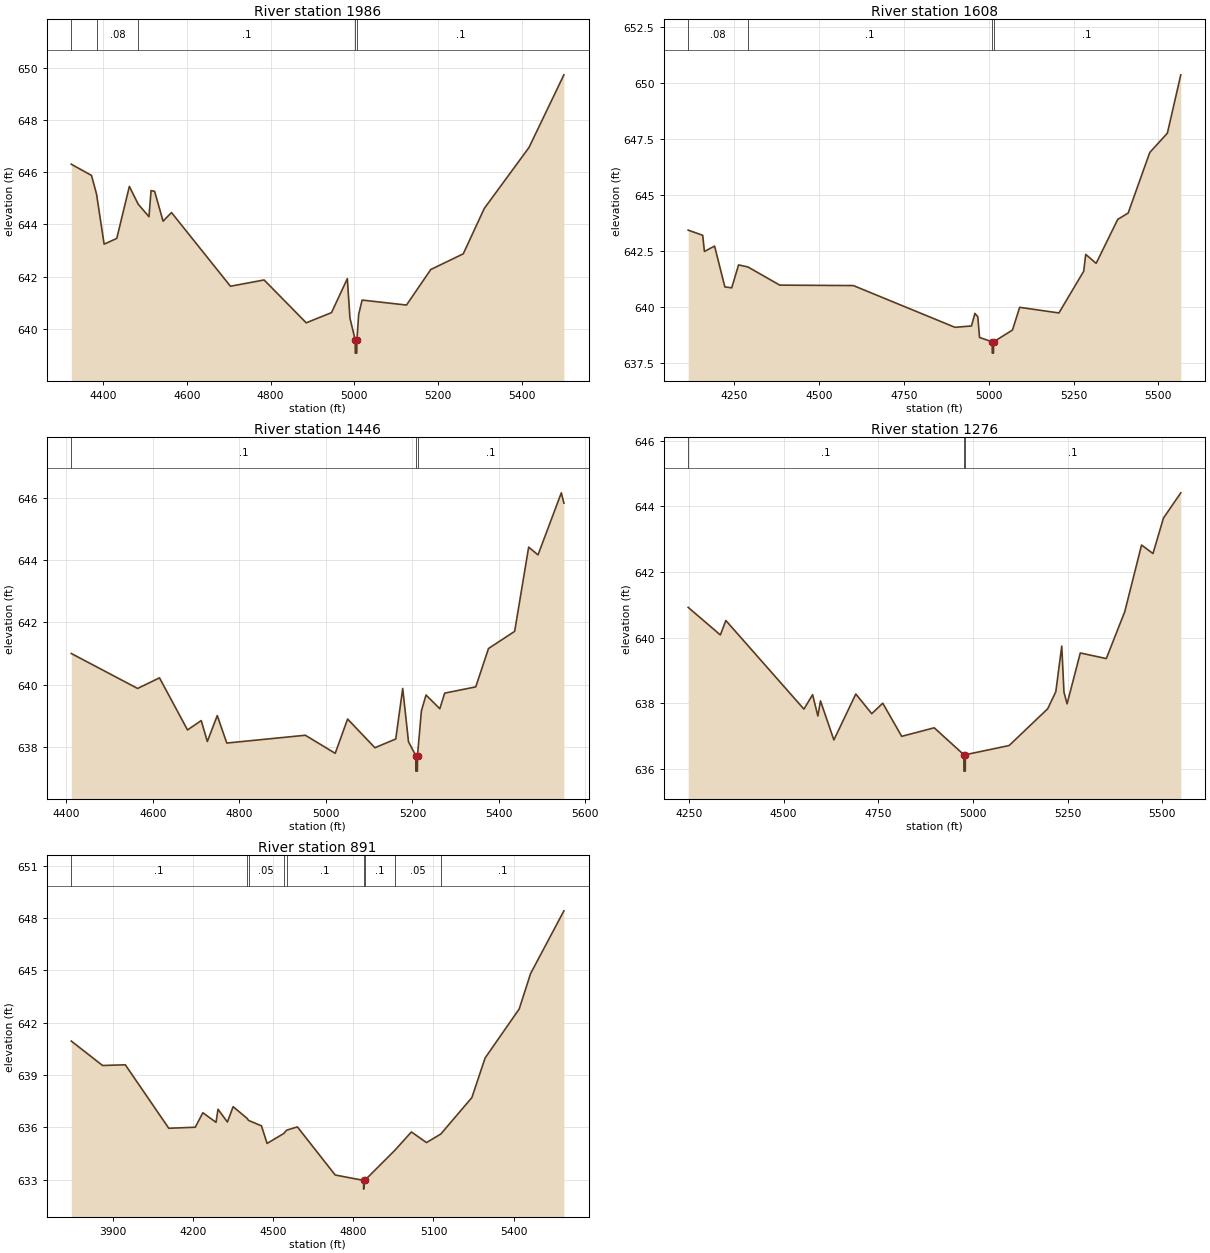
Type RM Length L Ch R = 1,1986,378,378,378
BEGIN DESCRIPTION:
UNT 063 in BCW 1.0
END DESCRIPTION:
XS GIS Cut Line= 3
      1965931.25     13566882.95      1965858.23     13566243.85
      1965433.97     13565919.16
#Sta/Elev= 30
  4323.4  646.30  4371.7  645.87  4383.7  645.16  4401.9  643.24  4432.1  643.46
  4462.2  645.45  4483.3  644.77  4509.1  644.29  4514.1  645.29  4522.6  645.26
  4542.8  644.12  4562.9  644.45  4703.8  641.63  4784.3  641.87  4885.0  640.23
  4945.4  640.62  4983.2  641.92  4989.5  640.41  5002.1  639.57  5002.3  639.07
  5005.8  639.07  5006.1  639.57  5010.3  640.55  5018.6  641.10  5124.6  640.91
  5182.7  642.27  5260.3  642.87  5310.7  644.61  5417.5  646.94  5500.9  649.72
#Mann=5,-1,0
  4323.4     0.1       0  4383.7    0.08       0  4483.3     0.1       0
  5002.1    0.07       0  5006.1     0.1       0
Bank Sta=5002.1,5006.1
Exp/Cntr=0.3,0.1

Type RM Length L Ch R = 1,1608,162,162,162
BEGIN DESCRIPTION:
UNT 063 in BCW 2.0
END DESCRIPTION:
XS GIS Cut Line= 3
      1966004.17     13566902.11      1966122.98     13566031.18
      1965819.56     13565545.69
#Sta/Elev= 30
  4114.6  643.43  4157.4  643.20  4162.5  642.48  4192.4  642.72  4222.7  640.90
  4242.9  640.86  4263.1  641.88  4290.6  641.79  4384.5  640.98  4601.4  640.96
  4900.7  639.10  4949.4  639.16  4959.5  639.72  4968.0  639.57  4973.1  638.65
  5010.4  638.45  5010.7  637.95  5014.2  637.95  5014.4  638.45  5070.2  638.98
  5091.4  639.99  5207.0  639.74  5280.1  641.60  5286.0  642.35  5316.7  641.95
  5380.4  643.91  5411.0  644.19  5474.7  646.89  5526.6  647.75  5566.1  650.35
#Mann=4,-1,0
  4114.6    0.08       0  4290.6     0.1       0  5010.4    0.07       0
  5014.4     0.1       0
Bank Sta=5010.4,5014.4
Exp/Cntr=0.3,0.1

Type RM Length L Ch R = 1,1446,170,170,170
BEGIN DESCRIPTION:
Mapping XS efe44e69
END DESCRIPTION:
XS GIS Cut Line= 4
      1966079.53     13566488.24      1966280.03     13566136.72
      1966240.97     13565876.30      1966064.14     13565439.44
#Sta/Elev= 30
  4411.1  641.00  4564.5  639.88  4615.1  640.22  4679.9  638.55  4711.6  638.85
  4725.7  638.18  4748.7  639.01  4770.7  638.13  4952.4  638.38  5021.5  637.80
  5050.1  638.90  5113.3  637.98  5161.5  638.26  5177.6  639.88  5191.0  638.17
  5207.8  637.73  5208.0  637.23  5211.5  637.23  5211.8  637.73  5220.8  639.16
  5231.5  639.67  5263.4  639.23  5274.7  639.73  5346.5  639.93  5376.0  641.16
  5436.5  641.71  5468.9  644.41  5490.5  644.16  5544.4  646.15  5550.4  645.82
#Mann=3,-1,0
  4411.1     0.1       0  5207.8    0.07       0  5211.8     0.1       0
Bank Sta=5207.8,5211.8
Exp/Cntr=0.3,0.1

Type RM Length L Ch R = 1,1276,385,385,385
BEGIN DESCRIPTION:
Mapping XS afd0fb18
END DESCRIPTION:
XS GIS Cut Line= 3
      1966079.51     13566498.69      1966459.72     13565993.49
      1966123.79     13565415.39
#Sta/Elev= 30
  4247.8  640.92  4332.8  640.08  4347.3  640.52  4553.5  637.82  4576.4  638.26
  4590.3  637.61  4597.2  638.07  4632.6  636.88  4690.5  638.28  4732.6  637.68
  4761.7  638.00  4811.7  636.99  4897.6  637.25  4975.8  636.43  4976.1  635.93
  4979.6  635.93  4979.8  636.43  5095.4  636.71  5197.2  637.83  5218.7  638.35
  5234.4  639.74  5240.2  638.34  5248.4  637.98  5283.3  639.53  5352.0  639.36
  5400.8  640.79  5445.1  642.82  5475.3  642.56  5502.9  643.64  5548.7  644.41
#Mann=3,-1,0
  4247.8     0.1       0  4975.8    0.07       0  4979.8     0.1       0
Bank Sta=4975.8,4979.8
Exp/Cntr=0.3,0.1

Type RM Length L Ch R = 1,891,0,0,0
BEGIN DESCRIPTION:
UNT 063 in BCW 3.0
END DESCRIPTION:
XS GIS Cut Line= 4
      1966070.15     13566535.76      1966756.59     13565808.59
      1966309.62     13565362.77      1966153.63     13565219.79
#Sta/Elev= 30
  3745.0  640.94  3862.1  639.54  3947.1  639.58  4109.7  635.94  4208.8  636.00
  4237.2  636.83  4286.5  636.28  4293.8  637.03  4329.0  636.30  4350.4  637.18
  4402.4  636.51  4408.1  636.39  4456.4  636.08  4477.5  635.07  4539.8  635.64
  4550.6  635.83  4590.8  636.02  4732.3  633.26  4838.6  632.95  4838.8  632.45
  4842.6  632.95  4955.7  634.68  5017.4  635.73  5073.9  635.12  5127.4  635.61
  5243.6  637.70  5293.1  639.97  5420.6  642.78  5463.2  644.81  5587.9  648.41
#Mann=9,-1,0
  3745.0     0.1       0  4402.4    0.08       0  4408.1    0.05       0
  4539.8    0.08       0  4550.6     0.1       0  4838.6    0.04       0
  4842.6     0.1       0  4955.7    0.05       0  5127.4     0.1       0
Bank Sta=4838.6,4842.6
Exp/Cntr=0.3,0.1

Chan Stop Cuts=-1