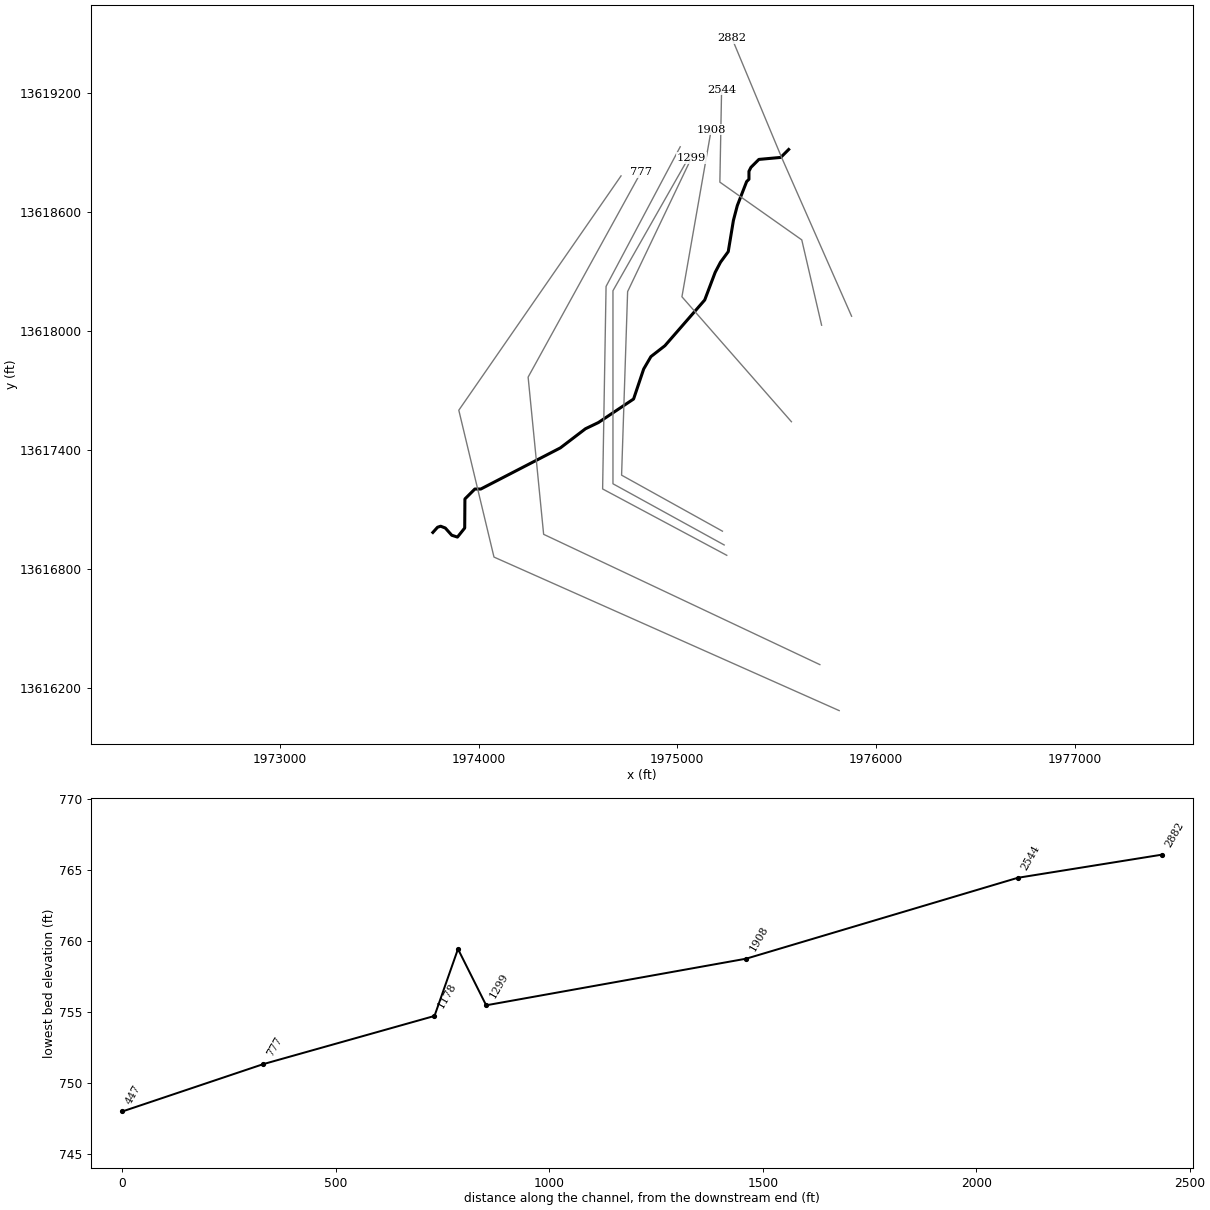
--- UNT 120 in BCW.prj (project) ---

Proj Title=UNT 120 in BCW Base Level Engineering
Current Plan=p01
Default Exp/Contr=0.3,0.1
English Units
Geom File=g01
Flow File=f01
Plan File=p01
BEGIN DESCRIPTION:
UNT 120 in BCW
END DESCRIPTION:

--- UNT 120 in BCW.p01 (plan) ---

Plan Title=Multiple Run
Short Identifier=Multiple
Geom File=g01
Flow File=f01
Subcritical Flow
K Sum by GR= 0
Std Step Tol= 0.01
Critical Tol= 0.01
Num of Std Step Trials= 20
Max Error Tol= 0.3
Flow Tol Ratio= 0.001
Split Flow NTrial= 30
Split Flow Tol= 0.02
Split Flow Ratio= 0.02
Log Output Level= 0
Friction Slope Method= 1
Unsteady Friction Slope Method= 2
Unsteady Bridges Friction Slope Method= 1
Parabolic Critical Depth
Global Vel Dist=  1 , 1 , 1
Global Log Level= 0
CheckData=True
Encroach Param= -1, 0, 0, 0
BEGIN DESCRIPTION:
Multiple Run
END DESCRIPTION:

--- UNT 120 in BCW.f01 (steady flow) ---

Flow Title=Multiple
Number of Profiles=7
Profile Names=10-year,25-year,50-year,1pct_min,100-year,1pct_plu,500-year
River Rch & RM= UNT 120 in BCW,Reach-1,2882
     495     693     859     527    1052    2100    1585
Boundary for River Rch & Prof#=UNT 120 in BCW,Reach-1,1
Up Type=0
Dn Type=3
Dn Slope=0.005
Boundary for River Rch & Prof#=UNT 120 in BCW,Reach-1,2
Up Type=0
Dn Type=3
Dn Slope=0.005
Boundary for River Rch & Prof#=UNT 120 in BCW,Reach-1,3
Up Type=0
Dn Type=3
Dn Slope=0.005
Boundary for River Rch & Prof#=UNT 120 in BCW,Reach-1,4
Up Type=0
Dn Type=3
Dn Slope=0.005
Boundary for River Rch & Prof#=UNT 120 in BCW,Reach-1,5
Up Type=0
Dn Type=3
Dn Slope=0.005
Boundary for River Rch & Prof#=UNT 120 in BCW,Reach-1,6
Up Type=0
Dn Type=3
Dn Slope=0.005
Boundary for River Rch & Prof#=UNT 120 in BCW,Reach-1,7
Up Type=0
Dn Type=3
Dn Slope=0.005

--- UNT 120 in BCW.g01 (geometry) ---

Geom Title=Existing Conditions

River Reach=UNT 120 in BCW,Reach-1
Reach XY= 30
      1975560.80     13618914.54      1975520.80     13618874.54
      1975410.80     13618864.54      1975370.80     13618824.54
      1975360.80     13618804.54      1975360.80     13618764.54
      1975349.11     13618752.85      1975302.14     13618631.86
      1975282.61     13618557.64      1975256.57     13618400.09
      1975217.50     13618346.70      1975190.80     13618295.92
      1975138.08     13618156.60      1974937.56     13617926.13
      1974867.24     13617871.44      1974830.78     13617808.94
      1974780.00     13617657.90      1974602.92     13617539.41
      1974537.82     13617508.16      1974411.51     13617411.80
      1974010.80     13617204.54      1973980.80     13617204.54
      1973930.80     13617154.54      1973929.74     13617008.16
      1973893.28     13616962.59      1973864.64     13616971.70
      1973832.09     13617008.16      1973808.65     13617017.27
      1973793.02     13617012.07      1973769.45     13616985.89

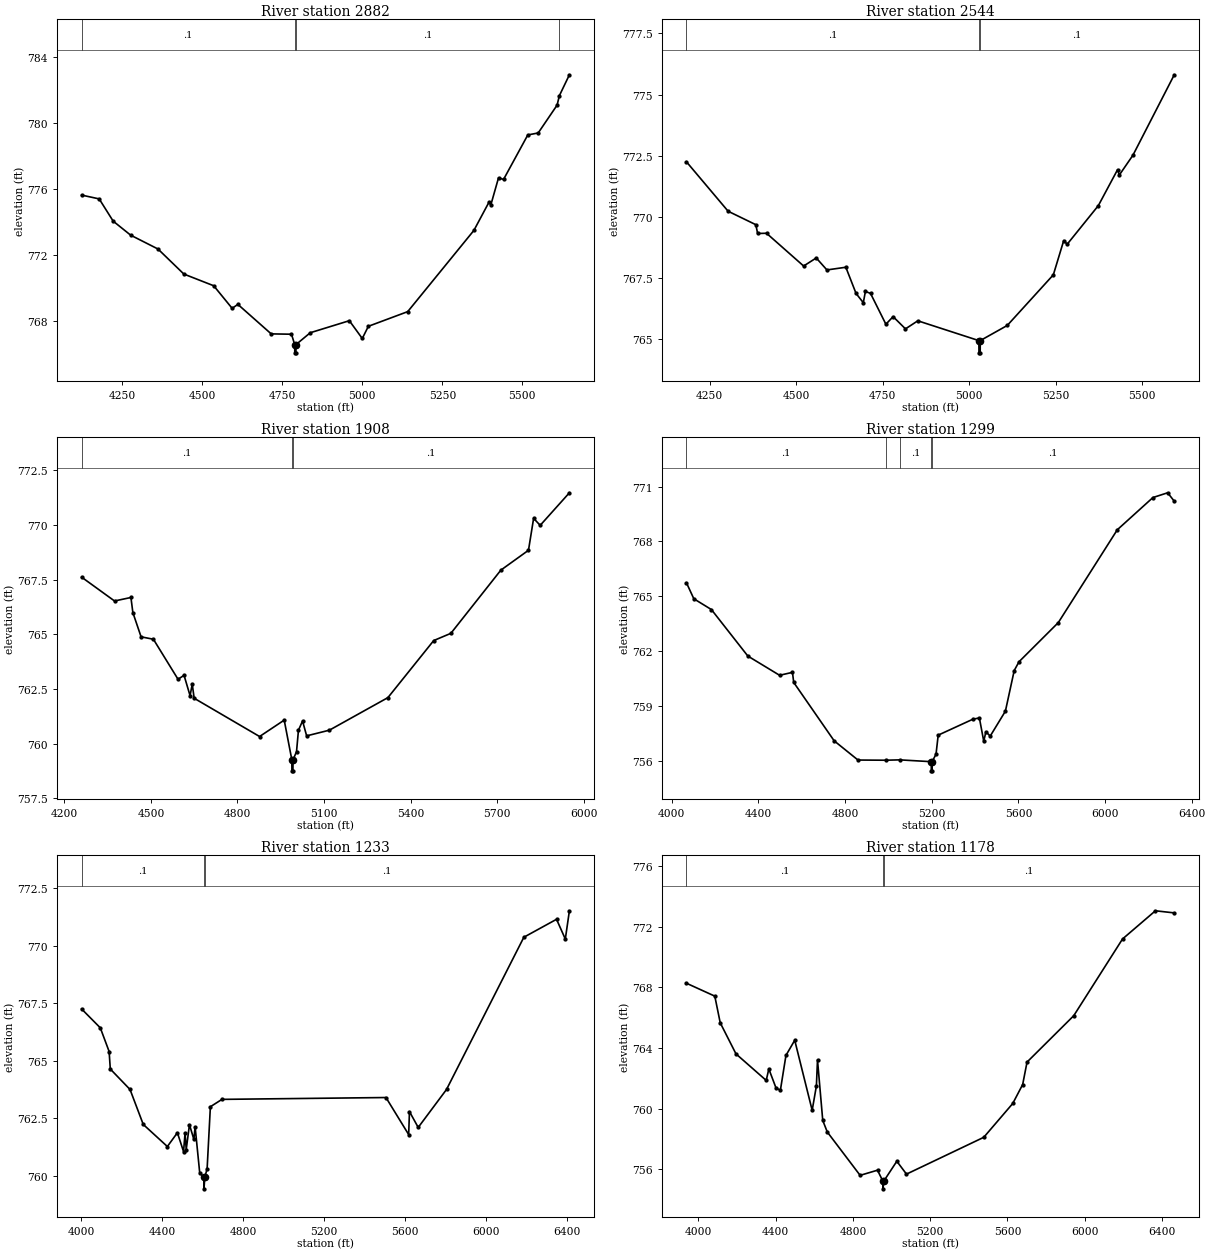
Type RM Length L Ch R = 1,2882,338,338,338
BEGIN DESCRIPTION:
UNT 120 in BCW 3.0
END DESCRIPTION:
XS GIS Cut Line= 3
      1975877.55     13618074.78      1975525.00     13618875.00
      1975275.02     13619474.96
#Sta/Elev= 30
  4122.7  775.64  4177.6  775.41  4221.3  774.06  4275.9  773.21  4361.3  772.37
  4442.2  770.85  4535.5  770.14  4593.1  768.77  4611.0  769.01  4715.2  767.22
  4778.6  767.20  4788.6  766.57  4788.9  766.07  4792.4  766.07  4792.6  766.57
  4837.3  767.29  4959.4  768.02  4999.8  766.94  5018.8  767.68  5141.8  768.57
  5348.7  773.50  5396.3  775.23  5401.8  775.06  5425.6  776.69  5441.3  776.59
  5517.1  779.29  5549.6  779.41  5608.7  781.10  5615.7  781.67  5647.1  782.94
#Mann=4,-1,0
  4122.7     0.1       0  4788.6    0.07       0  4792.6     0.1       0
  5615.7    0.08       0
Bank Sta=4788.6,4792.6
Exp/Cntr=0.3,0.1

Type RM Length L Ch R = 1,2544,636,636,636
BEGIN DESCRIPTION:
Mapping XS 10ba6328
END DESCRIPTION:
XS GIS Cut Line= 4
      1975726.53     13618029.58      1975626.70     13618459.29
      1975214.37     13618750.09      1975223.05     13619214.50
#Sta/Elev= 30
  4182.7  772.25  4303.1  770.23  4383.2  769.68  4388.4  769.32  4414.1  769.33
  4521.4  767.99  4557.9  768.32  4588.7  767.83  4643.4  767.94  4672.9  766.87
  4693.9  766.49  4700.0  766.95  4714.8  766.87  4759.2  765.61  4780.1  765.92
  4815.8  765.42  4851.5  765.75  5028.0  764.94  5028.3  764.44  5031.8  764.44
  5032.0  764.94  5110.1  765.56  5243.3  767.63  5273.3  769.03  5283.3  768.88
  5373.4  770.46  5429.0  771.93  5434.0  771.71  5473.4  772.52  5592.9  775.81
#Mann=3,-1,0
  4182.7     0.1       0  5028.0    0.07       0  5032.0     0.1       0
Bank Sta=5028,5032
Exp/Cntr=0.3,0.1

Type RM Length L Ch R = 1,1908,609,609,609
BEGIN DESCRIPTION:
Mapping XS 6f9f3b6e
END DESCRIPTION:
XS GIS Cut Line= 3
      1975574.60     13617543.51      1975023.40     13618172.83
      1975170.96     13619014.82
#Sta/Elev= 30
  4259.5  767.61  4373.6  766.52  4430.5  766.68  4437.2  765.99  4465.7  764.88
  4508.4  764.77  4593.8  762.94  4614.7  763.12  4635.5  762.19  4643.1  762.71
  4649.8  762.07  4876.6  760.32  4962.0  761.07  4988.5  759.25  4988.7  758.75
  4992.2  758.75  4992.5  759.25  5004.7  759.63  5011.4  760.61  5025.6  761.03
  5039.8  760.35  5118.6  760.61  5321.6  762.10  5480.4  764.71  5539.9  765.04
  5713.1  767.93  5809.0  768.84  5826.8  770.30  5849.6  769.98  5950.9  771.47
#Mann=3,-1,0
  4259.5     0.1       0  4988.5    0.07       0  4992.5     0.1       0
Bank Sta=4988.5,4992.5
Exp/Cntr=0.3,0.1

Type RM Length L Ch R = 1,1299,66,66,66
BEGIN DESCRIPTION:
Mapping XS 07518315
END DESCRIPTION:
XS GIS Cut Line= 4
      1975227.40     13616992.27      1974719.58     13617274.39
      1974749.96     13618198.87      1975071.15     13618871.63
#Sta/Elev= 30
  4068.1  765.74  4102.0  764.87  4183.2  764.28  4351.4  761.74  4497.8  760.69
  4557.3  760.85  4563.0  760.30  4749.7  757.11  4859.7  756.06  4987.7  756.05
  5051.9  756.07  5197.9  755.97  5198.2  755.47  5201.7  755.47  5201.9  755.97
  5219.9  756.38  5229.9  757.42  5390.0  758.29  5420.0  758.36  5440.1  757.09
  5450.1  757.60  5470.1  757.37  5540.1  758.73  5580.8  760.95  5603.0  761.43
  5784.4  763.57  6056.6  768.64  6221.0  770.40  6289.0  770.66  6319.5  770.20
#Mann=5,-1,0
  4068.1     0.1       0  4987.7    0.05       0  5051.9     0.1       0
  5197.9   0.033       0  5201.9     0.1       0
Bank Sta=5197.9,5201.9
Exp/Cntr=0.3,0.1

Type RM Length L Ch R = 1,1233,55,55,55
BEGIN DESCRIPTION:
Mapping XS 08d37071
END DESCRIPTION:
XS GIS Cut Line= 4
      1975236.04     13616922.85      1974676.18     13617230.99
      1974676.18     13618203.21      1975070.55     13618896.62
#Sta/Elev= 30
  4003.5  767.25  4095.8  766.43  4139.4  765.40  4145.1  764.64  4242.6  763.75
  4307.9  762.23  4427.0  761.27  4476.5  761.87  4506.9  761.05  4514.4  761.86
  4520.1  761.14  4536.1  762.22  4557.9  761.58  4564.0  762.13  4586.8  760.12
  4607.7  759.93  4607.9  759.43  4611.7  759.93  4623.3  760.30  4639.4  763.00
  4696.6  763.32  5506.6  763.40  5618.7  761.79  5622.6  762.79  5665.8  762.10
  5805.6  763.75  6187.6  770.37  6349.0  771.15  6392.3  770.29  6412.5  771.52
#Mann=3,-1,0
  4003.5     0.1       0  4607.7    0.07       0  4611.7     0.1       0
Bank Sta=4607.7,4611.7
Exp/Cntr=0.3,0.1

Type RM Length L Ch R = 1,1178,401,401,401
BEGIN DESCRIPTION:
Mapping XS 6ca4d95d
END DESCRIPTION:
XS GIS Cut Line= 4
      1975249.06     13616870.76      1974624.09     13617204.95
      1974641.45     13618224.91      1975014.73     13618928.06
#Sta/Elev= 30
  3938.6  768.28  4085.2  767.43  4113.3  765.67  4194.9  763.62  4351.4  761.87
  4364.8  762.63  4403.0  761.34  4424.9  761.24  4453.5  763.52  4498.9  764.52
  4589.2  759.90  4611.1  761.51  4616.8  763.22  4644.0  759.23  4667.4  758.47
  4837.4  755.61  4927.4  755.95  4955.4  755.22  4955.7  754.72  4959.4  755.22
  5027.4  756.54  5077.4  755.69  5477.5  758.12  5627.5  760.35  5678.8  761.60
  5701.4  763.08  5943.2  766.14  6195.7  771.20  6366.0  773.06  6463.5  772.92
#Mann=3,-1,0
  3938.6     0.1       0  4955.4    0.07       0  4959.4     0.1       0
Bank Sta=4955.4,4959.4
Exp/Cntr=0.3,0.1

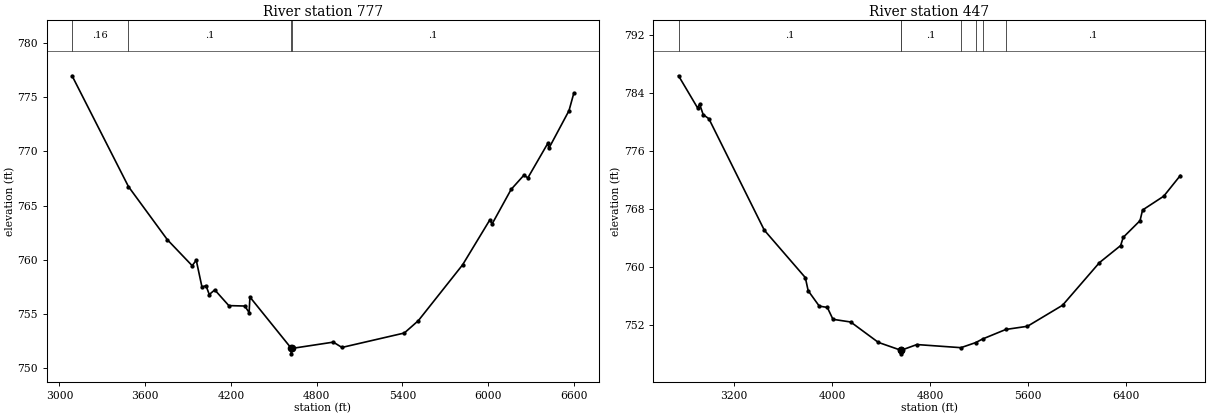
Type RM Length L Ch R = 1,777,330,330,330
BEGIN DESCRIPTION:
Mapping XS 17fac40a
END DESCRIPTION:
XS GIS Cut Line= 4
      1975717.75     13616320.23      1974327.14     13616976.47
      1974249.02     13617768.13      1974816.74     13618799.41
#Sta/Elev= 30
  3088.8  776.98  3483.2  766.76  3755.3  761.86  3929.2  759.46  3957.5  759.97
  3997.6  757.49  4025.9  757.62  4048.6  756.80  4087.0  757.23  4185.3  755.78
  4297.1  755.74  4327.4  755.14  4333.0  756.57  4622.9  751.83  4623.1  751.33
  4626.9  751.83  4916.4  752.41  4976.7  751.92  5412.9  753.25  5511.2  754.39
  5820.8  759.54  6012.0  763.70  6027.2  763.31  6160.4  766.50  6249.7  767.81
  6277.2  767.56  6418.3  770.78  6424.0  770.28  6565.1  773.76  6599.2  775.39
#Mann=4,-1,0
  3088.8    0.16       0  3483.2     0.1       0  4622.9    0.07       0
  4626.9     0.1       0
Bank Sta=4622.9,4626.9
Exp/Cntr=0.3,0.1

Type RM Length L Ch R = 1,447,0,0,0
BEGIN DESCRIPTION:
UNT 120 in BCW 1.0
END DESCRIPTION:
XS GIS Cut Line= 4
      1975815.04     13616088.64      1974077.14     13616861.88
      1973900.06     13617601.47      1974716.79     13618781.56
#Sta/Elev= 30
  2745.5  786.34  2900.4  781.93  2918.1  782.42  2946.8  780.98  2993.3  780.42
  3446.0  765.05  3781.0  758.51  3804.2  756.70  3894.8  754.58  3960.5  754.40
  4006.6  752.76  4151.5  752.39  4377.1  749.58  4560.4  748.50  4560.7  748.00
  4564.4  748.50  4692.0  749.28  5051.6  748.85  5172.2  749.55  5228.9  750.05
  5418.0  751.36  5594.9  751.80  5881.6  754.70  6182.9  760.58  6355.9  762.93
  6376.9  764.06  6514.1  766.36  6535.0  767.83  6708.0  769.74  6843.3  772.59
#Mann=7,-1,0
  2745.5     0.1       0  4560.4    0.07       0  4564.4     0.1       0
  5051.6    0.05       0  5172.2     0.1       0  5228.9    0.05       0
  5418.0     0.1       0
Bank Sta=4560.4,4564.4
Exp/Cntr=0.3,0.1

Chan Stop Cuts=-1