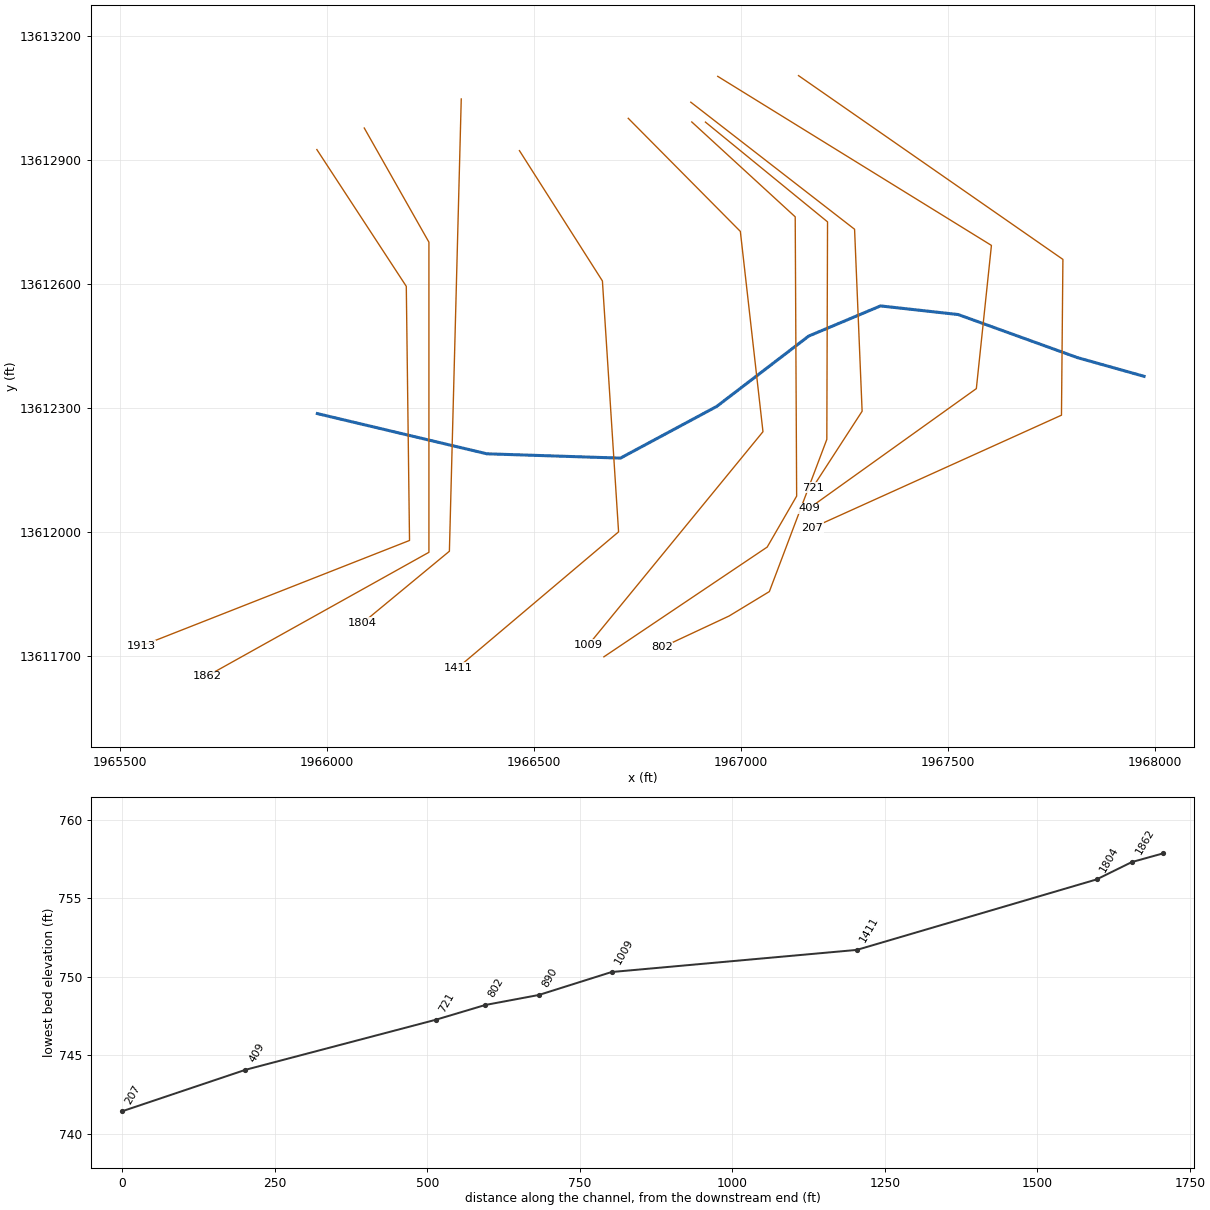
--- UNT 121 in BCW.prj (project) ---

Proj Title=UNT 121 in BCW Base Level Engineering
Current Plan=p01
Default Exp/Contr=0.3,0.1
English Units
Geom File=g01
Flow File=f01
Plan File=p01
BEGIN DESCRIPTION:
UNT 121 in BCW
END DESCRIPTION:

--- UNT 121 in BCW.p01 (plan) ---

Plan Title=Multiple Run
Short Identifier=Multiple
Geom File=g01
Flow File=f01
Subcritical Flow
K Sum by GR= 0
Std Step Tol= 0.01
Critical Tol= 0.01
Num of Std Step Trials= 20
Max Error Tol= 0.3
Flow Tol Ratio= 0.001
Split Flow NTrial= 30
Split Flow Tol= 0.02
Split Flow Ratio= 0.02
Log Output Level= 0
Friction Slope Method= 1
Unsteady Friction Slope Method= 2
Unsteady Bridges Friction Slope Method= 1
Parabolic Critical Depth
Global Vel Dist=  1 , 1 , 1
Global Log Level= 0
CheckData=True
Encroach Param= -1, 0, 0, 0
BEGIN DESCRIPTION:
Multiple Run
END DESCRIPTION:

--- UNT 121 in BCW.f01 (steady flow) ---

Flow Title=Multiple
Number of Profiles=7
Profile Names=10-year,25-year,50-year,1pct_min,100-year,1pct_plu,500-year
River Rch & RM= UNT 121 in BCW,Reach-1,1913
     342     464     563     339     675    1348     971
Boundary for River Rch & Prof#=UNT 121 in BCW,Reach-1,1
Up Type=0
Dn Type=3
Dn Slope=0.005
Boundary for River Rch & Prof#=UNT 121 in BCW,Reach-1,2
Up Type=0
Dn Type=3
Dn Slope=0.005
Boundary for River Rch & Prof#=UNT 121 in BCW,Reach-1,3
Up Type=0
Dn Type=3
Dn Slope=0.005
Boundary for River Rch & Prof#=UNT 121 in BCW,Reach-1,4
Up Type=0
Dn Type=3
Dn Slope=0.005
Boundary for River Rch & Prof#=UNT 121 in BCW,Reach-1,5
Up Type=0
Dn Type=3
Dn Slope=0.005
Boundary for River Rch & Prof#=UNT 121 in BCW,Reach-1,6
Up Type=0
Dn Type=3
Dn Slope=0.005
Boundary for River Rch & Prof#=UNT 121 in BCW,Reach-1,7
Up Type=0
Dn Type=3
Dn Slope=0.005

--- UNT 121 in BCW.g01 (geometry) ---

Geom Title=Existing Conditions

River Reach=UNT 121 in BCW,Reach-1
Reach XY= 9
      1965976.25     13612285.71      1966385.98     13612188.48
      1966708.89     13612178.07      1966941.53     13612303.07
      1967163.75     13612473.21      1967337.36     13612546.12
      1967524.86     13612525.29      1967813.06     13612421.12
      1967974.26     13612375.85

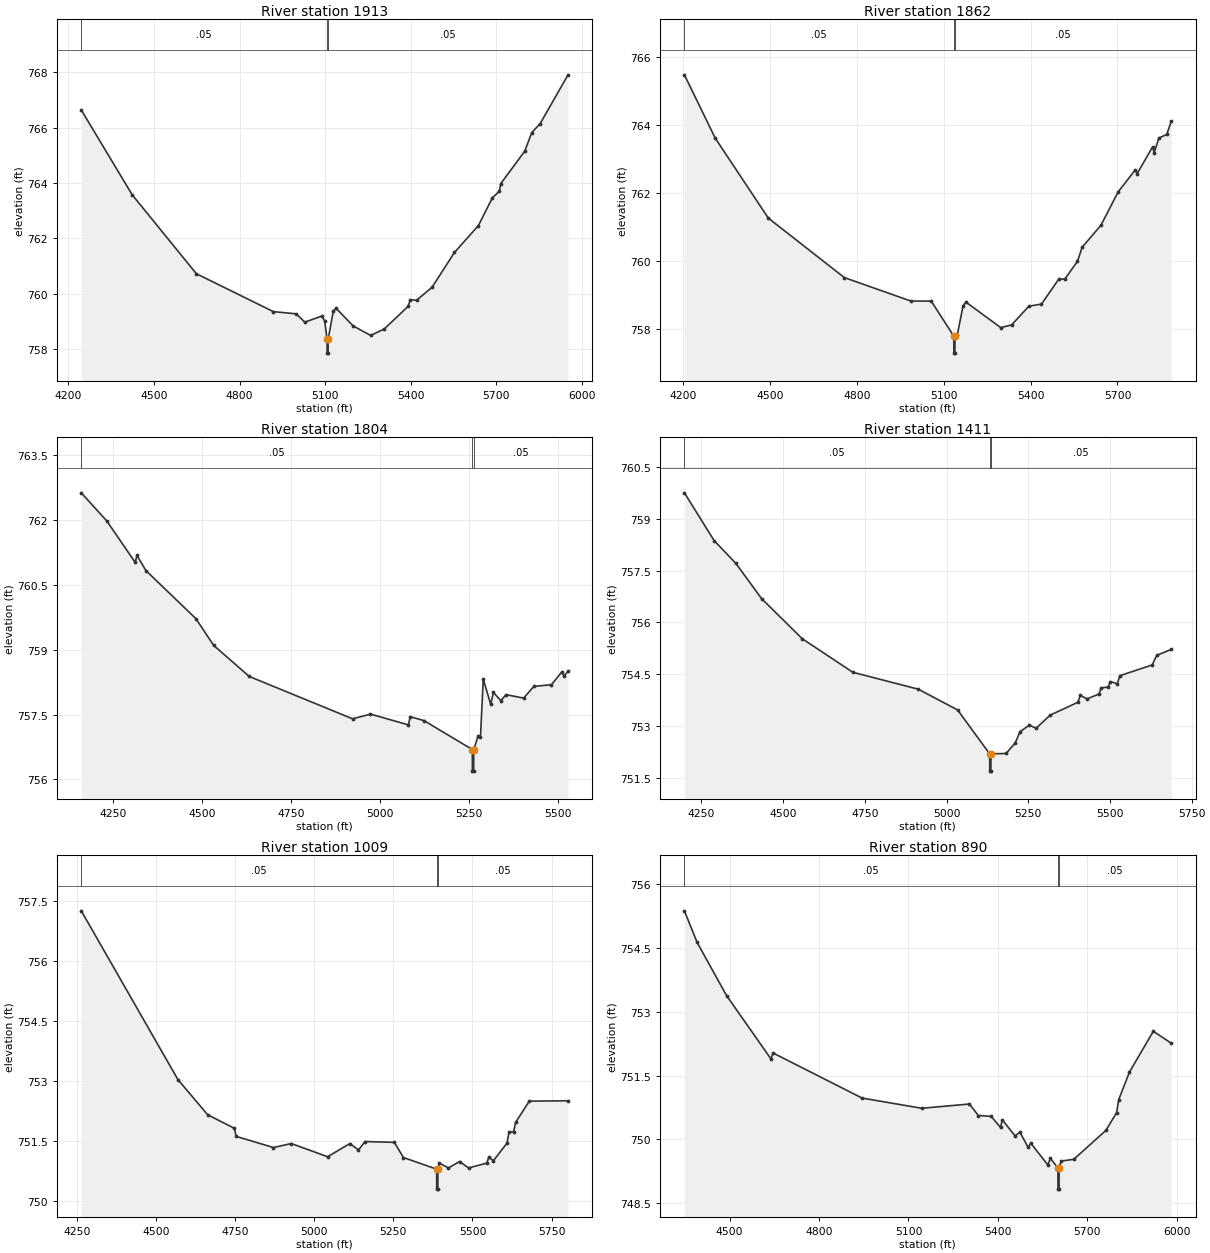
Type RM Length L Ch R = 1,1913,51,51,51
BEGIN DESCRIPTION:
UNT 121 in BCW 3.0
END DESCRIPTION:
XS GIS Cut Line= 4
      1965975.14     13612924.21      1966191.27     13612593.49
      1966199.09     13611978.91      1965550.61     13611723.69
#Sta/Elev= 30
  4245.0  766.64  4423.8  763.57  4648.6  760.72  4918.6  759.35  4998.6  759.27
  5028.6  758.97  5088.6  759.19  5098.6  759.01  5106.6  758.35  5106.9  757.85
  5110.4  757.85  5110.6  758.35  5128.6  759.37  5138.6  759.47  5198.6  758.83
  5259.6  758.49  5306.9  758.72  5390.8  759.54  5398.8  759.78  5420.6  759.76
  5474.8  760.23  5553.4  761.49  5637.3  762.46  5686.1  763.46  5710.5  763.70
  5715.9  763.98  5799.8  765.15  5824.2  765.82  5854.0  766.15  5951.6  767.91
#Mann=3,-1,0
  4245.0    0.05       0  5106.6    0.03       0  5110.6    0.05       0
Bank Sta=5106.6,5110.6
Exp/Cntr=0.3,0.1

Type RM Length L Ch R = 1,1862,58,58,58
BEGIN DESCRIPTION:
Mapping XS 030df522
END DESCRIPTION:
XS GIS Cut Line= 4
      1966089.69     13612976.35      1966245.96     13612700.26
      1966245.96     13611950.26      1965709.71     13611650.90
#Sta/Elev= 30
  4204.2  765.48  4310.6  763.62  4493.9  761.27  4756.7  759.52  4986.7  758.83
  5056.7  758.83  5134.7  757.80  5135.0  757.30  5138.5  757.30  5138.7  757.80
  5146.7  757.83  5166.7  758.69  5176.7  758.80  5296.8  758.05  5334.5  758.13
  5393.9  758.68  5437.4  758.74  5496.8  759.47  5518.5  759.48  5561.9  760.00
  5577.9  760.41  5643.0  761.06  5702.4  762.04  5761.8  762.69  5767.5  762.57
  5821.2  763.36  5826.9  763.19  5842.9  763.62  5870.4  763.73  5885.6  764.11
#Mann=3,-1,0
  4204.2    0.05       0  5134.7    0.03       0  5138.7    0.05       0
Bank Sta=5134.7,5138.7
Exp/Cntr=0.3,0.1

Type RM Length L Ch R = 1,1804,393,393,393
BEGIN DESCRIPTION:
Mapping XS 0891a3b7
END DESCRIPTION:
XS GIS Cut Line= 3
      1966324.09     13613046.59      1966295.44     13611952.87
      1966085.46     13611779.18
#Sta/Elev= 30
  4161.5  762.63  4233.1  761.98  4312.9  761.02  4317.9  761.18  4343.2  760.83
  4483.2  759.72  4533.2  759.10  4633.3  758.38  4923.4  757.40  4973.4  757.51
  5080.0  757.26  5085.0  757.45  5123.4  757.36  5259.4  756.69  5259.6  756.19
  5263.1  756.19  5263.4  756.69  5275.7  757.00  5282.2  756.97  5290.0  758.32
  5310.9  757.74  5318.7  758.01  5339.5  757.82  5353.9  757.96  5403.4  757.88
  5432.0  758.15  5481.5  758.19  5510.2  758.48  5516.7  758.39  5528.1  758.50
#Mann=3,-1,0
  4161.5    0.05       0  5259.4    0.03       0  5263.4    0.05       0
Bank Sta=5259.4,5263.4
Exp/Cntr=0.3,0.1

Type RM Length L Ch R = 1,1411,402,402,402
BEGIN DESCRIPTION:
Mapping XS e7a2ef47
END DESCRIPTION:
XS GIS Cut Line= 4
      1966464.72     13612921.61      1966665.23     13612606.51
      1966704.30     13611999.74      1966316.26     13611671.60
#Sta/Elev= 30
  4197.7  759.75  4288.5  758.37  4355.1  757.71  4433.9  756.69  4558.3  755.53
  4713.0  754.56  4913.4  754.07  5033.7  753.47  5131.9  752.20  5132.1  751.70
  5135.6  751.70  5135.9  752.20  5182.0  752.21  5210.4  752.52  5224.7  752.84
  5253.3  753.03  5274.1  752.94  5317.0  753.32  5401.6  753.69  5409.3  753.89
  5430.1  753.79  5466.4  753.93  5473.0  754.11  5493.9  754.13  5501.6  754.29
  5522.4  754.23  5530.2  754.46  5629.0  754.77  5643.3  755.05  5687.4  755.22
#Mann=3,-1,0
  4197.7    0.05       0  5131.9    0.03       0  5135.9    0.05       0
Bank Sta=5131.9,5135.9
Exp/Cntr=0.3,0.1

Type RM Length L Ch R = 1,1009,119,119,119
BEGIN DESCRIPTION:
UNT 121 in BCW 2.0
END DESCRIPTION:
XS GIS Cut Line= 4
      1966727.70     13612999.78      1966998.57     13612726.31
      1967053.25     13612241.93      1966631.37     13611726.29
#Sta/Elev= 30
  4263.5  757.25  4569.0  753.03  4663.0  752.15  4747.8  751.81  4752.9  751.61
  4871.1  751.33  4927.5  751.43  5042.2  751.10  5112.6  751.43  5139.7  751.27
  5160.5  751.48  5253.1  751.46  5281.8  751.08  5386.8  750.79  5387.0  750.29
  5390.5  750.29  5390.8  750.79  5395.2  750.94  5423.9  750.82  5459.1  750.98
  5487.8  750.82  5545.2  750.94  5551.7  751.09  5566.1  751.00  5609.1  751.44
  5615.6  751.72  5629.9  751.72  5636.4  751.96  5679.5  752.49  5802.1  752.50
#Mann=3,-1,0
  4263.5    0.05       0  5386.8    0.03       0  5390.8    0.05       0
Bank Sta=5386.8,5390.8
Exp/Cntr=0.3,0.1

Type RM Length L Ch R = 1,890,88,88,88
BEGIN DESCRIPTION:
Mapping XS 96904421
END DESCRIPTION:
XS GIS Cut Line= 5
      1966881.18     13612991.02      1967131.16     13612761.53
      1967134.63     13612086.18      1967063.45     13611962.92
      1966668.83     13611697.52
#Sta/Elev= 30
  4348.6  755.37  4391.1  754.63  4489.8  753.38  4638.9  751.89  4645.7  752.03
  4944.5  750.97  5144.5  750.73  5304.5  750.83  5334.5  750.56  5377.3  750.54
  5408.8  750.28  5414.6  750.46  5457.7  750.08  5473.5  750.17  5501.6  749.81
  5510.3  749.91  5567.3  749.40  5576.1  749.55  5601.3  749.33  5601.6  748.83
  5605.1  748.83  5605.3  749.33  5612.2  749.49  5654.3  749.53  5762.3  750.21
  5798.3  750.63  5805.0  750.93  5841.2  751.58  5921.3  752.54  5981.2  752.26
#Mann=3,-1,0
  4348.6    0.05       0  5601.3    0.03       0  5605.3    0.05       0
Bank Sta=5601.3,5605.3
Exp/Cntr=0.3,0.1

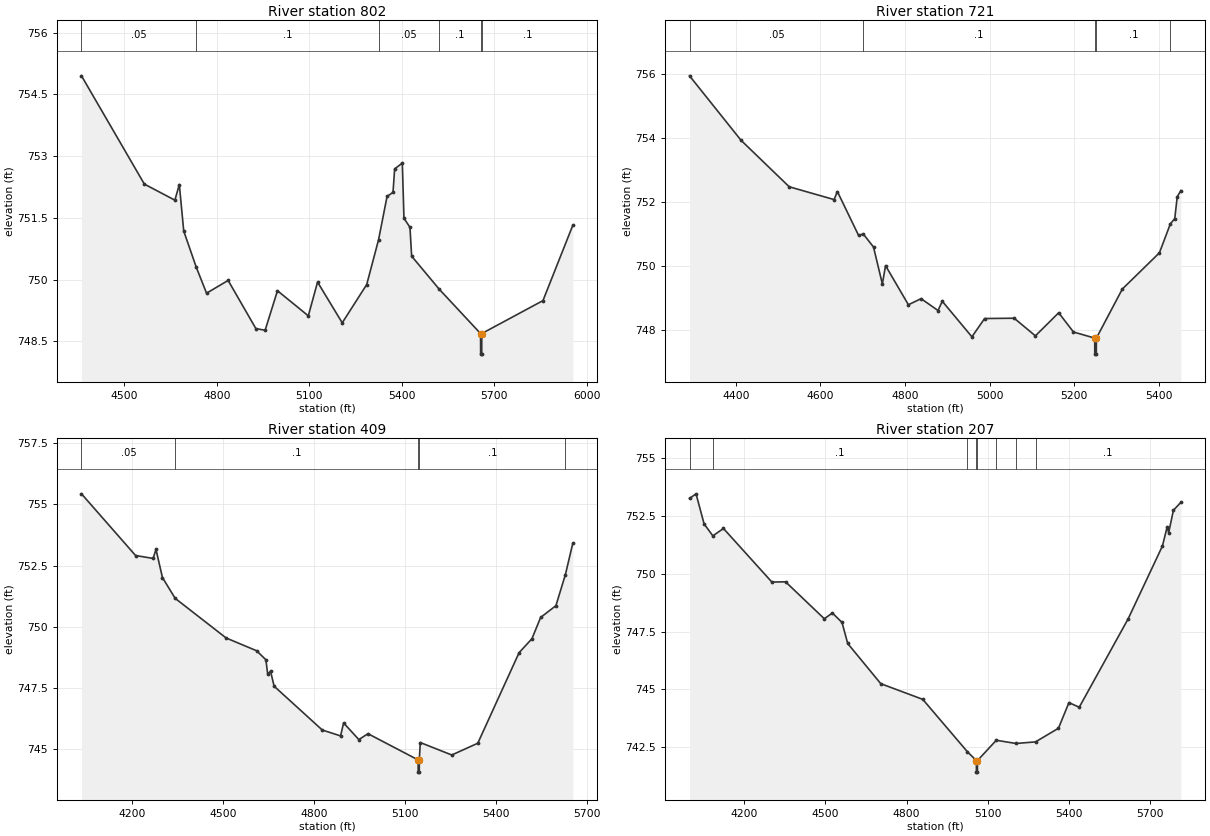
Type RM Length L Ch R = 1,802,81,81,81
BEGIN DESCRIPTION:
Mapping XS eb3baf2c
END DESCRIPTION:
XS GIS Cut Line= 6
      1966914.18     13612990.67      1967209.28     13612749.38
      1967207.55     13612223.34      1967068.66     13611855.28
      1966971.43     13611796.25      1966809.28     13611720.35
#Sta/Elev= 30
  4361.4  754.95  4565.3  752.32  4664.3  751.93  4678.7  752.31  4693.0  751.18
  4733.7  750.30  4767.0  749.67  4837.0  749.98  4927.0  748.81  4957.0  748.77
  4997.0  749.73  5097.0  749.12  5127.0  749.94  5207.0  748.95  5286.4  749.88
  5324.9  750.97  5352.4  752.02  5371.7  752.12  5377.0  752.69  5401.9  752.83
  5407.2  751.49  5426.7  751.27  5432.1  750.57  5521.2  749.77  5655.6  748.69
  5655.9  748.19  5659.4  748.19  5659.6  748.69  5858.0  749.49  5954.8  751.32
#Mann=6,-1,0
  4361.4    0.05       0  4733.7     0.1       0  5324.9    0.05       0
  5521.2     0.1       0  5655.6    0.07       0  5659.6     0.1       0
Bank Sta=5655.6,5659.6
Exp/Cntr=0.3,0.1

Type RM Length L Ch R = 1,721,312,312,312
BEGIN DESCRIPTION:
Mapping XS 2d214c45
END DESCRIPTION:
XS GIS Cut Line= 4
      1966878.79     13613038.79      1967274.61     13612731.51
      1967292.84     13612291.41      1967173.04     13612106.50
#Sta/Elev= 30
  4290.6  755.93  4412.4  753.92  4526.3  752.47  4632.5  752.07  4640.3  752.32
  4690.5  750.95  4701.3  751.00  4725.7  750.59  4746.6  749.44  4754.2  750.01
  4808.2  748.79  4838.2  748.98  4878.3  748.61  4888.3  748.90  4958.4  747.79
  4988.4  748.36  5058.4  748.37  5108.5  747.82  5163.6  748.54  5198.6  747.94
  5248.8  747.75  5249.0  747.25  5252.5  747.25  5252.8  747.75  5314.1  749.28
  5401.8  750.41  5427.6  751.31  5438.1  751.48  5444.0  752.16  5452.5  752.35
#Mann=5,-1,0
  4290.6    0.05       0  4701.3     0.1       0  5248.8    0.07       0
  5252.8     0.1       0  5427.6    0.05       0
Bank Sta=5248.8,5252.8
Exp/Cntr=0.3,0.1

Type RM Length L Ch R = 1,409,202,202,202
BEGIN DESCRIPTION:
Mapping XS 692517c8
END DESCRIPTION:
XS GIS Cut Line= 4
      1966943.89     13613101.30      1967605.34     13612692.45
      1967568.88     13612346.10      1967165.27     13612057.06
#Sta/Elev= 30
  4032.3  755.43  4210.9  752.91  4268.8  752.79  4278.3  753.16  4299.6  752.01
  4341.6  751.16  4510.0  749.54  4610.4  749.02  4641.2  748.65  4647.1  748.07
  4656.6  748.18  4668.4  747.57  4827.4  745.78  4887.8  745.54  4897.8  746.07
  4948.1  745.39  4978.3  745.63  5143.8  744.56  5144.1  744.06  5147.6  744.06
  5147.8  744.56  5150.9  745.27  5254.9  744.76  5340.8  745.24  5477.2  748.94
  5519.6  749.51  5548.4  750.38  5598.8  750.86  5630.1  752.13  5654.6  753.41
#Mann=5,-1,0
  4032.3    0.05       0  4341.6     0.1       0  5143.8    0.07       0
  5147.8     0.1       0  5630.1    0.05       0
Bank Sta=5143.8,5147.8
Exp/Cntr=0.3,0.1

Type RM Length L Ch R = 1,207,0,0,0
BEGIN DESCRIPTION:
UNT 121 in BCW 1.0
END DESCRIPTION:
XS GIS Cut Line= 4
      1967139.16     13613103.06      1967778.08     13612658.60
      1967774.61     13612281.86      1967172.98     13612009.65
#Sta/Elev= 30
  3997.6  753.27  4021.7  753.47  4051.4  752.17  4083.8  751.65  4123.0  751.97
  4301.9  749.65  4352.5  749.66  4495.7  748.06  4525.4  748.31  4561.1  747.90
  4582.1  746.99  4704.3  745.25  4859.5  744.57  5024.5  742.30  5057.5  741.92
  5057.8  741.42  5061.3  741.42  5061.5  741.92  5131.1  742.80  5204.0  742.66
  5276.1  742.73  5360.8  743.32  5399.5  744.43  5437.6  744.23  5618.4  748.06
  5744.9  751.21  5762.5  752.04  5768.0  751.79  5785.6  752.76  5813.0  753.10
#Mann=8,-1,0
  3997.6    0.05       0  4083.8     0.1       0  5024.5    0.16       0
  5057.5    0.07       0  5061.5    0.16       0  5131.1     0.1       0
  5204.0    0.16       0  5276.1     0.1       0
Bank Sta=5057.5,5061.5
Exp/Cntr=0.3,0.1

Chan Stop Cuts=-1