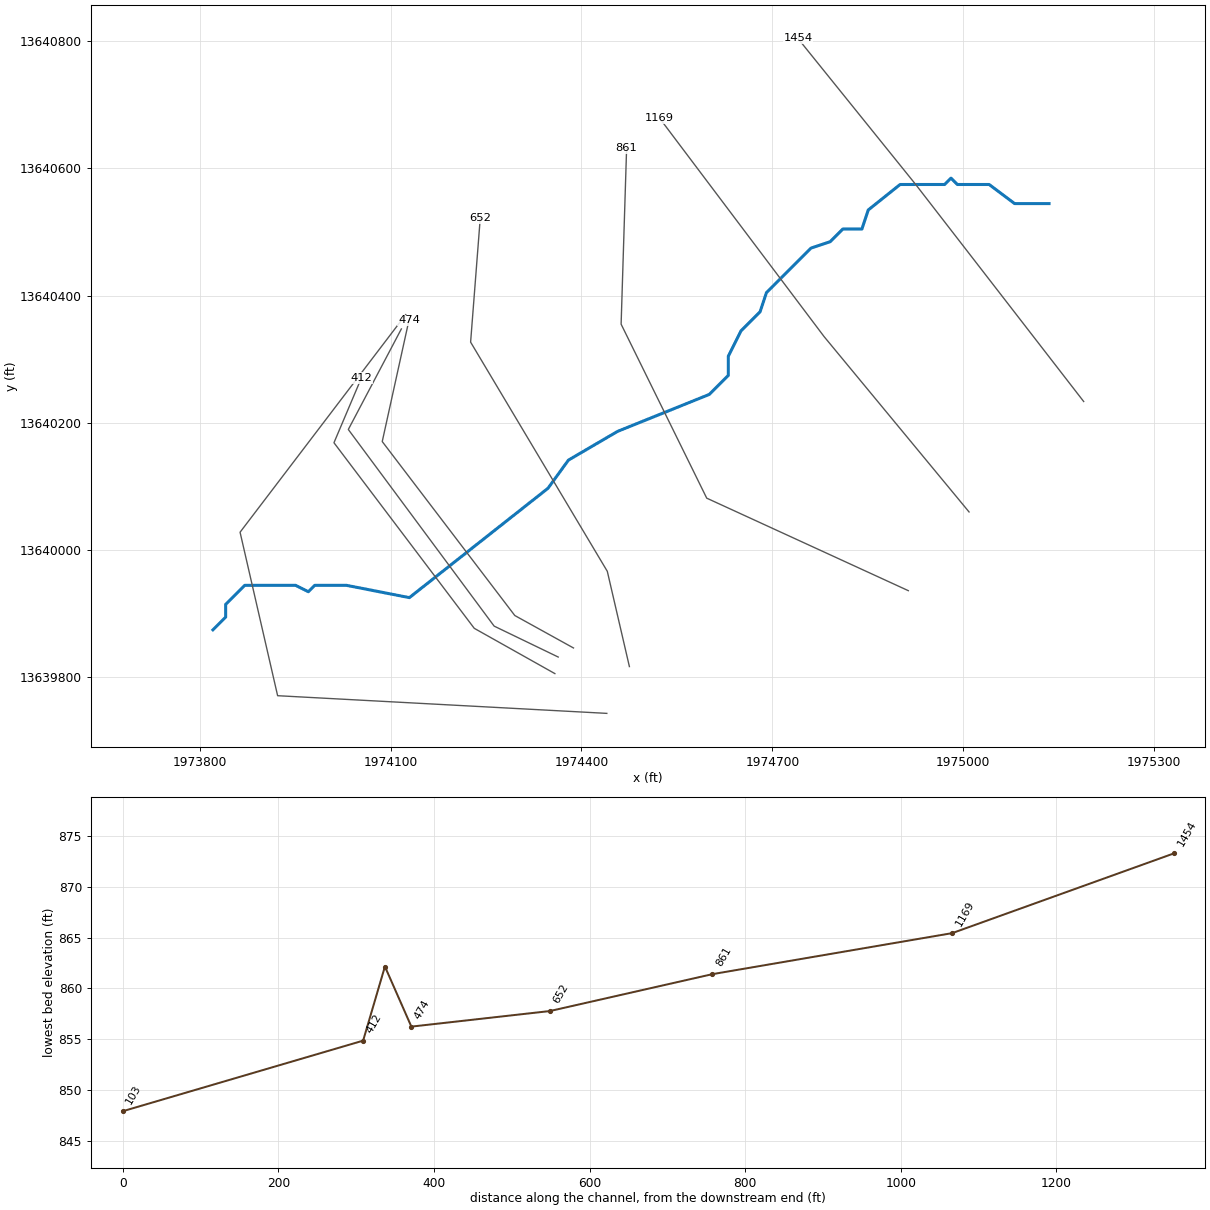
--- UNT 122 in BCW.prj (project) ---

Proj Title=UNT 122 in BCW Base Level Engineering
Current Plan=p01
Default Exp/Contr=0.3,0.1
English Units
Geom File=g01
Flow File=f01
Plan File=p01
BEGIN DESCRIPTION:
UNT 122 in BCW
END DESCRIPTION:

--- UNT 122 in BCW.p01 (plan) ---

Plan Title=Multiple Run
Short Identifier=Multiple
Geom File=g01
Flow File=f01
Subcritical Flow
K Sum by GR= 0
Std Step Tol= 0.01
Critical Tol= 0.01
Num of Std Step Trials= 20
Max Error Tol= 0.3
Flow Tol Ratio= 0.001
Split Flow NTrial= 30
Split Flow Tol= 0.02
Split Flow Ratio= 0.02
Log Output Level= 0
Friction Slope Method= 1
Unsteady Friction Slope Method= 2
Unsteady Bridges Friction Slope Method= 1
Parabolic Critical Depth
Global Vel Dist=  1 , 1 , 1
Global Log Level= 0
CheckData=True
Encroach Param= -1, 0, 0, 0
BEGIN DESCRIPTION:
Multiple Run
END DESCRIPTION:

--- UNT 122 in BCW.f01 (steady flow) ---

Flow Title=Multiple
Number of Profiles=7
Profile Names=10-year,25-year,50-year,1pct_min,100-year,1pct_plu,500-year
River Rch & RM= UNT 122 in BCW,Reach-1,1454
     240     320     383     228     456     909     645
Boundary for River Rch & Prof#=UNT 122 in BCW,Reach-1,1
Up Type=0
Dn Type=3
Dn Slope=0.005
Boundary for River Rch & Prof#=UNT 122 in BCW,Reach-1,2
Up Type=0
Dn Type=3
Dn Slope=0.005
Boundary for River Rch & Prof#=UNT 122 in BCW,Reach-1,3
Up Type=0
Dn Type=3
Dn Slope=0.005
Boundary for River Rch & Prof#=UNT 122 in BCW,Reach-1,4
Up Type=0
Dn Type=3
Dn Slope=0.005
Boundary for River Rch & Prof#=UNT 122 in BCW,Reach-1,5
Up Type=0
Dn Type=3
Dn Slope=0.005
Boundary for River Rch & Prof#=UNT 122 in BCW,Reach-1,6
Up Type=0
Dn Type=3
Dn Slope=0.005
Boundary for River Rch & Prof#=UNT 122 in BCW,Reach-1,7
Up Type=0
Dn Type=3
Dn Slope=0.005

--- UNT 122 in BCW.g01 (geometry) ---

Geom Title=Existing Conditions

River Reach=UNT 122 in BCW,Reach-1
Reach XY= 30
      1975134.89     13640544.54      1975080.80     13640544.54
      1975040.80     13640574.54      1974990.80     13640574.54
      1974980.80     13640584.54      1974970.80     13640574.54
      1974900.80     13640574.54      1974850.80     13640534.54
      1974840.80     13640504.54      1974810.80     13640504.54
      1974790.80     13640484.54      1974760.80     13640474.54
      1974690.80     13640404.54      1974680.80     13640374.54
      1974650.80     13640344.54      1974630.80     13640304.54
      1974630.80     13640274.54      1974600.80     13640244.54
      1974456.82     13640186.51      1974379.57     13640141.37
      1974347.45     13640097.10      1974129.57     13639925.23
      1974030.80     13639944.54      1973980.80     13639944.54
      1973970.80     13639934.54      1973950.80     13639944.54
      1973870.80     13639944.54      1973840.80     13639914.54
      1973840.80     13639894.54      1973820.80     13639874.54

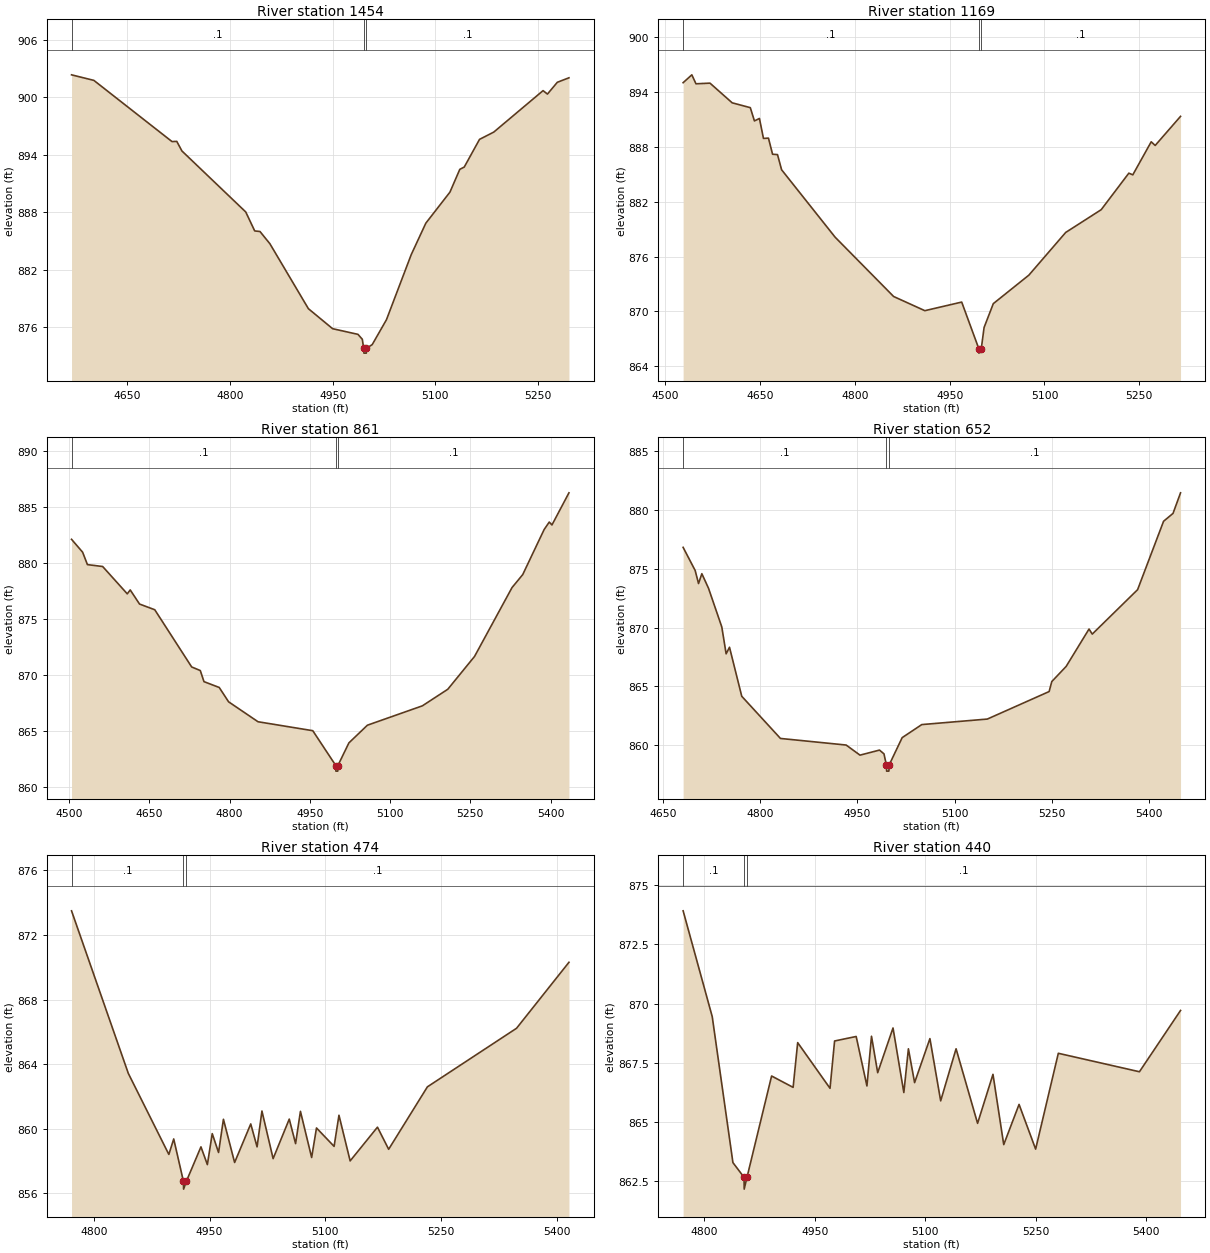
Type RM Length L Ch R = 1,1454,285,285,285
BEGIN DESCRIPTION:
UNT 122 in BCW 3.0
END DESCRIPTION:
XS GIS Cut Line= 3
      1975189.36     13640233.48      1974925.00     13640575.00
      1974740.12     13640804.26
#Sta/Elev= 30
  4568.7  902.34  4601.3  901.76  4715.4  895.37  4722.4  895.39  4729.9  894.39
  4823.1  888.02  4836.2  886.04  4843.9  885.98  4858.4  884.70  4914.6  877.92
  4950.0  875.83  4987.0  875.24  4993.3  874.73  4995.4  873.78  4995.7  873.28
  4999.2  873.28  4999.4  873.78  5007.8  874.17  5028.6  876.77  5064.8  883.57
  5086.1  886.85  5121.3  890.09  5135.7  892.47  5142.2  892.71  5164.5  895.60
  5185.3  896.36  5257.3  900.69  5263.7  900.33  5278.1  901.56  5295.1  902.03
#Mann=3,-1,0
  4568.7     0.1       0  4995.4    0.07       0  4999.4     0.1       0
Bank Sta=4995.4,4999.4
Exp/Cntr=0.3,0.1

Type RM Length L Ch R = 1,1169,308,308,308
BEGIN DESCRIPTION:
UNT 122 in BCW 2.0
END DESCRIPTION:
XS GIS Cut Line= 3
      1975009.24     13640059.87      1974781.38     13640335.48
      1974523.11     13640678.39
#Sta/Elev= 30
  4528.4  895.00  4542.2  895.86  4548.7  894.88  4570.9  894.95  4606.0  892.80
  4634.7  892.27  4641.2  890.82  4649.1  891.09  4655.5  888.91  4663.4  888.94
  4669.9  887.18  4677.7  887.14  4684.2  885.48  4768.9  878.11  4861.4  871.63
  4910.8  870.08  4969.1  871.02  4996.1  865.94  4996.3  865.44  5000.1  865.94
  5004.5  868.24  5019.1  870.85  5075.3  873.96  5133.6  878.63  5189.8  881.12
  5233.5  885.11  5239.8  884.93  5268.9  888.54  5275.2  888.14  5315.3  891.32
#Mann=3,-1,0
  4528.4     0.1       0  4996.1    0.07       0  5000.1     0.1       0
Bank Sta=4996.1,5000.1
Exp/Cntr=0.3,0.1

Type RM Length L Ch R = 1,861,209,209,209
BEGIN DESCRIPTION:
Mapping XS 1ef43f65
END DESCRIPTION:
XS GIS Cut Line= 4
      1974913.78     13639936.16      1974596.92     13640081.57
      1974462.37     13640355.01      1974471.00     13640631.38
#Sta/Elev= 30
  4504.5  882.11  4525.2  880.96  4534.2  879.85  4562.7  879.68  4608.7  877.24
  4614.2  877.59  4631.6  876.33  4660.1  875.82  4729.1  870.71  4745.2  870.39
  4752.1  869.40  4780.6  868.88  4798.1  867.60  4853.1  865.82  4955.5  865.02
  4998.5  861.91  4998.7  861.41  5002.2  861.41  5002.5  861.91  5023.0  863.93
  5057.6  865.51  5160.4  867.24  5207.9  868.72  5257.9  871.65  5328.0  877.80
  5348.0  878.96  5388.0  882.98  5397.6  883.65  5402.6  883.39  5434.4  886.26
#Mann=3,-1,0
  4504.5     0.1       0  4998.5    0.07       0  5002.5     0.1       0
Bank Sta=4998.5,5002.5
Exp/Cntr=0.3,0.1

Type RM Length L Ch R = 1,652,178,178,178
BEGIN DESCRIPTION:
Mapping XS fa36e492
END DESCRIPTION:
XS GIS Cut Line= 4
      1974475.38     13639816.86      1974440.67     13639966.55
      1974225.82     13640326.79      1974240.93     13640521.10
#Sta/Elev= 30
  4680.8  876.82  4699.4  874.85  4704.6  873.74  4709.7  874.58  4720.0  873.34
  4740.5  870.05  4747.2  867.76  4752.4  868.32  4771.3  864.15  4831.1  860.56
  4932.5  860.00  4953.9  859.14  4984.0  859.57  4990.9  859.25  4994.7  858.28
  4995.0  857.78  4998.5  857.78  4998.7  858.28  5019.0  860.63  5049.3  861.74
  5150.5  862.21  5245.9  864.55  5250.0  865.40  5272.2  866.69  5307.5  869.87
  5312.5  869.44  5382.5  873.22  5422.6  879.04  5437.2  879.71  5448.8  881.46
#Mann=3,-1,0
  4680.8     0.1       0  4994.7    0.07       0  4998.7     0.1       0
Bank Sta=4994.7,4998.7
Exp/Cntr=0.3,0.1

Type RM Length L Ch R = 1,474,34,34,34
BEGIN DESCRIPTION:
Mapping XS 888c7a0b
END DESCRIPTION:
XS GIS Cut Line= 4
      1974387.49     13639846.11      1974295.27     13639897.11
      1974086.93     13640170.54      1974128.97     13640361.33
#Sta/Elev= 30
  4771.2  873.50  4844.8  863.42  4897.3  858.40  4903.6  859.36  4916.1  856.75
  4916.4  856.25  4920.1  856.75  4938.9  858.87  4947.2  857.77  4953.5  859.69
  4961.7  858.52  4968.0  860.58  4982.5  857.90  5003.4  860.29  5011.6  858.87
  5017.9  861.09  5032.4  858.14  5053.3  860.59  5061.5  859.07  5067.8  861.07
  5082.3  858.21  5088.6  860.04  5111.4  858.90  5117.7  860.83  5132.2  858.00
  5167.6  860.09  5182.1  858.72  5232.3  862.59  5347.8  866.22  5415.7  870.31
#Mann=3,-1,0
  4771.2     0.1       0  4916.1    0.07       0  4920.1     0.1       0
Bank Sta=4916.1,4920.1
Exp/Cntr=0.3,0.1

Type RM Length L Ch R = 1,440,28,28,28
BEGIN DESCRIPTION:
Mapping XS 0d49b080
END DESCRIPTION:
XS GIS Cut Line= 4
      1974363.48     13639831.86      1974262.79     13639880.47
      1974033.62     13640189.50      1974116.97     13640347.52
#Sta/Elev= 30
  4771.4  873.92  4810.9  869.45  4839.0  863.28  4854.1  862.66  4854.3  862.16
  4858.1  862.66  4891.5  866.94  4920.7  866.46  4926.9  868.35  4970.8  866.42
  4977.0  868.42  5006.3  868.61  5020.9  866.52  5027.1  868.62  5035.5  867.08
  5056.3  868.97  5071.0  866.24  5077.2  868.09  5085.6  866.66  5106.4  868.52
  5121.0  865.89  5141.9  868.09  5171.1  864.94  5192.0  867.01  5206.6  864.04
  5227.4  865.74  5249.9  863.85  5280.7  867.90  5390.8  867.12  5446.6  869.71
#Mann=3,-1,0
  4771.4     0.1       0  4854.1    0.07       0  4858.1     0.1       0
Bank Sta=4854.1,4858.1
Exp/Cntr=0.3,0.1

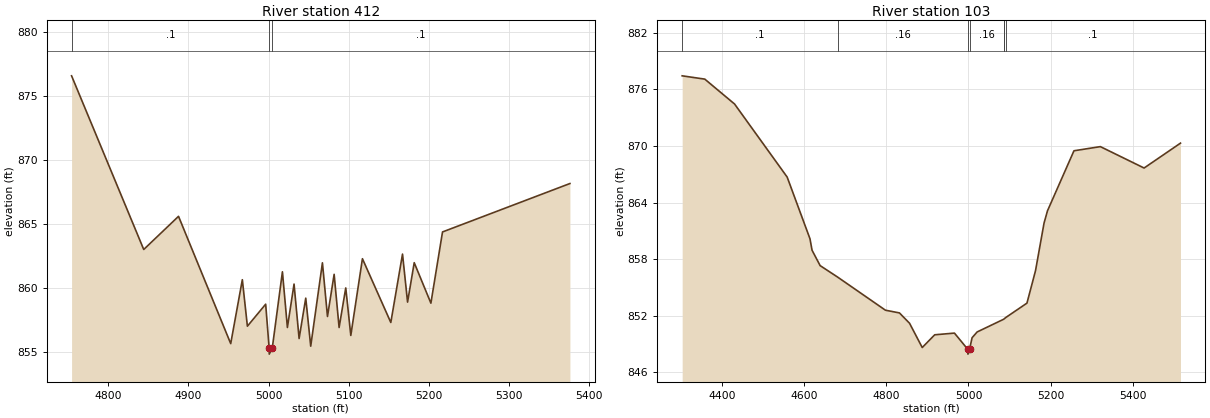
Type RM Length L Ch R = 1,412,309,309,309
BEGIN DESCRIPTION:
Mapping XS 1f043ace
END DESCRIPTION:
XS GIS Cut Line= 4
      1974358.27     13639805.82      1974231.54     13639877.00
      1974011.05     13640168.66      1974054.21     13640270.52
#Sta/Elev= 30
  4754.2  876.60  4844.2  863.04  4887.6  865.63  4952.7  855.69  4967.2  860.68
  4973.5  857.05  4996.3  858.77  5000.6  855.37  5000.8  854.87  5004.6  855.37
  5017.2  861.30  5023.4  856.95  5031.7  860.34  5038.0  856.09  5046.3  859.24
  5052.5  855.49  5067.1  862.00  5073.4  857.81  5081.7  861.10  5087.9  856.95
  5096.2  860.04  5102.5  856.33  5117.0  862.32  5152.4  857.34  5167.0  862.68
  5173.3  858.93  5181.6  862.01  5202.4  858.85  5216.9  864.41  5375.8  868.19
#Mann=3,-1,0
  4754.2     0.1       0  5000.6    0.07       0  5004.6     0.1       0
Bank Sta=5000.6,5004.6
Exp/Cntr=0.3,0.1

Type RM Length L Ch R = 1,103,0,0,0
BEGIN DESCRIPTION:
UNT 122 in BCW 1.0
END DESCRIPTION:
XS GIS Cut Line= 4
      1974439.90     13639743.31      1973922.51     13639771.09
      1973863.48     13640028.04      1974123.87     13640370.01
#Sta/Elev= 30
  4303.9  877.45  4358.9  877.10  4431.3  874.46  4559.2  866.71  4614.7  860.16
  4619.7  858.95  4639.3  857.32  4682.6  856.08  4798.1  852.59  4832.2  852.30
  4856.8  851.20  4887.6  848.63  4917.9  849.98  4965.9  850.16  4998.5  848.43
  4998.7  847.93  5002.5  848.43  5008.8  849.67  5021.0  850.28  5085.6  851.63
  5086.2  851.65  5090.6  851.81  5142.2  853.34  5163.0  856.78  5183.8  861.84
  5192.1  863.13  5256.5  869.50  5320.7  869.94  5427.0  867.67  5515.5  870.31
#Mann=7,-1,0
  4303.9     0.1       0  4682.6    0.16       0  4998.5    0.07       0
  5002.5    0.16       0  5085.6     0.1       0  5086.2    0.16       0
  5090.6     0.1       0
Bank Sta=4998.5,5002.5
Exp/Cntr=0.3,0.1

Chan Stop Cuts=-1