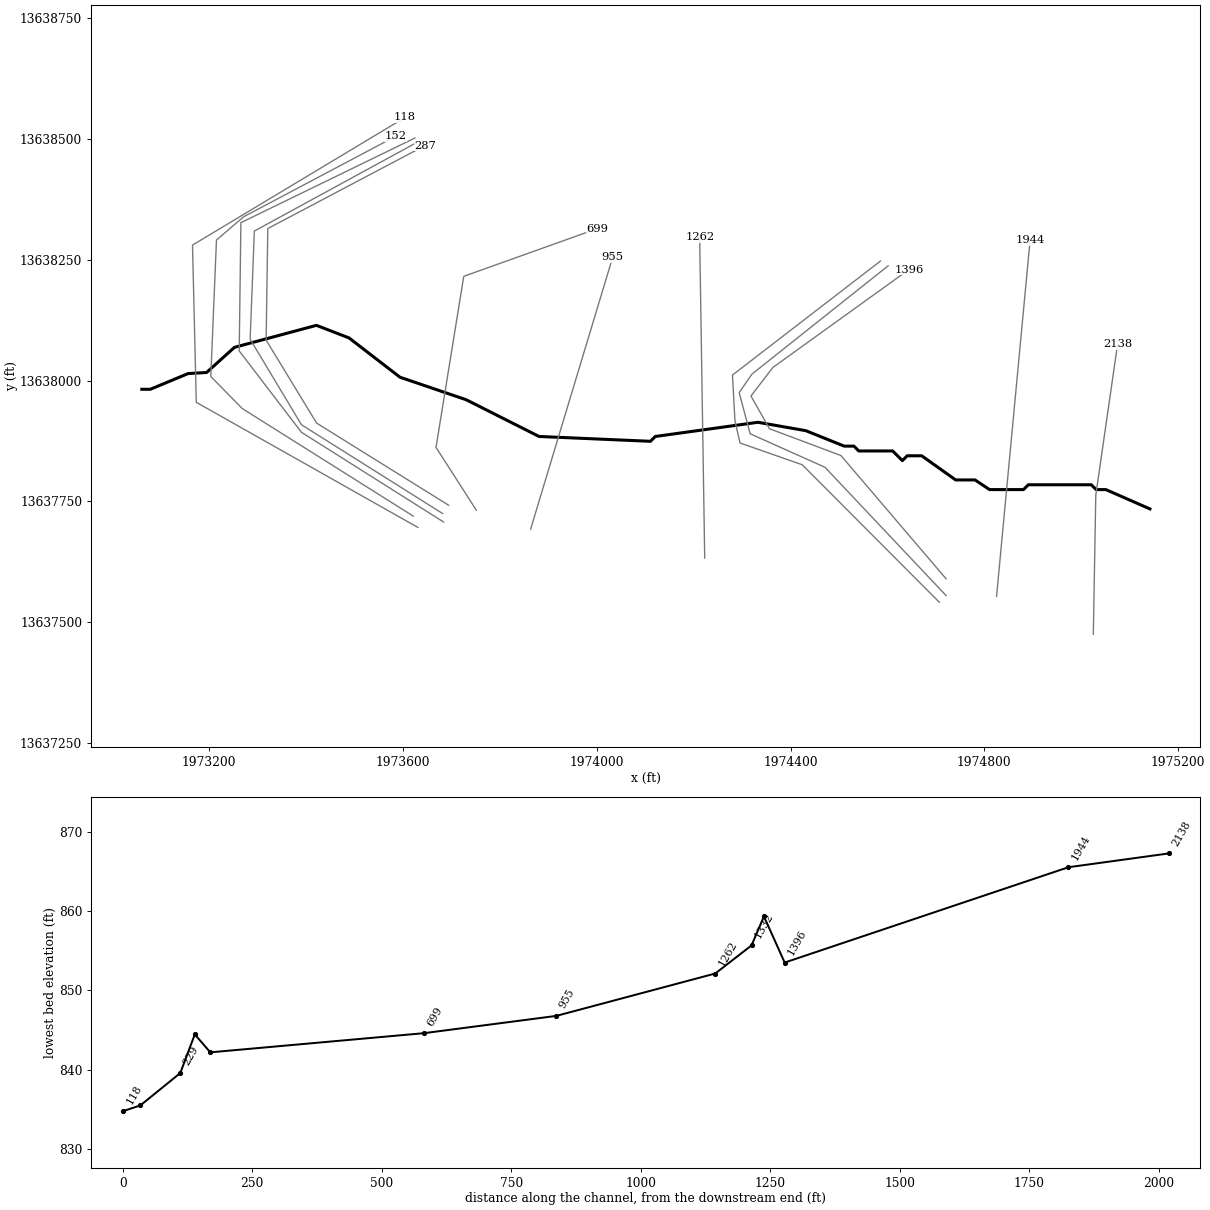
--- UNT 123 in BCW.prj (project) ---

Proj Title=UNT 123 in BCW Base Level Engineering
Current Plan=p01
Default Exp/Contr=0.3,0.1
English Units
Geom File=g01
Flow File=f01
Plan File=p01
BEGIN DESCRIPTION:
UNT 123 in BCW
END DESCRIPTION:

--- UNT 123 in BCW.p01 (plan) ---

Plan Title=Multiple Run
Short Identifier=Multiple
Geom File=g01
Flow File=f01
Subcritical Flow
K Sum by GR= 0
Std Step Tol= 0.01
Critical Tol= 0.01
Num of Std Step Trials= 20
Max Error Tol= 0.3
Flow Tol Ratio= 0.001
Split Flow NTrial= 30
Split Flow Tol= 0.02
Split Flow Ratio= 0.02
Log Output Level= 0
Friction Slope Method= 1
Unsteady Friction Slope Method= 2
Unsteady Bridges Friction Slope Method= 1
Parabolic Critical Depth
Global Vel Dist=  1 , 1 , 1
Global Log Level= 0
CheckData=True
Encroach Param= -1, 0, 0, 0
BEGIN DESCRIPTION:
Multiple Run
END DESCRIPTION:

--- UNT 123 in BCW.f01 (steady flow) ---

Flow Title=Multiple
Number of Profiles=7
Profile Names=10-year,25-year,50-year,1pct_min,100-year,1pct_plu,500-year
River Rch & RM= UNT 123 in BCW,Reach-1,2138
     241     321     385     229     458     913     647
Boundary for River Rch & Prof#=UNT 123 in BCW,Reach-1,1
Up Type=0
Dn Type=3
Dn Slope=0.005
Boundary for River Rch & Prof#=UNT 123 in BCW,Reach-1,2
Up Type=0
Dn Type=3
Dn Slope=0.005
Boundary for River Rch & Prof#=UNT 123 in BCW,Reach-1,3
Up Type=0
Dn Type=3
Dn Slope=0.005
Boundary for River Rch & Prof#=UNT 123 in BCW,Reach-1,4
Up Type=0
Dn Type=3
Dn Slope=0.005
Boundary for River Rch & Prof#=UNT 123 in BCW,Reach-1,5
Up Type=0
Dn Type=3
Dn Slope=0.005
Boundary for River Rch & Prof#=UNT 123 in BCW,Reach-1,6
Up Type=0
Dn Type=3
Dn Slope=0.005
Boundary for River Rch & Prof#=UNT 123 in BCW,Reach-1,7
Up Type=0
Dn Type=3
Dn Slope=0.005

--- UNT 123 in BCW.g01 (geometry) ---

Geom Title=Existing Conditions

River Reach=UNT 123 in BCW,Reach-1
Reach XY= 30
      1975141.83     13637734.54      1975050.80     13637774.54
      1975030.80     13637774.54      1975020.80     13637784.54
      1974890.80     13637784.54      1974880.80     13637774.54
      1974810.80     13637774.54      1974780.80     13637794.54
      1974740.80     13637794.54      1974670.80     13637844.54
      1974640.80     13637844.54      1974630.80     13637834.54
      1974610.80     13637854.54      1974540.80     13637854.54
      1974530.80     13637864.54      1974510.80     13637864.54
      1974431.43     13637896.55      1974332.69     13637913.91
      1974120.80     13637884.54      1974110.80     13637874.54
      1973880.80     13637884.54      1973730.48     13637960.57
      1973593.76     13638007.23      1973488.51     13638088.61
      1973421.23     13638114.65      1973251.96     13638069.08
      1973194.45     13638016.99      1973156.48     13638014.82
      1973078.35     13637982.27      1973060.80     13637982.27

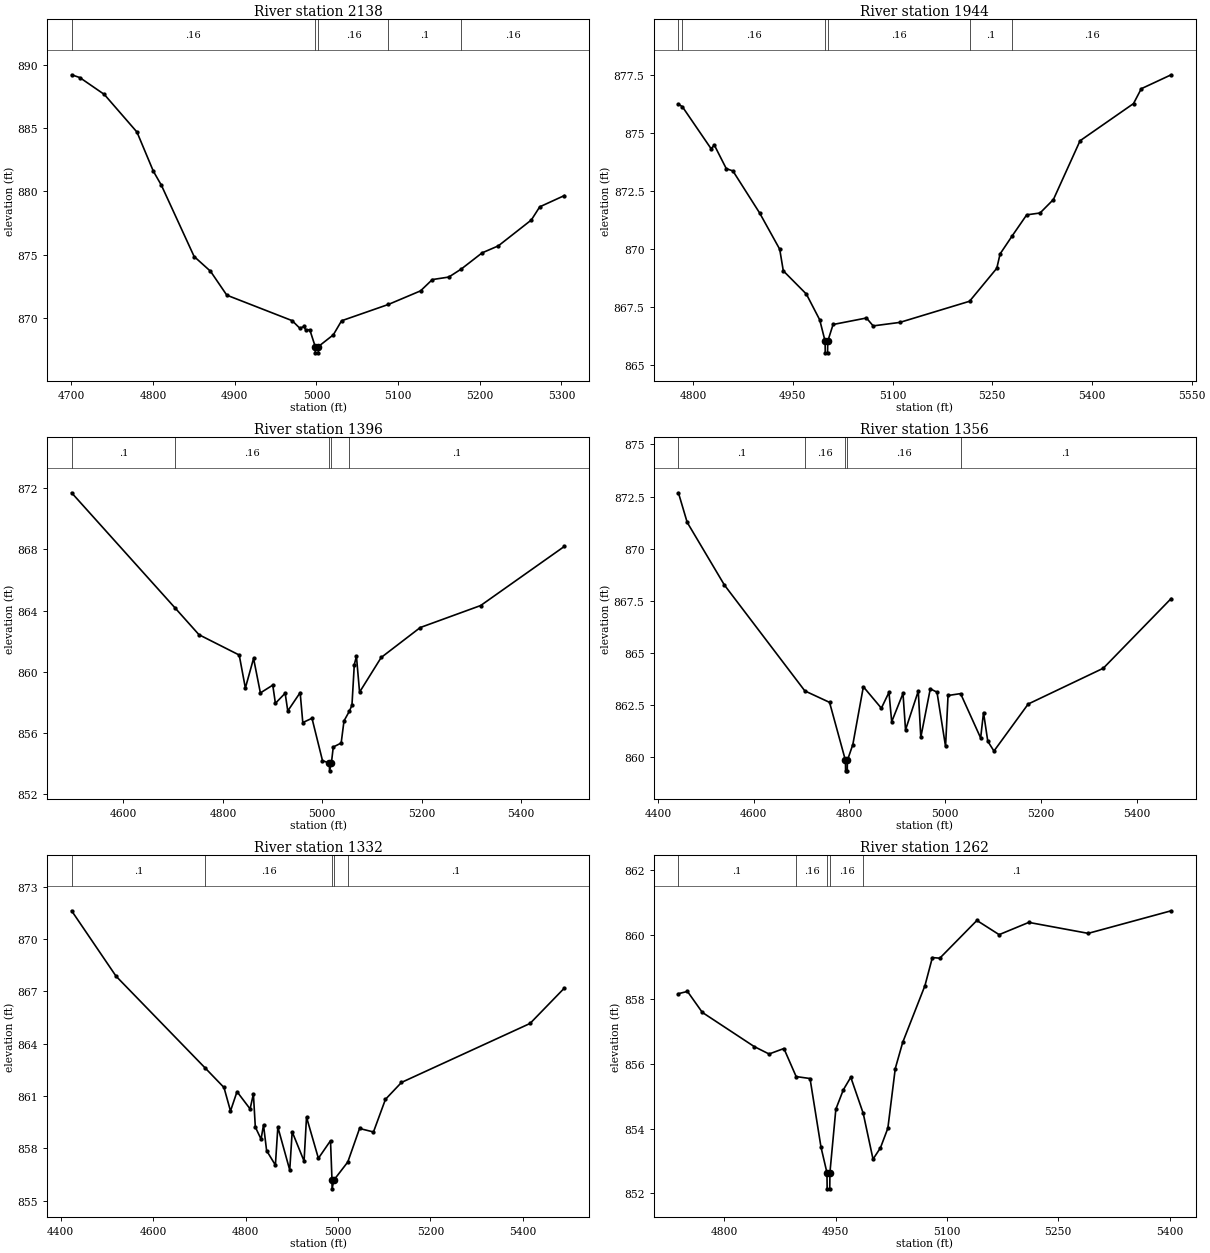
Type RM Length L Ch R = 1,2138,194,194,194
BEGIN DESCRIPTION:
UNT 123 in BCW 3.0
END DESCRIPTION:
XS GIS Cut Line= 3
      1975025.00     13637475.00      1975030.08     13637762.99
      1975075.01     13638075.04
#Sta/Elev= 30
  4700.3  889.20  4710.3  888.98  4740.3  887.65  4780.3  884.68  4800.3  881.60
  4810.3  880.47  4850.3  874.86  4870.3  873.70  4890.3  871.81  4970.3  869.80
  4979.7  869.20  4984.7  869.34  4986.8  869.08  4991.9  869.08  4998.5  867.76
  4998.7  867.26  5002.2  867.26  5002.5  867.76  5020.7  868.68  5030.8  869.79
  5088.2  871.08  5127.5  872.15  5141.9  873.04  5162.1  873.24  5177.5  873.88
  5202.9  875.15  5222.7  875.70  5263.1  877.74  5273.4  878.78  5303.6  879.67
#Mann=5,-1,0
  4700.3    0.16       0  4998.5    0.07       0  5002.5    0.16       0
  5088.2     0.1       0  5177.5    0.16       0
Bank Sta=4998.5,5002.5
Exp/Cntr=0.3,0.1

Type RM Length L Ch R = 1,1944,548,548,548
BEGIN DESCRIPTION:
Mapping XS 4345a71b
END DESCRIPTION:
XS GIS Cut Line= 2
      1974825.21     13637553.31      1974894.52     13638291.46
#Sta/Elev= 30
  4777.8  876.23  4783.9  876.11  4826.9  874.31  4831.9  874.46  4849.8  873.45
  4859.8  873.35  4900.0  871.54  4930.2  869.98  4935.6  869.05  4970.3  868.05
  4990.4  866.94  4998.5  866.02  4998.7  865.52  5002.2  865.52  5002.5  866.02
  5010.5  866.74  5060.7  867.02  5070.8  866.68  5110.9  866.83  5215.8  867.74
  5256.8  869.16  5261.8  869.78  5280.1  870.56  5301.8  871.46  5321.9  871.54
  5342.0  872.12  5382.1  874.65  5462.5  876.25  5474.2  876.89  5519.2  877.49
#Mann=6,-1,0
  4777.8     0.1       0  4783.9    0.16       0  4998.5    0.07       0
  5002.5    0.16       0  5215.8     0.1       0  5280.1    0.16       0
Bank Sta=4998.5,5002.5
Exp/Cntr=0.3,0.1

Type RM Length L Ch R = 1,1396,40,40,40
BEGIN DESCRIPTION:
Mapping XS fbc48ec8
END DESCRIPTION:
XS GIS Cut Line= 6
      1974721.02     13637589.85      1974504.03     13637845.02
      1974356.46     13637900.58      1974318.27     13637968.29
      1974363.41     13638027.32      1974644.33     13638230.20
#Sta/Elev= 30
  4495.7  871.71  4704.4  864.15  4751.9  862.42  4832.8  861.09  4845.2  858.93
  4861.7  860.87  4875.4  858.61  4900.3  859.12  4905.6  857.93  4925.2  858.59
  4930.5  857.43  4955.4  858.63  4960.7  856.67  4979.2  856.95  5000.3  854.18
  5014.2  854.01  5014.5  853.51  5018.2  854.01  5022.0  855.07  5037.9  855.33
  5043.6  856.78  5054.5  857.42  5059.6  857.81  5064.3  860.46  5068.6  861.01
  5074.9  858.66  5118.4  860.93  5197.0  862.89  5318.5  864.33  5486.9  868.20
#Mann=5,-1,0
  4495.7     0.1       0  4704.4    0.16       0  5014.2    0.07       0
  5018.2    0.16       0  5054.5     0.1       0
Bank Sta=5014.2,5018.2
Exp/Cntr=0.3,0.1

Type RM Length L Ch R = 1,1356,24,24,24
BEGIN DESCRIPTION:
Mapping XS 8a544e44
END DESCRIPTION:
XS GIS Cut Line= 6
      1974721.07     13637555.07      1974471.05     13637820.72
      1974316.53     13637890.16      1974293.96     13637975.23
      1974320.01     13638013.43      1974601.47     13638237.91
#Sta/Elev= 30
  4443.0  872.68  4461.3  871.26  4539.0  868.25  4707.1  863.16  4758.7  862.61
  4791.9  859.82  4792.2  859.32  4795.7  859.32  4795.9  859.82  4807.3  860.58
  4829.3  863.36  4866.9  862.33  4882.8  863.09  4888.5  861.68  4912.1  863.04
  4917.4  861.29  4944.0  863.15  4949.3  860.93  4969.1  863.26  4983.1  863.10
  5001.0  860.49  5006.2  862.94  5032.4  863.03  5074.3  860.90  5080.3  862.12
  5089.2  860.74  5102.1  860.27  5173.6  862.53  5330.5  864.25  5472.3  867.60
#Mann=5,-1,0
  4443.0     0.1       0  4707.1    0.16       0  4791.9    0.07       0
  4795.9    0.16       0  5032.4     0.1       0
Bank Sta=4791.9,4795.9
Exp/Cntr=0.3,0.1

Type RM Length L Ch R = 1,1332,70,70,70
BEGIN DESCRIPTION:
Mapping XS c6052a53
END DESCRIPTION:
XS GIS Cut Line= 6
      1974707.13     13637541.24      1974424.17     13637825.93
      1974295.70     13637871.07      1974285.28     13637916.20
      1974280.08     13638011.69      1974585.66     13638247.82
#Sta/Elev= 30
  4423.9  871.61  4520.0  867.86  4713.0  862.59  4753.4  861.48  4767.5  860.13
  4781.6  861.24  4809.9  860.25  4817.0  861.11  4821.2  859.21  4833.6  858.52
  4838.9  859.33  4845.6  857.86  4864.6  857.03  4869.9  859.21  4895.6  856.75
  4900.9  858.94  4926.6  857.26  4931.9  859.78  4957.6  857.42  4983.8  858.43
  4987.0  856.17  4987.2  855.67  4991.0  856.17  5021.2  857.21  5046.6  859.13
  5076.7  858.93  5102.6  860.80  5137.3  861.77  5415.3  865.15  5489.6  867.18
#Mann=5,-1,0
  4423.9     0.1       0  4713.0    0.16       0  4987.0    0.07       0
  4991.0    0.16       0  5021.2     0.1       0
Bank Sta=4987,4991
Exp/Cntr=0.3,0.1

Type RM Length L Ch R = 1,1262,307,307,307
BEGIN DESCRIPTION:
Mapping XS c8ec9391
END DESCRIPTION:
XS GIS Cut Line= 2
      1974222.78     13637632.78      1974212.37     13638296.90
#Sta/Elev= 30
  4738.0  858.18  4750.2  858.25  4770.2  857.60  4840.2  856.54  4860.2  856.31
  4880.2  856.48  4896.7  855.61  4915.4  855.55  4930.2  853.42  4938.2  852.63
  4938.5  852.13  4942.0  852.13  4942.2  852.63  4950.2  854.60  4960.3  855.20
  4970.3  855.59  4987.1  854.47  5000.3  853.05  5010.3  853.40  5020.3  854.01
  5030.3  855.86  5040.3  856.67  5070.3  858.43  5080.3  859.30  5090.3  859.28
  5140.3  860.45  5170.3  860.01  5210.3  860.39  5290.3  860.05  5402.2  860.75
#Mann=5,-1,0
  4738.0     0.1       0  4896.7    0.16       0  4938.2    0.07       0
  4942.2    0.16       0  4987.1     0.1       0
Bank Sta=4938.2,4942.2
Exp/Cntr=0.3,0.1

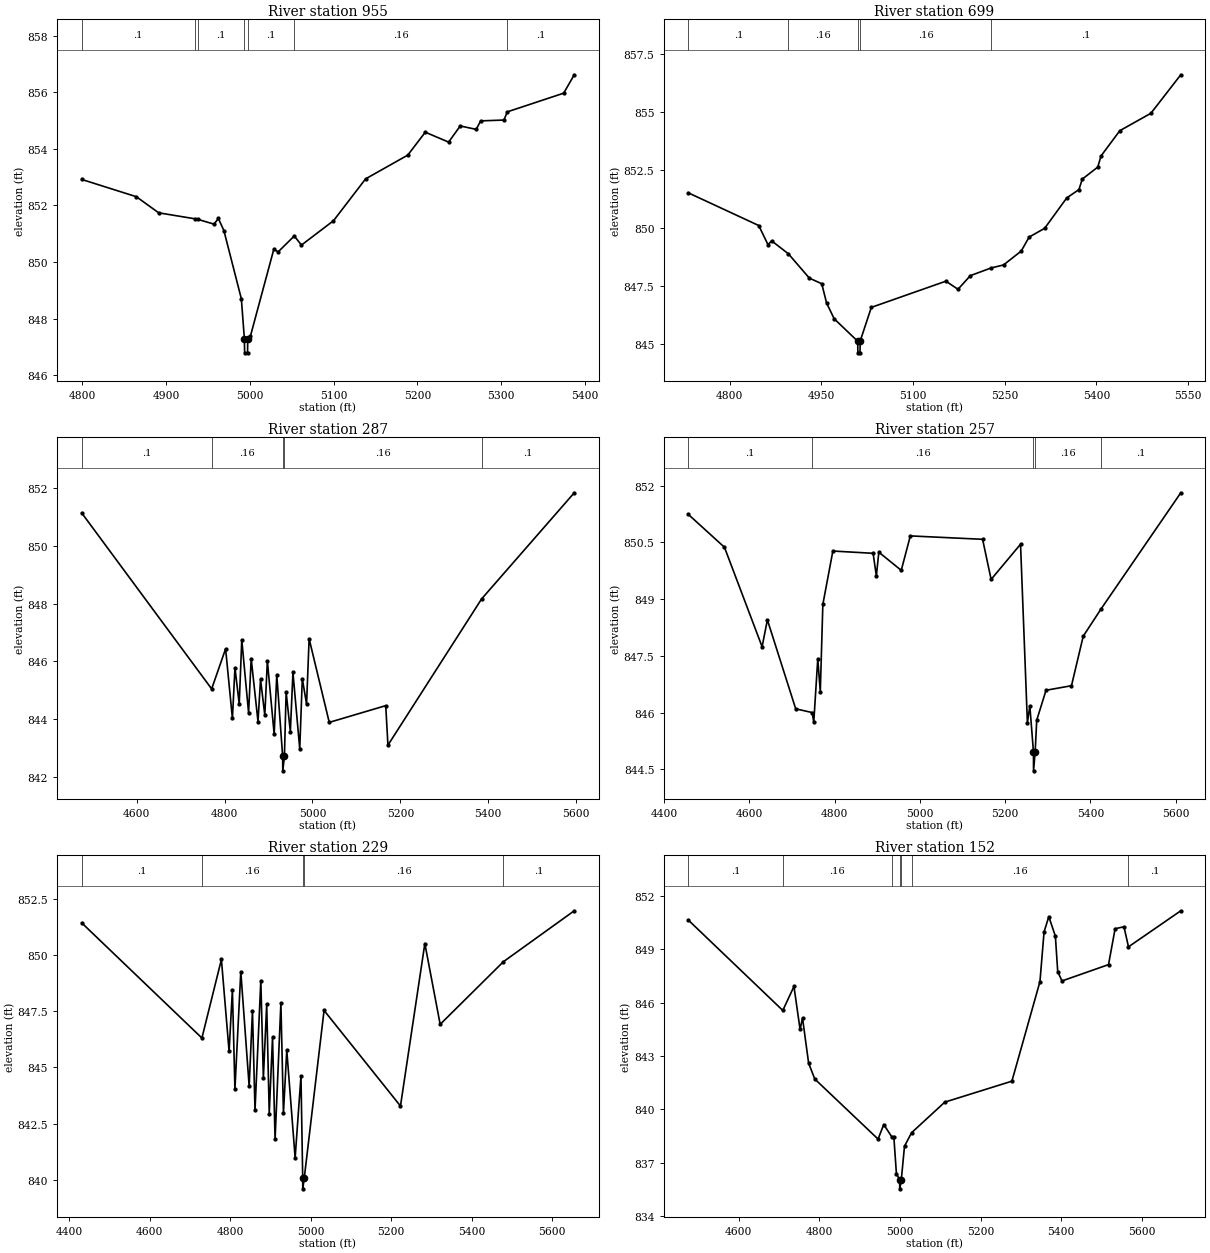
Type RM Length L Ch R = 1,955,256,256,256
BEGIN DESCRIPTION:
Mapping XS 8f19c975
END DESCRIPTION:
XS GIS Cut Line= 2
      1973863.40     13637692.64      1974032.69     13638255.22
#Sta/Elev= 30
  4799.6  852.92  4864.7  852.31  4891.4  851.74  4934.4  851.53  4938.0  851.51
  4957.4  851.34  4962.6  851.54  4969.2  851.11  4990.0  848.70  4993.6  847.29
  4993.9  846.79  4997.4  846.79  4997.6  847.29  5000.9  847.39  5028.7  850.45
  5033.9  850.36  5053.1  850.92  5061.7  850.60  5099.9  851.46  5138.2  852.94
  5188.5  853.78  5209.4  854.59  5237.2  854.24  5251.1  854.81  5270.2  854.69
  5275.4  854.99  5303.2  855.02  5307.3  855.31  5374.5  855.97  5387.1  856.62
#Mann=7,-1,0
  4799.6     0.1       0  4934.4    0.16       0  4938.0     0.1       0
  4993.6    0.07       0  4997.6     0.1       0  5053.1    0.16       0
  5307.3     0.1       0
Bank Sta=4993.6,4997.6
Exp/Cntr=0.3,0.1

Type RM Length L Ch R = 1,699,412,412,412
BEGIN DESCRIPTION:
Mapping XS ee20937f
END DESCRIPTION:
XS GIS Cut Line= 4
      1973751.42     13637731.76      1973668.10     13637861.95
      1973725.39     13638216.12      1974000.69     13638314.81
#Sta/Elev= 30
  4732.2  851.51  4847.5  850.10  4862.7  849.27  4868.6  849.44  4896.0  848.88
  4930.4  847.83  4950.6  847.59  4958.5  846.76  4970.9  846.08  5009.4  845.11
  5009.7  844.61  5013.2  844.61  5013.4  845.11  5031.7  846.57  5153.7  847.70
  5173.5  847.35  5193.8  847.94  5227.7  848.27  5248.0  848.40  5277.0  849.00
  5289.8  849.60  5315.3  849.98  5351.4  851.29  5371.4  851.65  5376.8  852.10
  5402.2  852.62  5407.5  853.10  5438.3  854.19  5489.1  854.94  5538.0  856.60
#Mann=5,-1,0
  4732.2     0.1       0  4896.0    0.16       0  5009.4    0.07       0
  5013.4    0.16       0  5227.7     0.1       0
Bank Sta=5009.4,5013.4
Exp/Cntr=0.3,0.1

Type RM Length L Ch R = 1,287,30,30,30
BEGIN DESCRIPTION:
Mapping XS f649cee5
END DESCRIPTION:
XS GIS Cut Line= 5
      1973694.12     13637742.17      1973421.57     13637912.30
      1973317.40     13638084.17      1973320.87     13638315.08
      1973645.49     13638486.93
#Sta/Elev= 30
  4475.2  851.14  4770.8  845.04  4802.5  846.43  4818.0  844.02  4823.8  845.77
  4833.5  844.52  4839.3  846.74  4854.8  844.21  4860.7  846.09  4876.2  843.91
  4882.0  845.37  4891.7  844.13  4897.5  846.01  4913.0  843.47  4918.9  845.53
  4932.3  842.70  4932.6  842.20  4936.3  842.70  4940.2  844.93  4949.8  843.56
  4955.7  845.61  4971.2  842.96  4977.0  845.40  4986.7  844.51  4992.5  846.78
  5038.3  843.88  5166.8  844.46  5171.8  843.09  5384.9  848.16  5595.7  851.84
#Mann=5,-1,0
  4475.2     0.1       0  4770.8    0.16       0  4932.3    0.07       0
  4936.3    0.16       0  5384.9     0.1       0
Bank Sta=4932.3,4936.3
Exp/Cntr=0.3,0.1

Type RM Length L Ch R = 1,257,28,28,28
BEGIN DESCRIPTION:
Mapping XS a45eb20f
END DESCRIPTION:
XS GIS Cut Line= 5
      1973682.00     13637724.79      1973390.32     13637908.83
      1973284.42     13638085.91      1973293.10     13638309.87
      1973626.45     13638492.17
#Sta/Elev= 30
  4456.9  851.24  4541.8  850.37  4630.1  847.74  4642.5  848.45  4708.9  846.10
  4747.6  846.00  4751.3  845.75  4760.7  847.42  4766.6  846.55  4772.6  848.86
  4796.1  850.27  4890.5  850.21  4898.1  849.61  4903.9  850.24  4956.5  849.76
  4977.8  850.67  5147.3  850.58  5167.3  849.52  5236.3  850.45  5252.4  845.73
  5258.1  846.18  5266.6  844.96  5266.8  844.46  5270.6  844.96  5274.3  845.80
  5296.1  846.59  5355.8  846.71  5383.4  848.02  5424.6  848.73  5612.2  851.81
#Mann=5,-1,0
  4456.9     0.1       0  4747.6    0.16       0  5266.6    0.07       0
  5270.6    0.16       0  5424.6     0.1       0
Bank Sta=5266.6,5270.6
Exp/Cntr=0.3,0.1

Type RM Length L Ch R = 1,229,77,77,77
BEGIN DESCRIPTION:
Mapping XS 60a2818d
END DESCRIPTION:
XS GIS Cut Line= 5
      1973683.76     13637707.41      1973390.32     13637893.20
      1973261.85     13638061.60      1973265.32     13638327.23
      1973624.65     13638502.56
#Sta/Elev= 30
  4430.7  851.44  4729.5  846.31  4778.0  849.81  4797.1  845.71  4805.3  848.45
  4811.6  844.03  4826.2  849.27  4847.0  844.16  4855.2  847.52  4861.5  843.09
  4876.0  848.87  4882.3  844.52  4890.6  847.81  4896.9  842.94  4905.1  846.34
  4911.4  841.79  4925.9  847.87  4932.2  842.96  4940.5  845.77  4961.3  840.97
  4975.8  844.61  4980.1  840.09  4980.3  839.59  4984.1  840.09  5033.2  847.54
  5223.2  843.28  5283.8  850.52  5321.9  846.92  5479.1  849.71  5655.3  851.98
#Mann=5,-1,0
  4430.7     0.1       0  4729.5    0.16       0  4980.1    0.07       0
  4984.1    0.16       0  5479.1     0.1       0
Bank Sta=4980.1,4984.1
Exp/Cntr=0.3,0.1

Type RM Length L Ch R = 1,152,34,34,34
BEGIN DESCRIPTION:
Mapping XS ac556146
END DESCRIPTION:
XS GIS Cut Line= 6
      1973621.12     13637719.62      1973268.28     13637942.26
      1973203.18     13638008.67      1973214.90     13638291.22
      1973270.89     13638339.40      1973584.70     13638506.07
#Sta/Elev= 30
  4474.7  850.65  4709.3  845.56  4737.0  846.91  4752.2  844.49  4758.2  845.14
  4773.4  842.59  4788.7  841.70  4945.7  838.32  4959.8  839.14  4980.2  838.43
  4984.9  838.43  4991.2  836.38  4999.3  836.02  4999.5  835.52  5003.3  836.02
  5011.3  837.92  5028.9  838.68  5111.3  840.40  5277.8  841.58  5347.4  847.18
  5357.6  849.98  5369.4  850.84  5385.7  849.74  5391.5  847.75  5402.0  847.22
  5517.6  848.14  5533.9  850.16  5555.9  850.27  5567.1  849.14  5696.9  851.17
#Mann=7,-1,0
  4474.7     0.1       0  4709.3    0.16       0  4980.2     0.1       0
  4999.3    0.07       0  5003.3     0.1       0  5028.9    0.16       0
  5567.1     0.1       0
Bank Sta=4999.3,5003.3
Exp/Cntr=0.3,0.1

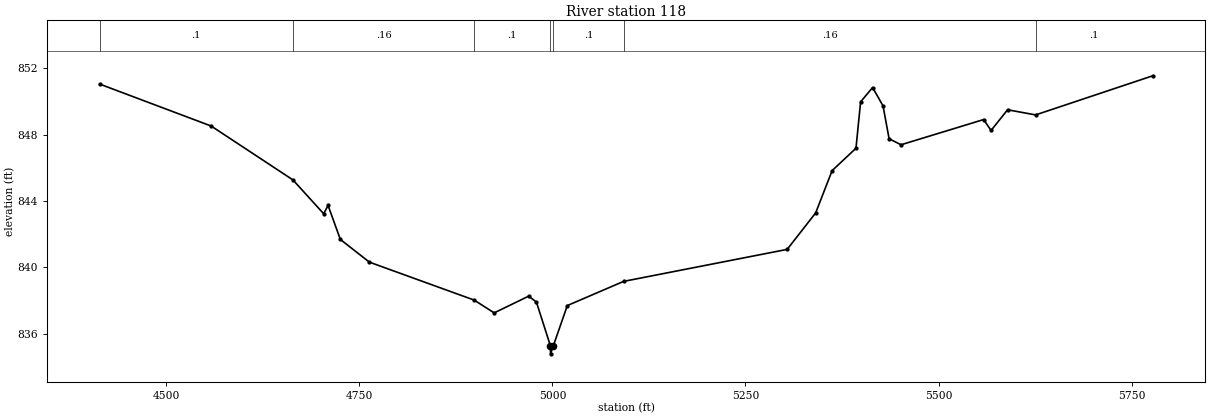
Type RM Length L Ch R = 1,118,0,0,0
BEGIN DESCRIPTION:
UNT 123 in BCW 1.0
END DESCRIPTION:
XS GIS Cut Line= 4
      1973630.81     13637696.13      1973173.23     13637955.29
      1973165.42     13638280.81      1973604.18     13638545.10
#Sta/Elev= 30
  4413.7  851.05  4558.1  848.52  4664.0  845.27  4703.8  843.23  4709.5  843.73
  4725.4  841.68  4763.0  840.31  4898.8  838.02  4924.6  837.25  4969.3  838.26
  4979.3  837.90  4997.3  835.28  4997.6  834.78  5001.3  835.28  5019.3  837.69
  5092.2  839.15  5304.0  841.08  5340.9  843.28  5362.2  845.83  5393.1  847.18
  5399.1  849.98  5414.6  850.84  5428.1  849.74  5436.0  847.75  5451.5  847.39
  5558.4  848.91  5568.0  848.25  5589.4  849.50  5625.7  849.19  5777.4  851.55
#Mann=7,-1,0
  4413.7     0.1       0  4664.0    0.16       0  4898.8     0.1       0
  4997.3    0.07       0  5001.3     0.1       0  5092.2    0.16       0
  5625.7     0.1       0
Bank Sta=4997.3,5001.3
Exp/Cntr=0.3,0.1

Chan Stop Cuts=-1