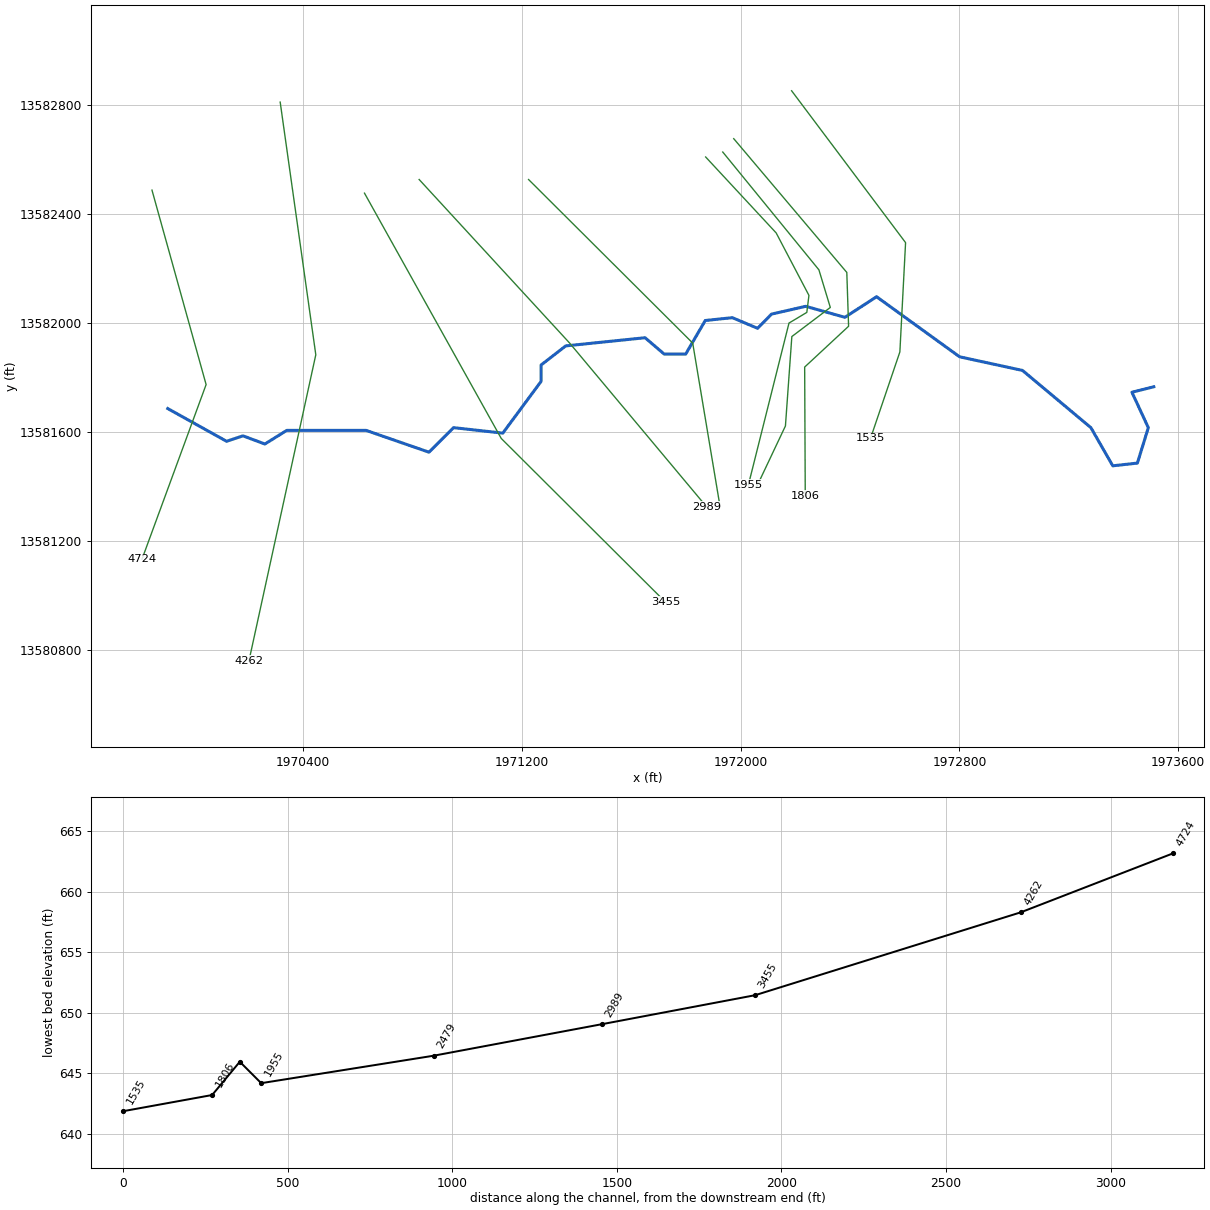
--- UNT 124 in BCW.prj (project) ---

Proj Title=UNT 124 in BCW Base Level Engineering
Current Plan=p01
Default Exp/Contr=0.3,0.1
English Units
Geom File=g01
Flow File=f01
Plan File=p01
Y Axis Title=Elevation
X Axis Title(PF)=Main Channel Distance
X Axis Title(XS)=Station
BEGIN DESCRIPTION:
UNT 124 in BCW
END DESCRIPTION:
DSS Export Rating Curves= 0
DSS Export Rating Curve Sorted= 0
DSS Export Volume Flow Curves= 0
DXF OffsetX= 0
DXF OffsetY= 0
DXF ScaleX= 1
DXF ScaleY= 10

--- UNT 124 in BCW.p01 (plan) ---

Plan Title=Multiple Run
Short Identifier=Multiple
Geom File=g01
Flow File=f01
Subcritical Flow
K Sum by GR= 0
Std Step Tol= 0.01
Critical Tol= 0.01
Num of Std Step Trials= 20
Max Error Tol= 0.3
Flow Tol Ratio= 0.001
Split Flow NTrial= 30
Split Flow Tol= 0.02
Split Flow Ratio= 0.02
Log Output Level= 0
Friction Slope Method= 1
Unsteady Friction Slope Method= 2
Unsteady Bridges Friction Slope Method= 1
Parabolic Critical Depth
Global Vel Dist=  1 , 1 , 1
Global Log Level= 0
CheckData=True
Encroach Param= -1, 0, 0, 0
BEGIN DESCRIPTION:
Multiple Run
END DESCRIPTION:

--- UNT 124 in BCW.f01 (steady flow) ---

Flow Title=Multiple
Number of Profiles=7
Profile Names=10-year,25-year,50-year,1pct_min,100-year,1pct_plu,500-year
River Rch & RM= UNT 124 in BCW,Reach-1,4724
     400     552     675     410     817    1631    1201
Boundary for River Rch & Prof#=UNT 124 in BCW,Reach-1,1
Up Type=0
Dn Type=3
Dn Slope=0.005
Boundary for River Rch & Prof#=UNT 124 in BCW,Reach-1,2
Up Type=0
Dn Type=3
Dn Slope=0.005
Boundary for River Rch & Prof#=UNT 124 in BCW,Reach-1,3
Up Type=0
Dn Type=3
Dn Slope=0.005
Boundary for River Rch & Prof#=UNT 124 in BCW,Reach-1,4
Up Type=0
Dn Type=3
Dn Slope=0.005
Boundary for River Rch & Prof#=UNT 124 in BCW,Reach-1,5
Up Type=0
Dn Type=3
Dn Slope=0.005
Boundary for River Rch & Prof#=UNT 124 in BCW,Reach-1,6
Up Type=0
Dn Type=3
Dn Slope=0.005
Boundary for River Rch & Prof#=UNT 124 in BCW,Reach-1,7
Up Type=0
Dn Type=3
Dn Slope=0.005

--- UNT 124 in BCW.g01 (geometry) ---

Geom Title=Existing Conditions
Program Version=5.05

River Reach=UNT 124 in BCW  ,Reach-1
Reach XY= 30
       1969905.8     13581684.54       1970120.8     13581564.54
       1970180.8     13581584.54       1970260.8     13581554.54
       1970340.8     13581604.54       1970630.8     13581604.54
       1970860.8     13581524.54       1970950.8     13581614.54
       1971130.8     13581594.54       1971270.8     13581784.54
       1971270.8     13581844.54       1971360.8     13581914.54
       1971650.8     13581944.54       1971720.8     13581884.54
      1971799.35     13581884.54      1971870.97     13582007.73
      1971969.93     13582018.14      1972062.37     13581979.08
      1972113.16     13582031.16      1972238.16     13582059.81
      1972381.39     13582019.45      1972497.27     13582094.97
       1972800.8     13581874.54       1973030.8     13581824.54
       1973280.8     13581614.54       1973360.8     13581474.54
       1973450.8     13581484.54       1973490.8     13581614.54
       1973430.8     13581744.54       1973510.8     13581764.54

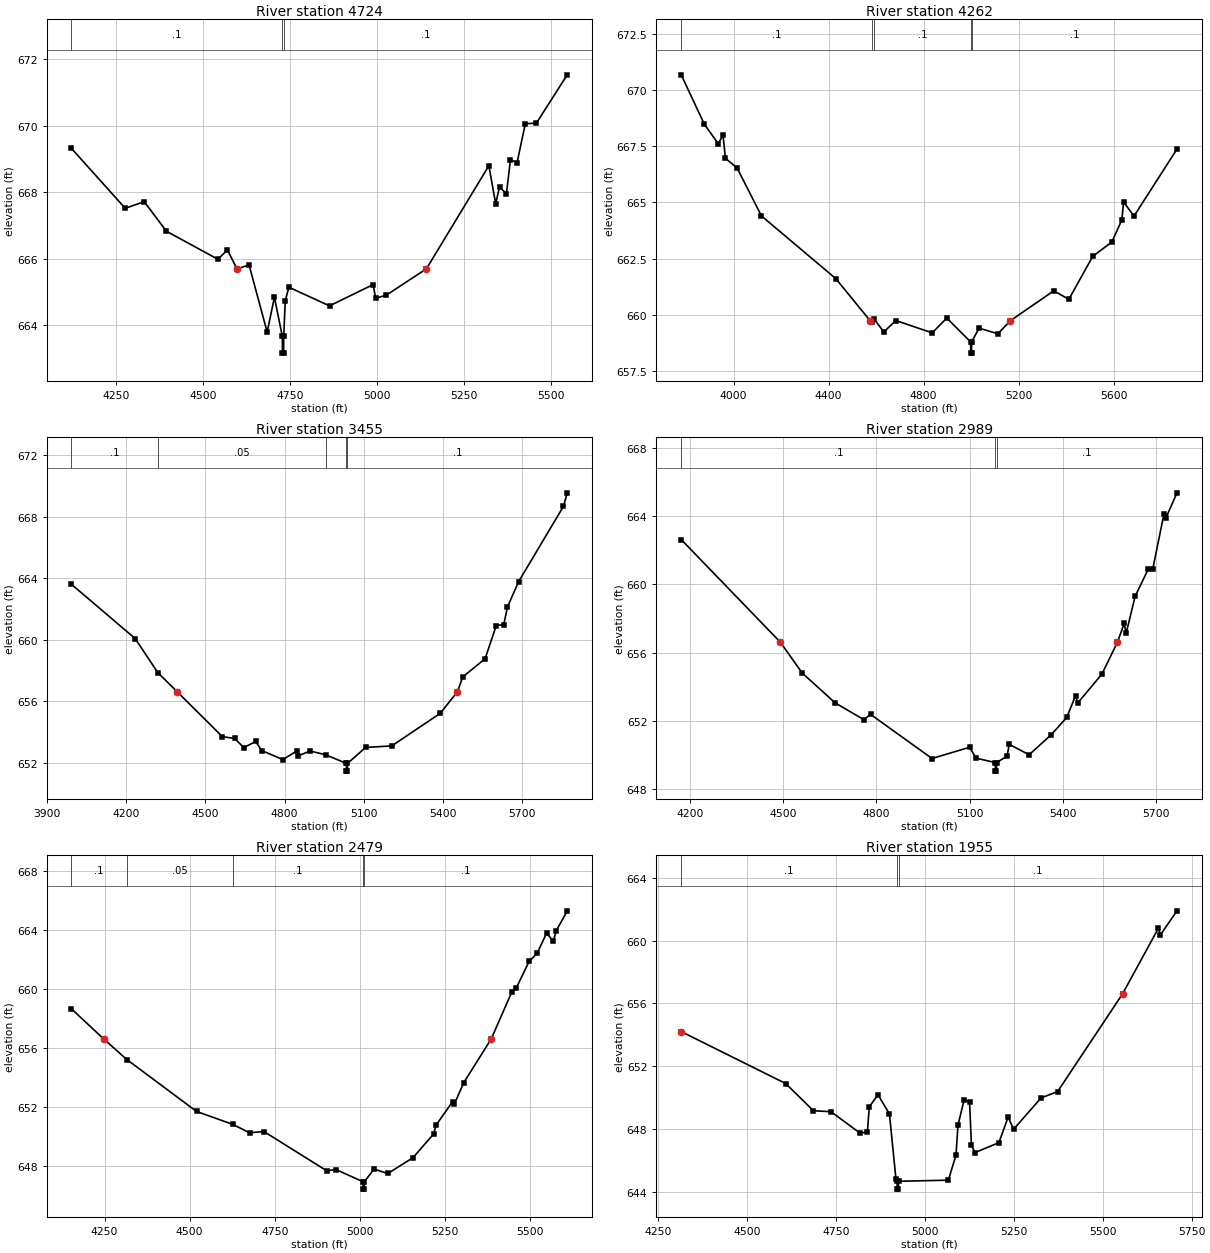
Type RM Length L Ch R = 1 ,4724    ,462,462,462
BEGIN DESCRIPTION:
UNT 124 in BCW 7.0
END DESCRIPTION:
XS GIS Cut Line= 3
      1969848.06     13582486.19      1970045.98     13581772.66
      1969811.61     13581132.06
#Sta/Elev= 30
  4123.1  669.32  4277.4  667.52  4331.9  667.72  4395.8  666.83  4543.3  665.99
  4570.6  666.27 4598.21665.7003  4632.8  665.82  4684.7   663.8  4705.5  664.85
  4728.2  663.67  4728.5  663.17    4732  663.17  4732.2  663.67  4736.6  664.74
    4747  665.15  4863.6  664.59  4988.9  665.23  4995.8  664.82  5026.3  664.91
 5141.55665.7003  5320.9   668.8  5340.3  667.66  5351.4  668.16  5371.3  667.96
  5382.8  668.98  5401.8  668.89  5425.4  670.06  5457.4  670.08  5545.7  671.53
#Mann= 3 ,-1 , 0
  4123.1      .1       0  4728.2     .07       0  4732.2      .1       0
Bank Sta=4598.21,5141.55
XS Rating Curve= 0 ,0
Exp/Cntr=0.3,0.1

Type RM Length L Ch R = 1 ,4262    ,807,807,807
BEGIN DESCRIPTION:
UNT 124 in BCW 6.0
END DESCRIPTION:
XS GIS Cut Line= 3
       1970316.8     13582809.15      1970447.02     13581882.03
      1970202.55     13580758.53
#Sta/Elev= 30
  3779.8  670.67  3877.3  668.47  3935.5  667.61  3955.7  667.99  3965.8  666.96
  4014.8  666.53  4117.2   664.4  4430.3  661.61 4574.81659.7391  4584.4   659.7
    4592  659.81  4632.2  659.24  4682.7  659.75  4835.8   659.2  4897.2  659.86
  4997.5   658.8  4997.8   658.3  5001.3   658.3  5001.5   658.8  5033.3  659.41
  5112.1  659.16 5164.57659.7391  5347.5  661.07  5410.7  660.69  5511.2   662.6
  5591.8  663.24    5634  664.23  5640.9  665.02  5684.9  664.39  5865.8  667.37
#Mann= 5 ,-1 , 0
  3779.8      .1       0  4584.4     .05       0    4592      .1       0
  4997.5     .07       0  5001.5      .1       0
Bank Sta=4574.81,5164.57
XS Rating Curve= 0 ,0
Exp/Cntr=0.3,0.1

Type RM Length L Ch R = 1 ,3455    ,466,466,466
BEGIN DESCRIPTION:
UNT 124 in BCW 5.0
END DESCRIPTION:
XS GIS Cut Line= 3
      1970625.01     13582474.99        1971125.       13581575.
      1971725.02     13580974.98
#Sta/Elev= 30
  3992.8   663.6  4234.2  660.07  4320.1  657.85 4393.14656.6164  4564.8  653.69
  4610.5  653.58    4646  652.98  4690.6  653.38  4713.5  652.79  4793.6   652.2
  4846.2  652.76  4851.9  652.44  4896.5  652.76  4956.7  652.51  5034.5  651.95
  5034.7  651.45  5038.2  651.45  5038.5  651.95  5107.2  652.99  5206.2  653.09
    5390  655.21 5455.06656.6164  5474.9  657.57  5559.8  658.76  5602.2  660.92
  5630.5  660.98  5644.6  662.13    5687  663.78  5856.7  668.67  5870.9  669.55
#Mann= 5 ,-1 , 0
  3992.8      .1       0  4320.1     .05       0  4956.7      .1       0
  5034.5     .07       0  5038.5      .1       0
Bank Sta=4393.14,5455.06
XS Rating Curve= 0 ,0
Exp/Cntr=0.3,0.1

Type RM Length L Ch R = 1 ,2989    ,510,510,510
BEGIN DESCRIPTION:
UNT 124 in BCW 4.0
END DESCRIPTION:
XS GIS Cut Line= 3
      1970824.97     13582525.03        1971375.       13581925.
        1971875.       13581325.
#Sta/Elev= 30
  4172.4  662.63 4491.13656.6141  4561.8   654.8  4667.9  653.05  4759.8  652.07
  4781.4  652.38  4979.3  649.79  5100.3  650.45  5121.1  649.81  5182.9  649.55
  5183.1  649.05  5186.6  649.05  5186.9  649.55  5220.7  649.93  5227.8  650.62
  5291.6  650.01  5363.2  651.19  5412.7   652.2  5441.3  653.48  5447.8  653.04
  5525.9  654.74 5575.98656.6146  5597.5  657.71    5604  657.14  5632.7   659.3
  5675.6  660.92  5689.3  660.88  5725.1   664.1  5731.6  663.89  5767.4  665.37
#Mann= 3 ,-1 , 0
  4172.4      .1       0  5182.9     .07       0  5186.9      .1       0
Bank Sta=4491.13,5575.98
XS Rating Curve= 0 ,0
Exp/Cntr=0.3,0.1

Type RM Length L Ch R = 1 ,2479    ,524,524,524
BEGIN DESCRIPTION:
UNT 124 in BCW 3.0
END DESCRIPTION:
XS GIS Cut Line= 3
      1971224.97     13582525.03        1971825.       13581925.
      1971924.99     13581325.04
#Sta/Elev= 30
  4152.6  658.66 4247.73656.6133  4315.2  655.23  4520.3  651.71  4626.1  650.84
  4675.9  650.27  4718.3  650.35  4902.2   647.7  4930.5  647.77  5009.3  646.95
  5009.6  646.45  5013.1  646.45  5013.3  646.95  5041.7   647.8  5082.3  647.51
  5155.8  648.57  5216.6  650.18  5224.2  650.79  5272.4  652.37  5277.4  652.19
  5305.3  653.66 5385.88656.6132  5447.2  659.83  5459.9  660.08  5497.9   661.9
  5520.7  662.41  5548.6  663.78  5568.9  663.25  5576.5  663.92  5609.4   665.3
#Mann= 5 ,-1 , 0
  4152.6      .1       0  4315.2     .05       0  4626.1      .1       0
  5009.3     .07       0  5013.3      .1       0
Bank Sta=4247.73,5385.88
XS Rating Curve= 0 ,0
Exp/Cntr=0.3,0.1

Type RM Length L Ch R = 1 ,1955    ,65,65,65
BEGIN DESCRIPTION:
Mapping XS 6f3e384a
END DESCRIPTION:
XS GIS Cut Line= 6
      1971872.35     13582607.74      1972130.18     13582329.08
      1972249.97     13582099.91      1972242.16     13582037.41
      1972177.05     13581998.35      1972028.62     13581404.62
#Sta/Elev= 30
  4315.6  654.21  4609.4   650.9  4687.2  649.17  4736.5  649.11  4817.2  647.76
  4838.7   647.8  4844.1  649.42  4868.5  650.19  4900.7  648.97  4918.9  644.85
  4922.3  644.68  4922.5  644.18    4926  644.18  4926.3  644.68  5066.3  644.75
  5087.7  646.34  5093.3  648.24  5110.6  649.87  5125.9  649.73  5131.2  646.96
  5141.5  646.51  5208.4  647.14  5234.3  648.77  5249.6  647.99  5326.9  649.99
  5373.3  650.39 5555.85 656.613  5656.8   660.8    5662  660.36  5708.8   661.9
#Mann= 3 ,-1 , 0
  4315.6      .1       0  4922.3     .07       0  4926.3      .1       0
Bank Sta=4315.6,5555.85
XS Rating Curve= 0 ,0
Exp/Cntr=0.3,0.1

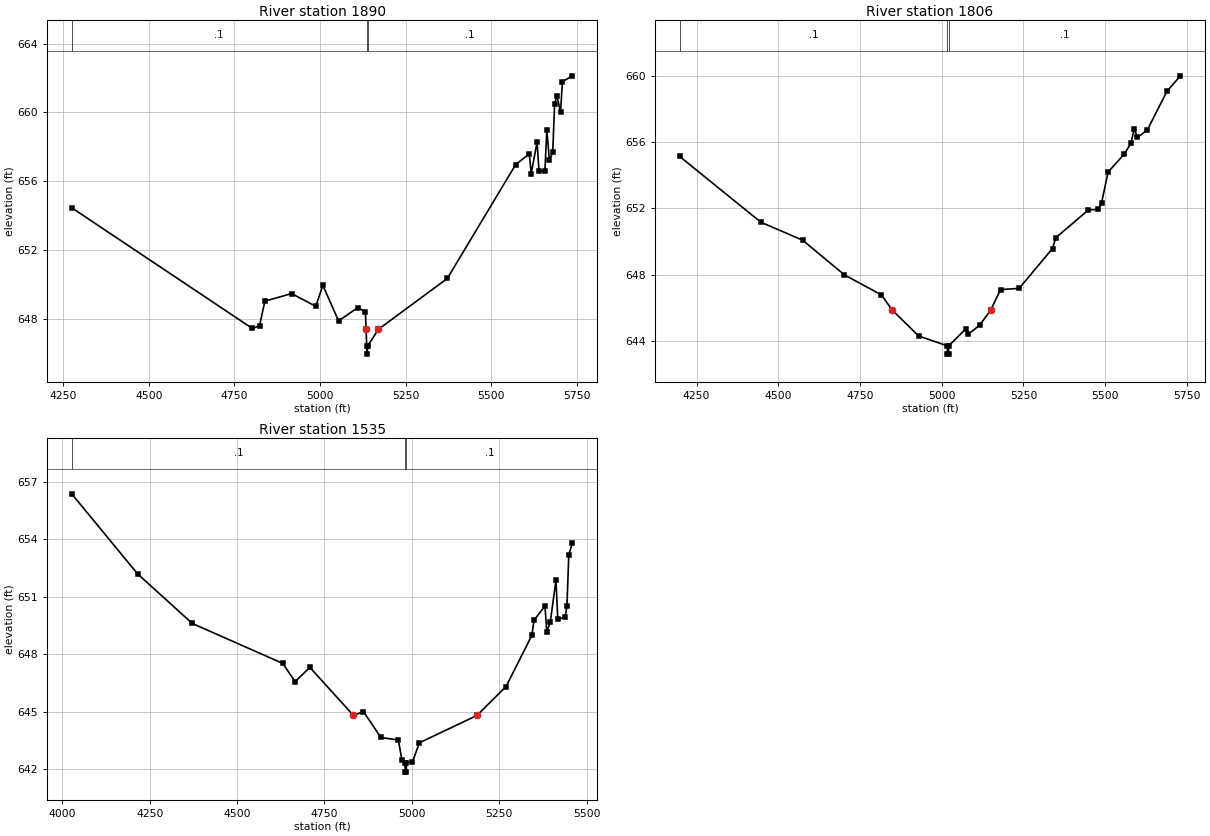
Type RM Length L Ch R = 1 ,1890    ,84,84,84
BEGIN DESCRIPTION:
Mapping XS 82d4dc99
END DESCRIPTION:
XS GIS Cut Line= 6
      1971934.88     13582625.94      1972286.43     13582193.66
      1972328.09     13582055.64      1972187.47     13581948.87
      1972164.03     13581620.75      1972057.28     13581394.22
#Sta/Elev= 30
  4275.3  654.46  4802.5  647.44  4823.3   647.6    4839  649.03  4916.9  649.47
  4987.4  648.73  5008.2  649.95    5054  647.88  5110.4  648.66  5132.4   648.4
 5134.26647.3926    5136  646.45  5136.3  645.95    5140  646.45 5170.21647.3933
  5371.4  650.35  5570.5  656.96  5610.6   657.6  5616.1  656.45  5633.3  658.28
  5638.9  656.57  5656.1  656.62  5661.7  658.98  5669.2  657.23  5678.9  657.68
  5684.4   660.5  5691.3  660.98  5701.7  660.01  5707.2  661.79  5736.4  662.13
#Mann= 3 ,-1 , 0
  4275.3      .1       0    5136     .07       0    5140      .1       0
Bank Sta=5134.26,5170.21
XS Rating Curve= 0 ,0
Exp/Cntr=0.3,0.1

Type RM Length L Ch R = 1 ,1806    ,271,271,271
BEGIN DESCRIPTION:
UNT 124 in BCW 2.0
END DESCRIPTION:
XS GIS Cut Line= 5
      1971975.02     13582674.98      1972388.42     13582184.12
      1972394.93     13581986.63      1972234.34     13581836.89
      1972236.51     13581363.82
#Sta/Elev= 30
  4198.2  655.14  4446.6  651.17  4574.6  650.08  4702.1  647.99  4815.3  646.78
 4848.99645.8548  4929.1   644.3  5017.2   643.7  5017.4   643.2  5020.9   643.2
  5021.2   643.7  5074.1  644.73    5081  644.39  5116.6  644.96 5149.71645.8547
  5180.1   647.1  5236.8  647.17    5339  649.58    5349  650.23    5449  651.91
    5479  651.94    5489  652.33    5509   654.2    5559  655.29    5579  655.95
    5589   656.8    5599  656.29    5629  656.74    5689  659.07  5730.2  660.01
#Mann= 3 ,-1 , 0
  4198.2      .1       0  5017.2     .07       0  5021.2      .1       0
Bank Sta=4848.99,5149.71
XS Rating Curve= 0 ,0
Exp/Cntr=0.3,0.1

Type RM Length L Ch R = 1 ,1535    ,0,0,0
BEGIN DESCRIPTION:
UNT 124 in BCW 1.0
END DESCRIPTION:
XS GIS Cut Line= 4
      1972186.62     13582850.75      1972603.27     13582293.49
      1972582.43     13581892.45        1972475.     13581575.01
#Sta/Elev= 30
  4026.8  656.37  4215.6  652.19  4371.9  649.61  4630.4  647.53  4665.8  646.58
  4708.2  647.32 4832.94 644.813  4861.3  645.02  4911.3  643.67  4961.4  643.53
  4971.4   642.5  4980.4  642.36  4980.6  641.86  4984.1  641.86  4984.4  642.36
  5001.5  642.38  5021.5  643.39 5185.92 644.813  5269.3  646.32  5343.2  648.99
  5349.3  649.78  5380.7  650.52    5386  649.18    5396  649.69  5412.2  651.87
  5417.4  649.84  5438.2  649.93  5443.6   650.5  5448.9   653.2  5459.3  653.81
#Mann= 3 ,-1 , 0
  4026.8      .1       0  4980.4     .07       0  4984.4      .1       0
Bank Sta=4832.94,5185.92
XS Rating Curve= 0 ,0
Exp/Cntr=0.3,0.1
LCMann Table=0

Chan Stop Cuts=-1
Use User Specified Reach Order=0
Composite Channel Slope=5