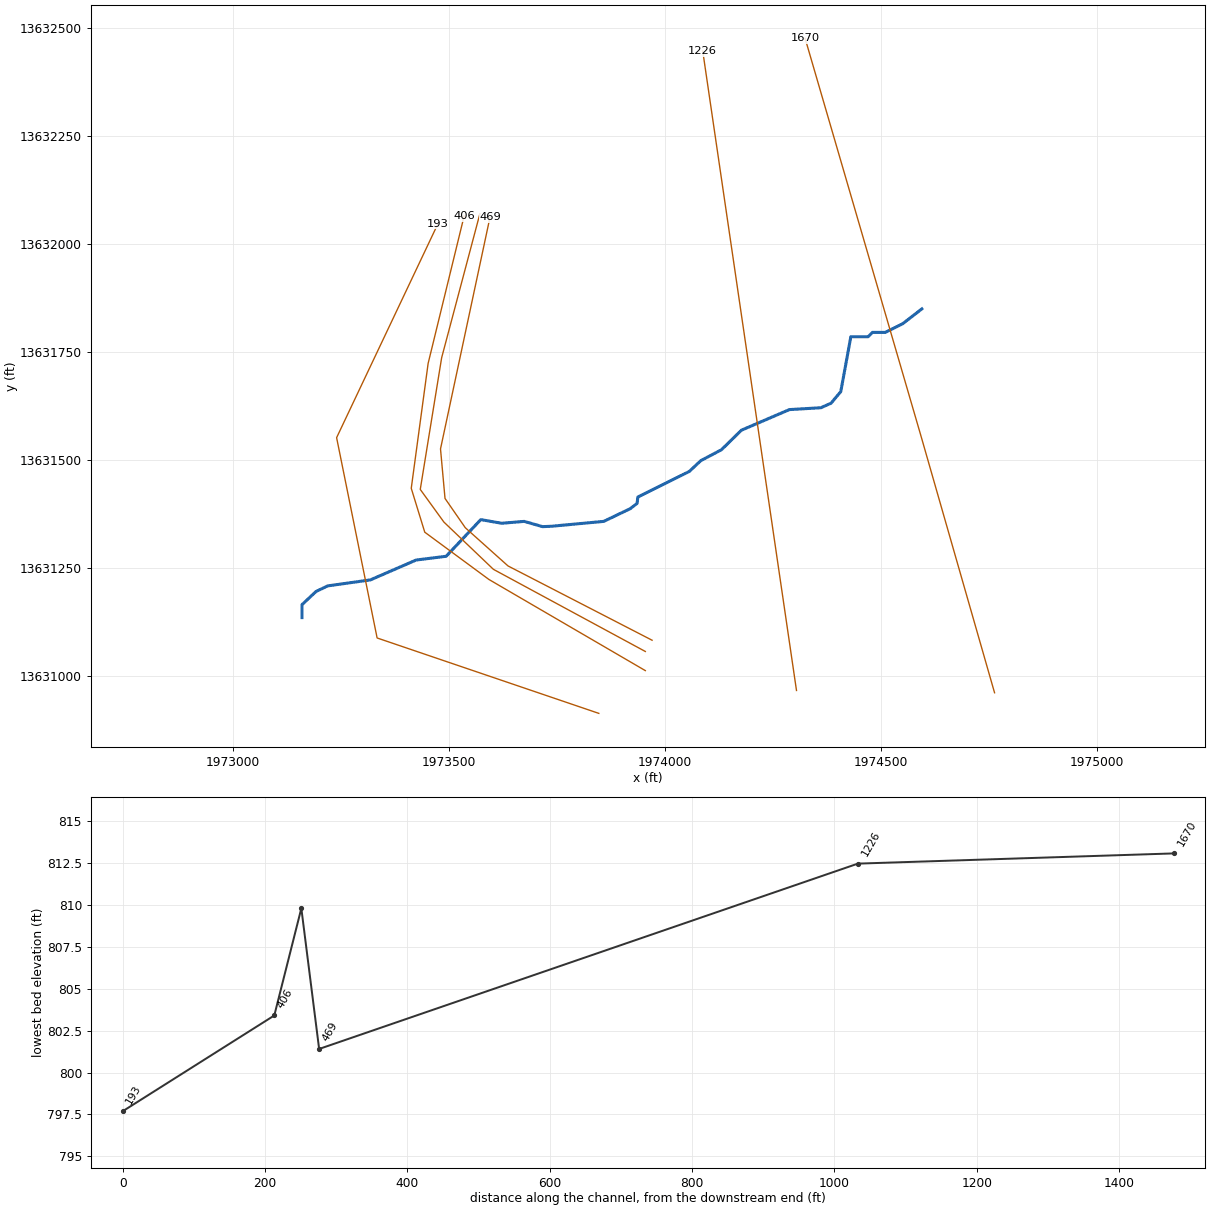
--- UNT 125 in BCW.prj (project) ---

Proj Title=UNT 125 in BCW Base Level Engineering
Current Plan=p01
Default Exp/Contr=0.3,0.1
English Units
Geom File=g01
Flow File=f01
Plan File=p01
BEGIN DESCRIPTION:
UNT 125 in BCW
END DESCRIPTION:

--- UNT 125 in BCW.p01 (plan) ---

Plan Title=Multiple Run
Short Identifier=Multiple
Geom File=g01
Flow File=f01
Subcritical Flow
K Sum by GR= 0
Std Step Tol= 0.01
Critical Tol= 0.01
Num of Std Step Trials= 20
Max Error Tol= 0.3
Flow Tol Ratio= 0.001
Split Flow NTrial= 30
Split Flow Tol= 0.02
Split Flow Ratio= 0.02
Log Output Level= 0
Friction Slope Method= 1
Unsteady Friction Slope Method= 2
Unsteady Bridges Friction Slope Method= 1
Parabolic Critical Depth
Global Vel Dist=  1 , 1 , 1
Global Log Level= 0
CheckData=True
Encroach Param= -1, 0, 0, 0
BEGIN DESCRIPTION:
Multiple Run
END DESCRIPTION:

--- UNT 125 in BCW.f01 (steady flow) ---

Flow Title=Multiple
Number of Profiles=7
Profile Names=10-year,25-year,50-year,1pct_min,100-year,1pct_plu,500-year
River Rch & RM= UNT 125 in BCW,Reach-1,1670
     420     581     713     434     865    1726    1278
Boundary for River Rch & Prof#=UNT 125 in BCW,Reach-1,1
Up Type=0
Dn Type=3
Dn Slope=0.005
Boundary for River Rch & Prof#=UNT 125 in BCW,Reach-1,2
Up Type=0
Dn Type=3
Dn Slope=0.005
Boundary for River Rch & Prof#=UNT 125 in BCW,Reach-1,3
Up Type=0
Dn Type=3
Dn Slope=0.005
Boundary for River Rch & Prof#=UNT 125 in BCW,Reach-1,4
Up Type=0
Dn Type=3
Dn Slope=0.005
Boundary for River Rch & Prof#=UNT 125 in BCW,Reach-1,5
Up Type=0
Dn Type=3
Dn Slope=0.005
Boundary for River Rch & Prof#=UNT 125 in BCW,Reach-1,6
Up Type=0
Dn Type=3
Dn Slope=0.005
Boundary for River Rch & Prof#=UNT 125 in BCW,Reach-1,7
Up Type=0
Dn Type=3
Dn Slope=0.005

--- UNT 125 in BCW.g01 (geometry) ---

Geom Title=Existing Conditions

River Reach=UNT 125 in BCW,Reach-1
Reach XY= 30
      1974595.17     13631848.91      1974550.80     13631814.54
      1974510.80     13631794.54      1974480.80     13631794.54
      1974470.80     13631784.54      1974430.80     13631784.54
      1974407.56     13631657.51      1974384.99     13631630.61
      1974361.56     13631620.19      1974288.64     13631615.85
      1974177.53     13631568.11      1974131.52     13631522.97
      1974083.78     13631497.79      1974056.87     13631472.62
      1973937.95     13631413.59      1973936.21     13631398.83
      1973920.59     13631386.68      1973858.95     13631357.17
      1973738.29     13631345.88      1973717.46     13631345.01
      1973674.93     13631357.17      1973622.84     13631352.83
      1973574.42     13631361.23      1973494.37     13631276.44
      1973424.93     13631267.76      1973319.02     13631221.75
      1973220.06     13631207.86      1973193.15     13631194.84
      1973160.80     13631164.54      1973160.80     13631134.54

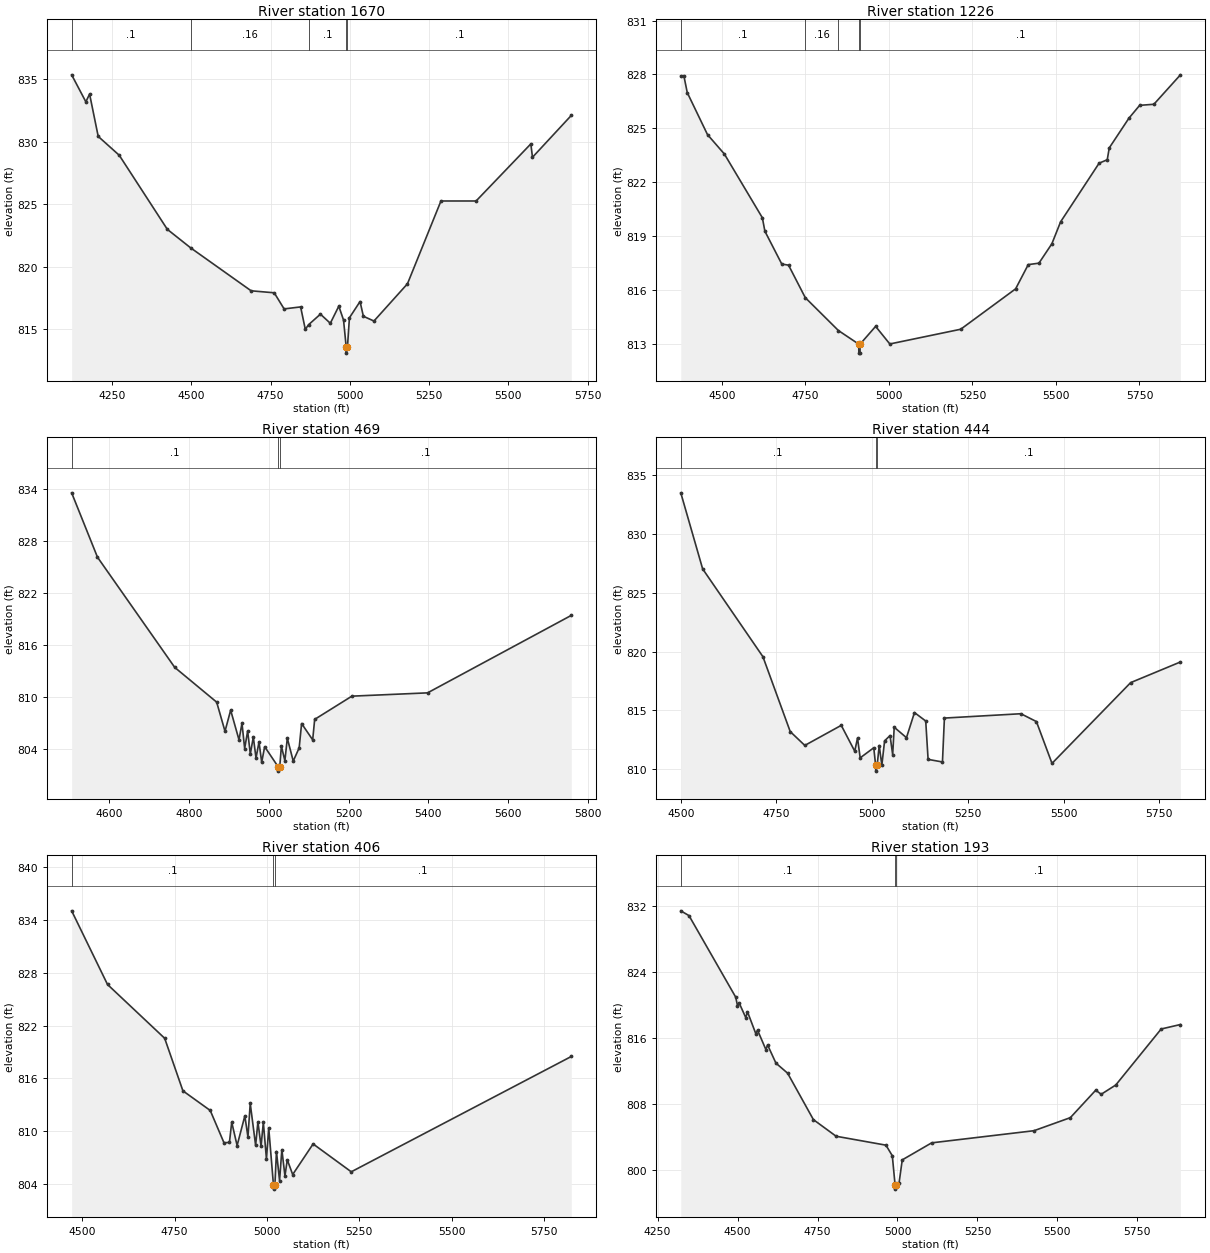
Type RM Length L Ch R = 1,1670,444,444,444
BEGIN DESCRIPTION:
UNT 125 in BCW 3.0
END DESCRIPTION:
XS GIS Cut Line= 3
      1974763.41     13630960.59      1974593.26     13631554.37
      1974325.00     13632475.00
#Sta/Elev= 30
  4122.1  835.37  4166.9  833.21  4178.7  833.83  4205.9  830.44  4272.3  828.93
  4424.0  823.00  4497.5  821.52  4688.4  818.08  4761.3  817.92  4792.5  816.63
  4844.6  816.79  4859.4  814.99  4869.5  815.36  4907.1  816.21  4938.3  815.48
  4965.1  816.85  4980.0  815.74  4988.4  813.59  4988.7  813.09  4992.4  813.59
  4998.6  815.92  5032.1  817.22  5042.6  816.04  5076.0  815.66  5181.7  818.64
  5287.4  825.27  5398.3  825.27  5571.0  829.84  5576.2  828.77  5698.7  832.12
#Mann=5,-1,0
  4122.1     0.1       0  4497.5    0.16       0  4869.5     0.1       0
  4988.4    0.07       0  4992.4     0.1       0
Bank Sta=4988.4,4992.4
Exp/Cntr=0.3,0.1

Type RM Length L Ch R = 1,1226,757,757,757
BEGIN DESCRIPTION:
Mapping XS be6b091f
END DESCRIPTION:
XS GIS Cut Line= 2
      1974305.06     13630965.85      1974088.06     13632445.82
#Sta/Elev= 30
  4376.9  827.92  4386.1  827.93  4396.3  826.99  4456.9  824.65  4507.4  823.57
  4621.1  820.02  4628.7  819.27  4679.3  817.44  4699.5  817.38  4749.6  815.57
  4848.7  813.74  4909.7  812.98  4910.0  812.48  4913.5  812.48  4913.7  812.98
  4960.2  813.97  5002.7  812.99  5214.9  813.81  5379.3  816.06  5417.1  817.41
  5449.1  817.49  5487.8  818.57  5513.9  819.79  5629.3  823.06  5653.6  823.25
  5659.6  823.91  5718.3  825.56  5750.6  826.28  5793.2  826.34  5872.7  827.98
#Mann=5,-1,0
  4376.9     0.1       0  4749.6    0.16       0  4848.7     0.1       0
  4909.7    0.07       0  4913.7     0.1       0
Bank Sta=4909.7,4913.7
Exp/Cntr=0.3,0.1

Type RM Length L Ch R = 1,469,25,25,25
BEGIN DESCRIPTION:
Mapping XS 219e46e2
END DESCRIPTION:
XS GIS Cut Line= 6
      1973970.89     13631082.13      1973637.53     13631254.02
      1973538.57     13631342.56      1973491.70     13631410.27
      1973481.28     13631524.86      1973595.72     13632060.61
#Sta/Elev= 30
  4505.4  833.52  4570.1  826.10  4763.9  813.38  4869.1  809.37  4890.0  806.01
  4904.2  808.44  4925.1  805.02  4932.6  806.93  4939.3  804.02  4946.8  806.04
  4953.5  803.39  4961.0  805.34  4967.8  802.92  4975.3  804.78  4982.0  802.43
  4989.5  804.23  5023.3  801.91  5023.6  801.41  5027.3  801.91  5031.4  804.29
  5040.2  802.61  5046.3  805.21  5061.1  802.57  5076.0  804.09  5082.1  806.90
  5109.9  805.02  5114.9  807.38  5208.2  810.06  5398.0  810.44  5758.5  819.38
#Mann=3,-1,0
  4505.4     0.1       0  5023.3    0.07       0  5027.3     0.1       0
Bank Sta=5023.3,5027.3
Exp/Cntr=0.3,0.1

Type RM Length L Ch R = 1,444,38,38,38
BEGIN DESCRIPTION:
Mapping XS 4f50412c
END DESCRIPTION:
XS GIS Cut Line= 6
      1973955.24     13631056.11      1973603.68     13631246.21
      1973489.10     13631355.59      1973434.41     13631431.11
      1973483.89     13631735.79      1973572.43     13632069.14
#Sta/Elev= 30
  4500.1  833.52  4557.2  827.04  4714.6  819.56  4785.9  813.18  4824.0  812.00
  4919.2  813.71  4954.4  811.51  4961.7  812.63  4968.6  810.94  5004.1  811.80
  5009.0  810.31  5009.3  809.81  5013.0  810.31  5018.3  811.99  5025.2  810.32
  5032.4  812.39  5046.6  812.84  5053.5  811.21  5057.5  813.55  5089.5  812.66
  5110.4  814.80  5139.8  814.08  5146.0  810.81  5183.5  810.59  5188.6  814.33
  5388.4  814.70  5428.9  814.03  5469.6  810.47  5675.0  817.35  5805.0  819.11
#Mann=3,-1,0
  4500.1     0.1       0  5009.0    0.07       0  5013.0     0.1       0
Bank Sta=5009,5013
Exp/Cntr=0.3,0.1

Type RM Length L Ch R = 1,406,213,213,213
BEGIN DESCRIPTION:
Mapping XS ae60fd69
END DESCRIPTION:
XS GIS Cut Line= 6
      1973955.23     13631011.84      1973593.26     13631222.77
      1973444.82     13631332.15      1973413.57     13631433.71
      1973452.64     13631722.77      1973535.98     13632063.97
#Sta/Elev= 30
  4471.5  835.07  4568.6  826.69  4723.3  820.57  4772.7  814.59  4846.6  812.36
  4883.8  808.69  4898.6  808.72  4904.8  811.02  4919.4  808.37  4940.3  811.74
  4948.7  809.35  4954.9  813.16  4969.5  808.39  4975.7  811.07  4984.2  808.29
  4990.4  811.01  4998.8  806.83  5005.0  810.37  5017.7  803.91  5017.9  803.41
  5021.7  803.91  5025.9  807.69  5034.3  804.38  5040.5  807.90  5048.9  804.91
  5055.2  806.75  5069.8  805.07  5125.1  808.55  5228.4  805.38  5824.0  818.50
#Mann=3,-1,0
  4471.5     0.1       0  5017.7    0.07       0  5021.7     0.1       0
Bank Sta=5017.7,5021.7
Exp/Cntr=0.3,0.1

Type RM Length L Ch R = 1,193,0,0,0
BEGIN DESCRIPTION:
UNT 125 in BCW 1.0
END DESCRIPTION:
XS GIS Cut Line= 4
      1973847.63     13630912.87      1973334.58     13631087.36
      1973240.83     13631550.90      1973475.19     13632045.66
#Sta/Elev= 30
  4322.5  831.37  4348.2  830.79  4494.3  820.92  4499.8  819.90  4505.0  820.22
  4525.8  818.44  4531.1  819.15  4557.2  816.49  4562.5  816.93  4588.6  814.58
  4593.9  815.14  4620.0  812.94  4656.6  811.72  4737.2  806.10  4808.2  804.09
  4964.0  803.01  4983.9  801.73  4992.6  798.19  4992.9  797.69  4996.6  798.19
  5004.8  798.38  5015.0  801.23  5106.9  803.29  5426.9  804.76  5540.6  806.34
  5619.9  809.66  5637.1  809.17  5682.6  810.29  5824.6  817.07  5884.8  817.61
#Mann=3,-1,0
  4322.5     0.1       0  4992.6    0.07       0  4996.6     0.1       0
Bank Sta=4992.6,4996.6
Exp/Cntr=0.3,0.1

Chan Stop Cuts=-1