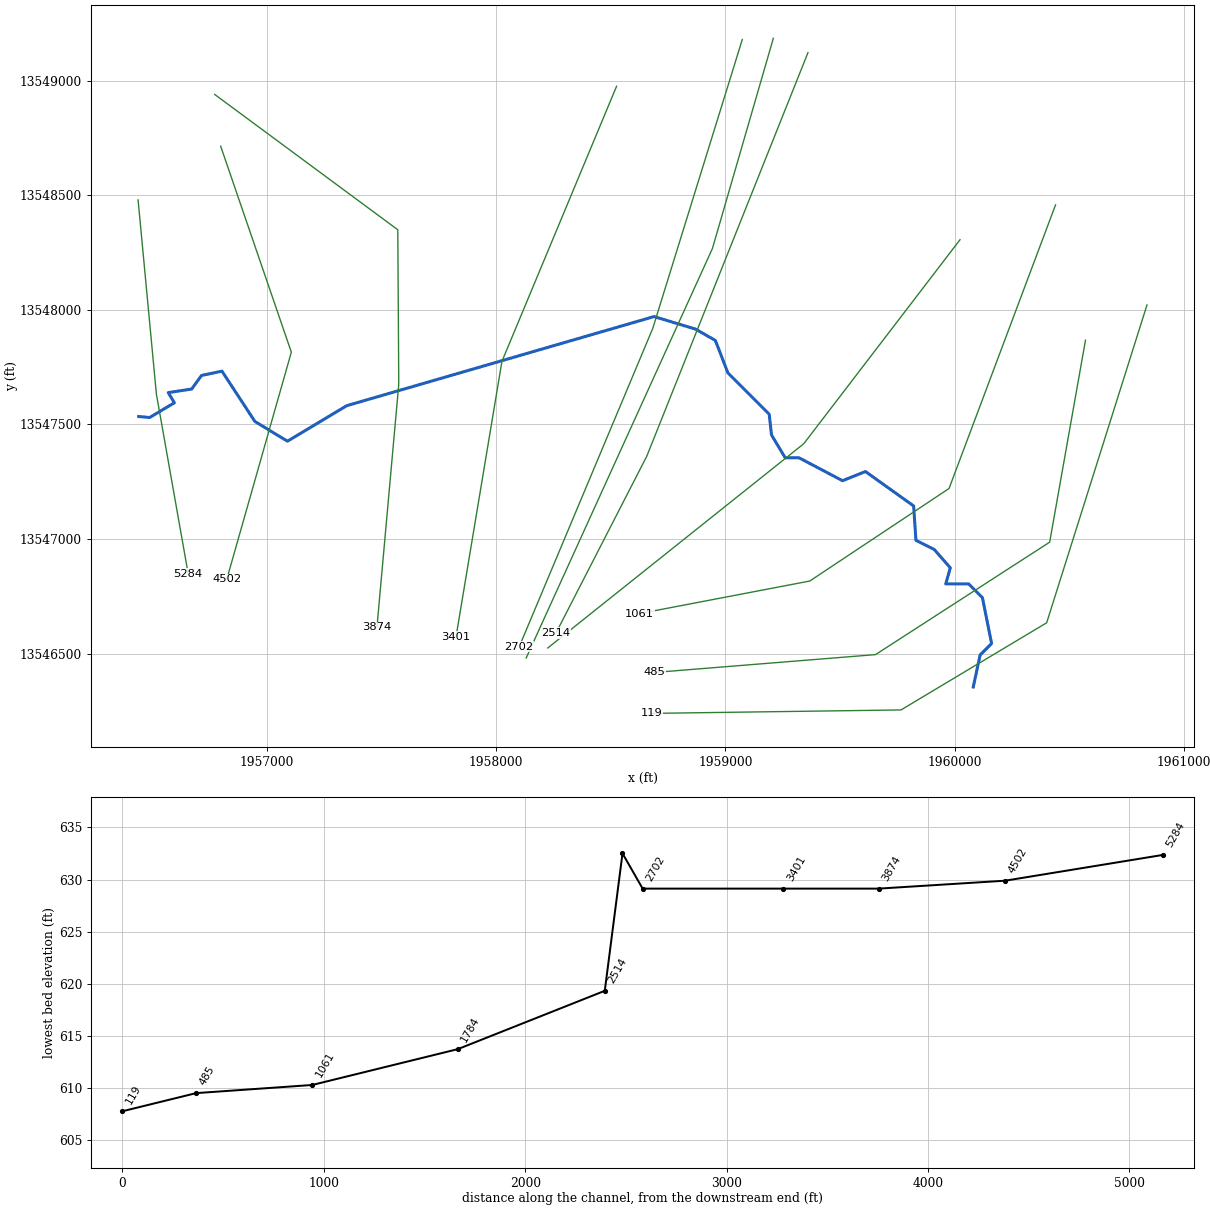
--- UNT 150 in BCW.prj (project) ---

Proj Title=UNT 150 in BCW Base Level Engineering
Current Plan=p01
Default Exp/Contr=0.3,0.1
English Units
Geom File=g01
Flow File=f01
Plan File=p01
Y Axis Title=Elevation
X Axis Title(PF)=Main Channel Distance
X Axis Title(XS)=Station
BEGIN DESCRIPTION:
UNT 150 in BCW
END DESCRIPTION:
DSS Export Rating Curves= 0
DSS Export Rating Curve Sorted= 0
DSS Export Volume Flow Curves= 0
DXF OffsetX= 0
DXF OffsetY= 0
DXF ScaleX= 1
DXF ScaleY= 10

--- UNT 150 in BCW.p01 (plan) ---

Plan Title=Multiple Run
Short Identifier=Multiple
Geom File=g01
Flow File=f01
Subcritical Flow
K Sum by GR= 0
Std Step Tol= 0.01
Critical Tol= 0.01
Num of Std Step Trials= 20
Max Error Tol= 0.3
Flow Tol Ratio= 0.001
Split Flow NTrial= 30
Split Flow Tol= 0.02
Split Flow Ratio= 0.02
Log Output Level= 0
Friction Slope Method= 1
Unsteady Friction Slope Method= 2
Unsteady Bridges Friction Slope Method= 1
Parabolic Critical Depth
Global Vel Dist=  1 , 1 , 1
Global Log Level= 0
CheckData=True
Encroach Param= -1, 0, 0, 0
BEGIN DESCRIPTION:
Multiple Run
END DESCRIPTION:

--- UNT 150 in BCW.f01 (steady flow) ---

Flow Title=Multiple
Number of Profiles=7
Profile Names=10-year,25-year,50-year,1pct_min,100-year,1pct_plu,500-year
River Rch & RM= UNT 150 in BCW,Reach-1,5284
     379     534     665     411     821    1637    1264
River Rch & RM= UNT 150 in BCW,Reach-1,2702
     796    1160    1474     927    1850    3692    2939
Boundary for River Rch & Prof#=UNT 150 in BCW,Reach-1,1
Up Type=0
Dn Type=3
Dn Slope=0.005
Boundary for River Rch & Prof#=UNT 150 in BCW,Reach-1,2
Up Type=0
Dn Type=3
Dn Slope=0.005
Boundary for River Rch & Prof#=UNT 150 in BCW,Reach-1,3
Up Type=0
Dn Type=3
Dn Slope=0.005
Boundary for River Rch & Prof#=UNT 150 in BCW,Reach-1,4
Up Type=0
Dn Type=3
Dn Slope=0.005
Boundary for River Rch & Prof#=UNT 150 in BCW,Reach-1,5
Up Type=0
Dn Type=3
Dn Slope=0.005
Boundary for River Rch & Prof#=UNT 150 in BCW,Reach-1,6
Up Type=0
Dn Type=3
Dn Slope=0.005
Boundary for River Rch & Prof#=UNT 150 in BCW,Reach-1,7
Up Type=0
Dn Type=3
Dn Slope=0.005

--- UNT 150 in BCW.g01 (geometry) ---

Geom Title=Existing Conditions
Program Version=5.05

River Reach=UNT 150 in BCW  ,Reach-1
Reach XY= 30
       1956440.8     13547534.54      1956488.69     13547530.28
      1956596.33     13547594.52      1956569.42     13547638.79
      1956671.85     13547654.42      1956714.39     13547713.44
      1956803.79     13547732.54      1956947.46     13547512.92
      1957089.39     13547426.98       1957348.5     13547581.93
      1958688.52     13547970.53       1958868.9     13547916.02
      1958955.88     13547866.54       1959010.8     13547724.54
       1959190.8     13547544.54       1959200.8     13547454.54
       1959260.8     13547354.54       1959320.8     13547354.54
       1959510.8     13547254.54       1959610.8     13547294.54
       1959820.8     13547144.54       1959830.8     13546994.54
       1959910.8     13546954.54       1959980.8     13546874.54
       1959960.8     13546804.54       1960060.8     13546804.54
       1960120.8     13546744.54       1960160.8     13546544.54
       1960110.8     13546494.54       1960080.8     13546354.54

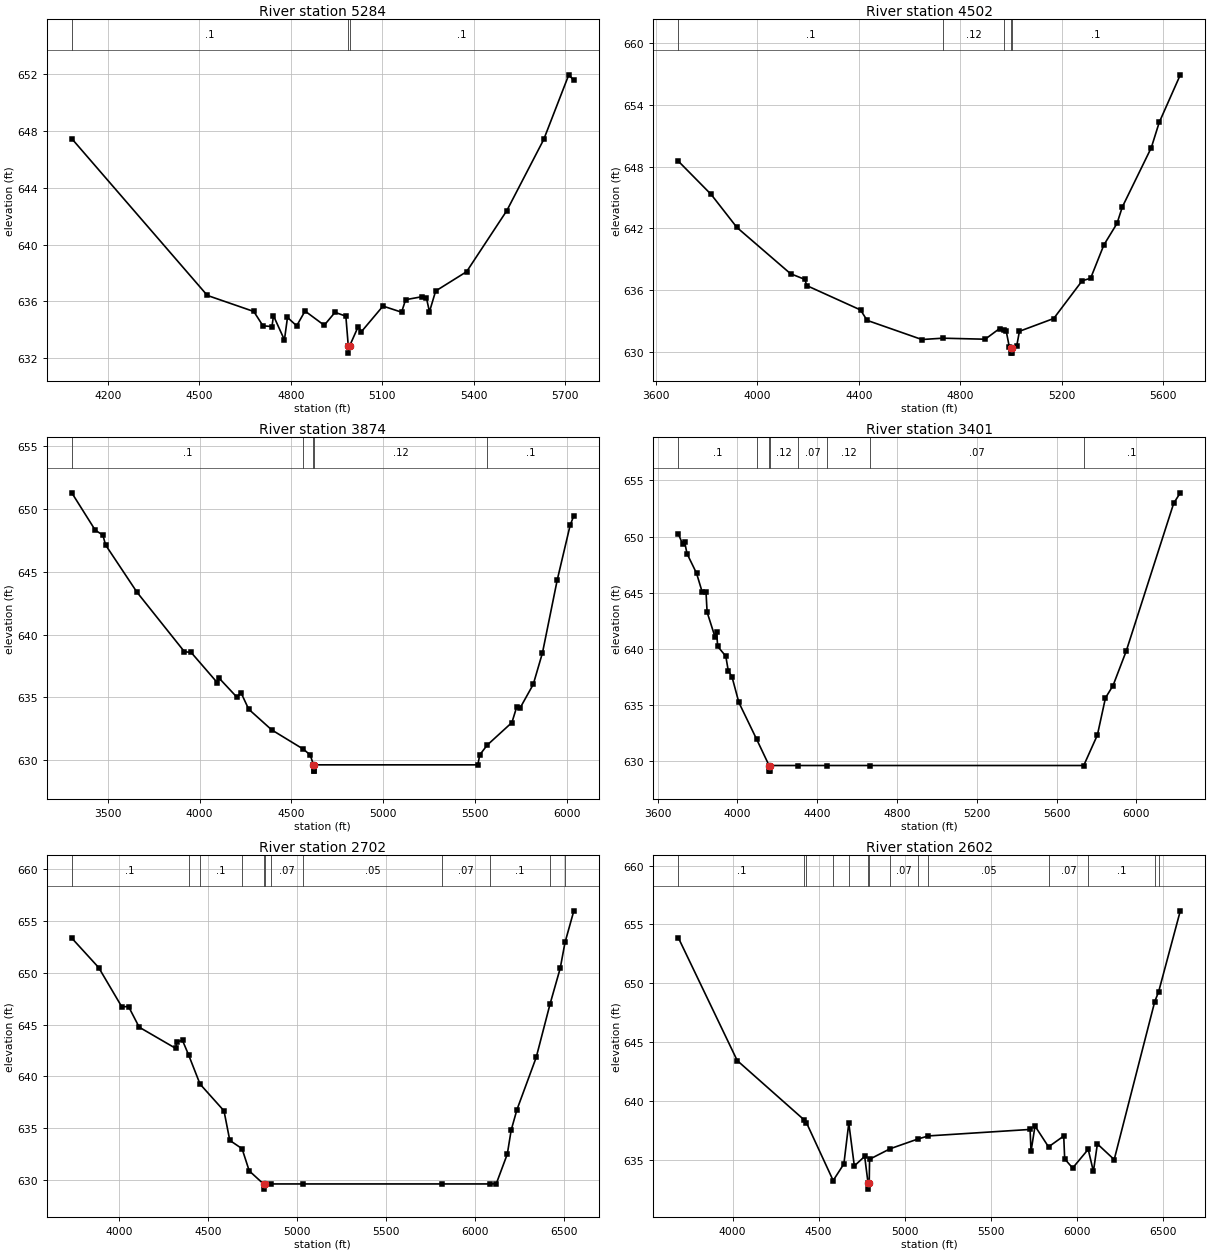
Type RM Length L Ch R = 1 ,5284    ,782,782,782
BEGIN DESCRIPTION:
UNT 150 in BCW 10.0
END DESCRIPTION:
XS GIS Cut Line= 3
      1956437.98     13548479.27      1956517.84     13547632.07
      1956656.49      13546848.7
#Sta/Elev= 30
  4081.5  647.45    4526  636.42  4678.4  635.29  4708.5  634.28    4738  634.23
    4743  634.99  4778.9  633.29  4788.9  634.87    4819  634.28  4846.5  635.32
  4909.4  634.32  4944.8  635.23  4980.3  634.96  4988.3  632.86  4988.6  632.36
  4992.6  632.86  5020.9  634.23    5031  633.86  5102.1  635.67  5163.1  635.24
  5176.3  636.12  5230.4  636.33  5244.3  636.27  5254.5  635.27  5274.8  636.73
  5376.3  638.09  5508.3  642.39  5629.2  647.39  5711.4  651.94    5728  651.55
#Mann= 3 ,-1 , 0
  4081.5      .1       0  4988.3     .07       0  4992.6      .1       0
Bank Sta=4988.3,4992.6
XS Rating Curve= 0 ,0
Exp/Cntr=0.3,0.1

Type RM Length L Ch R = 1 ,4502    ,628,628,628
BEGIN DESCRIPTION:
UNT 150 in BCW 9.0
END DESCRIPTION:
XS GIS Cut Line= 3
      1956798.21      13548713.7      1957106.38     13547815.23
        1956825.     13546824.99
#Sta/Elev= 30
  3687.9  648.53  3817.7  645.29  3919.1  642.09  4130.5   637.6  4187.6  637.04
    4194  636.45  4406.5  634.08  4432.5  633.07  4648.4  631.21  4730.8  631.34
  4897.9  631.24  4954.4  632.27  4972.3   632.1  4981.1     632  4993.5  630.44
  4999.7  630.39    5000  629.89  5003.7  629.89    5004  630.39  5022.2  630.58
    5033  632.01  5168.1  633.25  5280.2  636.91  5313.7  637.16  5365.7  640.38
  5417.7  642.48  5438.5  644.07  5552.8  649.83    5584  652.28  5667.2   656.9
#Mann= 5 ,-1 , 0
  3687.9      .1       0  4730.8     .12       0  4972.3      .1       0
  4999.7     .07       0    5004      .1       0
Bank Sta=4999.7,5004
XS Rating Curve= 0 ,0
Exp/Cntr=0.3,0.1

Type RM Length L Ch R = 1 ,3874    ,473,473,473
BEGIN DESCRIPTION:
UNT 150 in BCW 8.0
END DESCRIPTION:
XS GIS Cut Line= 4
      1956772.19     13548939.36      1957570.79     13548349.09
        1957575.       13547675.      1957479.82     13546614.94
#Sta/Elev= 30
  3304.6  651.29  3432.2  648.32  3473.9  647.92  3488.5  647.14  3659.7  643.37
  3917.4  638.64  3954.1  638.58    4096  636.18  4103.9  636.57  4203.4  635.01
  4225.5  635.37  4267.2  634.06  4391.8  632.42  4564.3  630.88  4601.8  630.42
  4619.5  629.63  4619.8  629.13  4623.7  629.13    4624  629.63  5513.9  629.63
    5524  630.42  5564.6   631.2  5699.2     633  5724.8  634.22  5744.9  634.19
  5815.3  636.04  5865.4  638.55  5945.7  644.35    6016  648.71  6036.1  649.47
#Mann= 5 ,-1 , 0
  3304.6      .1       0  4564.3     .12       0  4619.5     .07       0
    4624     .12       0  5564.6      .1       0
Bank Sta=4619.5,4624
XS Rating Curve= 0 ,0
Exp/Cntr=0.3,0.1

Type RM Length L Ch R = 1 ,3401    ,699,699,699
BEGIN DESCRIPTION:
UNT 150 in BCW 7.0
END DESCRIPTION:
XS GIS Cut Line= 3
      1958525.01     13548975.03        1958025.       13547775.
        1957825.     13546574.99
#Sta/Elev= 30
  3703.8  650.27  3725.5  649.34  3736.3   649.5  3747.7  648.49  3795.4  646.75
  3824.6  645.03    3843  645.07  3848.5  643.28    3888  641.08  3896.1   641.5
  3901.5  640.23  3942.2  639.36  3954.6  638.06    3973  637.54  4007.7  635.24
  4096.4  631.98  4159.2  629.63  4159.5  629.13  4163.5  629.13  4163.9  629.63
  4306.5  629.63  4449.9  629.63  4665.8  629.63  5736.3  629.63  5804.7  632.34
  5845.3  635.65  5883.3  636.75  5949.2  639.81  6187.4  652.98  6220.4   653.9
#Mann= 8 ,-1 , 0
  3703.8      .1       0  4096.4     .12       0  4159.2     .07       0
  4163.9     .12       0  4306.5     .07       0  4449.9     .12       0
  4665.8     .07       0  5736.3      .1       0
Bank Sta=4159.2,4163.9
XS Rating Curve= 0 ,0
Exp/Cntr=0.3,0.1

Type RM Length L Ch R = 1 ,2702    ,100,100,100
BEGIN DESCRIPTION:
UNT 150 in BCW 6.0
END DESCRIPTION:
XS GIS Cut Line= 3
      1959073.39     13549178.93      1958682.77     13547918.53
      1958100.16     13546529.62
#Sta/Elev= 30
  3731.9  653.34  3883.2   650.5  4013.5  646.71  4051.4  646.74  4111.3  644.75
  4317.3   642.7  4322.6  643.34  4355.2  643.47  4389.3  642.08  4453.8  639.26
  4588.6  636.68  4621.2  633.83  4690.3  633.03  4730.6  630.89    4811  629.63
  4811.5  629.13  4817.6  629.63  4853.6  629.63  5034.9  629.63  5812.9  629.63
  6084.5  629.63    6121  629.65  6183.1  632.51  6204.8  634.81  6237.3  636.79
  6345.7  641.83    6423  646.94  6480.9  650.43  6507.9  652.92  6557.6  655.97
#Mann= 12 ,-1 , 0
  3731.9      .1       0  4389.3     .05       0  4453.8      .1       0
  4690.3     .12       0    4811     .07       0  4817.6     .12       0
  4853.6     .07       0  5034.9     .05       0  5812.9     .07       0
  6084.5      .1       0    6423     .16       0  6507.9      .1       0
Bank Sta=4811,4817.6
XS Rating Curve= 0 ,0
Exp/Cntr=0.3,0.1

Type RM Length L Ch R = 1 ,2602    ,88,88,88
BEGIN DESCRIPTION:
UNT 150 in BCW 5.0
END DESCRIPTION:
XS GIS Cut Line= 3
      1959208.81     13549184.14      1958943.19     13548267.49
      1958130.69     13546481.04
#Sta/Elev= 30
  3684.5  653.88  4027.2  643.43  4416.9  638.38  4429.1  638.16  4584.6  633.24
  4646.8  634.65  4675.4  638.12  4707.5  634.48  4767.6  635.29  4787.4  633.01
  4787.9  632.51    4794  633.01  4796.2  635.05  4915.7  635.94  5077.4  636.77
  5137.8  637.03  5728.6  637.58  5734.1  635.71  5757.2  637.87  5835.8   636.1
  5924.1  637.02  5929.6  635.08  5975.7   634.3  6066.3  635.89  6096.5  634.01
  6119.6  636.35  6217.3  635.02  6452.9  648.44  6475.7  649.29  6601.4  656.15
#Mann= 14 ,-1 , 0
  3684.5      .1       0  4416.9     .05       0  4429.1      .1       0
  4584.6     .05       0  4675.4      .1       0  4787.4     .07       0
    4794      .1       0  4915.7     .07       0  5077.4      .1       0
  5137.8     .05       0  5835.8     .07       0  6066.3      .1       0
  6452.9     .16       0  6475.7      .1       0
Bank Sta=4787.4,4794
XS Rating Curve= 0 ,0
Exp/Cntr=0.3,0.1

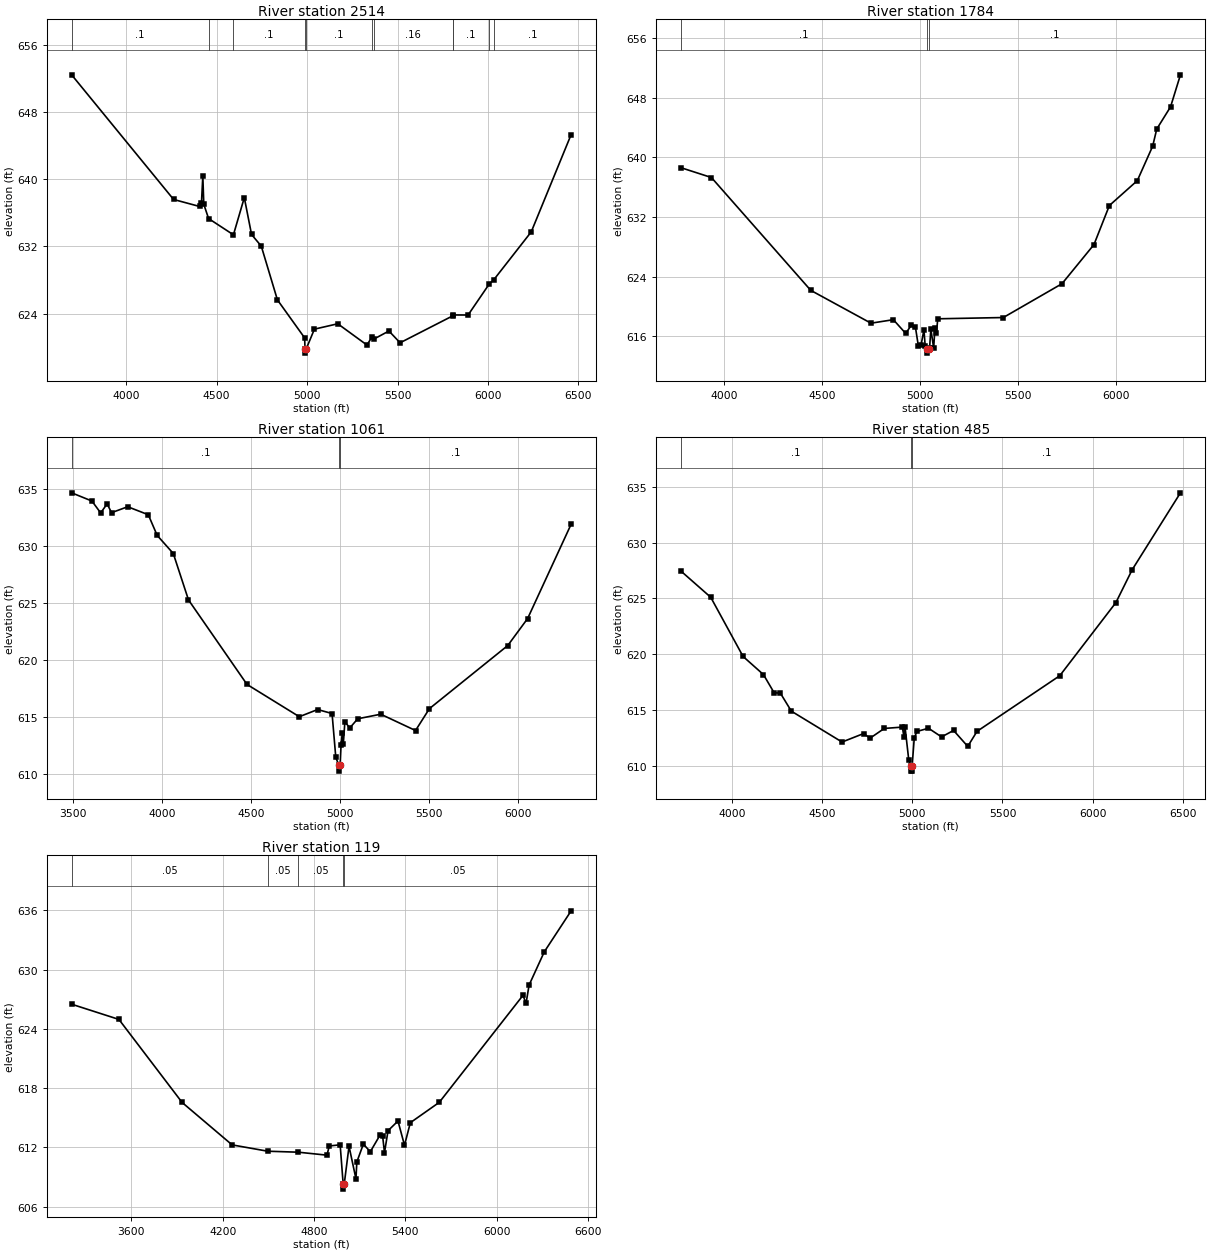
Type RM Length L Ch R = 1 ,2514    ,730,730,730
BEGIN DESCRIPTION:
UNT 150 in BCW 4.0
END DESCRIPTION:
XS GIS Cut Line= 3
      1959359.87      13549121.7      1958656.73     13547361.24
       1958260.9     13546590.41
#Sta/Elev= 30
    3698  652.41  4261.8  637.59  4405.1  636.76  4415.9  637.15  4423.4  640.36
  4428.8  637.02  4455.3  635.32  4592.7  633.39  4652.8  637.81  4692.8  633.43
  4746.7  632.04  4835.9  625.65  4986.5  621.13  4988.6  619.82  4989.1  619.32
  4995.2  619.82  5040.4  622.17  5169.7  622.81  5331.2  620.28  5358.4  621.24
  5369.2  620.99  5452.6  621.95  5514.3  620.55  5805.2  623.75  5806.6  623.86
  5890.2  623.85    6008  627.56  6031.9  628.03  6239.6  633.74  6460.2  645.31
#Mann= 11 ,-1 , 0
    3698      .1       0  4455.3     .05       0  4592.7      .1       0
  4988.6     .07       0  4995.2      .1       0  5358.4     .05       0
  5369.2     .16       0  5805.2     .05       0  5806.6      .1       0
    6008     .07       0  6031.9      .1       0
Bank Sta=4988.6,4995.2
XS Rating Curve= 0 ,0
Exp/Cntr=0.3,0.1

Type RM Length L Ch R = 1 ,1784    ,723,723,723
BEGIN DESCRIPTION:
UNT 150 in BCW 3.0
END DESCRIPTION:
XS GIS Cut Line= 3
      1960023.02     13548305.65      1959341.63     13547415.93
      1958224.98     13546524.98
#Sta/Elev= 30
  3780.9  638.62  3936.5   637.3  4443.4  622.15  4750.8  617.74    4865  618.21
  4928.2  616.36    4957   617.5  4977.8  617.18  4992.2  614.74  5006.6  614.84
  5021.1  616.86  5027.4  614.65  5038.5  614.22    5039  613.72  5045.2  614.22
  5049.9   614.4  5056.3  616.96  5070.7  614.39  5077.1  617.07  5085.1  616.44
  5091.5  618.33  5426.2   618.5  5725.6  623.04  5888.9   628.3  5967.4  633.54
  6109.9  636.88  6188.4  641.51  6209.2  643.81  6279.6  646.79  6330.1  651.09
#Mann= 3 ,-1 , 0
  3780.9      .1       0  5038.5     .07       0  5045.2      .1       0
Bank Sta=5038.5,5045.2
XS Rating Curve= 0 ,0
Exp/Cntr=0.3,0.1

Type RM Length L Ch R = 1 ,1061    ,576,576,576
BEGIN DESCRIPTION:
UNT 150 in BCW 2.0
END DESCRIPTION:
XS GIS Cut Line= 4
      1960439.73     13548457.61      1959975.31     13547220.61
      1959367.67     13546816.97      1958625.01       13546675.
#Sta/Elev= 30
  3493.2  634.68  3607.2  633.96  3656.2  632.92  3692.6  633.71  3717.5  632.94
  3808.2  633.46  3923.9  632.76  3973.7  630.95  4064.4  629.36  4149.8  625.29
  4478.7  617.88  4772.6  615.05  4875.4  615.68  4956.6  615.33  4977.6  611.48
  4995.2  610.78  4995.7  610.28    5002  610.78    5007  612.54  5013.7  613.58
  5019.7  612.65  5028.7  614.62  5055.8  614.06  5100.9  614.87  5230.2  615.27
  5425.6  613.84  5503.8  615.76  5943.8  621.29  6055.6  623.66  6300.1  631.93
#Mann= 3 ,-1 , 0
  3493.2      .1       0  4995.2     .07       0    5002      .1       0
Bank Sta=4995.2,5002
XS Rating Curve= 0 ,0
Exp/Cntr=0.3,0.1

Type RM Length L Ch R = 1 ,485     ,366,366,366
BEGIN DESCRIPTION:
Mapping XS da6fbc34
END DESCRIPTION:
XS GIS Cut Line= 4
      1960570.38     13547867.57      1960414.13     13546986.51
      1959654.58     13546496.06      1958688.37     13546418.07
#Sta/Elev= 30
    3718  627.45  3883.1   625.1  4062.3  619.79  4175.4  618.16  4234.5  616.53
    4269   616.5    4330  614.88    4611  612.11  4730.1  612.87  4766.4  612.46
    4845  613.33  4945.1  613.45  4953.8  612.59  4959.8  613.48  4980.9  610.46
  4992.7     610  4993.2   609.5    4999   609.5  4999.5     610  5011.2   612.5
  5026.4  613.06  5089.8  613.35  5162.4  612.57    5229  613.15  5307.5  611.72
    5359  613.07  5817.5  618.06  6128.5  624.62  6218.8  627.57  6486.3  634.47
#Mann= 3 ,-1 , 0
    3718      .1       0  4992.7     .07       0  4999.5      .1       0
Bank Sta=4992.7,4999.5
XS Rating Curve= 0 ,0
Exp/Cntr=0.3,0.1

Type RM Length L Ch R = 1 ,119     ,0,0,0
BEGIN DESCRIPTION:
UNT 150 in BCW 1.0
END DESCRIPTION:
XS GIS Cut Line= 4
      1960838.61     13548021.24      1960401.11     13546634.95
      1959765.69     13546254.74      1958678.76     13546239.73
#Sta/Elev= 30
    3208  626.49  3518.6  624.95  3933.6  616.54  4262.3  612.24  4496.2   611.6
  4697.8   611.5    4885   611.2  4900.5  612.13  4971.8  612.25  4991.7  608.26
  4992.2  607.76  4998.5  608.26  5030.1   612.1  5075.6   608.8  5081.4  610.51
  5124.2  612.32  5169.9  611.55  5235.1  613.27  5250.6  613.16  5263.1  611.46
  5286.4  613.68  5351.8  614.66  5394.5   612.2  5432.9  614.49  5622.9  616.55
  6172.9  627.39  6192.9  626.57  6212.9  628.43  6312.9   631.8  6489.2  635.95
#Mann= 5 ,-1 , 0
    3208     .05       0  4496.2     .05       0  4697.8     .05       0
  4991.7     .03       0  4998.5     .05       0
Bank Sta=4991.7,4998.5
XS Rating Curve= 0 ,0
Exp/Cntr=0.3,0.1
LCMann Table=0

Chan Stop Cuts=-1
Use User Specified Reach Order=0
Composite Channel Slope=5