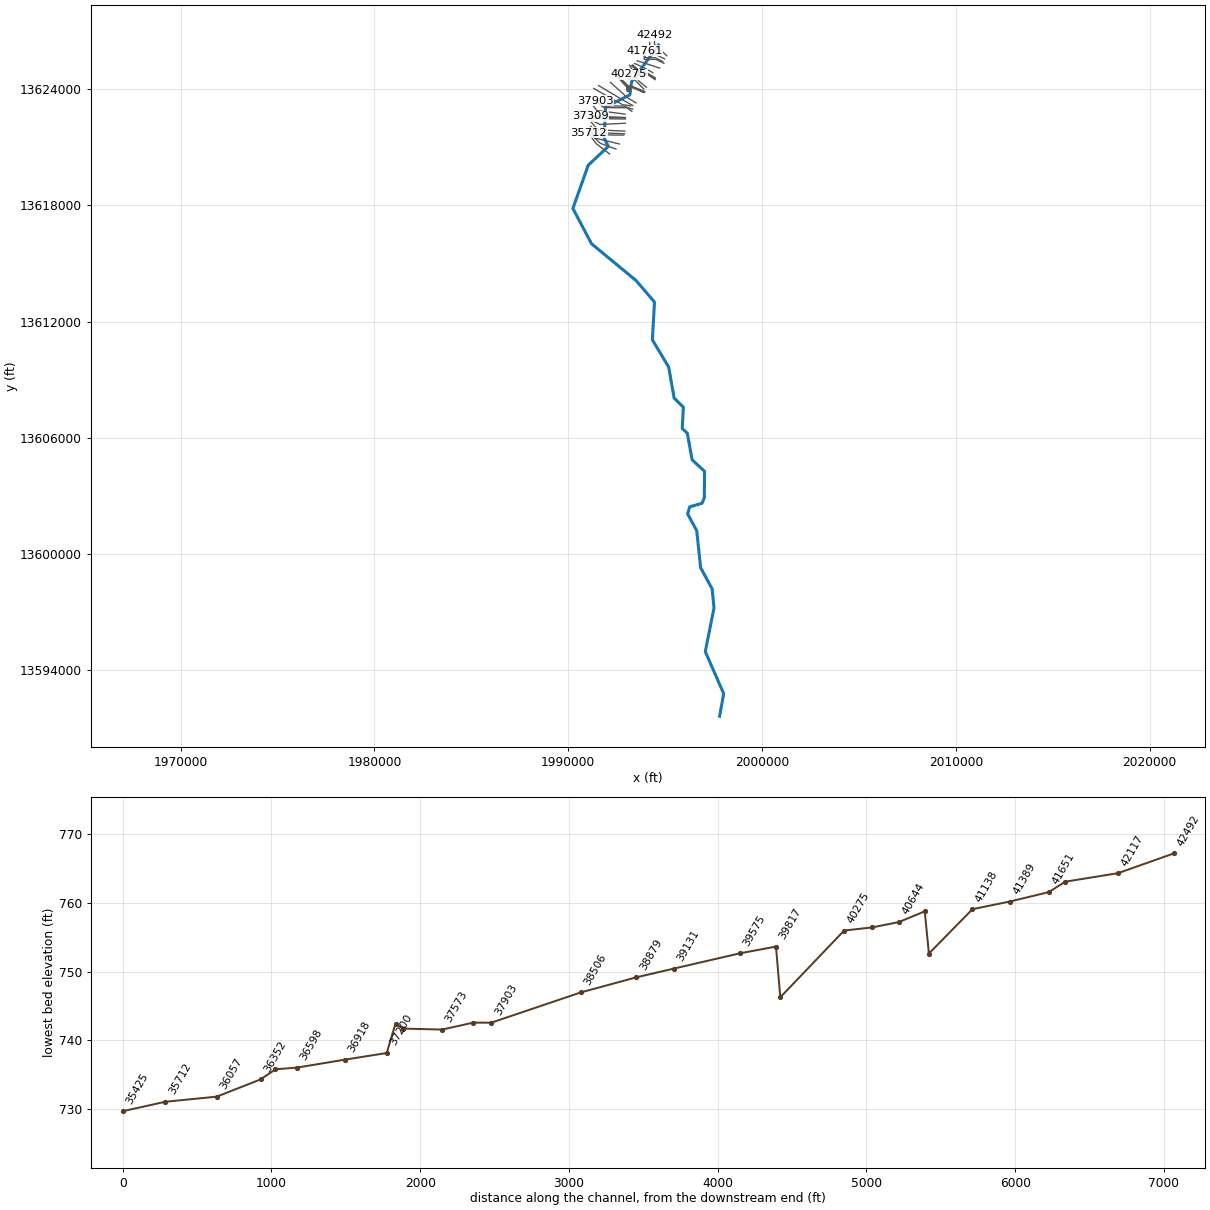
--- BURNT BOOT CREEK.prj (project) ---

Proj Title=BURNT BOOT CREEK Base Level Engineering
Current Plan=p01
Default Exp/Contr=0.3,0.1
English Units
Geom File=g01
Flow File=f01
Plan File=p01
Y Axis Title=Elevation
X Axis Title(PF)=Main Channel Distance
X Axis Title(XS)=Station
BEGIN DESCRIPTION:
BURNT BOOT CREEK
END DESCRIPTION:
DSS Export Rating Curves= 0
DSS Export Rating Curve Sorted= 0
DSS Export Volume Flow Curves= 0
DXF OffsetX= 0
DXF OffsetY= 0
DXF ScaleX= 1
DXF ScaleY= 10

--- BURNT BOOT CREEK.p01 (plan) ---

Plan Title=Multiple Run
Short Identifier=Multiple
Geom File=g01
Flow File=f01
Subcritical Flow
K Sum by GR= 0
Std Step Tol= 0.01
Critical Tol= 0.01
Num of Std Step Trials= 20
Max Error Tol= 0.3
Flow Tol Ratio= 0.001
Split Flow NTrial= 30
Split Flow Tol= 0.02
Split Flow Ratio= 0.02
Log Output Level= 0
Friction Slope Method= 1
Unsteady Friction Slope Method= 2
Unsteady Bridges Friction Slope Method= 1
Parabolic Critical Depth
Global Vel Dist=  1 , 1 , 1
Global Log Level= 0
CheckData=True
Encroach Param= -1, 0, 0, 0
BEGIN DESCRIPTION:
Multiple Run
END DESCRIPTION:

--- BURNT BOOT CREEK.f01 (steady flow) ---

Flow Title=Multiple
Program Version=5.05
Number of Profiles= 7
Profile Names=10-year,25-year,50-year,1pct_min,100-year,1pct_plu,500-year
River Rch & RM=BURNT BOOT CREEK,Reach-1         ,42492
     492     683     839     511    1019    2033    1508
River Rch & RM=BURNT BOOT CREEK,Reach-1         ,30549
     713    1008    1255     772    1541    3075    2333
River Rch & RM=BURNT BOOT CREEK,Reach-1         ,25093
    1127    1629    2058    1283    2560    5108    3983
River Rch & RM=BURNT BOOT CREEK,Reach-1         ,23720
    1127    1629    2058    1283    2560    5108    3983
River Rch & RM=BURNT BOOT CREEK,Reach-1         ,18385
    1259    1830    2321    1452    2898    5782    4539
River Rch & RM=BURNT BOOT CREEK,Reach-1         ,16869
    1434    2095    2667    1674    3340    6663    5265
River Rch & RM=BURNT BOOT CREEK,Reach-1         ,15098
    1538    2249    2863    1797    3585    7153    5651
River Rch & RM=BURNT BOOT CREEK,Reach-1         ,9312
    1667    2445    3118    1961    3912    7805    6187
River Rch & RM=BURNT BOOT CREEK,Reach-1         ,6435
    1949    2874    3679    2320    4629    9237    7368
Boundary for River Rch & Prof#=BURNT BOOT CREEK,Reach-1         , 1
Up Type= 0
Dn Type= 3
Dn Slope=0.005
Boundary for River Rch & Prof#=BURNT BOOT CREEK,Reach-1         , 2
Up Type= 0
Dn Type= 3
Dn Slope=0.005
Boundary for River Rch & Prof#=BURNT BOOT CREEK,Reach-1         , 3
Up Type= 0
Dn Type= 3
Dn Slope=0.005
Boundary for River Rch & Prof#=BURNT BOOT CREEK,Reach-1         , 4
Up Type= 0
Dn Type= 3
Dn Slope=0.005
Boundary for River Rch & Prof#=BURNT BOOT CREEK,Reach-1         , 5
Up Type= 0
Dn Type= 3
Dn Slope=0.005
Boundary for River Rch & Prof#=BURNT BOOT CREEK,Reach-1         , 6
Up Type= 0
Dn Type= 3
Dn Slope=0.005
Boundary for River Rch & Prof#=BURNT BOOT CREEK,Reach-1         , 7
Up Type= 0
Dn Type= 3
Dn Slope=0.005
DSS Import GetInterval= 0
DSS Import GetPeak= 0
DSS Import FillOption= 0

--- BURNT BOOT CREEK.g01 (geometry) ---

Geom Title=Existing Conditions

River Reach=BURNT BOOT CREEK,Reach-1
Reach XY= 30
      1994661.44     13626270.54      1993270.80     13624374.54
      1993180.80     13623694.54      1991930.67     13623071.04
      1991850.80     13621474.54      1992066.30     13621035.45
      1991030.80     13620064.54      1990240.80     13617834.54
      1991200.80     13616014.54      1993490.80     13614124.54
      1994450.80     13613004.54      1994341.80     13611054.75
      1995180.80     13609654.54      1995463.76     13608054.54
      1995940.11     13607579.28      1995882.89     13606481.45
      1996142.44     13606237.63      1996392.63     13604862.71
      1997034.37     13604272.65      1997020.80     13602904.54
      1996906.76     13602624.21      1996266.14     13602438.01
      1996159.23     13602075.64      1996629.02     13601208.75
      1996830.80     13599304.54      1997425.30     13598202.99
      1997520.80     13597224.54      1997070.80     13594974.54
      1998020.80     13592804.54      1997810.80     13591634.54

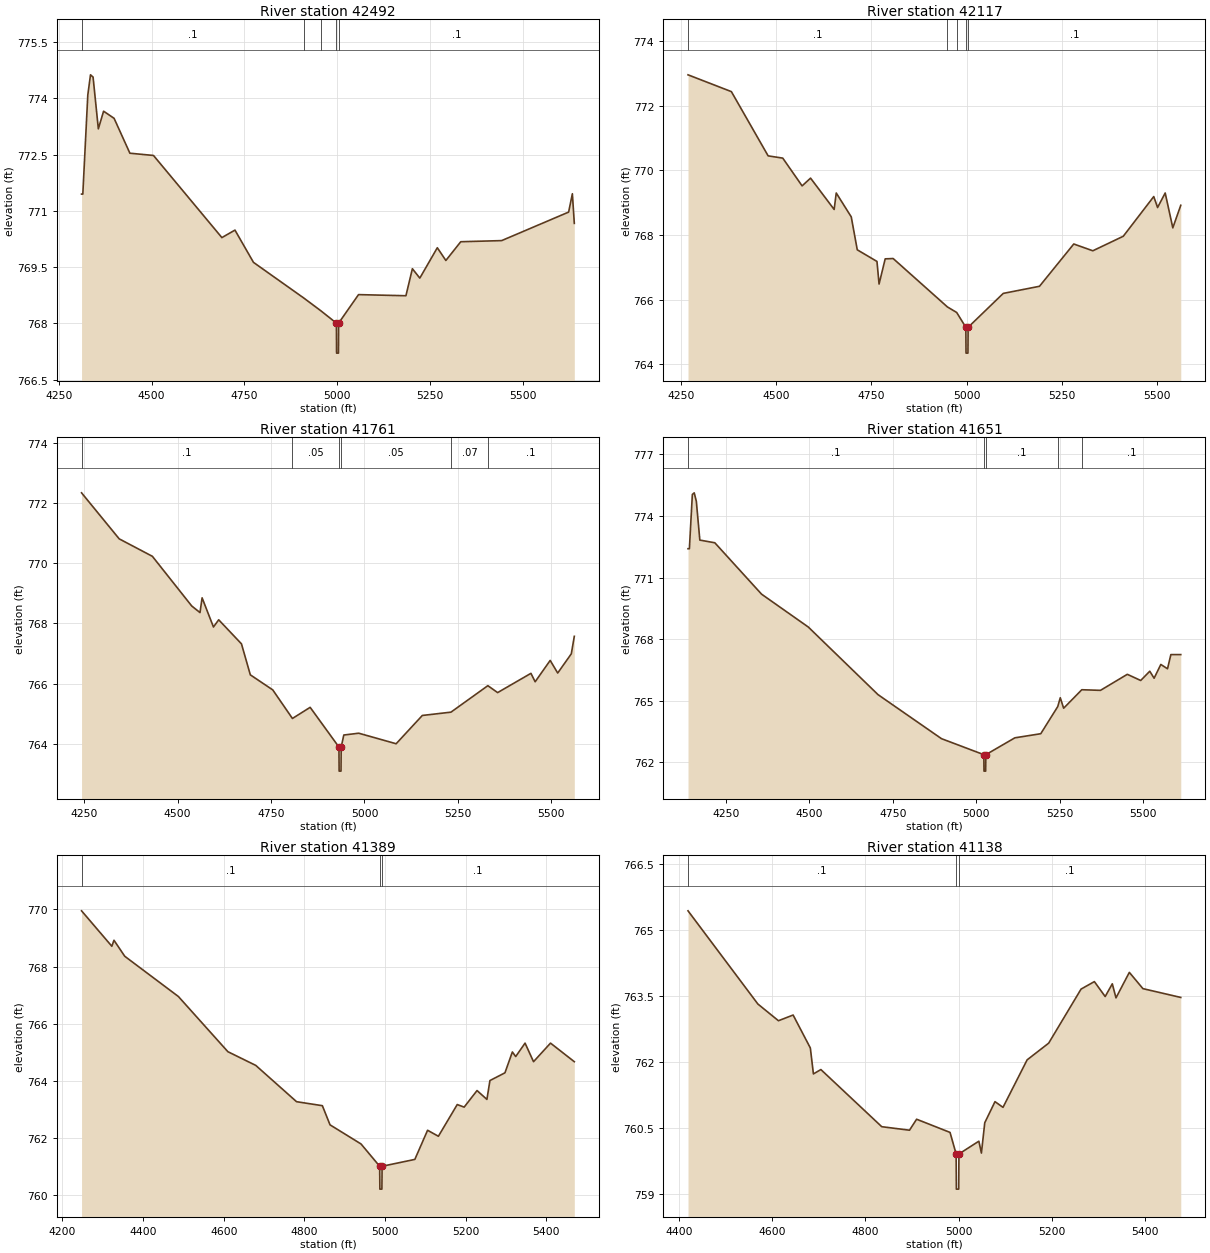
Type RM Length L Ch R = 1,42492,375,375,375
BEGIN DESCRIPTION:
BURNT BOOT CREEK 73.0
END DESCRIPTION:
XS GIS Cut Line= 4
      1995084.96     13625711.02      1994616.10     13626151.94
      1994445.77     13626311.93      1994468.86     13626760.23
#Sta/Elev= 30
  4311.5  771.45  4314.9  771.45  4328.3  774.09  4335.6  774.63  4342.5  774.57
  4356.7  773.19  4370.8  773.66  4399.1  773.47  4441.6  772.54  4505.1  772.48
  4689.2  770.29  4724.4  770.49  4774.2  769.63  4909.5  768.68  4955.4  768.34
  4997.4  768.01  4997.9  767.21  5002.9  767.21  5003.4  768.01  5057.0  768.77
  5184.5  768.74  5201.9  769.46  5221.9  769.21  5269.0  770.02  5292.0  769.68
  5332.1  770.18  5442.2  770.21  5622.4  770.97  5632.5  771.46  5637.7  770.67
#Mann=5,-1,0
  4311.5     0.1       0  4909.5    0.07       0  4955.4     0.1       0
  4997.4    0.07       0  5003.4     0.1       0
Bank Sta=4997.4,5003.4
Exp/Cntr=0.3,0.1

Type RM Length L Ch R = 1,42117,356,356,356
BEGIN DESCRIPTION:
BURNT BOOT CREEK 72.0
END DESCRIPTION:
XS GIS Cut Line= 4
      1994973.77     13625550.62      1994516.61     13625775.22
      1994204.11     13625992.23      1994204.11     13626395.92
#Sta/Elev= 30
  4268.4  772.96  4382.2  772.44  4478.7  770.45  4517.1  770.38  4567.9  769.52
  4590.1  769.76  4652.0  768.79  4657.5  769.30  4696.9  768.56  4712.7  767.54
  4764.4  767.18  4769.9  766.48  4786.0  767.26  4806.9  767.27  4949.4  765.77
  4973.6  765.60  4997.7  765.14  4998.2  764.34  5003.2  764.34  5003.7  765.14
  5095.9  766.19  5191.0  766.41  5281.0  767.72  5331.0  767.51  5411.0  767.96
  5491.0  769.19  5501.0  768.85  5521.0  769.30  5541.0  768.22  5561.9  768.92
#Mann=5,-1,0
  4268.4     0.1       0  4949.4    0.07       0  4973.6     0.1       0
  4997.7    0.07       0  5003.7     0.1       0
Bank Sta=4997.7,5003.7
Exp/Cntr=0.3,0.1

Type RM Length L Ch R = 1,41761,110,110,110
BEGIN DESCRIPTION:
BURNT BOOT CREEK 71.0
END DESCRIPTION:
XS GIS Cut Line= 4
      1994878.70     13625413.51      1994496.30     13625610.28
      1993974.05     13625615.29      1993939.36     13625979.20
#Sta/Elev= 30
  4243.3  772.34  4344.0  770.81  4432.7  770.23  4537.9  768.58  4560.1  768.36
  4565.7  768.85  4596.1  767.88  4610.1  768.12  4671.0  767.32  4694.7  766.29
  4754.7  765.79  4807.3  764.84  4854.7  765.21  4931.7  763.89  4932.2  763.09
  4937.2  763.09  4937.7  763.89  4944.7  764.29  4984.7  764.35  5084.7  764.00
  5154.7  764.94  5231.3  765.05  5330.0  765.93  5356.1  765.70  5445.2  766.34
  5456.5  766.06  5496.7  766.77  5516.8  766.35  5553.2  766.99  5561.2  767.57
#Mann=6,-1,0
  4243.3     0.1       0  4807.3    0.05       0  4931.7    0.04       0
  4937.7    0.05       0  5231.3    0.07       0  5330.0     0.1       0
Bank Sta=4931.7,4937.7
Exp/Cntr=0.3,0.1

Type RM Length L Ch R = 1,41651,262,262,262
BEGIN DESCRIPTION:
BURNT BOOT CREEK 70.0
END DESCRIPTION:
XS GIS Cut Line= 4
      1994937.32     13625322.06      1994531.03     13625523.47
      1993930.67     13625523.47      1993891.61     13625944.54
#Sta/Elev= 30
  4136.3  772.40  4140.4  772.40  4149.3  775.04  4154.9  775.12  4161.2  774.71
  4171.7  772.82  4216.6  772.69  4356.7  770.19  4496.8  768.59  4705.8  765.30
  4895.8  763.16  5022.8  762.38  5023.3  761.58  5028.3  761.58  5028.8  762.38
  5115.8  763.20  5193.4  763.40  5244.3  764.72  5251.9  765.15  5262.0  764.64
  5316.4  765.54  5372.4  765.51  5452.8  766.29  5492.9  765.99  5520.1  766.44
  5533.1  766.10  5553.2  766.77  5573.3  766.56  5583.3  767.25  5613.0  767.25
#Mann=5,-1,0
  4136.3     0.1       0  5022.8    0.07       0  5028.8     0.1       0
  5244.3    0.05       0  5316.4     0.1       0
Bank Sta=5022.8,5028.8
Exp/Cntr=0.3,0.1

Type RM Length L Ch R = 1,41389,251,251,251
BEGIN DESCRIPTION:
Mapping XS afe026e7
END DESCRIPTION:
XS GIS Cut Line= 2
      1994720.98     13625076.64      1993558.88     13625453.89
#Sta/Elev= 30
  4247.5  769.95  4322.6  768.71  4327.9  768.92  4354.6  768.36  4487.7  766.95
  4610.3  765.02  4679.5  764.54  4780.6  763.27  4844.6  763.13  4863.6  762.46
  4940.5  761.79  4986.7  761.01  4987.2  760.21  4992.2  760.21  4992.7  761.01
  5073.9  761.25  5105.5  762.27  5132.3  762.06  5179.0  763.17  5196.2  763.08
  5228.1  763.66  5252.6  763.35  5260.1  764.01  5297.3  764.28  5315.7  765.01
  5324.0  764.85  5347.2  765.32  5368.2  764.67  5410.3  765.32  5469.3  764.67
#Mann=3,-1,0
  4247.5     0.1       0  4986.7    0.07       0  4992.7     0.1       0
Bank Sta=4986.7,4992.7
Exp/Cntr=0.3,0.1

Type RM Length L Ch R = 1,41138,293,293,293
BEGIN DESCRIPTION:
BURNT BOOT CREEK 69.0
END DESCRIPTION:
XS GIS Cut Line= 3
      1994365.25     13624839.72      1993847.87     13625124.46
      1993420.81     13625315.99
#Sta/Elev= 30
  4418.9  765.43  4569.0  763.31  4613.2  762.93  4644.7  763.06  4681.7  762.31
  4688.3  761.72  4704.3  761.82  4835.1  760.52  4894.7  760.44  4910.0  760.69
  4981.8  760.39  4994.9  759.90  4995.4  759.10  5000.4  759.10  5000.9  759.90
  5043.7  760.19  5049.2  759.92  5056.4  760.61  5078.4  761.09  5095.6  760.96
  5147.4  762.04  5193.7  762.42  5263.3  763.65  5291.9  763.82  5315.1  763.48
  5330.4  763.77  5338.3  763.45  5367.0  764.03  5396.2  763.66  5477.5  763.46
#Mann=3,-1,0
  4418.9     0.1       0  4994.9    0.07       0  5000.9     0.1       0
Bank Sta=4994.9,5000.9
Exp/Cntr=0.3,0.1

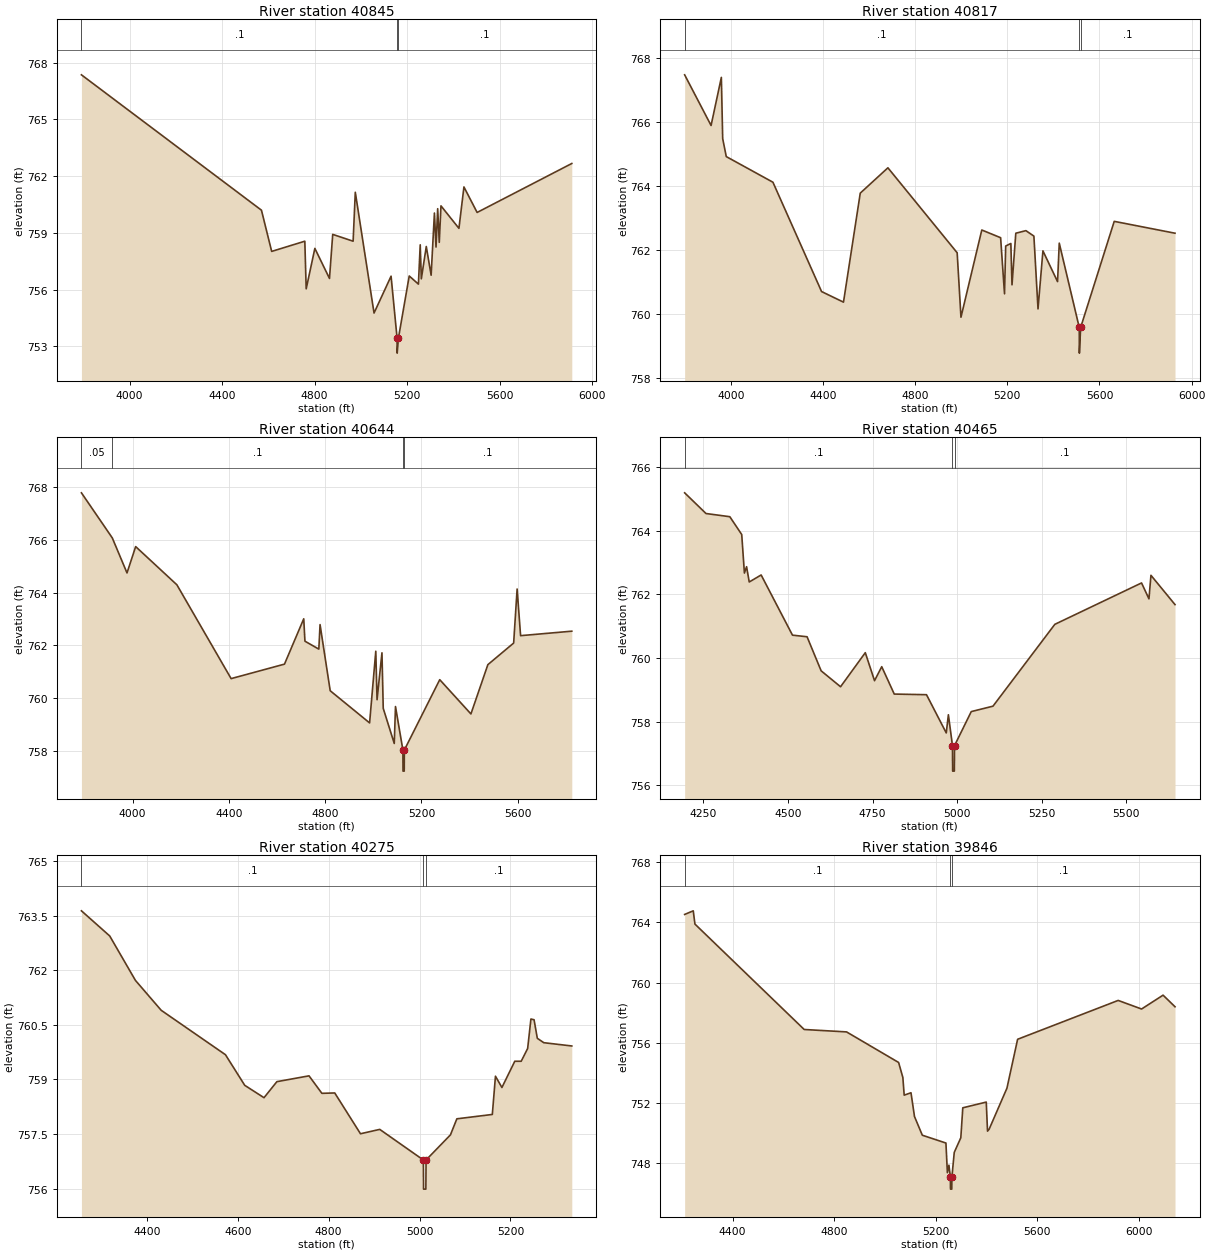
Type RM Length L Ch R = 1,40845,28,28,28
BEGIN DESCRIPTION:
Mapping XS ed72dd20
END DESCRIPTION:
XS GIS Cut Line= 6
      1994488.90     13624573.25      1993857.42     13624950.84
      1993829.20     13624712.13      1993599.17     13624759.87
      1993690.31     13624924.80      1993328.97     13625236.38
#Sta/Elev= 30
  3791.8  767.36  4570.1  760.20  4614.3  758.02  4757.6  758.56  4763.5  756.04
  4801.0  758.18  4864.2  756.59  4878.2  758.92  4966.4  758.56  4975.8  761.15
  5056.9  754.76  5130.5  756.71  5156.4  753.44  5156.9  752.64  5162.4  753.44
  5209.0  756.72  5248.7  756.29  5256.5  758.37  5261.3  756.57  5282.7  758.28
  5303.7  756.76  5317.9  760.05  5324.8  758.25  5332.0  760.28  5338.9  758.50
  5346.2  760.43  5423.9  759.24  5445.5  761.43  5502.5  760.08  5911.8  762.67
#Mann=3,-1,0
  3791.8     0.1       0  5156.4    0.07       0  5162.4     0.1       0
Bank Sta=5156.4,5162.4
Exp/Cntr=0.3,0.1

Type RM Length L Ch R = 1,40817,173,173,173
BEGIN DESCRIPTION:
Mapping XS dd119e90
END DESCRIPTION:
XS GIS Cut Line= 6
      1994483.24     13624545.92      1993877.81     13624910.48
      1993862.62     13624691.30      1993550.12     13624739.04
      1993643.44     13624914.82      1993311.40     13625214.30
#Sta/Elev= 30
  3799.5  767.46  3914.2  765.88  3958.8  767.38  3964.6  765.47  3980.1  764.91
  4182.7  764.11  4393.8  760.70  4488.9  760.37  4561.7  763.77  4681.7  764.56
  4982.3  761.91  4998.8  759.90  5089.2  762.62  5170.9  762.38  5187.8  760.63
  5192.9  762.12  5215.3  762.20  5220.3  760.91  5236.8  762.52  5280.6  762.60
  5315.3  762.43  5333.2  760.16  5354.5  761.97  5418.0  761.01  5425.4  762.21
  5512.2  759.58  5512.7  758.78  5518.2  759.58  5664.0  762.89  5927.8  762.52
#Mann=3,-1,0
  3799.5     0.1       0  5512.2    0.07       0  5518.2     0.1       0
Bank Sta=5512.2,5518.2
Exp/Cntr=0.3,0.1

Type RM Length L Ch R = 1,40644,179,179,179
BEGIN DESCRIPTION:
Mapping XS 1604ec1c
END DESCRIPTION:
XS GIS Cut Line= 6
      1994483.12     13624482.04      1993904.07     13624867.66
      1993862.84     13624660.41      1993534.06     13624715.75
      1993611.10     13624916.48      1993259.19     13625199.37
#Sta/Elev= 30
  3787.1  767.79  3915.3  766.08  3976.5  764.75  4012.5  765.75  4183.8  764.30
  4409.2  760.74  4631.0  761.29  4711.0  763.01  4716.0  762.16  4773.7  761.86
  4778.8  762.79  4821.0  760.28  4984.7  759.06  5010.4  761.78  5015.7  759.94
  5036.1  761.72  5041.4  759.61  5087.2  758.28  5092.3  759.68  5123.1  758.03
  5123.6  757.23  5128.6  757.23  5129.1  758.03  5276.2  760.70  5405.8  759.40
  5476.2  761.27  5583.4  762.09  5597.8  764.14  5612.2  762.37  5825.0  762.54
#Mann=4,-1,0
  3787.1    0.05       0  3915.3     0.1       0  5123.1    0.07       0
  5129.1     0.1       0
Bank Sta=5123.1,5129.1
Exp/Cntr=0.3,0.1

Type RM Length L Ch R = 1,40465,190,190,190
BEGIN DESCRIPTION:
Mapping XS 4a4a6f2d
END DESCRIPTION:
XS GIS Cut Line= 3
      1994035.24     13624087.04      1993653.28     13624399.56
      1993162.81     13625219.90
#Sta/Elev= 30
  4194.8  765.19  4257.9  764.54  4328.3  764.44  4363.5  763.88  4371.4  762.67
  4377.8  762.87  4385.7  762.39  4420.9  762.61  4513.5  760.72  4556.6  760.67
  4598.2  759.60  4655.6  759.10  4728.7  760.17  4756.0  759.29  4777.3  759.73
  4814.3  758.87  4909.6  758.85  4968.0  757.65  4974.3  758.22  4986.4  757.25
  4986.9  756.45  4991.9  756.45  4992.4  757.25  5041.9  758.32  5106.1  758.49
  5288.9  761.06  5545.2  762.36  5567.1  761.86  5573.0  762.60  5644.1  761.68
#Mann=3,-1,0
  4194.8     0.1       0  4986.4    0.07       0  4992.4     0.1       0
Bank Sta=4986.4,4992.4
Exp/Cntr=0.3,0.1

Type RM Length L Ch R = 1,40275,429,429,429
BEGIN DESCRIPTION:
BURNT BOOT CREEK 68.0
END DESCRIPTION:
XS GIS Cut Line= 3
      1993899.01     13624000.99      1993375.00     13624525.00
      1993131.73     13624759.00
#Sta/Elev= 30
  4256.3  763.63  4318.5  762.94  4375.1  761.72  4431.7  760.90  4573.1  759.68
  4615.5  758.84  4657.9  758.50  4686.2  758.94  4756.9  759.10  4785.2  758.62
  4813.5  758.63  4870.1  757.51  4912.5  757.63  5008.4  756.79  5008.9  755.99
  5013.9  755.99  5014.4  756.79  5068.0  757.48  5082.1  757.92  5160.1  758.04
  5167.0  759.09  5181.2  758.78  5209.5  759.50  5223.6  759.50  5237.8  759.85
  5245.0  760.66  5251.9  760.64  5259.1  760.13  5273.3  760.01  5334.9  759.92
#Mann=3,-1,0
  4256.3     0.1       0  5008.4    0.07       0  5014.4     0.1       0
Bank Sta=5008.4,5014.4
Exp/Cntr=0.3,0.1

Type RM Length L Ch R = 1,39846,29,29,29
BEGIN DESCRIPTION:
Mapping XS 9ec54b6c
END DESCRIPTION:
XS GIS Cut Line= 6
      1993936.43     13623874.45      1993170.78     13624181.75
      1993147.35     13623986.43      1993082.24     13623976.02
      1993097.87     13624160.91      1992629.54     13624605.82
#Sta/Elev= 30
  4211.3  764.52  4245.2  764.76  4251.8  763.88  4682.1  756.88  4848.8  756.72
  5053.9  754.69  5070.6  753.69  5075.8  752.52  5102.6  752.68  5116.4  751.10
  5147.2  749.86  5240.2  749.34  5245.9  747.37  5252.0  747.87  5257.7  747.08
  5258.2  746.28  5263.2  746.28  5263.7  747.08  5273.0  748.72  5298.8  749.69
  5306.6  751.68  5399.0  752.06  5404.0  750.13  5410.1  750.25  5480.4  752.98
  5522.5  756.23  5918.5  758.81  6010.6  758.24  6095.3  759.16  6142.3  758.39
#Mann=3,-1,0
  4211.3     0.1       0  5257.7    0.07       0  5263.7     0.1       0
Bank Sta=5257.7,5263.7
Exp/Cntr=0.3,0.1

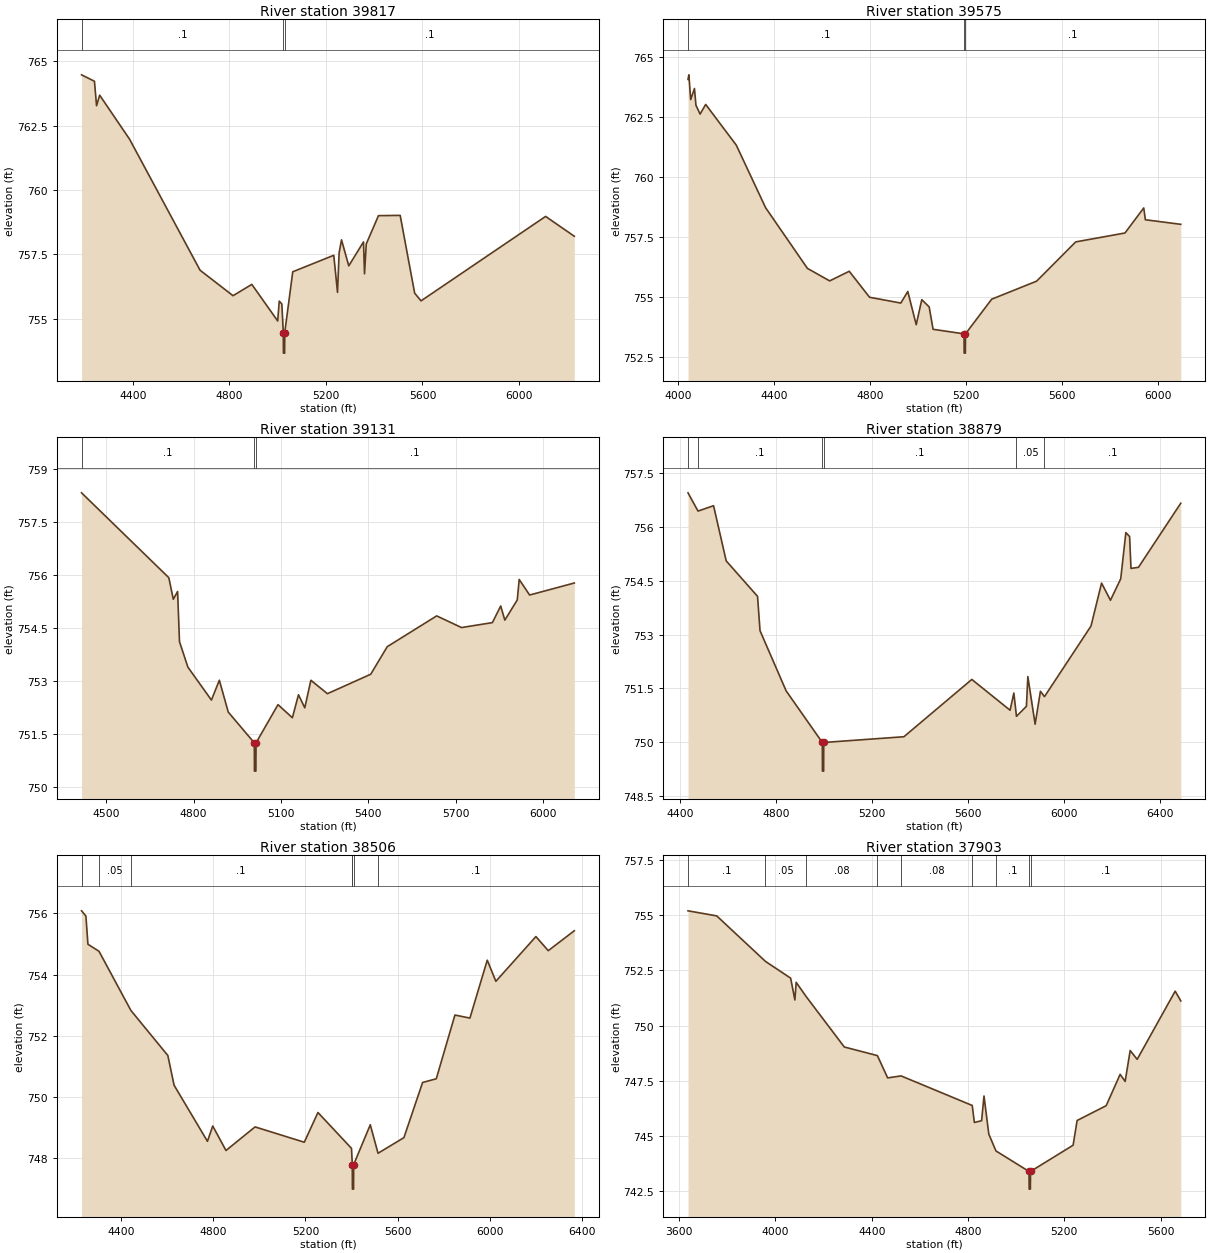
Type RM Length L Ch R = 1,39817,242,242,242
BEGIN DESCRIPTION:
Mapping XS 2555c5ef
END DESCRIPTION:
XS GIS Cut Line= 6
      1993954.61     13623835.40      1993175.99     13624150.50
      1993181.20     13623929.14      1993077.03     13623926.54
      1993048.39     13624134.87      1992590.04     13624598.43
#Sta/Elev= 30
  4186.8  764.47  4240.3  764.22  4249.0  763.27  4261.9  763.68  4385.8  761.97
  4678.1  756.88  4814.8  755.89  4892.6  756.33  4999.8  754.91  5006.3  755.68
  5017.0  755.57  5023.1  754.46  5023.6  753.66  5028.6  753.66  5029.1  754.46
  5062.3  756.82  5232.3  757.46  5247.8  756.02  5254.4  757.55  5264.4  758.06
  5294.5  757.05  5355.5  757.98  5359.8  756.74  5366.9  757.90  5417.6  759.00
  5507.6  759.01  5567.6  755.99  5594.1  755.69  6110.4  758.97  6229.4  758.20
#Mann=3,-1,0
  4186.8     0.1       0  5023.1    0.07       0  5029.1     0.1       0
Bank Sta=5023.1,5029.1
Exp/Cntr=0.3,0.1

Type RM Length L Ch R = 1,39575,444,444,444
BEGIN DESCRIPTION:
Mapping XS 41ba8098
END DESCRIPTION:
XS GIS Cut Line= 6
      1993905.13     13623809.36      1993225.47     13624108.83
      1993183.80     13623869.25      1993030.16     13623879.66
      1993006.72     13624114.04      1992559.40     13624597.77
#Sta/Elev= 30
  4041.5  764.05  4045.1  764.24  4052.6  763.21  4068.4  763.67  4074.4  762.98
  4091.8  762.61  4115.1  763.01  4242.6  761.32  4364.8  758.72  4539.0  756.20
  4631.7  755.68  4713.2  756.08  4798.0  755.00  4928.1  754.76  4957.2  755.24
  4992.3  753.86  5015.5  754.90  5046.2  754.60  5062.6  753.67  5191.6  753.48
  5192.1  752.68  5197.1  752.68  5197.6  753.48  5306.7  754.92  5494.1  755.67
  5656.8  757.30  5862.1  757.67  5940.3  758.71  5947.1  758.22  6094.6  758.03
#Mann=3,-1,0
  4041.5     0.1       0  5191.6    0.07       0  5197.6     0.1       0
Bank Sta=5191.6,5197.6
Exp/Cntr=0.3,0.1

Type RM Length L Ch R = 1,39131,252,252,252
BEGIN DESCRIPTION:
BURNT BOOT CREEK 67.0
END DESCRIPTION:
XS GIS Cut Line= 3
      1993494.59     13623281.56      1993025.00     13623575.00
      1992181.53     13624338.60
#Sta/Elev= 30
  4415.3  758.33  4714.9  755.93  4730.2  755.32  4745.0  755.54  4751.5  754.12
  4780.4  753.40  4861.1  752.47  4888.3  753.03  4918.9  752.13  5008.3  751.26
  5008.8  750.46  5013.8  750.46  5014.3  751.26  5089.7  752.34  5139.0  751.97
  5160.0  752.62  5181.6  752.25  5202.5  753.03  5259.3  752.65  5408.0  753.20
  5464.8  753.98  5634.4  754.85  5719.6  754.52  5825.7  754.66  5854.1  755.13
  5868.3  754.73  5910.9  755.30  5917.6  755.88  5953.4  755.44  6106.8  755.78
#Mann=3,-1,0
  4415.3     0.1       0  5008.3    0.07       0  5014.3     0.1       0
Bank Sta=5008.3,5014.3
Exp/Cntr=0.3,0.1

Type RM Length L Ch R = 1,38879,373,373,373
BEGIN DESCRIPTION:
BURNT BOOT CREEK 66.0
END DESCRIPTION:
XS GIS Cut Line= 3
      1993338.32     13623142.68      1992825.00     13623425.00
      1991563.44     13624177.34
#Sta/Elev= 30
  4433.5  756.96  4475.2  756.45  4540.0  756.60  4592.7  755.06  4723.4  754.07
  4733.8  753.11  4842.7  751.43  4993.5  749.99  4994.0  749.19  4999.0  749.19
  4999.5  749.99  5333.7  750.15  5616.9  751.75  5776.5  750.89  5792.1  751.37
  5803.1  750.72  5844.6  751.00  5850.5  751.83  5880.9  750.50  5903.0  751.42
  5919.9  751.27  6113.8  753.24  6158.0  754.44  6195.0  753.96  6237.8  754.56
  6259.2  755.85  6274.8  755.74  6280.6  754.85  6311.7  754.88  6488.2  756.67
#Mann=6,-1,0
  4433.5    0.05       0  4475.2     0.1       0  4993.5    0.07       0
  4999.5     0.1       0  5803.1    0.05       0  5919.9     0.1       0
Bank Sta=4993.5,4999.5
Exp/Cntr=0.3,0.1

Type RM Length L Ch R = 1,38506,603,603,603
BEGIN DESCRIPTION:
Mapping XS 733677ba
END DESCRIPTION:
XS GIS Cut Line= 3
      1993232.31     13623127.85      1992802.58     13623188.62
      1991318.49     13624023.68
#Sta/Elev= 30
  4229.3  756.08  4248.2  755.91  4256.9  754.99  4305.0  754.76  4443.3  752.83
  4603.5  751.36  4630.6  750.39  4775.3  748.56  4798.2  749.06  4855.6  748.26
  4981.8  749.03  5195.2  748.53  5254.5  749.50  5400.0  748.33  5403.4  747.80
  5403.9  747.00  5408.9  747.00  5409.4  747.80  5481.4  749.10  5515.0  748.17
  5627.3  748.68  5708.3  750.48  5767.6  750.60  5848.5  752.68  5913.5  752.58
  5988.7  754.47  6026.0  753.78  6199.7  755.24  6253.2  754.78  6366.2  755.43
#Mann=7,-1,0
  4229.3    0.08       0  4305.0    0.05       0  4443.3     0.1       0
  5400.0    0.05       0  5403.4    0.07       0  5409.4    0.05       0
  5515.0     0.1       0
Bank Sta=5403.4,5409.4
Exp/Cntr=0.3,0.1

Type RM Length L Ch R = 1,37903,121,121,121
BEGIN DESCRIPTION:
Mapping XS 65a883df
END DESCRIPTION:
XS GIS Cut Line= 4
      1993327.76     13622954.24      1992876.37     13623110.49
      1991743.56     13623136.54      1991397.15     13623400.67
#Sta/Elev= 30
  3637.2  755.20  3756.5  754.97  3958.7  752.91  4063.4  752.15  4081.0  751.16
  4086.3  751.96  4128.2  751.31  4286.3  749.03  4423.7  748.64  4466.3  747.63
  4522.1  747.72  4817.6  746.38  4826.4  745.61  4856.4  745.69  4866.4  746.81
  4886.4  745.08  4916.1  744.32  5053.5  743.39  5054.0  742.59  5059.0  742.59
  5059.5  743.39  5236.5  744.58  5253.1  745.70  5373.7  746.37  5431.8  747.79
  5452.6  747.47  5473.5  748.87  5502.5  748.47  5660.4  751.56  5683.6  751.12
#Mann=9,-1,0
  3637.2     0.1       0  3958.7    0.05       0  4128.2    0.08       0
  4423.7    0.05       0  4522.1    0.08       0  4817.6    0.05       0
  4916.1     0.1       0  5053.5    0.07       0  5059.5     0.1       0
Bank Sta=5053.5,5059.5
Exp/Cntr=0.3,0.1

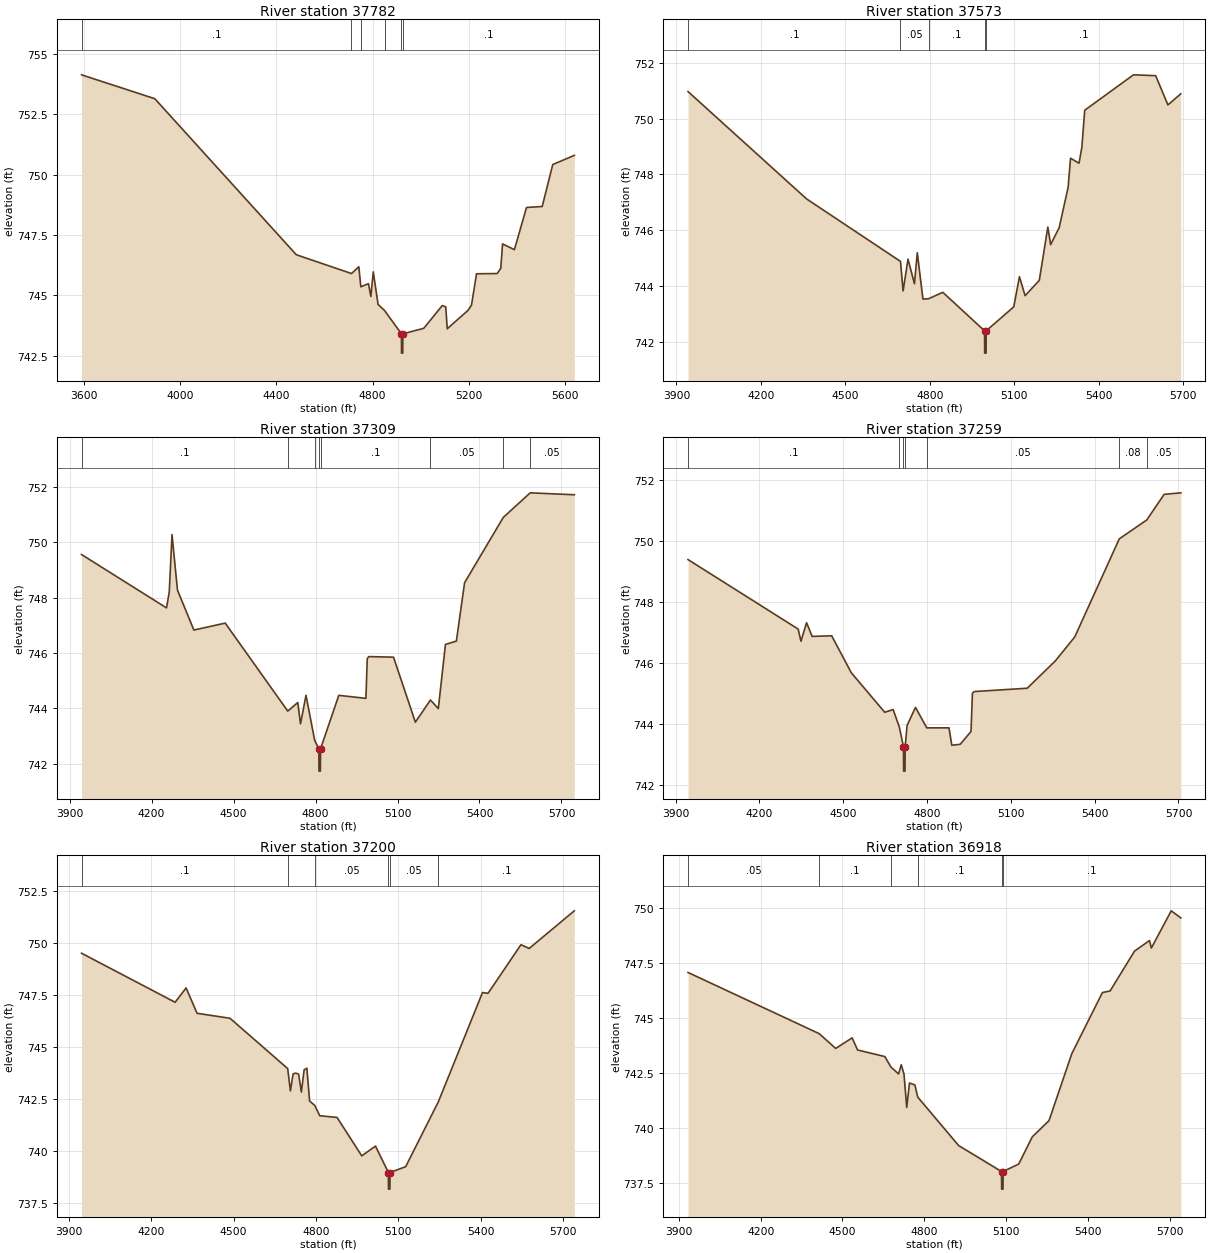
Type RM Length L Ch R = 1,37782,209,209,209
BEGIN DESCRIPTION:
Mapping XS 1ee6d904
END DESCRIPTION:
XS GIS Cut Line= 4
      1993280.02     13622845.73      1993019.60     13623028.03
      1991843.38     13623036.71      1991392.01     13623357.87
#Sta/Elev= 30
  3590.6  754.14  3895.1  753.15  4483.1  746.68  4712.6  745.90  4743.1  746.18
  4751.4  745.35  4783.1  745.48  4793.1  744.95  4803.1  745.97  4823.1  744.62
  4849.8  744.37  4920.1  743.40  4920.6  742.60  4925.6  742.60  4926.1  743.40
  5013.1  743.63  5089.6  744.57  5104.4  744.52  5110.5  743.61  5196.6  744.37
  5211.4  744.59  5232.3  745.89  5318.4  745.90  5333.1  746.12  5340.5  747.13
  5389.7  746.89  5440.1  748.64  5505.3  748.68  5549.1  750.42  5638.7  750.80
#Mann=6,-1,0
  3590.6     0.1       0  4712.6    0.08       0  4751.4    0.05       0
  4849.8     0.1       0  4920.1    0.07       0  4926.1     0.1       0
Bank Sta=4920.1,4926.1
Exp/Cntr=0.3,0.1

Type RM Length L Ch R = 1,37573,264,264,264
BEGIN DESCRIPTION:
Mapping XS 6dd235ae
END DESCRIPTION:
XS GIS Cut Line= 3
      1992932.84     13622702.50      1991478.80     13622884.80
      1991305.35     13623110.28
#Sta/Elev= 30
  3941.3  750.97  4362.4  747.12  4695.8  744.88  4705.1  743.82  4722.6  744.96
  4745.4  744.08  4755.5  745.19  4775.6  743.53  4795.4  743.54  4846.2  743.77
  4994.3  742.39  4994.8  741.59  4999.8  741.59  5000.3  742.39  5098.1  743.25
  5118.3  744.33  5138.4  743.65  5188.8  744.20  5219.1  746.11  5229.1  745.48
  5259.4  746.09  5291.2  747.54  5299.7  748.58  5329.9  748.40  5340.0  748.98
  5350.1  750.30  5523.2  751.57  5602.0  751.54  5645.6  750.49  5691.2  750.89
#Mann=5,-1,0
  3941.3     0.1       0  4695.8    0.05       0  4795.4     0.1       0
  4994.3    0.07       0  5000.3     0.1       0
Bank Sta=4994.3,5000.3
Exp/Cntr=0.3,0.1

Type RM Length L Ch R = 1,37309,50,50,50
BEGIN DESCRIPTION:
Mapping XS 3fd3cfa4
END DESCRIPTION:
XS GIS Cut Line= 2
      1992945.81     13622529.76      1991143.74     13622599.21
#Sta/Elev= 30
  3943.6  749.56  4254.6  747.63  4264.6  748.21  4274.7  750.28  4294.7  748.27
  4354.7  746.83  4469.4  747.08  4698.3  743.90  4735.0  744.21  4745.0  743.44
  4765.0  744.47  4796.9  742.84  4812.1  742.53  4812.6  741.73  4817.6  741.73
  4818.1  742.53  4885.1  744.47  4984.3  744.36  4989.3  745.80  4995.2  745.87
  5085.3  745.85  5165.3  743.50  5220.5  744.30  5249.3  743.99  5275.4  746.31
  5315.4  746.43  5345.4  748.54  5487.0  750.90  5585.6  751.79  5747.0  751.72
#Mann=8,-1,0
  3943.6     0.1       0  4698.3    0.05       0  4796.9     0.1       0
  4812.1    0.07       0  4818.1     0.1       0  5220.5    0.05       0
  5487.0    0.08       0  5585.6    0.05       0
Bank Sta=4812.1,4818.1
Exp/Cntr=0.3,0.1

Type RM Length L Ch R = 1,37259,59,59,59
BEGIN DESCRIPTION:
Mapping XS b879330a
END DESCRIPTION:
XS GIS Cut Line= 2
      1992949.29     13622501.99      1991185.37     13622533.24
#Sta/Elev= 30
  3944.1  749.40  4338.5  747.12  4348.5  746.72  4368.5  747.33  4388.5  746.88
  4458.5  746.90  4528.5  745.69  4648.5  744.39  4678.5  744.48  4700.5  743.91
  4715.5  743.26  4716.0  742.46  4721.0  742.46  4721.5  743.26  4728.5  743.96
  4758.5  744.55  4799.0  743.88  4878.5  743.88  4888.5  743.31  4918.5  743.34
  4957.3  743.76  4962.3  745.01  4968.6  745.07  5158.6  745.18  5258.6  746.07
  5328.6  746.86  5488.2  750.08  5586.7  750.70  5648.7  751.54  5708.3  751.59
#Mann=7,-1,0
  3944.1     0.1       0  4700.5    0.08       0  4715.5    0.04       0
  4721.5    0.08       0  4799.0    0.05       0  5488.2    0.08       0
  5586.7    0.05       0
Bank Sta=4715.5,4721.5
Exp/Cntr=0.3,0.1

Type RM Length L Ch R = 1,37200,282,282,282
BEGIN DESCRIPTION:
Mapping XS 66f06584
END DESCRIPTION:
XS GIS Cut Line= 2
      1992945.83     13622449.90      1991150.65     13622470.74
#Sta/Elev= 30
  3945.8  749.53  4286.7  747.17  4326.7  747.86  4366.7  746.64  4486.7  746.40
  4696.9  743.98  4706.7  742.91  4716.7  743.73  4726.7  743.76  4736.7  743.71
  4746.7  742.85  4756.7  743.92  4766.7  744.00  4776.7  742.42  4795.3  742.21
  4813.8  741.71  4876.7  741.63  4966.7  739.78  5016.7  740.25  5063.7  738.98
  5064.2  738.18  5069.2  738.18  5069.7  738.98  5126.7  739.26  5245.7  742.38
  5406.7  747.64  5426.7  747.60  5546.7  749.94  5576.7  749.76  5741.1  751.57
#Mann=6,-1,0
  3945.8     0.1       0  4696.9    0.08       0  4795.3    0.05       0
  5063.7    0.04       0  5069.7    0.05       0  5245.7     0.1       0
Bank Sta=5063.7,5069.7
Exp/Cntr=0.3,0.1

Type RM Length L Ch R = 1,36918,320,320,320
BEGIN DESCRIPTION:
Mapping XS f2bc98bb
END DESCRIPTION:
XS GIS Cut Line= 3
      1992945.79     13622231.15      1991633.31     13622168.65
      1991192.35     13622387.40
#Sta/Elev= 30
  3933.8  747.05  4414.8  744.27  4475.2  743.60  4535.3  744.08  4555.3  743.53
  4655.4  743.23  4677.4  742.76  4705.5  742.44  4715.5  742.86  4725.5  742.43
  4735.5  740.92  4745.5  742.03  4765.5  741.94  4775.8  741.39  4925.7  739.19
  5082.9  738.01  5083.4  737.21  5088.4  737.21  5088.9  738.01  5146.0  738.35
  5196.0  739.59  5257.0  740.32  5340.8  743.37  5452.9  746.14  5480.9  746.21
  5570.5  748.02  5625.4  748.50  5632.2  748.16  5705.0  749.85  5740.0  749.53
#Mann=6,-1,0
  3933.8    0.05       0  4414.8     0.1       0  4677.4    0.05       0
  4775.8     0.1       0  5082.9    0.07       0  5088.9     0.1       0
Bank Sta=5082.9,5088.9
Exp/Cntr=0.3,0.1

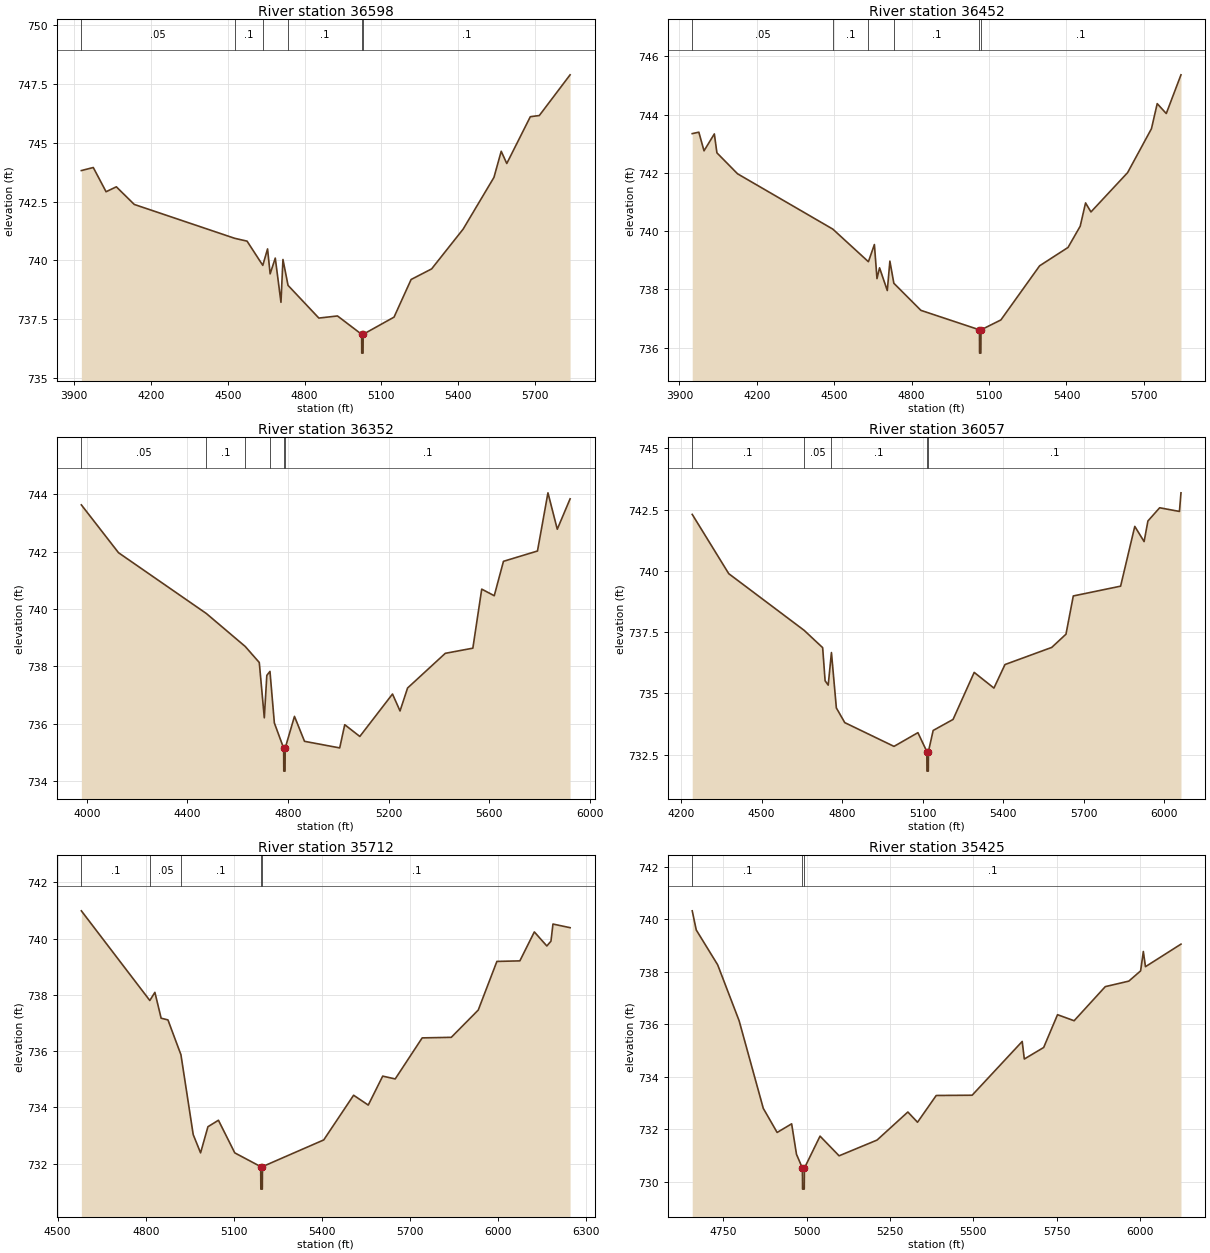
Type RM Length L Ch R = 1,36598,146,146,146
BEGIN DESCRIPTION:
Mapping XS 94def419
END DESCRIPTION:
XS GIS Cut Line= 3
      1992921.50     13621824.90      1991539.56     13621887.40
      1991189.47     13622279.09
#Sta/Elev= 30
  3928.2  743.82  3974.8  743.95  4024.8  742.92  4064.8  743.13  4134.9  742.38
  4527.2  740.94  4575.4  740.82  4636.8  739.79  4655.4  740.49  4665.5  739.43
  4685.5  740.10  4707.8  738.22  4715.5  740.04  4735.4  738.94  4855.7  737.55
  4928.5  737.64  5022.8  736.86  5023.3  736.06  5028.3  736.06  5028.8  736.86
  5149.3  737.59  5216.0  739.19  5296.1  739.64  5419.1  741.33  5539.5  743.53
  5567.9  744.64  5589.6  744.12  5681.6  746.11  5716.7  746.16  5836.9  747.89
#Mann=6,-1,0
  3928.2    0.05       0  4527.2     0.1       0  4636.8    0.05       0
  4735.4     0.1       0  5022.8    0.07       0  5028.8     0.1       0
Bank Sta=5022.8,5028.8
Exp/Cntr=0.3,0.1

Type RM Length L Ch R = 1,36452,100,100,100
BEGIN DESCRIPTION:
Mapping XS d5a1b5a3
END DESCRIPTION:
XS GIS Cut Line= 3
      1992900.63     13621689.49      1991438.87     13621741.57
      1991164.55     13622074.92
#Sta/Elev= 30
  3949.5  743.35  3975.1  743.40  3995.2  742.76  4035.2  743.34  4045.2  742.69
  4125.2  741.97  4494.4  740.07  4632.4  738.95  4655.6  739.54  4665.6  738.37
  4675.6  738.74  4705.6  737.96  4715.6  738.97  4731.0  738.21  4835.7  737.28
  5062.8  736.61  5063.3  735.81  5068.3  735.81  5068.8  736.61  5145.9  736.95
  5296.0  738.81  5406.1  739.44  5453.3  740.17  5474.1  740.97  5495.0  740.66
  5637.0  742.01  5729.5  743.52  5751.8  744.38  5786.9  744.04  5843.9  745.37
#Mann=6,-1,0
  3949.5    0.05       0  4494.4     0.1       0  4632.4    0.05       0
  4731.0     0.1       0  5062.8    0.07       0  5068.8     0.1       0
Bank Sta=5062.8,5068.8
Exp/Cntr=0.3,0.1

Type RM Length L Ch R = 1,36352,295,295,295
BEGIN DESCRIPTION:
Mapping XS 0700a4a5
END DESCRIPTION:
XS GIS Cut Line= 3
      1992872.87     13621620.04      1991376.37     13621630.46
      1991102.07     13621984.62
#Sta/Elev= 30
  3977.9  743.63  4125.8  741.96  4475.1  739.84  4629.8  738.69  4685.8  738.13
  4705.8  736.20  4715.8  737.68  4728.3  737.82  4745.8  736.02  4782.8  735.14
  4783.3  734.34  4788.3  734.34  4788.8  735.14  4825.8  736.25  4865.8  735.38
  5005.8  735.15  5025.8  735.96  5085.8  735.55  5215.8  737.03  5245.8  736.44
  5275.8  737.24  5425.8  738.45  5535.5  738.63  5570.8  740.69  5620.6  740.46
  5657.3  741.66  5792.6  742.02  5834.3  744.05  5871.4  742.78  5922.4  743.84
#Mann=6,-1,0
  3977.9    0.05       0  4475.1     0.1       0  4629.8    0.05       0
  4728.3     0.1       0  4782.8    0.07       0  4788.8     0.1       0
Bank Sta=4782.8,4788.8
Exp/Cntr=0.3,0.1

Type RM Length L Ch R = 1,36057,345,345,345
BEGIN DESCRIPTION:
Mapping XS 939aa56b
END DESCRIPTION:
XS GIS Cut Line= 3
      1992637.21     13621163.16      1991383.75     13621465.24
      1991116.37     13621923.60
#Sta/Elev= 30
  4242.0  742.31  4378.0  739.89  4658.4  737.58  4727.7  736.87  4736.8  735.52
  4748.3  735.34  4760.4  736.67  4778.7  734.41  4810.0  733.81  4993.4  732.84
  5082.4  733.40  5115.6  732.63  5116.1  731.83  5121.1  731.83  5121.6  732.63
  5139.2  733.49  5213.3  733.94  5292.0  735.86  5365.5  735.22  5406.6  736.18
  5580.8  736.88  5633.8  737.42  5661.0  738.98  5837.2  739.38  5890.0  741.82
  5924.7  741.20  5938.9  742.04  5982.6  742.58  6056.3  742.43  6062.0  743.19
#Mann=5,-1,0
  4242.0     0.1       0  4658.4    0.05       0  4760.4     0.1       0
  5115.6    0.07       0  5121.6     0.1       0
Bank Sta=5115.6,5121.6
Exp/Cntr=0.3,0.1

Type RM Length L Ch R = 1,35712,287,287,287
BEGIN DESCRIPTION:
Mapping XS 1b909b37
END DESCRIPTION:
XS GIS Cut Line= 3
      1992460.14     13620899.27      1991658.05     13621194.41
      1991060.85     13621743.00
#Sta/Elev= 30
  4580.7  740.99  4814.0  737.80  4831.3  738.09  4852.6  737.17  4875.8  737.11
  4920.1  735.87  4961.9  733.03  4987.0  732.38  5012.1  733.31  5047.9  733.54
  5103.5  732.38  5191.9  731.89  5192.4  731.09  5197.4  731.09  5197.9  731.89
  5406.7  732.84  5508.5  734.43  5558.4  734.08  5607.7  735.11  5650.3  735.01
  5742.2  736.47  5841.4  736.49  5933.3  737.46  5996.8  739.19  6075.1  739.21
  6124.4  740.24  6167.0  739.74  6181.1  739.91  6187.9  740.52  6246.3  740.39
#Mann=5,-1,0
  4580.7     0.1       0  4814.0    0.05       0  4920.1     0.1       0
  5191.9    0.07       0  5197.9     0.1       0
Bank Sta=5191.9,5197.9
Exp/Cntr=0.3,0.1

Type RM Length L Ch R = 1,35425,256,256,256
BEGIN DESCRIPTION:
Mapping XS d6038d13
END DESCRIPTION:
XS GIS Cut Line= 3
      1992133.75     13620645.79      1991446.25     13621177.04
      1991082.69     13621651.40
#Sta/Elev= 30
  4656.6  740.32  4668.7  739.59  4733.0  738.26  4797.3  736.13  4869.8  732.79
  4911.4  731.87  4954.9  732.20  4969.4  731.04  4987.2  730.51  4987.7  729.71
  4992.7  729.71  4993.2  730.51  5040.1  731.73  5097.3  730.98  5211.1  731.58
  5303.6  732.65  5332.6  732.26  5388.7  733.28  5496.5  733.29  5646.7  735.34
  5653.0  734.67  5711.1  735.11  5752.7  736.36  5802.5  736.13  5896.0  737.43
  5966.6  737.64  6002.0  738.03  6010.2  738.77  6016.5  738.19  6123.1  739.05
#Mann=3,-1,0
  4656.6     0.1       0  4987.2    0.07       0  4993.2     0.1       0
Bank Sta=4987.2,4993.2
Exp/Cntr=0.3,0.1