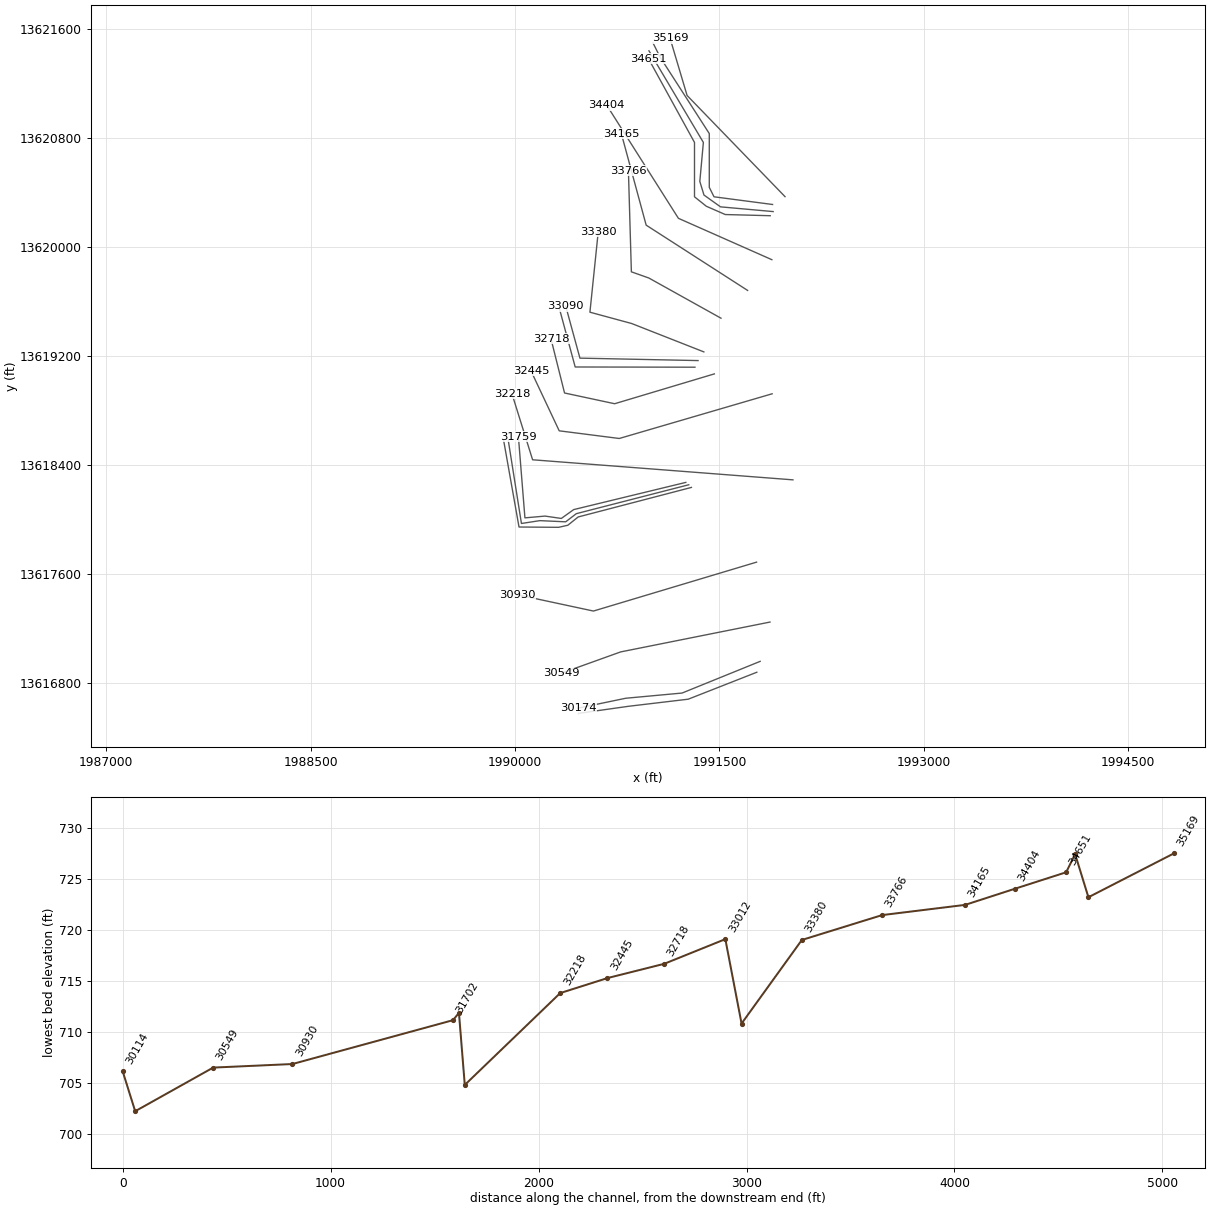
HEC-RAS study BURNT BOOT CREEK.prj: BURNT BOOT CREEK Base Level Engineering

--- BURNT BOOT CREEK.g01 (geometry) --- (continued)

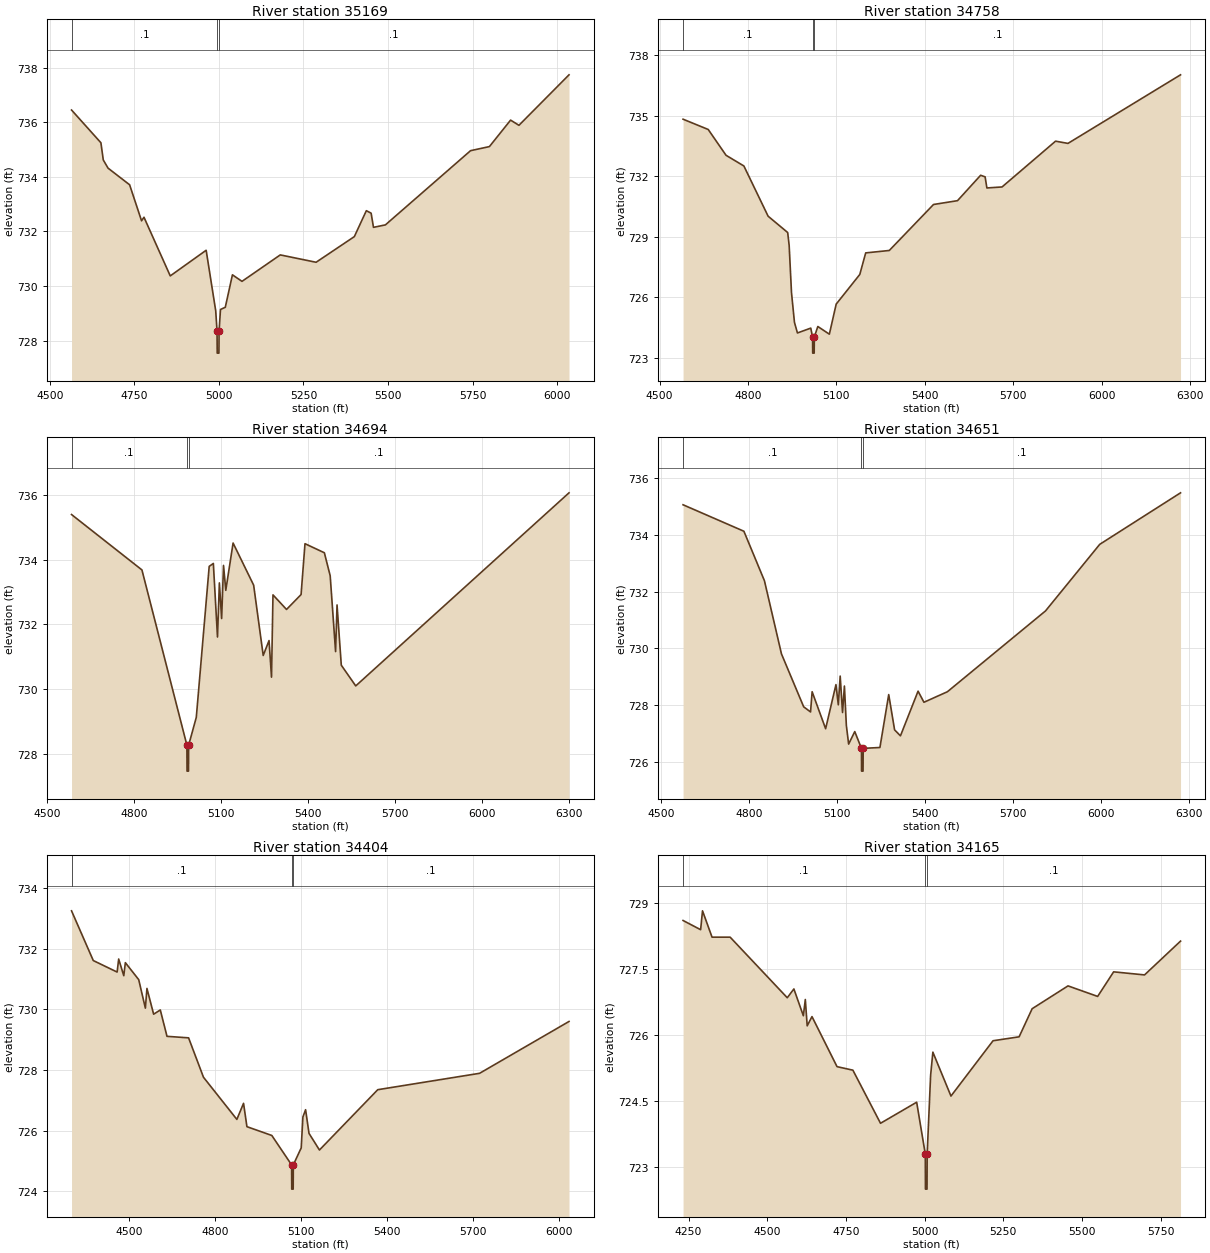
Type RM Length L Ch R = 1,35169,411,411,411
BEGIN DESCRIPTION:
Mapping XS d885efc4
END DESCRIPTION:
XS GIS Cut Line= 3
      1991980.95     13620368.04      1991262.22     13621111.07
      1991137.39     13621530.63
#Sta/Elev= 30
  4563.9  736.45  4650.8  735.25  4657.8  734.62  4671.9  734.32  4735.7  733.71
  4771.0  732.39  4778.2  732.52  4855.9  730.37  4962.1  731.31  4990.4  729.09
  4994.3  728.34  4994.8  727.54  4999.8  727.54  5000.3  728.34  5004.5  729.14
  5018.7  729.22  5039.8  730.41  5068.1  730.17  5181.3  731.14  5287.3  730.87
  5400.4  731.81  5435.9  732.76  5450.1  732.67  5457.0  732.15  5492.3  732.24
  5744.2  734.96  5800.0  735.11  5862.6  736.08  5887.3  735.89  6035.4  737.74
#Mann=3,-1,0
  4563.9     0.1       0  4994.3    0.07       0  5000.3     0.1       0
Bank Sta=4994.3,5000.3
Exp/Cntr=0.3,0.1

Type RM Length L Ch R = 1,34758,64,64,64
BEGIN DESCRIPTION:
Mapping XS 5099de57
END DESCRIPTION:
XS GIS Cut Line= 6
      1991889.54     13620310.53      1991459.88     13620366.95
      1991425.15     13620436.39      1991425.15     13620831.36
      1991064.91     13621391.25      1991012.83     13621495.41
#Sta/Elev= 30
  4579.5  734.84  4664.9  734.33  4725.4  733.05  4786.0  732.52  4868.2  730.03
  4934.7  729.22  4939.7  728.57  4947.6  726.24  4957.7  724.76  4967.8  724.24
  5013.0  724.48  5019.1  724.04  5019.6  723.24  5024.6  723.24  5025.1  724.04
  5037.0  724.56  5076.1  724.18  5099.3  725.67  5179.4  727.14  5199.5  728.21
  5279.6  728.33  5429.7  730.61  5511.2  730.80  5589.7  732.06  5604.9  731.98
  5610.9  731.43  5662.4  731.48  5844.0  733.75  5886.2  733.64  6268.3  737.04
#Mann=3,-1,0
  4579.5     0.1       0  5019.1    0.07       0  5025.1     0.1       0
Bank Sta=5019.1,5025.1
Exp/Cntr=0.3,0.1

Type RM Length L Ch R = 1,34694,43,43,43
BEGIN DESCRIPTION:
Mapping XS 98aeb581
END DESCRIPTION:
XS GIS Cut Line= 6
      1991893.86     13620258.44      1991507.62     13620293.16
      1991386.09     13620379.97      1991355.71     13620479.79
      1991381.75     13620766.25      1990982.45     13621438.98
#Sta/Elev= 30
  4584.0  735.39  4826.8  733.68  4981.9  728.27  4982.4  727.47  4987.4  727.47
  4987.9  728.27  5014.3  729.13  5058.8  733.79  5073.1  733.88  5087.4  731.61
  5093.9  733.28  5101.7  732.18  5108.2  733.82  5116.0  733.05  5141.2  734.51
  5212.1  733.21  5245.1  731.04  5265.2  731.50  5273.7  730.37  5278.8  732.91
  5325.5  732.46  5375.7  732.92  5389.2  734.49  5456.0  734.21  5476.1  733.50
  5494.7  731.16  5499.7  732.60  5514.4  730.74  5564.2  730.10  6299.8  736.06
#Mann=3,-1,0
  4584.0     0.1       0  4981.9    0.07       0  4987.9     0.1       0
Bank Sta=4981.9,4987.9
Exp/Cntr=0.3,0.1

Type RM Length L Ch R = 1,34651,247,247,247
BEGIN DESCRIPTION:
Mapping XS a3303959
END DESCRIPTION:
XS GIS Cut Line= 6
      1991872.22     13620228.06      1991542.34     13620236.74
      1991403.45     13620297.50      1991316.65     13620366.95
      1991316.65     13620766.25      1990978.13     13621382.53
#Sta/Elev= 30
  4575.7  735.05  4783.0  734.12  4853.0  732.38  4911.0  729.81  4986.7  727.95
  5010.1  727.77  5015.5  728.48  5061.5  727.18  5096.7  728.73  5104.7  728.02
  5111.1  729.03  5119.1  727.75  5125.5  728.68  5132.1  727.30  5139.9  726.64
  5160.8  727.08  5183.5  726.49  5184.0  725.69  5189.0  725.69  5189.5  726.49
  5246.5  726.52  5276.5  728.38  5296.5  727.14  5316.5  726.93  5376.5  728.50
  5396.5  728.11  5476.5  728.48  5810.8  731.32  5995.6  733.66  6270.9  735.47
#Mann=3,-1,0
  4575.7     0.1       0  5183.5    0.07       0  5189.5     0.1       0
Bank Sta=5183.5,5189.5
Exp/Cntr=0.3,0.1

Type RM Length L Ch R = 1,34404,239,239,239
BEGIN DESCRIPTION:
BURNT BOOT CREEK 56.0
END DESCRIPTION:
XS GIS Cut Line= 3
      1991884.31     13619905.16      1991198.59     13620208.96
      1990671.57     13621041.10
#Sta/Elev= 30
  4300.5  733.25  4376.3  731.61  4459.5  731.23  4464.9  731.66  4482.7  731.11
  4488.2  731.54  4534.8  730.98  4558.0  730.04  4563.5  730.69  4586.8  729.84
  4610.1  729.98  4633.4  729.11  4708.7  729.06  4760.7  727.76  4877.1  726.37
  4900.4  726.90  4912.2  726.13  4999.0  725.84  5068.0  724.87  5068.5  724.07
  5073.5  724.07  5074.0  724.87  5101.5  725.43  5107.4  726.45  5116.8  726.69
  5128.7  725.91  5165.1  725.36  5368.5  727.35  5723.6  727.89  6035.5  729.60
#Mann=3,-1,0
  4300.5     0.1       0  5068.0    0.07       0  5074.0     0.1       0
Bank Sta=5068,5074
Exp/Cntr=0.3,0.1

Type RM Length L Ch R = 1,34165,399,399,399
BEGIN DESCRIPTION:
Mapping XS 93a78c96
END DESCRIPTION:
XS GIS Cut Line= 3
      1991706.40     13619679.45      1990961.92     13620158.90
      1990780.03     13620830.19
#Sta/Elev= 30
  4232.6  728.61  4288.4  728.40  4294.4  728.83  4324.7  728.23  4382.2  728.23
  4563.7  726.85  4584.8  727.05  4614.9  726.44  4621.1  726.81  4627.1  726.21
  4642.3  726.42  4721.9  725.28  4772.3  725.20  4860.1  723.99  4975.0  724.47
  5002.4  723.29  5002.9  722.49  5007.9  722.49  5008.4  723.29  5019.3  725.08
  5026.5  725.61  5084.0  724.61  5217.7  725.87  5300.6  725.96  5342.0  726.60
  5456.0  727.12  5550.2  726.88  5601.0  727.44  5699.2  727.37  5813.6  728.14
#Mann=3,-1,0
  4232.6     0.1       0  5002.4    0.07       0  5008.4     0.1       0
Bank Sta=5002.4,5008.4
Exp/Cntr=0.3,0.1

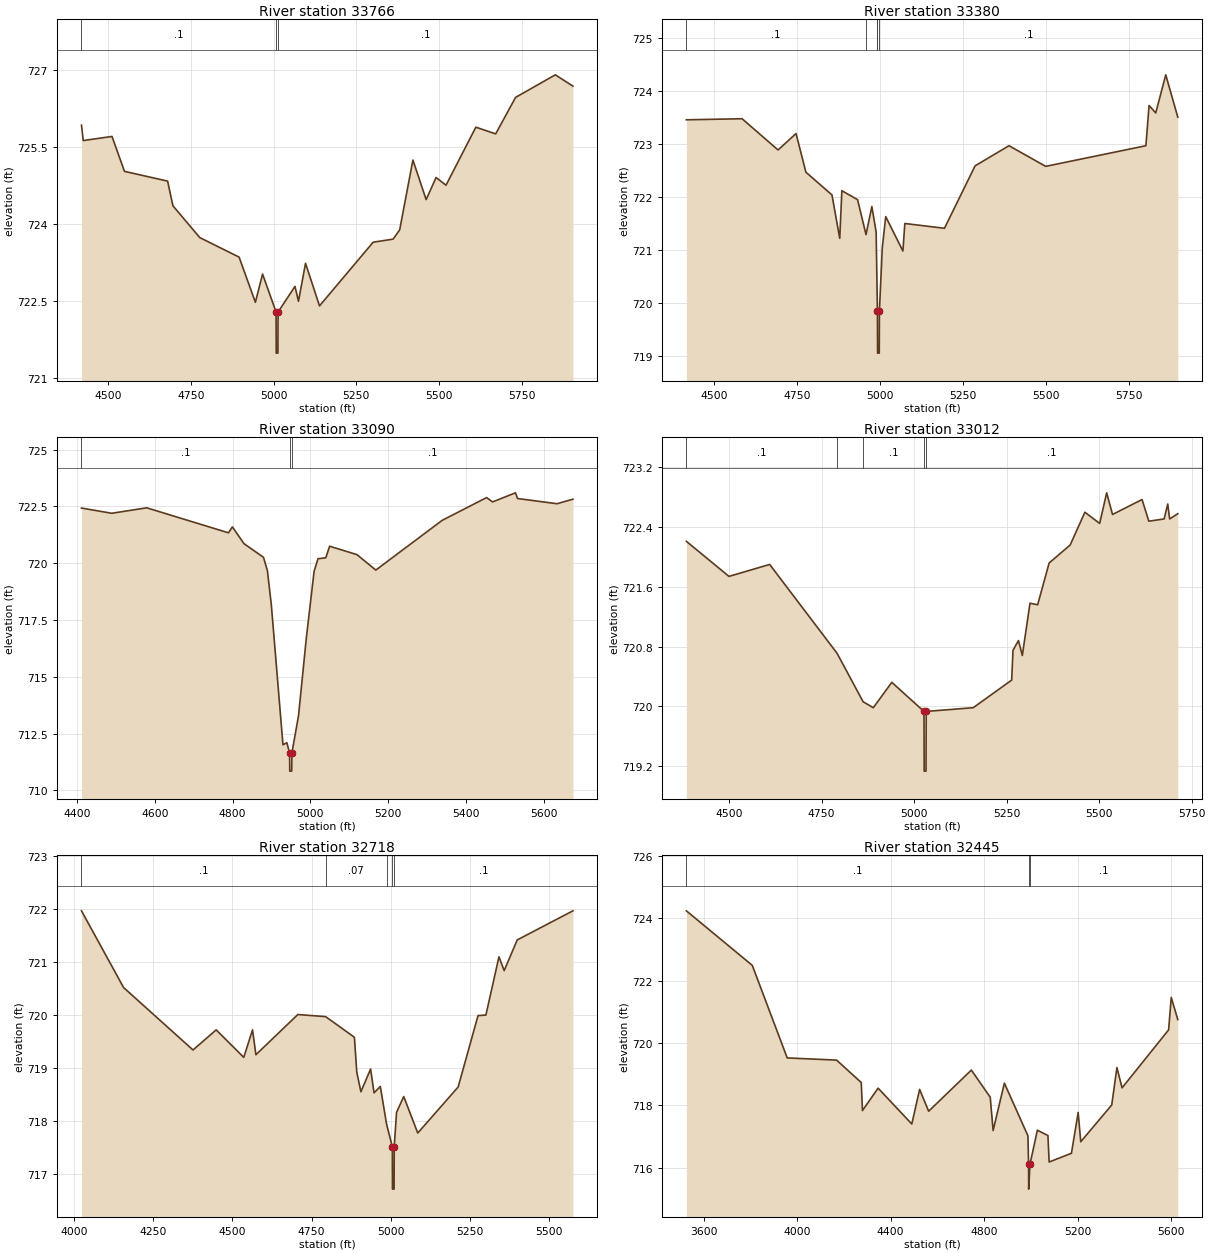
Type RM Length L Ch R = 1,33766,386,386,386
BEGIN DESCRIPTION:
BURNT BOOT CREEK 55.0
END DESCRIPTION:
XS GIS Cut Line= 4
      1991511.11     13619475.44      1990981.58     13619770.59
      1990853.42     13619816.02      1990831.72     13620558.20
#Sta/Elev= 30
  4419.7  725.93  4425.0  725.63  4511.9  725.71  4549.6  725.03  4679.9  724.84
  4695.9  724.36  4777.1  723.74  4895.9  723.36  4945.1  722.48  4966.8  723.03
  5007.6  722.29  5008.1  721.49  5013.1  721.49  5013.6  722.29  5064.7  722.79
  5075.3  722.50  5096.6  723.24  5138.8  722.41  5300.9  723.65  5361.0  723.71
  5381.0  723.89  5421.0  725.25  5461.0  724.48  5491.0  724.91  5521.0  724.76
  5611.1  725.89  5671.1  725.76  5731.1  726.47  5851.2  726.91  5904.4  726.69
#Mann=3,-1,0
  4419.7     0.1       0  5007.6    0.07       0  5013.6     0.1       0
Bank Sta=5007.6,5013.6
Exp/Cntr=0.3,0.1

Type RM Length L Ch R = 1,33380,290,290,290
BEGIN DESCRIPTION:
BURNT BOOT CREEK 54.0
END DESCRIPTION:
XS GIS Cut Line= 4
      1991385.25     13619228.05      1990855.71     13619436.39
      1990549.24     13619519.57      1990610.36     13620111.12
#Sta/Elev= 30
  4415.5  723.46  4583.5  723.48  4691.9  722.89  4746.1  723.20  4775.8  722.47
  4854.4  722.04  4877.8  721.22  4884.2  722.12  4931.6  721.95  4957.0  721.29
  4974.6  721.82  4987.5  721.34  4990.7  720.12  4991.4  719.85  4991.9  719.05
  4996.9  719.05  4997.4  719.85  5006.0  721.04  5016.4  721.63  5068.2  720.98
  5074.0  721.50  5193.5  721.41  5285.8  722.59  5388.0  722.97  5498.6  722.58
  5800.6  722.97  5810.2  723.73  5830.3  723.59  5860.5  724.31  5896.8  723.51
#Mann=5,-1,0
  4415.5     0.1       0  4957.0    0.07       0  4990.7     0.1       0
  4991.4    0.07       0  4997.4     0.1       0
Bank Sta=4991.4,4997.4
Exp/Cntr=0.3,0.1

Type RM Length L Ch R = 1,33090,78,78,78
BEGIN DESCRIPTION:
Mapping XS f67ffda2
END DESCRIPTION:
XS GIS Cut Line= 3
      1991342.70     13619164.26      1990475.90     13619182.21
      1990371.65     13619564.26
#Sta/Elev= 30
  4411.8  722.43  4489.5  722.20  4579.5  722.44  4789.6  721.34  4799.6  721.60
  4829.6  720.86  4879.6  720.26  4889.6  719.67  4899.6  718.19  4929.6  712.01
  4939.6  712.10  4946.6  711.65  4947.1  710.85  4952.1  710.85  4952.6  711.65
  4969.6  713.29  4989.6  716.70  5009.6  719.64  5019.6  720.20  5039.6  720.24
  5049.6  720.75  5119.7  720.38  5168.3  719.70  5338.9  721.89  5452.9  722.89
  5468.3  722.70  5527.2  723.10  5532.4  722.85  5634.1  722.62  5674.8  722.82
#Mann=3,-1,0
  4411.8     0.1       0  4946.6    0.07       0  4952.6     0.1       0
Bank Sta=4946.6,4952.6
Exp/Cntr=0.3,0.1

Type RM Length L Ch R = 1,33012,294,294,294
BEGIN DESCRIPTION:
Mapping XS 625c9d97
END DESCRIPTION:
XS GIS Cut Line= 3
      1991320.12     13619115.64      1990441.09     13619117.23
      1990324.09     13619550.59
#Sta/Elev= 30
  4384.7  722.21  4499.8  721.74  4609.8  721.90  4791.8  720.71  4862.3  720.06
  4889.8  719.98  4939.8  720.32  5026.8  719.93  5027.3  719.13  5032.3  719.13
  5032.8  719.93  5159.8  719.98  5263.7  720.35  5267.3  720.75  5282.1  720.88
  5292.5  720.68  5313.2  721.38  5333.9  721.36  5365.0  721.92  5421.7  722.16
  5461.6  722.60  5501.5  722.45  5520.4  722.86  5536.2  722.57  5616.0  722.77
  5634.3  722.48  5675.7  722.51  5685.4  722.71  5690.6  722.51  5712.6  722.58
#Mann=5,-1,0
  4384.7     0.1       0  4791.8    0.12       0  4862.3     0.1       0
  5026.8    0.07       0  5032.8     0.1       0
Bank Sta=5026.8,5032.8
Exp/Cntr=0.3,0.1

Type RM Length L Ch R = 1,32718,273,273,273
BEGIN DESCRIPTION:
BURNT BOOT CREEK 52.0
END DESCRIPTION:
XS GIS Cut Line= 4
      1991462.31     13619066.55      1990730.71     13618847.42
      1990362.97     13618926.26      1990263.14     13619325.55
#Sta/Elev= 30
  4023.3  721.97  4156.2  720.52  4375.4  719.34  4448.5  719.72  4535.6  719.20
  4563.3  719.72  4573.9  719.25  4706.3  720.01  4794.1  719.97  4884.9  719.58
  4892.4  718.92  4905.4  718.55  4936.0  718.98  4946.9  718.53  4966.7  718.65
  4986.4  717.94  5004.6  717.51  5005.1  716.71  5010.1  716.71  5010.6  717.51
  5017.9  718.16  5040.6  718.46  5084.9  717.77  5212.4  718.64  5275.2  719.99
  5300.0  720.00  5341.2  721.10  5357.7  720.84  5398.9  721.42  5574.7  721.97
#Mann=5,-1,0
  4023.3     0.1       0  4794.1    0.07       0  4986.4     0.1       0
  5004.6    0.07       0  5010.6     0.1       0
Bank Sta=5004.6,5010.6
Exp/Cntr=0.3,0.1

Type RM Length L Ch R = 1,32445,227,227,227
BEGIN DESCRIPTION:
Mapping XS 32ae1ed5
END DESCRIPTION:
XS GIS Cut Line= 4
      1991886.40     13618920.40      1990764.56     13618592.21
      1990323.90     13618648.48      1990115.86     13619090.58
#Sta/Elev= 30
  3526.7  724.24  3808.6  722.49  3958.0  719.52  4169.1  719.45  4274.6  718.73
  4279.8  717.83  4346.7  718.55  4490.8  717.40  4524.3  718.51  4562.9  717.81
  4745.5  719.13  4826.2  718.26  4838.6  717.19  4886.7  718.71  4987.5  717.02
  4990.2  716.11  4990.7  715.31  4996.2  716.11  5027.8  717.20  5073.0  717.03
  5078.2  716.18  5173.5  716.46  5202.3  717.77  5213.3  716.83  5345.9  718.01
  5368.0  719.21  5390.1  718.56  5589.1  720.42  5600.4  721.46  5628.4  720.75
#Mann=3,-1,0
  3526.7     0.1       0  4990.2    0.07       0  4996.2     0.1       0
Bank Sta=4990.2,4996.2
Exp/Cntr=0.3,0.1

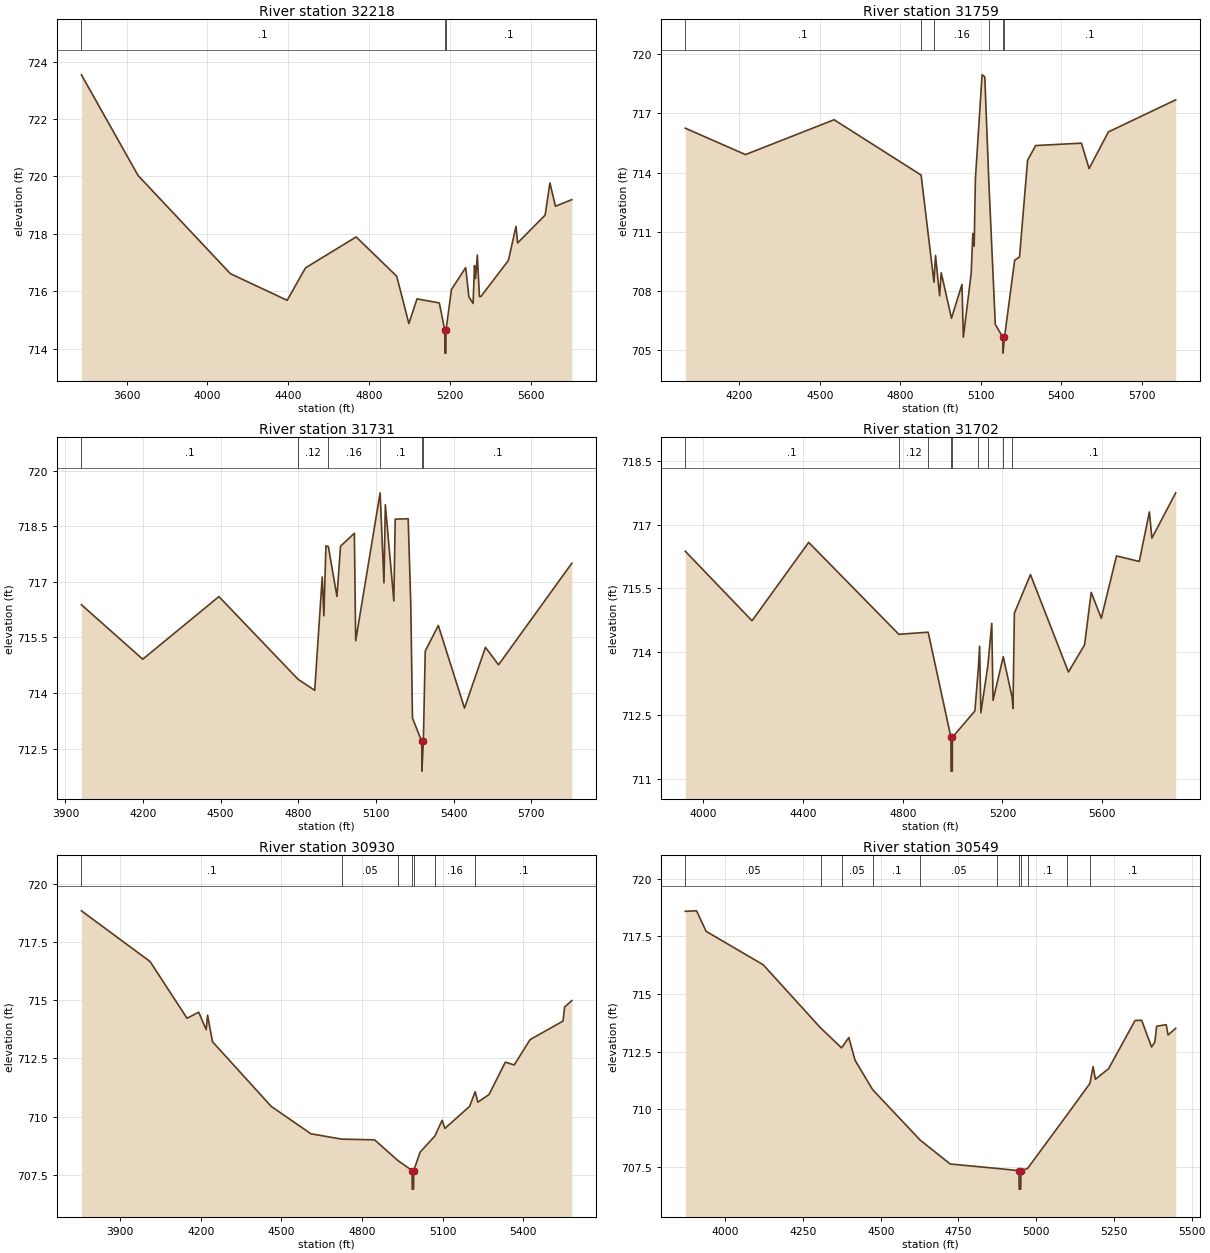
Type RM Length L Ch R = 1,32218,459,459,459
BEGIN DESCRIPTION:
Mapping XS 8db0dcdc
END DESCRIPTION:
XS GIS Cut Line= 3
      1992039.19     13618288.44      1990128.59     13618435.81
      1989976.97     13618921.00
#Sta/Elev= 30
  3376.8  723.54  3657.0  720.03  4113.2  716.61  4394.0  715.68  4484.3  716.81
  4735.0  717.89  4935.6  716.52  4995.8  714.87  5035.9  715.73  5146.2  715.59
  5173.3  714.64  5173.8  713.84  5178.8  713.84  5179.3  714.64  5206.4  716.06
  5276.6  716.82  5292.4  715.80  5313.2  715.57  5320.1  716.89  5325.4  716.44
  5334.1  717.26  5344.6  715.81  5352.6  715.82  5487.8  717.07  5525.5  718.26
  5533.2  717.68  5669.4  718.65  5693.1  719.77  5720.4  718.96  5801.4  719.19
#Mann=3,-1,0
  3376.8     0.1       0  5173.3    0.07       0  5179.3     0.1       0
Bank Sta=5173.3,5179.3
Exp/Cntr=0.3,0.1

Type RM Length L Ch R = 1,31759,28,28,28
BEGIN DESCRIPTION:
Mapping XS c5142acc
END DESCRIPTION:
XS GIS Cut Line= 6
      1991252.85     13618269.73      1990430.36     13618070.07
      1990339.22     13618004.97      1990219.86     13618022.33
      1990072.29     13618009.31      1990024.43     13618605.07
#Sta/Elev= 30
  3999.2  716.25  4223.4  714.91  4553.5  716.68  4877.7  713.87  4925.6  708.43
  4931.4  709.79  4946.6  707.74  4952.6  708.91  4990.9  706.60  5029.9  708.32
  5035.1  705.64  5064.4  708.90  5070.3  710.90  5075.4  710.26  5080.0  713.68
  5104.9  718.96  5114.9  718.86  5130.5  713.39  5154.1  706.29  5182.3  705.63
  5182.8  704.83  5188.3  705.63  5226.3  709.55  5244.3  709.71  5274.4  714.62
  5304.5  715.37  5475.0  715.49  5503.5  714.20  5575.3  716.06  5826.2  717.69
#Mann=6,-1,0
  3999.2     0.1       0  4877.7    0.12       0  4925.6    0.16       0
  5130.5     0.1       0  5182.3    0.07       0  5188.3     0.1       0
Bank Sta=5182.3,5188.3
Exp/Cntr=0.3,0.1

Type RM Length L Ch R = 1,31731,29,29,29
BEGIN DESCRIPTION:
BURNT BOOT CREEK 49.0
END DESCRIPTION:
XS GIS Cut Line= 6
      1991274.52     13618252.36      1990449.46     13618040.12
      1990371.33     13617980.23      1990182.10     13617988.91
      1990046.68     13617968.07      1989950.64     13618574.68
#Sta/Elev= 30
  3962.1  716.38  4199.1  714.91  4493.4  716.60  4799.1  714.37  4863.6  714.07
  4892.7  717.13  4899.0  716.08  4907.0  717.97  4916.4  717.95  4949.6  716.60
  4963.4  717.96  5016.9  718.31  5022.0  715.41  5116.4  719.40  5131.3  716.97
  5136.5  719.08  5169.5  716.48  5174.7  718.69  5224.8  718.70  5234.8  716.42
  5241.5  713.32  5277.5  712.69  5278.0  711.89  5283.5  712.69  5290.8  715.13
  5341.3  715.82  5442.5  713.59  5523.5  715.23  5574.1  714.76  5857.3  717.50
#Mann=6,-1,0
  3962.1     0.1       0  4799.1    0.12       0  4916.4    0.16       0
  5116.4     0.1       0  5277.5    0.07       0  5283.5     0.1       0
Bank Sta=5277.5,5283.5
Exp/Cntr=0.3,0.1

Type RM Length L Ch R = 1,31702,772,772,772
BEGIN DESCRIPTION:
Mapping XS b4cfed2a
END DESCRIPTION:
XS GIS Cut Line= 6
      1991294.09     13618232.84      1990462.91     13618015.82
      1990386.96     13617955.05      1990319.68     13617939.86
      1990028.89     13617942.03      1989915.93     13618579.00
#Sta/Elev= 30
  3927.1  716.37  4194.9  714.73  4422.3  716.58  4784.2  714.41  4901.9  714.46
  4993.3  711.98  4993.8  711.18  4998.8  711.18  4999.3  711.98  5089.5  712.60
  5103.2  713.60  5108.4  714.13  5113.5  712.56  5141.7  713.68  5157.2  714.67
  5162.4  712.85  5203.3  713.88  5238.7  712.93  5242.4  712.66  5248.0  714.91
  5312.5  715.82  5464.9  713.52  5529.7  714.16  5556.3  715.40  5596.9  714.79
  5657.9  716.26  5749.3  716.13  5789.9  717.30  5800.0  716.68  5895.5  717.75
#Mann=9,-1,0
  3927.1     0.1       0  4784.2    0.12       0  4901.9    0.16       0
  4993.3    0.07       0  4999.3    0.16       0  5103.2     0.1       0
  5141.7    0.16       0  5203.3    0.12       0  5238.7     0.1       0
Bank Sta=4993.3,4999.3
Exp/Cntr=0.3,0.1

Type RM Length L Ch R = 1,30930,381,381,381
BEGIN DESCRIPTION:
BURNT BOOT CREEK 48.0
END DESCRIPTION:
XS GIS Cut Line= 3
      1991772.05     13617684.11      1990575.00     13617325.00
      1990013.14     13617445.56
#Sta/Elev= 30
  3756.3  718.85  4011.6  716.67  4149.1  714.23  4192.6  714.49  4220.4  713.74
  4225.6  714.36  4243.9  713.22  4462.3  710.44  4610.2  709.26  4724.9  709.03
  4846.8  709.00  4933.6  708.11  4986.5  707.68  4987.0  706.88  4992.0  706.88
  4992.5  707.68  5016.3  708.47  5071.5  709.17  5098.1  709.84  5108.3  709.49
  5200.4  710.44  5221.2  711.07  5231.1  710.62  5272.7  710.95  5333.3  712.34
  5366.3  712.22  5425.4  713.31  5548.1  714.11  5553.7  714.71  5580.7  714.99
#Mann=7,-1,0
  3756.3     0.1       0  4724.9    0.05       0  4933.6     0.1       0
  4986.5    0.07       0  4992.5     0.1       0  5071.5    0.16       0
  5221.2     0.1       0
Bank Sta=4986.5,4992.5
Exp/Cntr=0.3,0.1

Type RM Length L Ch R = 1,30549,375,375,375
BEGIN DESCRIPTION:
BURNT BOOT CREEK 47.0
END DESCRIPTION:
XS GIS Cut Line= 3
      1991870.64     13617244.13      1990775.00     13617025.00
      1990341.96     13616869.36
#Sta/Elev= 30
  3871.2  718.59  3907.5  718.61  3938.1  717.72  4121.7  716.27  4307.0  713.52
  4374.0  712.66  4397.1  713.11  4417.4  712.12  4473.7  710.85  4626.6  708.66
  4723.4  707.62  4872.6  707.43  4944.6  707.33  4945.1  706.53  4950.3  706.53
  4950.8  707.33  4972.3  707.43  5099.5  709.76  5172.9  711.12  5182.9  711.85
  5190.4  711.30  5232.9  711.76  5318.0  713.85  5339.2  713.86  5371.1  712.70
  5381.7  712.92  5387.3  713.60  5418.1  713.67  5424.2  713.22  5448.7  713.51
#Mann=11,-1,0
  3871.2    0.05       0  4307.0     0.1       0  4374.0    0.05       0
  4473.7     0.1       0  4626.6    0.05       0  4872.6    0.12       0
  4944.6    0.07       0  4950.8    0.12       0  4972.3     0.1       0
  5099.5    0.16       0  5172.9     0.1       0
Bank Sta=4944.6,4950.8
Exp/Cntr=0.3,0.1

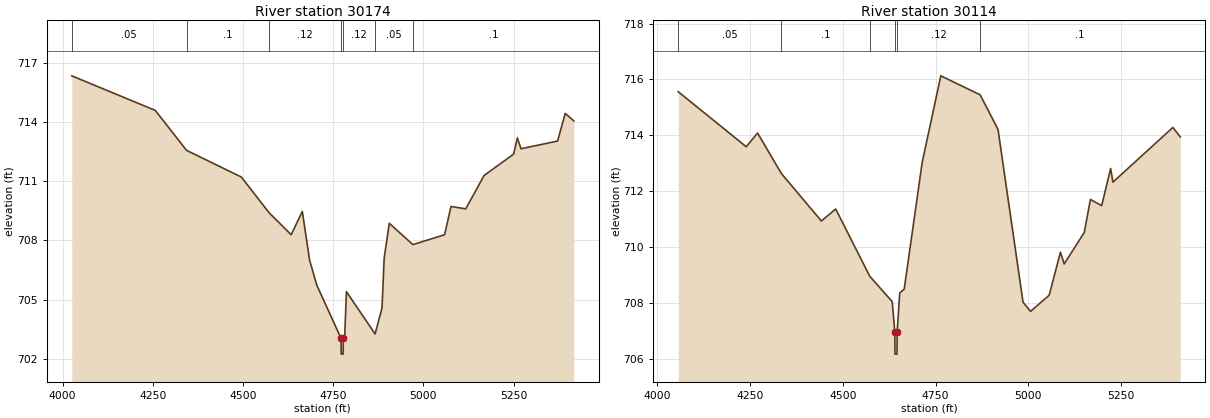
Type RM Length L Ch R = 1,30174,60,60,60
BEGIN DESCRIPTION:
Mapping XS 5eea2340
END DESCRIPTION:
XS GIS Cut Line= 4
      1991798.45     13616955.50      1991225.50     13616722.85
      1990812.31     13616684.65      1990461.65     13616611.75
#Sta/Elev= 30
  4025.4  716.33  4256.9  714.58  4343.5  712.56  4495.3  711.21  4572.4  709.40
  4633.5  708.29  4664.4  709.47  4684.5  707.01  4704.5  705.74  4771.7  703.05
  4772.2  702.25  4777.5  702.25  4778.0  703.05  4781.6  703.05  4786.6  705.41
  4866.1  703.27  4885.3  704.59  4891.2  707.10  4905.4  708.87  4970.8  707.79
  5058.7  708.29  5076.4  709.72  5117.3  709.60  5168.3  711.29  5250.1  712.37
  5260.3  713.19  5270.5  712.64  5371.9  713.03  5393.0  714.43  5416.9  714.05
#Mann=7,-1,0
  4025.4    0.05       0  4343.5     0.1       0  4572.4    0.12       0
  4771.7    0.07       0  4778.0    0.12       0  4866.1    0.05       0
  4970.8     0.1       0
Bank Sta=4771.7,4778
Exp/Cntr=0.3,0.1

Type RM Length L Ch R = 1,30114,59,59,59
BEGIN DESCRIPTION:
Mapping XS e00f684c
END DESCRIPTION:
XS GIS Cut Line= 4
      1991774.07     13616875.61      1991270.64     13616677.71
      1990833.14     13616625.63      1990465.13     13616573.55
#Sta/Elev= 30
  4056.4  715.56  4239.6  713.59  4270.3  714.08  4334.4  712.63  4442.2  710.93
  4480.8  711.36  4572.6  708.95  4633.2  708.04  4640.1  706.96  4640.6  706.16
  4645.9  706.16  4646.4  706.96  4653.4  708.35  4665.5  708.49  4713.8  713.02
  4764.1  716.13  4870.1  715.45  4918.3  714.21  4985.7  708.02  5005.9  707.69
  5056.2  708.27  5086.5  709.81  5096.6  709.39  5150.8  710.52  5167.3  711.70
  5197.6  711.48  5221.9  712.81  5227.9  712.32  5389.5  714.28  5409.6  713.94
#Mann=6,-1,0
  4056.4    0.05       0  4334.4     0.1       0  4572.6    0.12       0
  4640.1    0.07       0  4646.4    0.12       0  4870.1     0.1       0
Bank Sta=4640.1,4646.4
Exp/Cntr=0.3,0.1