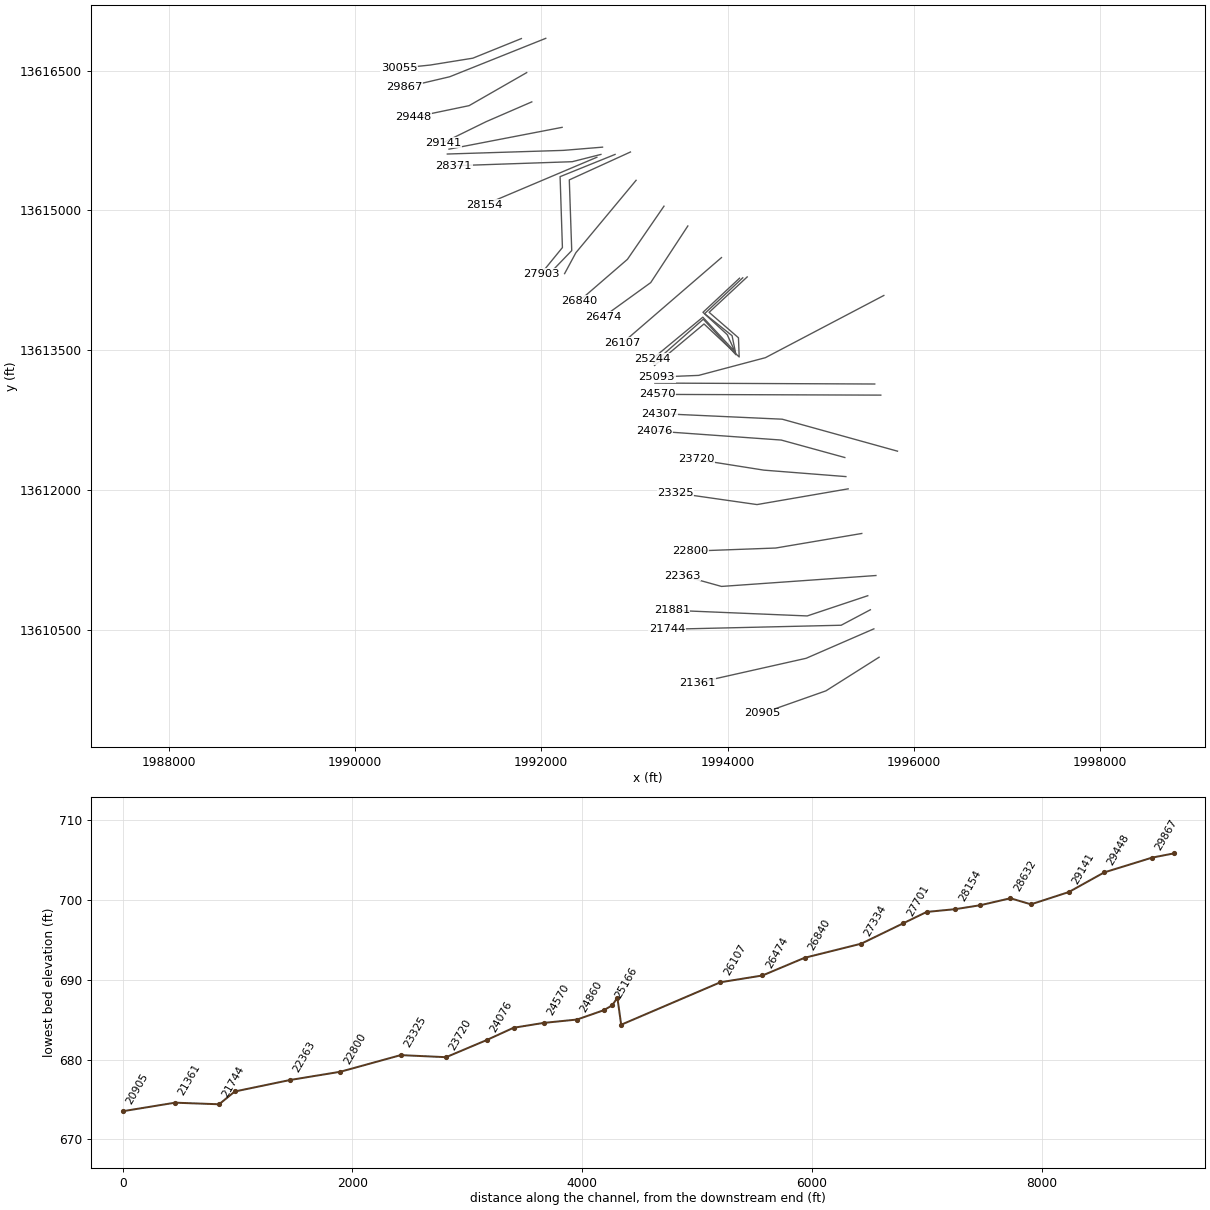
HEC-RAS study BURNT BOOT CREEK.prj: BURNT BOOT CREEK Base Level Engineering

--- BURNT BOOT CREEK.g01 (geometry) --- (continued)

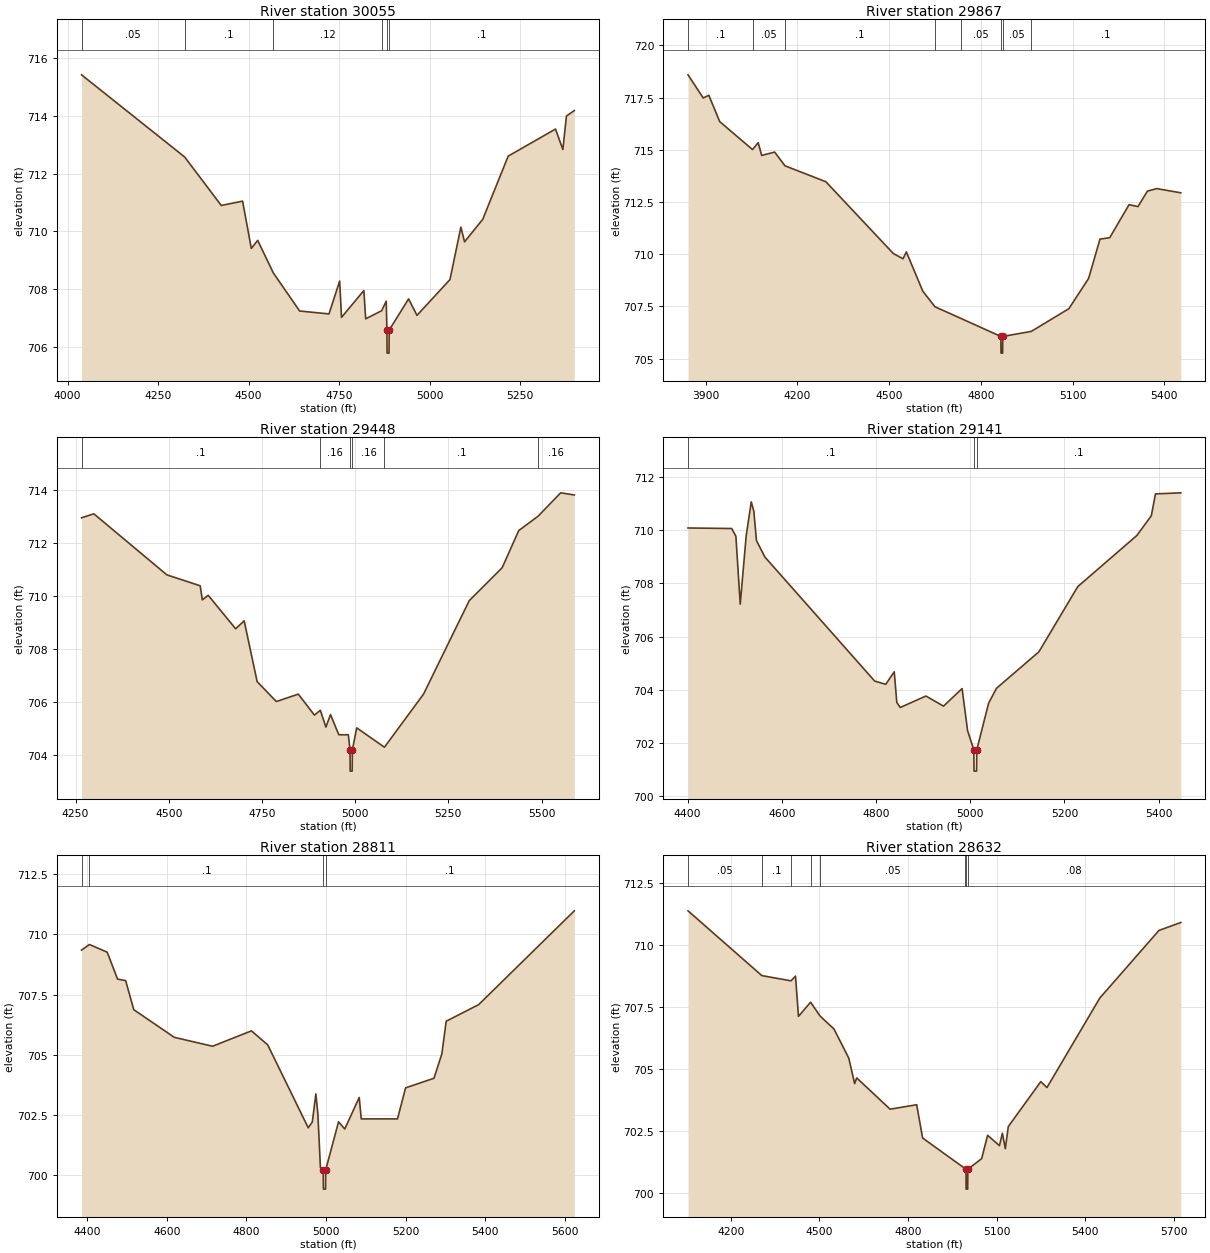
Type RM Length L Ch R = 1,30055,188,188,188
BEGIN DESCRIPTION:
Mapping XS f92fc803
END DESCRIPTION:
XS GIS Cut Line= 4
      1991786.28     13616845.25      1991265.43     13616634.74
      1990807.53     13616560.96      1990473.31     13616526.23
#Sta/Elev= 30
  4038.5  715.43  4323.5  712.58  4424.5  710.90  4483.5  711.05  4507.6  709.41
  4525.2  709.69  4568.5  708.56  4641.2  707.24  4722.3  707.14  4751.7  708.28
  4756.8  707.02  4818.6  707.95  4823.6  706.97  4867.7  707.25  4880.4  707.58
  4882.3  706.58  4882.8  705.78  4888.1  705.78  4888.6  706.58  4942.2  707.66
  4965.4  707.09  5056.5  708.33  5086.7  710.15  5096.8  709.64  5147.1  710.42
  5217.4  712.61  5348.1  713.55  5368.5  712.84  5378.3  714.00  5400.1  714.19
#Mann=6,-1,0
  4038.5    0.05       0  4323.5     0.1       0  4568.5    0.12       0
  4867.7     0.1       0  4882.3    0.07       0  4888.6     0.1       0
Bank Sta=4882.3,4888.6
Exp/Cntr=0.3,0.1

Type RM Length L Ch R = 1,29867,419,419,419
BEGIN DESCRIPTION:
BURNT BOOT CREEK 46.0
END DESCRIPTION:
XS GIS Cut Line= 3
      1992048.19     13616847.75      1991017.36     13616435.42
      1990528.76     13616320.35
#Sta/Elev= 30
  3842.0  718.59  3891.8  717.48  3910.1  717.61  3945.7  716.35  4053.0  715.01
  4071.6  715.34  4083.0  714.73  4125.5  714.89  4159.4  714.23  4293.0  713.47
  4513.8  710.03  4545.5  709.78  4556.3  710.11  4610.1  708.23  4650.0  707.48
  4735.2  706.92  4865.5  706.06  4866.0  705.26  4871.3  705.26  4871.8  706.06
  4965.1  706.30  5088.2  707.39  5152.7  708.84  5189.9  710.72  5221.8  710.79
  5284.9  712.37  5314.2  712.28  5345.1  713.02  5375.9  713.14  5454.2  712.94
#Mann=8,-1,0
  3842.0     0.1       0  4053.0    0.05       0  4159.4     0.1       0
  4650.0    0.12       0  4735.2    0.05       0  4865.5    0.07       0
  4871.8    0.05       0  4965.1     0.1       0
Bank Sta=4865.5,4871.8
Exp/Cntr=0.3,0.1

Type RM Length L Ch R = 1,29448,307,307,307
BEGIN DESCRIPTION:
BURNT BOOT CREEK 45.0
END DESCRIPTION:
XS GIS Cut Line= 3
      1991843.53     13616479.78      1991225.00     13616125.00
      1990629.16     13616000.81
#Sta/Elev= 30
  4266.1  712.94  4299.0  713.09  4495.0  710.79  4584.3  710.38  4590.1  709.85
  4605.9  710.02  4679.4  708.76  4702.3  709.06  4737.1  706.77  4788.6  706.02
  4847.5  706.30  4890.7  705.51  4906.6  705.69  4921.5  705.06  4933.9  705.53
  4956.1  704.77  4981.7  704.77  4986.2  704.20  4986.7  703.40  4992.0  703.40
  4992.5  704.20  5004.2  705.03  5078.5  704.30  5183.4  706.30  5306.0  709.82
  5394.3  711.06  5438.8  712.46  5490.7  713.00  5551.2  713.88  5587.8  713.80
#Mann=6,-1,0
  4266.1     0.1       0  4906.6    0.16       0  4986.2    0.07       0
  4992.5    0.16       0  5078.5     0.1       0  5490.7    0.16       0
Bank Sta=4986.2,4992.5
Exp/Cntr=0.3,0.1

Type RM Length L Ch R = 1,29141,330,330,330
BEGIN DESCRIPTION:
BURNT BOOT CREEK 44.0
END DESCRIPTION:
XS GIS Cut Line= 3
      1991898.21     13616165.54      1991407.79     13615952.88
      1990948.88     13615727.76
#Sta/Elev= 30
  4401.1  710.08  4493.8  710.06  4502.7  709.77  4511.9  707.22  4524.5  709.78
  4535.3  711.06  4540.8  710.71  4546.3  709.61  4564.2  708.99  4797.3  704.33
  4820.7  704.21  4838.7  704.68  4844.2  703.53  4851.5  703.34  4906.0  703.77
  4943.3  703.39  4982.7  704.05  4994.4  702.47  5007.6  701.75  5008.1  700.95
  5013.4  700.95  5013.9  701.75  5039.0  703.50  5055.7  704.06  5145.7  705.43
  5228.3  707.88  5353.7  709.80  5384.3  710.54  5393.1  711.36  5446.8  711.40
#Mann=3,-1,0
  4401.1     0.1       0  5007.6    0.07       0  5013.9     0.1       0
Bank Sta=5007.6,5013.9
Exp/Cntr=0.3,0.1

Type RM Length L Ch R = 1,28811,179,179,179
BEGIN DESCRIPTION:
Mapping XS 6a9e71a7
END DESCRIPTION:
XS GIS Cut Line= 2
      1992223.73     13615892.11      1991009.21     13615657.88
#Sta/Elev= 30
  4386.2  709.35  4406.1  709.58  4450.6  709.26  4476.6  708.14  4496.9  708.08
  4517.3  706.87  4619.1  705.72  4715.1  705.35  4812.6  705.99  4853.4  705.41
  4955.2  701.96  4965.4  702.20  4974.4  703.37  4979.5  702.51  4985.8  700.30
  4992.8  700.21  4993.3  699.41  4998.6  699.41  4999.1  700.21  5031.3  702.21
  5046.9  701.91  5083.2  703.22  5088.3  702.33  5179.3  702.33  5199.6  703.62
  5270.9  704.02  5290.7  705.04  5301.5  706.39  5383.0  707.08  5623.1  710.98
#Mann=4,-1,0
  4386.2    0.08       0  4406.1     0.1       0  4992.8    0.07       0
  4999.1     0.1       0
Bank Sta=4992.8,4999.1
Exp/Cntr=0.3,0.1

Type RM Length L Ch R = 1,28632,261,261,261
BEGIN DESCRIPTION:
BURNT BOOT CREEK 43.0
END DESCRIPTION:
XS GIS Cut Line= 3
      1992657.81     13615679.45      1992236.78     13615644.72
      1990991.15     13615605.66
#Sta/Elev= 30
  4054.9  711.38  4305.0  708.77  4403.8  708.56  4418.9  708.75  4429.0  707.13
  4470.0  707.70  4502.3  707.14  4549.2  706.62  4599.2  705.45  4619.2  704.42
  4626.1  704.65  4739.3  703.39  4829.3  703.57  4849.3  702.23  4994.0  700.99
  4996.2  700.97  4996.7  700.17  5002.0  700.17  5002.5  700.97  5049.4  701.40
  5069.4  702.34  5109.5  701.92  5119.5  702.42  5129.5  701.80  5139.5  702.69
  5249.5  704.50  5270.4  704.26  5449.6  707.87  5649.7  710.59  5723.6  710.91
#Mann=8,-1,0
  4054.9    0.05       0  4305.0     0.1       0  4403.8    0.05       0
  4470.0    0.08       0  4502.3    0.05       0  4994.0    0.08       0
  4996.2    0.07       0  5002.5    0.08       0
Bank Sta=4996.2,5002.5
Exp/Cntr=0.3,0.1

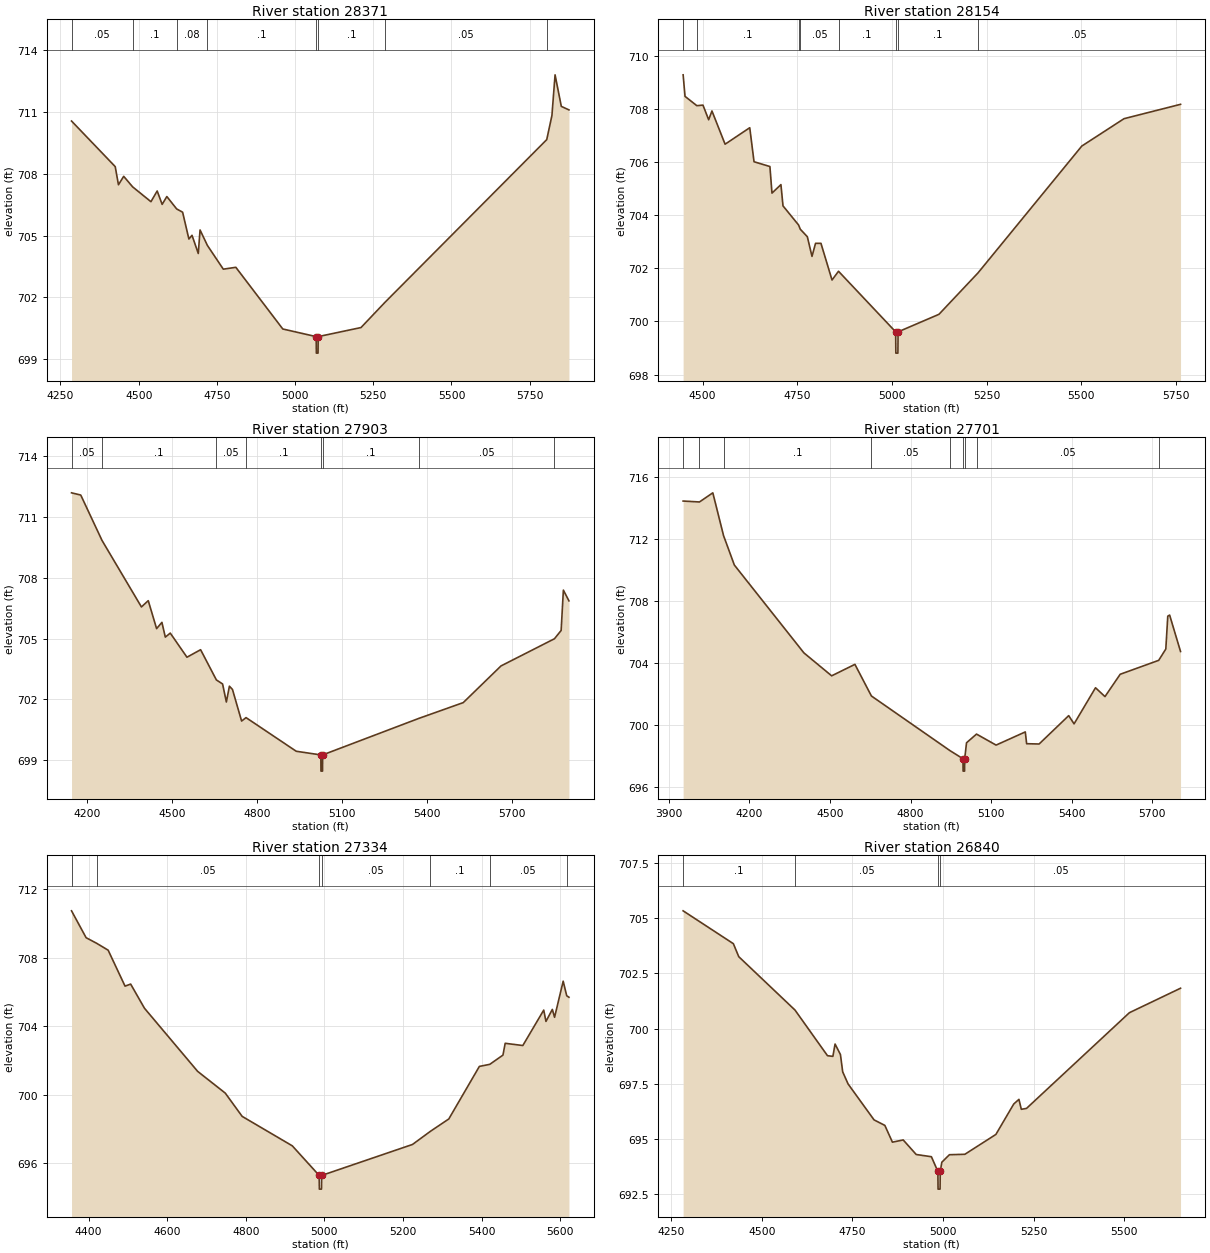
Type RM Length L Ch R = 1,28371,217,217,217
BEGIN DESCRIPTION:
BURNT BOOT CREEK 42.0
END DESCRIPTION:
XS GIS Cut Line= 3
      1992640.40     13615601.31      1992332.27     13615523.20
      1991060.59     13615479.79
#Sta/Elev= 30
  4285.3  710.55  4425.0  708.34  4435.3  707.46  4452.1  707.87  4480.6  707.36
  4539.2  706.64  4559.1  707.16  4575.0  706.51  4590.0  706.89  4621.4  706.29
  4640.5  706.13  4660.5  704.83  4670.5  705.01  4690.5  704.13  4696.2  705.27
  4719.7  704.52  4770.5  703.37  4810.6  703.46  4960.7  700.47  5067.5  700.10
  5068.0  699.30  5073.4  699.30  5073.9  700.10  5210.8  700.54  5287.2  701.76
  5804.6  709.65  5821.2  710.82  5831.2  712.79  5851.2  711.26  5875.6  711.09
#Mann=8,-1,0
  4285.3    0.05       0  4480.6     0.1       0  4621.4    0.08       0
  4719.7     0.1       0  5067.5    0.07       0  5073.9     0.1       0
  5287.2    0.05       0  5804.6     0.1       0
Bank Sta=5067.5,5073.9
Exp/Cntr=0.3,0.1

Type RM Length L Ch R = 1,28154,251,251,251
BEGIN DESCRIPTION:
Mapping XS 1578e84a
END DESCRIPTION:
XS GIS Cut Line= 2
      1992597.03     13615570.94      1991387.56     13615059.41
#Sta/Elev= 30
  4448.6  709.28  4453.6  708.47  4484.7  708.12  4501.0  708.14  4516.0  707.59
  4524.7  707.92  4559.4  706.67  4624.5  707.29  4635.8  706.01  4677.7  705.83
  4683.2  704.83  4706.8  705.15  4712.3  704.35  4753.4  703.63  4758.0  703.47
  4776.5  703.19  4788.8  702.45  4798.2  702.94  4812.5  702.94  4841.7  701.56
  4858.8  701.89  5009.7  699.61  5010.2  698.81  5015.6  698.81  5016.1  699.61
  5124.0  700.27  5227.2  701.83  5501.1  706.60  5612.6  707.63  5761.8  708.17
#Mann=8,-1,0
  4448.6    0.05       0  4484.7     0.1       0  4753.4    0.08       0
  4758.0    0.05       0  4858.8     0.1       0  5009.7    0.07       0
  5016.1     0.1       0  5227.2    0.05       0
Bank Sta=5009.7,5016.1
Exp/Cntr=0.3,0.1

Type RM Length L Ch R = 1,27903,202,202,202
BEGIN DESCRIPTION:
Mapping XS 41640e0c
END DESCRIPTION:
XS GIS Cut Line= 4
      1992792.35     13615601.33      1992202.06     13615362.61
      1992227.02     13614601.41      1991999.42     13614322.40
#Sta/Elev= 30
  4143.7  712.19  4176.3  712.08  4251.5  709.84  4390.8  706.56  4414.9  706.87
  4444.4  705.49  4463.2  705.80  4475.2  705.07  4492.7  705.27  4551.7  704.08
  4600.0  704.45  4655.7  702.96  4677.7  702.76  4691.0  701.87  4701.8  702.65
  4712.6  702.49  4744.9  700.93  4760.6  701.10  4938.1  699.44  5025.0  699.26
  5025.5  698.46  5030.9  698.46  5031.4  699.26  5371.2  701.06  5528.4  701.84
  5661.9  703.65  5850.8  704.99  5874.5  705.40  5882.4  707.39  5902.1  706.86
#Mann=8,-1,0
  4143.7    0.05       0  4251.5     0.1       0  4655.7    0.05       0
  4760.6     0.1       0  5025.0    0.07       0  5031.4     0.1       0
  5371.2    0.05       0  5850.8     0.1       0
Bank Sta=5025,5031.4
Exp/Cntr=0.3,0.1

Type RM Length L Ch R = 1,27701,367,367,367
BEGIN DESCRIPTION:
BURNT BOOT CREEK 39.0
END DESCRIPTION:
XS GIS Cut Line= 4
      1992957.30     13615627.37      1992300.90     13615327.88
      1992327.01     13614568.93      1992070.47     13614302.17
#Sta/Elev= 30
  3953.7  714.48  4014.5  714.42  4064.2  715.01  4104.1  712.25  4144.3  710.35
  4403.2  704.68  4506.4  703.20  4593.0  703.94  4654.3  701.90  4947.0  698.37
  4995.1  697.85  4995.6  697.05  5001.0  697.05  5001.5  697.85  5008.3  698.88
  5045.5  699.44  5118.3  698.73  5227.0  699.58  5232.0  698.82  5278.4  698.80
  5388.5  700.63  5408.5  700.10  5488.3  702.43  5523.5  701.86  5580.1  703.30
  5723.4  704.20  5749.9  704.93  5757.2  707.05  5764.1  707.12  5804.7  704.77
#Mann=9,-1,0
  3953.7    0.05       0  4014.5    0.08       0  4104.1     0.1       0
  4654.3    0.05       0  4947.0    0.08       0  4995.1    0.07       0
  5001.5    0.08       0  5045.5    0.05       0  5723.4    0.16       0
Bank Sta=4995.1,5001.5
Exp/Cntr=0.3,0.1

Type RM Length L Ch R = 1,27334,494,494,494
BEGIN DESCRIPTION:
Mapping XS f73a0306
END DESCRIPTION:
XS GIS Cut Line= 3
      1993018.02     13615323.53      1992371.51     13614546.03
      1992250.54     13614321.64
#Sta/Elev= 30
  4356.5  710.75  4393.6  709.18  4420.6  708.85  4449.7  708.45  4492.7  706.35
  4507.0  706.47  4542.1  705.06  4677.5  701.37  4747.8  700.10  4790.8  698.74
  4918.4  697.02  4986.8  695.29  4987.3  694.49  4992.7  694.49  4993.2  695.29
  5224.4  697.10  5270.1  697.87  5316.8  698.59  5394.6  701.66  5421.0  701.78
  5454.6  702.32  5460.3  703.01  5505.2  702.88  5558.4  704.95  5564.1  704.29
  5580.3  704.99  5586.0  704.53  5607.9  706.64  5616.9  705.79  5622.6  705.70
#Mann=7,-1,0
  4356.5     0.1       0  4420.6    0.05       0  4986.8   0.035       0
  4993.2    0.05       0  5270.1     0.1       0  5421.0    0.05       0
  5616.9     0.1       0
Bank Sta=4986.8,4993.2
Exp/Cntr=0.3,0.1

Type RM Length L Ch R = 1,26840,366,366,366
BEGIN DESCRIPTION:
BURNT BOOT CREEK 38.0
END DESCRIPTION:
XS GIS Cut Line= 3
      1993317.52     13615045.78      1992925.00     13614475.00
      1992410.36     13614030.11
#Sta/Elev= 30
  4282.7  705.34  4421.4  703.85  4436.3  703.26  4591.5  700.84  4681.2  698.77
  4696.1  698.74  4702.1  699.30  4717.0  698.82  4723.1  698.04  4738.0  697.49
  4809.7  695.86  4839.5  695.61  4860.4  694.85  4890.2  694.95  4926.1  694.29
  4968.0  694.19  4985.9  693.52  4986.4  692.72  4991.9  692.72  4992.4  693.52
  4996.8  693.94  5017.7  694.28  5060.4  694.30  5146.0  695.20  5195.3  696.58
  5209.6  696.79  5216.2  696.34  5230.5  696.38  5514.5  700.72  5655.7  701.83
#Mann=4,-1,0
  4282.7     0.1       0  4591.5    0.05       0  4985.9   0.035       0
  4992.4    0.05       0
Bank Sta=4985.9,4992.4
Exp/Cntr=0.3,0.1

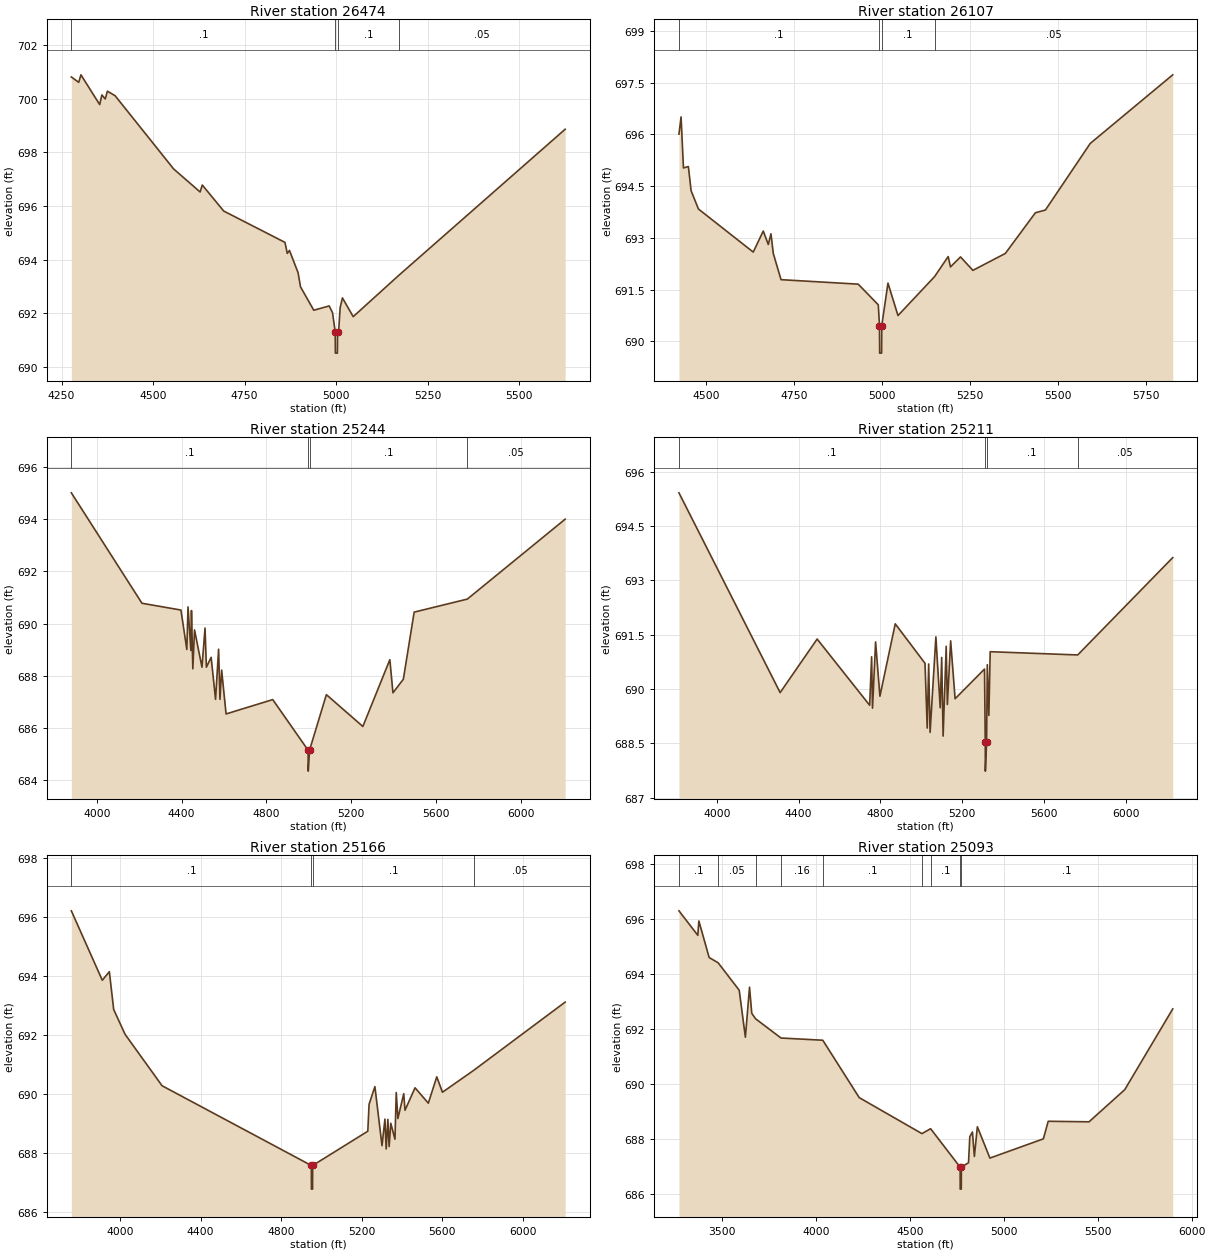
Type RM Length L Ch R = 1,26474,367,367,367
BEGIN DESCRIPTION:
BURNT BOOT CREEK 37.0
END DESCRIPTION:
XS GIS Cut Line= 3
      1993573.57     13614833.07      1993175.00     13614225.00
      1992670.80     13613860.86
#Sta/Elev= 30
  4276.8  700.81  4297.0  700.61  4303.0  700.89  4354.2  699.78  4360.2  700.14
  4369.3  699.99  4375.3  700.28  4396.4  700.11  4556.2  697.38  4628.6  696.52
  4634.5  696.78  4693.0  695.81  4860.4  694.64  4866.7  694.23  4872.7  694.34
  4896.2  693.51  4902.9  692.98  4939.1  692.11  4981.2  692.27  4990.3  692.02
  4997.6  691.31  4998.1  690.51  5003.6  690.51  5004.1  691.31  5006.9  691.31
  5011.2  692.21  5017.4  692.57  5046.8  691.87  5172.1  693.42  5625.8  698.86
#Mann=4,-1,0
  4276.8     0.1       0  4997.6    0.07       0  5004.1     0.1       0
  5172.1    0.05       0
Bank Sta=4997.6,5004.1
Exp/Cntr=0.3,0.1

Type RM Length L Ch R = 1,26107,863,863,863
BEGIN DESCRIPTION:
Mapping XS 98797c43
END DESCRIPTION:
XS GIS Cut Line= 2
      1993934.72     13614493.70      1992872.21     13613577.02
#Sta/Elev= 30
  4423.5  696.01  4429.5  696.51  4436.3  695.03  4450.3  695.07  4458.0  694.37
  4478.8  693.84  4634.6  692.59  4663.1  693.20  4677.4  692.81  4685.0  693.12
  4691.6  692.55  4713.6  691.79  4933.0  691.66  4990.0  691.06  4993.4  690.46
  4993.9  689.66  4999.4  689.66  4999.9  690.46  5017.5  691.69  5046.0  690.75
  5150.1  691.88  5188.6  692.46  5195.2  692.16  5223.7  692.45  5258.8  692.06
  5351.0  692.55  5436.5  693.73  5465.0  693.81  5592.3  695.74  5826.8  697.73
#Mann=4,-1,0
  4423.5     0.1       0  4993.4    0.07       0  4999.9     0.1       0
  5150.1    0.05       0
Bank Sta=4993.4,4999.9
Exp/Cntr=0.3,0.1

Type RM Length L Ch R = 1,25244,33,33,33
BEGIN DESCRIPTION:
Mapping XS 58b62def
END DESCRIPTION:
XS GIS Cut Line= 6
      1994128.44     13614272.32      1993736.09     13613906.01
      1993996.51     13613666.43      1994079.84     13613482.40
      1993734.35     13613853.93      1993190.95     13613404.28
#Sta/Elev= 30
  3879.8  695.01  4212.9  690.78  4396.8  690.52  4424.5  689.01  4430.1  690.64
  4443.7  688.97  4446.4  690.50  4452.8  688.27  4460.8  689.76  4496.0  688.33
  4510.4  689.83  4516.8  688.33  4539.2  688.71  4560.0  687.10  4574.4  689.02
  4580.8  687.10  4588.8  688.22  4609.6  686.54  4829.8  687.09  4996.7  685.15
  4997.2  684.35  5003.3  685.15  5082.8  687.28  5254.9  686.06  5382.2  688.62
  5396.9  687.35  5445.9  687.87  5496.9  690.44  5747.8  690.94  6209.1  694.00
#Mann=4,-1,0
  3879.8     0.1       0  4996.7    0.07       0  5003.3     0.1       0
  5747.8    0.05       0
Bank Sta=4996.7,5003.3
Exp/Cntr=0.3,0.1

Type RM Length L Ch R = 1,25211,45,45,45
BEGIN DESCRIPTION:
Mapping XS 7a77f8f2
END DESCRIPTION:
XS GIS Cut Line= 6
      1994163.18     13614276.67      1993753.45     13613891.25
      1994048.59     13613655.14      1994090.26     13613450.28
      1993739.56     13613832.22      1993204.88     13613360.03
#Sta/Elev= 30
  3814.9  695.42  4309.9  689.90  4490.9  691.38  4747.8  689.55  4757.3  690.89
  4761.7  689.47  4776.8  691.30  4797.9  689.80  4872.9  691.80  5018.5  690.71
  5029.3  688.92  5036.4  690.69  5043.4  688.80  5071.7  691.44  5092.9  689.48
  5100.0  690.87  5107.1  688.70  5122.2  691.18  5127.9  689.57  5143.9  691.33
  5165.7  689.73  5309.6  690.55  5313.2  688.53  5313.7  687.73  5319.8  688.53
  5323.2  690.67  5330.8  689.27  5337.4  691.03  5765.4  690.94  6230.3  693.63
#Mann=4,-1,0
  3814.9     0.1       0  5313.2    0.07       0  5319.8     0.1       0
  5765.4    0.05       0
Bank Sta=5313.2,5319.8
Exp/Cntr=0.3,0.1

Type RM Length L Ch R = 1,25166,73,73,73
BEGIN DESCRIPTION:
Mapping XS 179b10b2
END DESCRIPTION:
XS GIS Cut Line= 6
      1994210.89     13614286.19      1993802.06     13613906.01
      1994117.17     13613632.57      1994124.98     13613426.84
      1993747.38     13613781.01      1993216.10     13613335.68
#Sta/Elev= 30
  3757.4  696.20  3911.1  693.85  3946.2  694.14  3967.8  692.86  4024.4  692.02
  4208.1  690.28  4949.9  687.58  4950.4  686.78  4956.0  686.78  4956.5  687.58
  5230.5  688.74  5236.8  689.65  5265.8  690.25  5301.1  688.25  5315.6  689.15
  5321.9  688.14  5330.2  689.14  5336.5  688.22  5344.7  689.01  5365.5  688.47
  5371.8  690.05  5380.0  689.17  5409.1  690.01  5415.4  689.45  5465.2  690.21
  5531.2  689.69  5573.2  690.58  5601.5  690.06  5758.6  690.81  6211.1  693.11
#Mann=4,-1,0
  3757.4     0.1       0  4949.9    0.07       0  4956.5     0.1       0
  5758.6    0.05       0
Bank Sta=4949.9,4956.5
Exp/Cntr=0.3,0.1

Type RM Length L Ch R = 1,25093,233,233,233
BEGIN DESCRIPTION:
Mapping XS 83e04208
END DESCRIPTION:
XS GIS Cut Line= 4
      1995678.04     13614087.05      1994406.23     13613419.03
      1993690.08     13613228.93      1993239.78     13613210.71
#Sta/Elev= 30
  3271.1  696.30  3371.4  695.41  3377.1  695.93  3431.9  694.60  3479.5  694.41
  3591.9  693.41  3624.7  691.70  3646.7  693.52  3658.6  692.57  3679.1  692.37
  3814.4  691.67  4036.6  691.59  4230.7  689.50  4564.5  688.19  4610.5  688.37
  4767.7  686.97  4768.2  686.17  4773.8  686.17  4774.3  686.97  4812.4  687.13
  4819.2  688.08  4833.1  688.25  4843.5  687.36  4859.4  688.44  4926.2  687.30
  5210.7  688.00  5236.6  688.64  5453.7  688.62  5643.9  689.79  5899.3  692.73
#Mann=9,-1,0
  3271.1     0.1       0  3479.5    0.05       0  3679.1     0.1       0
  3814.4    0.16       0  4036.6     0.1       0  4564.5    0.08       0
  4610.5     0.1       0  4767.7    0.07       0  4774.3     0.1       0
Bank Sta=4767.7,4774.3
Exp/Cntr=0.3,0.1

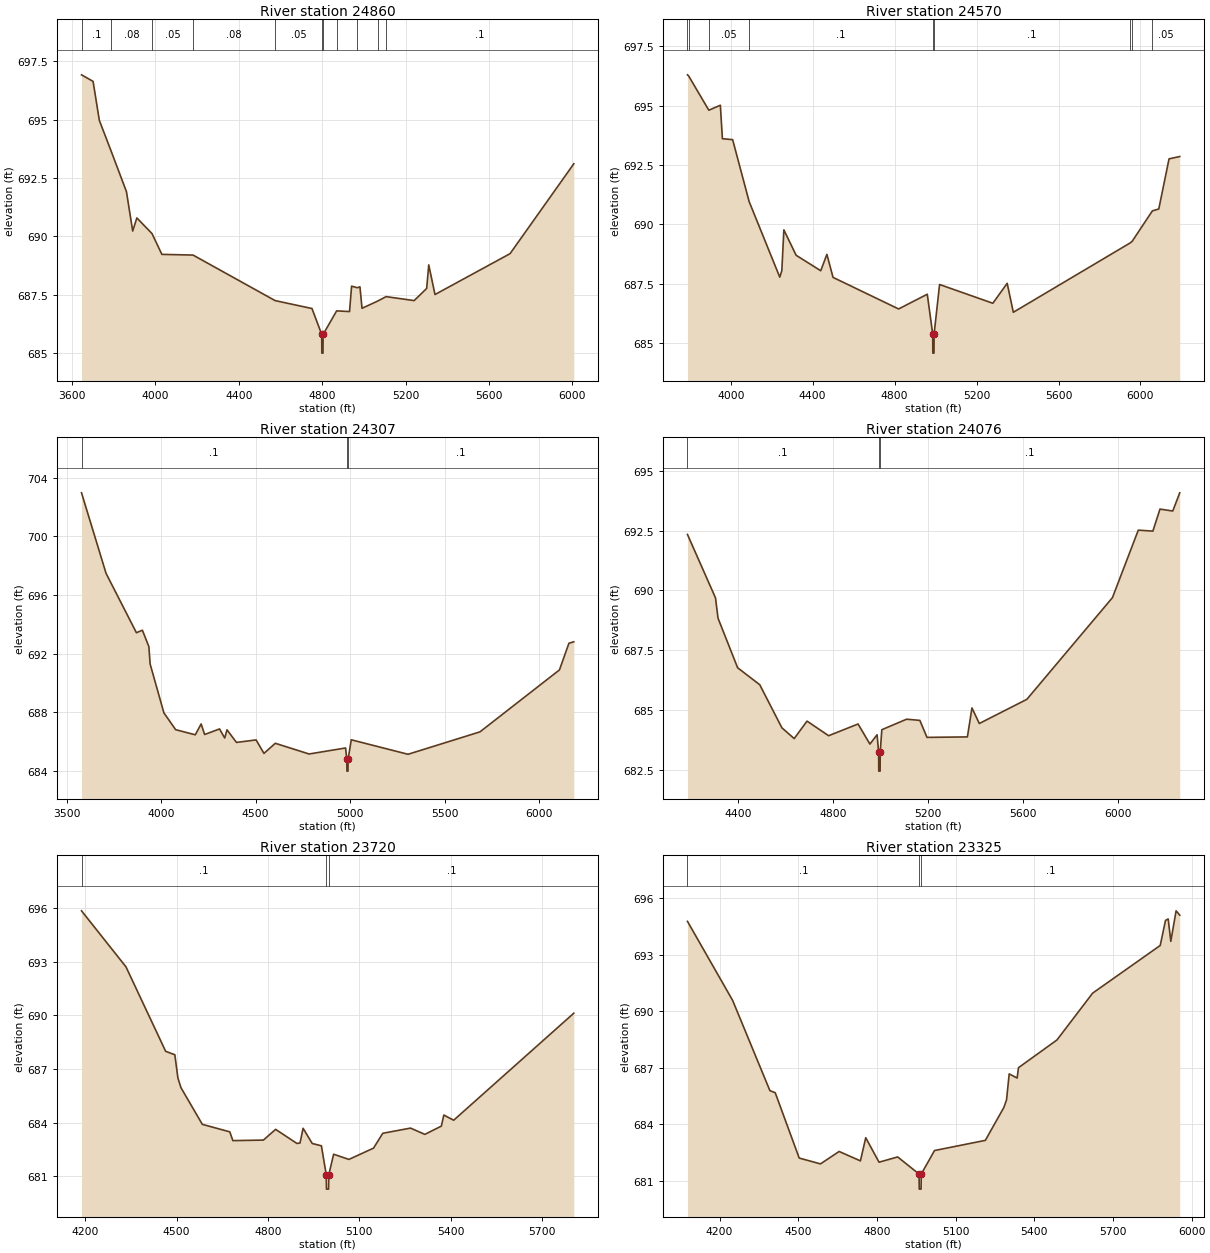
Type RM Length L Ch R = 1,24860,290,290,290
BEGIN DESCRIPTION:
BURNT BOOT CREEK 36.0
END DESCRIPTION:
XS GIS Cut Line= 2
      1995580.37     13613136.39      1993219.19     13613146.37
#Sta/Elev= 30
  3645.8  696.92  3701.2  696.64  3731.2  694.97  3787.1  693.67  3861.2  691.92
  3891.2  690.23  3911.2  690.79  3983.9  690.12  4031.2  689.23  4180.7  689.20
  4574.3  687.25  4751.2  686.91  4797.9  685.80  4798.4  685.00  4804.0  685.00
  4804.5  685.80  4869.5  686.81  4931.2  686.78  4941.2  687.87  4968.0  687.80
  4981.2  687.84  4991.2  686.92  5066.4  687.23  5106.6  687.42  5241.2  687.25
  5301.2  687.77  5311.2  688.78  5341.2  687.51  5701.2  689.26  6007.0  693.11
#Mann=11,-1,0
  3645.8     0.1       0  3787.1    0.08       0  3983.9    0.05       0
  4180.7    0.08       0  4574.3    0.05       0  4797.9    0.04       0
  4804.5    0.05       0  4869.5    0.08       0  4968.0    0.05       0
  5066.4    0.08       0  5106.6     0.1       0
Bank Sta=4797.9,4804.5
Exp/Cntr=0.3,0.1

Type RM Length L Ch R = 1,24570,263,263,263
BEGIN DESCRIPTION:
BURNT BOOT CREEK 35.0
END DESCRIPTION:
XS GIS Cut Line= 2
      1995645.46     13613017.03      1993242.67     13613024.84
#Sta/Elev= 30
  3788.9  696.30  3794.8  696.25  3893.2  694.81  3949.4  695.02  3959.4  693.61
  4009.4  693.57  4090.0  690.96  4239.4  687.78  4249.4  688.05  4259.4  689.77
  4319.4  688.70  4439.4  688.05  4469.4  688.74  4499.4  687.77  4819.4  686.44
  4959.4  687.06  4986.0  685.38  4986.5  684.58  4992.2  684.58  4992.7  685.38
  5019.4  687.47  5279.4  686.68  5349.4  687.52  5379.4  686.30  5949.6  689.22
  5959.6  689.29  6058.0  690.57  6089.4  690.65  6139.4  692.76  6191.7  692.86
#Mann=9,-1,0
  3788.9    0.05       0  3794.8    0.08       0  3893.2    0.05       0
  4090.0     0.1       0  4986.0    0.07       0  4992.7     0.1       0
  5949.6    0.05       0  5959.6    0.08       0  6058.0    0.05       0
Bank Sta=4986,4992.7
Exp/Cntr=0.3,0.1

Type RM Length L Ch R = 1,24307,231,231,231
BEGIN DESCRIPTION:
BURNT BOOT CREEK 34.0
END DESCRIPTION:
XS GIS Cut Line= 3
      1995824.70     13612415.19      1994587.07     13612758.58
      1993269.13     13612818.79
#Sta/Elev= 30
  3579.2  702.97  3709.0  697.47  3869.5  693.42  3901.1  693.59  3935.4  692.47
  3942.1  691.28  4014.8  687.95  4077.0  686.80  4180.8  686.45  4211.9  687.19
  4230.3  686.47  4309.2  686.85  4336.5  686.23  4348.6  686.79  4398.7  685.93
  4502.5  686.10  4544.0  685.18  4604.1  685.87  4782.7  685.14  4975.8  685.55
  4982.4  684.77  4982.9  683.97  4988.6  683.97  4989.1  684.77  5005.8  686.11
  5306.1  685.12  5686.5  686.65  6107.0  690.88  6157.0  692.70  6182.9  692.80
#Mann=3,-1,0
  3579.2     0.1       0  4982.4    0.07       0  4989.1     0.1       0
Bank Sta=4982.4,4989.1
Exp/Cntr=0.3,0.1

Type RM Length L Ch R = 1,24076,356,356,356
BEGIN DESCRIPTION:
BURNT BOOT CREEK 33.0
END DESCRIPTION:
XS GIS Cut Line= 3
      1995258.93     13612347.13      1994576.66     13612534.63
      1993211.91     13612632.19
#Sta/Elev= 30
  4186.3  692.34  4304.5  689.69  4315.2  688.84  4397.8  686.77  4491.1  686.06
  4584.5  684.26  4636.3  683.81  4690.5  684.54  4781.5  683.93  4905.6  684.42
  4955.7  683.58  4985.8  683.97  4992.4  683.25  4992.9  682.45  4998.6  682.45
  4999.1  683.25  5005.8  684.18  5110.3  684.62  5166.2  684.57  5196.3  683.86
  5366.7  683.88  5385.9  685.09  5416.9  684.44  5617.4  685.45  5978.3  689.70
  6087.3  692.52  6148.7  692.48  6178.8  693.40  6232.6  693.32  6262.1  694.08
#Mann=3,-1,0
  4186.3     0.1       0  4992.4    0.07       0  4999.1     0.1       0
Bank Sta=4992.4,4999.1
Exp/Cntr=0.3,0.1

Type RM Length L Ch R = 1,23720,395,395,395
BEGIN DESCRIPTION:
BURNT BOOT CREEK 32.0
END DESCRIPTION:
XS GIS Cut Line= 3
      1995270.59     13612142.32      1994389.16     13612211.71
      1993665.23     13612326.29
#Sta/Elev= 30
  4187.7  695.84  4333.7  692.71  4464.1  687.99  4494.2  687.80  4504.3  686.50
  4514.3  685.96  4584.5  683.91  4674.8  683.49  4684.8  683.00  4785.1  683.03
  4825.3  683.63  4895.5  682.84  4905.5  682.87  4915.5  683.69  4945.6  682.84
  4975.7  682.71  4991.6  681.09  4992.3  680.29  4999.2  680.29  5000.0  681.09
  5015.8  682.24  5066.0  681.95  5146.9  682.58  5177.3  683.41  5268.4  683.70
  5315.4  683.35  5369.7  683.81  5377.8  684.43  5410.2  684.14  5804.8  690.12
#Mann=3,-1,0
  4187.7     0.1       0  4991.6    0.07       0  5000.0     0.1       0
Bank Sta=4991.6,5000
Exp/Cntr=0.3,0.1

Type RM Length L Ch R = 1,23325,525,525,525
BEGIN DESCRIPTION:
BURNT BOOT CREEK 31.0
END DESCRIPTION:
XS GIS Cut Line= 3
      1995294.75     13612010.78      1994316.24     13611841.92
      1993441.20     13611966.92
#Sta/Elev= 30
  4077.8  694.77  4250.1  690.57  4392.1  685.78  4412.4  685.67  4503.8  682.20
  4584.9  681.89  4656.0  682.55  4737.2  682.05  4757.5  683.28  4808.2  681.98
  4879.2  682.26  4960.8  681.35  4961.5  680.55  4968.4  680.55  4969.2  681.35
  5019.7  682.60  5213.5  683.14  5284.2  684.89  5294.3  685.29  5304.4  686.67
  5334.7  686.45  5339.9  687.00  5486.4  688.47  5622.7  690.96  5880.2  693.49
  5900.4  694.82  5910.6  694.90  5920.6  693.71  5940.8  695.33  5954.7  695.10
#Mann=3,-1,0
  4077.8     0.1       0  4960.8    0.07       0  4969.2     0.1       0
Bank Sta=4960.8,4969.2
Exp/Cntr=0.3,0.1

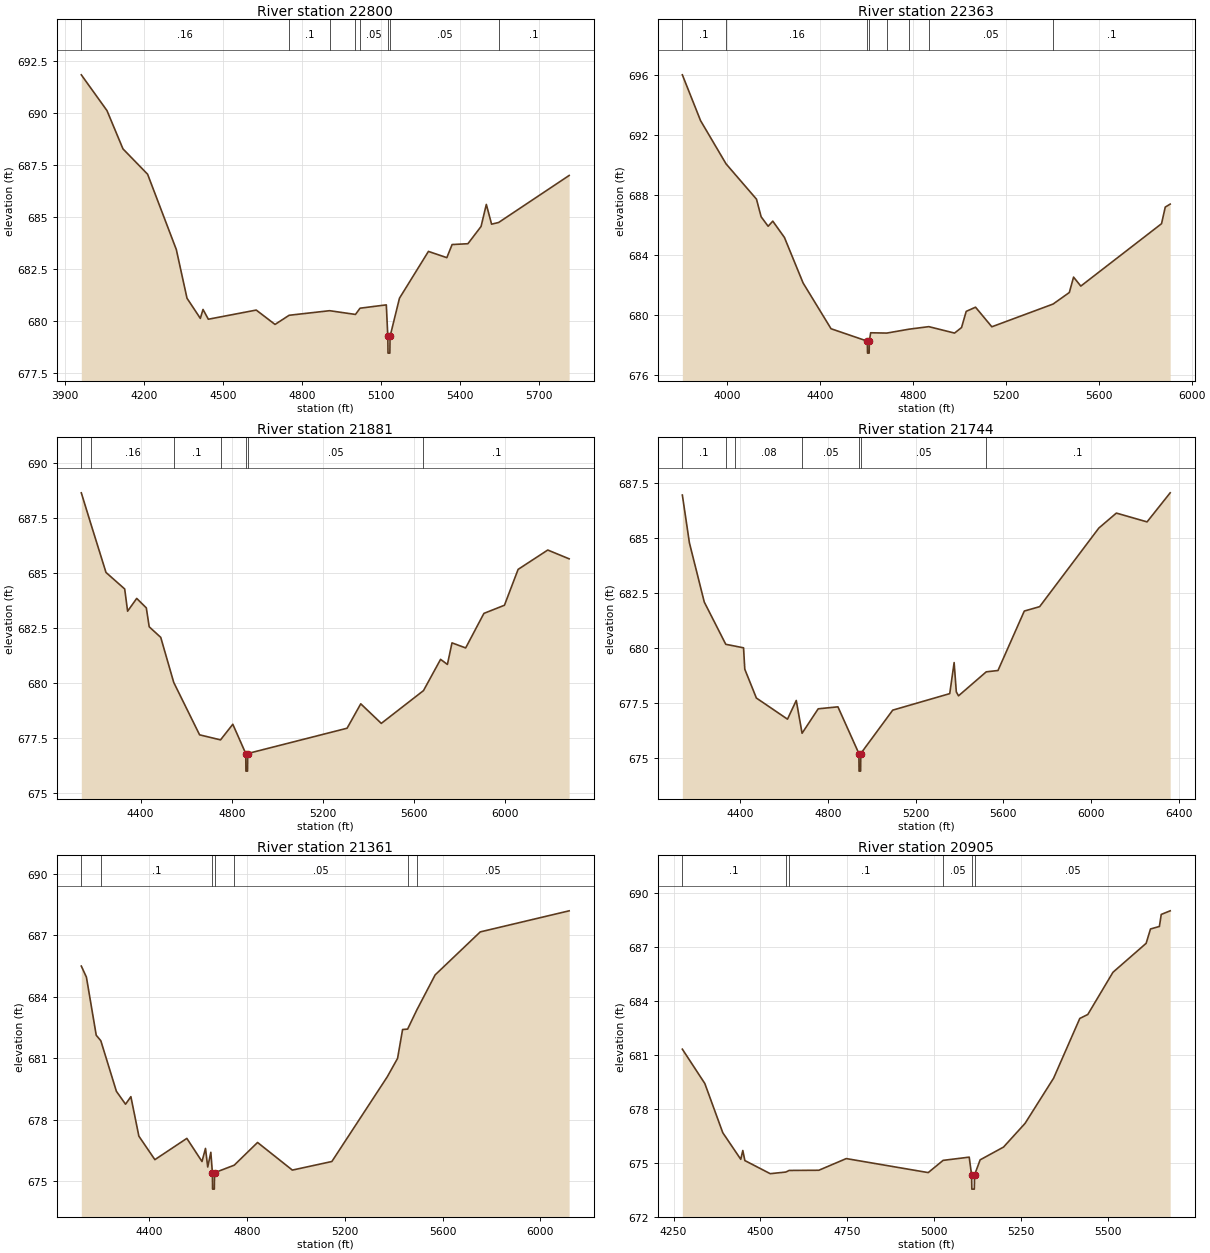
Type RM Length L Ch R = 1,22800,437,437,437
BEGIN DESCRIPTION:
BURNT BOOT CREEK 30.0
END DESCRIPTION:
XS GIS Cut Line= 3
      1995441.19     13611531.58      1994516.76     13611375.34
      1993600.43     13611341.45
#Sta/Elev= 30
  3961.7  691.85  4059.3  690.13  4120.1  688.29  4213.8  687.07  4322.9  683.45
  4363.5  681.11  4414.2  680.14  4424.4  680.57  4444.6  680.10  4626.7  680.54
  4698.2  679.85  4751.8  680.29  4905.6  680.51  5003.9  680.33  5021.4  680.63
  5121.2  680.79  5126.9  679.27  5127.7  678.47  5134.7  678.47  5135.4  679.27
  5171.2  681.11  5281.3  683.36  5351.3  683.06  5371.3  683.69  5431.4  683.73
  5481.4  684.56  5501.4  685.62  5521.4  684.67  5548.1  684.75  5816.2  687.01
#Mann=8,-1,0
  3961.7    0.16       0  4751.8     0.1       0  4905.6    0.05       0
  5003.9    0.16       0  5021.4    0.05       0  5126.9    0.03       0
  5135.4    0.05       0  5548.1     0.1       0
Bank Sta=5126.9,5135.4
Exp/Cntr=0.3,0.1

Type RM Length L Ch R = 1,22363,482,482,482
BEGIN DESCRIPTION:
Mapping XS e878b054
END DESCRIPTION:
XS GIS Cut Line= 3
      1995593.12     13611080.20      1993935.16     13610963.01
      1993514.54     13611080.09
#Sta/Elev= 30
  3808.9  696.04  3887.2  692.98  3996.9  690.09  4127.8  687.73  4147.9  686.55
  4177.9  685.92  4198.0  686.26  4248.1  685.17  4328.3  682.13  4448.6  679.07
  4604.8  678.24  4605.5  677.44  4612.5  677.44  4613.3  678.24  4619.0  678.80
  4688.5  678.78  4784.2  679.04  4869.2  679.21  4979.9  678.78  5010.0  679.15
  5030.1  680.23  5070.2  680.51  5140.3  679.20  5403.8  680.72  5473.7  681.49
  5491.9  682.52  5523.1  681.92  5870.4  686.09  5886.4  687.20  5907.6  687.40
#Mann=8,-1,0
  3808.9     0.1       0  3996.9    0.16       0  4604.8    0.03       0
  4613.3    0.16       0  4688.5     0.1       0  4784.2    0.12       0
  4869.2    0.05       0  5403.8     0.1       0
Bank Sta=4604.8,4613.3
Exp/Cntr=0.3,0.1

Type RM Length L Ch R = 1,21881,137,137,137
BEGIN DESCRIPTION:
BURNT BOOT CREEK 29.0
END DESCRIPTION:
XS GIS Cut Line= 3
      1995505.63     13610863.38      1994855.30     13610646.17
      1993401.32     13610706.93
#Sta/Elev= 30
  4139.7  688.65  4184.3  687.15  4248.1  685.03  4330.1  684.28  4342.9  683.27
  4382.9  683.85  4425.0  683.42  4437.7  682.56  4488.3  682.08  4545.4  680.03
  4658.8  677.65  4750.7  677.42  4804.6  678.13  4861.4  676.80  4862.2  676.00
  4869.2  676.00  4870.0  676.80  5306.1  677.95  5366.1  679.06  5456.2  678.17
  5641.4  679.66  5716.4  681.08  5746.4  680.85  5766.5  681.83  5826.5  681.60
  5906.6  683.17  5996.7  683.54  6056.7  685.17  6186.8  686.05  6280.6  685.65
#Mann=7,-1,0
  4139.7     0.1       0  4184.3    0.16       0  4545.4     0.1       0
  4750.7    0.05       0  4861.4    0.03       0  4870.0    0.05       0
  5641.4     0.1       0
Bank Sta=4861.4,4870
Exp/Cntr=0.3,0.1

Type RM Length L Ch R = 1,21744,383,383,383
BEGIN DESCRIPTION:
BURNT BOOT CREEK 28.0
END DESCRIPTION:
XS GIS Cut Line= 3
      1995533.34     13610712.51      1995219.89     13610546.34
      1993349.56     13610502.95
#Sta/Elev= 30
  4136.0  686.94  4168.2  684.77  4236.0  682.08  4334.1  680.16  4375.4  680.08
  4415.2  680.00  4420.8  679.03  4473.7  677.72  4615.7  676.76  4655.7  677.61
  4682.2  676.12  4755.7  677.23  4845.8  677.32  4941.4  675.20  4942.2  674.40
  4949.3  674.40  4950.1  675.20  5095.8  677.17  5355.9  677.92  5375.9  679.33
  5385.9  678.00  5395.9  677.82  5522.5  678.91  5576.0  678.97  5696.0  681.67
  5766.0  681.87  6036.1  685.44  6116.1  686.12  6256.1  685.72  6361.6  687.04
#Mann=7,-1,0
  4136.0     0.1       0  4334.1    0.05       0  4375.4    0.08       0
  4682.2    0.05       0  4941.4    0.04       0  4950.1    0.05       0
  5522.5     0.1       0
Bank Sta=4941.4,4950.1
Exp/Cntr=0.3,0.1

Type RM Length L Ch R = 1,21361,456,456,456
BEGIN DESCRIPTION:
BURNT BOOT CREEK 27.0
END DESCRIPTION:
XS GIS Cut Line= 3
      1995571.03     13610507.54      1994843.82     13610191.53
      1993670.23     13609927.64
#Sta/Elev= 30
  4122.0  685.50  4142.9  684.96  4183.1  682.12  4201.9  681.85  4265.6  679.38
  4303.0  678.75  4324.8  679.12  4357.5  677.19  4423.0  676.04  4553.8  677.08
  4615.7  675.95  4630.1  676.59  4639.2  675.68  4651.9  676.40  4658.3  675.40
  4659.1  674.60  4666.2  674.60  4667.0  675.40  4747.6  675.77  4843.1  676.88
  4985.4  675.53  5147.1  675.95  5373.8  680.09  5415.9  680.99  5436.4  682.40
  5457.0  682.42  5494.4  683.35  5569.7  685.07  5754.2  687.17  6117.8  688.20
#Mann=7,-1,0
  4122.0    0.05       0  4201.9     0.1       0  4658.3   0.035       0
  4667.0     0.1       0  4747.6    0.05       0  5457.0     0.1       0
  5494.4    0.05       0
Bank Sta=4658.3,4667
Exp/Cntr=0.3,0.1

Type RM Length L Ch R = 1,20905,269,269,269
BEGIN DESCRIPTION:
BURNT BOOT CREEK 26.0
END DESCRIPTION:
XS GIS Cut Line= 3
      1995626.97     13610202.98      1995056.15     13609841.87
      1994369.74     13609600.07
#Sta/Elev= 30
  4275.4  681.32  4340.0  679.41  4391.7  676.67  4443.4  675.19  4449.3  675.68
  4455.2  675.12  4528.1  674.39  4572.9  674.48  4582.7  674.57  4668.0  674.58
  4746.9  675.23  4982.6  674.45  5025.4  675.13  5100.5  675.31  5107.3  674.33
  5108.1  673.53  5115.2  673.53  5116.0  674.33  5132.0  675.16  5199.2  675.87
  5261.2  677.19  5343.4  679.71  5418.6  683.03  5441.6  683.25  5514.0  685.60
  5609.4  687.21  5622.0  688.01  5647.6  688.15  5652.9  688.82  5678.6  689.02
#Mann=6,-1,0
  4275.4     0.1       0  4572.9    0.05       0  4582.7     0.1       0
  5025.4    0.05       0  5107.3    0.07       0  5116.0    0.05       0
Bank Sta=5107.3,5116
Exp/Cntr=0.3,0.1