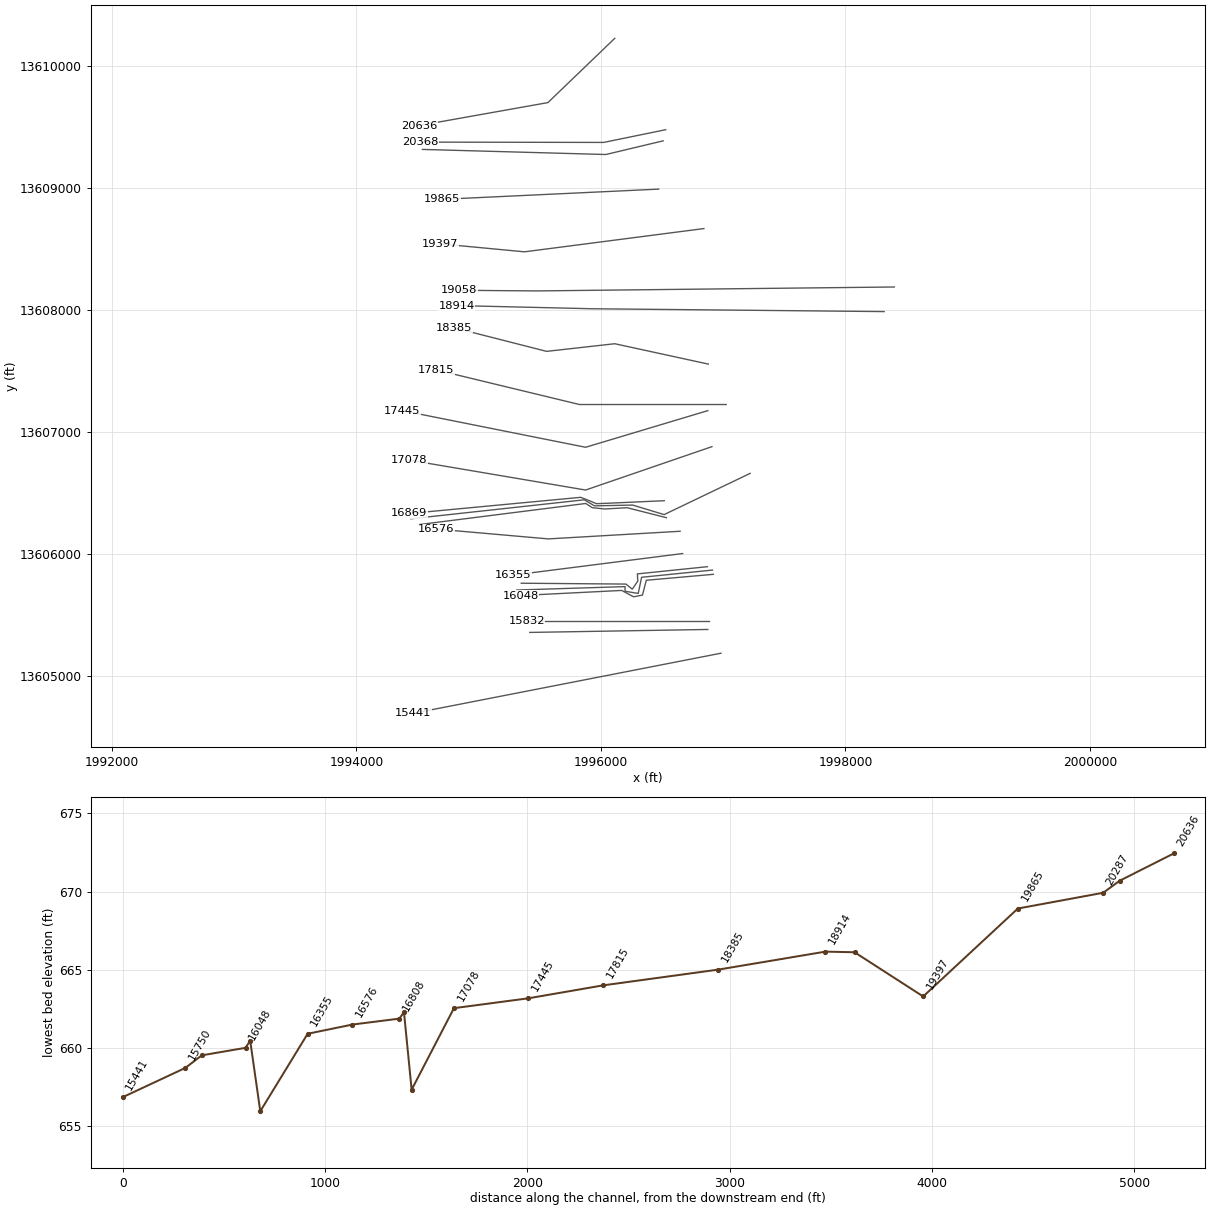
HEC-RAS study BURNT BOOT CREEK.prj: BURNT BOOT CREEK Base Level Engineering

--- BURNT BOOT CREEK.g01 (geometry) --- (continued)

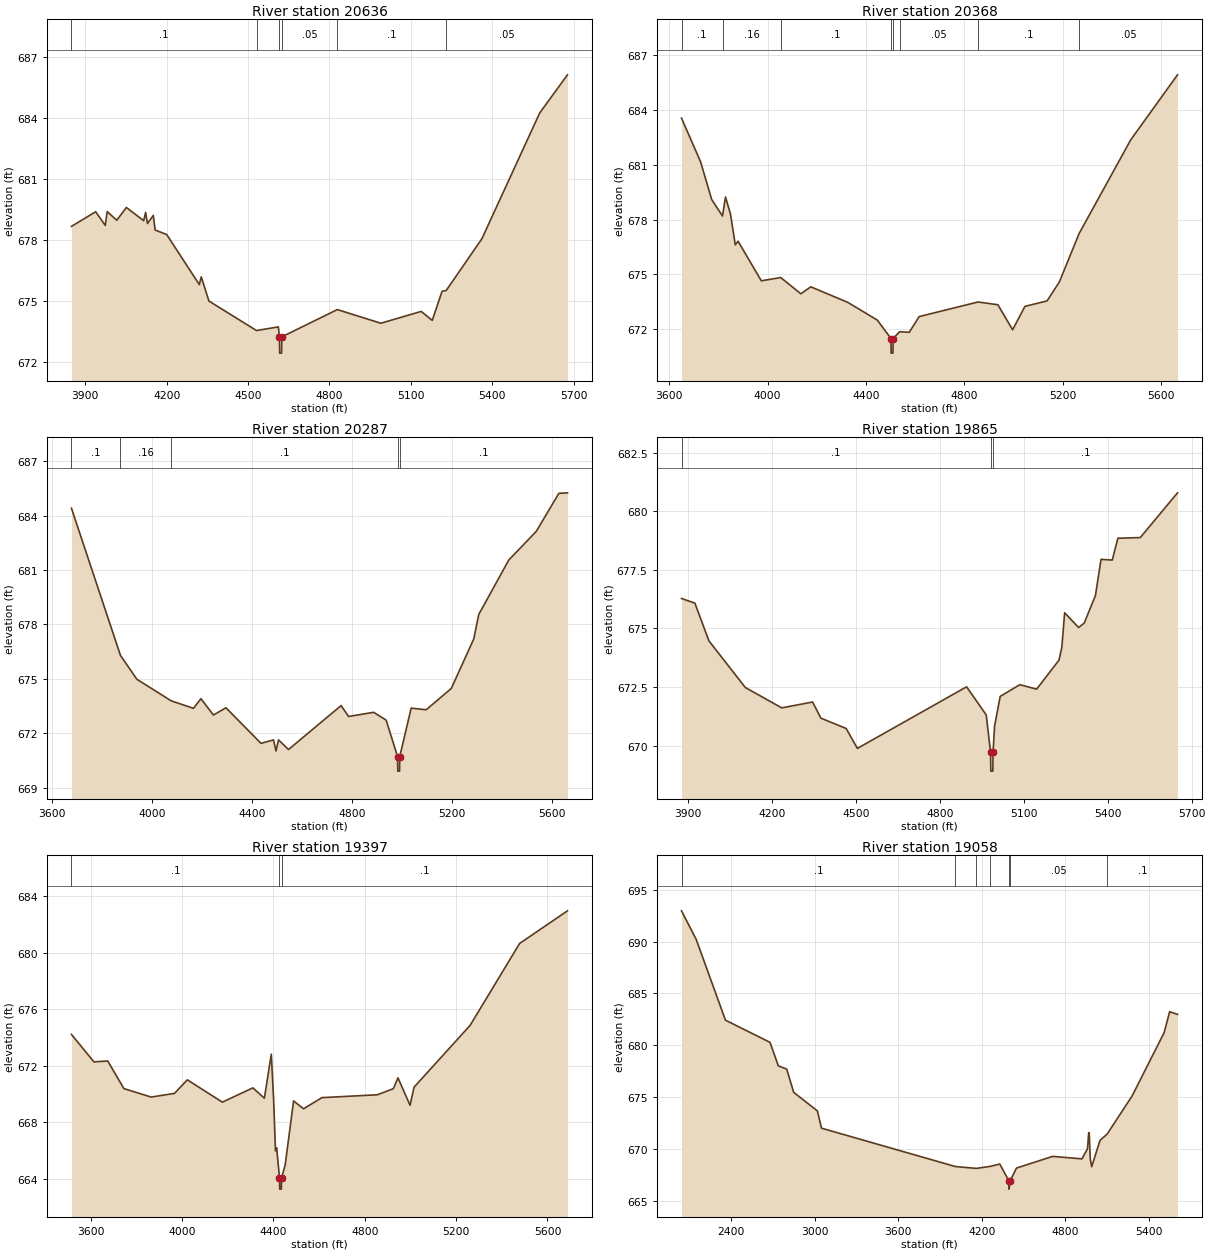
Type RM Length L Ch R = 1,20636,268,268,268
BEGIN DESCRIPTION:
Mapping XS b76165e3
END DESCRIPTION:
XS GIS Cut Line= 3
      1996113.47     13610222.64      1995566.56     13609696.56
      1994514.50     13609509.06
#Sta/Elev= 30
  3849.3  678.67  3938.5  679.39  3973.7  678.72  3981.0  679.40  4016.2  678.97
  4051.7  679.60  4115.3  678.95  4122.5  679.36  4129.4  678.81  4150.8  679.21
  4157.7  678.49  4200.2  678.27  4320.3  675.81  4327.5  676.19  4355.8  675.00
  4531.1  673.55  4611.5  673.73  4615.6  673.24  4616.4  672.44  4623.5  672.44
  4624.3  673.24  4828.9  674.58  4989.1  673.91  5137.9  674.49  5178.6  674.05
  5214.8  675.48  5230.1  675.52  5361.4  678.06  5574.7  684.25  5676.8  686.12
#Mann=6,-1,0
  3849.3     0.1       0  4531.1    0.05       0  4615.6    0.07       0
  4624.3    0.05       0  4828.9     0.1       0  5230.1    0.05       0
Bank Sta=4615.6,4624.3
Exp/Cntr=0.3,0.1

Type RM Length L Ch R = 1,20368,81,81,81
BEGIN DESCRIPTION:
BURNT BOOT CREEK 25.0
END DESCRIPTION:
XS GIS Cut Line= 3
      1996530.12     13609474.69      1996022.29     13609370.52
      1994524.90     13609373.12
#Sta/Elev= 30
  3650.1  683.56  3727.6  681.17  3772.8  679.10  3816.7  678.20  3828.9  679.24
  3849.3  678.30  3868.6  676.62  3879.9  676.82  3974.5  674.65  4053.2  674.83
  4135.1  673.94  4175.8  674.32  4325.8  673.47  4445.8  672.50  4501.4  671.49
  4502.2  670.69  4509.4  670.69  4510.1  671.49  4536.5  671.86  4575.8  671.83
  4615.8  672.69  4855.1  673.49  4935.8  673.34  4995.8  671.97  5045.8  673.25
  5135.8  673.55  5185.8  674.59  5266.1  677.24  5475.8  682.37  5665.9  685.93
#Mann=8,-1,0
  3650.1     0.1       0  3816.7    0.16       0  4053.2     0.1       0
  4501.4    0.07       0  4510.1     0.1       0  4536.5    0.05       0
  4855.1     0.1       0  5266.1    0.05       0
Bank Sta=4501.4,4510.1
Exp/Cntr=0.3,0.1

Type RM Length L Ch R = 1,20287,422,422,422
BEGIN DESCRIPTION:
BURNT BOOT CREEK 24.0
END DESCRIPTION:
XS GIS Cut Line= 3
      1996509.28     13609383.54      1996040.52     13609271.56
      1994540.55     13609313.23
#Sta/Elev= 30
  3678.0  684.40  3873.7  676.30  3939.4  674.98  4076.9  673.79  4165.5  673.38
  4195.5  673.91  4245.5  673.01  4295.5  673.41  4435.6  671.45  4485.6  671.64
  4495.6  671.03  4505.6  671.64  4545.6  671.11  4755.7  673.53  4785.7  672.93
  4885.8  673.16  4935.8  672.73  4981.4  670.72  4982.2  669.92  4989.4  669.92
  4990.1  670.72  5035.8  673.39  5095.8  673.30  5195.9  674.47  5285.9  677.20
  5305.9  678.55  5426.0  681.55  5536.0  683.13  5626.0  685.22  5660.5  685.25
#Mann=5,-1,0
  3678.0     0.1       0  3873.7    0.16       0  4076.9     0.1       0
  4981.4    0.07       0  4990.1     0.1       0
Bank Sta=4981.4,4990.1
Exp/Cntr=0.3,0.1

Type RM Length L Ch R = 1,19865,468,468,468
BEGIN DESCRIPTION:
Mapping XS b3d0ec93
END DESCRIPTION:
XS GIS Cut Line= 2
      1996472.86     13608988.23      1994702.02     13608904.90
#Sta/Elev= 30
  3876.7  676.28  3924.6  676.08  3974.7  674.47  4104.8  672.48  4235.0  671.61
  4345.1  671.86  4375.1  671.17  4465.2  670.73  4505.3  669.88  4895.7  672.51
  4965.8  671.31  4981.4  669.71  4982.2  668.91  4989.4  668.91  4990.2  669.71
  4995.8  670.84  5015.8  672.10  5085.9  672.60  5146.0  672.41  5226.0  673.65
  5236.1  674.20  5246.1  675.67  5296.1  675.04  5316.1  675.23  5356.2  676.41
  5376.2  677.95  5416.3  677.92  5436.3  678.85  5516.4  678.88  5649.5  680.79
#Mann=3,-1,0
  3876.7     0.1       0  4981.4    0.07       0  4990.2     0.1       0
Bank Sta=4981.4,4990.2
Exp/Cntr=0.3,0.1

Type RM Length L Ch R = 1,19397,339,339,339
BEGIN DESCRIPTION:
BURNT BOOT CREEK 23.0
END DESCRIPTION:
XS GIS Cut Line= 3
      1996842.59     13608665.31      1995375.00     13608475.00
      1994686.37     13608540.31
#Sta/Elev= 30
  3515.9  674.22  3614.3  672.28  3674.8  672.34  3745.4  670.39  3864.8  669.79
  3967.2  670.05  4023.2  671.01  4176.6  669.43  4310.1  670.44  4360.5  669.71
  4390.8  672.82  4400.8  669.68  4409.2  665.98  4414.3  666.20  4426.7  664.08
  4427.5  663.28  4434.7  663.28  4435.5  664.08  4451.3  664.96  4488.4  669.52
  4531.9  668.96  4612.6  669.75  4854.6  669.95  4925.2  670.38  4945.4  671.15
  4998.3  669.21  5015.9  670.49  5261.3  674.86  5477.9  680.65  5687.5  682.96
#Mann=3,-1,0
  3515.9     0.1       0  4426.7    0.07       0  4435.5     0.1       0
Bank Sta=4426.7,4435.5
Exp/Cntr=0.3,0.1

Type RM Length L Ch R = 1,19058,144,144,144
BEGIN DESCRIPTION:
BURNT BOOT CREEK 22.0
END DESCRIPTION:
XS GIS Cut Line= 3
      1998400.56     13608187.11      1995472.81     13608154.89
      1994838.66     13608160.09
#Sta/Elev= 30
  2042.6  692.96  2148.2  690.20  2358.2  682.41  2678.2  680.27  2738.2  678.00
  2798.2  677.69  2848.2  675.45  3018.2  673.66  3048.2  671.99  4009.2  668.29
  4159.5  668.11  4257.9  668.30  4328.3  668.53  4393.9  666.91  4394.7  666.11
  4402.7  666.91  4448.3  668.14  4708.3  669.27  4918.3  669.03  4958.3  670.01
  4966.9  671.55  4970.5  671.55  4978.3  668.98  4988.3  668.27  5048.3  670.82
  5098.7  671.41  5278.3  675.09  5508.4  681.20  5548.4  683.23  5604.7  682.97
#Mann=7,-1,0
  2042.6     0.1       0  4009.2    0.05       0  4159.5    0.08       0
  4257.9    0.05       0  4393.9    0.04       0  4402.7    0.05       0
  5098.7     0.1       0
Bank Sta=4393.9,4402.7
Exp/Cntr=0.3,0.1

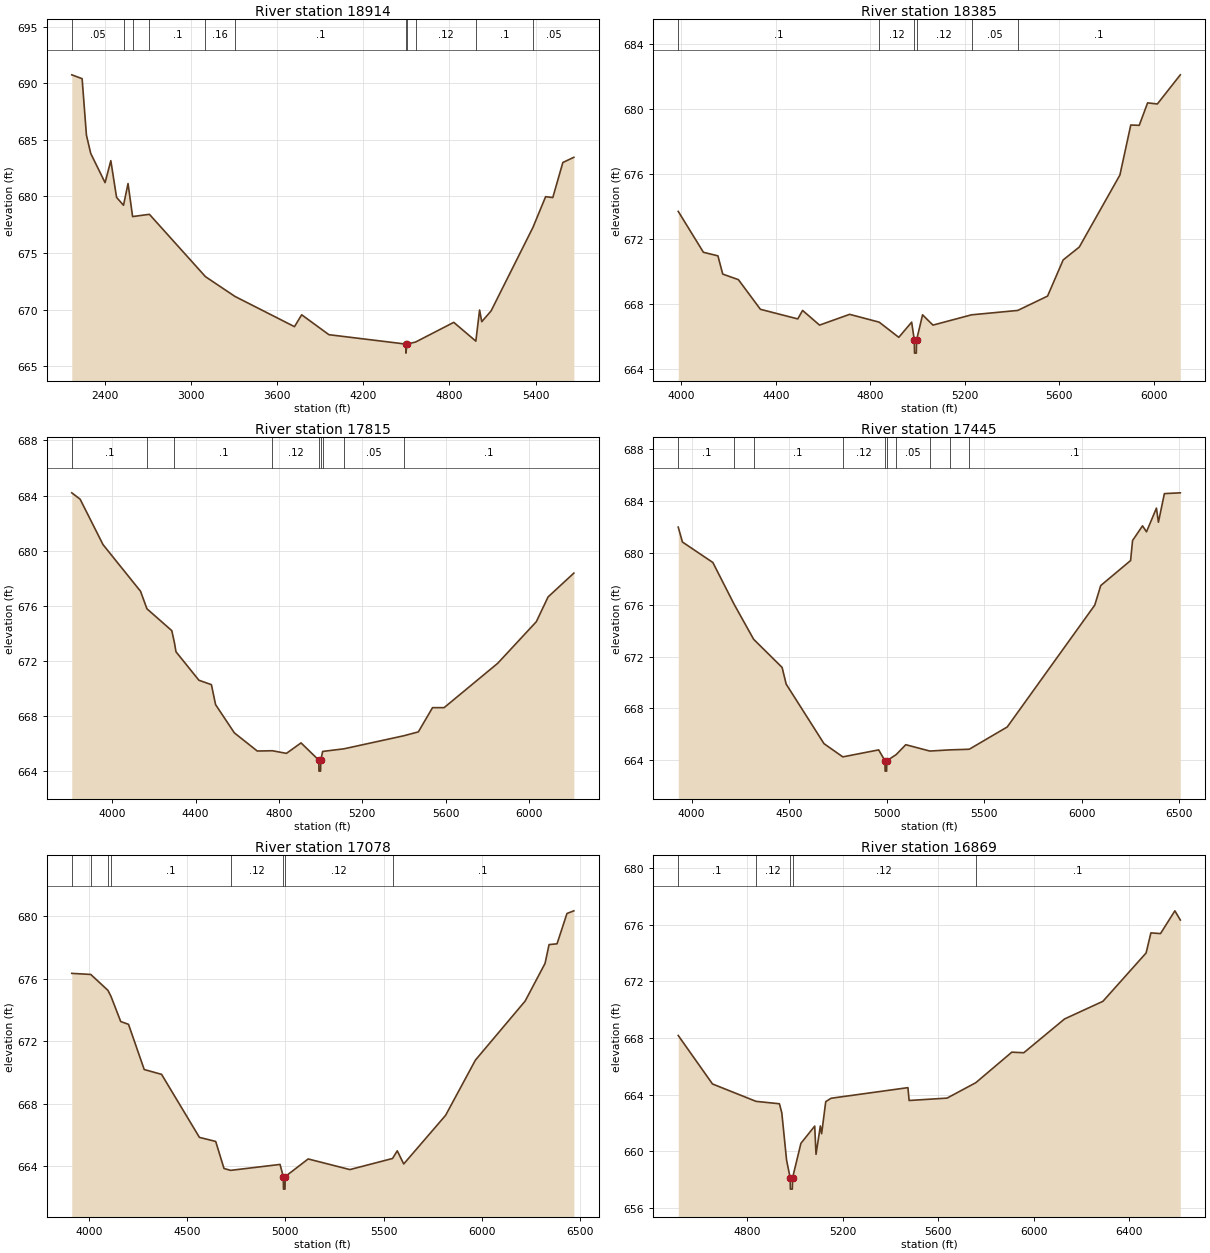
Type RM Length L Ch R = 1,18914,529,529,529
BEGIN DESCRIPTION:
BURNT BOOT CREEK 21.0
END DESCRIPTION:
XS GIS Cut Line= 3
      1998317.20     13607985.72      1995925.94     13608009.06
      1994818.32     13608035.06
#Sta/Elev= 30
  2167.4  690.75  2239.6  690.41  2269.6  685.42  2299.6  683.80  2399.6  681.22
  2439.6  683.16  2479.6  679.92  2528.0  679.22  2559.6  681.14  2591.4  678.22
  2708.6  678.42  3099.1  672.91  3305.1  671.16  3719.7  668.49  3769.7  669.54
  3959.7  667.78  4495.3  666.95  4496.1  666.15  4504.1  666.95  4563.6  667.13
  4829.8  668.87  4983.6  667.21  5009.8  669.96  5024.9  668.93  5089.9  669.88
  5381.9  677.27  5470.0  679.98  5520.0  679.90  5590.0  683.00  5666.7  683.46
#Mann=11,-1,0
  2167.4    0.05       0  2528.0    0.08       0  2591.4    0.05       0
  2708.6     0.1       0  3099.1    0.16       0  3305.1     0.1       0
  4495.3    0.07       0  4504.1     0.1       0  4563.6    0.12       0
  4983.6     0.1       0  5381.9    0.05       0
Bank Sta=4495.3,4504.1
Exp/Cntr=0.3,0.1

Type RM Length L Ch R = 1,18385,570,570,570
BEGIN DESCRIPTION:
Mapping XS 60f044b1
END DESCRIPTION:
XS GIS Cut Line= 4
      1996879.03     13607555.94      1996113.44     13607722.60
      1995556.15     13607660.10      1994800.95     13607852.81
#Sta/Elev= 30
  3987.6  673.70  4094.1  671.19  4155.5  670.97  4175.9  669.85  4242.1  669.51
  4335.2  667.69  4493.2  667.10  4513.7  667.62  4585.3  666.72  4712.6  667.38
  4837.7  666.90  4920.5  665.97  4974.9  666.90  4986.2  665.80  4987.1  665.00
  4994.7  665.00  4995.7  665.80  5021.1  667.35  5065.0  666.72  5228.1  667.35
  5423.6  667.62  5549.8  668.50  5615.8  670.72  5684.0  671.51  5855.8  675.93
  5901.8  679.00  5937.5  678.98  5973.0  680.36  6014.1  680.29  6111.3  682.08
#Mann=6,-1,0
  3987.6     0.1       0  4837.7    0.12       0  4986.2    0.07       0
  4995.7    0.12       0  5228.1    0.05       0  5423.6     0.1       0
Bank Sta=4986.2,4995.7
Exp/Cntr=0.3,0.1

Type RM Length L Ch R = 1,17815,370,370,370
BEGIN DESCRIPTION:
BURNT BOOT CREEK 20.0
END DESCRIPTION:
XS GIS Cut Line= 3
      1997024.96     13607225.00      1995825.00     13607225.00
      1994649.91     13607509.06
#Sta/Elev= 30
  3806.3  684.20  3846.3  683.74  3956.3  680.44  4136.3  677.05  4166.9  675.78
  4286.3  674.19  4299.1  673.30  4306.3  672.66  4416.3  670.59  4476.3  670.27
  4496.3  668.82  4586.3  666.77  4696.3  665.45  4768.7  665.47  4836.3  665.28
  4906.3  666.04  4991.5  664.79  4992.4  663.99  5000.1  663.99  5001.0  664.79
  5010.1  665.42  5112.1  665.61  5399.8  666.56  5469.2  666.84  5537.2  668.60
  5592.7  668.60  5849.9  671.82  6035.1  674.84  6091.6  676.64  6215.2  678.37
#Mann=9,-1,0
  3806.3     0.1       0  4166.9    0.05       0  4299.1     0.1       0
  4768.7    0.12       0  4991.5    0.07       0  5001.0    0.12       0
  5010.1    0.16       0  5112.1    0.05       0  5399.8     0.1       0
Bank Sta=4991.5,5001
Exp/Cntr=0.3,0.1

Type RM Length L Ch R = 1,17445,367,367,367
BEGIN DESCRIPTION:
BURNT BOOT CREEK 19.0
END DESCRIPTION:
XS GIS Cut Line= 3
      1996874.99     13607175.00      1995875.00     13606875.00
      1994375.02     13607175.00
#Sta/Elev= 30
  3931.3  682.00  3953.0  680.85  4108.8  679.27  4219.0  676.01  4317.9  673.34
  4463.7  671.17  4484.6  669.88  4678.6  665.28  4774.9  664.26  4958.8  664.80
  4990.9  663.96  4991.9  663.16  4999.6  663.16  5000.5  663.96  5048.8  664.44
  5097.7  665.20  5221.1  664.71  5322.1  664.80  5423.1  664.85  5617.8  666.57
  6066.5  675.98  6097.1  677.49  6250.1  679.42  6260.3  680.97  6311.3  682.10
  6331.7  681.64  6382.6  683.47  6392.8  682.38  6423.4  684.59  6505.0  684.65
#Mann=10,-1,0
  3931.3     0.1       0  4219.0    0.05       0  4317.9     0.1       0
  4774.9    0.12       0  4990.9    0.07       0  5000.5    0.12       0
  5048.8    0.05       0  5221.1     0.1       0  5322.1    0.16       0
  5423.1     0.1       0
Bank Sta=4990.9,5000.5
Exp/Cntr=0.3,0.1

Type RM Length L Ch R = 1,17078,209,209,209
BEGIN DESCRIPTION:
BURNT BOOT CREEK 18.0
END DESCRIPTION:
XS GIS Cut Line= 3
      1996908.54     13606880.14      1995875.00     13606525.00
      1994430.50     13606770.08
#Sta/Elev= 30
  3911.4  676.33  4008.3  676.26  4096.0  675.24  4111.2  674.86  4160.8  673.25
  4200.6  673.07  4280.5  670.18  4369.0  669.87  4561.8  665.84  4644.7  665.58
  4687.0  663.85  4720.7  663.73  4972.5  664.11  4989.1  663.33  4990.1  662.53
  4997.8  662.53  4998.7  663.33  5115.8  664.46  5328.4  663.78  5545.7  664.49
  5569.7  664.98  5602.7  664.14  5816.0  667.25  5967.8  670.78  6221.4  674.56
  6322.8  676.97  6343.1  678.17  6383.7  678.22  6434.4  680.16  6469.4  680.33
#Mann=8,-1,0
  3911.4    0.05       0  4008.3    0.08       0  4096.0    0.05       0
  4111.2     0.1       0  4720.7    0.12       0  4989.1    0.07       0
  4998.7    0.12       0  5545.7     0.1       0
Bank Sta=4989.1,4998.7
Exp/Cntr=0.3,0.1

Type RM Length L Ch R = 1,16869,38,38,38
BEGIN DESCRIPTION:
Mapping XS e2600dfe
END DESCRIPTION:
XS GIS Cut Line= 6
      1996518.34     13606437.53      1996054.84     13606416.70
      1995962.83     13606413.23      1995902.07     13606439.27
      1995834.36     13606465.31      1994432.39     13606332.94
#Sta/Elev= 30
  4510.7  668.18  4654.2  664.75  4836.5  663.52  4934.5  663.35  4944.5  662.71
  4964.5  659.36  4979.5  658.11  4980.4  657.31  4988.6  657.31  4989.6  658.11
  5024.5  660.55  5082.3  661.77  5087.8  659.77  5105.9  661.78  5111.3  661.23
  5128.5  663.50  5151.1  663.74  5472.8  664.49  5477.8  663.58  5636.7  663.75
  5757.0  664.84  5907.9  667.00  5958.1  666.96  6128.8  669.35  6289.6  670.60
  6470.4  674.02  6490.4  675.44  6530.6  675.39  6590.9  677.00  6613.6  676.35
#Mann=5,-1,0
  4510.7     0.1       0  4836.5    0.12       0  4979.5    0.07       0
  4989.6    0.12       0  5757.0     0.1       0
Bank Sta=4979.5,4989.6
Exp/Cntr=0.3,0.1

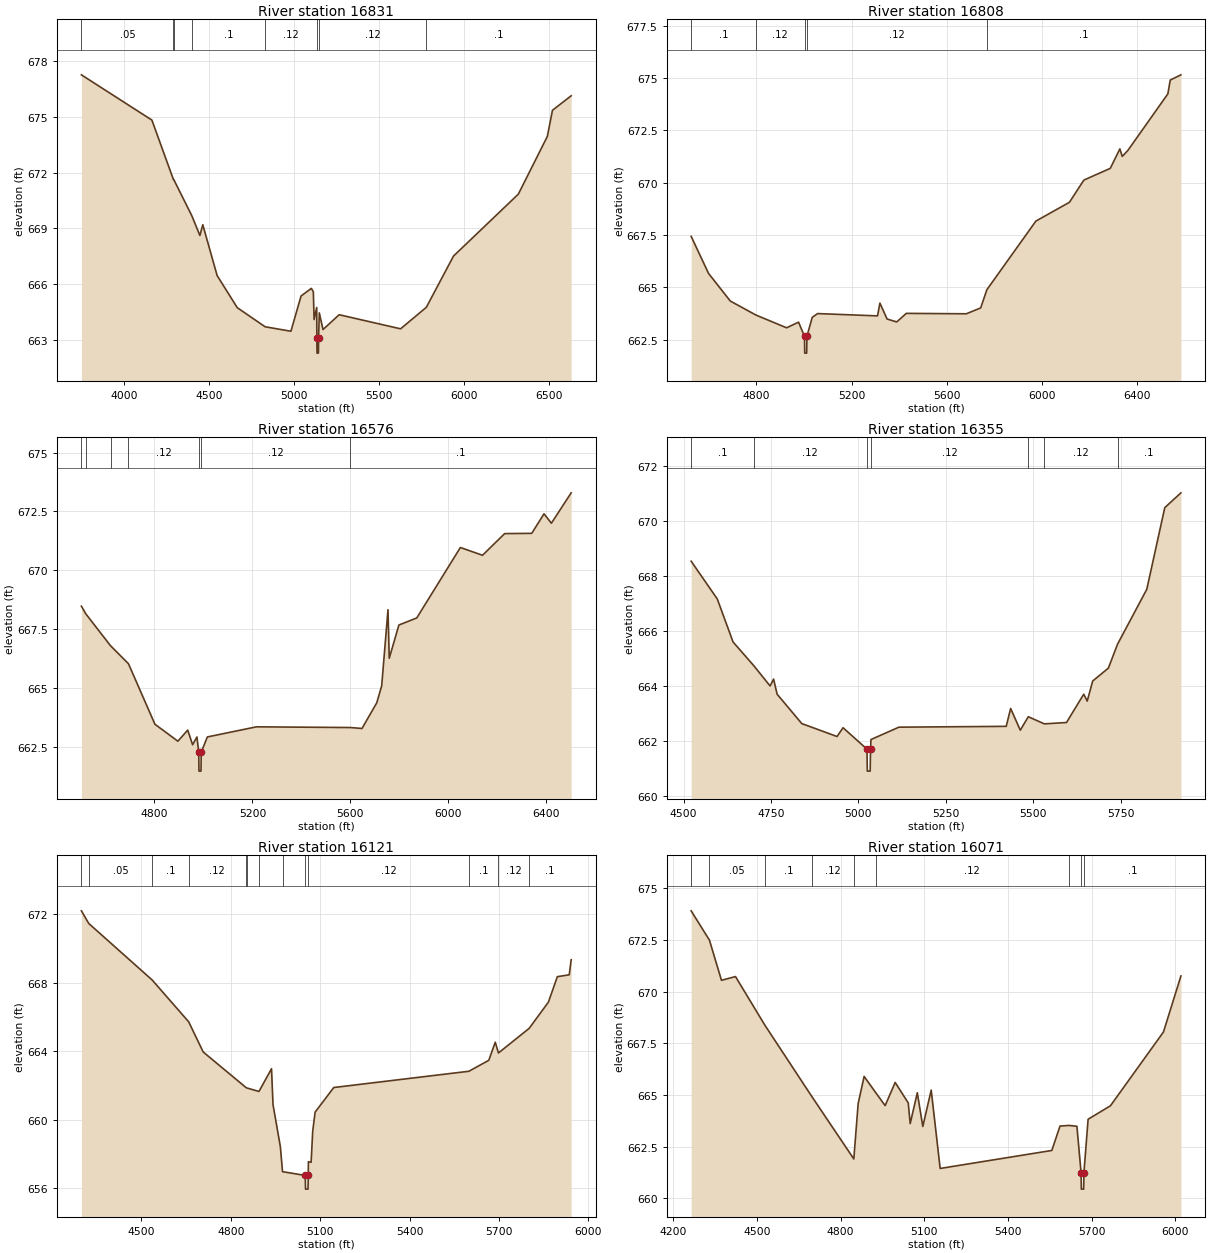
Type RM Length L Ch R = 1,16831,23,23,23
BEGIN DESCRIPTION:
BURNT BOOT CREEK 17.0
END DESCRIPTION:
XS GIS Cut Line= 6
      1997221.10     13606661.42      1996517.15     13606323.85
      1996260.14     13606401.94      1995947.64     13606395.43
      1995864.31     13606444.91      1994445.42     13606289.54
#Sta/Elev= 30
  3746.2  677.27  4161.8  674.83  4288.9  671.62  4290.9  671.62  4396.4  669.69
  4444.7  668.61  4461.8  669.19  4546.4  666.45  4665.0  664.72  4829.3  663.69
  4981.3  663.45  5041.2  665.35  5101.7  665.76  5113.5  665.58  5118.0  664.08
  5133.4  664.73  5134.2  663.07  5135.2  662.27  5143.4  662.27  5144.3  663.07
  5148.6  664.44  5170.5  663.54  5265.7  664.34  5627.8  663.58  5779.7  664.74
  5939.7  667.50  6322.0  670.84  6493.0  673.95  6523.2  675.36  6633.4  676.14
#Mann=8,-1,0
  3746.2    0.05       0  4288.9    0.08       0  4290.9    0.05       0
  4396.4     0.1       0  4829.3    0.12       0  5134.2    0.07       0
  5144.3    0.12       0  5779.7     0.1       0
Bank Sta=5134.2,5144.3
Exp/Cntr=0.3,0.1

Type RM Length L Ch R = 1,16808,232,232,232
BEGIN DESCRIPTION:
Mapping XS 46088c38
END DESCRIPTION:
XS GIS Cut Line= 6
      1996535.73     13606298.65      1996214.57     13606380.24
      1996032.27     13606369.83      1995929.84     13606380.24
      1995876.02     13606414.96      1994510.53     13606241.80
#Sta/Elev= 30
  4526.2  667.44  4599.2  665.67  4690.5  664.35  4798.3  663.68  4927.2  663.07
  4977.3  663.34  5002.3  662.66  5003.3  661.86  5011.5  661.86  5012.4  662.66
  5034.8  663.57  5057.5  663.75  5309.0  663.64  5319.1  664.25  5349.3  663.49
  5389.6  663.35  5430.0  663.76  5682.0  663.74  5742.4  664.02  5768.4  664.89
  5974.3  668.17  6115.4  669.07  6175.9  670.13  6286.8  670.69  6327.1  671.62
  6337.2  671.26  6360.9  671.55  6528.7  674.25  6538.8  674.91  6583.6  675.16
#Mann=5,-1,0
  4526.2     0.1       0  4798.3    0.12       0  5002.3    0.07       0
  5012.4    0.12       0  5768.4     0.1       0
Bank Sta=5002.3,5012.4
Exp/Cntr=0.3,0.1

Type RM Length L Ch R = 1,16576,221,221,221
BEGIN DESCRIPTION:
Mapping XS 1680908d
END DESCRIPTION:
XS GIS Cut Line= 3
      1996648.18     13606187.45      1995570.03     13606124.95
      1994654.62     13606205.34
#Sta/Elev= 30
  4502.2  668.48  4520.5  668.15  4621.2  666.80  4694.2  666.04  4802.3  663.47
  4896.0  662.75  4936.1  663.22  4956.1  662.60  4973.8  662.93  4981.1  662.28
  4982.1  661.48  4990.3  661.48  4991.2  662.28  5016.2  662.93  5216.6  663.36
  5599.5  663.33  5647.4  663.29  5707.7  664.38  5727.8  665.10  5753.5  668.33
  5758.6  666.27  5798.0  667.68  5870.9  667.98  6049.0  670.97  6139.3  670.64
  6229.7  671.56  6340.1  671.57  6390.3  672.40  6420.4  672.00  6501.1  673.29
#Mann=7,-1,0
  4502.2     0.1       0  4520.5    0.05       0  4621.2     0.1       0
  4694.2    0.12       0  4981.1    0.07       0  4991.2    0.12       0
  5599.5     0.1       0
Bank Sta=4981.1,4991.2
Exp/Cntr=0.3,0.1

Type RM Length L Ch R = 1,16355,234,234,234
BEGIN DESCRIPTION:
Mapping XS 9bbadc31
END DESCRIPTION:
XS GIS Cut Line= 2
      1996668.96     13606005.15      1995279.18     13605828.18
#Sta/Elev= 30
  4521.8  668.53  4596.4  667.16  4641.7  665.59  4700.8  664.73  4747.6  663.99
  4757.6  664.24  4767.7  663.69  4838.3  662.62  4939.1  662.15  4956.3  662.47
  5024.7  661.69  5025.7  660.89  5033.9  660.89  5034.9  661.69  5036.2  662.04
  5116.1  662.49  5423.0  662.52  5435.7  663.17  5463.3  662.38  5486.2  662.87
  5532.1  662.61  5595.5  662.66  5644.8  663.69  5654.8  663.44  5670.4  664.17
  5715.3  664.64  5741.5  665.51  5825.2  667.51  5876.6  670.48  5922.8  671.02
#Mann=7,-1,0
  4521.8     0.1       0  4700.8    0.12       0  5024.7    0.07       0
  5034.9    0.12       0  5486.2     0.1       0  5532.1    0.12       0
  5741.5     0.1       0
Bank Sta=5024.7,5034.9
Exp/Cntr=0.3,0.1

Type RM Length L Ch R = 1,16121,50,50,50
BEGIN DESCRIPTION:
Mapping XS 26097362
END DESCRIPTION:
XS GIS Cut Line= 6
      1996871.38     13605897.51      1996298.51     13605838.49
      1996301.98     13605779.46      1996256.84     13605713.49
      1996204.76     13605755.16      1995348.58     13605762.09
#Sta/Elev= 30
  4298.9  672.20  4323.6  671.46  4536.1  668.16  4658.9  665.71  4707.4  663.95
  4849.6  661.89  4852.9  661.85  4894.6  661.64  4936.7  662.97  4941.8  660.86
  4966.4  658.41  4973.6  656.95  5049.8  656.73  5050.8  655.93  5059.1  655.93
  5060.0  656.73  5060.4  657.53  5069.5  657.50  5074.9  659.32  5082.9  660.43
  5145.5  661.87  5598.7  662.82  5665.5  663.46  5687.3  664.52  5698.0  663.89
  5801.1  665.33  5865.5  666.86  5895.5  668.35  5935.5  668.46  5941.9  669.34
#Mann=13,-1,0
  4298.9    0.08       0  4323.6    0.05       0  4536.1     0.1       0
  4658.9    0.12       0  4849.6     0.1       0  4852.9    0.12       0
  4894.6     0.1       0  4973.6    0.12       0  5049.8    0.07       0
  5060.0    0.12       0  5598.7     0.1       0  5698.0    0.12       0
  5801.1     0.1       0
Bank Sta=5049.8,5060
Exp/Cntr=0.3,0.1

Type RM Length L Ch R = 1,16071,23,23,23
BEGIN DESCRIPTION:
Mapping XS 7f074103
END DESCRIPTION:
XS GIS Cut Line= 6
      1996913.06     13605869.74      1996333.23     13605810.71
      1996305.45     13605678.77      1996197.81     13605696.13
      1996197.81     13605734.32      1995312.42     13605706.55
#Sta/Elev= 30
  4264.6  673.91  4330.2  672.49  4373.2  670.55  4423.5  670.73  4528.8  668.38
  4696.6  664.94  4847.6  661.91  4863.2  664.59  4884.6  665.90  4925.4  665.13
  4959.9  664.49  4995.9  665.61  5042.7  664.62  5049.7  663.62  5075.2  665.11
  5094.9  663.48  5125.0  665.24  5157.1  661.45  5557.3  662.32  5586.7  663.50
  5618.9  663.53  5647.3  663.49  5662.2  661.25  5663.2  660.45  5671.5  660.45
  5672.4  661.25  5687.4  663.83  5767.4  664.48  5957.5  668.05  6020.1  670.76
#Mann=9,-1,0
  4264.6    0.08       0  4330.2    0.05       0  4528.8     0.1       0
  4696.6    0.12       0  4847.6     0.1       0  4925.4    0.12       0
  5618.9     0.1       0  5662.2    0.07       0  5672.4     0.1       0
Bank Sta=5662.2,5672.4
Exp/Cntr=0.3,0.1

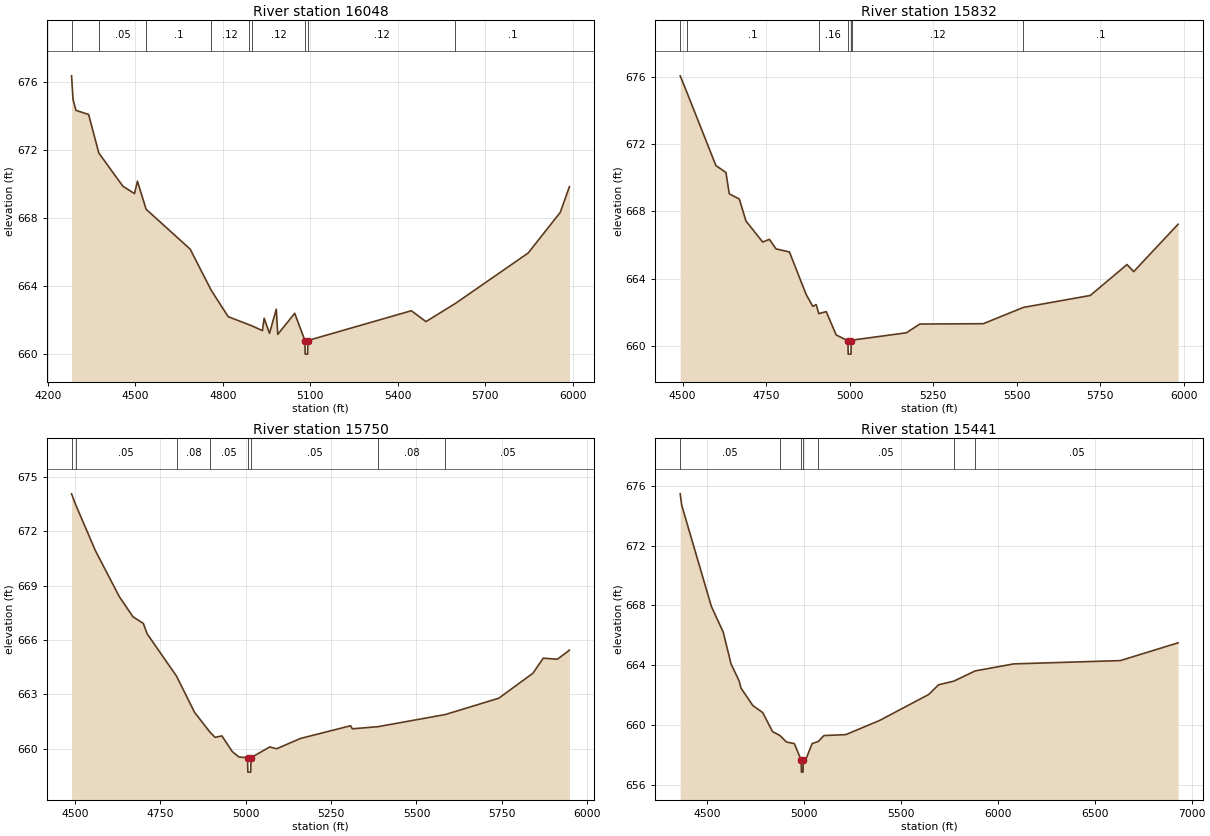
Type RM Length L Ch R = 1,16048,216,216,216
BEGIN DESCRIPTION:
Mapping XS 53ec4dfe
END DESCRIPTION:
XS GIS Cut Line= 6
      1996919.99     13605835.01      1996371.42     13605786.41
      1996340.17     13605664.88      1996267.26     13605650.99
      1996170.03     13605703.07      1995343.66     13605661.41
#Sta/Elev= 30
  4281.1  676.34  4286.1  674.96  4296.2  674.31  4339.6  674.07  4374.5  671.81
  4456.8  669.86  4496.9  669.42  4507.0  670.15  4536.8  668.50  4687.7  666.16
  4760.0  663.74  4818.2  662.19  4890.7  661.71  4899.9  661.65  4935.5  661.37
  4941.4  662.10  4959.7  661.21  4983.0  662.63  4988.1  661.15  5046.2  662.39
  5081.1  660.79  5082.1  659.99  5090.4  659.99  5091.3  660.79  5446.1  662.54
  5496.1  661.90  5597.3  662.97  5846.6  665.93  5956.7  668.32  5988.1  669.83
#Mann=9,-1,0
  4281.1     0.1       0  4374.5    0.05       0  4536.8     0.1       0
  4760.0    0.12       0  4890.7     0.1       0  4899.9    0.12       0
  5081.1    0.07       0  5091.3    0.12       0  5597.3     0.1       0
Bank Sta=5081.1,5091.3
Exp/Cntr=0.3,0.1

Type RM Length L Ch R = 1,15832,82,82,82
BEGIN DESCRIPTION:
Mapping XS 46213be2
END DESCRIPTION:
XS GIS Cut Line= 2
      1996881.81     13605456.54      1995392.21     13605456.54
#Sta/Elev= 30
  4493.0  676.07  4514.2  675.03  4599.8  670.73  4629.8  670.32  4639.8  669.05
  4669.8  668.74  4689.8  667.43  4739.8  666.18  4759.8  666.34  4779.8  665.77
  4819.8  665.59  4869.8  663.06  4889.8  662.35  4899.8  662.46  4907.8  661.92
  4929.8  662.04  4959.8  660.65  4994.7  660.31  4995.6  659.51  5004.0  659.51
  5004.9  660.31  5006.1  660.34  5169.8  660.78  5209.8  661.30  5399.8  661.32
  5519.8  662.29  5719.8  663.00  5829.8  664.84  5849.8  664.42  5982.6  667.24
#Mann=7,-1,0
  4493.0    0.08       0  4514.2     0.1       0  4907.8    0.16       0
  4994.7    0.07       0  5004.9    0.16       0  5006.1    0.12       0
  5519.8     0.1       0
Bank Sta=4994.7,5004.9
Exp/Cntr=0.3,0.1

Type RM Length L Ch R = 1,15750,309,309,309
BEGIN DESCRIPTION:
Mapping XS 469bec65
END DESCRIPTION:
XS GIS Cut Line= 2
      1996874.89     13605383.63      1995418.30     13605359.35
#Sta/Elev= 30
  4490.8  674.06  4502.8  673.46  4560.7  670.92  4630.7  668.38  4670.7  667.27
  4700.7  666.91  4712.1  666.33  4797.9  664.00  4850.7  662.00  4896.2  660.90
  4910.8  660.62  4930.8  660.70  4960.8  659.84  4980.8  659.53  5005.7  659.50
  5006.6  658.70  5015.0  658.70  5015.9  659.50  5070.8  660.09  5090.8  659.99
  5160.8  660.56  5307.2  661.26  5312.2  661.09  5387.9  661.21  5584.6  661.88
  5740.9  662.78  5840.9  664.16  5870.9  664.99  5912.3  664.93  5947.6  665.43
#Mann=8,-1,0
  4490.8    0.08       0  4502.8    0.05       0  4797.9    0.08       0
  4896.2    0.05       0  5005.7    0.04       0  5015.9    0.05       0
  5387.9    0.08       0  5584.6    0.05       0
Bank Sta=5005.7,5015.9
Exp/Cntr=0.3,0.1

Type RM Length L Ch R = 1,15441,343,343,343
BEGIN DESCRIPTION:
Mapping XS 518b05b7
END DESCRIPTION:
XS GIS Cut Line= 2
      1996982.56     13605189.19      1994462.75     13604696.65
#Sta/Elev= 30
  4362.7  675.47  4370.4  674.71  4523.2  667.94  4584.4  666.21  4625.1  664.07
  4665.9  662.96  4676.2  662.46  4737.2  661.29  4788.2  660.82  4839.1  659.54
  4876.3  659.29  4910.4  658.85  4951.2  658.74  4986.8  657.63  4987.8  656.83
  4996.2  656.83  4997.1  657.63  5012.3  657.74  5042.9  658.74  5075.6  658.89
  5104.0  659.28  5216.1  659.34  5389.3  660.28  5644.1  662.03  5695.0  662.68
  5773.0  662.92  5884.0  663.61  6083.0  664.08  6632.4  664.30  6930.2  665.49
#Mann=7,-1,0
  4362.7    0.05       0  4876.3     0.1       0  4986.8    0.07       0
  4997.1     0.1       0  5075.6    0.05       0  5773.0     0.1       0
  5884.0    0.05       0
Bank Sta=4986.8,4997.1
Exp/Cntr=0.3,0.1