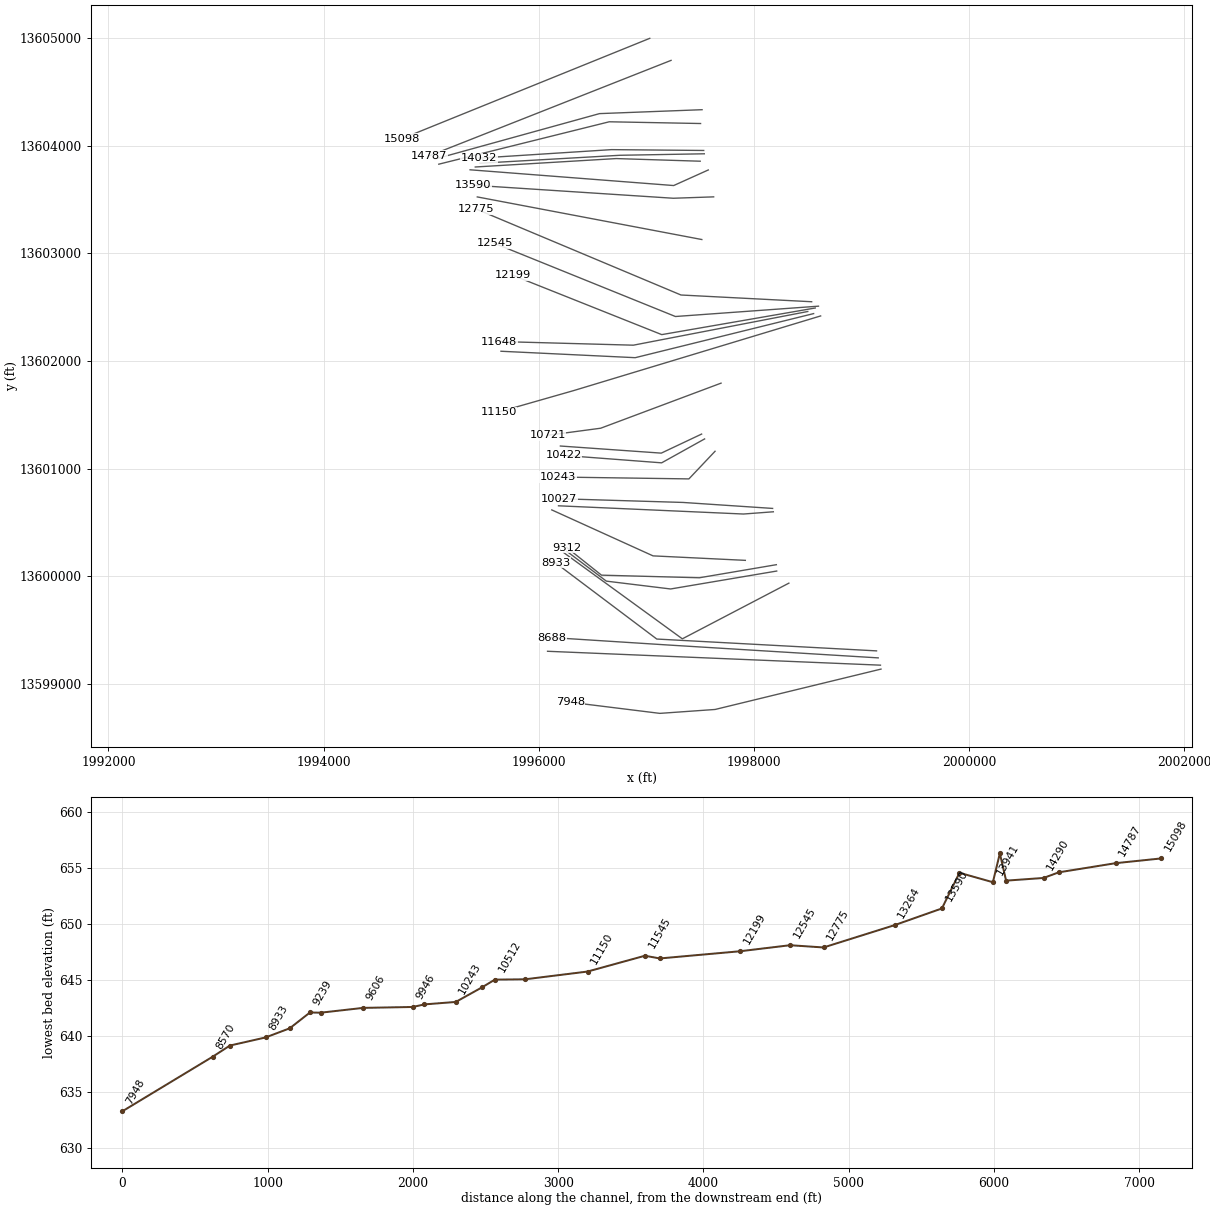
HEC-RAS study BURNT BOOT CREEK.prj: BURNT BOOT CREEK Base Level Engineering

--- BURNT BOOT CREEK.g01 (geometry) --- (continued)

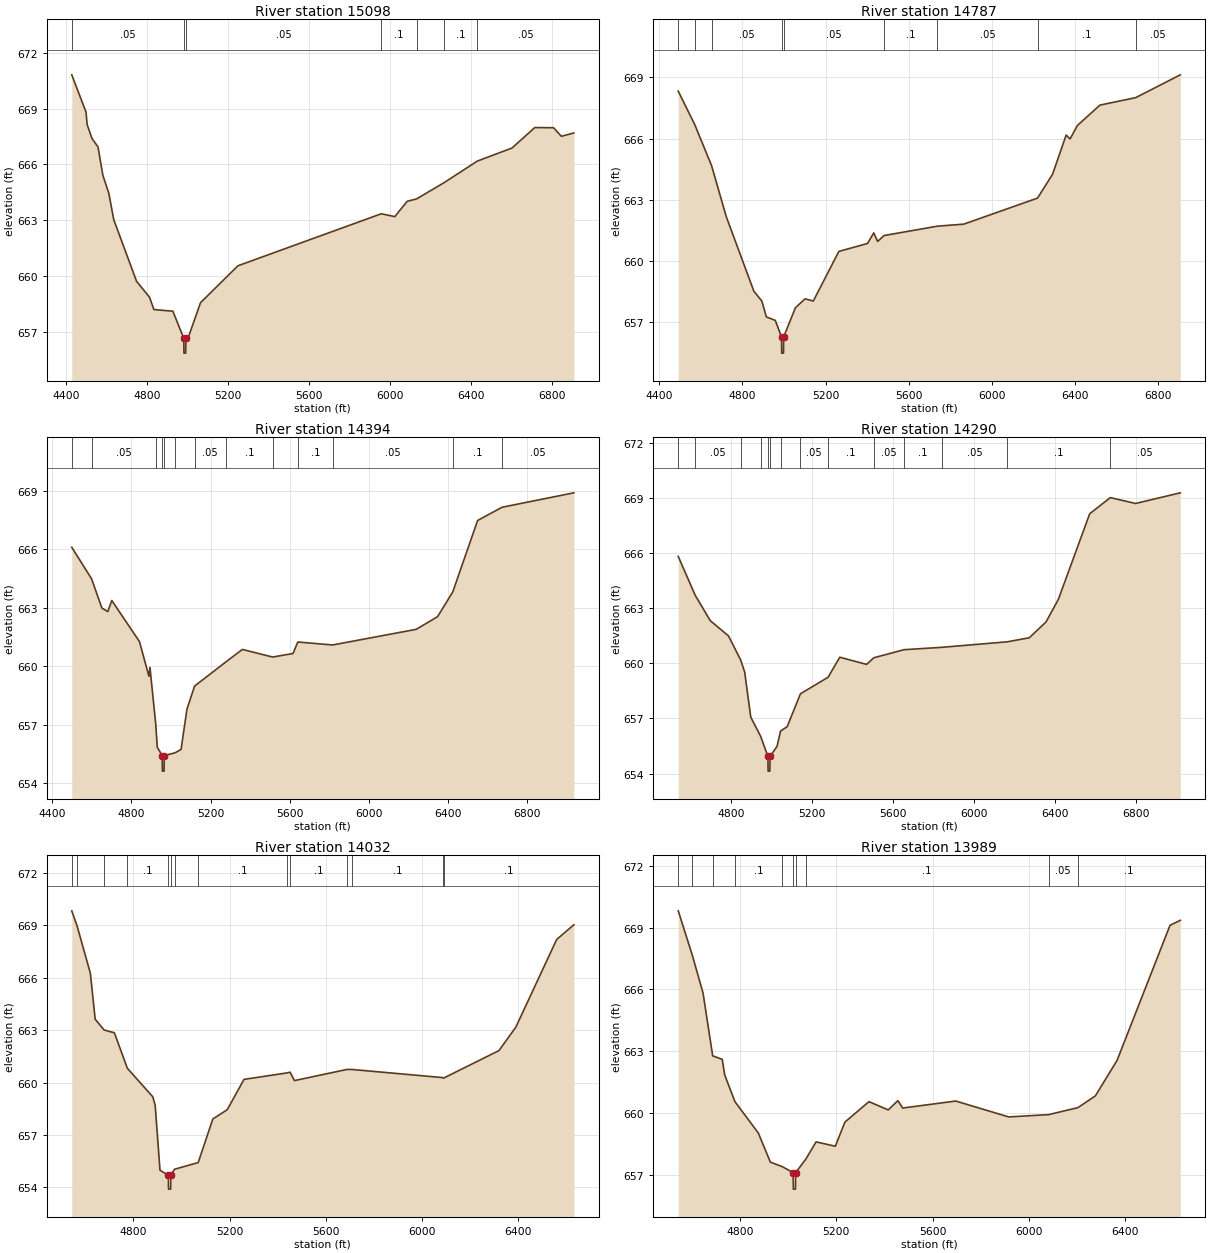
Type RM Length L Ch R = 1,15098,311,311,311
BEGIN DESCRIPTION:
Mapping XS ccf7ec63
END DESCRIPTION:
XS GIS Cut Line= 2
      1997031.12     13604998.20      1994731.91     13604067.33
#Sta/Elev= 30
  4427.8  670.81  4498.3  668.81  4503.7  668.14  4527.9  667.39  4557.4  666.94
  4581.5  665.41  4611.0  664.45  4635.1  663.04  4747.7  659.73  4812.0  658.87
  4833.6  658.21  4927.3  658.12  4981.1  656.67  4982.0  655.87  4990.6  655.87
  4991.5  656.67  5005.0  656.76  5064.0  658.58  5249.0  660.56  5956.7  663.35
  6023.8  663.20  6085.0  664.02  6131.8  664.15  6267.0  665.02  6431.5  666.18
  6602.8  666.88  6715.4  667.98  6807.9  667.97  6846.8  667.51  6908.3  667.69
#Mann=7,-1,0
  4427.8    0.05       0  4981.1    0.03       0  4991.5    0.05       0
  5956.7     0.1       0  6131.8    0.05       0  6267.0     0.1       0
  6431.5    0.05       0
Bank Sta=4981.1,4991.5
Exp/Cntr=0.3,0.1

Type RM Length L Ch R = 1,14787,393,393,393
BEGIN DESCRIPTION:
Mapping XS e2484853
END DESCRIPTION:
XS GIS Cut Line= 2
      1997229.05     13604793.34      1994983.65     13603906.74
#Sta/Elev= 30
  4491.1  668.33  4570.6  666.68  4651.3  664.67  4722.3  662.15  4854.9  658.49
  4893.2  658.01  4914.8  657.23  4957.7  657.06  4987.7  656.25  4988.6  655.45
  4997.2  655.45  4998.1  656.25  5054.5  657.68  5101.1  658.12  5140.5  658.01
  5263.4  660.45  5401.3  660.84  5431.1  661.36  5450.1  660.94  5480.8  661.23
  5736.6  661.69  5863.9  661.79  6218.6  663.07  6290.9  664.24  6356.3  666.17
  6375.3  665.98  6410.4  666.64  6518.6  667.64  6691.1  668.01  6905.2  669.13
#Mann=9,-1,0
  4491.1    0.05       0  4570.6    0.08       0  4651.3    0.05       0
  4987.7    0.04       0  4998.1    0.05       0  5480.8     0.1       0
  5736.6    0.05       0  6218.6     0.1       0  6691.1    0.05       0
Bank Sta=4987.7,4998.1
Exp/Cntr=0.3,0.1

Type RM Length L Ch R = 1,14394,104,104,104
BEGIN DESCRIPTION:
Mapping XS a78eb63a
END DESCRIPTION:
XS GIS Cut Line= 3
      1997517.28     13604335.02      1996563.94     13604298.60
      1995035.74     13603876.36
#Sta/Elev= 30
  4498.2  666.11  4598.4  664.49  4650.6  662.99  4680.6  662.81  4700.6  663.38
  4840.7  661.27  4888.7  659.49  4893.7  659.95  4922.8  657.06  4930.8  655.85
  4955.6  655.43  4956.5  654.63  4965.2  654.63  4966.0  655.43  5021.1  655.57
  5050.9  655.74  5080.9  657.81  5119.4  658.99  5277.7  660.23  5361.1  660.87
  5514.1  660.48  5617.1  660.66  5641.4  661.25  5818.1  661.10  6240.2  661.90
  6348.4  662.55  6425.3  663.82  6550.9  667.48  6674.5  668.16  7037.7  668.90
#Mann=13,-1,0
  4498.2    0.08       0  4598.4    0.05       0  4922.8     0.1       0
  4955.6    0.07       0  4966.0     0.1       0  5021.1    0.08       0
  5119.4    0.05       0  5277.7     0.1       0  5514.1    0.05       0
  5641.4     0.1       0  5818.1    0.05       0  6425.3     0.1       0
  6674.5    0.05       0
Bank Sta=4955.6,4966
Exp/Cntr=0.3,0.1

Type RM Length L Ch R = 1,14290,258,258,258
BEGIN DESCRIPTION:
Mapping XS 4603c291
END DESCRIPTION:
XS GIS Cut Line= 3
      1997503.32     13604206.55      1996654.62     13604222.74
      1995070.47     13603828.62
#Sta/Elev= 30
  4537.8  665.82  4621.8  663.70  4696.2  662.32  4786.2  661.49  4846.4  660.18
  4866.2  659.52  4896.2  657.07  4944.9  656.03  4981.0  654.93  4981.9  654.13
  4990.6  654.13  4991.5  654.93  5026.2  655.48  5043.4  656.31  5076.2  656.55
  5141.8  658.34  5278.3  659.24  5336.3  660.33  5468.7  659.94  5504.3  660.30
  5653.4  660.74  5840.7  660.87  6164.6  661.17  6272.7  661.39  6355.4  662.25
  6416.8  663.49  6571.3  668.14  6673.1  669.02  6798.0  668.70  7019.1  669.28
#Mann=14,-1,0
  4537.8    0.08       0  4621.8    0.05       0  4846.4    0.08       0
  4944.9     0.1       0  4981.0    0.07       0  4991.5     0.1       0
  5043.4    0.08       0  5141.8    0.05       0  5278.3     0.1       0
  5504.3    0.05       0  5653.4     0.1       0  5840.7    0.05       0
  6164.6     0.1       0  6673.1    0.05       0
Bank Sta=4981,4991.5
Exp/Cntr=0.3,0.1

Type RM Length L Ch R = 1,14032,43,43,43
BEGIN DESCRIPTION:
Mapping XS 0c81cfd9
END DESCRIPTION:
XS GIS Cut Line= 3
      1997532.46     13603956.11      1996676.26     13603963.96
      1995443.72     13603885.03
#Sta/Elev= 30
  4543.0  669.84  4565.1  668.98  4620.5  666.26  4640.5  663.63  4677.7  663.01
  4720.5  662.85  4774.4  660.82  4880.5  659.18  4890.5  658.69  4910.5  654.97
  4945.2  654.69  4946.1  653.89  4954.8  653.89  4955.7  654.69  4971.2  655.03
  5069.6  655.41  5130.5  657.91  5190.5  658.44  5260.5  660.18  5439.0  660.55
  5452.5  660.59  5470.6  660.11  5689.4  660.75  5708.4  660.75  6089.4  660.28
  6091.4  660.25  6322.4  661.83  6392.5  663.17  6562.9  668.20  6634.3  669.04
#Mann=14,-1,0
  4543.0     0.1       0  4565.1    0.08       0  4677.7    0.05       0
  4774.4     0.1       0  4945.2    0.07       0  4955.7     0.1       0
  4971.2    0.08       0  5069.6     0.1       0  5439.0    0.05       0
  5452.5     0.1       0  5689.4    0.05       0  5708.4     0.1       0
  6089.4    0.05       0  6091.4     0.1       0
Bank Sta=4945.2,4955.7
Exp/Cntr=0.3,0.1

Type RM Length L Ch R = 1,13989,48,48,48
BEGIN DESCRIPTION:
Mapping XS 9986c958
END DESCRIPTION:
XS GIS Cut Line= 3
      1997538.08     13603925.29      1996753.37     13603911.41
      1995452.41     13603837.29
#Sta/Elev= 30
  4542.5  669.81  4600.2  667.69  4645.6  665.83  4685.8  662.78  4725.6  662.61
  4735.6  661.86  4778.3  660.56  4875.6  659.04  4925.6  657.63  4975.0  657.41
  5020.4  657.12  5021.3  656.32  5030.0  656.32  5030.9  657.12  5073.4  657.78
  5115.7  658.61  5195.7  658.40  5235.7  659.57  5335.7  660.56  5415.8  660.16
  5455.9  660.61  5475.9  660.25  5696.3  660.59  5916.7  659.82  6082.4  659.93
  6204.5  660.27  6277.2  660.84  6367.4  662.56  6587.7  669.11  6630.4  669.35
#Mann=10,-1,0
  4542.5     0.1       0  4600.2    0.08       0  4685.8    0.05       0
  4778.3     0.1       0  4975.0    0.08       0  5020.4    0.07       0
  5030.9    0.08       0  5073.4     0.1       0  6082.4    0.05       0
  6204.5     0.1       0
Bank Sta=5020.4,5030.9
Exp/Cntr=0.3,0.1

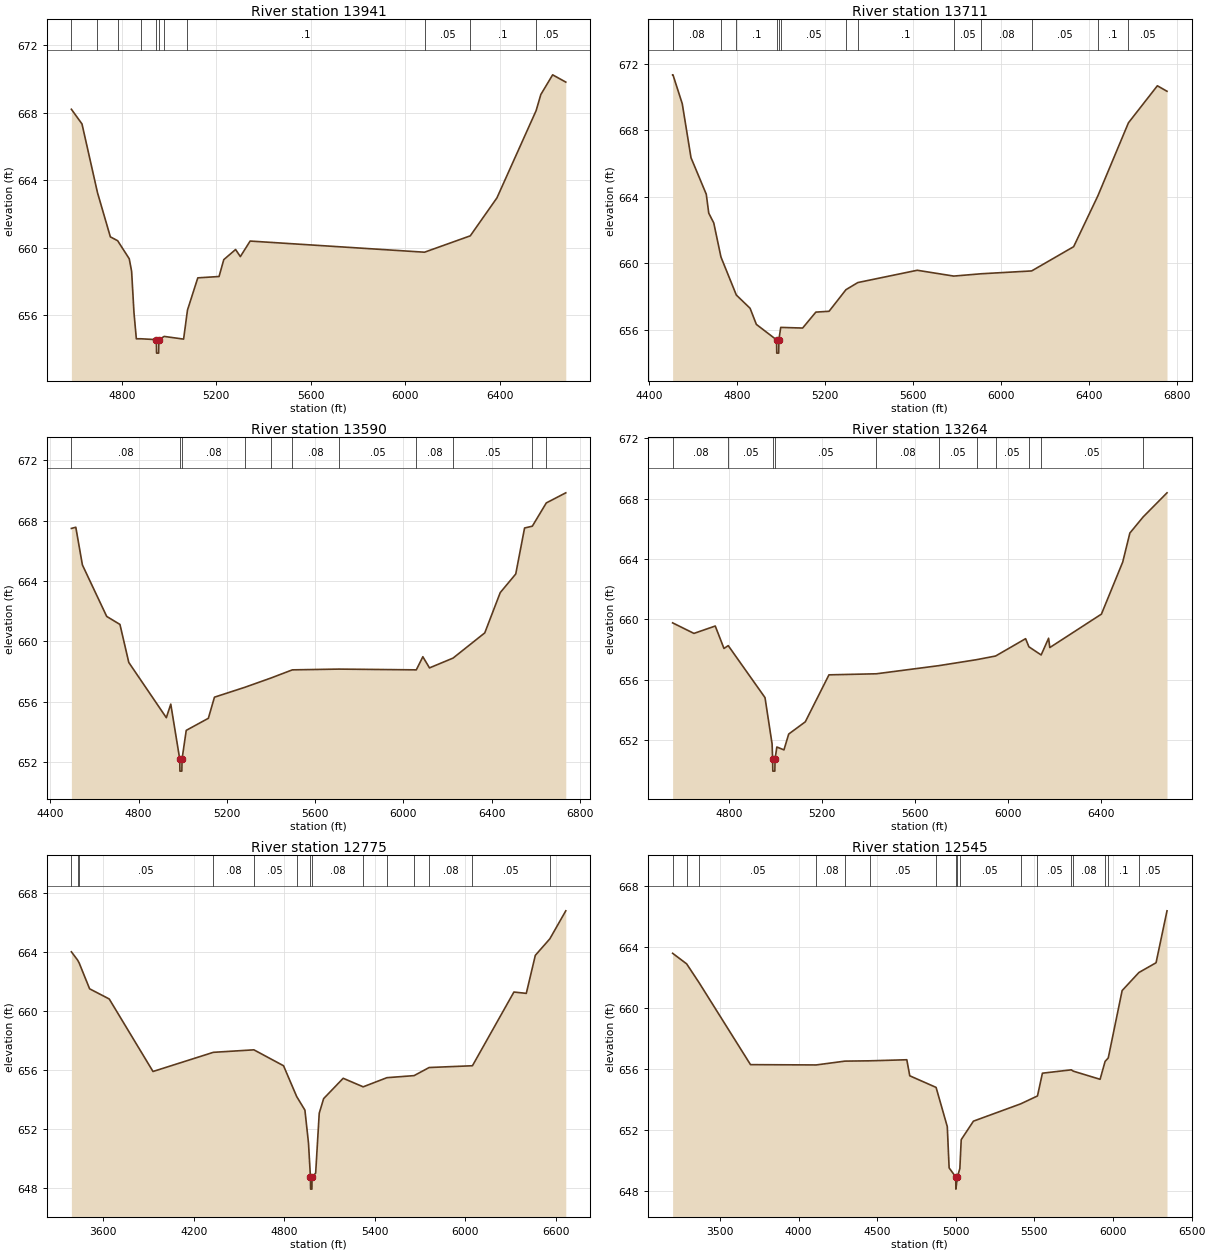
Type RM Length L Ch R = 1,13941,230,230,230
BEGIN DESCRIPTION:
Mapping XS 51b5894b
END DESCRIPTION:
XS GIS Cut Line= 3
      1997499.90     13603856.28      1996719.33     13603880.87
      1995409.53     13603802.60
#Sta/Elev= 30
  4586.2  668.20  4631.1  667.33  4696.7  663.26  4751.2  660.64  4782.1  660.41
  4831.2  659.34  4841.2  658.60  4851.2  656.15  4861.2  654.60  4880.6  654.60
  4946.0  654.55  4946.9  653.75  4955.6  653.75  4956.5  654.55  4979.2  654.74
  5061.3  654.58  5077.7  656.30  5121.4  658.21  5211.4  658.29  5231.4  659.29
  5281.4  659.89  5301.5  659.47  5343.0  660.39  6081.2  659.73  6275.0  660.70
  6387.9  662.95  6553.8  668.12  6573.6  669.07  6623.7  670.24  6679.3  669.81
#Mann=11,-1,0
  4586.2    0.08       0  4696.7    0.05       0  4782.1     0.1       0
  4880.6    0.15       0  4946.0    0.07       0  4956.5    0.15       0
  4979.2    0.08       0  5077.7     0.1       0  6081.2    0.05       0
  6275.0     0.1       0  6553.8    0.05       0
Bank Sta=4946,4956.5
Exp/Cntr=0.3,0.1

Type RM Length L Ch R = 1,13711,121,121,121
BEGIN DESCRIPTION:
BURNT BOOT CREEK 12.0
END DESCRIPTION:
XS GIS Cut Line= 3
      1997574.99     13603775.00      1997253.37     13603630.16
      1995361.25     13603776.52
#Sta/Elev= 30
  4505.8  671.35  4507.4  671.35  4549.7  669.61  4589.5  666.36  4659.0  664.16
  4670.3  663.02  4693.1  662.43  4725.8  660.38  4795.8  658.09  4858.5  657.29
  4887.0  656.32  4979.0  655.39  4979.9  654.59  4988.6  654.59  4989.5  655.39
  4998.0  656.14  5097.6  656.10  5157.8  657.06  5218.0  657.11  5294.8  658.41
  5348.9  658.84  5619.2  659.58  5785.6  659.23  5911.5  659.37  6140.2  659.54
  6331.3  661.00  6441.5  664.06  6580.7  668.46  6712.4  670.69  6756.3  670.36
#Mann=14,-1,0
  4505.8    0.05       0  4507.4    0.08       0  4725.8    0.05       0
  4795.8     0.1       0  4979.0    0.04       0  4989.5     0.1       0
  4998.0    0.05       0  5294.8    0.08       0  5348.9     0.1       0
  5785.6    0.05       0  5911.5    0.08       0  6140.2    0.05       0
  6441.5     0.1       0  6580.7    0.05       0
Bank Sta=4979,4989.5
Exp/Cntr=0.3,0.1

Type RM Length L Ch R = 1,13590,326,326,326
BEGIN DESCRIPTION:
BURNT BOOT CREEK 11.0
END DESCRIPTION:
XS GIS Cut Line= 3
      1997625.00     13603525.00      1997249.90     13603512.10
      1995388.66     13603633.20
#Sta/Elev= 30
  4495.3  667.49  4515.3  667.57  4545.3  665.07  4655.4  661.66  4715.4  661.13
  4755.5  658.61  4925.6  654.95  4945.7  655.85  4986.3  652.21  4987.2  651.41
  4995.9  651.41  4996.8  652.21  5015.8  654.11  5116.0  654.91  5143.7  656.31
  5280.5  656.96  5397.9  657.57  5496.7  658.12  5707.0  658.17  6058.4  658.12
  6088.1  658.99  6118.2  658.25  6225.0  658.90  6368.7  660.57  6438.8  663.24
  6509.0  664.47  6549.1  667.52  6584.2  667.64  6647.5  669.18  6735.8  669.85
#Mann=11,-1,0
  4495.3    0.08       0  4986.3    0.07       0  4996.8    0.08       0
  5280.5    0.05       0  5397.9     0.1       0  5496.7    0.08       0
  5707.0    0.05       0  6058.4    0.08       0  6225.0    0.05       0
  6584.2     0.1       0  6647.5    0.05       0
Bank Sta=4986.3,4996.8
Exp/Cntr=0.3,0.1

Type RM Length L Ch R = 1,13264,489,489,489
BEGIN DESCRIPTION:
Mapping XS bf37361e
END DESCRIPTION:
XS GIS Cut Line= 2
      1997514.95     13603128.50      1995428.18     13603524.44
#Sta/Elev= 30
  4558.1  659.76  4649.7  659.06  4741.3  659.55  4778.8  658.06  4797.0  658.25
  4955.0  654.80  4985.5  651.72  4987.7  650.72  4988.6  649.92  4997.3  649.92
  4998.2  650.72  5005.9  651.52  5036.4  651.33  5056.8  652.38  5128.0  653.19
  5229.8  656.31  5433.1  656.38  5702.0  656.92  5865.2  657.32  5945.7  657.56
  6074.6  658.71  6088.8  658.17  6141.4  657.63  6173.4  658.74  6178.5  658.12
  6400.3  660.34  6491.9  663.80  6522.5  665.72  6579.6  666.79  6682.1  668.39
#Mann=11,-1,0
  4558.1    0.08       0  4797.0    0.05       0  4987.7    0.04       0
  4998.2    0.05       0  5433.1    0.08       0  5702.0    0.05       0
  5865.2     0.1       0  5945.7    0.05       0  6088.8    0.08       0
  6141.4    0.05       0  6579.6     0.1       0
Bank Sta=4987.7,4998.2
Exp/Cntr=0.3,0.1

Type RM Length L Ch R = 1,12775,230,230,230
BEGIN DESCRIPTION:
Mapping XS 984e46e9
END DESCRIPTION:
XS GIS Cut Line= 3
      1998535.70     13602550.39      1997321.20     13602612.98
      1995418.79     13603411.46
#Sta/Elev= 30
  3388.1  664.03  3429.2  663.47  3439.9  663.27  3509.0  661.52  3639.1  660.83
  3929.5  655.91  4329.5  657.21  4598.7  657.38  4795.3  656.30  4882.6  654.21
  4937.1  653.29  4960.8  651.06  4973.9  648.73  4974.8  647.93  4983.5  647.93
  4984.4  648.73  5008.4  649.02  5032.1  653.08  5061.3  654.07  5191.0  655.45
  5323.6  654.87  5480.9  655.49  5661.2  655.63  5761.1  656.18  6048.3  656.30
  6323.4  661.30  6405.5  661.21  6465.4  663.79  6561.6  664.91  6667.4  666.81
#Mann=14,-1,0
  3388.1    0.05       0  3429.2    0.08       0  3439.9    0.05       0
  4329.5    0.08       0  4598.7    0.05       0  4882.6    0.08       0
  4973.9    0.04       0  4984.4    0.08       0  5323.6    0.08       0
  5480.9     0.1       0  5661.2    0.05       0  5761.1    0.08       0
  6048.3    0.05       0  6561.6     0.1       0
Bank Sta=4973.9,4984.4
Exp/Cntr=0.3,0.1

Type RM Length L Ch R = 1,12545,346,346,346
BEGIN DESCRIPTION:
Mapping XS 68b603bb
END DESCRIPTION:
XS GIS Cut Line= 3
      1998599.11     13602509.16      1997269.65     13602413.10
      1995590.41     13603092.25
#Sta/Elev= 30
  3198.9  663.57  3288.0  662.88  3367.0  661.65  3694.3  656.28  4112.0  656.26
  4294.6  656.51  4451.9  656.53  4688.4  656.60  4707.1  655.55  4874.5  654.79
  4945.8  652.22  4957.5  649.52  4999.6  648.93  5000.4  648.13  5010.1  648.93
  5025.7  649.48  5034.4  651.37  5112.1  652.58  5411.9  653.71  5519.4  654.23
  5550.8  655.72  5734.4  655.94  5748.2  655.85  5917.6  655.32  5949.4  656.49
  5969.6  656.72  6057.8  661.13  6164.3  662.31  6273.5  662.95  6343.2  666.35
#Mann=17,-1,0
  3198.9    0.05       0  3288.0    0.08       0  3367.0    0.05       0
  4112.0    0.08       0  4294.6     0.1       0  4451.9    0.05       0
  4874.5    0.08       0  4999.6    0.07       0  5010.1    0.08       0
  5025.7    0.05       0  5411.9     0.1       0  5519.4    0.05       0
  5734.4     0.1       0  5748.2    0.08       0  5949.4    0.05       0
  5969.6     0.1       0  6164.3    0.05       0
Bank Sta=4999.6,5010.1
Exp/Cntr=0.3,0.1

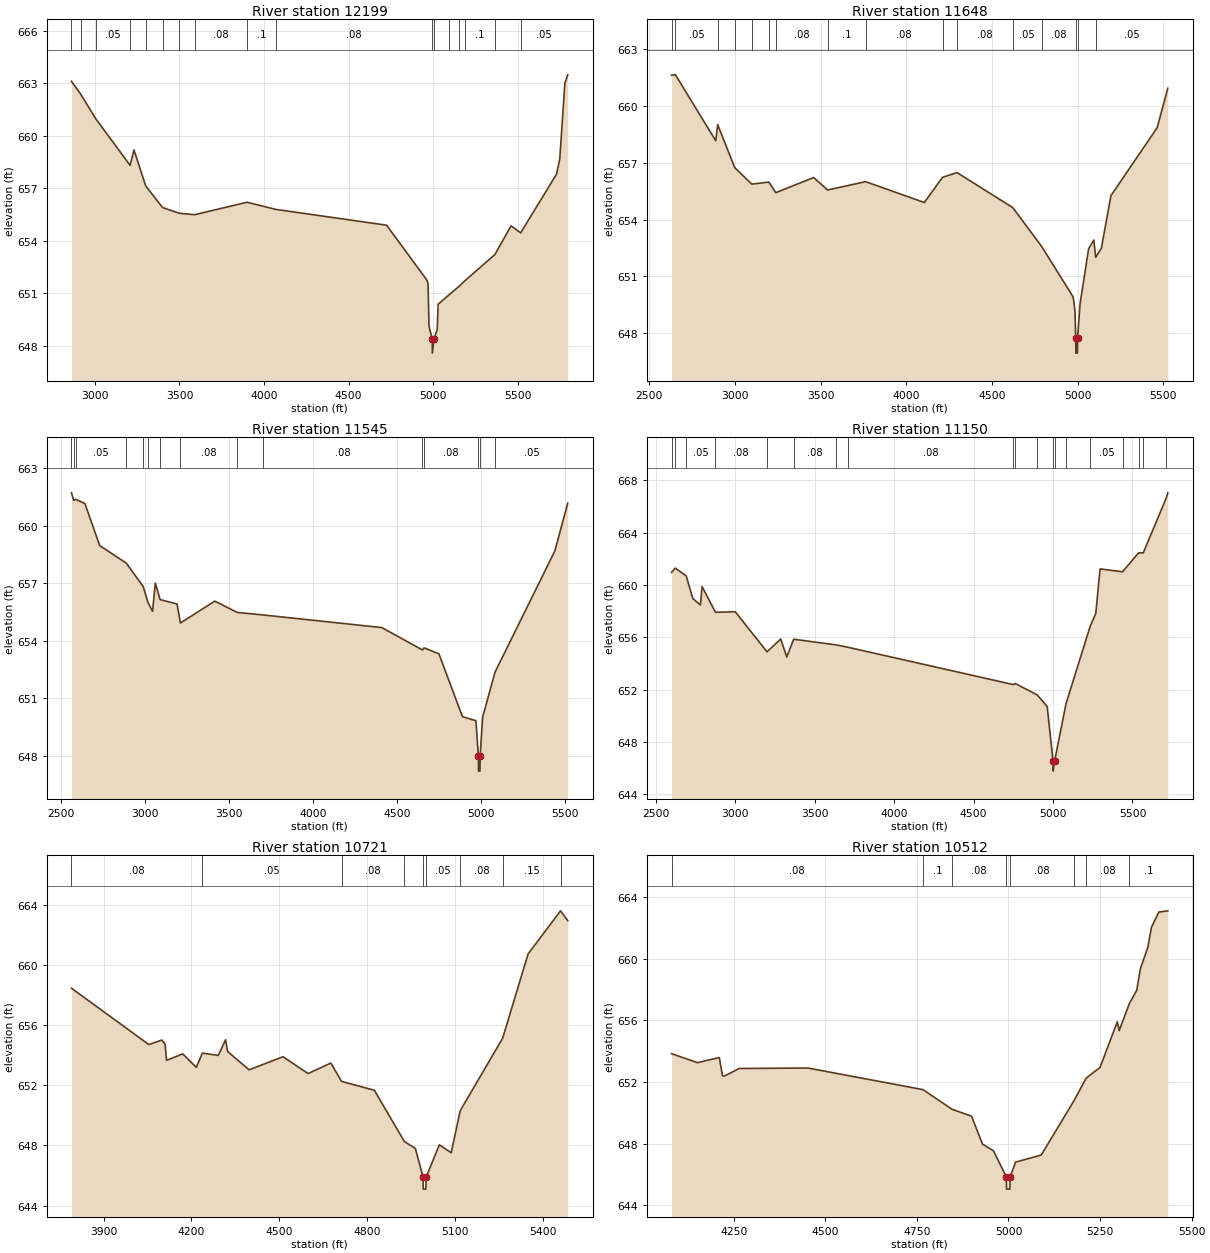
Type RM Length L Ch R = 1,12199,551,551,551
BEGIN DESCRIPTION:
Mapping XS 3852385d
END DESCRIPTION:
XS GIS Cut Line= 3
      1998569.10     13602492.23      1997142.46     13602244.79
      1995761.43     13602795.18
#Sta/Elev= 30
  2861.6  663.12  2915.0  662.40  3005.3  660.98  3208.2  658.32  3231.1  659.20
  3300.7  657.14  3400.0  655.91  3499.3  655.58  3590.0  655.50  3900.0  656.21
  4070.6  655.80  4725.0  654.90  4963.5  651.76  4970.4  651.54  4975.7  649.13
  4994.8  648.39  4995.6  647.59  5005.3  648.39  5024.3  648.94  5029.7  650.38
  5091.7  650.90  5150.5  651.38  5188.7  651.73  5365.0  653.22  5461.1  654.86
  5517.9  654.46  5730.7  657.83  5749.3  658.71  5779.2  663.01  5796.2  663.49
#Mann=17,-1,0
  2861.6    0.05       0  2915.0    0.08       0  3005.3    0.05       0
  3208.2     0.1       0  3300.7    0.05       0  3400.0    0.08       0
  3499.3    0.05       0  3590.0    0.08       0  3900.0     0.1       0
  4070.6    0.08       0  4994.8    0.07       0  5005.3    0.08       0
  5091.7    0.05       0  5150.5    0.08       0  5188.7     0.1       0
  5365.0    0.08       0  5517.9    0.05       0
Bank Sta=4994.8,5005.3
Exp/Cntr=0.3,0.1

Type RM Length L Ch R = 1,11648,103,103,103
BEGIN DESCRIPTION:
Mapping XS b338deca
END DESCRIPTION:
XS GIS Cut Line= 3
      1998499.65     13602459.68      1996878.64     13602146.65
      1995632.96     13602180.59
#Sta/Elev= 30
  2629.5  661.62  2652.3  661.64  2887.6  658.16  2898.9  659.01  2998.5  656.74
  3098.1  655.87  3197.7  655.98  3238.1  655.42  3459.2  656.22  3540.3  655.56
  3762.3  656.00  4105.2  654.90  4211.4  656.23  4295.9  656.48  4621.7  654.63
  4790.3  652.58  4974.4  649.91  4984.4  649.20  4989.1  647.75  4990.0  646.95
  4998.8  646.95  4999.7  647.75  5014.4  649.56  5064.4  652.46  5094.4  652.92
  5105.7  652.01  5138.6  652.48  5194.4  655.26  5464.5  658.85  5526.6  660.93
#Mann=16,-1,0
  2629.5    0.08       0  2652.3    0.05       0  2898.9     0.1       0
  2998.5    0.05       0  3098.1    0.08       0  3197.7    0.05       0
  3238.1    0.08       0  3540.3     0.1       0  3762.3    0.08       0
  4211.4    0.05       0  4295.9    0.08       0  4621.7    0.05       0
  4790.3    0.08       0  4989.1    0.07       0  4999.7    0.08       0
  5105.7    0.05       0
Bank Sta=4989.1,4999.7
Exp/Cntr=0.3,0.1

Type RM Length L Ch R = 1,11545,395,395,395
BEGIN DESCRIPTION:
Mapping XS e7bc17cd
END DESCRIPTION:
XS GIS Cut Line= 3
      1998553.95     13602440.15      1996896.08     13602030.51
      1995648.44     13602090.24
#Sta/Elev= 30
  2561.9  661.71  2575.1  661.32  2587.1  661.37  2642.0  661.15  2730.0  658.96
  2888.8  658.04  2989.3  656.82  3017.7  655.99  3044.9  655.53  3061.6  657.00
  3089.9  656.14  3191.1  655.91  3211.1  654.92  3415.8  656.06  3549.2  655.47
  3701.5  655.34  4410.9  654.68  4653.3  653.51  4663.3  653.62  4751.3  653.31
  4891.4  650.03  4971.5  649.82  4986.2  647.99  4987.1  647.19  4995.9  647.19
  4996.8  647.99  5011.6  650.00  5085.3  652.35  5442.0  658.68  5518.7  661.17
#Mann=15,-1,0
  2561.9    0.05       0  2575.1    0.08       0  2587.1    0.05       0
  2888.8     0.1       0  2989.3    0.05       0  3017.7    0.08       0
  3089.9     0.1       0  3211.1    0.08       0  3549.2     0.1       0
  3701.5    0.08       0  4653.3    0.05       0  4663.3    0.08       0
  4986.2    0.07       0  4996.8    0.08       0  5085.3    0.05       0
Bank Sta=4986.2,4996.8
Exp/Cntr=0.3,0.1

Type RM Length L Ch R = 1,11150,429,429,429
BEGIN DESCRIPTION:
BURNT BOOT CREEK 10.0
END DESCRIPTION:
XS GIS Cut Line= 3
      1998619.06     13602418.45      1996325.00     13601725.00
      1995624.99     13601525.00
#Sta/Elev= 30
  2597.9  660.96  2621.5  661.28  2690.1  660.69  2731.8  658.96  2779.7  658.47
  2790.2  659.87  2874.4  657.91  2999.1  657.95  3199.2  654.89  3285.1  655.87
  3323.3  654.50  3366.9  655.85  3634.6  655.42  3708.2  655.24  4749.2  652.39
  4762.0  652.47  4901.1  651.59  4963.1  650.71  4999.6  646.58  5000.4  645.78
  5010.2  646.58  5081.9  650.94  5234.5  656.87  5268.8  657.81  5296.1  661.22
  5437.3  661.00  5538.7  662.45  5567.7  662.44  5713.7  666.66  5722.5  667.03
#Mann=19,-1,0
  2597.9    0.05       0  2621.5    0.08       0  2690.1    0.05       0
  2874.4    0.08       0  3199.2     0.1       0  3366.9    0.08       0
  3634.6    0.05       0  3708.2    0.08       0  4749.2    0.05       0
  4762.0    0.08       0  4901.1    0.05       0  4999.6    0.04       0
  5010.2    0.05       0  5081.9    0.08       0  5234.5    0.05       0
  5437.3    0.08       0  5538.7    0.05       0  5567.7     0.1       0
  5713.7    0.08       0
Bank Sta=4999.6,5010.2
Exp/Cntr=0.3,0.1

Type RM Length L Ch R = 1,10721,209,209,209
BEGIN DESCRIPTION:
BURNT BOOT CREEK 9.0
END DESCRIPTION:
XS GIS Cut Line= 3
      1997693.72     13601793.89      1996575.00     13601375.00
      1996080.85     13601309.06
#Sta/Elev= 30
  3790.6  658.46  4054.6  654.71  4098.9  655.01  4109.6  654.75  4115.1  653.66
  4170.4  654.09  4216.4  653.19  4237.2  654.14  4291.5  653.99  4316.4  655.03
  4323.1  654.25  4396.6  653.03  4512.3  653.90  4597.8  652.78  4675.5  653.48
  4711.9  652.26  4824.0  651.67  4926.3  648.26  4963.8  647.80  4990.0  645.89
  4990.8  645.09  4999.7  645.09  5000.6  645.89  5045.7  648.04  5086.1  647.51
  5116.9  650.31  5261.6  655.13  5348.4  660.74  5459.2  663.61  5483.7  662.96
#Mann=9,-1,0
  3790.6    0.08       0  4237.2    0.05       0  4711.9    0.08       0
  4926.3    0.05       0  4990.0    0.04       0  5000.6    0.05       0
  5116.9    0.08       0  5261.6    0.15       0  5459.2     0.1       0
Bank Sta=4990,5000.6
Exp/Cntr=0.3,0.1

Type RM Length L Ch R = 1,10512,90,90,90
BEGIN DESCRIPTION:
Mapping XS 93d04d19
END DESCRIPTION:
XS GIS Cut Line= 3
      1997512.95     13601320.63      1997137.97     13601143.55
      1996200.48     13601209.52
#Sta/Elev= 30
  4080.4  653.84  4151.1  653.26  4210.8  653.59  4219.4  652.41  4224.9  652.39
  4264.9  652.88  4452.6  652.91  4766.6  651.51  4846.4  650.23  4899.1  649.79
  4929.1  647.98  4959.2  647.54  4994.0  645.86  4994.9  645.06  5003.8  645.06
  5004.6  645.86  5019.4  646.81  5089.5  647.27  5178.5  650.78  5212.3  652.26
  5249.9  652.95  5297.1  655.91  5302.1  655.33  5329.8  657.08  5350.2  657.96
  5360.2  659.36  5380.2  660.72  5390.3  662.03  5410.3  663.02  5434.9  663.10
#Mann=8,-1,0
  4080.4    0.08       0  4766.6     0.1       0  4846.4    0.08       0
  4994.0    0.07       0  5004.6    0.08       0  5178.5    0.05       0
  5212.3    0.08       0  5329.8     0.1       0
Bank Sta=4994,5004.6
Exp/Cntr=0.3,0.1

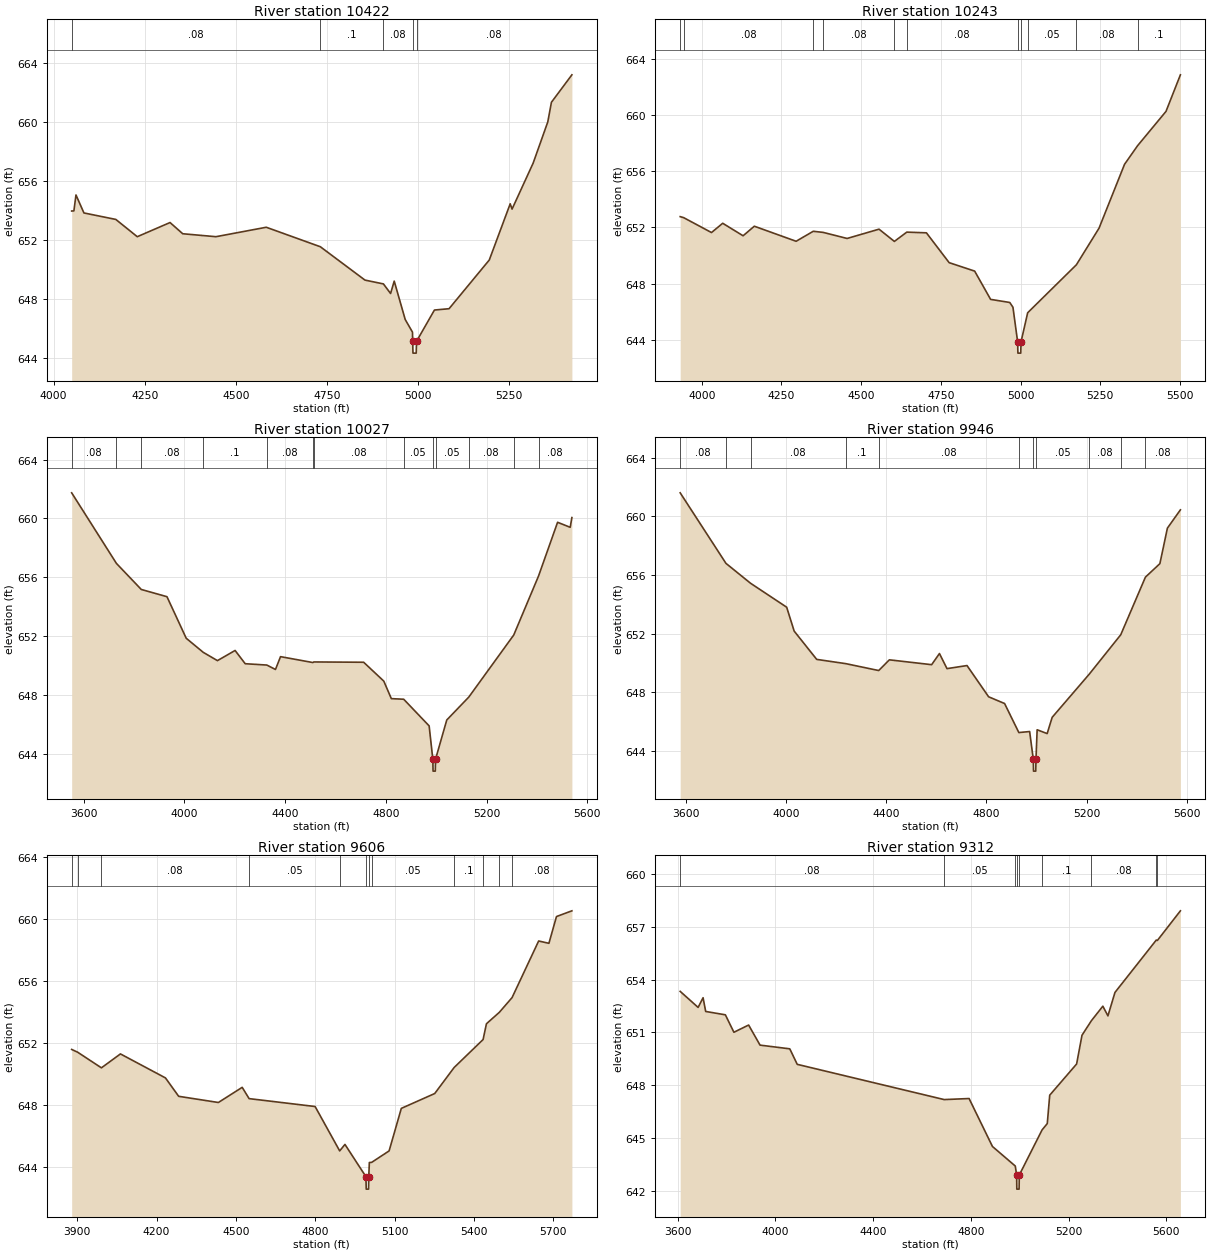
Type RM Length L Ch R = 1,10422,179,179,179
BEGIN DESCRIPTION:
BURNT BOOT CREEK 8.0
END DESCRIPTION:
XS GIS Cut Line= 3
      1997540.78     13601275.51      1997141.44     13601053.27
      1996229.09     13601122.66
#Sta/Elev= 30
  4049.6  653.99  4055.7  654.00  4061.4  655.08  4083.2  653.86  4170.7  653.42
  4229.5  652.25  4319.4  653.21  4354.2  652.45  4445.3  652.25  4583.3  652.89
  4731.6  651.57  4854.0  649.31  4904.7  649.05  4924.3  648.40  4934.3  649.24
  4964.4  646.64  4984.4  645.78  4984.9  645.16  4985.7  644.36  4994.6  644.36
  4995.5  645.16  5044.6  647.28  5084.7  647.37  5195.0  650.67  5252.4  654.48
  5257.5  654.12  5315.4  657.24  5355.5  660.03  5365.5  661.36  5421.6  663.22
#Mann=5,-1,0
  4049.6    0.08       0  4731.6     0.1       0  4904.7    0.08       0
  4984.9    0.07       0  4995.5    0.08       0
Bank Sta=4984.9,4995.5
Exp/Cntr=0.3,0.1

Type RM Length L Ch R = 1,10243,216,216,216
BEGIN DESCRIPTION:
Mapping XS 16efb4ec
END DESCRIPTION:
XS GIS Cut Line= 3
      1997637.95     13601160.90      1997394.92     13600903.97
      1996179.80     13600921.33
#Sta/Elev= 30
  3932.5  652.77  3943.3  652.70  4030.7  651.64  4065.9  652.30  4129.8  651.41
  4165.0  652.09  4296.1  651.02  4349.9  651.73  4381.1  651.65  4456.1  651.22
  4556.1  651.88  4604.3  651.01  4643.2  651.67  4704.8  651.62  4776.1  649.50
  4856.1  648.90  4906.1  646.89  4966.2  646.67  4976.2  646.33  4990.9  643.87
  4991.7  643.07  5000.6  643.07  5001.5  643.87  5022.4  645.94  5175.2  649.35
  5246.2  651.95  5326.2  656.49  5367.0  657.81  5456.2  660.25  5501.4  662.85
#Mann=11,-1,0
  3932.5    0.05       0  3943.3    0.08       0  4349.9    0.05       0
  4381.1    0.08       0  4604.3     0.1       0  4643.2    0.08       0
  4990.9    0.07       0  5001.5    0.08       0  5022.4    0.05       0
  5175.2    0.08       0  5367.0     0.1       0
Bank Sta=4990.9,5001.5
Exp/Cntr=0.3,0.1

Type RM Length L Ch R = 1,10027,81,81,81
BEGIN DESCRIPTION:
Mapping XS ce2c2d0a
END DESCRIPTION:
XS GIS Cut Line= 3
      1998172.70     13600629.66      1997339.36     13600685.22
      1996188.27     13600719.89
#Sta/Elev= 30
  3552.3  661.74  3730.0  656.95  3828.8  655.18  3930.8  654.69  4007.2  651.87
  4075.1  650.91  4131.3  650.35  4201.4  651.04  4241.5  650.14  4327.5  650.05
  4361.8  649.75  4381.8  650.62  4510.3  650.22  4514.1  650.26  4712.0  650.24
  4792.0  648.96  4822.0  647.77  4871.1  647.73  4972.1  645.92  4986.8  643.65
  4987.7  642.85  4996.6  642.85  4997.4  643.65  5042.1  646.32  5129.8  647.88
  5308.2  652.09  5406.8  656.10  5482.3  659.74  5532.4  659.40  5539.1  660.06
#Mann=13,-1,0
  3552.3    0.08       0  3730.0     0.1       0  3828.8    0.08       0
  4075.1     0.1       0  4327.5    0.08       0  4510.3    0.05       0
  4514.1    0.08       0  4871.1    0.05       0  4986.8    0.04       0
  4997.4    0.05       0  5129.8    0.08       0  5308.2    0.05       0
  5406.8    0.08       0
Bank Sta=4986.8,4997.4
Exp/Cntr=0.3,0.1

Type RM Length L Ch R = 1,9946,340,340,340
BEGIN DESCRIPTION:
BURNT BOOT CREEK 7.0
END DESCRIPTION:
XS GIS Cut Line= 3
      1998179.59     13600598.41      1997901.86     13600577.58
      1996183.07     13600653.97
#Sta/Elev= 30
  3576.1  661.60  3759.0  656.79  3857.5  655.43  4001.6  653.80  4031.6  652.17
  4121.7  650.24  4237.9  649.95  4369.4  649.48  4412.0  650.21  4581.0  649.88
  4612.2  650.64  4642.3  649.61  4722.3  649.82  4808.7  647.69  4872.5  647.23
  4929.5  645.25  4972.6  645.32  4987.3  643.42  4988.1  642.62  4997.0  642.62
  4997.9  643.42  5002.6  645.44  5042.6  645.18  5062.7  646.29  5210.2  649.22
  5336.7  651.92  5435.3  655.85  5493.1  656.77  5523.1  659.19  5575.1  660.44
#Mann=11,-1,0
  3576.1    0.08       0  3759.0     0.1       0  3857.5    0.08       0
  4237.9     0.1       0  4369.4    0.08       0  4929.5    0.05       0
  4987.3    0.04       0  4997.9    0.05       0  5210.2    0.08       0
  5336.7    0.05       0  5435.3    0.08       0
Bank Sta=4987.3,4997.9
Exp/Cntr=0.3,0.1

Type RM Length L Ch R = 1,9606,294,294,294
BEGIN DESCRIPTION:
Mapping XS 3d4cd371
END DESCRIPTION:
XS GIS Cut Line= 3
      1997919.27     13600147.02      1997061.58     13600188.69
      1996120.57     13600615.79
#Sta/Elev= 30
  3878.8  651.57  3901.5  651.39  3991.3  650.38  4063.3  651.28  4233.5  649.73
  4283.5  648.54  4433.7  648.14  4523.8  649.12  4549.9  648.39  4799.6  647.88
  4892.6  645.01  4912.5  645.43  4992.0  643.34  4992.9  642.54  5001.8  642.54
  5002.6  643.34  5004.8  644.26  5013.5  644.27  5079.5  645.01  5125.7  647.76
  5252.1  648.72  5325.4  650.40  5435.0  652.21  5447.7  653.23  5496.5  653.97
  5544.6  654.92  5645.2  658.58  5684.0  658.43  5712.6  660.16  5770.9  660.53
#Mann=12,-1,0
  3878.8    0.08       0  3901.5    0.05       0  3991.3    0.08       0
  4549.9    0.05       0  4892.6    0.08       0  4992.0    0.07       0
  5002.6    0.08       0  5013.5    0.05       0  5325.4     0.1       0
  5435.0    0.08       0  5496.5     0.1       0  5544.6    0.08       0
Bank Sta=4992,5002.6
Exp/Cntr=0.3,0.1

Type RM Length L Ch R = 1,9312,73,73,73
BEGIN DESCRIPTION:
BURNT BOOT CREEK 6.0
END DESCRIPTION:
XS GIS Cut Line= 4
      1998207.39     13600106.74      1997492.14     13599985.22
      1996582.42     13600009.52      1996259.75     13600266.27
#Sta/Elev= 30
  3609.9  653.33  3683.3  652.42  3703.6  652.97  3714.3  652.19  3794.9  652.00
  3829.8  651.01  3890.1  651.42  3936.9  650.28  4058.6  650.07  4089.1  649.19
  4690.8  647.19  4792.7  647.25  4888.3  644.53  4981.8  643.42  4987.3  642.91
  4988.1  642.11  4997.4  642.11  4998.2  642.91  5091.5  645.47  5112.8  645.83
  5122.8  647.44  5232.9  649.21  5254.9  650.84  5293.1  651.66  5340.3  652.49
  5361.1  651.94  5389.9  653.27  5559.0  656.24  5563.6  656.22  5657.8  657.90
#Mann=9,-1,0
  3609.9    0.08       0  4690.8    0.05       0  4981.8    0.08       0
  4987.3    0.07       0  4998.2    0.08       0  5091.5     0.1       0
  5293.1    0.08       0  5559.0     0.1       0  5563.6    0.08       0
Bank Sta=4987.3,4998.2
Exp/Cntr=0.3,0.1

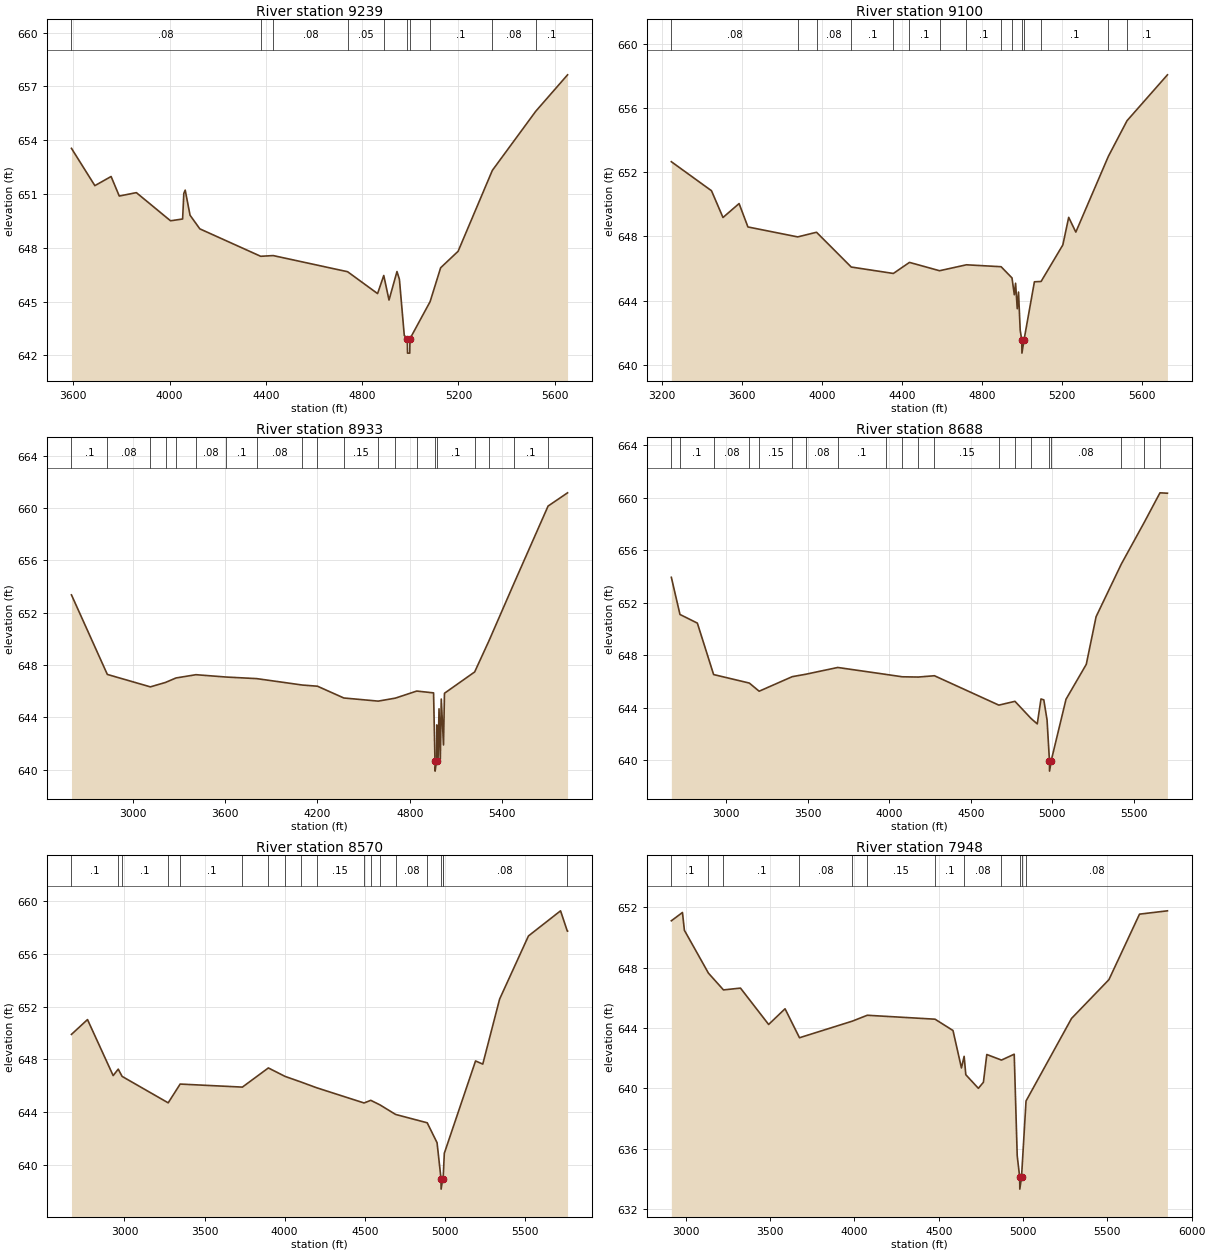
Type RM Length L Ch R = 1,9239,139,139,139
BEGIN DESCRIPTION:
Mapping XS be4de96e
END DESCRIPTION:
XS GIS Cut Line= 4
      1998210.85     13600047.71      1997224.78     13599881.05
      1996627.55     13599953.97      1996260.88     13600230.71
#Sta/Elev= 30
  3592.3  653.55  3689.5  651.47  3757.0  651.98  3790.9  650.89  3861.9  651.08
  4003.9  649.51  4054.1  649.61  4059.1  651.04  4064.8  651.22  4085.0  649.82
  4125.6  649.06  4378.5  647.53  4430.5  647.57  4739.5  646.67  4864.1  645.45
  4889.8  646.46  4911.6  645.09  4944.7  646.68  4954.8  646.25  4975.0  643.12
  4987.7  642.93  4988.5  642.13  4997.8  642.13  4998.6  642.93  5082.3  645.00
  5126.1  646.89  5198.7  647.81  5340.9  652.32  5521.4  655.62  5653.4  657.65
#Mann=10,-1,0
  3592.3    0.08       0  4378.5     0.1       0  4430.5    0.08       0
  4739.5    0.05       0  4889.8    0.08       0  4987.7    0.07       0
  4998.6    0.08       0  5082.3     0.1       0  5340.9    0.08       0
  5521.4     0.1       0
Bank Sta=4987.7,4998.6
Exp/Cntr=0.3,0.1

Type RM Length L Ch R = 1,9100,167,167,167
BEGIN DESCRIPTION:
Mapping XS e48abbcf
END DESCRIPTION:
XS GIS Cut Line= 3
      1998323.89     13599935.16      1997333.86     13599417.78
      1996230.06     13600220.01
#Sta/Elev= 30
  3246.0  652.66  3446.8  650.85  3504.3  649.18  3584.9  650.05  3629.1  648.59
  3878.2  647.97  3972.2  648.26  4145.9  646.09  4356.6  645.69  4437.2  646.38
  4587.7  645.86  4722.3  646.23  4895.5  646.11  4950.1  645.41  4961.7  644.36
  4967.9  645.08  4976.4  643.49  4982.6  644.53  4991.1  642.15  4999.0  641.52
  4999.8  640.72  5009.9  641.52  5062.2  645.17  5095.6  645.19  5204.4  647.47
  5233.7  649.19  5269.3  648.27  5432.3  653.00  5525.6  655.22  5727.6  658.08
#Mann=15,-1,0
  3246.0    0.08       0  3878.2     0.1       0  3972.2    0.08       0
  4145.9     0.1       0  4356.6    0.15       0  4437.2     0.1       0
  4587.7    0.08       0  4722.3     0.1       0  4895.5    0.05       0
  4950.1    0.08       0  4999.0    0.07       0  5009.9    0.08       0
  5095.6     0.1       0  5432.3    0.08       0  5525.6     0.1       0
Bank Sta=4999,5009.9
Exp/Cntr=0.3,0.1

Type RM Length L Ch R = 1,8933,245,245,245
BEGIN DESCRIPTION:
Mapping XS d73dd278
END DESCRIPTION:
XS GIS Cut Line= 3
      1999138.58     13599305.80      1997096.30     13599415.77
      1996155.35     13600124.10
#Sta/Elev= 30
  2601.8  653.37  2834.8  647.29  3114.4  646.34  3213.1  646.68  3280.9  647.02
  3410.5  647.27  3607.9  647.09  3805.3  646.97  4101.4  646.48  4200.0  646.39
  4371.2  645.49  4594.8  645.25  4706.4  645.48  4845.0  646.02  4954.3  645.88
  4963.5  640.70  4964.2  639.90  4974.4  640.70  4975.2  643.43  4983.5  640.81
  4989.7  644.66  4998.1  640.81  5004.3  645.41  5018.9  641.90  5025.1  645.85
  5221.3  647.48  5315.0  649.88  5474.1  654.18  5698.4  660.16  5824.8  661.17
#Mann=20,-1,0
  2601.8     0.1       0  2834.8    0.08       0  3114.4     0.1       0
  3213.1    0.15       0  3280.9     0.1       0  3410.5    0.08       0
  3607.9     0.1       0  3805.3    0.08       0  4101.4     0.1       0
  4200.0    0.15       0  4371.2    0.15       0  4594.8     0.1       0
  4706.4     0.1       0  4845.0     0.1       0  4963.5    0.07       0
  4974.4     0.1       0  5221.3    0.15       0  5315.0     0.1       0
  5474.1     0.1       0  5698.4     0.1       0
Bank Sta=4963.5,4974.4
Exp/Cntr=0.3,0.1

Type RM Length L Ch R = 1,8688,118,118,118
BEGIN DESCRIPTION:
Mapping XS ebb6b1f3
END DESCRIPTION:
XS GIS Cut Line= 3
      1999154.15     13599240.70      1997203.94     13599360.22
      1996118.53     13599429.57
#Sta/Elev= 30
  2664.6  653.95  2717.5  651.12  2824.1  650.46  2923.8  646.54  3142.9  645.89
  3202.9  645.27  3406.0  646.38  3487.4  646.56  3684.9  647.08  3981.2  646.55
  4080.0  646.37  4178.7  646.35  4277.5  646.45  4672.5  644.21  4771.3  644.50
  4870.1  643.19  4908.0  642.78  4930.9  644.68  4948.1  644.61  4968.1  643.08
  4982.7  639.98  4983.5  639.18  4993.6  639.98  5084.4  644.66  5208.6  647.32
  5268.7  650.95  5423.3  654.96  5564.4  658.15  5660.3  660.39  5706.1  660.36
#Mann=20,-1,0
  2664.6    0.15       0  2717.5     0.1       0  2923.8    0.08       0
  3142.9     0.1       0  3202.9    0.15       0  3406.0     0.1       0
  3487.4    0.08       0  3684.9     0.1       0  3981.2    0.05       0
  4080.0    0.08       0  4178.7     0.1       0  4277.5    0.15       0
  4672.5     0.1       0  4771.3    0.08       0  4870.1    0.05       0
  4982.7    0.07       0  4993.6    0.08       0  5423.3    0.05       0
  5564.4    0.08       0  5660.3    0.05       0
Bank Sta=4982.7,4993.6
Exp/Cntr=0.3,0.1

Type RM Length L Ch R = 1,8570,622,622,622
BEGIN DESCRIPTION:
BURNT BOOT CREEK 4.0
END DESCRIPTION:
XS GIS Cut Line= 2
      1999175.04     13599172.99      1996081.23     13599302.06
#Sta/Elev= 30
  2669.2  649.90  2769.3  651.02  2929.5  646.78  2961.1  647.27  2985.3  646.72
  3272.9  644.72  3347.6  646.14  3736.0  645.91  3898.2  647.36  4002.5  646.72
  4101.1  646.30  4199.7  645.86  4495.5  644.71  4537.4  644.91  4594.1  644.57
  4692.7  643.84  4889.8  643.21  4951.2  641.70  4975.8  638.99  4976.5  638.19
  4986.7  638.99  4989.7  639.13  4996.4  640.90  5191.4  647.89  5236.5  647.65
  5341.6  652.57  5521.7  657.35  5721.9  659.25  5764.4  657.71  5765.7  657.71
#Mann=19,-1,0
  2669.2     0.1       0  2961.1    0.08       0  2985.3     0.1       0
  3272.9    0.15       0  3347.6     0.1       0  3736.0    0.15       0
  3898.2     0.1       0  4002.5    0.08       0  4101.1     0.1       0
  4199.7    0.15       0  4495.5     0.1       0  4537.4    0.15       0
  4594.1     0.1       0  4692.7    0.08       0  4889.8    0.05       0
  4975.8    0.07       0  4986.7    0.05       0  4989.7    0.08       0
  5764.4    0.05       0
Bank Sta=4975.8,4986.7
Exp/Cntr=0.3,0.1

Type RM Length L Ch R = 1,7948,244,244,244
BEGIN DESCRIPTION:
BURNT BOOT CREEK 3.0
END DESCRIPTION:
XS GIS Cut Line= 4
      1999180.19     13599136.53      1997638.33     13598761.32
      1997125.00     13598725.00      1996290.65     13598828.38
#Sta/Elev= 30
  2914.1  651.10  2980.0  651.65  2991.5  650.47  3134.2  647.63  3223.3  646.52
  3324.2  646.64  3491.1  644.23  3588.4  645.27  3674.1  643.35  3987.3  644.45
  4076.1  644.84  4478.0  644.58  4584.5  643.83  4634.6  641.35  4650.6  642.12
  4660.5  640.90  4734.9  640.00  4764.9  640.40  4785.0  642.24  4872.1  641.87
  4947.6  642.26  4965.4  635.53  4980.0  634.12  4980.8  633.32  4990.9  634.12
  5017.7  639.16  5287.6  644.63  5509.3  647.20  5690.7  651.54  5856.3  651.76
#Mann=12,-1,0
  2914.1     0.1       0  3134.2    0.15       0  3223.3     0.1       0
  3674.1    0.08       0  3987.3     0.1       0  4076.1    0.15       0
  4478.0     0.1       0  4650.6    0.08       0  4872.1    0.05       0
  4980.0    0.04       0  4990.9    0.05       0  5017.7    0.08       0
Bank Sta=4980,4990.9
Exp/Cntr=0.3,0.1