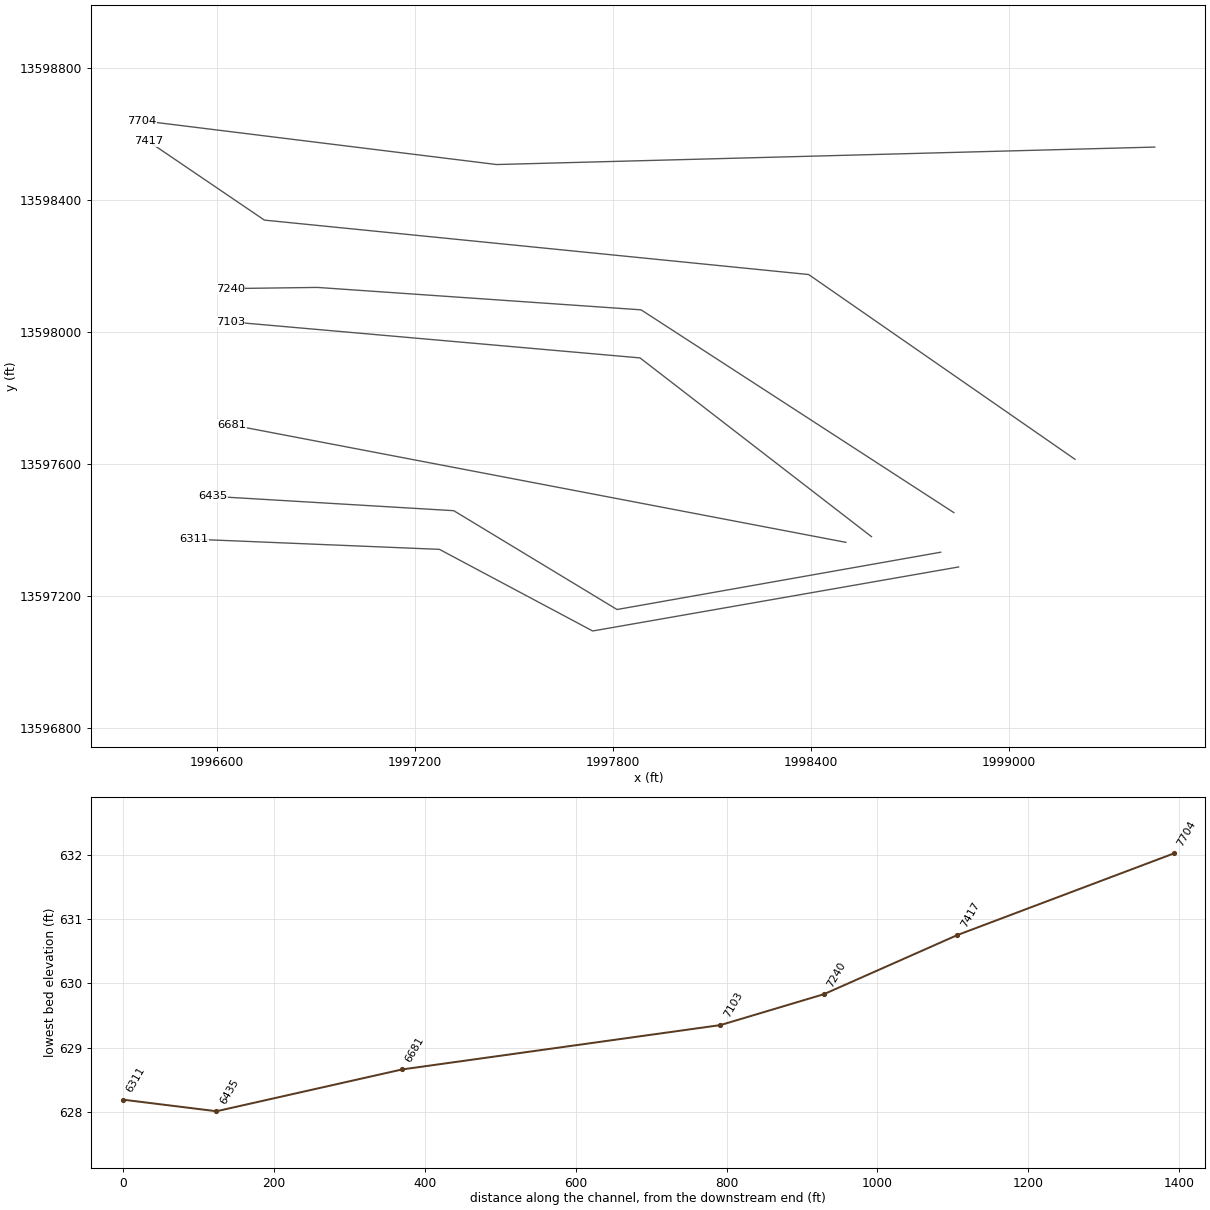
HEC-RAS study BURNT BOOT CREEK.prj: BURNT BOOT CREEK Base Level Engineering

--- BURNT BOOT CREEK.g01 (geometry) --- (continued)

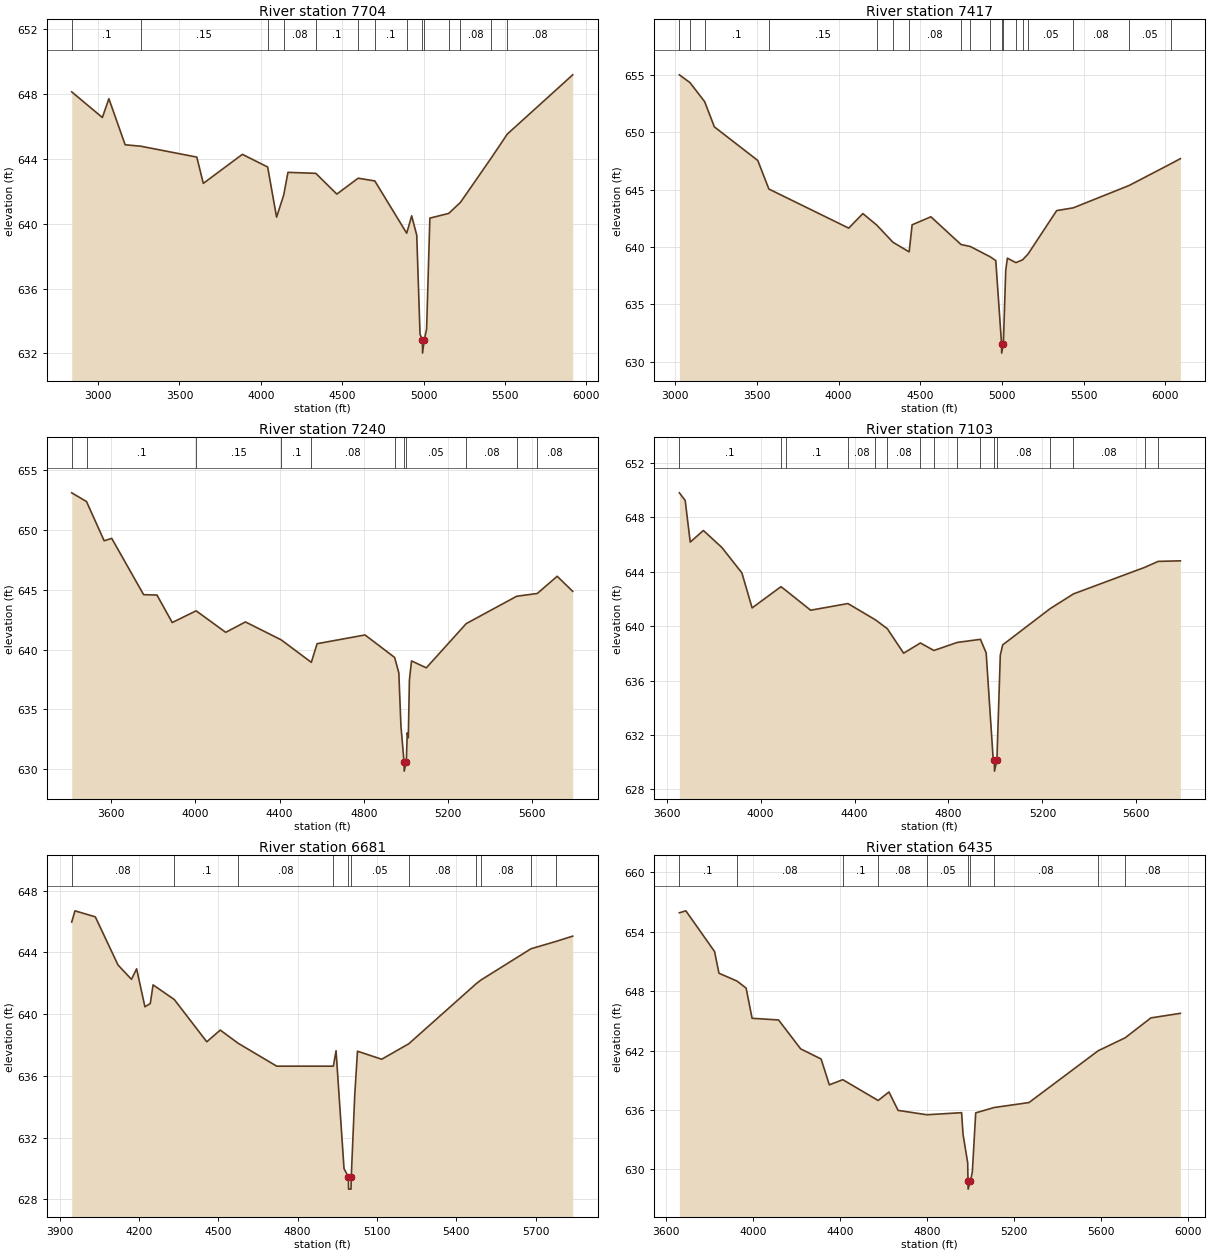
Type RM Length L Ch R = 1,7704,287,287,287
BEGIN DESCRIPTION:
BURNT BOOT CREEK 2.0
END DESCRIPTION:
XS GIS Cut Line= 3
      1999443.26     13598561.01      1997448.45     13598508.08
      1996374.04     13598640.87
#Sta/Elev= 30
  2838.0  648.12  3026.3  646.54  3066.3  647.70  3166.4  644.86  3262.8  644.77
  3606.5  644.10  3646.5  642.48  3886.6  644.27  4041.9  643.49  4096.7  640.40
  4140.4  641.76  4166.7  643.16  4337.6  643.10  4466.8  641.82  4598.0  642.80
  4700.3  642.63  4896.1  639.41  4926.7  640.48  4957.9  639.29  4978.1  633.18
  4992.8  632.82  4993.5  632.02  5003.7  632.82  5018.4  633.50  5038.5  640.34
  5154.3  640.63  5226.4  641.31  5415.9  644.05  5514.4  645.52  5916.1  649.17
#Mann=14,-1,0
  2838.0     0.1       0  3262.8    0.15       0  4041.9     0.1       0
  4140.4    0.08       0  4337.6     0.1       0  4598.0    0.15       0
  4700.3     0.1       0  4896.1    0.08       0  4992.8    0.07       0
  5003.7    0.08       0  5154.3     0.1       0  5226.4    0.08       0
  5415.9     0.1       0  5514.4    0.08       0
Bank Sta=4992.8,5003.7
Exp/Cntr=0.3,0.1

Type RM Length L Ch R = 1,7417,177,177,177
BEGIN DESCRIPTION:
Mapping XS 010e04e0
END DESCRIPTION:
XS GIS Cut Line= 4
      1999201.51     13597614.81      1998394.19     13598174.73
      1996744.88     13598339.66      1996393.29     13598578.39
#Sta/Elev= 30
  3026.3  655.02  3090.6  654.35  3181.0  652.68  3240.5  650.48  3506.0  647.55
  3573.9  645.06  4062.5  641.65  4148.7  642.92  4233.7  641.92  4332.9  640.42
  4432.1  639.58  4450.2  641.94  4565.0  642.64  4749.6  640.22  4806.0  640.05
  4928.0  639.15  4962.0  638.82  4997.5  631.55  4998.2  630.75  5008.4  631.55
  5023.0  637.98  5033.1  639.03  5085.3  638.64  5126.3  638.89  5159.8  639.40
  5334.6  643.18  5436.3  643.42  5777.8  645.37  6032.5  647.26  6091.3  647.71
#Mann=18,-1,0
  3026.3     0.1       0  3090.6    0.08       0  3181.0     0.1       0
  3573.9    0.15       0  4233.7     0.1       0  4332.9    0.15       0
  4432.1    0.08       0  4749.6     0.1       0  4806.0    0.08       0
  4928.0    0.05       0  4997.5    0.04       0  5008.4    0.05       0
  5085.3     0.1       0  5126.3    0.08       0  5159.8    0.05       0
  5436.3    0.08       0  5777.8    0.05       0  6032.5    0.08       0
Bank Sta=4997.5,5008.4
Exp/Cntr=0.3,0.1

Type RM Length L Ch R = 1,7240,137,137,137
BEGIN DESCRIPTION:
Mapping XS 588d3a80
END DESCRIPTION:
XS GIS Cut Line= 4
      1998834.34     13597453.17      1997886.44     13598067.74
      1996905.25     13598135.67      1996641.41     13598132.19
#Sta/Elev= 30
  3414.0  653.11  3484.3  652.38  3567.9  649.10  3603.9  649.30  3755.2  644.59
  3818.5  644.56  3891.0  642.26  4004.3  643.24  4144.8  641.44  4238.4  642.31
  4408.0  640.81  4550.9  638.93  4578.3  640.49  4805.8  641.22  4946.2  639.34
  4966.1  638.05  4976.2  633.58  4990.7  630.63  4991.5  629.83  5001.7  630.63
  5006.0  633.03  5011.0  632.62  5016.3  637.45  5026.3  639.05  5096.5  638.47
  5285.9  642.17  5525.5  644.46  5623.1  644.69  5717.5  646.13  5791.1  644.87
#Mann=11,-1,0
  3414.0    0.15       0  3484.3     0.1       0  4004.3    0.15       0
  4408.0     0.1       0  4550.9    0.08       0  4946.2    0.05       0
  4990.7    0.04       0  5001.7    0.05       0  5285.9    0.08       0
  5525.5     0.1       0  5623.1    0.08       0
Bank Sta=4990.7,5001.7
Exp/Cntr=0.3,0.1

Type RM Length L Ch R = 1,7103,422,422,422
BEGIN DESCRIPTION:
Mapping XS 0356b251
END DESCRIPTION:
XS GIS Cut Line= 3
      1998584.67     13597380.35      1997883.24     13597922.05
      1996641.40     13598031.50
#Sta/Elev= 30
  3654.3  649.81  3679.1  649.25  3700.5  646.19  3756.6  647.04  3835.4  645.79
  3920.5  643.92  3964.0  641.35  4086.8  642.91  4109.4  642.61  4213.1  641.18
  4371.8  641.67  4489.2  640.47  4539.7  639.82  4609.1  638.02  4680.4  638.77
  4738.0  638.22  4837.0  638.81  4936.1  639.04  4960.4  638.04  4990.5  630.18
  4995.1  630.15  4995.9  629.35  5006.1  630.15  5020.6  637.87  5030.7  638.63
  5233.2  641.30  5332.2  642.38  5635.3  644.33  5693.0  644.77  5787.2  644.81
#Mann=16,-1,0
  3654.3     0.1       0  4086.8    0.15       0  4109.4     0.1       0
  4371.8    0.08       0  4489.2     0.1       0  4539.7    0.08       0
  4680.4     0.1       0  4738.0    0.08       0  4837.0    0.05       0
  4936.1    0.08       0  4995.1    0.07       0  5006.1    0.08       0
  5233.2     0.1       0  5332.2    0.08       0  5635.3     0.1       0
  5693.0    0.08       0
Bank Sta=4995.1,5006.1
Exp/Cntr=0.3,0.1

Type RM Length L Ch R = 1,6681,246,246,246
BEGIN DESCRIPTION:
Mapping XS a4f79686
END DESCRIPTION:
XS GIS Cut Line= 2
      1998507.04     13597363.10      1996645.05     13597719.00
#Sta/Elev= 30
  3945.0  645.97  3957.3  646.70  4034.3  646.31  4120.2  643.19  4171.1  642.26
  4190.6  642.94  4222.0  640.48  4242.3  640.69  4252.8  641.90  4333.3  640.95
  4456.1  638.21  4507.0  638.97  4575.2  638.11  4720.8  636.63  4935.1  636.63
  4945.2  637.63  4975.4  629.99  4991.8  629.46  4992.6  628.66  5002.0  628.66
  5002.8  629.46  5016.1  634.80  5026.3  637.60  5117.9  637.08  5220.3  638.08
  5475.8  641.98  5493.1  642.21  5682.7  644.24  5778.0  644.72  5840.7  645.06
#Mann=11,-1,0
  3945.0    0.08       0  4333.3     0.1       0  4575.2    0.08       0
  4935.1    0.05       0  4991.8    0.04       0  5002.8    0.05       0
  5220.3    0.08       0  5475.8    0.05       0  5493.1    0.08       0
  5682.7     0.1       0  5778.0    0.08       0
Bank Sta=4991.8,5002.8
Exp/Cntr=0.3,0.1

Type RM Length L Ch R = 1,6435,124,124,124
BEGIN DESCRIPTION:
Mapping XS 75b254d7
END DESCRIPTION:
XS GIS Cut Line= 4
      1998794.42     13597333.17      1997813.49     13597159.55
      1997318.70     13597459.03      1996589.73     13597502.42
#Sta/Elev= 30
  3661.7  655.91  3691.6  656.11  3823.6  652.00  3843.9  649.81  3926.7  649.02
  3968.8  648.31  3996.2  645.26  4118.1  645.09  4219.7  642.17  4313.6  641.15
  4351.7  638.54  4413.5  639.06  4576.3  636.96  4625.9  637.82  4667.8  635.96
  4800.6  635.52  4960.0  635.73  4966.8  633.53  4988.1  630.67  4989.5  628.81
  4990.1  628.01  5000.7  628.81  5009.5  629.76  5025.0  635.71  5109.7  636.25
  5270.0  636.75  5588.3  641.98  5712.5  643.29  5831.0  645.30  5966.5  645.76
#Mann=10,-1,0
  3661.7     0.1       0  3926.7    0.08       0  4413.5     0.1       0
  4576.3    0.08       0  4800.6    0.05       0  4989.5    0.04       0
  5000.7    0.05       0  5109.7    0.08       0  5588.3    0.05       0
  5712.5    0.08       0
Bank Sta=4989.5,5000.7
Exp/Cntr=0.3,0.1

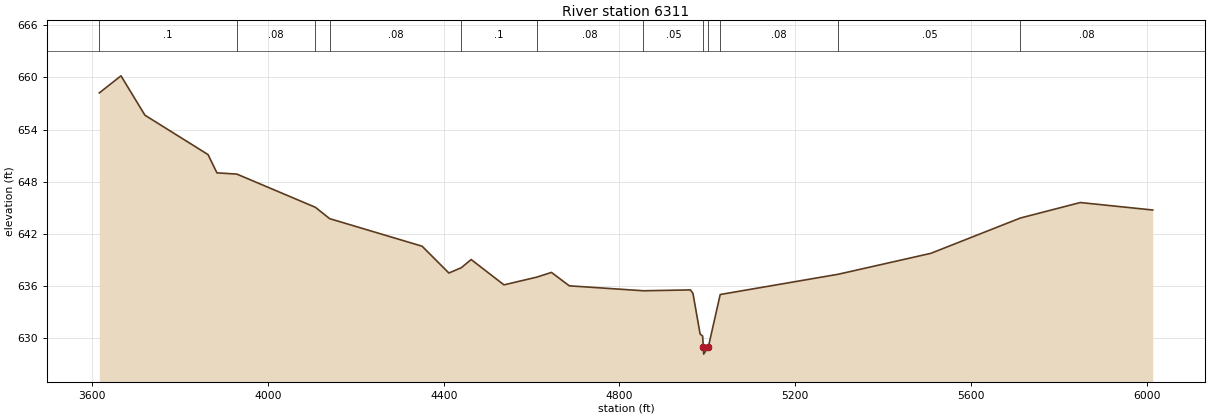
Type RM Length L Ch R = 1,6311,0,0,0
BEGIN DESCRIPTION:
BURNT BOOT CREEK 1.0
END DESCRIPTION:
XS GIS Cut Line= 4
      1998848.67     13597288.47      1997739.70     13597094.45
      1997275.29     13597341.84      1996530.23     13597372.65
#Sta/Elev= 30
  3616.2  658.21  3665.5  660.17  3719.9  655.65  3863.6  651.12  3883.9  649.02
  3929.1  648.88  4108.1  645.06  4140.3  643.76  4350.9  640.59  4411.8  637.51
  4440.1  638.12  4462.5  639.06  4537.2  636.15  4612.1  637.04  4645.3  637.58
  4685.9  636.04  4854.7  635.47  4961.7  635.57  4967.4  635.16  4983.7  630.50
  4989.4  630.26  4991.0  628.99  4991.7  628.19  5002.3  628.99  5029.4  635.04
  5298.1  637.37  5508.7  639.77  5712.6  643.83  5849.0  645.61  6013.9  644.75
#Mann=12,-1,0
  3616.2     0.1       0  3929.1    0.08       0  4108.1     0.1       0
  4140.3    0.08       0  4440.1     0.1       0  4612.1    0.08       0
  4854.7    0.05       0  4991.0    0.04       0  5002.3    0.05       0
  5029.4    0.08       0  5298.1    0.05       0  5712.6    0.08       0
Bank Sta=4991,5002.3
Exp/Cntr=0.3,0.1

Chan Stop Cuts=-1