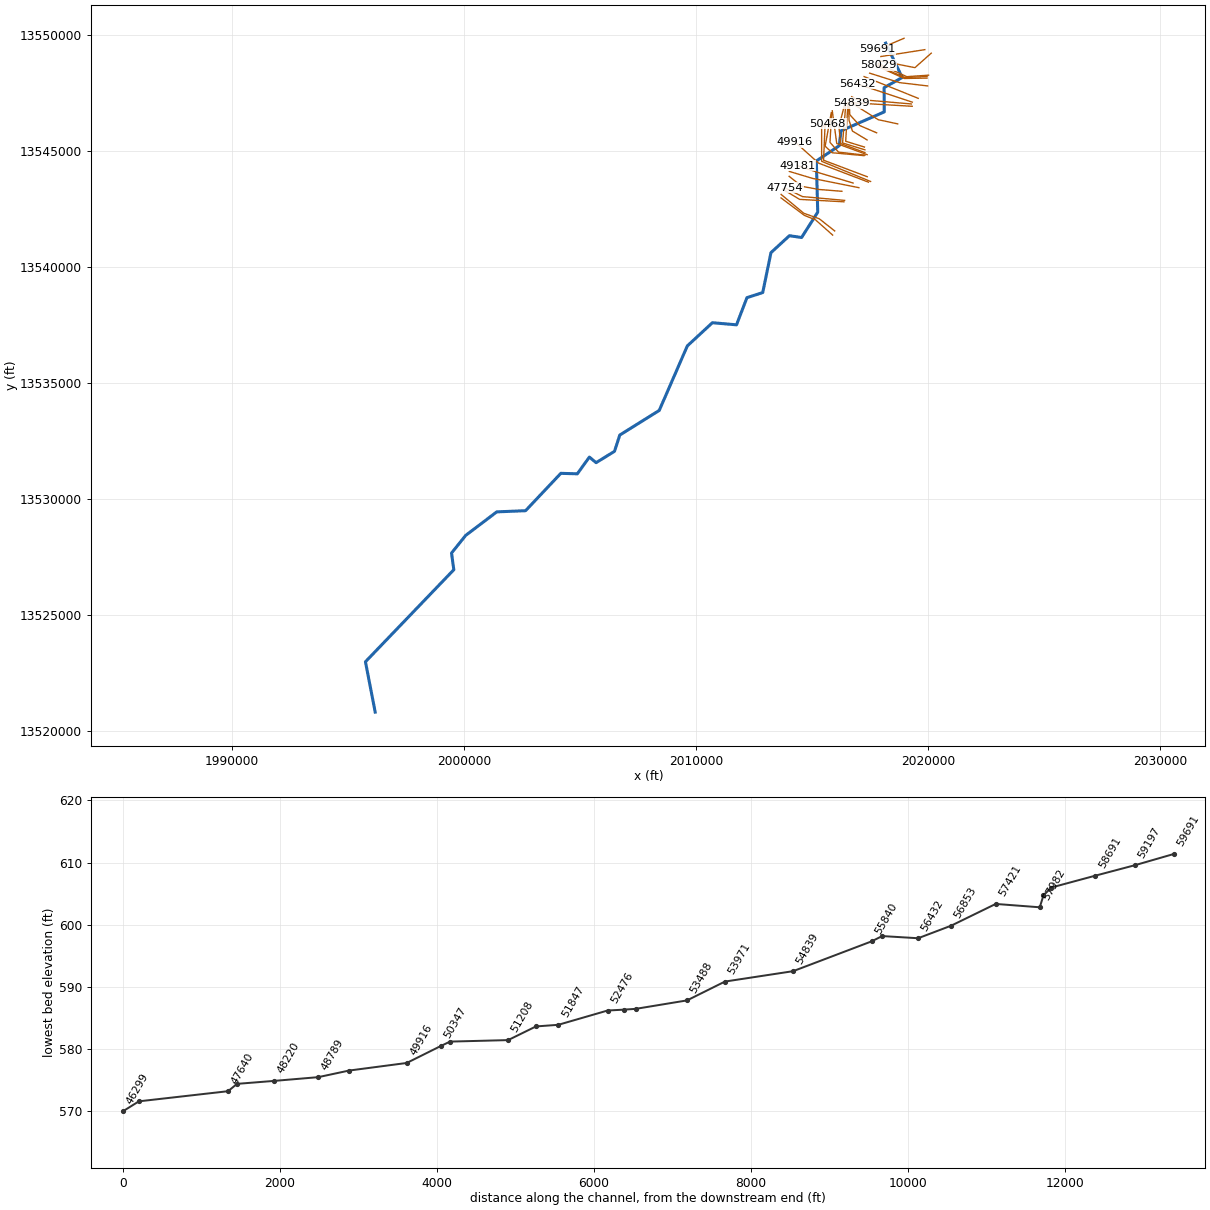
--- Becerro Creek.prj (project) ---

Proj Title=Becerro Creek Base Level Engineering
Current Plan=p01
Default Exp/Contr=0.3,0.1
English Units
Geom File=g01
Flow File=f01
Plan File=p01
Y Axis Title=Elevation
X Axis Title(PF)=Main Channel Distance
X Axis Title(XS)=Station
BEGIN DESCRIPTION:
Becerro Creek
END DESCRIPTION:
DSS Export Rating Curves= 0
DSS Export Rating Curve Sorted= 0
DSS Export Volume Flow Curves= 0
DXF OffsetX= 0
DXF OffsetY= 0
DXF ScaleX= 1
DXF ScaleY= 10

--- Becerro Creek.p01 (plan) ---

Plan Title=Multiple Run
Short Identifier=Multiple
Geom File=g01
Flow File=f01
Subcritical Flow
K Sum by GR= 0
Std Step Tol= 0.01
Critical Tol= 0.01
Num of Std Step Trials= 20
Max Error Tol= 0.3
Flow Tol Ratio= 0.001
Split Flow NTrial= 30
Split Flow Tol= 0.02
Split Flow Ratio= 0.02
Log Output Level= 0
Friction Slope Method= 1
Unsteady Friction Slope Method= 2
Unsteady Bridges Friction Slope Method= 1
Parabolic Critical Depth
Global Vel Dist=  1 , 1 , 1
Global Log Level= 0
CheckData=True
Encroach Param= -1, 0, 0, 0
BEGIN DESCRIPTION:
Multiple Run
END DESCRIPTION:

--- Becerro Creek.f01 (steady flow) ---

Flow Title=Multiple
Program Version=5.05
Number of Profiles= 7
Profile Names=10-year,25-year,50-year,1pct_min,100-year,1pct_plu,500-year
River Rch & RM=Becerro Creek,Reach-1         ,59691
     451     626     769     468     934    1864    1384
River Rch & RM=Becerro Creek,Reach-1         ,58127
     555     782     972     599    1194    2383    1817
River Rch & RM=Becerro Creek,Reach-1         ,49916
     852    1226    1546     964    1924    3839    3004
River Rch & RM=Becerro Creek,Reach-1         ,46504
     963    1399    1776    1117    2228    4446    3546
River Rch & RM=Becerro Creek,Reach-1         ,42148
     972    1409    1786    1121    2237    4464    3554
River Rch & RM=Becerro Creek,Reach-1         ,32620
    1044    1519    1929    1214    2423    4834    3870
River Rch & RM=Becerro Creek,Reach-1         ,30145
    1146    1674    2131    1345    2683    5354    4309
River Rch & RM=Becerro Creek,Reach-1         ,23608
    1201    1755    2235    1411    2815    5617    4525
River Rch & RM=Becerro Creek,Reach-1         ,15182
    1347    1972    2516    1590    3173    6330    5117
River Rch & RM=Becerro Creek,Reach-1         ,12781
    1347    1972    2516    1590    3173    6330    5117
River Rch & RM=Becerro Creek,Reach-1         ,1039
    1394    2044    2611    1652    3297    6578    5331
Boundary for River Rch & Prof#=Becerro Creek,Reach-1         , 1
Up Type= 0
Dn Type= 3
Dn Slope=0.00183
Boundary for River Rch & Prof#=Becerro Creek,Reach-1         , 2
Up Type= 0
Dn Type= 3
Dn Slope=0.00183
Boundary for River Rch & Prof#=Becerro Creek,Reach-1         , 3
Up Type= 0
Dn Type= 3
Dn Slope=0.00183
Boundary for River Rch & Prof#=Becerro Creek,Reach-1         , 4
Up Type= 0
Dn Type= 3
Dn Slope=0.00183
Boundary for River Rch & Prof#=Becerro Creek,Reach-1         , 5
Up Type= 0
Dn Type= 3
Dn Slope=0.00183
Boundary for River Rch & Prof#=Becerro Creek,Reach-1         , 6
Up Type= 0
Dn Type= 3
Dn Slope=0.00183
Boundary for River Rch & Prof#=Becerro Creek,Reach-1         , 7
Up Type= 0
Dn Type= 3
Dn Slope=0.00183
DSS Import GetInterval= 0
DSS Import GetPeak= 0
DSS Import FillOption= 0

--- Becerro Creek.g01 (geometry) ---

Geom Title=Existing Conditions

River Reach=Becerro Creek,Reach-1
Reach XY= 30
      2018180.80     13549653.75      2018890.98     13548171.74
      2018110.80     13547734.54      2018118.41     13546689.53
      2016250.80     13545874.54      2016180.80     13545234.54
      2015190.80     13544574.54      2015251.18     13542368.54
      2014555.52     13541277.57      2014030.80     13541354.54
      2013235.22     13540624.30      2012880.80     13538904.54
      2012200.80     13538684.54      2011750.80     13537514.54
      2010710.80     13537604.54      2009630.80     13536604.54
      2008420.80     13533824.54      2006720.80     13532764.54
      2006493.06     13532062.94      2005700.80     13531574.54
      2005410.80     13531814.54      2004890.80     13531094.54
      2004180.80     13531114.54      2002660.80     13529504.54
      2001420.80     13529454.54      2000078.50     13528438.70
      1999470.56     13527679.99      1999569.30     13526961.67
      1995760.80     13522994.54      1996180.80     13520824.54

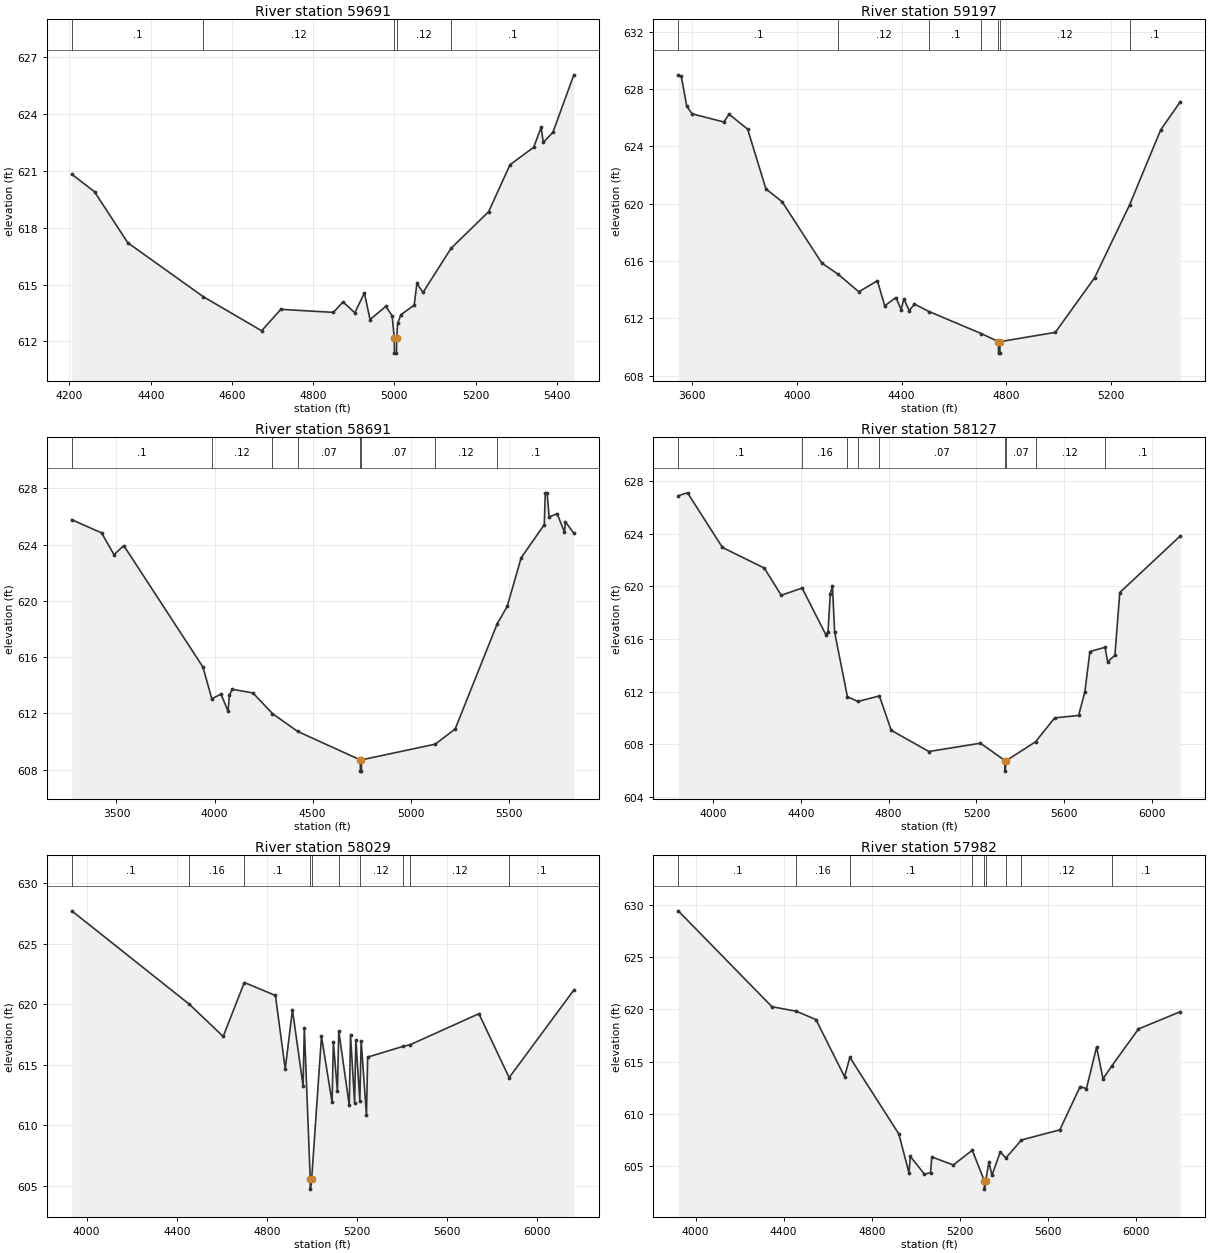
Type RM Length L Ch R = 1,59691,494,494,494
BEGIN DESCRIPTION:
Mapping XS a9a4e383
END DESCRIPTION:
XS GIS Cut Line= 2
      2018971.23     13549862.07      2017833.02     13549379.72
#Sta/Elev= 30
  4205.6  620.82  4261.7  619.89  4343.6  617.20  4529.9  614.35  4673.1  612.56
  4720.4  613.69  4849.7  613.53  4873.4  614.08  4902.5  613.51  4926.1  614.55
  4940.1  613.15  4978.9  613.85  4994.4  613.35  4999.6  612.18  5000.1  611.38
  5005.1  611.38  5005.6  612.18  5008.0  612.95  5016.1  613.41  5048.7  613.91
  5055.4  615.06  5070.4  614.58  5139.5  616.91  5232.0  618.84  5284.7  621.32
  5343.0  622.24  5361.2  623.29  5366.6  622.50  5390.3  623.03  5441.8  626.06
#Mann=5,-1,0
  4205.6     0.1       0  4529.9    0.12       0  4999.6    0.07       0
  5005.6    0.12       0  5139.5     0.1       0
Bank Sta=4999.6,5005.6
Exp/Cntr=0.3,0.1

Type RM Length L Ch R = 1,59197,506,506,506
BEGIN DESCRIPTION:
Mapping XS 3f5292b0
END DESCRIPTION:
XS GIS Cut Line= 2
      2019867.03     13549372.49      2017971.24     13549075.62
#Sta/Elev= 30
  3546.2  629.00  3557.8  628.90  3578.6  626.83  3598.9  626.28  3720.3  625.71
  3740.6  626.25  3811.4  625.21  3881.3  621.04  3943.0  620.15  4094.8  615.87
  4158.4  615.07  4236.5  613.86  4307.4  614.63  4335.3  612.88  4378.3  613.46
  4398.0  612.62  4408.6  613.36  4428.9  612.54  4449.1  613.00  4504.9  612.48
  4705.0  610.94  4770.0  610.38  4770.5  609.58  4775.5  609.58  4776.0  610.38
  4987.5  611.03  5137.4  614.84  5270.9  619.91  5390.4  625.17  5465.1  627.12
#Mann=7,-1,0
  3546.2     0.1       0  4158.4    0.12       0  4504.9     0.1       0
  4705.0    0.12       0  4770.0    0.07       0  4776.0    0.12       0
  5270.9     0.1       0
Bank Sta=4770,4776
Exp/Cntr=0.3,0.1

Type RM Length L Ch R = 1,58691,564,564,564
BEGIN DESCRIPTION:
Mapping XS e9955a95
END DESCRIPTION:
XS GIS Cut Line= 3
      2020143.13     13549221.47      2019439.99     13548596.45
      2017851.41     13548908.96
#Sta/Elev= 30
  3272.2  625.77  3424.2  624.83  3487.8  623.28  3537.3  623.93  3941.0  615.29
  3986.2  613.03  4033.0  613.37  4069.0  612.15  4075.7  613.27  4089.9  613.71
  4196.1  613.45  4295.5  611.98  4424.3  610.71  4743.2  608.69  4743.7  607.89
  4748.7  607.89  4749.2  608.69  5125.9  609.81  5227.0  610.89  5441.1  618.36
  5492.0  619.60  5563.4  623.06  5681.3  625.42  5686.4  627.68  5695.8  627.66
  5706.0  625.96  5746.8  626.20  5784.0  624.89  5789.1  625.62  5832.0  624.80
#Mann=8,-1,0
  3272.2     0.1       0  3986.2    0.12       0  4295.5     0.1       0
  4424.3    0.07       0  4743.2    0.07       0  4749.2    0.07       0
  5125.9    0.12       0  5441.1     0.1       0
Bank Sta=4743.2,4749.2
Exp/Cntr=0.3,0.1

Type RM Length L Ch R = 1,58127,98,98,98
BEGIN DESCRIPTION:
Mapping XS f0eae82c
END DESCRIPTION:
XS GIS Cut Line= 3
      2020025.95     13548272.67      2019088.43     13548207.56
      2017864.50     13548771.79
#Sta/Elev= 30
  3841.5  626.88  3883.8  627.10  4042.9  622.95  4233.4  621.39  4310.8  619.32
  4405.8  619.87  4514.1  616.33  4524.1  616.56  4534.1  619.45  4544.1  619.99
  4554.2  616.50  4612.3  611.62  4659.6  611.26  4758.0  611.68  4811.8  609.07
  4983.5  607.46  5218.5  608.09  5330.2  606.77  5330.7  605.97  5336.4  606.77
  5469.5  608.20  5556.4  610.01  5665.7  610.20  5694.1  611.99  5717.1  615.05
  5785.9  615.37  5798.1  614.27  5831.1  614.77  5853.2  619.53  6129.0  623.83
#Mann=9,-1,0
  3841.5     0.1       0  4405.8    0.16       0  4612.3     0.1       0
  4659.6    0.05       0  4758.0    0.07       0  5330.2    0.07       0
  5336.4    0.07       0  5469.5    0.12       0  5785.9     0.1       0
Bank Sta=5330.2,5336.4
Exp/Cntr=0.3,0.1

Type RM Length L Ch R = 1,58029,47,47,47
BEGIN DESCRIPTION:
Becerro Creek 88.0
END DESCRIPTION:
XS GIS Cut Line= 4
      2019966.03     13548215.38      2019019.85     13548167.63
      2018394.85     13548435.00      2017860.17     13548709.28
#Sta/Elev= 30
  3933.9  627.72  4455.8  619.99  4605.8  617.33  4699.7  621.79  4837.7  620.72
  4881.2  614.63  4913.2  619.53  4960.4  613.25  4965.9  618.04  4992.2  605.50
  4992.7  604.70  4998.4  605.50  5042.1  617.33  5089.2  611.87  5094.7  616.87
  5112.8  612.79  5118.8  617.79  5165.4  611.62  5170.9  617.46  5189.0  611.83
  5194.5  617.05  5212.3  612.00  5218.1  616.97  5241.7  610.80  5247.1  615.62
  5402.7  616.50  5435.1  616.64  5740.7  619.21  5874.9  613.92  6162.0  621.17
#Mann=10,-1,0
  3933.9     0.1       0  4455.8    0.16       0  4699.7     0.1       0
  4992.2    0.07       0  4998.4     0.1       0  5118.8    0.07       0
  5212.3    0.12       0  5402.7    0.07       0  5435.1    0.12       0
  5874.9     0.1       0
Bank Sta=4992.2,4998.4
Exp/Cntr=0.3,0.1

Type RM Length L Ch R = 1,57982,561,561,561
BEGIN DESCRIPTION:
Mapping XS a3518878
END DESCRIPTION:
XS GIS Cut Line= 3
      2019960.82     13548146.80      2018984.26     13548129.44
      2017794.99     13548667.65
#Sta/Elev= 30
  3920.7  629.42  4346.6  620.25  4458.1  619.81  4546.6  619.02  4676.6  613.56
  4700.9  615.40  4923.5  608.07  4969.7  604.34  4975.2  605.94  5039.0  604.25
  5067.6  604.35  5073.1  605.88  5171.0  605.11  5257.2  606.52  5312.0  603.60
  5312.5  602.80  5318.2  603.60  5332.8  605.40  5346.6  604.12  5384.5  606.36
  5409.8  605.78  5480.8  607.50  5655.1  608.47  5747.5  612.61  5776.1  612.41
  5822.3  616.39  5851.5  613.35  5890.6  614.56  6012.6  618.12  6202.8  619.77
#Mann=9,-1,0
  3920.7     0.1       0  4458.1    0.16       0  4700.9     0.1       0
  5257.2    0.12       0  5312.0    0.07       0  5318.2    0.12       0
  5409.8     0.1       0  5480.8    0.12       0  5890.6     0.1       0
Bank Sta=5312,5318.2
Exp/Cntr=0.3,0.1

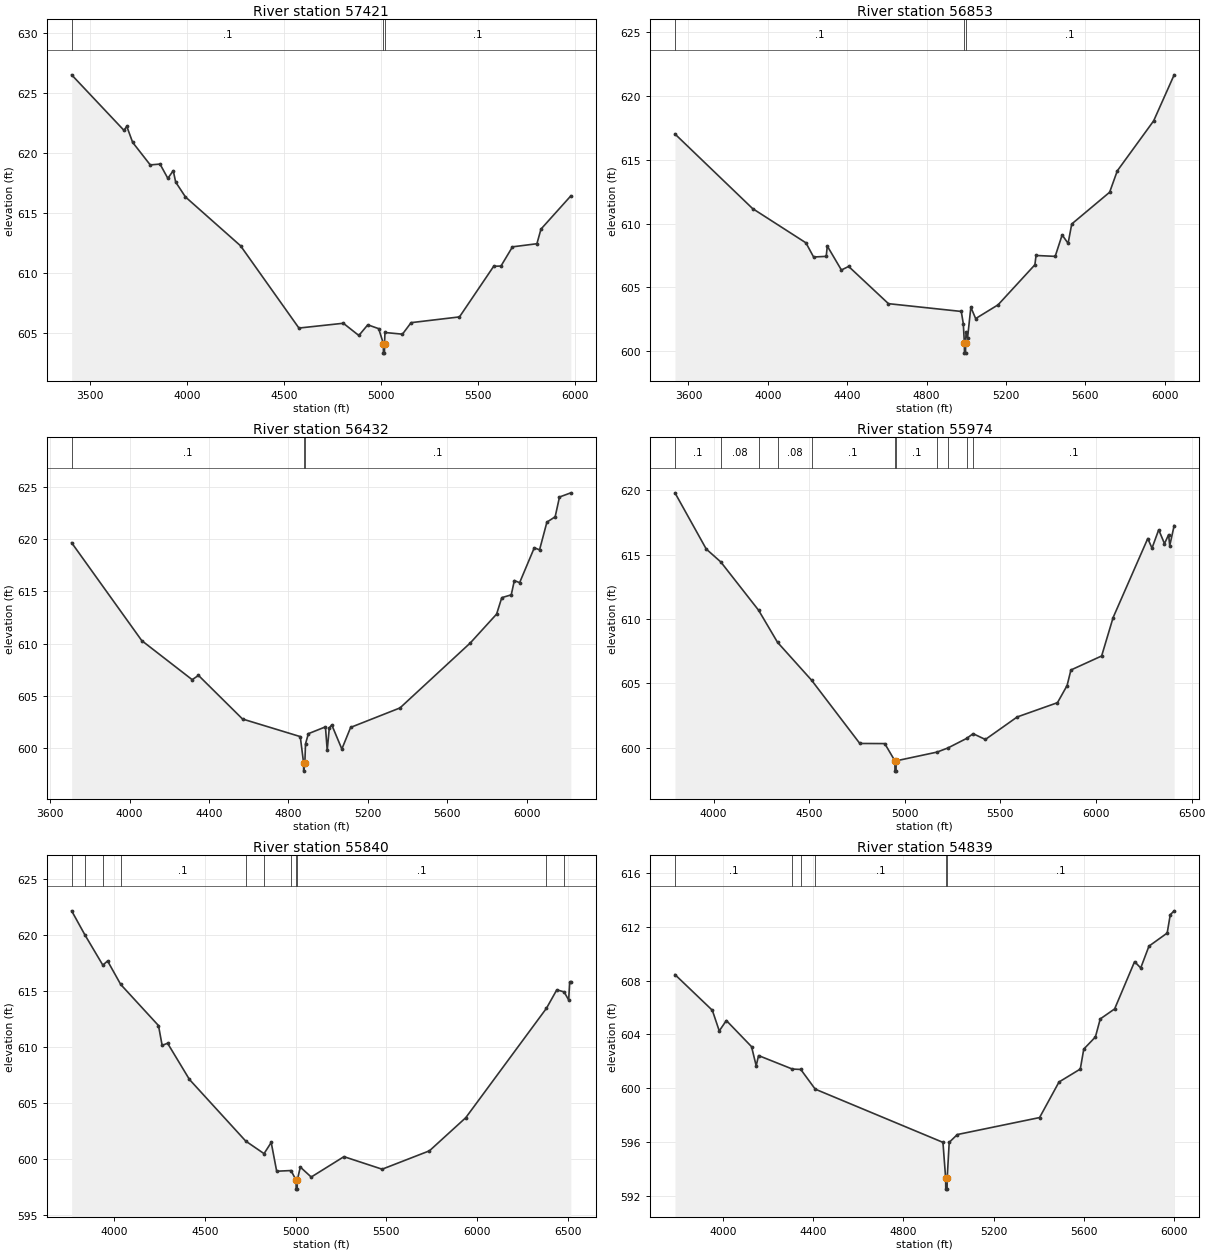
Type RM Length L Ch R = 1,57421,568,568,568
BEGIN DESCRIPTION:
Mapping XS ff009f09
END DESCRIPTION:
XS GIS Cut Line= 3
      2019986.88     13547808.26      2018775.93     13547951.49
      2017488.46     13548358.97
#Sta/Elev= 30
  3407.6  626.54  3677.1  621.91  3691.4  622.25  3721.7  620.91  3812.3  619.03
  3862.6  619.10  3902.9  617.91  3930.7  618.55  3943.2  617.60  3993.5  616.36
  4277.1  612.29  4577.6  605.43  4806.3  605.83  4886.1  604.81  4932.1  605.70
  4988.2  605.38  5012.2  604.14  5012.7  603.34  5017.9  603.34  5018.4  604.14
  5020.5  605.06  5110.5  604.92  5155.0  605.88  5404.1  606.36  5580.2  610.58
  5617.7  610.60  5676.9  612.20  5802.7  612.46  5823.7  613.68  5977.4  616.45
#Mann=3,-1,0
  3407.6     0.1       0  5012.2    0.07       0  5018.4     0.1       0
Bank Sta=5012.2,5018.4
Exp/Cntr=0.3,0.1

Type RM Length L Ch R = 1,56853,421,421,421
BEGIN DESCRIPTION:
Mapping XS d51d2fbb
END DESCRIPTION:
XS GIS Cut Line= 2
      2019583.20     13547274.42      2017249.09     13548211.53
#Sta/Elev= 30
  3531.9  617.03  3923.0  611.18  4191.9  608.49  4230.4  607.38  4294.0  607.43
  4299.4  608.24  4370.5  606.36  4407.0  606.64  4607.5  603.72  4974.4  603.11
  4984.7  602.15  4990.0  600.64  4990.5  599.84  4995.9  599.84  4996.4  600.64
  4998.6  601.48  5006.2  601.05  5022.7  603.44  5046.9  602.55  5159.9  603.63
  5345.4  606.77  5351.1  607.50  5447.6  607.43  5482.6  609.11  5512.7  608.45
  5531.0  609.97  5721.9  612.46  5760.6  614.14  5943.7  618.06  6047.1  621.67
#Mann=3,-1,0
  3531.9     0.1       0  4990.0    0.07       0  4996.4     0.1       0
Bank Sta=4990,4996.4
Exp/Cntr=0.3,0.1

Type RM Length L Ch R = 1,56432,458,458,458
BEGIN DESCRIPTION:
Mapping XS e50b2e90
END DESCRIPTION:
XS GIS Cut Line= 2
      2019327.10     13547109.49      2016940.00     13547899.40
#Sta/Elev= 30
  3708.3  619.65  4061.7  610.29  4315.5  606.56  4347.2  606.97  4569.2  602.80
  4859.9  601.12  4876.5  598.62  4877.0  597.82  4883.0  598.62  4886.3  600.43
  4900.8  601.40  4986.7  602.05  4995.6  599.81  5006.1  601.95  5018.5  602.24
  5069.3  599.93  5113.6  602.00  5362.1  603.86  5716.2  610.07  5848.8  612.83
  5874.8  614.40  5922.5  614.67  5938.2  616.04  5964.6  615.83  6038.6  619.17
  6065.1  618.97  6102.1  621.62  6143.7  622.13  6165.5  624.02  6222.7  624.42
#Mann=3,-1,0
  3708.3     0.1       0  4876.5    0.07       0  4883.0     0.1       0
Bank Sta=4876.5,4883
Exp/Cntr=0.3,0.1

Type RM Length L Ch R = 1,55974,134,134,134
BEGIN DESCRIPTION:
Mapping XS da22095e
END DESCRIPTION:
XS GIS Cut Line= 3
      2019288.13     13547031.35      2016909.61     13547235.34
      2016714.28     13547343.86
#Sta/Elev= 30
  3797.9  619.80  3961.6  615.43  4037.5  614.43  4235.5  610.67  4334.4  608.18
  4512.2  605.24  4764.6  600.32  4895.0  600.31  4948.1  598.97  4948.6  598.17
  4954.1  598.17  4954.6  598.97  5168.7  599.65  5225.2  599.97  5324.2  600.72
  5357.0  601.08  5421.2  600.63  5587.6  602.38  5798.3  603.49  5848.5  604.82
  5868.6  606.03  6029.2  607.12  6089.4  610.11  6270.5  616.25  6292.7  615.50
  6327.7  616.93  6357.9  615.85  6379.6  616.55  6385.3  615.69  6408.6  617.26
#Mann=11,-1,0
  3797.9     0.1       0  4037.5    0.08       0  4235.5    0.05       0
  4334.4    0.08       0  4512.2     0.1       0  4948.1    0.07       0
  4954.6     0.1       0  5168.7    0.08       0  5225.2    0.05       0
  5324.2    0.08       0  5357.0     0.1       0
Bank Sta=4948.1,4954.6
Exp/Cntr=0.3,0.1

Type RM Length L Ch R = 1,55840,1001,1001,1001
BEGIN DESCRIPTION:
Mapping XS 11b19643
END DESCRIPTION:
XS GIS Cut Line= 3
      2019322.77     13546931.52      2016783.74     13547079.09
      2016684.28     13547260.73
#Sta/Elev= 30
  3765.9  622.18  3839.1  620.03  3937.8  617.33  3964.0  617.70  4036.5  615.60
  4244.5  611.93  4264.5  610.16  4294.6  610.35  4414.8  607.12  4725.2  601.61
  4826.0  600.49  4865.5  601.49  4895.6  598.92  4974.7  598.98  5002.5  598.12
  5003.0  597.32  5008.5  597.32  5009.0  598.12  5025.8  599.29  5085.9  598.40
  5266.2  600.22  5476.6  599.10  5737.0  600.74  5937.3  603.70  6382.1  613.48
  6438.8  615.12  6479.0  614.94  6504.2  614.22  6509.9  615.78  6516.3  615.80
#Mann=11,-1,0
  3765.9    0.05       0  3839.1    0.08       0  3937.8    0.05       0
  4036.5     0.1       0  4725.2    0.05       0  4826.0    0.08       0
  4974.7     0.1       0  5002.5    0.07       0  5009.0     0.1       0
  6382.1    0.08       0  6479.0     0.1       0
Bank Sta=5002.5,5009
Exp/Cntr=0.3,0.1

Type RM Length L Ch R = 1,54839,868,868,868
BEGIN DESCRIPTION:
Mapping XS e1681b48
END DESCRIPTION:
XS GIS Cut Line= 3
      2018696.95     13546172.84      2017860.13     13546353.40
      2016708.69     13547071.32
#Sta/Elev= 30
  3787.9  608.44  3953.6  605.79  3984.3  604.26  4015.8  605.03  4127.5  603.09
  4148.0  601.67  4158.5  602.43  4308.3  601.43  4345.7  601.40  4409.6  599.94
  4975.9  595.99  4987.9  593.32  4988.4  592.52  4994.2  592.52  4994.7  593.32
  5003.6  595.99  5039.6  596.57  5404.2  597.83  5490.4  600.47  5584.7  601.43
  5600.1  602.91  5651.7  603.81  5673.2  605.15  5736.9  605.89  5825.4  609.40
  5852.6  608.93  5889.1  610.55  5969.9  611.52  5983.5  612.88  6000.9  613.17
#Mann=6,-1,0
  3787.9     0.1       0  4308.3    0.08       0  4345.7    0.05       0
  4409.6     0.1       0  4987.9    0.07       0  4994.7     0.1       0
Bank Sta=4987.9,4994.7
Exp/Cntr=0.3,0.1

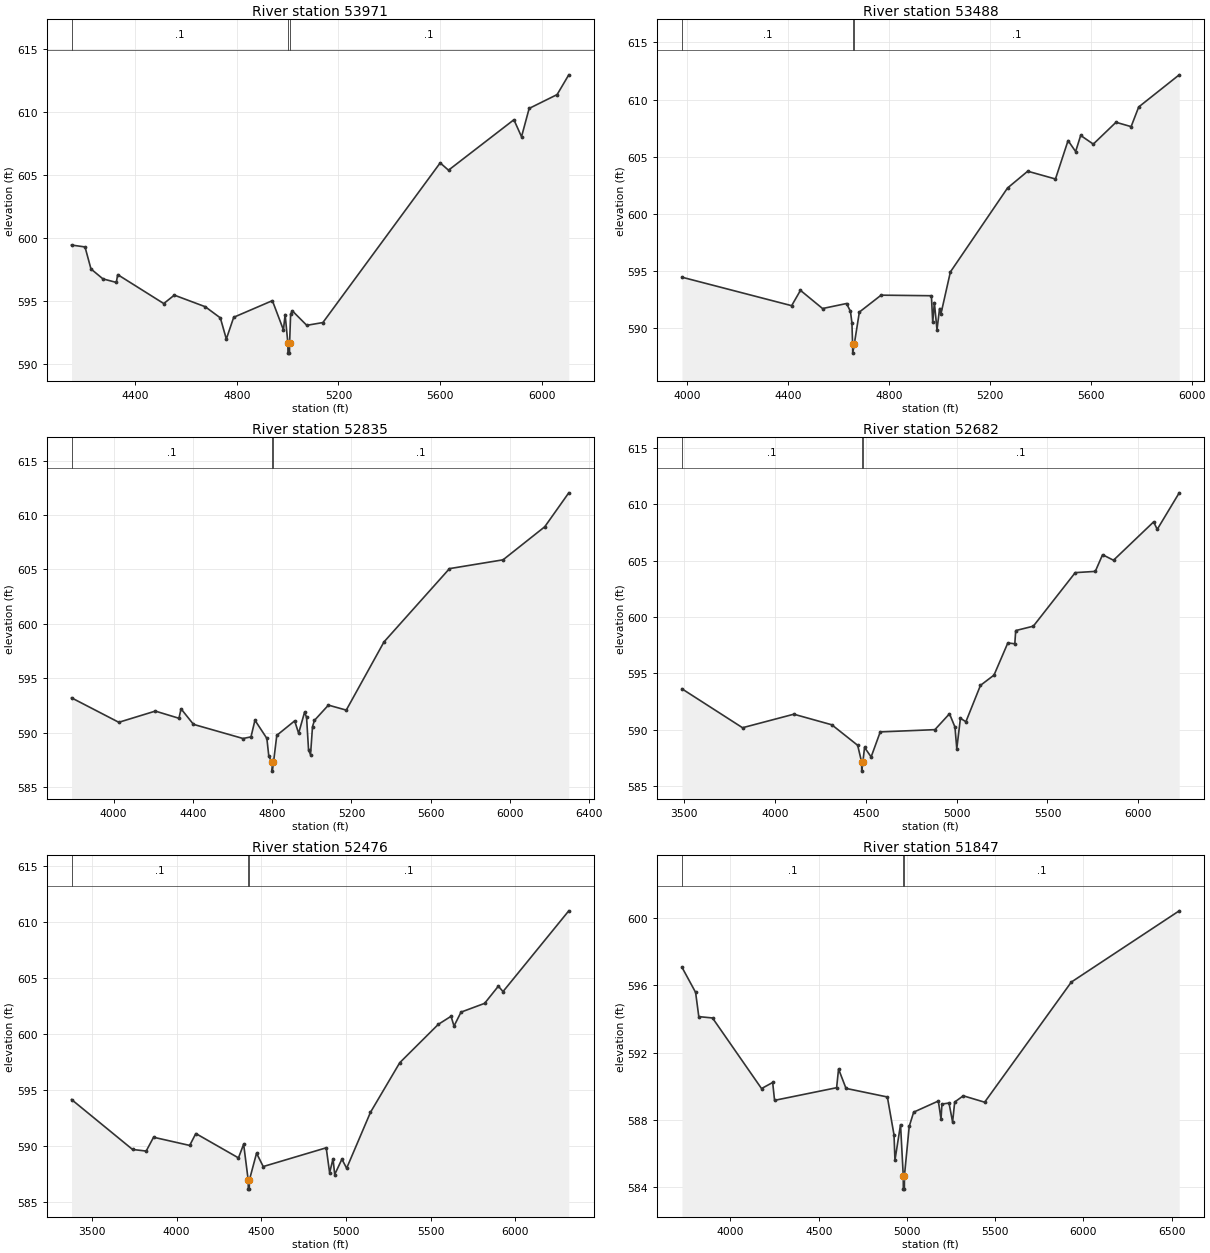
Type RM Length L Ch R = 1,53971,483,483,483
BEGIN DESCRIPTION:
Mapping XS 94fe9d37
END DESCRIPTION:
XS GIS Cut Line= 4
      2017788.94     13545789.17      2017059.78     13546101.66
      2016632.70     13546570.41      2016606.70     13547100.84
#Sta/Elev= 30
  4148.7  599.44  4201.8  599.29  4225.3  597.54  4272.5  596.75  4325.1  596.47
  4330.5  597.09  4512.0  594.79  4553.5  595.46  4675.2  594.54  4734.9  593.65
  4758.4  591.97  4787.5  593.70  4939.8  595.02  4983.3  592.70  4990.0  593.92
  5000.8  591.65  5001.3  590.85  5007.1  590.85  5007.6  591.65  5011.7  593.96
  5018.4  594.21  5075.2  593.06  5138.7  593.28  5600.7  605.97  5633.5  605.39
  5891.1  609.40  5921.1  608.05  5951.2  610.30  6061.3  611.40  6107.2  612.97
#Mann=3,-1,0
  4148.7     0.1       0  5000.8    0.07       0  5007.6     0.1       0
Bank Sta=5000.8,5007.6
Exp/Cntr=0.3,0.1

Type RM Length L Ch R = 1,53488,653,653,653
BEGIN DESCRIPTION:
Mapping XS 6cc60561
END DESCRIPTION:
XS GIS Cut Line= 4
      2017377.46     13545481.89      2016747.28     13545862.08
      2016601.45     13546325.62      2016575.41     13547075.65
#Sta/Elev= 30
  3978.4  594.46  4413.4  591.97  4448.4  593.31  4536.1  591.72  4631.2  592.16
  4646.7  591.47  4652.5  590.48  4655.2  588.62  4655.7  587.82  4662.0  588.62
  4682.0  591.41  4768.3  592.89  4967.8  592.84  4973.1  590.50  4979.5  592.24
  4990.0  589.87  5000.2  591.72  5005.5  591.24  5043.1  594.92  5269.7  602.26
  5349.8  603.73  5459.9  603.05  5509.9  606.41  5539.9  605.45  5559.9  606.86
  5609.9  606.10  5700.0  608.01  5760.0  607.63  5790.1  609.35  5950.8  612.16
#Mann=3,-1,0
  3978.4     0.1       0  4655.2    0.07       0  4662.0     0.1       0
Bank Sta=4655.2,4662
Exp/Cntr=0.3,0.1

Type RM Length L Ch R = 1,52835,153,153,153
BEGIN DESCRIPTION:
Mapping XS 9d22a1f8
END DESCRIPTION:
XS GIS Cut Line= 3
      2017262.93     13545174.57      2016455.62     13545424.58
      2016554.57     13547086.00
#Sta/Elev= 30
  3787.6  593.20  4026.2  590.95  4210.5  591.98  4329.8  591.32  4340.3  592.19
  4403.1  590.76  4653.2  589.46  4693.3  589.61  4713.3  591.14  4773.4  589.47
  4783.4  587.81  4800.1  587.26  4800.6  586.46  4806.9  587.26  4823.5  589.75
  4913.7  591.08  4933.7  589.94  4963.7  591.88  4973.8  591.41  4983.8  588.41
  4993.8  587.97  5003.8  590.56  5013.8  591.13  5084.0  592.53  5174.1  592.07
  5364.5  598.34  5695.0  605.08  5965.5  605.89  6175.9  608.93  6297.1  612.05
#Mann=3,-1,0
  3787.6     0.1       0  4800.1    0.07       0  4806.9     0.1       0
Bank Sta=4800.1,4806.9
Exp/Cntr=0.3,0.1

Type RM Length L Ch R = 1,52682,206,206,206
BEGIN DESCRIPTION:
Mapping XS f0a42ad6
END DESCRIPTION:
XS GIS Cut Line= 3
      2017283.73     13545054.79      2016320.20     13545351.66
      2016466.03     13547075.58
#Sta/Elev= 30
  3487.1  593.63  3820.6  590.18  4103.1  591.38  4312.4  590.44  4454.7  588.62
  4476.4  587.13  4476.9  586.33  4483.2  587.13  4492.5  588.43  4528.8  587.59
  4579.0  589.81  4880.0  590.01  4960.3  591.42  4990.4  590.24  5000.5  588.32
  5020.5  591.02  5050.6  590.71  5130.9  593.94  5205.5  594.85  5281.5  597.70
  5320.0  597.63  5325.0  598.80  5422.0  599.19  5652.8  603.94  5763.2  604.05
  5803.3  605.53  5863.5  605.04  6084.3  608.44  6104.4  607.78  6225.4  611.02
#Mann=3,-1,0
  3487.1     0.1       0  4476.4    0.07       0  4483.2     0.1       0
Bank Sta=4476.4,4483.2
Exp/Cntr=0.3,0.1

Type RM Length L Ch R = 1,52476,629,629,629
BEGIN DESCRIPTION:
Mapping XS 4651cef1
END DESCRIPTION:
XS GIS Cut Line= 4
      2017288.98     13544934.99      2016236.87     13545325.62
      2016163.95     13546054.79      2016434.58     13547100.86
#Sta/Elev= 30
  3379.8  594.17  3740.2  589.72  3820.6  589.58  3864.1  590.81  4077.4  590.08
  4113.6  591.14  4365.4  588.97  4395.9  590.19  4422.9  586.99  4423.4  586.19
  4429.2  586.19  4429.7  586.99  4472.1  589.39  4511.5  588.20  4883.4  589.87
  4903.5  587.65  4923.6  588.89  4933.6  587.49  4976.0  588.86  5004.0  588.05
  5144.7  593.03  5317.7  597.45  5545.0  600.86  5620.4  601.58  5637.9  600.71
  5679.3  601.95  5818.4  602.73  5899.6  604.26  5927.2  603.78  6315.4  610.97
#Mann=3,-1,0
  3379.8     0.1       0  4422.9    0.07       0  4429.7     0.1       0
Bank Sta=4422.9,4429.7
Exp/Cntr=0.3,0.1

Type RM Length L Ch R = 1,51847,284,284,284
BEGIN DESCRIPTION:
Mapping XS 51981297
END DESCRIPTION:
XS GIS Cut Line= 3
      2017377.45     13544846.47      2016070.20     13545325.62
      2015877.50     13546737.03
#Sta/Elev= 30
  3725.5  597.06  3802.7  595.57  3820.8  594.13  3898.5  594.05  4176.2  589.86
  4239.3  590.22  4250.0  589.16  4601.5  589.91  4612.5  591.02  4654.7  589.87
  4889.0  589.36  4926.7  587.11  4932.0  585.61  4963.6  587.72  4979.0  584.69
  4979.5  583.89  4985.3  583.89  4985.8  584.69  5012.9  587.62  5038.1  588.46
  5177.7  589.12  5193.0  588.04  5198.1  588.94  5238.3  589.00  5258.5  587.87
  5270.4  589.06  5319.0  589.43  5440.1  589.05  5931.0  596.18  6542.3  600.41
#Mann=3,-1,0
  3725.5     0.1       0  4979.0    0.07       0  4985.8     0.1       0
Bank Sta=4979,4985.8
Exp/Cntr=0.3,0.1

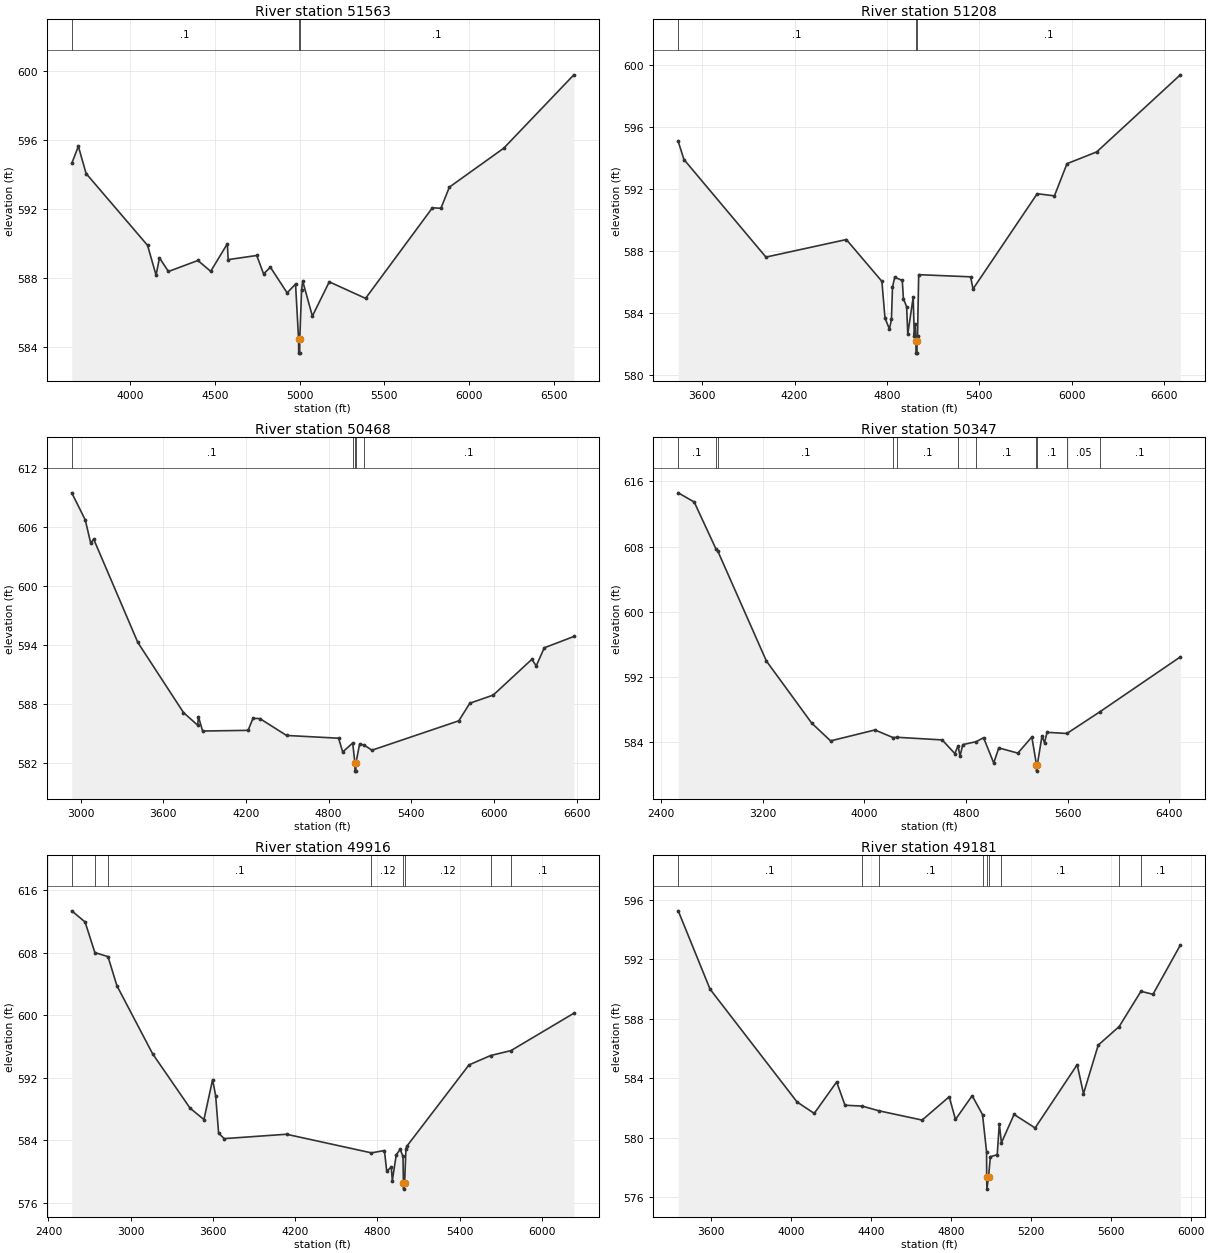
Type RM Length L Ch R = 1,51563,355,355,355
BEGIN DESCRIPTION:
Mapping XS 40b83028
END DESCRIPTION:
XS GIS Cut Line= 4
      2017288.97     13544825.62      2016148.33     13544955.83
      2015778.53     13545377.70      2015851.45     13546627.73
#Sta/Elev= 30
  3656.2  594.65  3695.1  595.64  3740.7  594.06  4103.1  589.89  4153.4  588.16
  4173.5  589.16  4226.4  588.37  4400.1  589.01  4475.5  588.38  4573.8  589.98
  4578.8  589.06  4747.2  589.30  4787.5  588.23  4827.6  588.62  4926.3  587.13
  4976.0  587.64  4994.0  584.43  4994.5  583.63  5000.4  583.63  5000.9  584.43
  5011.7  587.30  5018.3  587.81  5075.3  585.78  5174.9  587.77  5389.0  586.81
  5783.3  592.07  5833.3  592.04  5883.4  593.27  6204.0  595.53  6617.4  599.79
#Mann=3,-1,0
  3656.2     0.1       0  4994.0    0.07       0  5000.9     0.1       0
Bank Sta=4994,5000.9
Exp/Cntr=0.3,0.1

Type RM Length L Ch R = 1,51208,740,740,740
BEGIN DESCRIPTION:
Mapping XS 312a9c63
END DESCRIPTION:
XS GIS Cut Line= 4
      2017242.04     13544804.79      2015872.28     13544929.79
      2015570.20     13545211.04      2015835.83     13546658.98
#Sta/Elev= 30
  3444.9  595.05  3482.1  593.89  4014.3  587.61  4536.5  588.74  4767.4  586.05
  4787.5  583.68  4816.5  582.98  4829.4  583.60  4836.2  585.67  4850.4  586.31
  4899.7  586.11  4907.1  584.94  4928.1  584.41  4935.4  582.65  4970.6  585.03
  4977.9  582.55  4984.8  583.28  4988.6  582.23  4989.1  581.43  4995.0  581.43
  4995.5  582.23  4998.9  582.56  5006.3  586.48  5343.3  586.34  5359.1  585.56
  5776.0  591.69  5887.8  591.55  5969.1  593.62  6162.3  594.38  6705.2  599.34
#Mann=3,-1,0
  3444.9     0.1       0  4988.6    0.07       0  4995.5     0.1       0
Bank Sta=4988.6,4995.5
Exp/Cntr=0.3,0.1

Type RM Length L Ch R = 1,50468,121,121,121
BEGIN DESCRIPTION:
Mapping XS 01444b1b
END DESCRIPTION:
XS GIS Cut Line= 4
      2017383.74     13543896.34      2015502.49     13544606.87
      2015564.99     13546080.83      2015684.80     13546185.00
#Sta/Elev= 30
  2935.3  609.51  3033.0  606.76  3072.9  604.39  3094.3  604.80  3415.0  594.28
  3746.4  587.15  3849.6  585.86  3855.0  586.73  3885.3  585.27  4215.3  585.34
  4250.8  586.56  4300.5  586.54  4494.6  584.82  4872.2  584.54  4902.3  583.14
  4974.7  584.05  4991.0  581.99  4991.5  581.19  4997.4  581.19  4997.9  581.99
  5024.5  583.91  5054.3  583.87  5114.5  583.32  5745.1  586.31  5825.2  588.10
  5995.3  588.93  6275.6  592.57  6307.1  591.90  6365.7  593.74  6580.3  594.89
#Mann=5,-1,0
  2935.3     0.1       0  4974.7    0.07       0  4991.0    0.07       0
  4997.9    0.07       0  5054.3     0.1       0
Bank Sta=4991,4997.9
Exp/Cntr=0.3,0.1

Type RM Length L Ch R = 1,50347,431,431,431
BEGIN DESCRIPTION:
Mapping XS d0cab1f7
END DESCRIPTION:
XS GIS Cut Line= 4
      2017526.99     13543692.34      2015419.16     13544560.00
      2015419.16     13546002.70      2015580.29     13546169.03
#Sta/Elev= 30
  2534.4  614.60  2660.3  613.47  2831.4  607.72  2845.1  607.48  3228.6  593.97
  3585.5  586.35  3734.1  584.17  4083.3  585.51  4225.8  584.58  4259.0  584.61
  4612.8  584.29  4712.2  582.62  4738.3  583.55  4753.4  582.30  4775.1  583.71
  4881.5  584.08  4938.8  584.56  5018.8  581.46  5058.8  583.31  5208.8  582.67
  5318.8  584.65  5355.4  581.26  5355.9  580.46  5362.3  581.26  5398.8  584.77
  5418.8  583.95  5438.8  585.22  5595.1  585.08  5853.9  587.73  6488.1  594.47
#Mann=11,-1,0
  2534.4     0.1       0  2831.4    0.05       0  2845.1     0.1       0
  4225.8    0.05       0  4259.0     0.1       0  4738.3    0.07       0
  4881.5     0.1       0  5355.4    0.07       0  5362.3     0.1       0
  5595.1    0.05       0  5853.9     0.1       0
Bank Sta=5355.4,5362.3
Exp/Cntr=0.3,0.1

Type RM Length L Ch R = 1,49916,735,735,735
BEGIN DESCRIPTION:
Becerro Creek 70.0
END DESCRIPTION:
XS GIS Cut Line= 3
      2017435.83     13543661.96      2015288.95     13544481.87
      2014273.30     13545393.35
#Sta/Elev= 30
  2570.0  613.35  2667.2  611.92  2738.4  608.01  2834.4  607.49  2899.1  603.78
  3159.6  595.07  3433.0  588.11  3534.3  586.65  3597.4  591.76  3619.9  589.67
  3641.3  584.90  3682.2  584.21  4136.6  584.77  4756.1  582.39  4850.9  582.69
  4867.6  580.06  4901.1  580.56  4908.6  578.84  4937.0  582.12  4965.4  582.85
  4986.4  581.93  4989.4  578.55  4990.2  577.75  4998.3  578.55  5007.8  582.87
  5014.8  583.25  5467.8  593.64  5625.8  594.84  5774.2  595.47  6232.8  600.25
#Mann=8,-1,0
  2570.0     0.1       0  2738.4    0.05       0  2834.4     0.1       0
  4756.1    0.12       0  4989.4    0.07       0  4998.3    0.12       0
  5625.8    0.08       0  5774.2     0.1       0
Bank Sta=4989.4,4998.3
Exp/Cntr=0.3,0.1

Type RM Length L Ch R = 1,49181,392,392,392
BEGIN DESCRIPTION:
Becerro Creek 69.0
END DESCRIPTION:
XS GIS Cut Line= 3
      2016774.99     13543625.00      2015275.00     13544075.00
      2014375.02     13544374.99
#Sta/Elev= 30
  3433.8  595.27  3593.0  590.00  4028.9  582.40  4115.0  581.63  4227.3  583.75
  4269.0  582.18  4355.1  582.12  4440.3  581.80  4655.3  581.18  4791.0  582.75
  4822.4  581.22  4905.9  582.82  4957.8  581.55  4978.1  579.05  4978.8  577.33
  4979.7  576.53  4987.8  577.33  4997.2  578.71  5031.5  578.85  5042.0  580.93
  5052.5  579.65  5115.8  581.56  5221.2  580.65  5432.0  584.91  5463.6  582.96
  5537.4  586.23  5642.4  587.48  5751.3  589.85  5811.5  589.65  5948.5  592.96
#Mann=9,-1,0
  3433.8     0.1       0  4355.1    0.05       0  4440.3     0.1       0
  4957.8    0.12       0  4978.8    0.07       0  4987.8    0.12       0
  5052.5     0.1       0  5642.4    0.08       0  5751.3     0.1       0
Bank Sta=4978.8,4987.8
Exp/Cntr=0.3,0.1

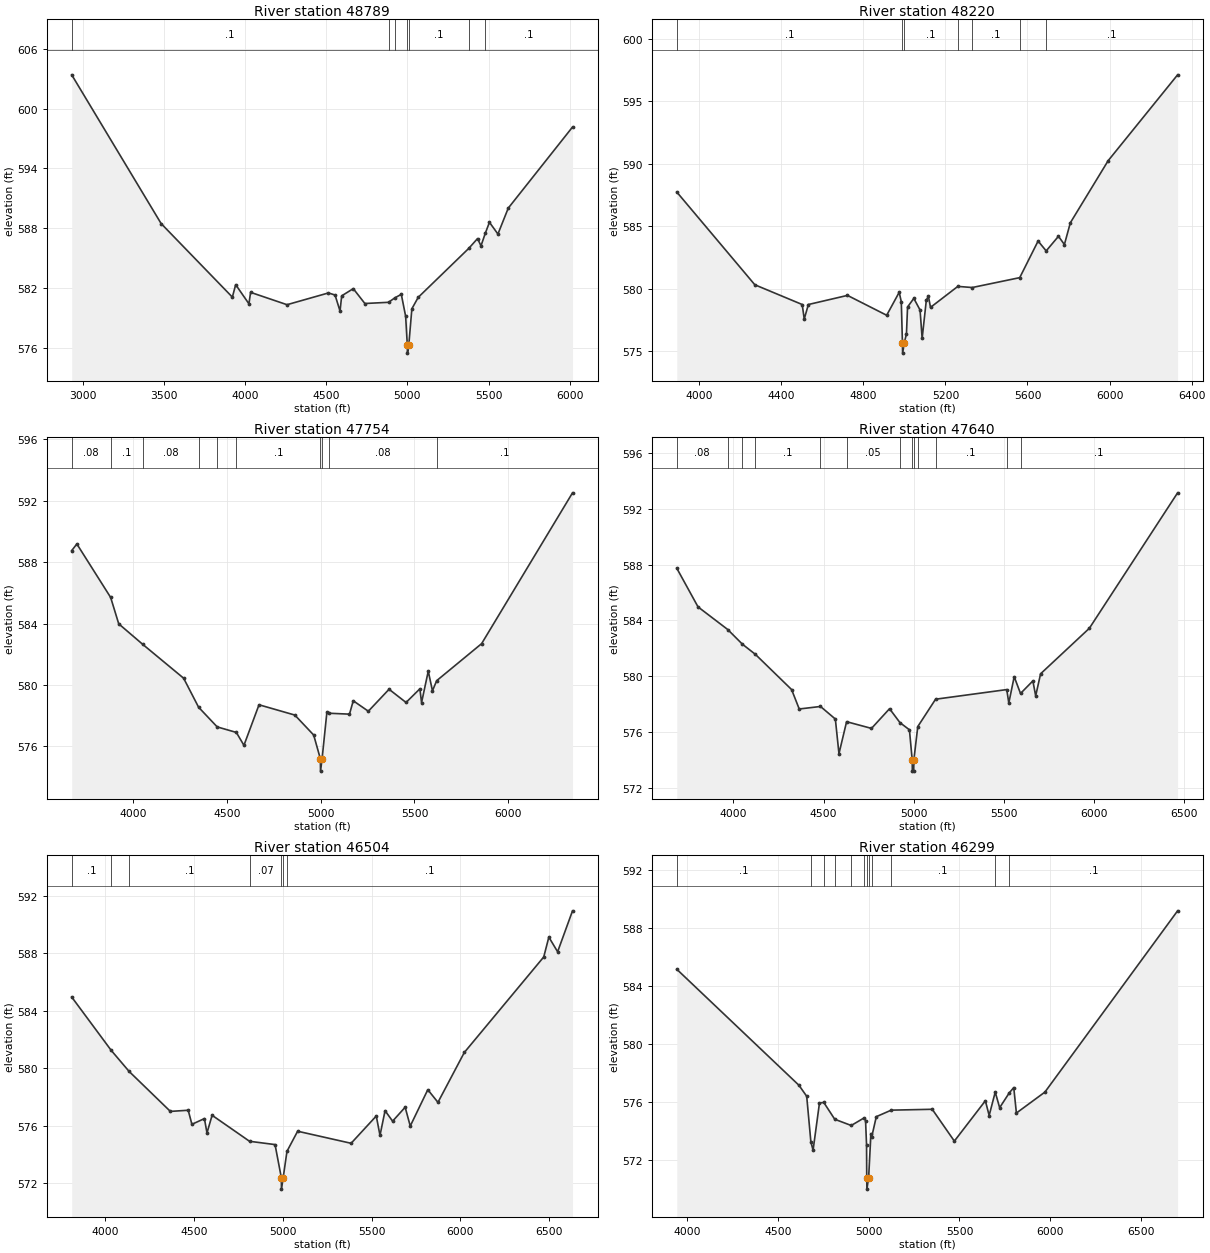
Type RM Length L Ch R = 1,48789,569,569,569
BEGIN DESCRIPTION:
Becerro Creek 68.0
END DESCRIPTION:
XS GIS Cut Line= 3
      2017025.00     13543425.00      2015025.00     13543825.00
      2014025.03     13544124.99
#Sta/Elev= 30
  2933.3  603.40  3484.0  588.47  3922.5  581.09  3942.9  582.34  4024.5  580.42
  4034.7  581.57  4259.0  580.33  4514.0  581.51  4554.8  581.30  4585.4  579.69
  4595.6  581.22  4667.0  581.94  4738.3  580.45  4884.0  580.57  4924.1  581.03
  4962.7  581.37  4989.4  579.17  4999.7  576.27  5000.6  575.47  5008.7  576.27
  5027.7  579.92  5066.9  581.07  5377.9  585.98  5432.3  586.97  5453.2  586.23
  5480.3  587.52  5505.4  588.60  5557.6  587.42  5621.1  590.02  6016.9  598.16
#Mann=7,-1,0
  2933.3     0.1       0  4884.0    0.07       0  4924.1     0.1       0
  4999.7    0.07       0  5008.7     0.1       0  5377.9    0.08       0
  5480.3     0.1       0
Bank Sta=4999.7,5008.7
Exp/Cntr=0.3,0.1

Type RM Length L Ch R = 1,48220,466,466,466
BEGIN DESCRIPTION:
Mapping XS 8458b8c0
END DESCRIPTION:
XS GIS Cut Line= 4
      2016294.16     13543268.33      2015309.78     13543346.45
      2014564.99     13543481.87      2014019.03     13543913.44
#Sta/Elev= 30
  3891.2  587.75  4271.5  580.33  4502.3  578.75  4512.3  577.59  4532.4  578.75
  4723.0  579.48  4914.0  577.89  4975.0  579.73  4985.2  578.97  4990.8  575.66
  4991.6  574.86  4999.9  575.66  5010.4  576.43  5015.7  578.55  5046.2  579.24
  5076.6  578.31  5086.8  576.04  5107.1  579.09  5117.2  579.42  5127.5  578.52
  5260.7  580.20  5330.9  580.11  5562.3  580.90  5651.8  583.83  5691.2  583.04
  5751.1  584.21  5780.0  583.55  5808.9  585.29  5993.2  590.26  6331.6  597.13
#Mann=7,-1,0
  3891.2     0.1       0  4990.8    0.07       0  4999.9     0.1       0
  5260.7    0.05       0  5330.9     0.1       0  5562.3    0.08       0
  5691.2     0.1       0
Bank Sta=4990.8,4999.9
Exp/Cntr=0.3,0.1

Type RM Length L Ch R = 1,47754,114,114,114
BEGIN DESCRIPTION:
Mapping XS 0cd3d9b8
END DESCRIPTION:
XS GIS Cut Line= 3
      2016408.78     13542877.70      2014596.24     13543039.16
      2013835.80     13543414.17
#Sta/Elev= 30
  3674.3  588.75  3701.7  589.18  3881.7  585.70  3924.8  583.98  4053.1  582.64
  4270.4  580.44  4350.2  578.55  4449.2  577.27  4551.2  576.91  4591.7  576.07
  4672.0  578.71  4862.8  578.04  4963.2  576.74  4998.8  575.19  4999.6  574.39
  5007.9  575.19  5033.4  578.21  5043.2  578.16  5153.9  578.10  5174.0  578.97
  5254.3  578.29  5364.7  579.72  5455.1  578.86  5528.9  579.75  5537.8  578.85
  5573.5  580.90  5595.8  579.62  5618.4  580.28  5857.7  582.69  6341.9  592.51
#Mann=10,-1,0
  3674.3    0.08       0  3881.7     0.1       0  4053.1    0.08       0
  4350.2    0.05       0  4449.2    0.08       0  4551.2     0.1       0
  4998.8    0.07       0  5007.9     0.1       0  5043.2    0.08       0
  5618.4     0.1       0
Bank Sta=4998.8,5007.9
Exp/Cntr=0.3,0.1

Type RM Length L Ch R = 1,47640,1136,1136,1136
BEGIN DESCRIPTION:
Mapping XS 7264527a
END DESCRIPTION:
XS GIS Cut Line= 3
      2016382.65     13542815.21      2014471.24     13542919.37
      2013731.66     13543362.08
#Sta/Elev= 30
  3686.2  587.74  3804.0  584.97  3968.7  583.35  4050.0  582.30  4122.1  581.57
  4322.7  579.05  4364.9  577.66  4482.8  577.84  4565.2  576.94  4585.2  574.46
  4627.5  576.75  4765.5  576.27  4865.6  577.68  4923.5  576.68  4975.8  576.17
  4991.2  574.01  4992.0  573.21  4999.5  573.21  5000.4  574.01  5022.1  576.40
  5120.8  578.36  5515.4  579.05  5526.6  578.09  5556.6  579.97  5591.6  578.77
  5660.1  579.67  5675.7  578.60  5702.9  580.18  5973.2  583.44  6462.4  593.14
#Mann=13,-1,0
  3686.2    0.08       0  3968.7     0.1       0  4050.0    0.05       0
  4122.1     0.1       0  4482.8    0.08       0  4627.5    0.05       0
  4923.5    0.08       0  4991.2    0.07       0  5000.4    0.08       0
  5022.1    0.05       0  5120.8     0.1       0  5515.4    0.08       0
  5591.6     0.1       0
Bank Sta=4991.2,5000.4
Exp/Cntr=0.3,0.1

Type RM Length L Ch R = 1,46504,205,205,205
BEGIN DESCRIPTION:
Mapping XS 924d7c14
END DESCRIPTION:
XS GIS Cut Line= 4
      2015981.67     13541559.99      2015314.99     13542086.04
      2014653.53     13542320.41      2013674.40     13543132.88
#Sta/Elev= 30
  3809.6  584.95  4032.1  581.24  4133.4  579.77  4365.8  576.99  4466.4  577.07
  4487.2  576.09  4557.7  576.49  4572.2  575.49  4601.1  576.72  4812.1  574.91
  4955.9  574.68  4991.3  572.38  4992.2  571.58  5001.8  572.38  5023.1  574.21
  5083.2  575.61  5384.7  574.77  5526.6  576.67  5547.5  575.32  5576.1  577.04
  5618.6  576.31  5689.4  577.28  5718.1  575.97  5817.0  578.50  5874.3  577.62
  6022.8  581.09  6470.7  587.74  6499.4  589.12  6548.9  588.10  6632.9  590.95
#Mann=7,-1,0
  3809.6     0.1       0  4032.1    0.07       0  4133.4     0.1       0
  4812.1    0.07       0  4991.3    0.07       0  5001.8    0.07       0
  5023.1     0.1       0
Bank Sta=4991.3,5001.8
Exp/Cntr=0.3,0.1

Type RM Length L Ch R = 1,46299,480,480,480
BEGIN DESCRIPTION:
Mapping XS 23e6addb
END DESCRIPTION:
XS GIS Cut Line= 4
      2015893.10     13541382.93      2015153.53     13542039.16
      2014674.37     13542231.87      2013669.14     13542981.89
#Sta/Elev= 30
  3942.5  585.17  4615.6  577.15  4658.3  576.39  4681.3  573.24  4693.4  572.66
  4728.7  575.93  4752.5  575.96  4812.8  574.80  4903.7  574.37  4974.0  574.89
  4982.6  574.71  4988.0  573.04  4989.1  570.77  4990.0  569.97  4999.6  570.77
  5012.2  573.81  5016.7  573.59  5041.8  574.98  5124.1  575.43  5350.0  575.49
  5471.8  573.29  5642.8  576.08  5663.6  575.06  5697.1  576.68  5721.4  575.60
  5774.7  576.63  5799.1  576.99  5813.7  575.23  5970.9  576.68  6701.9  589.21
#Mann=12,-1,0
  3942.5     0.1       0  4681.3    0.07       0  4752.5     0.1       0
  4812.8    0.07       0  4903.7     0.1       0  4974.0    0.07       0
  4989.1    0.07       0  4999.6    0.07       0  5016.7    0.12       0
  5124.1     0.1       0  5697.1    0.08       0  5774.7     0.1       0
Bank Sta=4989.1,4999.6
Exp/Cntr=0.3,0.1