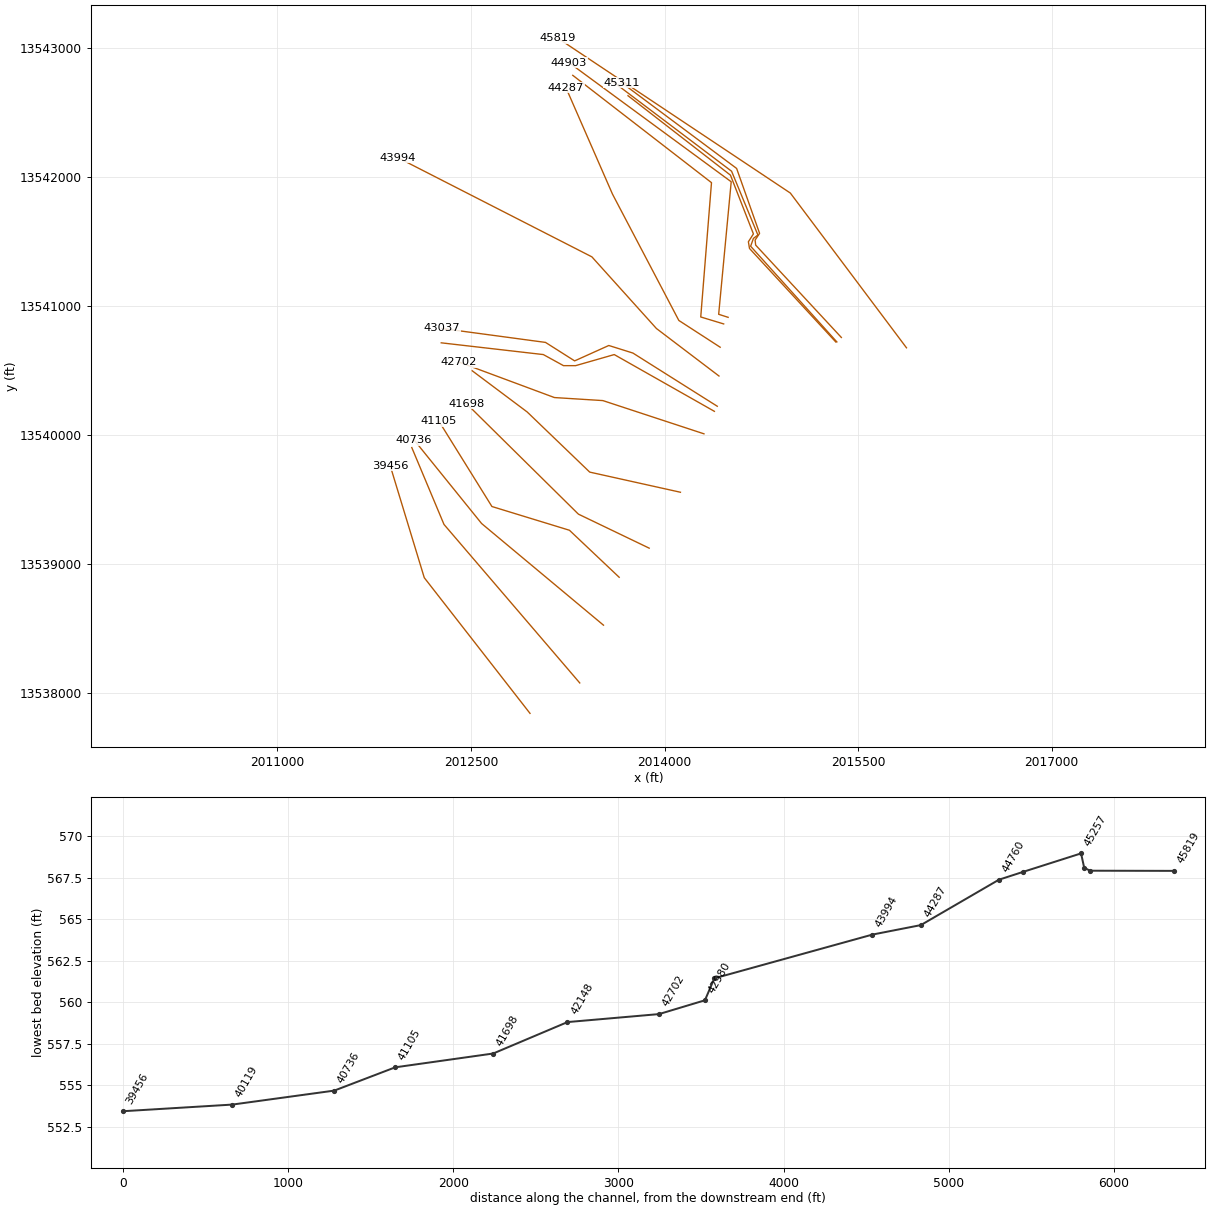
HEC-RAS study Becerro Creek.prj: Becerro Creek Base Level Engineering

--- Becerro Creek.g01 (geometry) --- (continued)

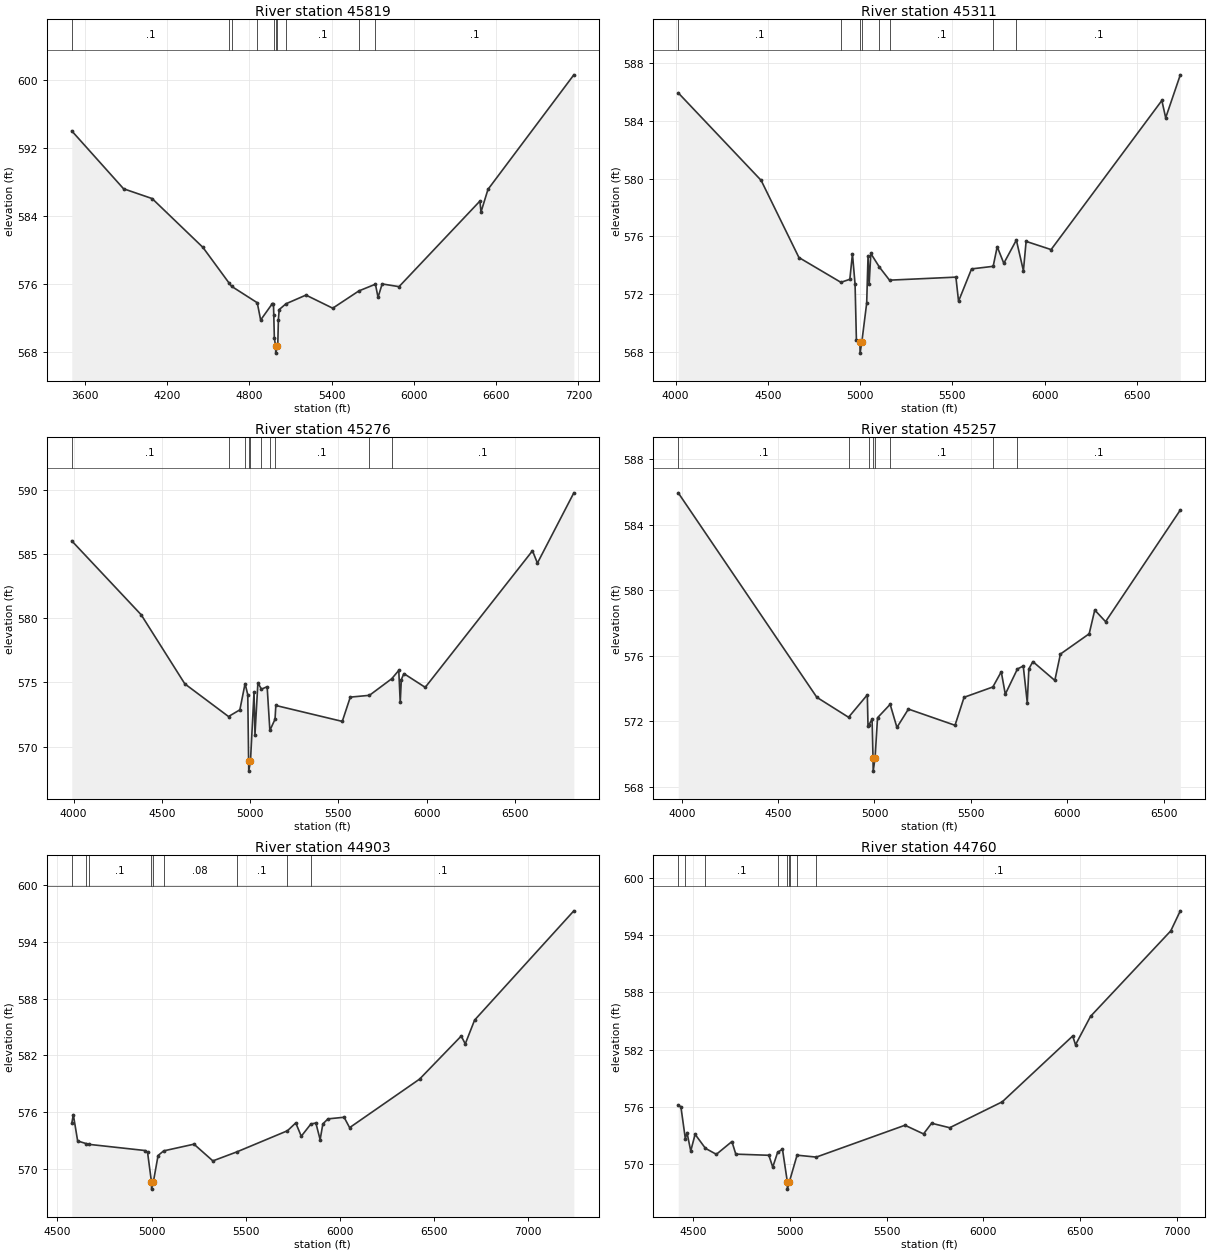
Type RM Length L Ch R = 1,45819,508,508,508
BEGIN DESCRIPTION:
Becerro Creek 63.0
END DESCRIPTION:
XS GIS Cut Line= 3
      2015874.97     13540675.03      2014975.00     13541875.00
      2013174.99     13543075.01
#Sta/Elev= 30
  3503.6  594.01  3881.7  587.21  4090.0  586.06  4460.8  580.32  4650.2  576.16
  4669.6  575.75  4857.0  573.82  4881.7  571.79  4967.1  573.72  4975.4  573.71
  4977.4  572.43  4981.7  569.69  4991.0  568.70  4991.8  567.90  5001.6  568.70
  5006.6  568.79  5011.1  571.83  5017.1  573.02  5066.7  573.70  5212.4  574.72
  5407.7  573.18  5598.5  575.21  5719.2  576.00  5738.2  574.45  5768.2  576.03
  5891.4  575.71  6481.8  585.77  6489.3  584.47  6540.4  587.14  7166.9  600.60
#Mann=10,-1,0
  3503.6     0.1       0  4650.2    0.05       0  4669.6     0.1       0
  4857.0    0.12       0  4977.4     0.1       0  4991.0    0.07       0
  5001.6     0.1       0  5066.7     0.1       0  5598.5    0.08       0
  5719.2     0.1       0
Bank Sta=4991,5001.6
Exp/Cntr=0.3,0.1

Type RM Length L Ch R = 1,45311,35,35,35
BEGIN DESCRIPTION:
Mapping XS e602b191
END DESCRIPTION:
XS GIS Cut Line= 6
      2015370.18     13540755.26      2014706.14     13541471.38
      2014701.80     13541510.44      2014736.52     13541562.53
      2014558.57     13542066.00      2013669.42     13542729.61
#Sta/Elev= 30
  4013.9  585.96  4463.4  579.89  4668.2  574.54  4895.8  572.82  4944.2  573.03
  4958.4  574.79  4972.6  572.69  4979.9  568.80  4998.9  568.71  4999.8  567.91
  5009.5  568.71  5035.6  571.38  5043.0  574.67  5049.0  572.70  5058.0  574.82
  5104.9  573.87  5159.4  572.97  5519.3  573.18  5533.6  571.51  5604.1  573.75
  5721.3  573.93  5743.2  575.29  5779.0  574.14  5847.0  575.75  5885.3  573.62
  5899.9  575.66  6035.4  575.09  6635.8  585.43  6656.6  584.23  6735.9  587.21
#Mann=8,-1,0
  4013.9     0.1       0  4895.8    0.07       0  4998.9    0.07       0
  5009.5    0.07       0  5104.9    0.12       0  5159.4     0.1       0
  5721.3    0.08       0  5847.0     0.1       0
Bank Sta=4998.9,5009.5
Exp/Cntr=0.3,0.1

Type RM Length L Ch R = 1,45276,19,19,19
BEGIN DESCRIPTION:
Mapping XS bda8c83f
END DESCRIPTION:
XS GIS Cut Line= 6
      2015335.50     13540720.49      2014667.08     13541462.70
      2014688.78     13541523.46      2014723.50     13541549.51
      2014519.51     13542044.30      2013560.32     13542769.12
#Sta/Elev= 30
  3990.0  586.01  4383.2  580.26  4630.6  574.88  4877.9  572.34  4942.2  572.86
  4971.7  574.90  4987.0  574.04  4991.8  568.89  4992.6  568.09  5002.4  568.89
  5022.5  574.24  5027.8  570.93  5044.4  574.96  5064.5  574.47  5096.8  574.66
  5112.2  571.26  5141.5  572.13  5146.0  573.20  5522.4  571.96  5567.8  573.85
  5676.3  573.99  5802.5  575.28  5842.4  575.93  5850.7  573.44  5857.0  575.22
  5871.5  575.68  5992.3  574.61  6599.9  585.24  6627.8  584.28  6834.2  589.75
#Mann=10,-1,0
  3990.0     0.1       0  4877.9    0.07       0  4971.7    0.12       0
  4991.8    0.07       0  5002.4    0.12       0  5064.5    0.07       0
  5112.2    0.12       0  5141.5     0.1       0  5676.3    0.08       0
  5802.5     0.1       0
Bank Sta=4991.8,5002.4
Exp/Cntr=0.3,0.1

Type RM Length L Ch R = 1,45257,354,354,354
BEGIN DESCRIPTION:
Mapping XS e16dbe1d
END DESCRIPTION:
XS GIS Cut Line= 6
      2015326.81     13540720.50      2014658.40     13541445.34
      2014649.71     13541497.42      2014688.78     13541558.19
      2014510.83     13542013.92      2013716.72     13542630.11
#Sta/Elev= 30
  3981.7  585.95  4700.9  573.46  4865.5  572.24  4962.9  573.61  4966.5  571.69
  4971.7  571.78  4987.6  572.13  4992.5  569.75  4993.3  568.95  5003.1  569.75
  5015.9  572.21  5081.4  573.03  5116.5  571.62  5176.2  572.74  5418.0  571.75
  5465.0  573.46  5614.3  574.09  5658.0  575.02  5678.9  573.65  5741.8  575.19
  5772.1  575.37  5792.9  573.13  5801.1  575.19  5821.9  575.64  5935.9  574.49
  5964.9  576.10  6114.2  577.34  6143.2  578.79  6199.3  578.08  6587.1  584.90
#Mann=8,-1,0
  3981.7     0.1       0  4865.5    0.07       0  4971.7    0.12       0
  4992.5    0.07       0  5003.1    0.12       0  5081.4     0.1       0
  5614.3    0.08       0  5741.8     0.1       0
Bank Sta=4992.5,5003.1
Exp/Cntr=0.3,0.1

Type RM Length L Ch R = 1,44903,143,143,143
BEGIN DESCRIPTION:
Mapping XS 1bb2ebef
END DESCRIPTION:
XS GIS Cut Line= 4
      2014492.76     13540911.38      2014419.39     13540934.92
      2014516.61     13541962.70      2013259.85     13542886.18
#Sta/Elev= 30
  4576.1  574.78  4584.3  575.72  4607.4  572.93  4651.2  572.66  4668.1  572.57
  4964.6  571.92  4978.9  571.74  4999.5  568.63  5000.3  567.83  5010.1  568.63
  5034.9  571.39  5064.6  571.88  5225.8  572.59  5326.2  570.82  5453.2  571.77
  5722.5  574.01  5766.8  574.84  5796.1  573.43  5847.4  574.73  5873.7  574.83
  5896.4  573.07  5910.9  574.74  5938.1  575.27  6023.8  575.44  6053.1  574.34
  6425.0  579.48  6646.4  584.04  6667.9  583.21  6717.5  585.73  7245.1  597.30
#Mann=9,-1,0
  4576.1     0.1       0  4651.2    0.08       0  4668.1     0.1       0
  4999.5    0.07       0  5010.1     0.1       0  5064.6    0.08       0
  5453.2     0.1       0  5722.5    0.08       0  5847.4     0.1       0
Bank Sta=4999.5,5010.1
Exp/Cntr=0.3,0.1

Type RM Length L Ch R = 1,44760,473,473,473
BEGIN DESCRIPTION:
Mapping XS 24b9db59
END DESCRIPTION:
XS GIS Cut Line= 4
      2014458.25     13540860.19      2014280.50     13540914.09
      2014363.84     13541955.76      2013288.72     13542788.10
#Sta/Elev= 30
  4425.3  576.18  4439.1  576.00  4461.9  572.66  4470.5  573.30  4489.9  571.37
  4512.3  573.12  4565.6  571.65  4622.0  571.02  4702.2  572.36  4722.3  571.04
  4892.9  570.92  4912.9  569.68  4938.1  571.23  4963.1  571.56  4987.9  568.17
  4988.7  567.37  4998.5  568.17  4999.5  568.20  5038.3  570.93  5137.5  570.73
  5595.1  574.07  5690.9  573.16  5732.5  574.28  5825.8  573.81  6097.2  576.53
  6460.5  583.43  6475.0  582.51  6552.5  585.49  6966.6  594.46  7015.7  596.56
#Mann=9,-1,0
  4425.3     0.1       0  4461.9    0.08       0  4565.6     0.1       0
  4938.1    0.12       0  4987.9    0.07       0  4998.5    0.12       0
  4999.5    0.08       0  5038.3    0.05       0  5137.5     0.1       0
Bank Sta=4987.9,4998.5
Exp/Cntr=0.3,0.1

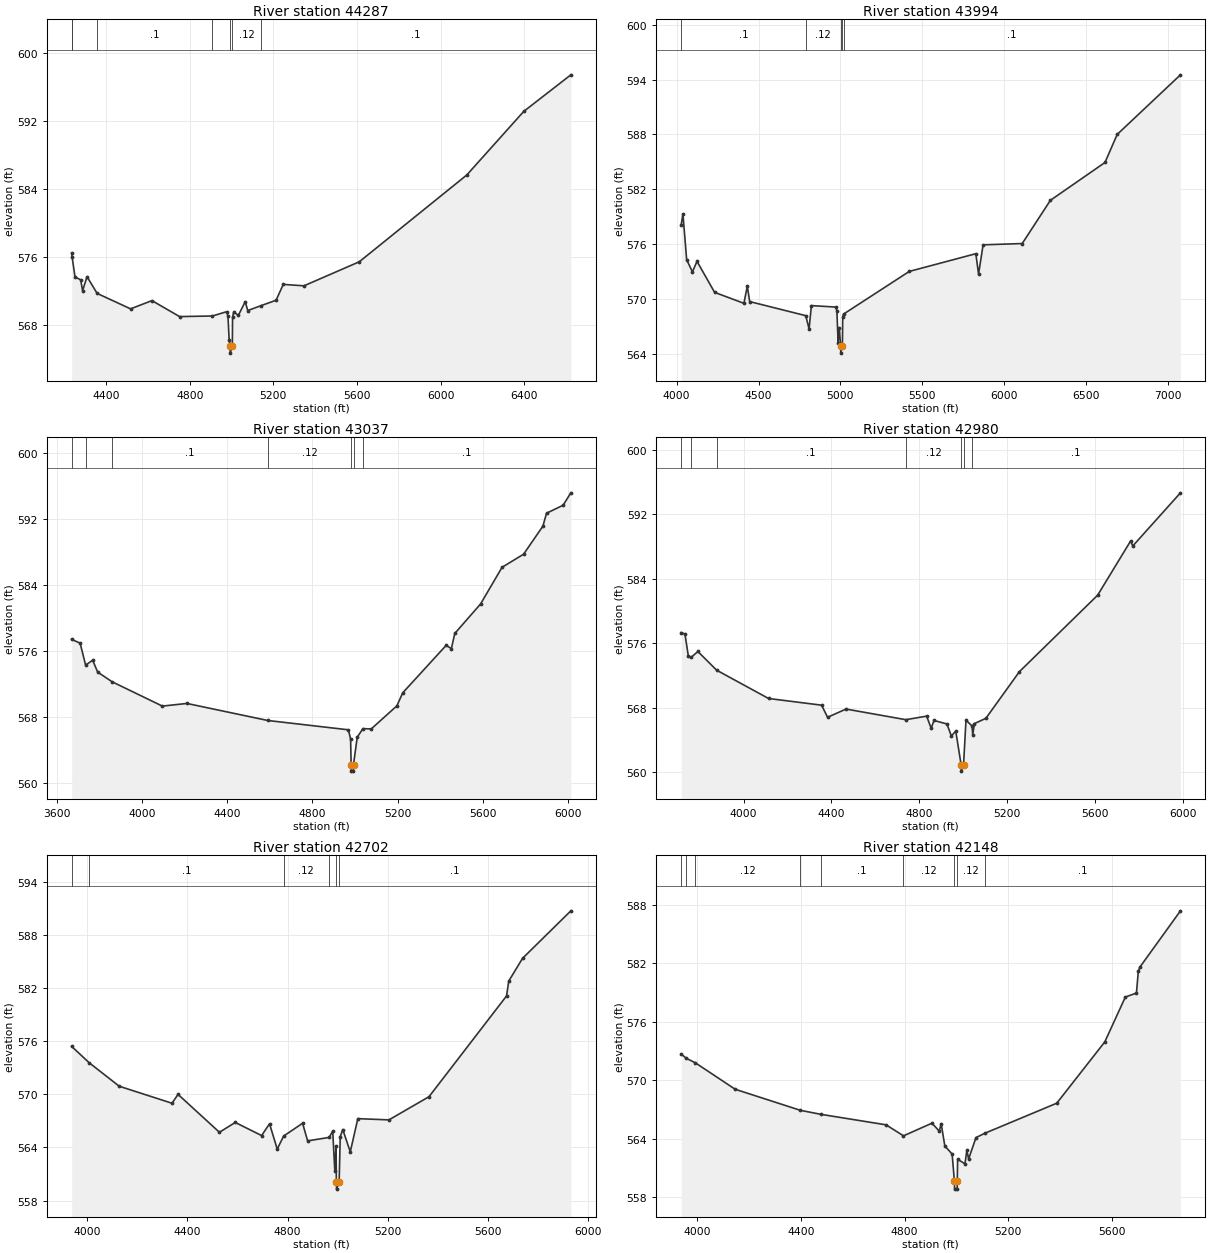
Type RM Length L Ch R = 1,44287,293,293,293
BEGIN DESCRIPTION:
Becerro Creek 60.0
END DESCRIPTION:
XS GIS Cut Line= 4
      2014431.10     13540679.56      2014110.65     13540887.18
      2013596.76     13541866.35      2013236.25     13542691.36
#Sta/Elev= 30
  4235.1  576.43  4237.4  575.96  4251.3  573.60  4278.4  573.27  4287.6  571.98
  4308.7  573.64  4357.0  571.67  4517.1  569.85  4619.2  570.82  4751.5  568.94
  4908.6  569.01  4975.9  569.51  4982.8  569.04  4988.5  566.24  4993.1  565.44
  4993.9  564.64  5003.8  565.44  5004.9  568.86  5010.5  569.49  5032.6  569.08
  5065.4  570.70  5077.5  569.65  5140.2  570.22  5213.0  570.86  5247.5  572.73
  5346.4  572.56  5611.1  575.39  6125.1  585.60  6397.9  593.09  6623.1  597.39
#Mann=7,-1,0
  4235.1     0.1       0  4237.4    0.08       0  4357.0     0.1       0
  4908.6    0.12       0  4993.1    0.07       0  5003.8    0.12       0
  5140.2     0.1       0
Bank Sta=4993.1,5003.8
Exp/Cntr=0.3,0.1

Type RM Length L Ch R = 1,43994,957,957,957
BEGIN DESCRIPTION:
Mapping XS efa424bf
END DESCRIPTION:
XS GIS Cut Line= 4
      2014421.78     13540456.28      2013937.04     13540824.68
      2013437.04     13541380.24      2011931.18     13542150.51
#Sta/Elev= 30
  4028.1  578.12  4038.6  579.29  4061.4  574.29  4096.7  572.96  4124.5  574.11
  4231.9  570.72  4410.8  569.52  4431.6  571.39  4446.1  569.71  4788.3  568.17
  4808.7  566.72  4822.9  569.27  4971.7  569.11  4978.4  568.71  4985.9  565.21
  4992.6  566.86  5001.4  564.87  5002.3  564.07  5012.1  564.87  5014.1  568.01
  5018.9  568.34  5420.4  573.01  5826.7  574.95  5843.3  572.72  5871.1  575.92
  6109.8  576.06  6281.9  580.79  6615.1  584.93  6689.6  588.00  7075.8  594.52
#Mann=5,-1,0
  4028.1     0.1       0  4788.3    0.12       0  5001.4    0.07       0
  5012.1    0.12       0  5018.9     0.1       0
Bank Sta=5001.4,5012.1
Exp/Cntr=0.3,0.1

Type RM Length L Ch R = 1,43037,57,57,57
BEGIN DESCRIPTION:
Becerro Creek 59.0
END DESCRIPTION:
XS GIS Cut Line= 6
      2014408.48     13540221.78      2013754.64     13540634.36
      2013568.01     13540692.95      2013303.25     13540573.59
      2013077.56     13540716.82      2012274.96     13540825.01
#Sta/Elev= 30
  3670.1  577.38  3709.9  576.93  3735.8  574.27  3768.8  574.86  3792.2  573.43
  3859.5  572.26  4095.9  569.31  4211.2  569.63  4590.3  567.57  4969.1  566.44
  4979.5  565.32  4982.0  562.24  4982.7  561.44  4992.3  561.44  4993.1  562.24
  5010.6  565.55  5037.4  566.58  5076.4  566.55  5196.7  569.34  5224.2  570.92
  5428.0  576.66  5452.5  576.27  5468.4  578.10  5589.5  581.67  5690.4  586.11
  5791.3  587.69  5882.1  591.09  5899.1  592.65  5976.9  593.62  6013.3  595.12
#Mann=7,-1,0
  3670.1     0.1       0  3735.8    0.08       0  3859.5     0.1       0
  4590.3    0.12       0  4982.0    0.07       0  4993.1    0.12       0
  5037.4     0.1       0
Bank Sta=4982,4993.1
Exp/Cntr=0.3,0.1

Type RM Length L Ch R = 1,42980,278,278,278
BEGIN DESCRIPTION:
Mapping XS 846d24d8
END DESCRIPTION:
XS GIS Cut Line= 6
      2014386.17     13540182.38      2013610.11     13540622.50
      2013310.63     13540536.56      2013216.88     13540536.56
      2013060.63     13540622.50      2012269.50     13540713.58
#Sta/Elev= 30
  3716.1  577.30  3733.1  577.13  3748.8  574.36  3762.8  574.26  3791.9  574.96
  3877.4  572.64  4113.7  569.13  4355.0  568.30  4382.3  566.80  4466.4  567.82
  4738.5  566.50  4833.2  566.94  4853.8  565.45  4867.0  566.40  4925.8  565.97
  4945.8  564.47  4965.8  565.10  4990.2  560.92  4991.0  560.12  5001.3  560.92
  5012.4  566.44  5039.7  565.73  5043.2  564.61  5050.3  566.01  5102.9  566.67
  5255.6  572.46  5611.6  581.94  5761.6  588.66  5771.7  588.05  5988.6  594.64
#Mann=7,-1,0
  3716.1     0.1       0  3762.8    0.08       0  3877.4     0.1       0
  4738.5    0.12       0  4990.2    0.07       0  5001.3    0.12       0
  5039.7     0.1       0
Bank Sta=4990.2,5001.3
Exp/Cntr=0.3,0.1

Type RM Length L Ch R = 1,42702,554,554,554
BEGIN DESCRIPTION:
Mapping XS 35a1c5dc
END DESCRIPTION:
XS GIS Cut Line= 4
      2014305.44     13540007.91      2013521.57     13540265.72
      2013146.57     13540289.16      2012404.36     13540565.21
#Sta/Elev= 30
  3937.6  575.41  4007.4  573.57  4127.6  570.91  4338.1  568.99  4362.4  569.99
  4527.6  565.71  4590.7  566.82  4696.0  565.34  4727.6  566.67  4758.3  563.81
  4783.8  565.28  4859.5  566.73  4879.6  564.74  4965.4  565.13  4979.8  565.83
  4988.2  561.33  4993.2  564.19  4994.3  560.09  4995.0  559.29  5005.4  560.09
  5009.8  565.22  5019.9  566.02  5049.9  563.50  5080.0  567.25  5204.2  567.11
  5364.2  569.73  5673.7  581.11  5682.5  582.79  5737.7  585.36  5930.4  590.72
#Mann=6,-1,0
  3937.6    0.08       0  4007.4     0.1       0  4783.8    0.12       0
  4965.4     0.1       0  4994.3    0.07       0  5005.4     0.1       0
Bank Sta=4994.3,5005.4
Exp/Cntr=0.3,0.1

Type RM Length L Ch R = 1,42148,450,450,450
BEGIN DESCRIPTION:
Mapping XS bb58d368
END DESCRIPTION:
XS GIS Cut Line= 4
      2014123.16     13539554.78      2013420.01     13539711.04
      2012935.63     13540177.18      2012509.27     13540496.95
#Sta/Elev= 30
  3938.3  572.68  3957.8  572.24  3992.1  571.79  4146.6  569.06  4397.9  566.90
  4476.7  566.49  4728.6  565.41  4795.6  564.28  4905.4  565.58  4933.7  564.76
  4940.9  565.54  4955.0  563.24  4983.3  562.41  4991.9  559.61  4992.6  558.81
  5002.4  558.81  5003.1  559.61  5004.4  561.87  5032.7  561.41  5039.9  562.78
  5046.9  561.92  5075.2  564.10  5109.7  564.55  5386.7  567.63  5572.1  573.93
  5651.3  578.53  5694.1  578.94  5701.3  581.19  5707.6  581.61  5863.8  587.38
#Mann=9,-1,0
  3938.3     0.1       0  3957.8    0.07       0  3992.1    0.12       0
  4397.9    0.07       0  4476.7     0.1       0  4795.6    0.12       0
  4991.9    0.07       0  5003.1    0.12       0  5109.7     0.1       0
Bank Sta=4991.9,5003.1
Exp/Cntr=0.3,0.1

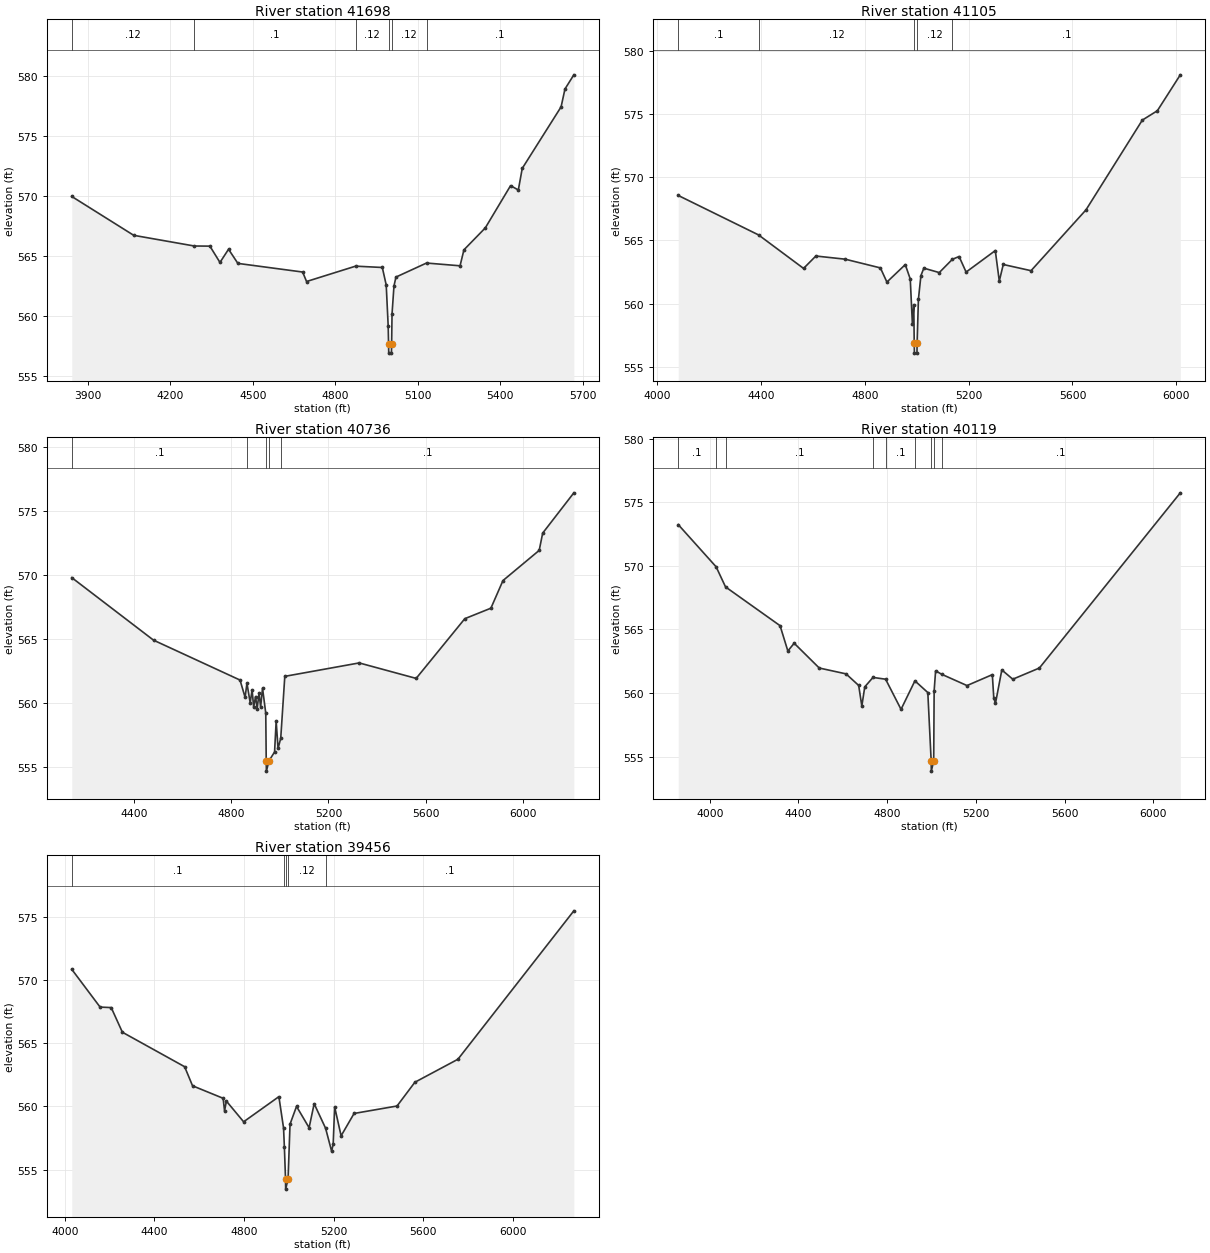
Type RM Length L Ch R = 1,41698,593,593,593
BEGIN DESCRIPTION:
Mapping XS f8e236c1
END DESCRIPTION:
XS GIS Cut Line= 3
      2013880.96     13539121.18      2013332.33     13539385.08
      2012465.68     13540241.33
#Sta/Elev= 30
  3840.8  569.98  4066.3  566.74  4286.7  565.85  4343.4  565.84  4380.1  564.48
  4411.3  565.58  4445.3  564.40  4681.0  563.68  4695.2  562.89  4873.6  564.17
  4970.9  564.06  4985.1  562.60  4992.2  559.22  4993.6  557.72  4994.3  556.92
  5004.1  556.92  5004.8  557.72  5006.3  560.20  5013.3  562.51  5020.5  563.26
  5131.7  564.43  5253.8  564.20  5267.9  565.53  5345.7  567.36  5437.6  570.88
  5465.9  570.52  5480.1  572.32  5621.5  577.45  5635.6  578.94  5667.9  580.12
#Mann=6,-1,0
  3840.8    0.12       0  4286.7     0.1       0  4873.6    0.12       0
  4993.6    0.07       0  5004.8    0.12       0  5131.7     0.1       0
Bank Sta=4993.6,5004.8
Exp/Cntr=0.3,0.1

Type RM Length L Ch R = 1,41105,369,369,369
BEGIN DESCRIPTION:
Mapping XS 04b9427f
END DESCRIPTION:
XS GIS Cut Line= 4
      2013648.31     13538895.49      2013262.89     13539260.08
      2012662.19     13539444.11      2012252.47     13540103.84
#Sta/Elev= 30
  4080.3  568.56  4389.8  565.44  4563.4  562.79  4610.8  563.77  4723.7  563.52
  4859.6  562.83  4884.7  561.71  4955.5  563.09  4974.7  561.95  4983.0  558.36
  4988.2  559.93  4990.0  556.89  4990.7  556.09  5000.5  556.09  5001.2  556.89
  5006.1  560.34  5015.8  562.22  5027.0  562.81  5086.5  562.46  5137.0  563.51
  5162.9  563.73  5190.0  562.50  5302.5  564.20  5317.9  561.79  5333.2  563.10
  5440.3  562.61  5652.1  567.42  5869.3  574.52  5927.2  575.26  6015.7  578.10
#Mann=5,-1,0
  4080.3     0.1       0  4389.8    0.12       0  4990.0    0.07       0
  5001.2    0.12       0  5137.0     0.1       0
Bank Sta=4990,5001.2
Exp/Cntr=0.3,0.1

Type RM Length L Ch R = 1,40736,617,617,617
BEGIN DESCRIPTION:
Mapping XS 3cb38362
END DESCRIPTION:
XS GIS Cut Line= 3
      2013526.77     13538523.98      2012582.33     13539312.17
      2012059.59     13539959.54
#Sta/Elev= 30
  4145.6  569.82  4481.4  564.93  4836.7  561.81  4857.5  560.46  4865.1  561.56
  4878.4  560.04  4886.2  561.04  4892.7  559.70  4900.5  560.52  4907.0  559.58
  4914.8  560.77  4921.3  559.71  4929.1  561.18  4942.4  559.22  4944.3  555.49
  4945.0  554.69  4955.5  555.49  4978.6  556.19  4985.1  558.60  4992.9  556.46
  5003.9  557.26  5020.6  562.10  5326.1  563.15  5560.1  561.94  5760.0  566.61
  5867.1  567.43  5916.7  569.59  6065.5  571.95  6079.8  573.30  6207.8  576.45
#Mann=5,-1,0
  4145.6     0.1       0  4865.1    0.12       0  4944.3    0.07       0
  4955.5    0.12       0  5003.9     0.1       0
Bank Sta=4944.3,4955.5
Exp/Cntr=0.3,0.1

Type RM Length L Ch R = 1,40119,663,663,663
BEGIN DESCRIPTION:
Mapping XS 49b6f741
END DESCRIPTION:
XS GIS Cut Line= 3
      2013342.77     13538076.03      2012290.67     13539305.22
      2012041.17     13539901.24
#Sta/Elev= 30
  3857.8  573.24  4028.7  569.92  4071.1  568.34  4317.0  565.29  4352.1  563.30
  4380.6  563.91  4493.7  561.96  4614.5  561.50  4671.5  560.59  4685.7  558.97
  4699.0  560.48  4736.1  561.22  4792.9  561.08  4862.5  558.71  4925.1  560.95
  4983.3  560.03  4998.4  554.65  4999.1  553.85  5009.8  554.65  5011.8  560.16
  5018.4  561.74  5045.6  561.47  5160.0  560.58  5274.2  561.44  5280.7  559.61
  5288.4  559.18  5317.0  561.81  5366.4  561.08  5486.4  561.96  6121.9  575.74
#Mann=9,-1,0
  3857.8     0.1       0  4028.7    0.05       0  4071.1     0.1       0
  4736.1    0.12       0  4792.9     0.1       0  4925.1    0.12       0
  4998.4    0.07       0  5009.8    0.12       0  5045.6     0.1       0
Bank Sta=4998.4,5009.8
Exp/Cntr=0.3,0.1

Type RM Length L Ch R = 1,39456,810,810,810
BEGIN DESCRIPTION:
Mapping XS 921ea2e0
END DESCRIPTION:
XS GIS Cut Line= 3
      2012957.36     13537839.91      2012137.89     13538892.03
      2011874.02     13539760.00
#Sta/Elev= 30
  4030.8  570.85  4157.2  567.86  4206.9  567.82  4256.7  565.87  4534.5  563.14
  4569.8  561.63  4706.4  560.64  4712.7  559.64  4720.8  560.42  4797.8  558.78
  4955.2  560.77  4976.0  558.29  4979.7  556.78  4984.8  554.25  4985.4  553.45
  4996.2  554.25  5004.9  558.59  5033.9  560.00  5090.0  558.31  5112.6  560.21
  5163.6  558.27  5190.7  556.44  5197.6  557.04  5204.0  559.96  5232.9  557.67
  5290.8  559.44  5482.5  560.03  5562.1  561.91  5754.2  563.73  6271.6  575.48
#Mann=5,-1,0
  4030.8     0.1       0  4979.7    0.12       0  4984.8    0.07       0
  4996.2    0.12       0  5163.6     0.1       0
Bank Sta=4984.8,4996.2
Exp/Cntr=0.3,0.1