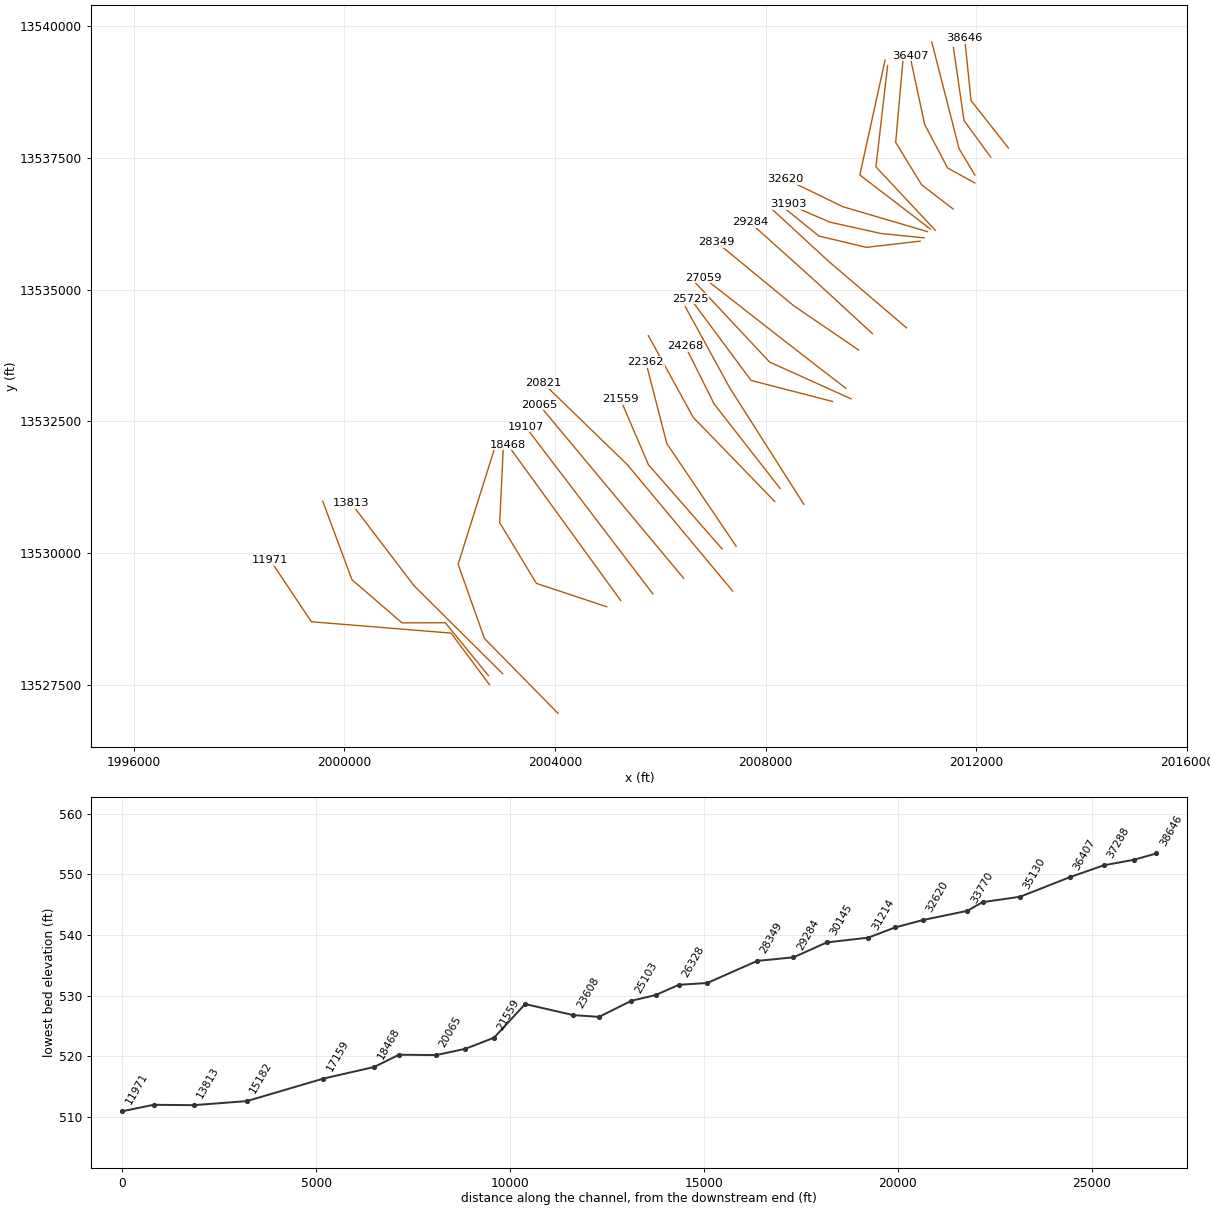
HEC-RAS study Becerro Creek.prj: Becerro Creek Base Level Engineering

--- Becerro Creek.g01 (geometry) --- (continued)

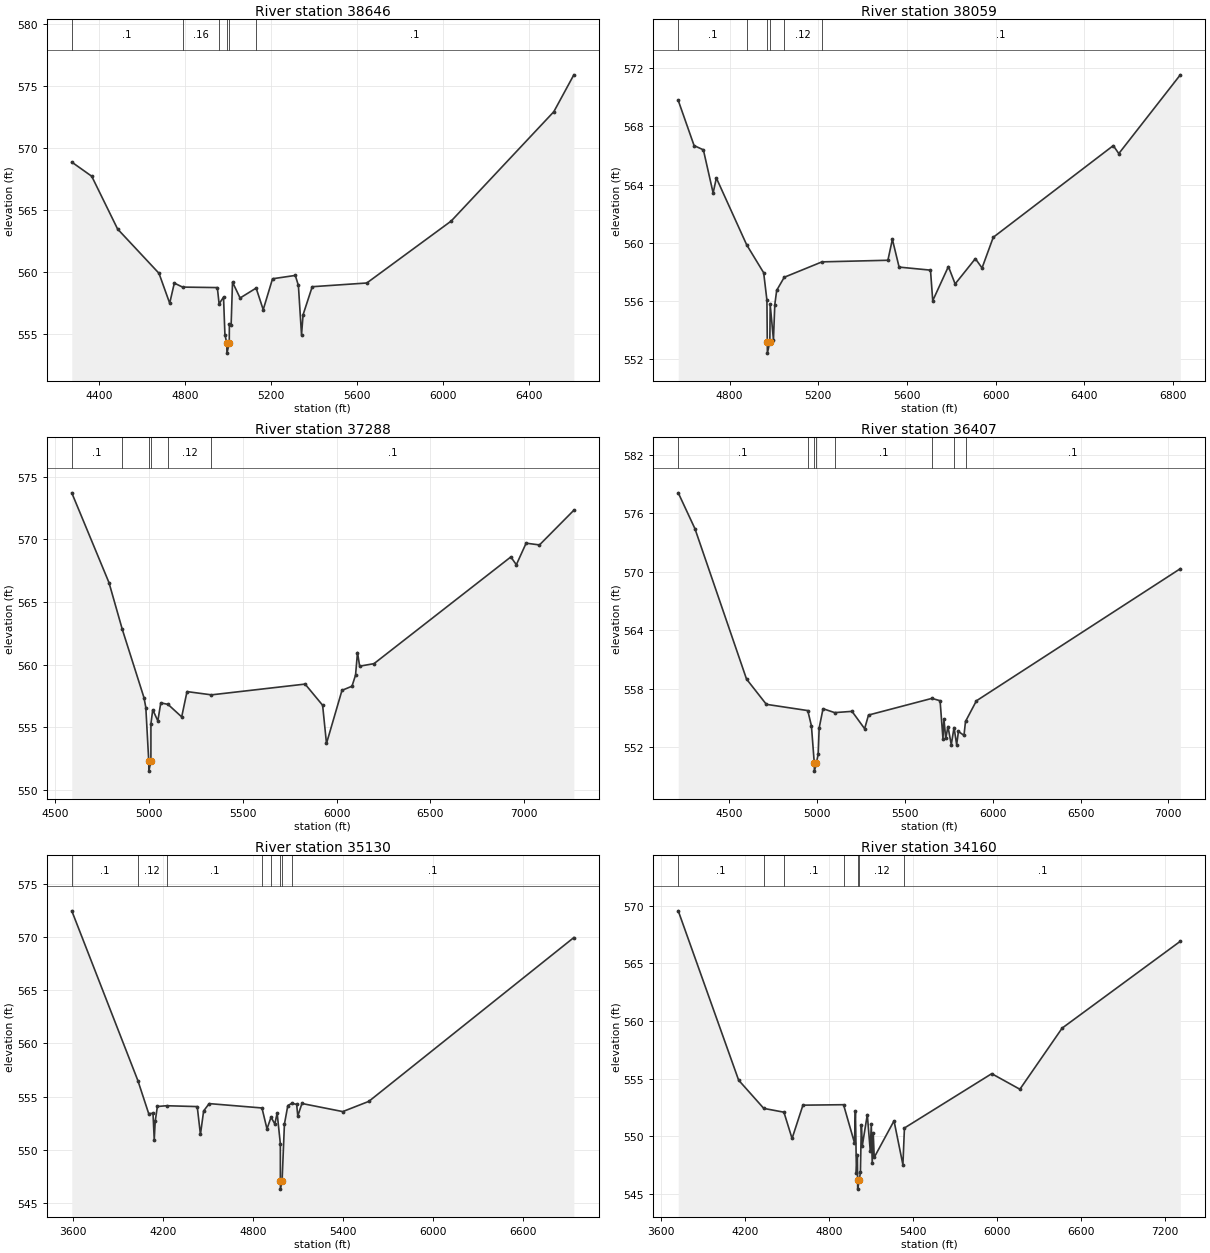
Type RM Length L Ch R = 1,38646,587,587,587
BEGIN DESCRIPTION:
Mapping XS b5395038
END DESCRIPTION:
XS GIS Cut Line= 3
      2012610.08     13537690.68      2011901.78     13538589.94
      2011780.45     13539772.02
#Sta/Elev= 30
  4273.9  568.85  4366.6  567.71  4486.8  563.46  4679.2  559.89  4728.9  557.48
  4750.4  559.10  4788.8  558.78  4950.3  558.74  4958.5  557.43  4979.1  557.97
  4985.5  554.96  4994.2  554.26  4994.9  553.46  5005.7  554.26  5006.3  555.83
  5014.4  555.72  5020.8  559.18  5056.0  557.90  5130.6  558.70  5163.5  556.96
  5206.8  559.45  5312.6  559.72  5327.0  558.91  5341.5  554.92  5348.7  556.55
  5391.2  558.81  5644.9  559.11  6036.9  564.10  6513.9  572.91  6606.9  575.88
#Mann=6,-1,0
  4273.9     0.1       0  4788.8    0.16       0  4958.5    0.12       0
  4994.2    0.07       0  5005.7    0.12       0  5130.6     0.1       0
Bank Sta=4994.2,5005.7
Exp/Cntr=0.3,0.1

Type RM Length L Ch R = 1,38059,771,771,771
BEGIN DESCRIPTION:
Mapping XS a5a9dd38
END DESCRIPTION:
XS GIS Cut Line= 3
      2012275.05     13537516.14      2011768.10     13538210.60
      2011566.71     13539599.46
#Sta/Elev= 30
  4568.7  569.79  4640.2  566.68  4682.0  566.39  4726.0  563.42  4740.6  564.45
  4877.3  559.85  4953.8  557.93  4968.5  556.04  4970.1  553.20  4970.7  552.40
  4981.6  553.20  4983.2  555.75  4997.9  553.32  5004.0  555.74  5012.5  556.72
  5046.6  557.62  5216.8  558.68  5513.8  558.79  5534.0  560.23  5564.3  558.32
  5705.8  558.11  5715.9  556.01  5786.6  558.36  5816.9  557.16  5908.0  558.90
  5938.2  558.26  5988.7  560.37  6529.8  566.68  6554.6  566.13  6831.9  571.55
#Mann=6,-1,0
  4568.7     0.1       0  4877.3    0.16       0  4970.1    0.07       0
  4981.6    0.16       0  5046.6    0.12       0  5216.8     0.1       0
Bank Sta=4970.1,4981.6
Exp/Cntr=0.3,0.1

Type RM Length L Ch R = 1,37288,881,881,881
BEGIN DESCRIPTION:
Becerro Creek 51.0
END DESCRIPTION:
XS GIS Cut Line= 3
      2011975.00     13537174.99      2011675.00     13537675.00
      2011155.72     13539701.83
#Sta/Elev= 30
  4589.1  573.72  4787.4  566.55  4858.5  562.81  4974.0  557.36  4983.7  556.58
  4999.3  552.30  4999.9  551.50  5010.8  552.30  5010.9  555.29  5020.6  556.40
  5047.8  555.51  5063.4  556.95  5101.8  556.83  5174.8  555.83  5203.2  557.85
  5333.6  557.59  5832.4  558.45  5925.8  556.76  5946.4  553.71  6029.0  557.95
  6082.3  558.28  6101.3  559.17  6111.6  560.97  6123.1  559.88  6199.5  560.08
  6928.6  568.60  6958.1  567.98  7010.2  569.70  7081.4  569.56  7264.5  572.33
#Mann=6,-1,0
  4589.1     0.1       0  4858.5    0.16       0  4999.3    0.07       0
  5010.8    0.16       0  5101.8    0.12       0  5333.6     0.1       0
Bank Sta=4999.3,5010.8
Exp/Cntr=0.3,0.1

Type RM Length L Ch R = 1,36407,1277,1277,1277
BEGIN DESCRIPTION:
Becerro Creek 50.0
END DESCRIPTION:
XS GIS Cut Line= 4
      2011974.98     13537025.01      2011456.46     13537309.56
      2011018.96     13538142.89      2010741.34     13539440.78
#Sta/Elev= 30
  4208.1  578.07  4303.3  574.39  4597.1  558.97  4710.0  556.38  4945.9  555.74
  4966.8  554.17  4983.1  550.33  4983.7  549.53  4994.6  550.33  5005.2  551.27
  5010.9  553.96  5032.9  555.93  5099.2  555.53  5198.0  555.66  5269.8  553.88
  5291.9  555.28  5653.1  556.99  5699.6  556.75  5716.0  552.87  5721.6  554.88
  5731.8  552.88  5744.4  554.10  5763.4  552.25  5779.1  554.00  5794.0  552.25
  5804.3  553.60  5835.7  553.19  5844.4  554.62  5906.5  556.74  7068.0  570.29
#Mann=8,-1,0
  4208.1     0.1       0  4945.9    0.12       0  4983.1    0.07       0
  4994.6    0.12       0  5099.2     0.1       0  5653.1    0.12       0
  5779.1    0.07       0  5844.4     0.1       0
Bank Sta=4983.1,4994.6
Exp/Cntr=0.3,0.1

Type RM Length L Ch R = 1,35130,970,970,970
BEGIN DESCRIPTION:
Becerro Creek 47.0
END DESCRIPTION:
XS GIS Cut Line= 4
      2011560.61     13536531.80      2010963.41     13536990.12
      2010470.35     13537795.67      2010616.18     13539434.53
#Sta/Elev= 30
  3594.8  572.45  4035.2  556.50  4106.7  553.42  4135.7  553.43  4143.9  550.96
  4150.3  552.69  4164.8  554.08  4226.3  554.15  4430.1  554.07  4451.4  551.45
  4472.7  553.66  4509.5  554.35  4861.1  553.94  4894.5  551.97  4921.3  553.07
  4946.7  552.44  4962.1  553.46  4983.4  550.58  4983.5  547.12  4984.1  546.32
  4995.1  547.12  5010.6  552.43  5033.3  554.17  5059.6  554.37  5092.0  554.28
  5099.5  553.18  5127.1  554.36  5398.9  553.60  5572.5  554.56  6937.4  569.94
#Mann=8,-1,0
  3594.8     0.1       0  4035.2    0.12       0  4226.3     0.1       0
  4861.1    0.16       0  4921.3    0.07       0  4983.5    0.07       0
  4995.1    0.07       0  5059.6     0.1       0
Bank Sta=4983.5,4995.1
Exp/Cntr=0.3,0.1

Type RM Length L Ch R = 1,34160,390,390,390
BEGIN DESCRIPTION:
Becerro Creek 46.0
END DESCRIPTION:
XS GIS Cut Line= 3
      2011225.00     13536125.01      2010095.35     13537330.39
      2010317.58     13539254.02
#Sta/Elev= 30
  3723.9  569.56  4155.5  554.88  4335.2  552.43  4479.4  552.10  4537.4  549.82
  4615.1  552.71  4905.4  552.75  4983.4  549.45  4990.2  552.18  4997.5  546.87
  5004.4  548.42  5005.9  546.23  5006.5  545.43  5017.5  546.23  5025.9  546.89
  5032.7  551.02  5039.6  549.21  5075.2  551.89  5096.2  548.77  5103.6  551.04
  5110.4  547.70  5117.7  550.26  5124.6  548.18  5266.2  551.35  5329.7  547.54
  5340.6  550.73  5964.4  555.44  6165.7  554.09  6467.7  559.39  7312.3  566.92
#Mann=7,-1,0
  3723.9     0.1       0  4335.2    0.12       0  4479.4     0.1       0
  4905.4    0.12       0  5005.9    0.07       0  5017.5    0.12       0
  5340.6     0.1       0
Bank Sta=5005.9,5017.5
Exp/Cntr=0.3,0.1

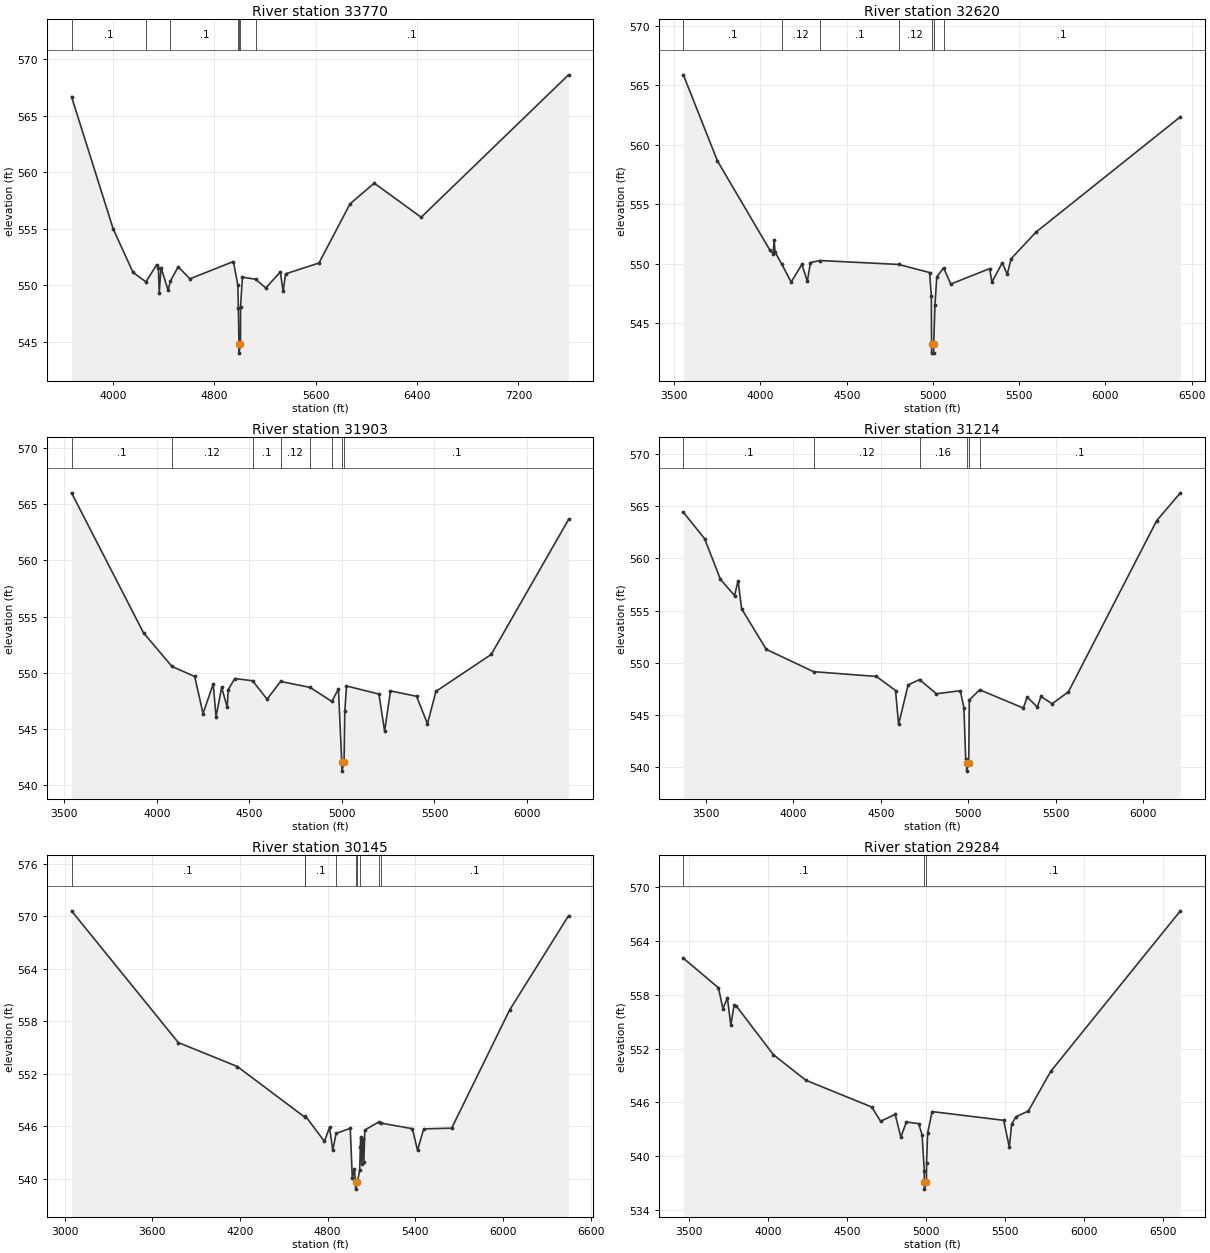
Type RM Length L Ch R = 1,33770,1150,1150,1150
BEGIN DESCRIPTION:
Mapping XS 660e77ec
END DESCRIPTION:
XS GIS Cut Line= 3
      2011130.10     13536149.82      2009789.80     13537177.62
      2010268.96     13539358.17
#Sta/Elev= 30
  3674.1  566.71  4002.5  555.01  4159.4  551.15  4261.3  550.31  4345.1  551.81
  4359.7  551.56  4366.0  549.34  4380.5  551.57  4436.6  549.56  4453.3  550.36
  4515.5  551.64  4608.9  550.58  4951.6  552.11  4986.9  550.00  4990.5  547.98
  4995.6  544.80  4996.2  544.00  5007.3  544.80  5007.8  548.10  5022.3  550.73
  5126.5  550.54  5207.2  549.77  5321.4  551.19  5344.0  549.47  5363.0  551.02
  5626.6  551.98  5871.9  557.22  6062.4  559.05  6433.0  556.03  7595.7  568.64
#Mann=7,-1,0
  3674.1     0.1       0  4261.3    0.12       0  4453.3     0.1       0
  4990.5    0.12       0  4995.6    0.07       0  5007.3    0.12       0
  5126.5     0.1       0
Bank Sta=4995.6,5007.3
Exp/Cntr=0.3,0.1

Type RM Length L Ch R = 1,32620,717,717,717
BEGIN DESCRIPTION:
Becerro Creek 45.0
END DESCRIPTION:
XS GIS Cut Line= 3
      2011074.48     13536101.24      2009470.35     13536573.45
      2008381.32     13537100.62
#Sta/Elev= 30
  3552.8  565.89  3750.3  558.65  4052.6  551.19  4073.5  550.84  4079.1  552.01
  4084.3  550.98  4123.7  549.96  4177.7  548.46  4240.3  549.95  4271.5  548.51
  4289.6  550.10  4345.9  550.27  4800.4  549.94  4980.4  549.26  4990.8  547.30
  4992.0  543.28  4992.5  542.48  5003.9  542.48  5004.4  543.28  5011.7  546.51
  5022.1  548.89  5061.7  549.65  5103.4  548.29  5328.6  549.59  5342.0  548.47
  5401.9  550.07  5430.9  549.11  5453.1  550.42  5597.6  552.66  6434.9  562.36
#Mann=7,-1,0
  3552.8     0.1       0  4123.7    0.12       0  4345.9     0.1       0
  4800.4    0.12       0  4992.0    0.07       0  5004.4    0.12       0
  5061.7     0.1       0
Bank Sta=4992,5004.4
Exp/Cntr=0.3,0.1

Type RM Length L Ch R = 1,31903,689,689,689
BEGIN DESCRIPTION:
Becerro Creek 44.0
END DESCRIPTION:
XS GIS Cut Line= 4
      2011012.04     13535983.17      2010185.63     13536066.51
      2009220.35     13536281.78      2008425.04     13536624.98
#Sta/Elev= 30
  3538.7  565.99  3927.7  553.55  4081.6  550.56  4204.4  549.67  4249.3  546.38
  4304.5  549.00  4319.7  546.08  4349.8  548.71  4380.2  546.93  4385.3  548.50
  4421.2  549.49  4517.2  549.29  4595.4  547.65  4668.4  549.23  4827.7  548.70
  4945.6  547.45  4981.1  548.57  4999.0  542.06  4999.5  541.26  5011.4  542.06
  5015.4  546.56  5024.5  548.83  5199.8  548.11  5230.6  544.81  5262.3  548.39
  5403.3  547.91  5462.1  545.47  5508.2  548.35  5806.7  551.63  6224.5  563.62
#Mann=8,-1,0
  3538.7     0.1       0  4081.6    0.12       0  4517.2     0.1       0
  4668.4    0.12       0  4827.7    0.16       0  4945.6    0.12       0
  4999.0    0.07       0  5011.4     0.1       0
Bank Sta=4999,5011.4
Exp/Cntr=0.3,0.1

Type RM Length L Ch R = 1,31214,1069,1069,1069
BEGIN DESCRIPTION:
Becerro Creek 43.0
END DESCRIPTION:
XS GIS Cut Line= 4
      2010935.62     13535920.67      2009914.80     13535802.62
      2009012.02     13536017.89      2008325.02     13536574.98
#Sta/Elev= 30
  3372.0  564.43  3493.4  561.90  3584.0  557.99  3664.6  556.44  3684.7  557.87
  3704.8  555.17  3845.8  551.27  4116.0  549.13  4475.5  548.67  4584.5  547.32
  4601.9  544.07  4656.4  547.86  4721.6  548.37  4817.6  547.01  4954.6  547.30
  4975.1  545.67  4985.4  540.73  4990.2  540.38  4990.7  539.58  5002.6  540.38
  5006.0  546.41  5064.9  547.39  5314.4  545.64  5337.1  546.69  5394.6  545.73
  5415.4  546.75  5479.4  546.05  5572.1  547.19  6077.2  563.64  6212.2  566.30
#Mann=6,-1,0
  3372.0     0.1       0  4116.0    0.12       0  4721.6    0.16       0
  4990.2    0.07       0  5002.6    0.16       0  5064.9     0.1       0
Bank Sta=4990.2,5002.6
Exp/Cntr=0.3,0.1

Type RM Length L Ch R = 1,30145,861,861,861
BEGIN DESCRIPTION:
Becerro Creek 42.0
END DESCRIPTION:
XS GIS Cut Line= 3
      2010675.04     13534274.97      2009186.22     13535547.00
      2008124.98     13536525.02
#Sta/Elev= 30
  3047.8  570.62  3778.5  555.56  4182.5  552.82  4643.4  547.04  4648.8  547.15
  4778.6  544.26  4813.7  545.87  4835.7  543.24  4858.4  545.17  4955.3  545.75
  4969.6  540.03  4983.9  541.10  4991.4  539.60  4992.1  538.80  5004.8  539.60
  5019.8  540.99  5024.7  543.67  5026.6  544.71  5034.0  541.73  5040.8  544.58
  5048.2  541.85  5055.0  545.56  5151.6  546.49  5165.3  546.35  5380.5  545.71
  5415.7  543.24  5458.2  545.69  5649.3  545.77  6045.7  559.27  6449.2  570.06
#Mann=9,-1,0
  3047.8     0.1       0  4643.4    0.05       0  4648.8     0.1       0
  4858.4    0.16       0  4991.4    0.07       0  5004.8    0.16       0
  5024.7    0.07       0  5151.6    0.12       0  5165.3     0.1       0
Bank Sta=4991.4,5004.8
Exp/Cntr=0.3,0.1

Type RM Length L Ch R = 1,29284,935,935,935
BEGIN DESCRIPTION:
Becerro Creek 41.0
END DESCRIPTION:
XS GIS Cut Line= 3
      2010028.50     13534164.61      2008875.00     13535225.00
      2007700.41     13536279.16
#Sta/Elev= 30
  3465.9  562.07  3688.0  558.77  3716.1  556.44  3744.5  557.66  3766.0  554.61
  3787.0  556.87  3801.2  556.74  4034.9  551.33  4240.2  548.48  4657.6  545.49
  4714.3  543.90  4806.2  544.67  4841.9  542.14  4877.1  543.82  4954.8  543.64
  4976.3  542.41  4990.5  538.33  4990.6  537.14  4991.2  536.34  5004.0  537.14
  5004.7  539.29  5011.5  542.59  5039.8  544.98  5492.8  544.01  5528.7  541.00
  5542.9  543.58  5570.6  544.40  5649.1  545.05  5790.4  549.46  6611.0  567.35
#Mann=3,-1,0
  3465.9     0.1       0  4990.6    0.07       0  5004.0     0.1       0
Bank Sta=4990.6,5004
Exp/Cntr=0.3,0.1

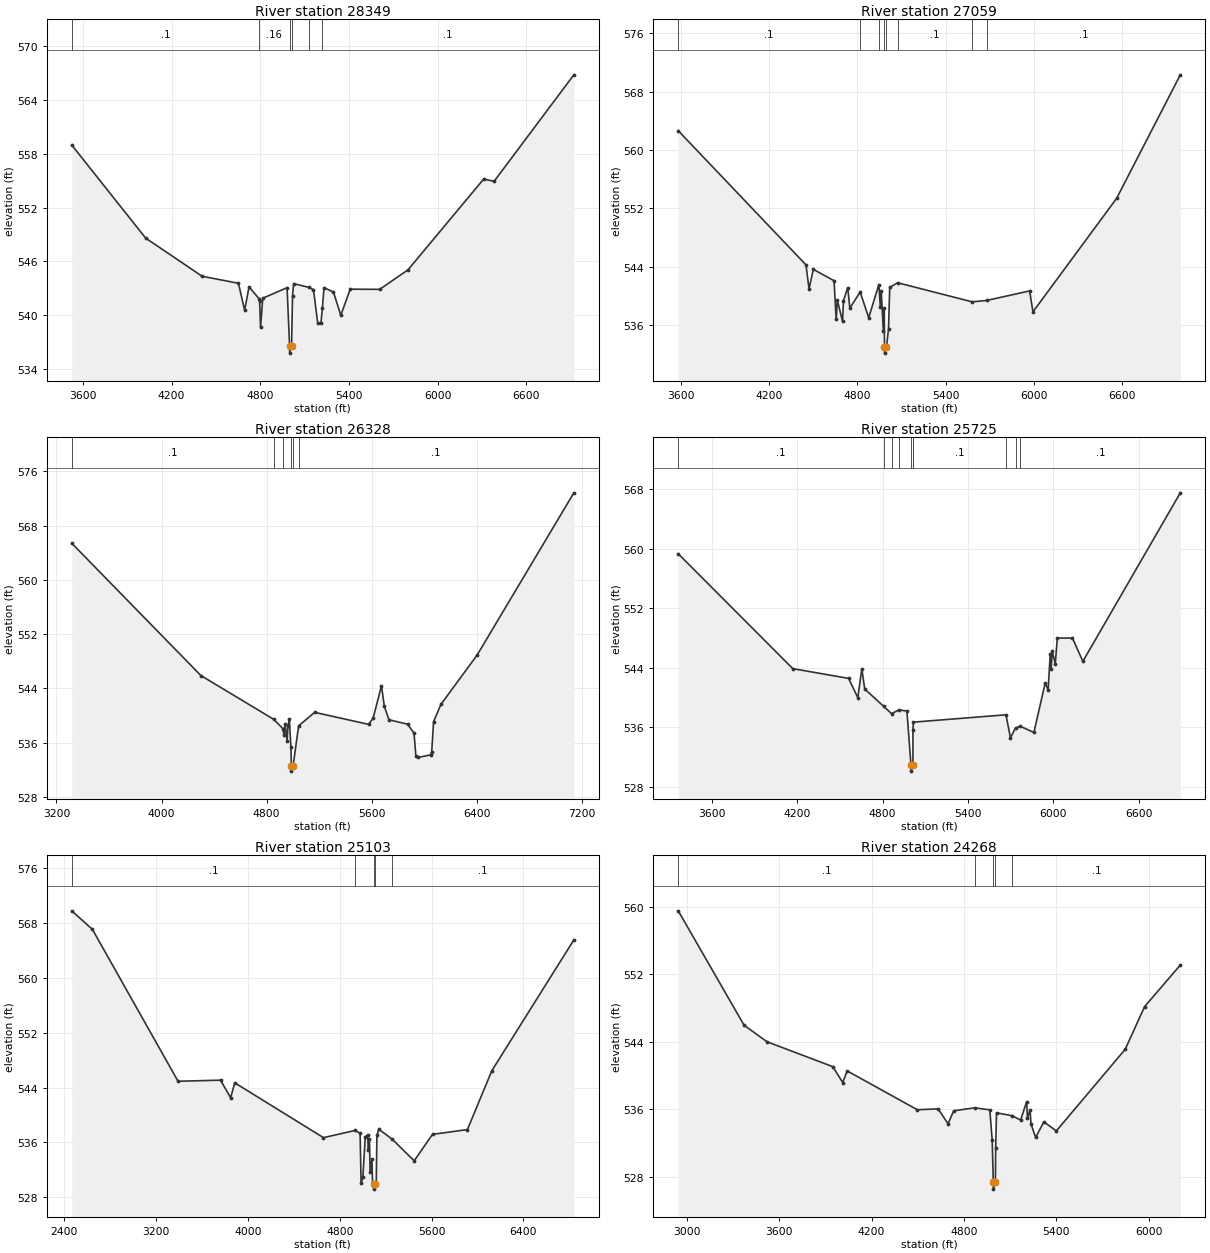
Type RM Length L Ch R = 1,28349,1290,1290,1290
BEGIN DESCRIPTION:
Becerro Creek 40.0
END DESCRIPTION:
XS GIS Cut Line= 3
      2009768.08     13533852.11      2008538.93     13534690.64
      2007064.96     13535904.19
#Sta/Elev= 30
  3525.0  558.98  4025.0  548.59  4407.4  544.33  4652.7  543.55  4694.6  540.53
  4724.5  543.14  4792.2  541.83  4796.3  541.52  4802.4  538.63  4817.3  541.88
  4981.9  543.06  4998.9  536.55  4999.5  535.75  5012.3  536.55  5018.7  542.18
  5026.1  543.51  5128.3  543.09  5160.5  542.84  5188.9  539.13  5211.1  539.09
  5220.7  540.80  5232.0  543.06  5295.8  542.56  5345.3  539.98  5409.2  542.89
  5608.6  542.87  5800.1  545.05  6312.3  555.19  6382.6  554.93  6922.2  566.82
#Mann=6,-1,0
  3525.0     0.1       0  4792.2    0.16       0  4998.9    0.07       0
  5012.3    0.16       0  5128.3    0.12       0  5220.7     0.1       0
Bank Sta=4998.9,5012.3
Exp/Cntr=0.3,0.1

Type RM Length L Ch R = 1,27059,731,731,731
BEGIN DESCRIPTION:
Becerro Creek 39.0
END DESCRIPTION:
XS GIS Cut Line= 3
      2009525.04     13533124.97      2008425.00     13533975.00
      2006824.99     13535225.01
#Sta/Elev= 30
  3579.1  562.64  4449.5  544.22  4470.3  540.92  4499.3  543.61  4640.7  542.05
  4655.0  536.73  4663.2  539.40  4698.5  536.46  4704.8  539.31  4733.8  541.11
  4748.3  538.30  4818.6  540.49  4876.9  536.97  4945.9  541.52  4955.7  538.51
  4962.0  540.70  4976.5  535.15  4982.9  538.26  4984.2  532.91  4984.9  532.11
  4997.7  532.91  5011.8  535.45  5019.9  541.13  5073.8  541.77  5581.6  539.15
  5680.4  539.34  5973.2  540.65  5995.8  537.78  6565.6  553.35  6999.7  570.31
#Mann=8,-1,0
  3579.1     0.1       0  4818.6    0.16       0  4945.9    0.12       0
  4984.2    0.07       0  4997.7    0.12       0  5073.8     0.1       0
  5581.6    0.07       0  5680.4     0.1       0
Bank Sta=4984.2,4997.7
Exp/Cntr=0.3,0.1

Type RM Length L Ch R = 1,26328,603,603,603
BEGIN DESCRIPTION:
Becerro Creek 38.0
END DESCRIPTION:
XS GIS Cut Line= 3
      2009625.00     13532925.00      2008075.00     13533625.00
      2006625.02     13535174.98
#Sta/Elev= 30
  3316.6  565.41  4299.6  545.91  4855.0  539.44  4923.9  538.09  4933.7  537.07
  4940.5  538.73  4956.8  536.32  4962.5  538.51  4973.4  539.43  4985.4  535.33
  4988.6  532.61  4989.3  531.81  5002.2  532.61  5044.0  538.48  5166.1  540.48
  5576.4  538.71  5611.6  539.63  5675.1  544.41  5696.6  541.37  5731.8  539.39
  5873.4  538.73  5922.8  537.42  5936.9  534.08  5951.1  533.82  6050.3  534.21
  6057.6  534.68  6071.7  539.10  6127.9  541.66  6403.9  548.94  7139.8  572.85
#Mann=6,-1,0
  3316.6     0.1       0  4855.0    0.16       0  4923.9    0.12       0
  4988.6    0.07       0  5002.2    0.12       0  5044.0     0.1       0
Bank Sta=4988.6,5002.2
Exp/Cntr=0.3,0.1

Type RM Length L Ch R = 1,25725,622,622,622
BEGIN DESCRIPTION:
Becerro Creek 37.0
END DESCRIPTION:
XS GIS Cut Line= 3
      2009275.04     13532874.99      2007725.00     13533275.00
      2006575.03     13534824.96
#Sta/Elev= 30
  3362.4  559.32  4168.0  543.89  4560.4  542.58  4625.3  539.99  4653.4  543.87
  4674.0  541.15  4807.2  538.82  4862.6  537.84  4913.8  538.34  4970.5  538.20
  4999.2  530.92  4999.9  530.12  5012.8  530.92  5013.0  535.65  5016.4  536.70
  5667.0  537.69  5698.7  534.61  5734.5  535.92  5768.6  536.14  5863.5  535.31
  5942.9  541.95  5963.7  541.04  5978.3  545.80  5984.5  543.79  5992.9  546.20
  6013.8  544.55  6028.4  548.00  6134.8  547.99  6207.9  544.87  6893.2  567.51
#Mann=10,-1,0
  3362.4     0.1       0  4807.2    0.12       0  4862.6     0.1       0
  4913.8    0.12       0  4999.2    0.07       0  5012.8    0.12       0
  5016.4     0.1       0  5667.0    0.12       0  5734.5    0.07       0
  5768.6     0.1       0
Bank Sta=4999.2,5012.8
Exp/Cntr=0.3,0.1

Type RM Length L Ch R = 1,25103,835,835,835
BEGIN DESCRIPTION:
Becerro Creek 36.0
END DESCRIPTION:
XS GIS Cut Line= 3
      2008724.99     13530925.01      2007325.00     13533125.00
      2006475.02     13534674.97
#Sta/Elev= 30
  2464.0  569.79  2644.3  567.07  3390.2  544.92  3760.2  545.08  3848.3  542.52
  3884.7  544.69  4657.7  536.69  4931.8  537.74  4976.8  537.33  4985.3  530.01
  5000.5  530.88  5021.7  536.82  5042.9  537.07  5048.8  534.87  5058.1  536.52
  5064.0  531.66  5079.7  533.52  5085.4  530.12  5094.7  529.98  5095.5  529.18
  5108.3  529.98  5117.3  530.04  5123.3  537.01  5139.4  537.92  5256.4  536.47
  5448.0  533.31  5607.7  537.17  5911.9  537.87  6124.3  546.45  6839.4  565.55
#Mann=5,-1,0
  2464.0     0.1       0  4931.8    0.12       0  5094.7    0.07       0
  5108.3    0.12       0  5256.4     0.1       0
Bank Sta=5094.7,5108.3
Exp/Cntr=0.3,0.1

Type RM Length L Ch R = 1,24268,660,660,660
BEGIN DESCRIPTION:
Becerro Creek 35.0
END DESCRIPTION:
XS GIS Cut Line= 3
      2008274.97     13531225.03      2007025.00     13532825.00
      2006475.00     13533925.01
#Sta/Elev= 30
  2944.5  559.53  3372.2  545.96  3521.5  544.00  3948.4  541.05  4012.6  539.17
  4041.5  540.55  4497.3  535.94  4632.2  536.05  4696.3  534.28  4733.4  535.82
  4869.4  536.17  4967.6  535.93  4983.2  532.33  4990.4  527.33  4991.2  526.53
  5004.0  527.33  5005.6  531.35  5011.2  535.58  5113.1  535.23  5167.7  534.72
  5206.8  536.90  5212.4  534.95  5229.2  535.95  5234.8  534.27  5265.5  532.66
  5318.6  534.51  5399.7  533.43  5846.9  543.11  5972.7  548.17  6204.7  553.10
#Mann=5,-1,0
  2944.5     0.1       0  4869.4    0.12       0  4990.4    0.07       0
  5004.0    0.12       0  5113.1     0.1       0
Bank Sta=4990.4,5004
Exp/Cntr=0.3,0.1

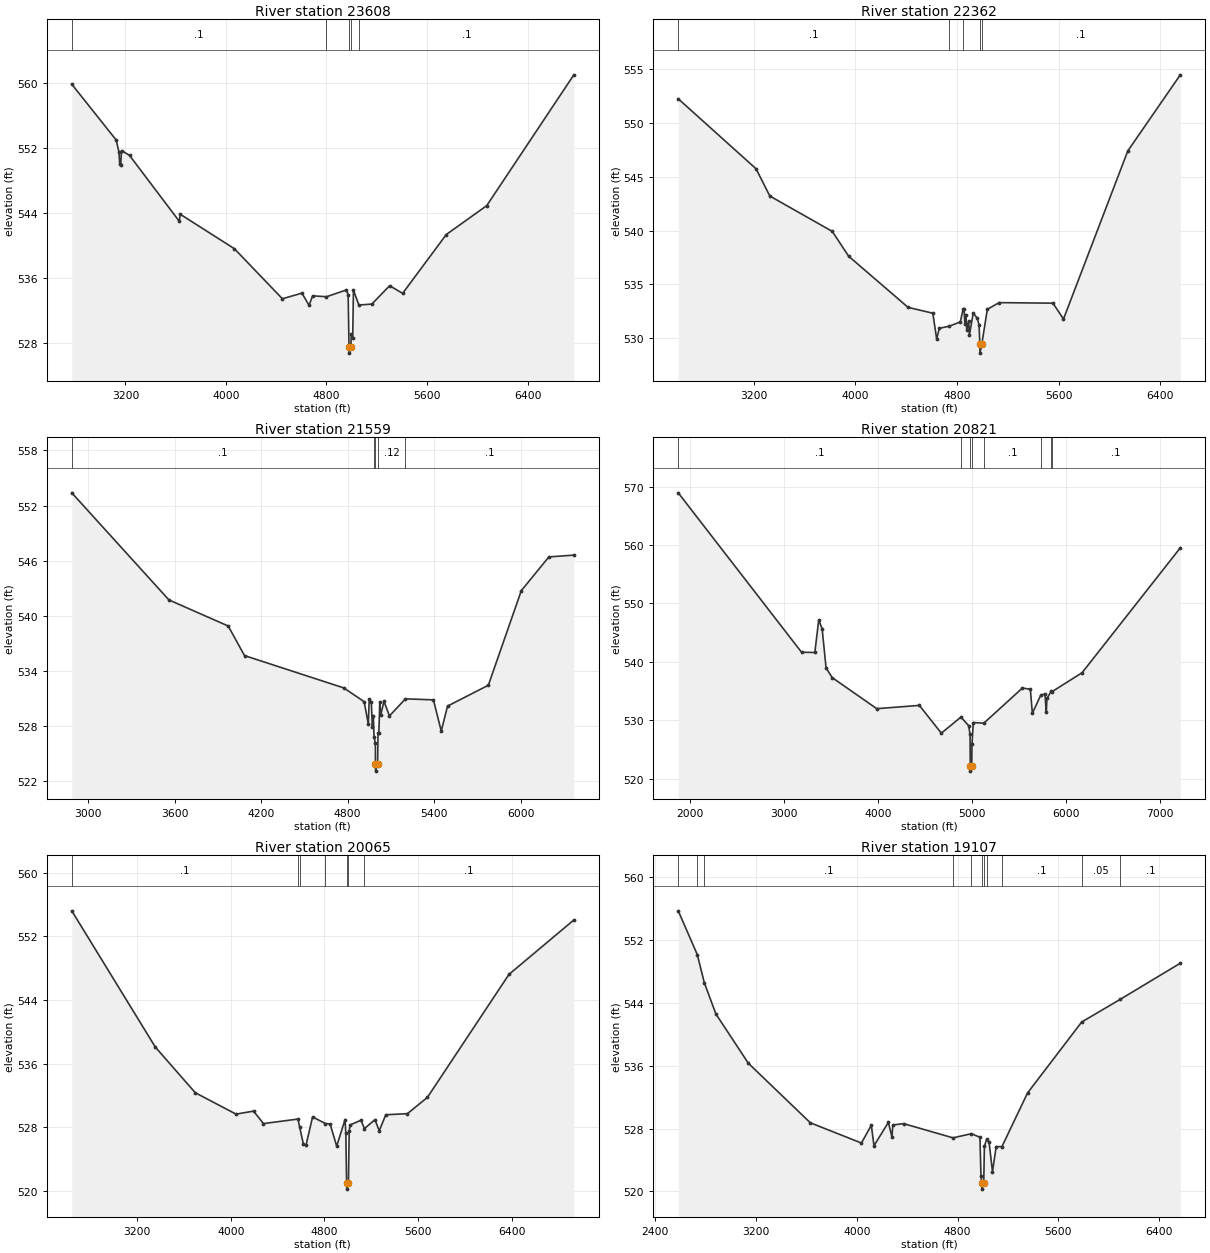
Type RM Length L Ch R = 1,23608,1246,1246,1246
BEGIN DESCRIPTION:
Becerro Creek 34.0
END DESCRIPTION:
XS GIS Cut Line= 3
      2008174.97     13530975.03      2006625.00     13532575.00
      2005775.00     13534125.00
#Sta/Elev= 30
  2773.1  559.80  3126.6  552.95  3148.0  551.52  3154.9  550.00  3162.1  549.87
  3169.1  551.66  3232.6  551.07  3628.8  542.98  3635.9  543.85  4067.3  539.62
  4449.1  533.48  4604.7  534.17  4661.3  532.67  4689.6  533.84  4800.1  533.73
  4958.4  534.56  4972.5  533.97  4979.3  527.61  4980.5  526.81  4994.1  527.61
  4997.2  529.16  5008.8  528.71  5014.5  534.54  5057.6  532.71  5161.4  532.83
  5302.6  535.08  5405.9  534.14  5753.5  541.36  6075.1  544.90  6768.5  560.95
#Mann=5,-1,0
  2773.1     0.1       0  4800.1    0.12       0  4979.3    0.07       0
  4994.1    0.12       0  5057.6     0.1       0
Bank Sta=4979.3,4994.1
Exp/Cntr=0.3,0.1

Type RM Length L Ch R = 1,22362,803,803,803
BEGIN DESCRIPTION:
Becerro Creek 33.0
END DESCRIPTION:
XS GIS Cut Line= 3
      2007439.99     13530128.10      2006125.00     13532075.00
      2005724.99     13533625.03
#Sta/Elev= 30
  2606.5  552.21  3219.1  545.72  3327.0  543.20  3818.5  539.92  3947.4  537.62
  4414.9  532.88  4609.7  532.34  4639.7  529.96  4660.7  530.94  4739.4  531.14
  4825.5  531.53  4848.4  532.73  4855.5  532.73  4861.5  531.34  4870.4  532.21
  4876.5  530.78  4891.4  531.60  4897.5  530.33  4927.4  532.35  4958.5  531.89
  4973.6  531.26  4979.4  529.44  4980.7  528.64  4994.3  529.44  5038.5  532.70
  5131.1  533.32  5554.9  533.27  5637.5  531.80  6143.6  547.38  6556.7  554.43
#Mann=5,-1,0
  2606.5     0.1       0  4739.4    0.12       0  4848.4     0.1       0
  4979.4    0.07       0  4994.3     0.1       0
Bank Sta=4979.4,4994.3
Exp/Cntr=0.3,0.1

Type RM Length L Ch R = 1,21559,738,738,738
BEGIN DESCRIPTION:
Becerro Creek 32.0
END DESCRIPTION:
XS GIS Cut Line= 3
      2007174.98     13530075.02      2005775.00     13531675.00
      2005242.05     13532919.81
#Sta/Elev= 30
  2887.9  553.39  3561.3  541.73  3972.2  538.89  4085.2  535.67  4773.3  532.15
  4914.7  530.65  4943.2  528.22  4949.8  530.90  4964.1  530.58  4971.7  527.93
  4978.3  529.13  4983.2  526.80  4992.5  526.12  4992.6  523.89  4993.9  523.09
  5007.7  523.89  5010.6  527.29  5016.6  527.29  5023.0  530.63  5028.4  529.16
  5052.0  530.69  5090.0  529.10  5200.8  530.96  5394.6  530.85  5449.0  527.45
  5492.5  530.17  5775.4  532.44  6003.8  542.74  6194.8  546.41  6368.0  546.61
#Mann=5,-1,0
  2887.9     0.1       0  4983.2    0.12       0  4992.6    0.07       0
  5007.7    0.12       0  5200.8     0.1       0
Bank Sta=4992.6,5007.7
Exp/Cntr=0.3,0.1

Type RM Length L Ch R = 1,20821,756,756,756
BEGIN DESCRIPTION:
Becerro Creek 31.0
END DESCRIPTION:
XS GIS Cut Line= 3
      2007374.97     13529275.04      2005375.00     13531675.00
      2003775.01     13533224.99
#Sta/Elev= 30
  1870.1  568.94  3184.1  541.64  3326.0  541.59  3367.7  547.18  3404.1  545.64
  3445.8  538.97  3510.2  537.30  3986.0  531.97  4440.3  532.53  4674.6  527.77
  4883.7  530.53  4966.2  529.04  4980.5  527.55  4983.3  522.07  4984.7  521.27
  4998.5  522.07  5001.2  525.94  5015.4  529.59  5127.8  529.49  5538.6  535.50
  5623.5  535.30  5644.8  531.18  5734.5  534.29  5779.1  534.48  5793.3  531.34
  5800.4  533.72  5844.3  534.93  5851.4  534.85  6175.2  538.13  7221.8  559.52
#Mann=8,-1,0
  1870.1     0.1       0  4883.7    0.12       0  4983.3    0.07       0
  4998.5    0.12       0  5127.8     0.1       0  5734.5    0.12       0
  5844.3    0.07       0  5851.4     0.1       0
Bank Sta=4983.3,4998.5
Exp/Cntr=0.3,0.1

Type RM Length L Ch R = 1,20065,958,958,958
BEGIN DESCRIPTION:
Mapping XS c91d223a
END DESCRIPTION:
XS GIS Cut Line= 2
      2006443.47     13529518.73      2003700.54     13532810.25
#Sta/Elev= 30
  2643.8  555.22  3356.8  538.09  3697.8  532.35  4045.4  529.66  4195.1  530.04
  4279.7  528.47  4574.5  529.04  4587.9  528.09  4620.7  525.86  4642.9  525.76
  4698.8  529.31  4807.7  528.48  4848.5  528.42  4904.5  525.63  4976.1  528.98
  4982.6  527.23  4989.0  521.03  4990.6  520.23  5004.9  521.03  5011.2  527.58
  5019.1  528.30  5111.5  528.89  5141.6  527.85  5231.2  528.96  5267.7  527.57
  5323.7  529.58  5508.5  529.72  5679.0  531.77  6374.9  547.23  6928.4  554.07
#Mann=7,-1,0
  2643.8     0.1       0  4574.5    0.12       0  4587.9     0.1       0
  4807.7    0.12       0  4989.0    0.07       0  5004.9    0.12       0
  5141.6     0.1       0
Bank Sta=4989,5004.9
Exp/Cntr=0.3,0.1

Type RM Length L Ch R = 1,19107,639,639,639
BEGIN DESCRIPTION:
Mapping XS 9e678f65
END DESCRIPTION:
XS GIS Cut Line= 2
      2005860.10     13529220.16      2003443.43     13532393.78
#Sta/Elev= 30
  2581.2  555.73  2732.5  550.16  2788.3  546.58  2880.6  542.59  3138.3  536.32
  3630.5  528.74  4036.5  526.16  4115.4  528.43  4136.3  525.82  4250.6  528.78
  4279.7  526.92  4286.0  528.46  4372.1  528.63  4764.2  526.82  4910.8  527.35
  4978.2  526.89  4986.5  521.92  4992.6  521.09  4994.3  520.29  5008.5  521.09
  5013.6  525.76  5031.9  526.64  5050.9  526.26  5078.0  522.51  5107.1  525.70
  5152.9  525.70  5356.6  532.54  5786.6  541.57  6094.2  544.47  6570.2  549.06
#Mann=11,-1,0
  2581.2     0.1       0  2732.5    0.05       0  2788.3     0.1       0
  4764.2    0.07       0  4910.8    0.12       0  4992.6    0.07       0
  5008.5    0.12       0  5031.9    0.07       0  5152.9     0.1       0
  5786.6    0.05       0  6094.2     0.1       0
Bank Sta=4992.6,5008.5
Exp/Cntr=0.3,0.1

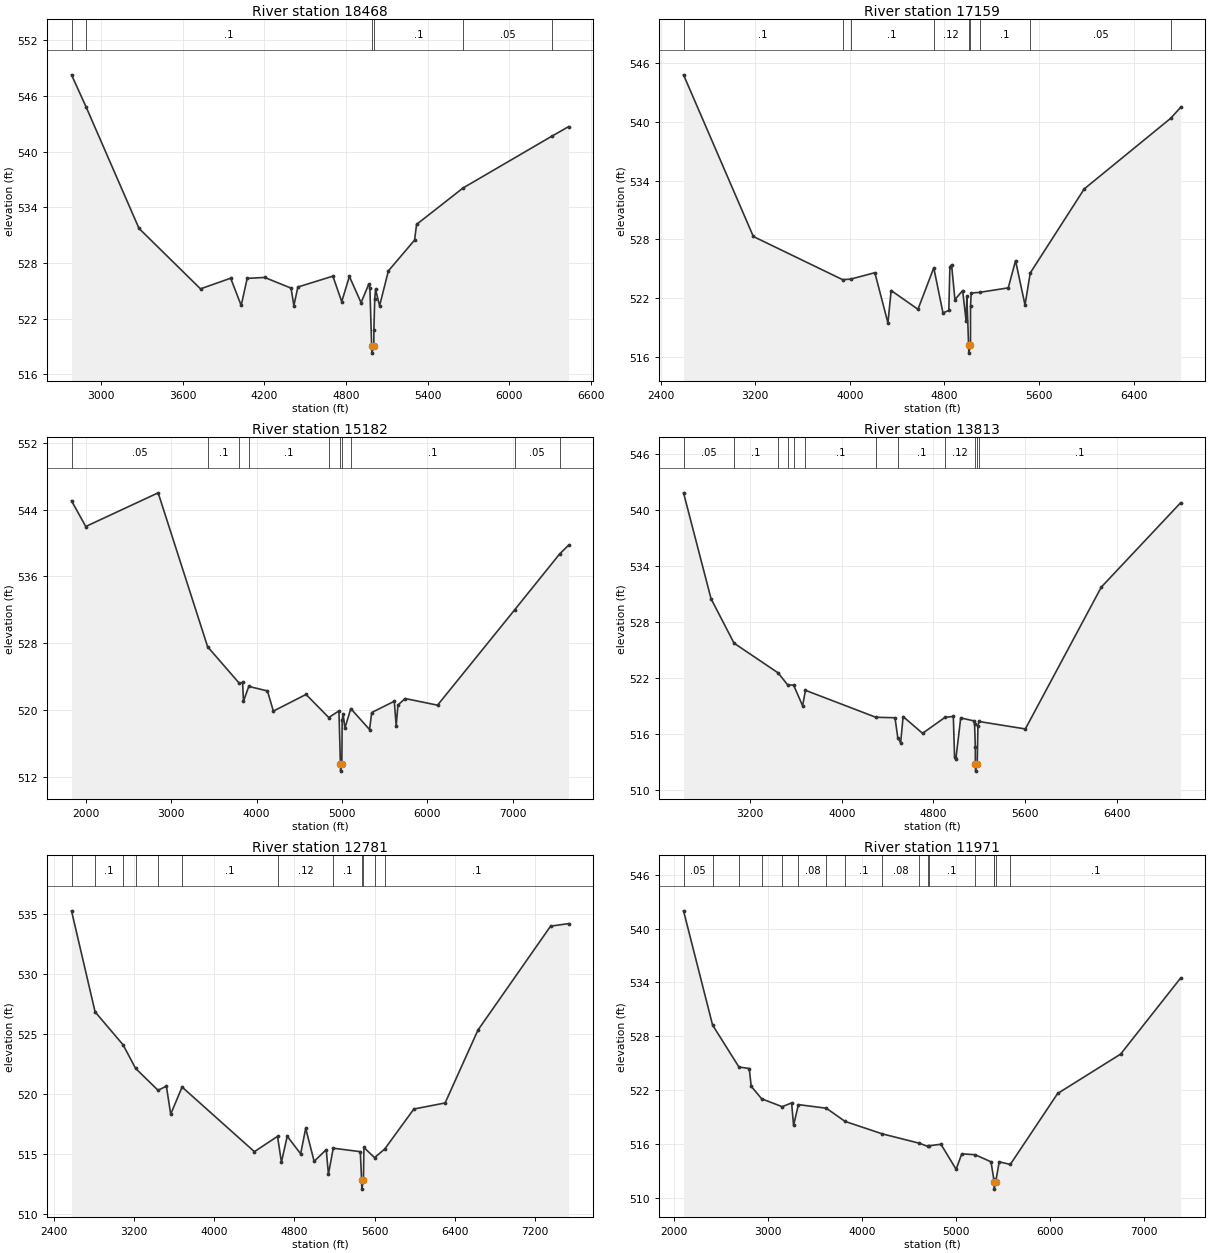
Type RM Length L Ch R = 1,18468,1309,1309,1309
BEGIN DESCRIPTION:
Mapping XS 79385bd1
END DESCRIPTION:
XS GIS Cut Line= 2
      2005249.00     13529095.15      2003103.18     13532053.46
#Sta/Elev= 30
  2782.1  548.28  2889.2  544.82  3278.3  531.72  3730.6  525.20  3952.4  526.35
  4029.7  523.41  4073.8  526.33  4202.6  526.43  4396.2  525.28  4417.1  523.40
  4446.5  525.40  4703.9  526.57  4768.9  523.82  4825.3  526.54  4911.1  523.71
  4968.5  525.74  4976.1  525.28  4989.0  519.07  4990.6  518.27  5004.9  519.07
  5005.4  520.76  5011.6  524.11  5017.9  525.14  5047.2  523.37  5112.1  527.14
  5304.6  530.46  5319.3  532.15  5661.2  536.08  6312.3  541.65  6436.7  542.69
#Mann=6,-1,0
  2782.1    0.05       0  2889.2     0.1       0  4989.0    0.07       0
  5004.9     0.1       0  5661.2    0.05       0  6312.3     0.1       0
Bank Sta=4989,5004.9
Exp/Cntr=0.3,0.1

Type RM Length L Ch R = 1,17159,1977,1977,1977
BEGIN DESCRIPTION:
Becerro Creek 25.0
END DESCRIPTION:
XS GIS Cut Line= 4
      2004985.13     13528977.09      2003647.80     13529421.38
      2002950.39     13530574.32      2003019.83     13532018.79
#Sta/Elev= 30
  2593.7  544.80  3183.9  528.28  3938.4  523.87  4005.9  523.92  4211.4  524.58
  4322.0  519.45  4349.2  522.76  4576.1  520.84  4709.7  525.08  4787.6  520.47
  4836.9  520.72  4845.8  525.16  4860.3  525.39  4888.5  521.83  4953.8  522.75
  4983.5  519.62  4989.4  522.17  5004.2  517.16  5005.9  516.36  5020.2  517.16
  5020.4  521.16  5026.2  522.50  5096.5  522.57  5339.5  523.03  5401.1  525.81
  5481.2  521.28  5525.4  524.55  5981.8  533.14  6712.3  540.35  6796.5  541.47
#Mann=9,-1,0
  2593.7     0.1       0  3938.4    0.05       0  4005.9     0.1       0
  4709.7    0.12       0  5004.2    0.07       0  5020.2    0.12       0
  5096.5     0.1       0  5525.4    0.05       0  6712.3     0.1       0
Bank Sta=5004.2,5020.2
Exp/Cntr=0.3,0.1

Type RM Length L Ch R = 1,15182,1369,1369,1369
BEGIN DESCRIPTION:
Becerro Creek 24.0
END DESCRIPTION:
XS GIS Cut Line= 4
      2004058.31     13526952.57      2002660.89     13528374.67
      2002160.89     13529784.39      2002861.73     13532011.80
#Sta/Elev= 30
  1831.4  545.08  1998.1  541.99  2846.6  546.03  3426.8  527.56  3799.3  523.17
  3836.1  523.30  3846.7  521.04  3908.6  522.81  4127.5  522.27  4196.9  519.85
  4579.9  521.85  4845.9  519.08  4965.4  519.87  4982.8  513.45  4984.6  512.65
  4999.1  513.45  5003.3  518.78  5013.9  519.50  5035.1  517.81  5104.2  520.15
  5323.9  517.64  5349.5  519.68  5613.9  521.03  5636.1  518.11  5657.0  520.58
  5740.9  521.36  6120.6  520.56  7023.2  531.98  7553.4  538.72  7656.0  539.74
#Mann=10,-1,0
  1831.4    0.05       0  3426.8     0.1       0  3799.3    0.05       0
  3908.6     0.1       0  4845.9    0.12       0  4982.8    0.07       0
  4999.1    0.12       0  5104.2     0.1       0  7023.2    0.05       0
  7553.4     0.1       0
Bank Sta=4982.8,4999.1
Exp/Cntr=0.3,0.1

Type RM Length L Ch R = 1,13813,1032,1032,1032
BEGIN DESCRIPTION:
Becerro Creek 21.0
END DESCRIPTION:
XS GIS Cut Line= 3
      2003005.95     13527706.25      2001325.00     13529375.00
      2000131.85     13530941.18
#Sta/Elev= 30
  2619.4  541.80  2859.6  530.45  3060.3  525.69  3444.4  522.51  3527.7  521.23
  3580.2  521.19  3658.6  518.98  3683.1  520.64  4297.7  517.75  4464.8  517.70
  4489.0  515.57  4514.2  515.01  4535.5  517.83  4705.2  516.03  4901.2  517.74
  4973.9  517.84  4984.5  513.51  4995.3  513.23  5038.3  517.68  5151.4  517.37
  5159.5  517.01  5165.8  514.53  5165.9  512.78  5167.7  511.98  5182.2  512.78
  5188.6  516.80  5196.7  517.30  5602.3  516.50  6265.4  531.70  6956.9  540.73
#Mann=12,-1,0
  2619.4    0.05       0  3060.3     0.1       0  3444.4    0.05       0
  3527.7    0.08       0  3580.2    0.05       0  3683.1     0.1       0
  4297.7    0.12       0  4489.0     0.1       0  4901.2    0.12       0
  5165.9    0.07       0  5182.2    0.12       0  5196.7     0.1       0
Bank Sta=5165.9,5182.2
Exp/Cntr=0.3,0.1

Type RM Length L Ch R = 1,12781,810,810,810
BEGIN DESCRIPTION:
Mapping XS a6d2d58c
END DESCRIPTION:
XS GIS Cut Line= 5
      2002735.10     13527671.55      2001917.84     13528673.28
      2001096.22     13528671.54      2000144.83     13529490.98
      1999589.64     13530983.07
#Sta/Elev= 30
  2574.7  535.29  2810.0  526.85  3090.1  524.09  3214.1  522.13  3438.4  520.30
  3521.9  520.64  3565.0  518.30  3678.5  520.57  4400.4  515.17  4631.5  516.45
  4670.4  514.29  4728.2  516.46  4862.3  514.99  4912.6  517.12  4997.1  514.36
  5117.7  515.34  5139.5  513.29  5187.7  515.46  5457.9  515.17  5470.6  512.84
  5473.1  512.04  5488.9  512.84  5494.1  515.52  5600.2  514.67  5701.4  515.39
  5992.2  518.73  6304.6  519.24  6631.9  525.32  7357.5  534.01  7536.8  534.22
#Mann=12,-1,0
  2574.7    0.05       0  2810.0     0.1       0  3090.1    0.05       0
  3214.1     0.1       0  3438.4    0.05       0  3678.5     0.1       0
  4631.5    0.12       0  5187.7     0.1       0  5470.6    0.07       0
  5488.9     0.1       0  5600.2    0.07       0  5701.4     0.1       0
Bank Sta=5470.6,5488.9
Exp/Cntr=0.3,0.1

Type RM Length L Ch R = 1,11971,137,137,137
BEGIN DESCRIPTION:
Mapping XS e9ed4c62
END DESCRIPTION:
XS GIS Cut Line= 4
      2002755.92     13527497.96      2002026.78     13528477.10
      1999374.00     13528692.37      1998596.20     13529859.07
#Sta/Elev= 30
  2105.3  541.97  2414.1  529.25  2694.3  524.58  2803.9  524.41  2824.8  522.43
  2935.9  521.04  3153.8  520.16  3254.3  520.58  3275.2  518.08  3326.7  520.39
  3623.5  519.99  3822.8  518.52  4216.9  517.14  4612.6  516.09  4701.2  515.74
  4712.0  515.80  4841.7  515.98  5003.4  513.19  5063.6  514.91  5206.1  514.81
  5374.6  514.02  5403.9  512.08  5405.6  511.78  5408.1  510.98  5423.9  511.78
  5461.8  514.02  5579.5  513.73  6082.9  521.63  6753.0  526.02  7389.8  534.48
#Mann=17,-1,0
  2105.3    0.05       0  2414.1     0.1       0  2694.3    0.05       0
  2935.9     0.1       0  3153.8    0.05       0  3326.7    0.08       0
  3623.5    0.05       0  3822.8     0.1       0  4216.9    0.08       0
  4612.6    0.05       0  4701.2    0.12       0  4712.0     0.1       0
  5206.1    0.08       0  5403.9    0.05       0  5405.6    0.07       0
  5423.9    0.05       0  5579.5     0.1       0
Bank Sta=5405.6,5423.9
Exp/Cntr=0.3,0.1