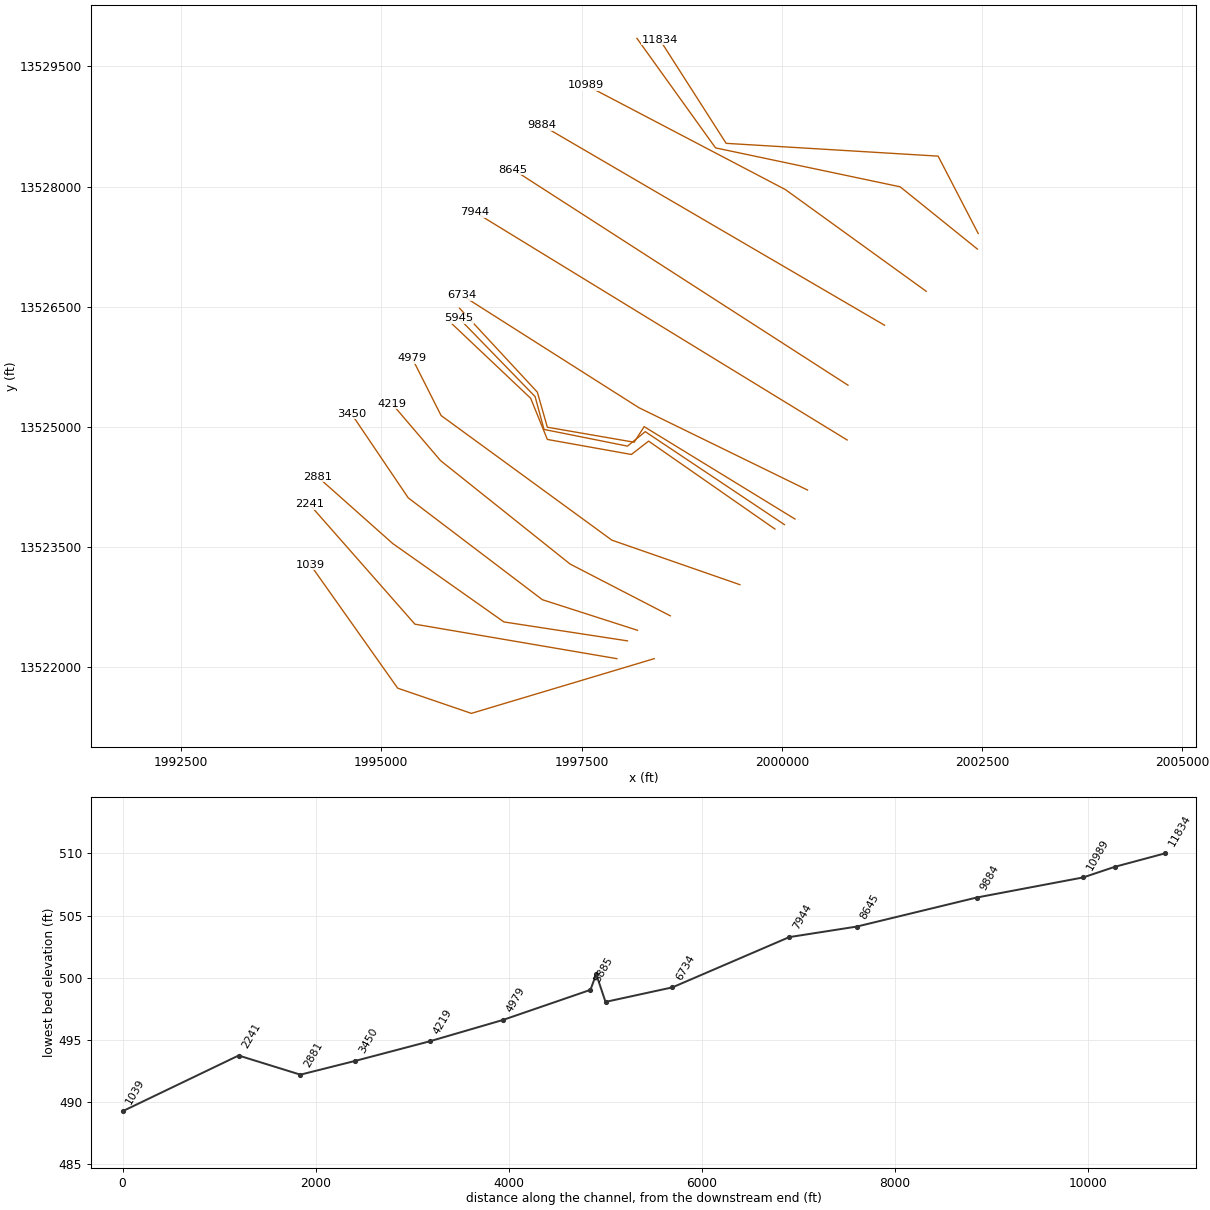
HEC-RAS study Becerro Creek.prj: Becerro Creek Base Level Engineering

--- Becerro Creek.g01 (geometry) --- (continued)

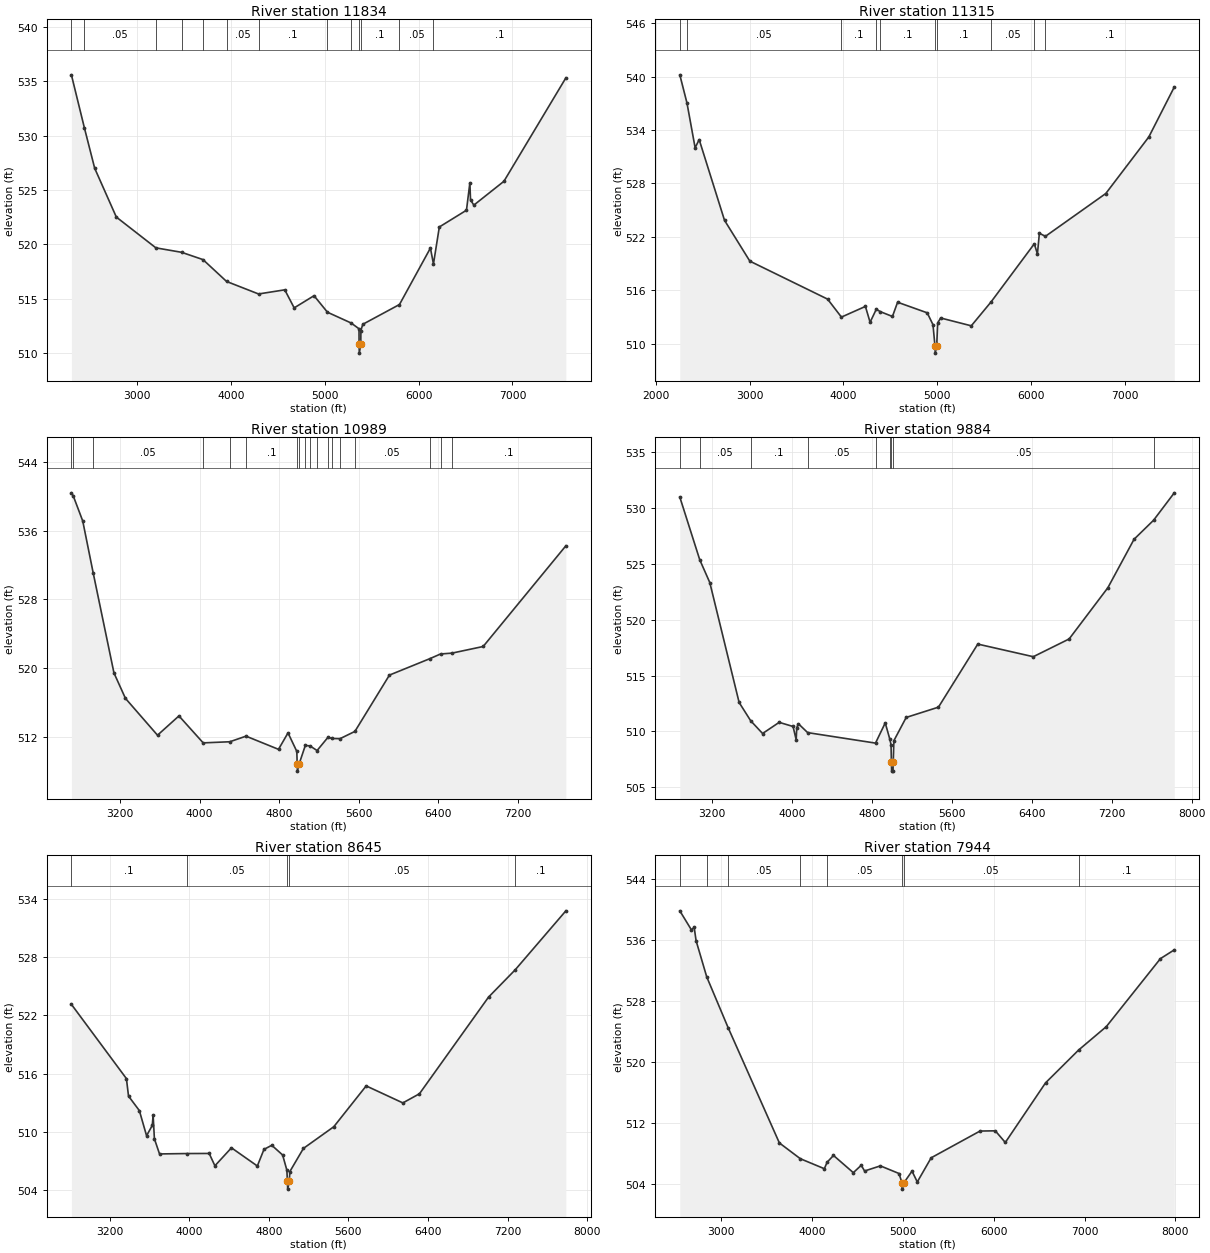
Type RM Length L Ch R = 1,11834,519,519,519
BEGIN DESCRIPTION:
Mapping XS 14f53b66
END DESCRIPTION:
XS GIS Cut Line= 4
      2002450.41     13527414.56      2001950.39     13528379.87
      1999304.55     13528539.60      1998478.16     13529831.27
#Sta/Elev= 30
  2298.5  535.59  2436.9  530.72  2546.8  527.00  2777.7  522.51  3199.1  519.68
  3473.6  519.27  3701.3  518.60  3952.8  516.59  4293.6  515.44  4573.2  515.82
  4673.4  514.16  4885.0  515.28  5028.4  513.76  5280.6  512.77  5364.6  512.24
  5365.2  510.80  5367.7  510.00  5383.5  510.80  5384.7  512.08  5404.7  512.65
  5796.0  514.47  6125.8  519.66  6158.2  518.20  6220.8  521.60  6510.1  523.14
  6546.5  525.67  6553.2  524.09  6588.8  523.61  6909.3  525.80  7569.7  535.31
#Mann=13,-1,0
  2298.5     0.1       0  2436.9    0.05       0  3199.1     0.1       0
  3473.6    0.05       0  3701.3     0.1       0  3952.8    0.05       0
  4293.6     0.1       0  5028.4    0.05       0  5280.6     0.1       0
  5365.2    0.07       0  5383.5     0.1       0  5796.0    0.05       0
  6158.2     0.1       0
Bank Sta=5365.2,5383.5
Exp/Cntr=0.3,0.1

Type RM Length L Ch R = 1,11315,326,326,326
BEGIN DESCRIPTION:
Mapping XS b58a90fe
END DESCRIPTION:
XS GIS Cut Line= 4
      2002440.33     13527219.91      2001476.83     13527996.79
      1999172.14     13528482.90      1998191.27     13529850.05
#Sta/Elev= 30
  2253.8  540.20  2330.5  537.02  2417.2  532.00  2460.4  532.92  2730.7  523.85
  3001.0  519.26  3830.6  514.99  3978.1  512.97  4234.1  514.17  4283.9  512.39
  4350.1  513.85  4393.4  513.58  4522.5  513.04  4577.4  514.64  4893.5  513.45
  4954.8  512.12  4976.3  509.72  4978.8  508.92  4994.7  509.72  5005.0  512.31
  5036.6  512.87  5363.6  511.99  5574.3  514.67  6036.2  521.21  6069.2  520.07
  6090.1  522.39  6154.9  522.05  6798.7  526.86  7257.9  533.22  7529.5  538.83
#Mann=10,-1,0
  2253.8     0.1       0  2330.5    0.05       0  3978.1     0.1       0
  4350.1    0.07       0  4393.4     0.1       0  4976.3    0.07       0
  4994.7     0.1       0  5574.3    0.05       0  6036.2    0.08       0
  6154.9     0.1       0
Bank Sta=4976.3,4994.7
Exp/Cntr=0.3,0.1

Type RM Length L Ch R = 1,10989,1105,1105,1105
BEGIN DESCRIPTION:
Mapping XS 7aed6ee4
END DESCRIPTION:
XS GIS Cut Line= 3
      2001801.99     13526692.78      2000044.14     13527962.34
      1997559.65     13529264.25
#Sta/Elev= 30
  2711.3  540.38  2730.2  540.02  2825.4  537.11  2930.4  531.09  3139.5  519.47
  3254.8  516.52  3577.4  512.24  3793.1  514.48  4036.9  511.35  4304.5  511.48
  4467.8  512.13  4794.4  510.60  4890.0  512.51  4978.5  510.36  4982.4  508.87
  4984.9  508.07  5000.8  508.87  5064.1  511.05  5111.0  511.00  5182.3  510.46
  5295.2  512.04  5327.4  511.86  5413.7  511.84  5562.7  512.68  5910.2  519.22
  6313.2  521.11  6423.9  521.67  6539.1  521.77  6852.8  522.54  7684.6  534.23
#Mann=18,-1,0
  2711.3    0.05       0  2730.2     0.1       0  2930.4    0.05       0
  4036.9     0.1       0  4304.5    0.12       0  4467.8     0.1       0
  4982.4    0.07       0  5000.8     0.1       0  5064.1    0.05       0
  5111.0     0.1       0  5182.3    0.05       0  5295.2     0.1       0
  5327.4    0.05       0  5413.7     0.1       0  5562.7    0.05       0
  6313.2    0.08       0  6423.9    0.05       0  6539.1     0.1       0
Bank Sta=4982.4,5000.8
Exp/Cntr=0.3,0.1

Type RM Length L Ch R = 1,9884,1239,1239,1239
BEGIN DESCRIPTION:
Mapping XS b827ed42
END DESCRIPTION:
XS GIS Cut Line= 2
      2001281.14     13526269.62      1997005.97     13528765.28
#Sta/Elev= 30
  2875.9  531.00  3075.6  525.38  3176.2  523.34  3469.7  512.60  3585.6  510.96
  3704.6  509.82  3870.7  510.82  4009.6  510.45  4040.9  509.26  4046.8  510.34
  4062.5  510.70  4155.7  509.90  4835.0  508.96  4932.5  510.77  4978.4  509.31
  4990.4  508.82  4994.2  507.25  4996.7  506.45  5010.1  506.45  5012.6  507.25
  5019.1  509.18  5142.3  511.26  5465.2  512.18  5858.9  517.83  6414.7  516.70
  6773.6  518.29  7161.3  522.88  7423.4  527.22  7618.4  528.92  7826.2  531.38
#Mann=9,-1,0
  2875.9     0.1       0  3075.6    0.05       0  3585.6     0.1       0
  4155.7    0.05       0  4835.0     0.1       0  4978.4    0.05       0
  4994.2   0.035       0  5012.6    0.05       0  7618.4     0.1       0
Bank Sta=4994.2,5012.6
Exp/Cntr=0.3,0.1

Type RM Length L Ch R = 1,8645,701,701,701
BEGIN DESCRIPTION:
Mapping XS 6a2fd994
END DESCRIPTION:
XS GIS Cut Line= 2
      2000825.42     13525520.91      1996647.91     13528211.88
#Sta/Elev= 30
  2817.0  523.13  3370.0  515.49  3391.1  513.69  3500.0  512.20  3572.6  509.61
  3630.1  510.68  3638.3  511.73  3651.2  509.30  3702.7  507.74  3974.1  507.78
  4201.8  507.79  4259.2  506.52  4425.6  508.37  4685.7  506.50  4752.4  508.21
  4830.9  508.63  4939.9  507.63  4982.4  506.07  4988.1  504.92  4990.6  504.12
  5006.5  504.92  5012.5  505.93  5148.9  508.31  5454.1  510.54  5779.4  514.74
  6148.1  512.99  6314.7  513.93  7008.8  523.87  7276.9  526.68  7786.2  532.75
#Mann=5,-1,0
  2817.0     0.1       0  3974.1    0.05       0  4988.1   0.035       0
  5006.5    0.05       0  7276.9     0.1       0
Bank Sta=4988.1,5006.5
Exp/Cntr=0.3,0.1

Type RM Length L Ch R = 1,7944,1210,1210,1210
BEGIN DESCRIPTION:
Mapping XS 7a9c0fc5
END DESCRIPTION:
XS GIS Cut Line= 2
      2000814.54     13524837.34      1996170.65     13527680.09
#Sta/Elev= 30
  2543.7  539.78  2672.1  537.27  2701.7  537.63  2723.0  535.86  2840.0  531.12
  3075.1  524.47  3640.0  509.33  3870.7  507.26  4135.2  505.95  4165.9  506.80
  4235.9  507.69  4454.3  505.43  4541.5  506.40  4578.2  505.65  4752.4  506.32
  4957.4  505.32  4990.8  504.07  4993.3  503.27  5009.2  504.07  5100.6  505.63
  5158.7  504.21  5311.5  507.38  5849.6  510.89  6017.6  510.92  6127.8  509.39
  6570.9  517.21  6934.3  521.51  7240.2  524.59  7836.1  533.51  7988.6  534.66
#Mann=8,-1,0
  2543.7    0.05       0  2840.0     0.1       0  3075.1    0.05       0
  3870.7     0.1       0  4165.9    0.05       0  4990.8   0.035       0
  5009.2    0.05       0  6934.3     0.1       0
Bank Sta=4990.8,5009.2
Exp/Cntr=0.3,0.1

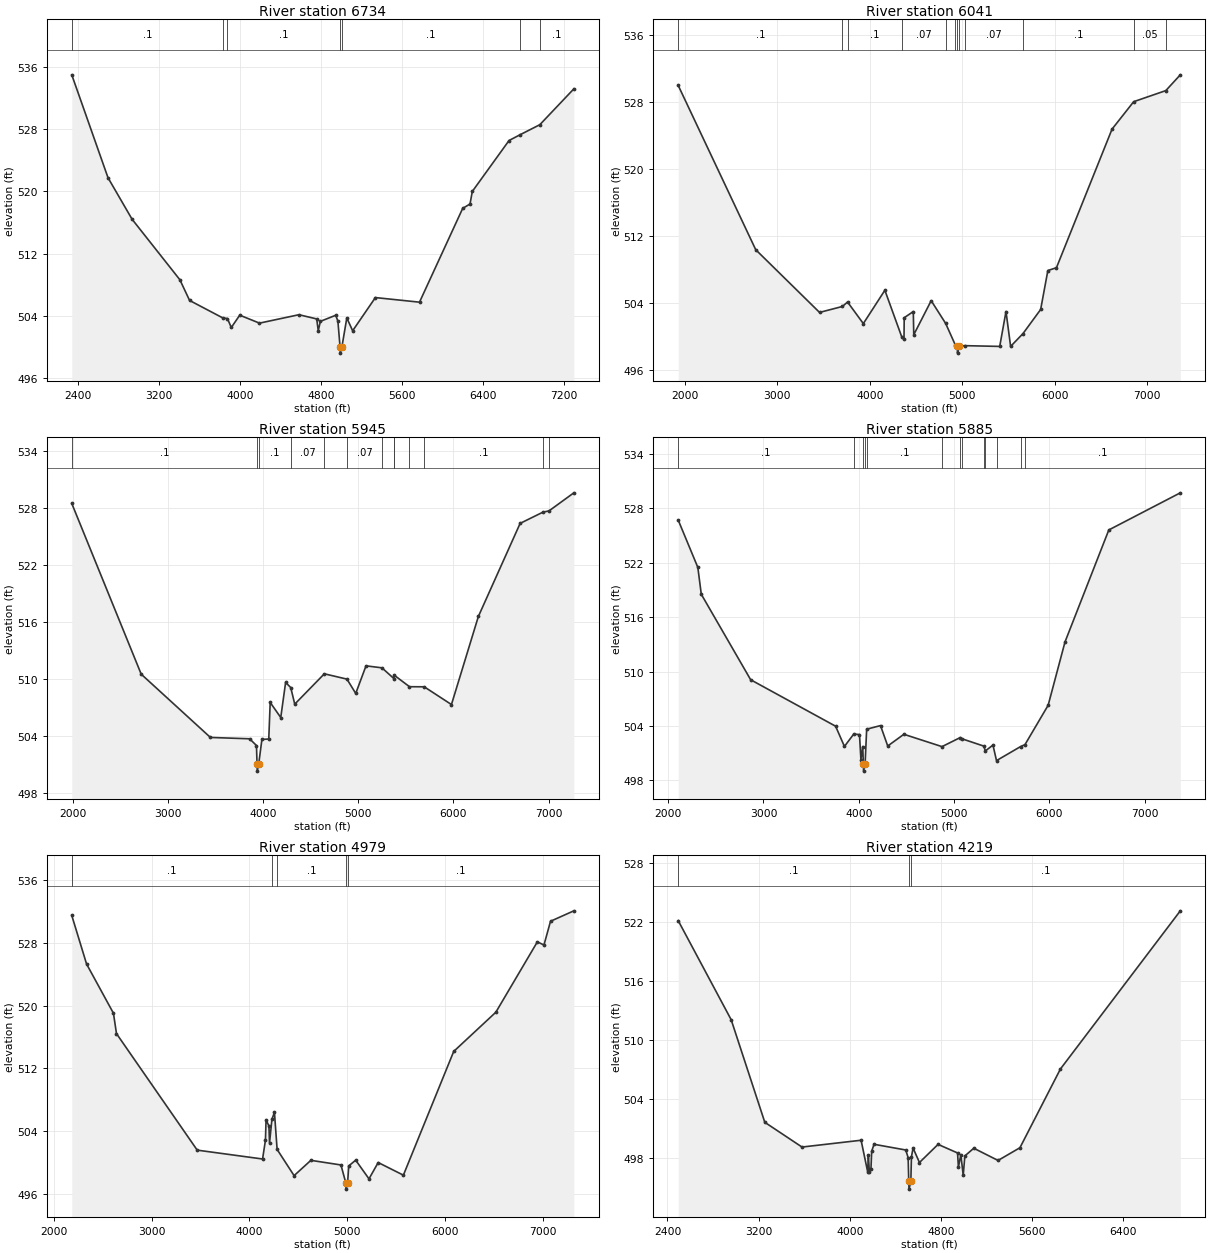
Type RM Length L Ch R = 1,6734,693,693,693
BEGIN DESCRIPTION:
Mapping XS 502228e9
END DESCRIPTION:
XS GIS Cut Line= 3
      2000320.16     13524212.35      1998216.01     13525240.12
      1996008.81     13526642.18
#Sta/Elev= 30
  2342.0  534.95  2699.8  521.74  2937.6  516.41  3409.1  508.65  3505.2  505.99
  3832.7  503.75  3878.3  503.67  3917.0  502.52  4000.2  504.10  4195.2  503.08
  4584.7  504.16  4760.0  503.62  4775.3  502.11  4796.5  503.31  4948.1  504.09
  4969.3  503.33  4990.5  500.03  4993.0  499.23  5008.9  500.03  5057.3  503.75
  5114.9  502.10  5339.4  506.36  5774.9  505.77  6201.3  517.81  6273.6  518.37
  6296.1  519.98  6658.9  526.52  6764.8  527.24  6962.9  528.55  7298.6  533.15
#Mann=7,-1,0
  2342.0     0.1       0  3832.7    0.12       0  3878.3     0.1       0
  4990.5    0.07       0  5008.9     0.1       0  6764.8    0.05       0
  6962.9     0.1       0
Bank Sta=4990.5,5008.9
Exp/Cntr=0.3,0.1

Type RM Length L Ch R = 1,6041,96,96,96
BEGIN DESCRIPTION:
Mapping XS d52256cc
END DESCRIPTION:
XS GIS Cut Line= 6
      2000163.54     13523850.77      1998281.55     13525003.57
      1998156.55     13524809.13      1997073.22     13524996.63
      1996948.22     13525434.13      1995977.25     13526481.38
#Sta/Elev= 30
  1926.7  529.95  2765.5  510.38  3456.1  502.91  3703.5  503.62  3759.2  504.15
  3929.9  501.58  4163.0  505.55  4345.8  499.99  4370.1  499.74  4372.3  502.28
  4470.7  503.01  4475.7  500.25  4664.2  504.31  4820.9  501.60  4925.0  499.04
  4946.7  498.86  4949.2  498.06  4965.1  498.86  5026.7  498.95  5406.1  498.86
  5473.9  503.02  5524.0  498.86  5658.0  500.39  5849.0  503.26  5927.0  507.90
  6020.1  508.24  6621.6  524.75  6855.8  528.02  7203.6  529.34  7360.5  531.22
#Mann=12,-1,0
  1926.7     0.1       0  3703.5    0.12       0  3759.2     0.1       0
  4345.8    0.07       0  4820.9    0.05       0  4925.0     0.1       0
  4946.7    0.07       0  4965.1     0.1       0  5026.7    0.07       0
  5658.0     0.1       0  6855.8    0.05       0  7203.6     0.1       0
Bank Sta=4946.7,4965.1
Exp/Cntr=0.3,0.1

Type RM Length L Ch R = 1,5945,60,60,60
BEGIN DESCRIPTION:
Mapping XS 6d9b1a36
END DESCRIPTION:
XS GIS Cut Line= 6
      2000031.51     13523781.38      1998295.44     13524941.07
      1998073.22     13524760.52      1997031.55     13524968.85
      1996920.44     13525378.57      1995969.54     13526357.23
#Sta/Elev= 30
  1990.7  528.51  2720.1  510.51  3447.1  503.84  3858.5  503.70  3930.6  502.99
  3936.4  501.09  3938.9  500.29  3954.8  501.09  3987.7  503.63  4059.8  503.68
  4074.8  507.53  4185.7  505.94  4236.7  509.64  4290.6  509.10  4332.6  507.35
  4643.4  510.55  4880.9  509.99  4973.3  508.48  5081.2  511.39  5248.4  511.18
  5374.1  510.05  5379.1  510.39  5537.8  509.19  5692.5  509.18  5978.5  507.31
  6261.4  516.60  6699.9  526.41  6941.1  527.60  7002.3  527.72  7264.0  529.63
#Mann=13,-1,0
  1990.7     0.1       0  3936.4    0.07       0  3954.8     0.1       0
  4290.6    0.07       0  4643.4     0.1       0  4880.9    0.07       0
  5248.4     0.1       0  5374.1    0.07       0  5379.1     0.1       0
  5537.8    0.07       0  5692.5     0.1       0  6941.1    0.05       0
  7002.3     0.1       0
Bank Sta=3936.4,3954.8
Exp/Cntr=0.3,0.1

Type RM Length L Ch R = 1,5885,906,906,906
BEGIN DESCRIPTION:
Mapping XS 0943eb45
END DESCRIPTION:
XS GIS Cut Line= 6
      1999913.46     13523725.82      1998337.11     13524823.02
      1998121.83     13524656.35      1997073.22     13524843.85
      1996864.88     13525357.74      1995838.56     13526328.58
#Sta/Elev= 30
  2105.6  526.69  2311.2  521.48  2347.4  518.52  2865.4  509.10  3756.5  503.98
  3849.0  501.75  3946.3  503.11  4007.0  503.06  4021.8  500.31  4040.9  501.74
  4047.5  499.83  4050.0  499.03  4065.9  499.83  4082.2  503.65  4227.5  504.05
  4303.3  501.80  4472.6  503.09  4872.6  501.73  5063.9  502.73  5080.2  502.60
  5310.6  501.79  5327.6  501.26  5407.2  501.90  5444.3  500.19  5697.6  501.74
  5743.0  501.95  5986.2  506.29  6163.0  513.27  6622.5  525.61  7372.5  529.70
#Mann=13,-1,0
  2105.6     0.1       0  3946.3    0.07       0  4047.5    0.07       0
  4065.9    0.07       0  4082.2     0.1       0  4872.6    0.07       0
  5063.9     0.1       0  5080.2    0.07       0  5310.6     0.1       0
  5327.6    0.07       0  5444.3     0.1       0  5697.6    0.07       0
  5743.0     0.1       0
Bank Sta=4047.5,4065.9
Exp/Cntr=0.3,0.1

Type RM Length L Ch R = 1,4979,760,760,760
BEGIN DESCRIPTION:
Mapping XS d2567e85
END DESCRIPTION:
XS GIS Cut Line= 4
      1999475.97     13523031.36      1997878.77     13523586.90
      1995746.83     13525142.46      1995385.74     13525857.70
#Sta/Elev= 30
  2185.1  531.49  2336.4  525.30  2611.0  519.03  2642.1  516.43  3467.2  501.58
  4135.2  500.45  4164.6  502.85  4170.8  505.46  4200.1  504.65  4206.3  502.49
  4230.7  505.51  4256.5  506.39  4283.8  501.67  4457.3  498.33  4628.8  500.28
  4936.3  499.69  4985.7  497.41  4988.2  496.61  5004.2  497.41  5015.8  499.57
  5086.9  500.30  5222.8  497.92  5316.8  500.00  5574.3  498.39  6088.7  514.16
  6519.5  519.16  6943.8  528.13  7011.0  527.72  7078.2  530.75  7316.5  532.08
#Mann=5,-1,0
  2185.1     0.1       0  4230.7    0.16       0  4283.8     0.1       0
  4985.7    0.07       0  5004.2     0.1       0
Bank Sta=4985.7,5004.2
Exp/Cntr=0.3,0.1

Type RM Length L Ch R = 1,4219,769,769,769
BEGIN DESCRIPTION:
Mapping XS c9a073e9
END DESCRIPTION:
XS GIS Cut Line= 4
      1998607.97     13522642.45      1997357.94     13523288.29
      1995739.88     13524579.96      1995135.71     13525288.30
#Sta/Elev= 30
  2494.5  522.13  2959.3  512.08  3254.6  501.67  3581.2  499.16  4100.1  499.85
  4157.7  496.65  4164.1  498.37  4172.2  496.66  4186.6  496.93  4193.0  498.74
  4213.8  499.44  4492.4  498.86  4513.2  498.08  4518.4  495.69  4520.9  494.89
  4536.9  495.69  4542.0  498.16  4556.4  499.06  4612.5  497.59  4775.8  499.43
  4947.1  498.56  4954.5  497.11  4975.9  498.39  4996.7  496.29  5011.2  498.26
  5089.6  499.04  5302.6  497.80  5494.7  499.09  5850.2  507.08  6902.9  523.13
#Mann=3,-1,0
  2494.5     0.1       0  4518.4    0.07       0  4536.9     0.1       0
Bank Sta=4518.4,4536.9
Exp/Cntr=0.3,0.1

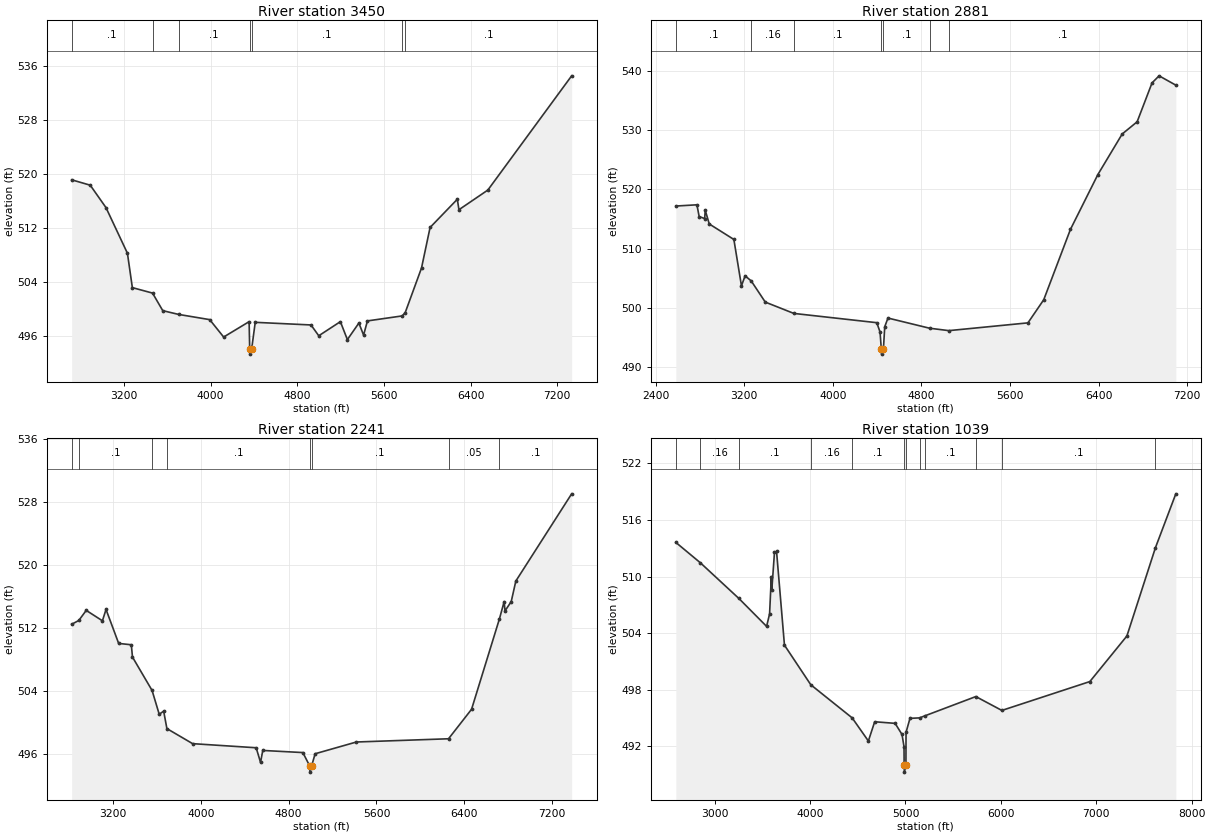
Type RM Length L Ch R = 1,3450,569,569,569
BEGIN DESCRIPTION:
Mapping XS 1ef45a22
END DESCRIPTION:
XS GIS Cut Line= 4
      1998198.21     13522461.91      1997010.72     13522843.85
      1995337.11     13524114.68      1994628.75     13525163.32
#Sta/Elev= 30
  2717.8  519.14  2889.2  518.34  3034.6  515.02  3232.4  508.26  3277.9  503.17
  3464.2  502.36  3558.5  499.76  3705.1  499.20  3991.6  498.43  4120.5  495.85
  4355.5  498.13  4360.8  494.12  4363.3  493.32  4379.3  494.12  4411.9  498.03
  4926.7  497.64  4998.2  496.04  5197.8  498.13  5262.3  495.47  5368.4  497.92
  5412.0  496.14  5447.4  498.24  5768.2  498.98  5795.8  499.46  5946.6  506.08
  6025.6  512.08  6277.0  516.26  6292.0  514.71  6558.7  517.62  7332.1  534.54
#Mann=7,-1,0
  2717.8     0.1       0  3464.2    0.16       0  3705.1     0.1       0
  4360.8    0.07       0  4379.3     0.1       0  5768.2    0.07       0
  5795.8     0.1       0
Bank Sta=4360.8,4379.3
Exp/Cntr=0.3,0.1

Type RM Length L Ch R = 1,2881,640,640,640
BEGIN DESCRIPTION:
Mapping XS 88e6791d
END DESCRIPTION:
XS GIS Cut Line= 4
      1998073.20     13522329.96      1996531.55     13522566.07
      1995142.66     13523545.24      1994205.16     13524378.57
#Sta/Elev= 30
  2583.2  517.17  2773.6  517.38  2793.8  515.40  2843.5  515.06  2848.6  516.47
  2884.9  514.15  3107.1  511.54  3175.6  503.72  3208.6  505.41  3263.6  504.55
  3390.7  500.98  3648.7  499.07  4397.1  497.51  4426.7  495.94  4438.3  493.01
  4440.8  492.21  4456.9  493.01  4469.0  496.83  4498.1  498.29  4873.1  496.58
  5047.4  496.17  5761.7  497.48  5904.4  501.38  6145.2  513.23  6392.7  522.47
  6612.7  529.32  6747.3  531.37  6881.9  537.93  6945.5  539.12  7096.5  537.55
#Mann=7,-1,0
  2583.2     0.1       0  3263.6    0.16       0  3648.7     0.1       0
  4438.3    0.07       0  4456.9     0.1       0  4873.1    0.12       0
  5047.4     0.1       0
Bank Sta=4438.3,4456.9
Exp/Cntr=0.3,0.1

Type RM Length L Ch R = 1,2241,1202,1202,1202
BEGIN DESCRIPTION:
Mapping XS 5c874b80
END DESCRIPTION:
XS GIS Cut Line= 3
      1997941.23     13522107.75      1995420.44     13522538.29
      1994101.01     13524038.27
#Sta/Elev= 30
  2823.0  512.50  2888.0  512.98  2955.7  514.26  3103.2  512.94  3136.1  514.38
  3251.2  510.07  3366.4  509.90  3377.1  508.34  3555.5  504.11  3620.6  501.09
  3661.2  501.48  3690.6  499.27  3925.0  497.36  4503.9  496.84  4543.8  494.98
  4564.1  496.50  4929.3  496.23  4991.0  494.55  4993.5  493.75  5009.6  494.55
  5040.9  496.08  5416.9  497.57  6256.3  497.98  6466.2  501.72  6719.6  513.16
  6763.2  515.38  6770.8  514.19  6827.6  515.38  6869.5  517.98  7378.0  529.04
#Mann=8,-1,0
  2823.0    0.16       0  2888.0     0.1       0  3555.5    0.16       0
  3690.6     0.1       0  4991.0    0.07       0  5009.6     0.1       0
  6256.3    0.05       0  6719.6     0.1       0
Bank Sta=4991,5009.6
Exp/Cntr=0.3,0.1

Type RM Length L Ch R = 1,1039,0,0,0
BEGIN DESCRIPTION:
Becerro Creek 1.0
END DESCRIPTION:
XS GIS Cut Line= 4
      1998406.56     13522107.74      1996125.00     13521425.00
      1995205.16     13521739.68      1994115.37     13523280.67
#Sta/Elev= 30
  2592.9  513.62  2850.1  511.46  3253.7  507.68  3544.4  504.72  3575.7  506.04
  3594.0  510.00  3599.2  508.62  3627.1  512.58  3648.8  512.66  3731.6  502.73
  4007.7  498.53  4441.4  495.02  4611.2  492.57  4677.4  494.61  4891.7  494.44
  4964.0  493.26  4984.8  491.97  4986.2  490.07  4988.7  489.27  5005.0  490.07
  5006.1  493.49  5047.4  494.97  5147.2  495.02  5201.7  495.23  5737.7  497.28
  6010.5  495.81  6933.0  498.87  7321.2  503.70  7620.1  513.05  7834.0  518.77
#Mann=12,-1,0
  2592.9     0.1       0  2850.1    0.16       0  3253.7     0.1       0
  4007.7    0.16       0  4441.4     0.1       0  4986.2    0.07       0
  5005.0     0.1       0  5147.2    0.12       0  5201.7     0.1       0
  5737.7    0.12       0  6010.5     0.1       0  7620.1    0.05       0
Bank Sta=4986.2,5005
Exp/Cntr=0.3,0.1

Chan Stop Cuts=-1