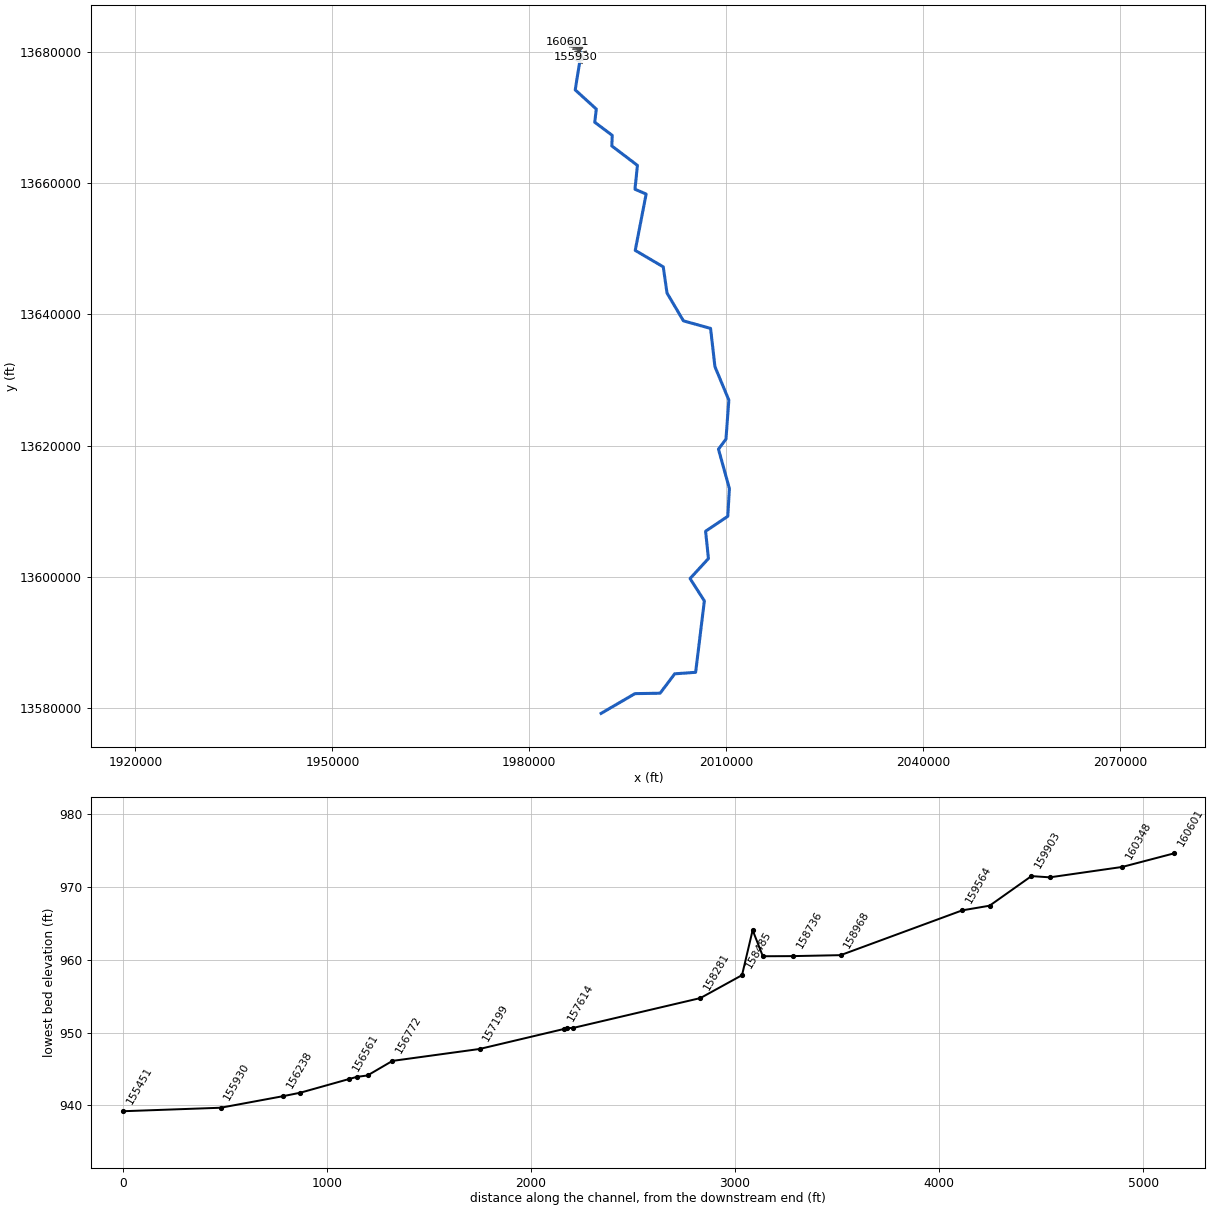
--- CHACON CREEK.prj (project) ---

Proj Title=CHACON CREEK Base Level Engineering
Current Plan=p02
Default Exp/Contr=0.3,0.1
English Units
Geom File=g01
Flow File=f01
Plan File=p02
Y Axis Title=Elevation
X Axis Title(PF)=Main Channel Distance
X Axis Title(XS)=Station
BEGIN DESCRIPTION:
CHACON CREEK
END DESCRIPTION:
DSS Export Rating Curves= 0
DSS Export Rating Curve Sorted= 0
DSS Export Volume Flow Curves= 0
DXF OffsetX= 0
DXF OffsetY= 0
DXF ScaleX= 1
DXF ScaleY= 10

--- CHACON CREEK.p02 (plan) ---

Plan Title=Multiple Run
Program Version=5.05
Short Identifier=Multiple Run
Geom File=g01
Flow File=f01
Subcritical Flow
K Sum by GR= 0
Std Step Tol= 0.01
Critical Tol= 0.01
Num of Std Step Trials= 20
Max Error Tol= 0.3
Flow Tol Ratio= 0.001
Split Flow NTrial= 30
Split Flow Tol= 0.02
Split Flow Ratio= 0.02
Log Output Level= 0
Friction Slope Method= 1
Unsteady Friction Slope Method= 2
Unsteady Bridges Friction Slope Method= 1
Parabolic Critical Depth
Global Vel Dist= 1 , 1 , 1
Global Log Level= 0
CheckData=True
Encroach Param=-1 ,0,0, 0
BEGIN DESCRIPTION:
Multiple Run
END DESCRIPTION:
Computation Interval=1MIN
Output Interval=1HOUR
Instantaneous Interval=1HOUR
Mapping Interval=1HOUR
Computation Time Step Use Courant=        0
Computation Time Step Use Time Series=    0
Computation Time Step Count To Double=0
Computation Time Step Max Doubling=0
Computation Time Step Max Halving=0
Computation Time Step Residence Courant=0
Run HTab= 0
Run UNet= 0
Run Sediment= 0
Run PostProcess= 0
Run WQNet= 0
Run RASMapper= 0
UNET Theta= 1
UNET Theta Warmup= 1
UNET ZTol= 0.02
UNET ZSATol= 0.02
UNET MxIter= 20
UNET Max Iter WO Improvement= 0
UNET MaxInSteps= 0
UNET DtIC= 0
UNET DtMin= 0
UNET MaxCRTS= 20
UNET WFStab= 2
UNET SFStab= 1
UNET WFX= 1
UNET SFX= 1
UNET 1D Methodology=Finite Difference
UNET DSS MLevel= 4
UNET Pardiso=0
UNET DZMax Abort= 100
UNET Use Existing IB Tables=-1
UNET Froude Reduction=False
UNET Froude Limit= 0.8
UNET Froude Power= 4
UNET D1 Cores= 0
UNET D2 Coriolis=0
UNET D2 Cores= 0
UNET D2 Theta= 1
UNET D2 Theta Warmup= 1
UNET D2 Z Tol= 0.01
UNET D2 Volume Tol= 0.01
UNET D2 Max Iterations= 20
UNET D2 Equation= 0
UNET D2 RampUpFraction=0.1
UNET D2 TimeSlices= 1
UNET D2 BCVolumeCheck=0
UNET D1D2 MaxIter= 0
UNET D1D2 ZTol=0.01
UNET D1D2 QTol=0.1
UNET D1D2 MinQTol=1
Write IC File= 0
Write IC File at Fixed DateTime=0
Write IC File at Sim End=0
Echo Input=False
Echo Parameters=False
Echo Output=False
Write Detailed= 0
HDF Write Warmup=0
HDF Write Time Slices=0
HDF Flush=0
HDF Face Node Velocities=0
HDF Compression= 1
HDF Chunk Size= 1
HDF Spatial Parts= 1
HDF Use Max Rows=0
HDF Fixed Rows= 1
Calibration Method= 0
Calibration Iterations= 20
Calibration Max Change=0.05
Calibration Tolerance=0.2
Calibration Maximum=1.5
Calibration Minimum=0.5
Calibration Optimization Method= 1
WQ AD Non Conservative
WQ ULTIMATE=-1
WQ Max Comp Step=1HOUR
WQ Output Interval=15MIN
WQ Output Selected Increments= 0
WQ Output face flow=0
WQ Output face velocity=0
WQ Output face area=0
WQ Output face dispersion=0
WQ Output cell volume=0
WQ Output cell surface area=0
WQ Output cell continuity=0
WQ Output cumulative cell continuity=0
WQ Output face conc=0
WQ Output face dconc_dx=0
WQ Output face courant=0
WQ Output face peclet=0
WQ Output face adv mass=0
WQ Output face disp mass=0
WQ Output cell mass=0
WQ Output cell source sink temp=0
WQ Output nsm pathways=0
WQ Output nsm derived pathways=0
WQ Output MaxMinRange=-1
WQ Daily Max Min Mean=-1
WQ Daily Range=0
WQ Daily Time=0
WQ Create Restart=0
WQ Fixed Restart=0
WQ System Summary=0
WQ Write To DSS=0
WQ Use Fixed Temperature=0
Sorting and Armoring Iterations= 10
XS Update Threshold= 0.02
Bed Roughness Predictor= 0
Hydraulics Update Threshold= 0.02
Energy Slope Method= 1
Volume Change Method= 1
Sediment Retention Method= 0
XS Weighting Method= 0
Number of US Weighted Cross Sections= 1
Number of DS Weighted Cross Sections= 1
Upstream XS Weight=0
Main XS Weight=1
Downstream XS Weight=0
Number of DS XS's Weighted with US Boundary= 1
Upstream Boundary Weight= 1
Weight of XSs Associated with US Boundary= 0
Number of US XS's Weighted with DS Boundary= 1
Downstream Boundary Weight= 0.5
Weight of XSs Associated with DS Boundary= 0.5
Percentile Method= 0
Sediment Output Level= 3
Mass or Volume Output= 0
Output Increment Type= 1
Profile and TS Output Increment= 1
XS Output Flag= 0
XS Output Increment= 10
Write Gradation File= 0
Read Gradation Hotstart= 0
Write HDF5 File= 1
Write Binary Output= 1
Write DSS Sediment File= 0
SV Curve= 0
Specific Gage Flag= 0

--- CHACON CREEK.f01 (steady flow) ---

Flow Title=Multiple
Program Version=5.05
Number of Profiles= 7
Profile Names=10-year,25-year,50-year,1pct_min,100-year,1pct_plu,500-year
River Rch & RM=CHACON CREEK,Reach-1         ,160601
     469     643     784     474     946    1888    1380
River Rch & RM=CHACON CREEK,Reach-1         ,159993
     910    1301    1632    1013    2020    4031    3106
River Rch & RM=CHACON CREEK,Reach-1         ,154111
    1104    1593    2011    1255    2504    4996    3895
River Rch & RM=CHACON CREEK,Reach-1         ,150559
    1452    2127    2714    1709    3409    6802    5403
River Rch & RM=CHACON CREEK,Reach-1         ,149574
    1567    2304    2945    1858    3708    7398    5902
River Rch & RM=CHACON CREEK,Reach-1         ,148863
    1567    2304    2945    1858    3708    7398    5902
River Rch & RM=CHACON CREEK,Reach-1         ,148013
    1742    2573    3300    2088    4166    8313    6671
River Rch & RM=CHACON CREEK,Reach-1         ,145362
    2084    3094    3981    2525    5038   10053    8107
River Rch & RM=CHACON CREEK,Reach-1         ,138793
    2313    3447    4446    2826    5640   11252    9114
River Rch & RM=CHACON CREEK,Reach-1         ,137319
    2313    3447    4446    2826    5640   11252    9114
River Rch & RM=CHACON CREEK,Reach-1         ,130981
    2535    3790    4900    3122    6228   12427   10107
River Rch & RM=CHACON CREEK,Reach-1         ,129428
    3241    4894    6370    4083    8146   16253   13382
River Rch & RM=CHACON CREEK,Reach-1         ,126577
    3336    5038    6558    4203    8386   16732   13771
River Rch & RM=CHACON CREEK,Reach-1         ,123231
    3742    5668    7393    4746    9469   18893   15602
River Rch & RM=CHACON CREEK,Reach-1         ,119408
    3793    5744    7490    4807    9591   19137   15796
River Rch & RM=CHACON CREEK,Reach-1         ,118131
    3793    5744    7490    4807    9591   19137   15796
River Rch & RM=CHACON CREEK,Reach-1         ,114583
    3946    5978    7798    5005    9986   19924   16447
River Rch & RM=CHACON CREEK,Reach-1         ,110508
    4029    6107    7969    5116   10208   20367   16824
River Rch & RM=CHACON CREEK,Reach-1         ,109501
    4161    6306    8227    5280   10536   21021   17353
River Rch & RM=CHACON CREEK,Reach-1         ,105759
    4784    7287    9541    6144   12259   24460   20323
River Rch & RM=CHACON CREEK,Reach-1         ,105172
    4866    7404    9687    6233   12436   24814   20583
River Rch & RM=CHACON CREEK,Reach-1         ,99102
    4957    7542    9867    6347   12664   25268   20952
River Rch & RM=CHACON CREEK,Reach-1         ,98079
    4957    7542    9867    6347   12664   25268   20952
River Rch & RM=CHACON CREEK,Reach-1         ,97804
    5061    7703   10082    6488   12944   25827   21427
River Rch & RM=CHACON CREEK,Reach-1         ,97128
    5061    7703   10082    6488   12944   25827   21427
River Rch & RM=CHACON CREEK,Reach-1         ,92692
    5155    7842   10259    6598   13165   26267   21767
River Rch & RM=CHACON CREEK,Reach-1         ,90889
    5612    8540   11175    7187   14340   28612   23708
River Rch & RM=CHACON CREEK,Reach-1         ,88813
    5612    8540   11175    7187   14340   28612   23708
River Rch & RM=CHACON CREEK,Reach-1         ,79316
    5707    8694   11383    7325   14615   29161   24191
River Rch & RM=CHACON CREEK,Reach-1         ,75560
    5707    8694   11383    7325   14615   29161   24191
River Rch & RM=CHACON CREEK,Reach-1         ,73049
    5795    8826   11555    7435   14835   29599   24548
River Rch & RM=CHACON CREEK,Reach-1         ,71824
    5795    8826   11555    7435   14835   29599   24548
River Rch & RM=CHACON CREEK,Reach-1         ,70713
    5828    8880   11628    7483   14931   29791   24718
River Rch & RM=CHACON CREEK,Reach-1         ,69358
    5828    8880   11628    7483   14931   29791   24718
River Rch & RM=CHACON CREEK,Reach-1         ,68792
    5777    8792   11504    7397   14759   29449   24394
River Rch & RM=CHACON CREEK,Reach-1         ,67142
    5777    8792   11504    7397   14759   29449   24394
River Rch & RM=CHACON CREEK,Reach-1         ,65901
    6207    9453   12375    7959   15881   31687   26261
River Rch & RM=CHACON CREEK,Reach-1         ,58694
    7900   12089   15881   10244   20440   40784   33991
River Rch & RM=CHACON CREEK,Reach-1         ,56789
    7900   12089   15881   10244   20440   40784   33991
River Rch & RM=CHACON CREEK,Reach-1         ,44660
    8353   12795   16819   10856   21661   43219   36062
River Rch & RM=CHACON CREEK,Reach-1         ,42277
    8353   12795   16819   10856   21661   43219   36062
River Rch & RM=CHACON CREEK,Reach-1         ,41108
    8829   13507   17741   11439   22825   45541   37917
River Rch & RM=CHACON CREEK,Reach-1         ,37010
    8829   13507   17741   11439   22825   45541   37917
River Rch & RM=CHACON CREEK,Reach-1         ,21902
    8820   13475   17683   11392   22729   45351   37687
River Rch & RM=CHACON CREEK,Reach-1         ,20892
    8820   13475   17683   11392   22729   45351   37687
River Rch & RM=CHACON CREEK,Reach-1         ,14124
    8890   13585   17828   11485   22916   45724   38001
River Rch & RM=CHACON CREEK,Reach-1         ,11506
    8890   13585   17828   11485   22916   45724   38001
River Rch & RM=CHACON CREEK,Reach-1         ,10552
    8982   13714   17988   11581   23107   46104   38268
Boundary for River Rch & Prof#=CHACON CREEK,Reach-1         , 1
Up Type= 0
Dn Type= 1
Dn Known WS=600.29
Boundary for River Rch & Prof#=CHACON CREEK,Reach-1         , 2
Up Type= 0
Dn Type= 1
Dn Known WS=601.35
Boundary for River Rch & Prof#=CHACON CREEK,Reach-1         , 3
Up Type= 0
Dn Type= 1
Dn Known WS=602.07
Boundary for River Rch & Prof#=CHACON CREEK,Reach-1         , 4
Up Type= 0
Dn Type= 1
Dn Known WS=601.34
Boundary for River Rch & Prof#=CHACON CREEK,Reach-1         , 5
Up Type= 0
Dn Type= 1
Dn Known WS=602.73
Boundary for River Rch & Prof#=CHACON CREEK,Reach-1         , 6
Up Type= 0
Dn Type= 1
Dn Known WS=604.59
Boundary for River Rch & Prof#=CHACON CREEK,Reach-1         , 7
Up Type= 0
Dn Type= 1
Dn Known WS=604.65
DSS Import GetInterval= 0
DSS Import GetPeak= 0
DSS Import FillOption= 0

--- CHACON CREEK.g01 (geometry) ---

Geom Title=Existing Conditions
Program Version=5.05

River Reach=CHACON CREEK    ,Reach-1
Reach XY= 30
      1986058.99     13682087.01       1987890.8     13679864.54
      1986990.06     13674225.28       1990200.8     13671304.54
       1989960.8     13669294.54      1992627.09     13667293.03
      1992567.69     13665678.97      1996463.29     13662718.27
       1996091.7     13659078.73       1997790.8     13658344.54
       1996130.8     13649754.54      2000398.23     13647244.89
       2000970.8     13643254.54       2003470.8     13639014.54
      2007607.24     13637858.73       2008270.8     13632031.26
       2010390.8     13626934.54       2009950.8     13620984.54
       2008810.8     13619444.54      2010474.06      13613433.2
       2010230.8     13609214.54       2006850.7     13606934.12
      2007283.63     13602770.96      2004484.62     13599721.99
       2006660.8     13596314.54       2005330.8     13585424.54
       2002140.8     13585194.54      1999919.39      13582236.8
       1996090.8     13582174.54       1990930.8     13579164.54

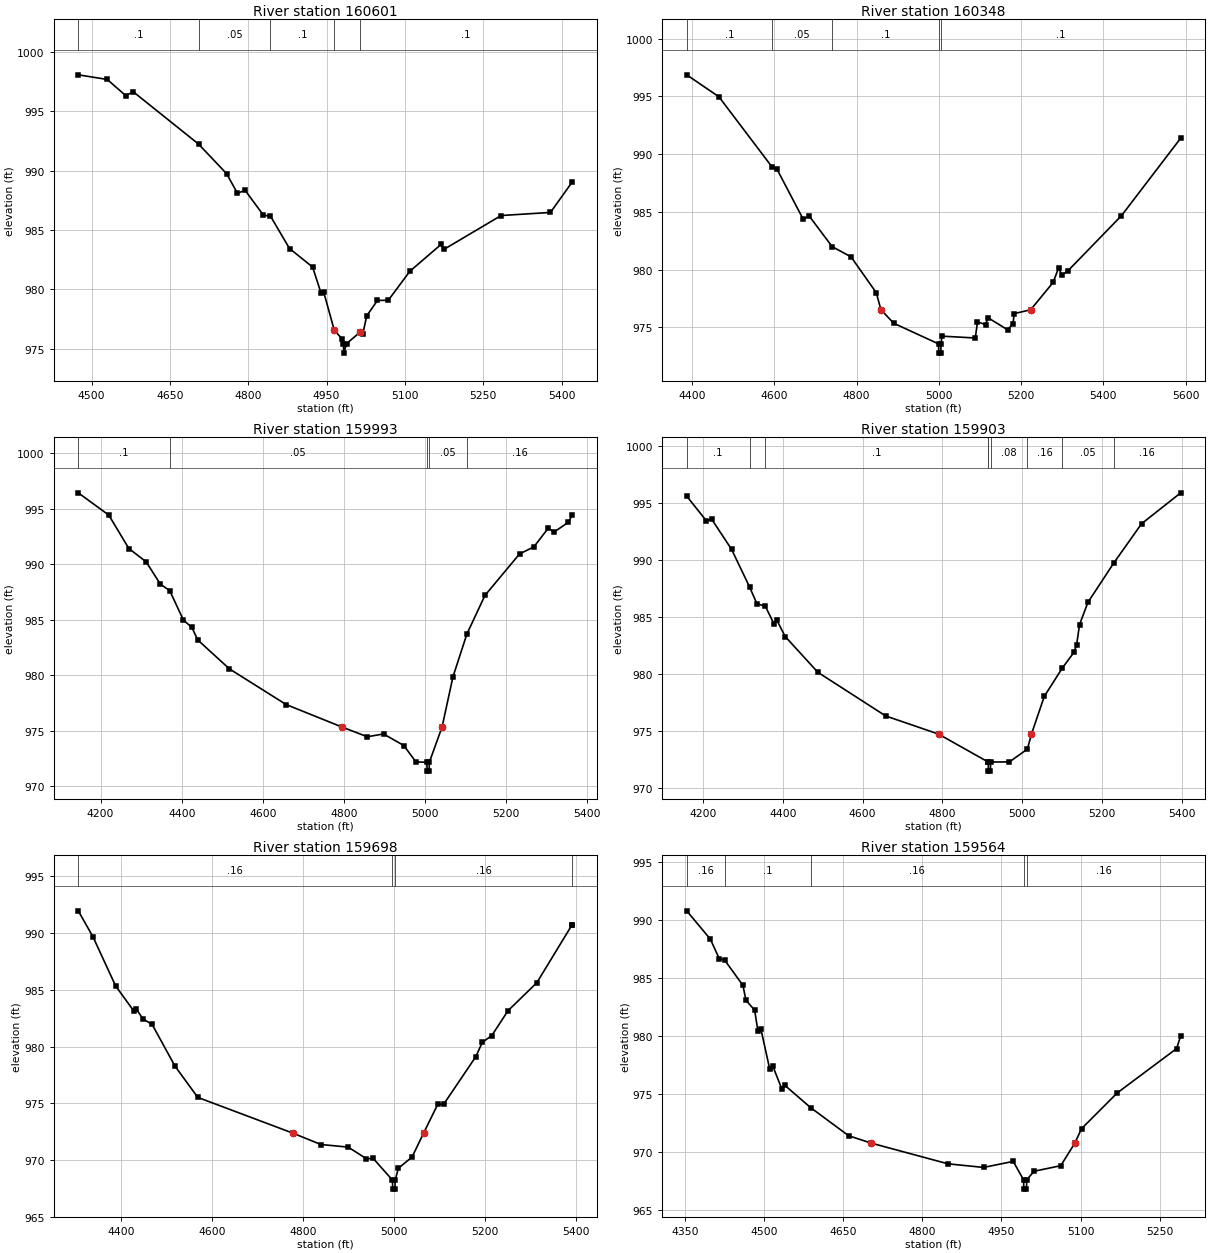
Type RM Length L Ch R = 1 ,160601  ,253,253,253
BEGIN DESCRIPTION:
CHACON CREEK 227.0
END DESCRIPTION:
XS GIS Cut Line= 3
      1986622.41     13681945.05      1986270.87     13681675.97
      1985784.71     13681545.75
#Sta/Elev= 30
  4474.4  998.08  4529.9  997.69  4565.3  996.33  4579.8  996.65  4704.7  992.25
  4758.4  989.76  4779.3   988.1  4793.8  988.36  4829.1  986.25  4842.5  986.18
    4879  983.45  4923.2  981.89  4939.4  979.69  4944.6  979.76  4964.6  976.58
  4979.5  975.84  4982.3  975.44  4982.8  974.64  4988.3  975.44  5014.3  976.42
  5019.5  976.28  5026.7  977.77  5047.4  979.08  5068.1  979.09  5109.5  981.54
  5169.3   983.8  5174.4  983.37  5284.2  986.23  5378.7  986.49  5420.4  989.06
#Mann= 5 ,-1 , 0
  4474.4      .1       0  4704.7     .05       0  4842.5      .1       0
  4964.6     .07       0  5014.3      .1       0
Bank Sta=4964.6,5014.3
XS Rating Curve= 0 ,0
Exp/Cntr=0.3,0.1

Type RM Length L Ch R = 1 ,160348  ,355,355,355
BEGIN DESCRIPTION:
Mapping XS 7b674706
END DESCRIPTION:
XS GIS Cut Line= 4
      1986594.25     13681885.58      1986294.74     13681625.15
      1986158.03     13681249.71      1985808.54     13681045.75
#Sta/Elev= 30
    4387  996.87  4465.3  994.97    4595  988.87  4606.8  988.68  4670.4  984.36
  4684.6  984.66  4740.6     982  4786.6  981.11  4847.9  978.01 4859.23976.5344
  4890.6  975.36  4999.3  973.58  4999.8  972.78  5004.8  972.78  5005.3  973.58
  5007.6  974.25  5088.7  974.09    5094  975.49  5113.9  975.24  5119.3  975.85
  5167.2   974.8  5180.4  975.34  5183.3   976.2 5223.21976.5337  5277.9   978.9
  5291.2  980.16  5299.4  979.53  5314.3  979.92  5444.1  984.68  5588.1  991.39
#Mann= 5 ,-1 , 0
    4387      .1       0    4595     .05       0  4740.6      .1       0
  4999.3     .07       0  5005.3      .1       0
Bank Sta=4859.23,5223.21
XS Rating Curve= 0 ,0
Exp/Cntr=0.3,0.1

Type RM Length L Ch R = 1 ,159993  ,90,90,90
BEGIN DESCRIPTION:
Mapping XS bd77a96d
END DESCRIPTION:
XS GIS Cut Line= 4
      1986605.06     13681871.27      1986368.53     13681662.04
      1986357.68     13681082.61      1986162.36     13680825.26
#Sta/Elev= 30
  4144.8  996.44  4220.2  994.43  4269.6  991.42  4312.3  990.22  4347.4   988.2
  4370.3  987.63  4404.3  984.96  4425.2   984.3  4439.4  983.18  4517.6  980.57
  4657.7  977.35 4795.25975.3266  4857.7  974.45  4897.7   974.7  4947.7  973.66
  4977.7  972.18  5004.7  972.15  5005.2  971.35  5010.2  971.35  5010.7  972.15
  5042.1975.3275  5068.9  979.84  5103.4  983.72  5147.9  987.19  5233.2  990.93
  5268.6  991.57    5304  993.25  5318.5  992.91  5353.9  993.79  5363.2  994.46
#Mann= 5 ,-1 , 0
  4144.8      .1       0  4370.3     .05       0  5004.7     .04       0
  5010.7     .05       0  5103.4     .16       0
Bank Sta=4795.25,5042.1
XS Rating Curve= 0 ,0
Exp/Cntr=0.3,0.1

Type RM Length L Ch R = 1 ,159903  ,205,205,205
BEGIN DESCRIPTION:
CHACON CREEK 226.0
END DESCRIPTION:
XS GIS Cut Line= 4
      1986628.96       13681840.      1986433.63     13681653.36
      1986440.14       13681011.      1986198.53     13680793.12
#Sta/Elev= 30
  4159.4  995.63  4208.1  993.49  4222.2   993.6  4271.9  990.96  4316.9  987.67
  4335.4  986.19  4356.3  985.98  4377.9  984.45  4385.1  984.77  4406.2  983.32
  4487.9  980.19  4657.9  976.36 4790.45974.7674  4914.8  972.32  4914.9  972.32
  4915.4  971.52  4920.4  971.52  4920.9  972.32    4968  972.33  5013.2  973.45
 5023.34974.7678  5055.4  978.07  5100.3  980.54  5129.6  981.93  5136.3  982.57
  5143.8  984.37  5164.7  986.31  5229.2  989.75  5299.2  993.21  5397.3  995.92
#Mann= 9 ,-1 , 0
  4159.4      .1       0  4316.9     .16       0  4356.3      .1       0
  4914.8     .08       0  4914.9     .07       0  4920.9     .08       0
  5013.2     .16       0  5100.3     .05       0  5229.2     .16       0
Bank Sta=4790.45,5023.34
XS Rating Curve= 0 ,0
Exp/Cntr=0.3,0.1

Type RM Length L Ch R = 1 ,159698  ,134,134,134
BEGIN DESCRIPTION:
CHACON CREEK 225.0
END DESCRIPTION:
XS GIS Cut Line= 3
      1986689.71     13681777.09      1986628.95     13680987.13
      1986424.97     13680774.97
#Sta/Elev= 30
  4305.4  991.96  4337.6  989.69  4387.7  985.34  4427.4  983.15  4432.4  983.34
  4447.9  982.44    4468  981.95  4518.1  978.29  4568.3  975.53 4777.19972.3859
  4839.1  971.38  4899.2  971.15  4939.4  970.12    4954  970.16  4996.5  968.25
    4997  967.45    5002  967.45  5002.5  968.25  5009.6  969.29  5039.7  970.28
 5065.06972.3857  5096.3  974.93  5109.1  974.92  5179.8  979.11    5194  980.37
  5215.1  980.98  5250.6  983.16  5314.1  985.63  5390.7  990.67    5392  990.67
#Mann= 4 ,-1 , 0
  4305.4     .16       0  4996.5     .07       0  5002.5     .16       0
  5390.7     .05       0
Bank Sta=4777.19,5065.06
XS Rating Curve= 0 ,0
Exp/Cntr=0.3,0.1

Type RM Length L Ch R = 1 ,159564  ,596,596,596
BEGIN DESCRIPTION:
Mapping XS 0b79b858
END DESCRIPTION:
XS GIS Cut Line= 2
      1987039.51     13681690.64      1986628.18     13680849.76
#Sta/Elev= 30
  4353.5  990.79  4398.3  988.35  4415.3  986.66  4425.3  986.55    4460  984.37
  4465.9  983.07  4482.2  982.24  4488.4  980.44  4493.9  980.64  4510.9  977.14
  4516.4  977.44  4533.4  975.48    4539  975.77  4588.7  973.82  4660.4  971.41
 4703.06 970.776  4848.6  968.99  4916.1  968.68  4972.2   969.2  4991.8  967.61
  4992.3  966.81  4997.3  966.81  4997.8  967.61  5011.7  968.35  5062.3  968.83
 5088.96 970.776  5101.7  972.02  5169.3   975.1  5281.8  978.92  5289.6  980.02
#Mann= 5 ,-1 , 0
  4353.5     .16       0  4425.3      .1       0  4588.7     .16       0
  4991.8     .07       0  4997.8     .16       0
Bank Sta=4703.06,5088.96
XS Rating Curve= 0 ,0
Exp/Cntr=0.3,0.1

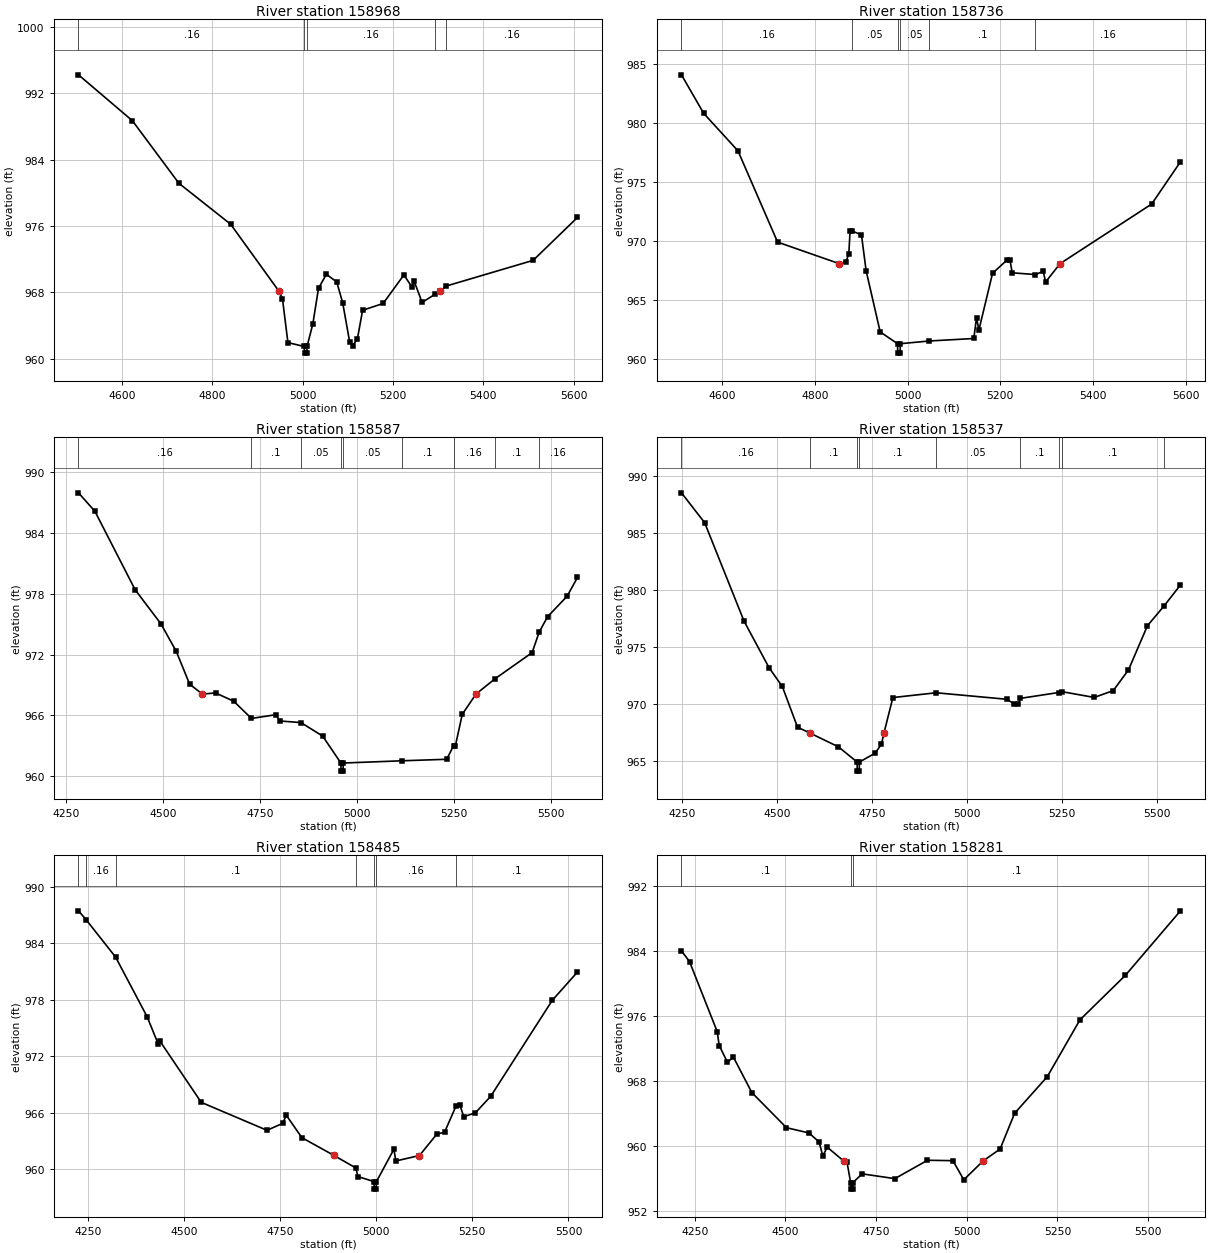
Type RM Length L Ch R = 1 ,158968  ,232,232,232
BEGIN DESCRIPTION:
Mapping XS db846a5e
END DESCRIPTION:
XS GIS Cut Line= 2
       1987695.8     13681331.32      1986693.17     13680867.77
#Sta/Elev= 30
  4503.9  994.22  4623.3  988.68  4726.1  981.14  4840.7   976.2 4947.68968.1146
  4955.4  967.21  4967.5  961.92  5003.7  961.45  5004.2  960.65  5009.3  960.65
  5009.8  961.45  5022.6  964.16  5035.2  968.47  5052.6  970.16  5075.5  969.24
  5088.7  966.73    5104  962.05  5110.7  961.53  5121.4   962.4  5132.8  965.82
  5178.3  966.64  5224.2  970.08  5241.6  968.66  5247.1   969.3  5264.5  966.77
  5294.1  967.78 5304.07968.1146  5318.4  968.75  5510.3  971.84  5608.5  977.02
#Mann= 5 ,-1 , 0
  4503.9     .16       0  5003.7     .07       0  5009.8     .16       0
  5294.1      .1       0  5318.4     .16       0
Bank Sta=4947.68,5304.07
XS Rating Curve= 0 ,0
Exp/Cntr=0.3,0.1

Type RM Length L Ch R = 1 ,158736  ,149,149,149
BEGIN DESCRIPTION:
Mapping XS 2ec85855
END DESCRIPTION:
XS GIS Cut Line= 3
      1987720.98     13681104.76      1987408.46     13680917.25
       1986703.6     13680820.03
#Sta/Elev= 30
  4512.5  984.11  4560.5  980.84  4634.3  977.67  4719.8  969.93 4852.76968.1038
  4867.6  968.28  4873.4  968.96  4876.1  970.88  4879.7  970.88  4900.6  970.55
  4910.7   967.5    4941  962.32  4978.4  961.32  4978.9  960.52    4984  960.52
  4984.5  961.32  5047.2  961.55  5142.9  961.76  5148.8  963.53  5153.8  962.47
  5183.3  967.29  5213.6  968.38  5220.7  968.45  5225.7  967.33  5275.4  967.18
  5292.6  967.45  5297.7  966.55 5328.86968.1035  5526.5  973.16  5588.5  976.74
#Mann= 6 ,-1 , 0
  4512.5     .16       0  4879.7     .05       0  4978.4    .033       0
  4984.5     .05       0  5047.2      .1       0  5275.4     .16       0
Bank Sta=4852.76,5328.86
XS Rating Curve= 0 ,0
Exp/Cntr=0.3,0.1

Type RM Length L Ch R = 1 ,158587  ,50,50,50
BEGIN DESCRIPTION:
Mapping XS f4bc0896
END DESCRIPTION:
XS GIS Cut Line= 4
       1987965.8       13680896.      1987451.43     13680754.92
      1987015.23     13680748.41       1986698.1     13680733.31
#Sta/Elev= 30
  4282.4  987.97  4324.7  986.15  4428.4  978.41    4495  975.04  4534.6  972.32
  4569.1  969.08 4602.12968.1015  4635.8  968.22  4682.8   967.4  4728.6   965.7
  4791.3  966.07  4801.7  965.45  4856.3  965.29  4912.2  963.96  4959.2   961.3
  4959.7   960.5  4964.8   960.5  4965.3   961.3  5116.7  961.52  5232.2  961.67
  5249.9  963.01  5254.6  963.01  5272.3  966.11 5307.57968.1015  5355.5  969.58
  5452.5   972.2  5470.7  974.23  5492.5  975.75  5542.6  977.76  5569.5  979.62
#Mann= 9 ,-1 , 0
  4282.4     .16       0  4728.6      .1       0  4856.3     .05       0
  4959.2    .033       0  4965.3     .05       0  5116.7      .1       0
  5249.9     .16       0  5355.5      .1       0  5470.7     .16       0
Bank Sta=4602.12,5307.57
XS Rating Curve= 0 ,0
Exp/Cntr=0.3,0.1

Type RM Length L Ch R = 1 ,158537  ,52,52,52
BEGIN DESCRIPTION:
CHACON CREEK 222.0
END DESCRIPTION:
XS GIS Cut Line= 3
      1987993.97     13680839.56      1987501.34     13680707.18
      1986698.09     13680692.02
#Sta/Elev= 30
  4248.4  988.49  4309.5  985.87    4413  977.25  4479.1  973.15  4513.9  971.51
  4553.9  967.94 4585.45967.4495  4587.1  967.42  4661.5  966.22  4710.7  964.89
  4711.2  964.09  4716.3  964.09  4716.8  964.89  4758.5  965.67  4774.8  966.46
 4781.58967.4499  4804.9  970.54  4918.8  970.96  5104.9  970.39  5124.9  969.97
  5134.5  969.95  5140.7  970.47    5241  970.98  5249.3  971.06  5334.9  970.55
    5385  971.15    5425  972.96    5475  976.84  5518.4  978.56  5561.9  980.41
#Mann= 9 ,-1 , 0
  4248.4     .16       0  4587.1      .1       0  4710.7    .033       0
  4716.8      .1       0  4918.8     .05       0  5140.7      .1       0
    5241     .16       0  5249.3      .1       0  5518.4     .16       0
Bank Sta=4585.45,4781.58
XS Rating Curve= 0 ,0
Exp/Cntr=0.3,0.1

Type RM Length L Ch R = 1 ,158485  ,204,204,204
BEGIN DESCRIPTION:
CHACON CREEK 221.0
END DESCRIPTION:
XS GIS Cut Line= 3
      1988022.22     13680733.23      1987299.52     13680652.93
      1986729.43     13680635.59
#Sta/Elev= 30
    4226  987.47  4246.1  986.51  4322.4  982.56  4404.3  976.23  4432.9  973.36
  4437.9  973.62  4545.2  967.12  4716.2  964.15  4756.5  964.88  4766.5  965.74
  4806.8  963.37 4890.51961.4733    4947  960.15  4952.9  959.23  4994.6   958.7
  4995.1   957.9  5000.2   957.9  5000.7   958.7  5046.1  962.14  5051.1  960.89
 5112.66961.4728  5157.8  963.75  5177.8  963.94  5207.1  966.68  5217.8   966.8
  5227.8   965.6  5257.8     966  5297.8  967.76  5457.9  977.96  5523.5  980.97
#Mann= 7 ,-1 , 0
    4226      .1       0  4246.1     .16       0  4322.4      .1       0
    4947     .16       0  4994.6     .07       0  5000.7     .16       0
  5207.1      .1       0
Bank Sta=4890.51,5112.66
XS Rating Curve= 0 ,0
Exp/Cntr=0.3,0.1

Type RM Length L Ch R = 1 ,158281  ,624,624,624
BEGIN DESCRIPTION:
CHACON CREEK 220.0
END DESCRIPTION:
XS GIS Cut Line= 3
      1987975.04     13680675.02      1987549.95     13680466.73
      1986648.11     13680422.55
#Sta/Elev= 30
  4213.1  984.07  4235.4  982.74  4311.6  974.14  4317.2  972.42  4339.7  970.39
  4356.6  970.97  4407.2  966.63  4502.7  962.31  4564.7  961.66  4592.7  960.56
  4602.9  958.84  4615.2  959.91 4660.11 958.229  4669.7  958.08  4679.7  955.55
  4680.2  954.75  4685.3  954.75  4685.8  955.55  4711.5  956.63  4801.6  956.04
  4891.7   958.3  4961.8  958.25  4991.8   955.9  5045.4958.2289  5091.9  959.68
    5132  964.08  5222.1  968.59  5312.2  975.58  5437.2  981.04  5589.4  988.99
#Mann= 3 ,-1 , 0
  4213.1      .1       0  4679.7     .07       0  4685.8      .1       0
Bank Sta=4660.11,5045.4
XS Rating Curve= 0 ,0
Exp/Cntr=0.3,0.1

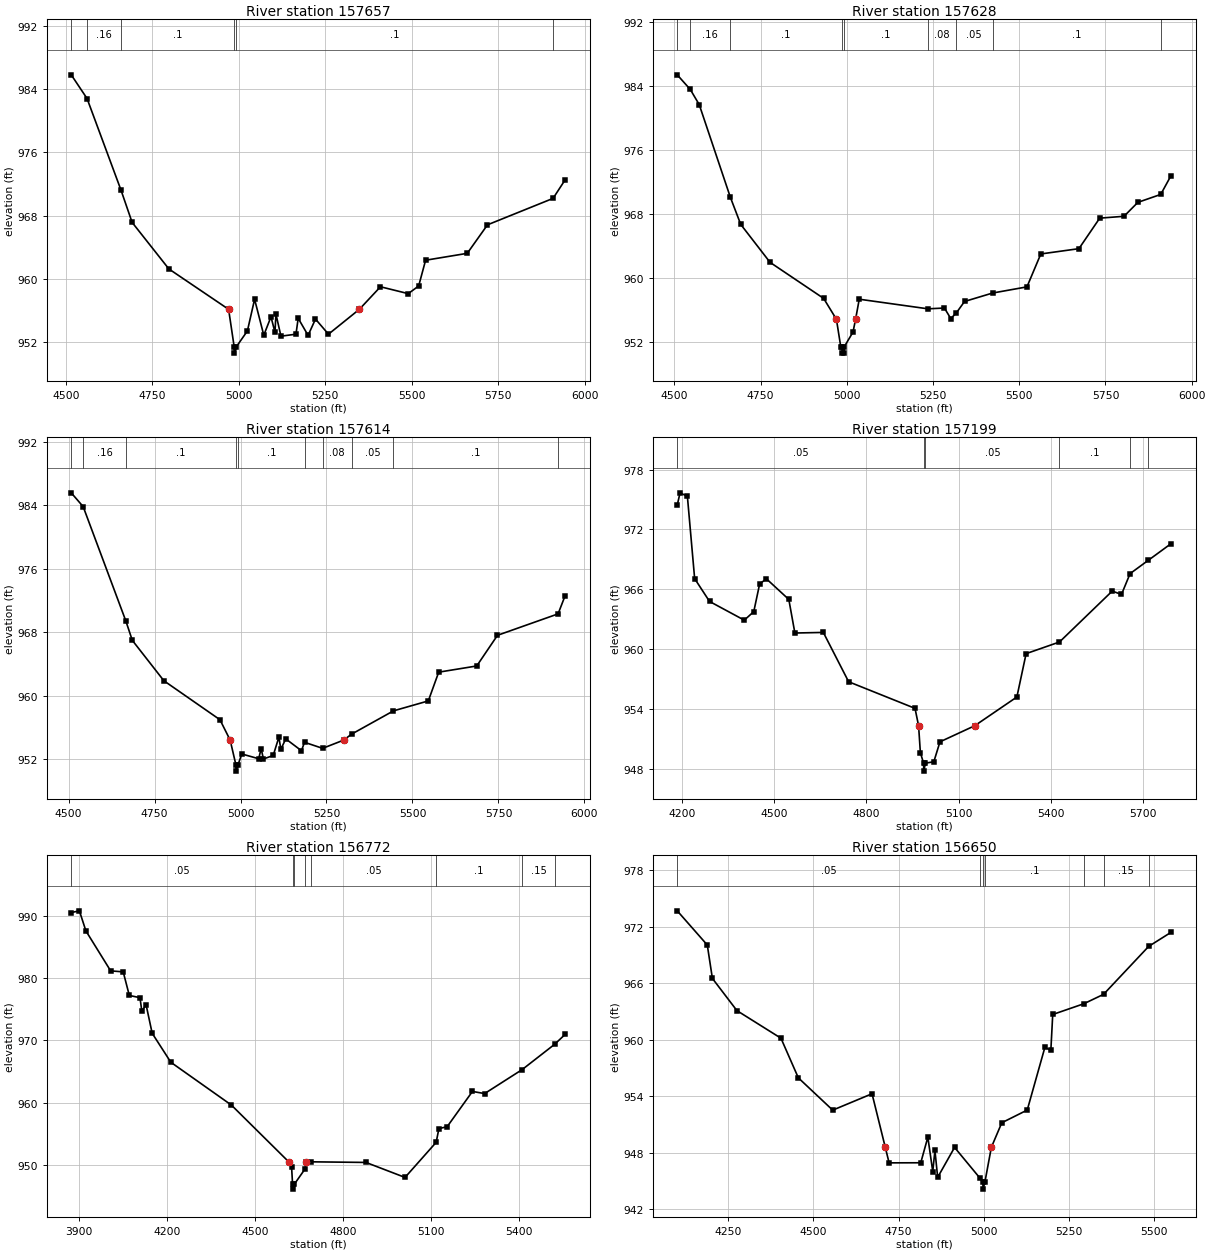
Type RM Length L Ch R = 1 ,157657  ,29,29,29
BEGIN DESCRIPTION:
Mapping XS 02f5cc55
END DESCRIPTION:
XS GIS Cut Line= 6
      1988063.15     13680635.11      1987651.71     13680275.75
      1987729.83      13680178.1      1987729.83     13680153.36
      1987697.28     13680140.34      1987003.26     13680092.16
#Sta/Elev= 30
    4516  985.78  4561.7  982.79    4660   971.2  4691.9  967.15  4798.2  961.27
 4970.81956.1719  4986.9  951.44  4987.4  950.64  4993.1  951.44  5025.1  953.44
  5045.9  957.44  5072.5   952.9  5093.3  955.23  5104.8  953.26  5107.6  955.57
  5122.1  952.78  5165.5  953.03  5171.9  955.04  5200.5  952.88  5221.9  954.94
  5259.4  953.03  5348.7 956.172  5409.7  959.02    5490  958.15  5520.1  959.12
  5540.1  962.37  5660.5  963.24    5719  966.84  5908.5  970.18  5943.2  972.51
#Mann= 6 ,-1 , 0
    4516      .1       0  4561.7     .16       0    4660      .1       0
  4986.9     .07       0  4993.1      .1       0  5908.5     .05       0
Bank Sta=4970.81,5348.7
XS Rating Curve= 0 ,0
Exp/Cntr=0.3,0.1

Type RM Length L Ch R = 1 ,157628  ,14,14,14
BEGIN DESCRIPTION:
CHACON CREEK 219.0
END DESCRIPTION:
XS GIS Cut Line= 6
        1988075.       13680625.      1987684.26     13680267.94
      1987751.97      13680183.3      1987758.48     13680153.36
      1987744.15     13680136.43      1987009.19     13680055.36
#Sta/Elev= 30
  4508.3  985.36  4546.2  983.53  4572.1  981.64  4662.3  970.08  4692.4  966.69
  4777.5  961.95  4932.9  957.45 4969.92954.8392  4982.4  951.44  4986.5  951.42
    4987  950.62  4992.2  950.62  4992.7  951.42    5018  953.25 5025.43954.8414
  5036.1  957.35  5235.3  956.15  5283.1  956.25  5301.4  954.94  5316.9   955.6
  5341.5  957.07  5422.6  958.12  5522.4  958.89  5562.6     963  5673.1  963.66
  5733.4  967.47  5803.8   967.7    5844  969.44  5910.3  970.43  5940.3  972.79
#Mann= 9 ,-1 , 0
  4508.3      .1       0  4546.2     .16       0  4662.3      .1       0
  4986.5     .07       0  4992.7      .1       0  5235.3     .08       0
  5316.9     .05       0  5422.6      .1       0  5910.3     .05       0
Bank Sta=4969.92,5025.43
XS Rating Curve= 0 ,0
Exp/Cntr=0.3,0.1

Type RM Length L Ch R = 1 ,157614  ,415,415,415
BEGIN DESCRIPTION:
Mapping XS 6e6df407
END DESCRIPTION:
XS GIS Cut Line= 6
      1988080.11     13680620.83       1987710.3     13680273.15
      1987778.01      13680179.4      1987778.01     13680142.94
      1987762.38      13680120.8      1987019.44     13680037.53
#Sta/Elev= 30
  4507.9  985.55  4542.6  983.81  4666.7  969.41  4685.4  966.98  4777.2  961.89
  4940.3  956.98  4969.9954.4176  4986.6  951.31  4987.1  950.51  4992.8  951.31
  5003.8  952.67  5052.9  952.07    5060  953.34  5066.7  952.04  5095.1  952.48
  5111.6  954.79  5117.3  953.26  5131.6  954.57  5177.2  953.08  5186.1  954.14
  5238.7  953.38  5300.1954.4176  5322.7  955.16  5444.8   958.1    5546  959.35
  5576.2  962.97  5686.8  963.75  5747.1  967.61  5923.3  970.31  5943.6  972.58
#Mann= 10 ,-1 , 0
  4507.9      .1       0  4542.6     .16       0  4666.7      .1       0
  4986.6     .07       0  4992.8      .1       0  5186.1     .05       0
  5238.7     .08       0  5322.7     .05       0  5444.8      .1       0
  5923.3     .05       0
Bank Sta=4969.9,5300.1
XS Rating Curve= 0 ,0
Exp/Cntr=0.3,0.1

Type RM Length L Ch R = 1 ,157199  ,427,427,427
BEGIN DESCRIPTION:
CHACON CREEK 218.0
END DESCRIPTION:
XS GIS Cut Line= 3
      1988667.14     13680112.56        1987875.       13679925.
      1987083.85     13679927.67
#Sta/Elev= 30
  4185.2  974.45  4194.4  975.68  4218.2  975.33  4241.8  967.07  4290.2  964.78
  4403.2   962.9    4434  963.76  4453.1  966.54  4475.1  967.05  4547.9  964.98
  4567.6  961.61  4660.1  961.67  4742.3  956.72  4958.1  954.05  4969.7952.3056
  4975.5  949.61  4985.9  948.55  4986.4  947.75  4992.1  948.55  5019.2  948.69
  5039.2  950.69 5152.38952.3077  5289.2  955.19  5319.2  959.54  5427.7  960.71
  5599.2  965.82  5629.2  965.48  5657.1  967.57    5716   968.9  5790.4  970.58
#Mann= 6 ,-1 , 0
  4185.2     .05       0  4985.9     .04       0  4992.1     .05       0
  5427.7      .1       0  5657.1     .15       0    5716      .1       0
Bank Sta=4969.7,5152.38
XS Rating Curve= 0 ,0
Exp/Cntr=0.3,0.1

Type RM Length L Ch R = 1 ,156772  ,122,122,122
BEGIN DESCRIPTION:
CHACON CREEK 217.0
END DESCRIPTION:
XS GIS Cut Line= 3
      1988524.97     13679025.03      1987758.29     13679669.85
       1987101.6     13679863.01
#Sta/Elev= 30
  3872.6  990.56  3900.5  990.84  3922.6  987.62  4007.2  981.19  4050.1  981.03
  4070.9  977.24  4107.3  976.88  4113.8  974.69  4128.1  975.76    4149  971.16
  4212.7   966.5  4419.5  959.62  4617.4   950.4    4625   949.7  4628.4  946.91
  4628.9  946.11  4634.6  946.91  4670.9  949.35  4674.4  950.46  4691.8   950.5
    4879   950.4  5012.4  947.99  5118.7  953.63  5128.1  955.84  5156.2  956.14
  5242.6  961.81  5284.3  961.47  5412.6  965.33  5523.3  969.39  5558.9  970.97
#Mann= 8 ,-1 , 0
  3872.6     .05       0  4628.4     .04       0  4634.6     .05       0
  4670.9     .08       0  4691.8     .05       0  5118.7      .1       0
  5412.6     .15       0  5523.3      .1       0
Bank Sta=4617.4,4674.4
XS Rating Curve= 0 ,0
Exp/Cntr=0.3,0.1

Type RM Length L Ch R = 1 ,156650  ,53,53,53
BEGIN DESCRIPTION:
Mapping XS 61d44e1b
END DESCRIPTION:
XS GIS Cut Line= 5
      1988284.35     13679091.71      1987781.72     13679427.67
      1987667.14      13679570.9      1987109.85      13679823.5
      1987062.94     13679839.14
#Sta/Elev= 30
  4100.2  973.67  4188.4  970.04  4203.4  966.49  4275.4  963.07  4404.6  960.14
  4455.6  955.93  4556.5   952.5  4671.9  954.24 4710.78948.5474    4722   946.9
  4814.9  946.91  4835.7  949.63  4850.1  945.98  4856.5  948.22  4864.5  945.36
  4914.1  948.54  4987.9  945.31  4997.2  944.91  4997.7  944.11  5003.4  944.91
 5022.03 948.546  5052.7  951.16  5127.4  952.51  5179.1  959.16  5196.7  958.87
  5202.2  962.66  5293.5   963.8  5351.4   964.8  5483.7  969.89  5549.5  971.39
#Mann= 7 ,-1 , 0
  4100.2     .05       0  4987.9      .1       0  4997.2     .07       0
  5003.4      .1       0  5293.5     .08       0  5351.4     .15       0
  5483.7      .1       0
Bank Sta=4710.78,5022.03
XS Rating Curve= 0 ,0
Exp/Cntr=0.3,0.1

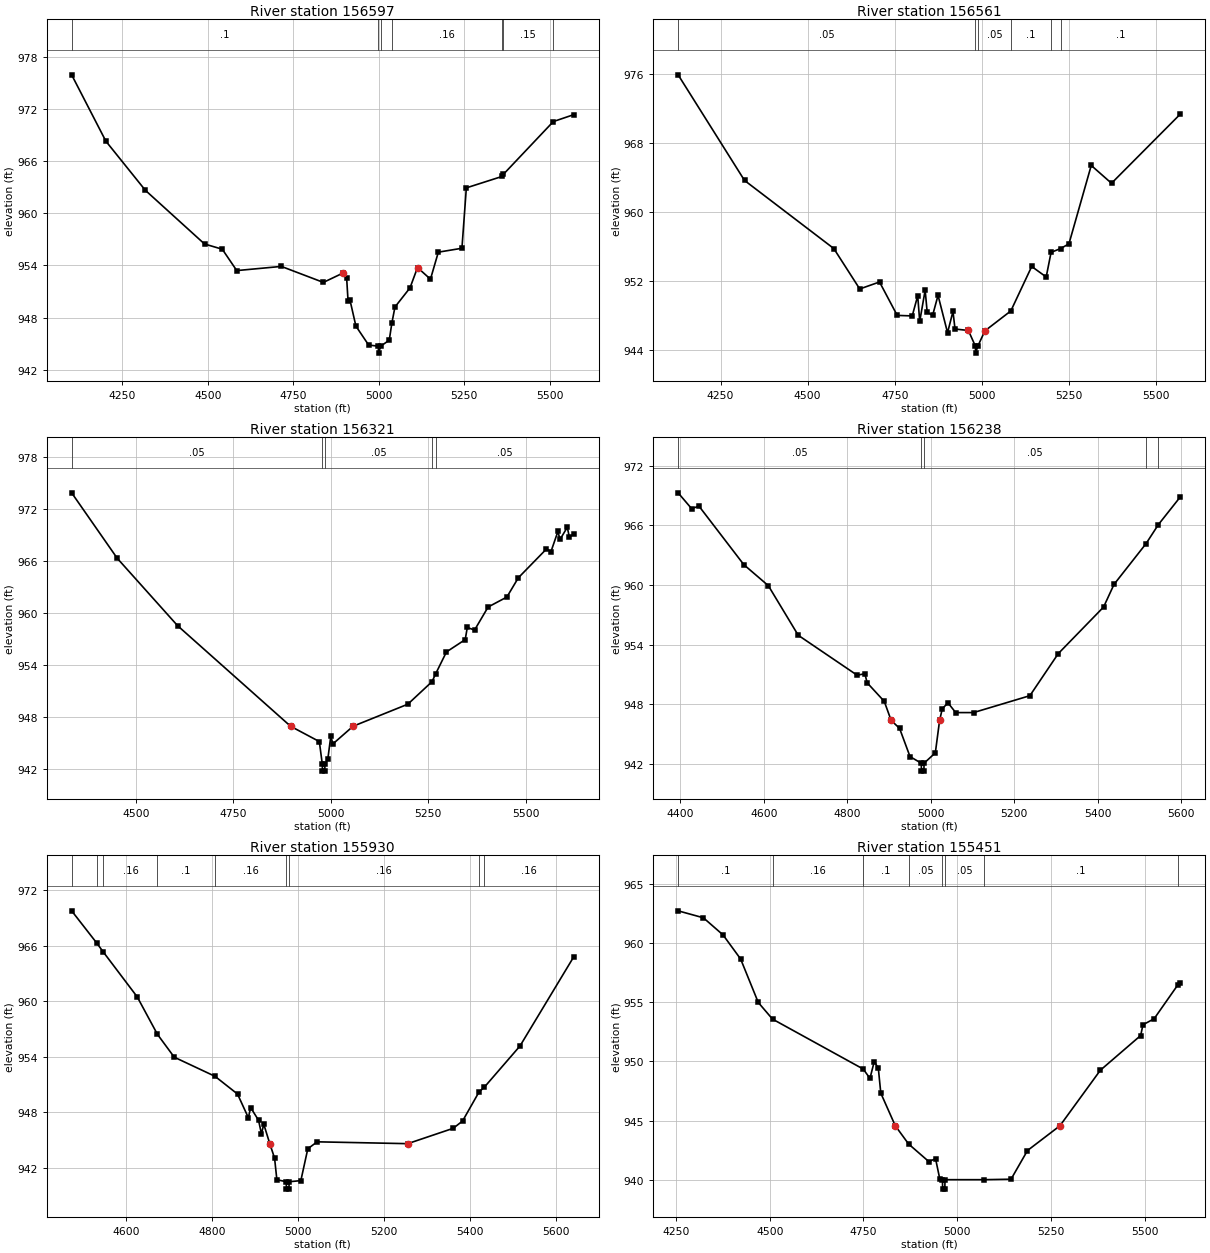
Type RM Length L Ch R = 1 ,156597  ,36,36,36
BEGIN DESCRIPTION:
CHACON CREEK 216.0
END DESCRIPTION:
XS GIS Cut Line= 5
      1988302.52     13679055.29      1987799.95     13679370.37
      1987729.64     13679427.67      1987667.14     13679526.62
      1987058.92     13679804.74
#Sta/Elev= 30
  4101.4  975.94  4201.6   968.3  4317.1  962.65  4490.3  956.47  4542.2  955.87
  4584.6  953.41  4715.1  953.89  4838.1  952.05  4895.7  953.13  4906.2  952.56
  4910.3  949.91  4915.8  950.04  4933.3  947.02  4970.6  944.84    4999  944.71
  4999.5  943.91  5005.8  944.71  5030.9   945.4  5038.4  947.34  5047.6  949.22
  5091.6  951.42  5113.6  953.76  5151.5  952.42  5174.5  955.53  5243.6  955.98
  5256.5  962.93  5361.4  964.25  5364.7  964.48    5511  970.56  5571.1  971.36
#Mann= 7 ,-1 , 0
  4101.4      .1       0    4999     .16       0  5005.8     .16       0
  5038.4     .16       0  5361.4      .1       0  5364.7     .15       0
    5511      .1       0
Bank Sta=4895.7,5113.6
XS Rating Curve= 0 ,0
Exp/Cntr=0.3,0.1

Type RM Length L Ch R = 1 ,156561  ,240,240,240
BEGIN DESCRIPTION:
Mapping XS 992fd5e9
END DESCRIPTION:
XS GIS Cut Line= 5
      1988294.75     13679047.45      1987854.64     13679287.04
      1987729.64     13679372.98      1987646.31      13679513.6
      1987070.76     13679758.41
#Sta/Elev= 30
  4128.1  975.94  4318.7  963.68  4575.1  955.77  4649.5  951.08  4706.3  951.89
  4757.1  948.01  4800.2  947.95  4815.9  950.29  4821.7  947.31  4837.3  950.94
  4843.1  948.38  4858.7  948.01  4874.3  950.34  4901.6     946  4917.2  948.47
    4923  946.43  4961.4  946.26  4981.6  944.43  4982.1  943.63  4988.4  944.43
  5008.7  946.21  5083.3  948.53  5143.2  953.69  5184.8  952.47  5198.8  955.33
  5226.1  955.77  5250.1  956.32  5314.1  965.42  5372.3  963.35  5569.8  971.38
#Mann= 6 ,-1 , 0
  4128.1     .05       0  4981.6     .04       0  4988.4     .05       0
  5083.3      .1       0  5198.8     .15       0  5226.1      .1       0
Bank Sta=4961.4,5008.7
XS Rating Curve= 0 ,0
Exp/Cntr=0.3,0.1

Type RM Length L Ch R = 1 ,156321  ,83,83,83
BEGIN DESCRIPTION:
Mapping XS f2a3f8ef
END DESCRIPTION:
XS GIS Cut Line= 2
      1988263.46     13679057.89      1987070.74     13679544.87
#Sta/Elev= 30
    4335  973.84  4452.1  966.28  4606.9  958.51 4896.57946.9182  4970.4  945.15
    4978  942.54  4978.5  941.74  4984.3  941.74  4984.8  942.54  4992.2  943.15
  4999.8  945.76  5005.2  944.88 5057.01 946.918  5197.4  949.46  5259.5  952.06
  5268.9  952.97  5296.5  955.49  5344.6  956.91    5350  958.31  5368.6  958.01
  5403.4  960.67  5451.5  961.82  5480.9  964.04    5553  967.36  5564.7  967.07
  5582.4  969.38  5587.8  968.46  5606.5  969.86  5611.9  968.72  5623.3  969.11
#Mann= 5 ,-1 , 0
    4335     .05       0    4978     .04       0  4984.8     .05       0
  5259.5      .1       0  5268.9     .05       0
Bank Sta=4896.57,5057.01
XS Rating Curve= 0 ,0
Exp/Cntr=0.3,0.1

Type RM Length L Ch R = 1 ,156238  ,308,308,308
BEGIN DESCRIPTION:
CHACON CREEK 215.0
END DESCRIPTION:
XS GIS Cut Line= 3
      1988201.04     13678997.96      1987729.64     13679193.29
      1987081.16     13679435.49
#Sta/Elev= 30
  4394.9  969.27  4427.4  967.67  4444.7  967.94  4552.3  962.04  4610.9  959.93
  4682.5  954.94  4823.6  950.92  4842.1  951.07  4847.5  950.16  4888.5  948.29
 4904.92 946.381  4925.2  945.57  4950.2  942.73  4977.1  942.07  4977.6  941.27
  4983.4  941.27  4983.9  942.07  5010.8  943.11 5021.05946.3817  5027.5  947.55
  5041.1  948.14  5059.6  947.16  5102.3  947.16  5237.2  948.86  5305.1  953.09
  5413.7  957.78  5438.7  960.06  5515.4  964.16    5545  966.08  5597.4  968.86
#Mann= 5 ,-1 , 0
  4394.9     .05       0  4977.1     .04       0  4983.9     .05       0
  5515.4     .08       0    5545     .05       0
Bank Sta=4904.92,5021.05
XS Rating Curve= 0 ,0
Exp/Cntr=0.3,0.1

Type RM Length L Ch R = 1 ,155930  ,479,479,479
BEGIN DESCRIPTION:
CHACON CREEK 214.0
END DESCRIPTION:
XS GIS Cut Line= 3
      1988133.27     13678737.57      1987635.89     13678919.85
      1987074.96     13679225.02
#Sta/Elev= 30
  4473.9  969.79    4532  966.32  4547.6  965.33  4626.4  960.48  4673.5  956.42
  4712.6  953.95  4807.4  951.88  4859.8  949.96    4885   947.4  4890.3   948.5
  4908.7  947.12  4915.5  945.65  4920.8   946.7 4934.85944.5904    4946  943.02
  4951.3  940.69  4973.1  940.47  4973.6  939.67  4979.4  939.67  4979.9  940.47
  5007.1  940.59  5023.3  944.04  5045.1  944.79 5255.73  944.59  5361.5  946.25
  5383.3  947.04  5421.7  950.19  5434.3  950.72  5516.9  955.16  5642.2  964.83
#Mann= 9 ,-1 , 0
  4473.9     .16       0    4532      .1       0  4547.6     .16       0
  4673.5      .1       0  4807.4     .16       0  4973.1     .07       0
  4979.9     .16       0  5421.7      .1       0  5434.3     .16       0
Bank Sta=4934.85,5255.73
XS Rating Curve= 0 ,0
Exp/Cntr=0.3,0.1

Type RM Length L Ch R = 1 ,155451  ,336,336,336
BEGIN DESCRIPTION:
CHACON CREEK 213.0
END DESCRIPTION:
XS GIS Cut Line= 3
      1988044.78     13678284.42        1987375.       13678575.
      1986872.91     13678919.83
#Sta/Elev= 30
  4255.7  962.76  4323.1  962.17  4375.5  960.72  4422.4  958.68  4469.4     955
  4507.4  953.59  4749.3  949.36  4767.3  948.57  4778.7  949.99  4789.6  949.43
  4796.2  947.32 4834.85 944.555  4870.4  943.01  4924.4  941.52  4942.2  941.77
  4953.3  940.08  4960.6  939.99  4961.1  939.19  4966.9  939.19  4967.4  939.99
  5072.2  939.99  5143.5  940.03  5187.4  942.46 5273.87944.5551  5381.7  949.26
  5489.2   952.2  5495.3  953.11  5525.1  953.62  5588.6   956.5  5594.9  956.62
#Mann= 8 ,-1 , 0
  4255.7      .1       0  4507.4     .16       0  4749.3      .1       0
  4870.4     .05       0  4960.6    .033       0  4967.4     .05       0
  5072.2      .1       0  5588.6     .16       0
Bank Sta=4834.85,5273.87
XS Rating Curve= 0 ,0
Exp/Cntr=0.3,0.1