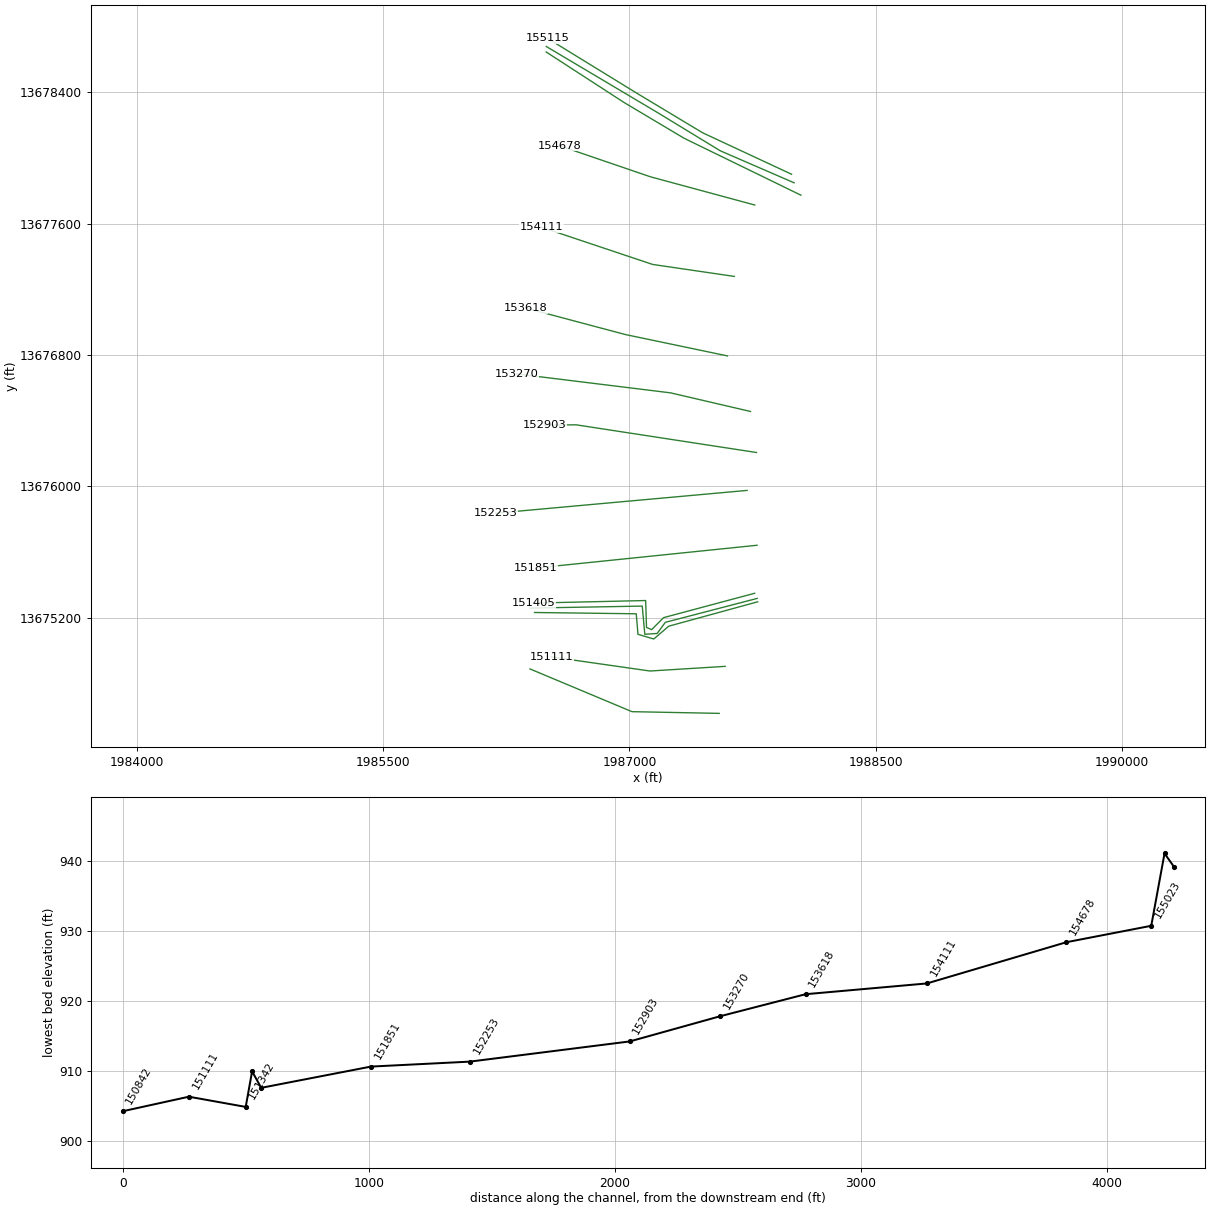
HEC-RAS study CHACON CREEK.prj: CHACON CREEK Base Level Engineering

--- CHACON CREEK.g01 (geometry) --- (continued)

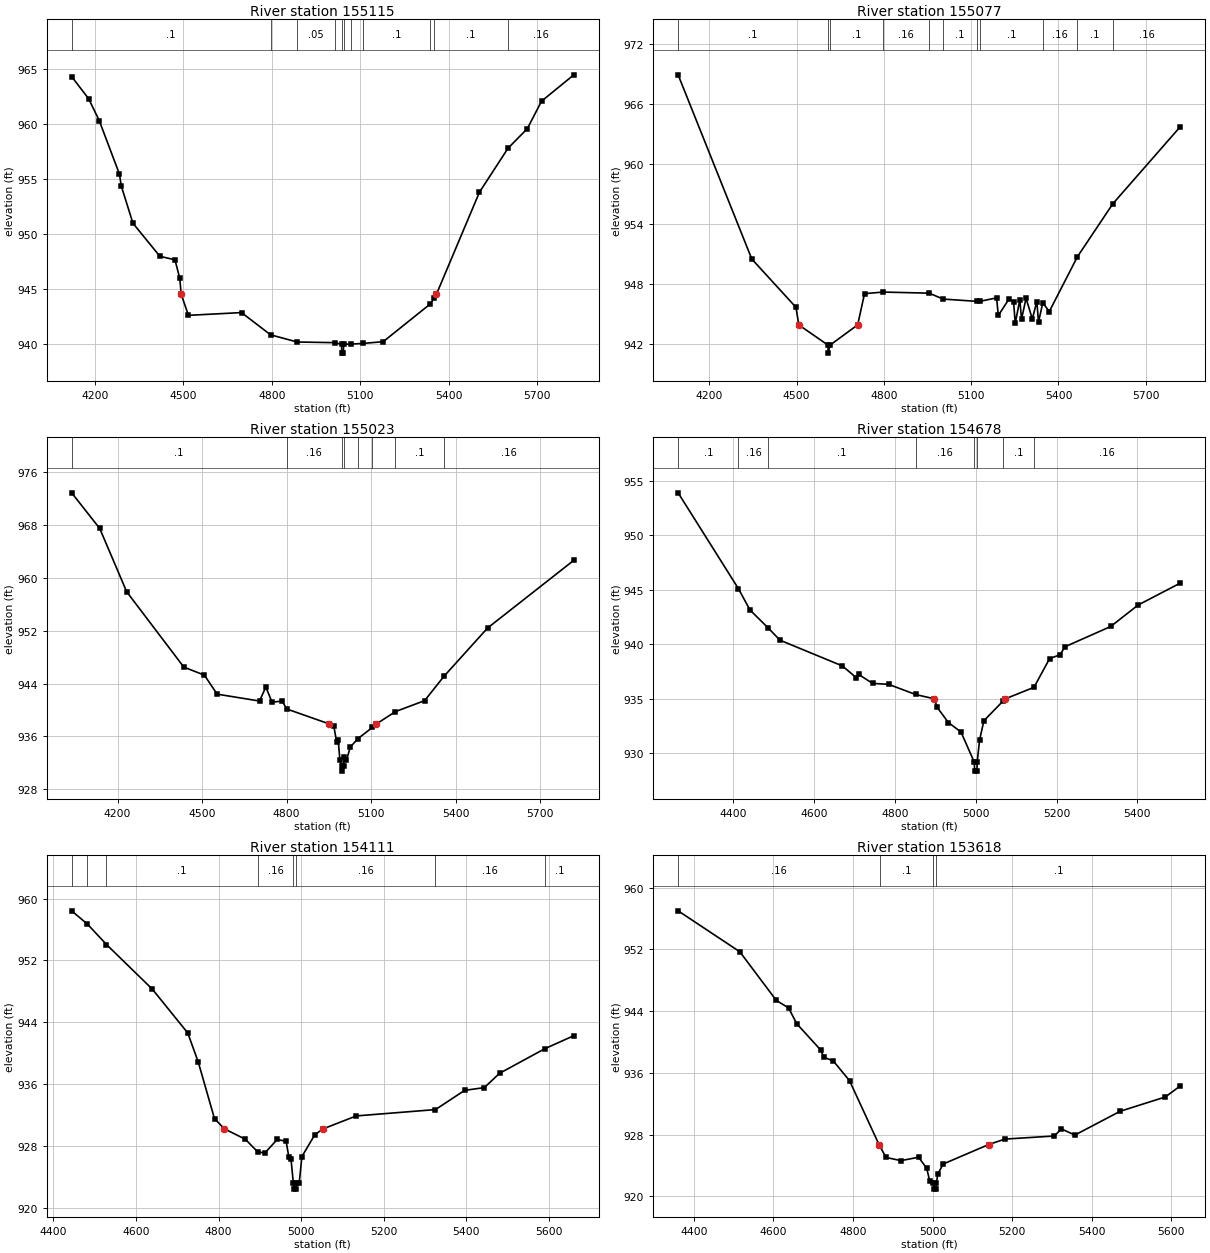
Type RM Length L Ch R = 1 ,155115  ,38,38,38
BEGIN DESCRIPTION:
Mapping XS 13549ffd
END DESCRIPTION:
XS GIS Cut Line= 4
      1987987.48     13677901.61      1987445.79     13678154.23
      1987047.35     13678393.81       1986500.5     13678729.73
#Sta/Elev= 30
  4120.6  964.29  4178.5  962.27  4214.3  960.29  4282.9  955.43  4288.8  954.38
  4328.6  950.98    4420  947.98  4471.3  947.66  4487.5  945.98 4492.41 944.529
    4517  942.62  4697.1  942.87  4795.8  940.85    4886   940.2  5013.8  940.14
  5036.6  939.99  5037.1  939.19    5043  939.19  5043.5  939.99  5067.7  940.01
  5109.8  940.07    5178  940.23  5337.6  943.65  5350.2  944.15 5358.62944.5286
  5504.7   953.8  5601.7  957.79    5667  959.56  5715.4  962.06    5825  964.45
#Mann= 11 ,-1 , 0
  4120.6      .1       0  4795.8     .16       0    4886     .05       0
  5013.8      .1       0  5036.6    .033       0  5043.5      .1       0
  5067.7     .05       0  5109.8      .1       0  5337.6     .16       0
  5350.2      .1       0  5601.7     .16       0
Bank Sta=4492.41,5358.62
XS Rating Curve= 0 ,0
Exp/Cntr=0.3,0.1

Type RM Length L Ch R = 1 ,155077  ,54,54,54
BEGIN DESCRIPTION:
CHACON CREEK 212.0
END DESCRIPTION:
XS GIS Cut Line= 4
      1988003.11     13677849.53      1987552.56     13678044.85
        1987175.       13678275.      1986492.88     13678680.14
#Sta/Elev= 30
  4092.4  968.89  4345.7  950.49  4497.5  945.67 4507.38 943.909  4607.8  941.89
  4608.3  941.09  4614.7  941.89 4709.65943.9092  4733.3  947.03  4797.2  947.19
  4955.6  947.08  5003.5  946.49  5120.3  946.26    5131  946.27  5187.4  946.61
  5193.2  944.85  5230.2   946.5  5245.8  946.15  5251.6  944.08  5267.2  946.42
  5273.1  944.48  5288.7  946.57  5310.1   944.5  5325.7  946.24  5331.5   944.2
  5346.2  946.12  5368.5  945.24  5465.3  950.72    5587  956.01    5819  963.71
#Mann= 11 ,-1 , 0
  4092.4      .1       0  4607.8    .033       0  4614.7      .1       0
  4797.2     .16       0  4955.6     .05       0  5003.5      .1       0
  5120.3     .16       0    5131      .1       0  5346.2     .16       0
  5465.3      .1       0    5587     .16       0
Bank Sta=4507.38,4709.65
XS Rating Curve= 0 ,0
Exp/Cntr=0.3,0.1

Type RM Length L Ch R = 1 ,155023  ,345,345,345
BEGIN DESCRIPTION:
CHACON CREEK 211.0
END DESCRIPTION:
XS GIS Cut Line= 4
      1988044.74     13677774.02      1987333.81     13678120.37
      1986966.62     13678339.12      1986492.65     13678646.43
#Sta/Elev= 30
  4036.8  972.89  4136.4   967.5  4232.1  957.91    4435  946.49  4508.2  945.27
  4553.3  942.39  4703.9  941.35  4726.2  943.47  4748.4  941.17  4784.2  941.35
  4800.3  940.15 4952.04937.8716  4967.7  937.54  4977.5  935.18  4983.3  935.37
  4989.2  932.44  4995.4  931.53  4995.9  930.73  5002.3  931.53  5004.7  932.84
  5012.5  932.36  5026.1  934.37  5052.7  935.63    5105  937.36 5118.75937.8719
    5186  939.74  5290.1  941.41  5358.7  945.09  5513.6  952.41  5819.9  962.67
#Mann= 8 ,-1 , 0
  4036.8      .1       0  4800.3     .16       0  4995.4     .07       0
  5002.3     .16       0  5052.7      .1       0    5105     .16       0
    5186      .1       0  5358.7     .16       0
Bank Sta=4952.04,5118.75
XS Rating Curve= 0 ,0
Exp/Cntr=0.3,0.1

Type RM Length L Ch R = 1 ,154678  ,567,567,567
BEGIN DESCRIPTION:
CHACON CREEK 210.0
END DESCRIPTION:
XS GIS Cut Line= 3
      1987763.45     13677714.14      1987128.08       13677886.
      1986574.99       13678075.
#Sta/Elev= 30
  4263.5  953.91  4412.7  945.12  4441.2  943.17    4487  941.49  4515.7  940.39
    4670  938.03  4704.7  936.94  4709.9  937.26  4744.6  936.43  4784.4  936.34
  4851.2  935.41 4897.63935.0117  4904.2  934.25  4932.2  932.84  4963.5  931.97
  4996.6  929.18  4997.1  928.38    5003  928.38  5003.5  929.18  5009.5  931.23
  5020.1     933  5068.6  934.85 5073.13935.0117  5144.2  936.07  5182.7   938.7
  5208.7  939.06  5220.9  939.79    5334  941.65  5401.9  943.62  5506.2  945.63
#Mann= 8 ,-1 , 0
  4263.5      .1       0  4412.7     .16       0    4487      .1       0
  4851.2     .16       0  4996.6     .07       0  5003.5     .16       0
  5068.6      .1       0  5144.2     .16       0
Bank Sta=4897.63,5073.13
XS Rating Curve= 0 ,0
Exp/Cntr=0.3,0.1

Type RM Length L Ch R = 1 ,154111  ,493,493,493
BEGIN DESCRIPTION:
CHACON CREEK 209.0
END DESCRIPTION:
XS GIS Cut Line= 3
      1987638.54     13677279.22       1987141.1     13677352.15
      1986464.05     13677578.69
#Sta/Elev= 30
  4444.2  958.41  4482.5  956.69  4528.6  954.06  4639.8  948.29  4725.5  942.64
    4751  938.88  4790.3  931.57 4814.41930.2637  4865.2  928.91  4895.6  927.25
  4912.7  927.17  4942.5   928.9  4963.9  928.64  4970.5  926.59  4975.7  926.32
  4981.3  923.28  4981.9  922.48  4988.2  922.48  4988.7  923.28  4995.6  923.29
    5002  926.68  5033.6  929.53 5053.71 930.264  5133.6  931.93  5325.7  932.75
  5396.3  935.23  5444.1  935.59  5480.9  937.43  5590.6  940.61  5660.9  942.29
#Mann= 8 ,-1 , 0
  4444.2      .1       0  4482.5     .16       0  4528.6      .1       0
  4895.6     .16       0  4981.3     .07       0  4988.7     .16       0
  5325.7     .16       0  5590.6      .1       0
Bank Sta=4814.41,5053.71
XS Rating Curve= 0 ,0
Exp/Cntr=0.3,0.1

Type RM Length L Ch R = 1 ,153618  ,348,348,348
BEGIN DESCRIPTION:
CHACON CREEK 208.0
END DESCRIPTION:
XS GIS Cut Line= 3
      1987596.78     13676794.86        1986975.       13676925.
      1986368.82     13677086.21
#Sta/Elev= 30
  4360.4  956.98  4515.5  951.68  4607.4  945.37  4638.1  944.41  4658.5  942.37
  4719.8   938.9    4726  938.04  4750.5  937.54  4791.3  934.99 4865.32926.7175
  4867.6  926.48  4883.3  925.04  4920.7  924.63    4965  925.07  4985.4  923.63
  4993.1  921.96  5002.3  921.74  5002.9  920.94  5009.2  920.94  5009.8  921.74
  5013.1  922.88  5026.7  924.19  5141.3926.7177  5181.9  927.42  5306.1  927.82
    5324  928.74  5357.8  927.94  5471.6  931.02  5585.5  932.88  5622.9  934.31
#Mann= 4 ,-1 , 0
  4360.4     .16       0  4867.6      .1       0  5002.3     .07       0
  5009.8      .1       0
Bank Sta=4865.32,5141.3
XS Rating Curve= 0 ,0
Exp/Cntr=0.3,0.1

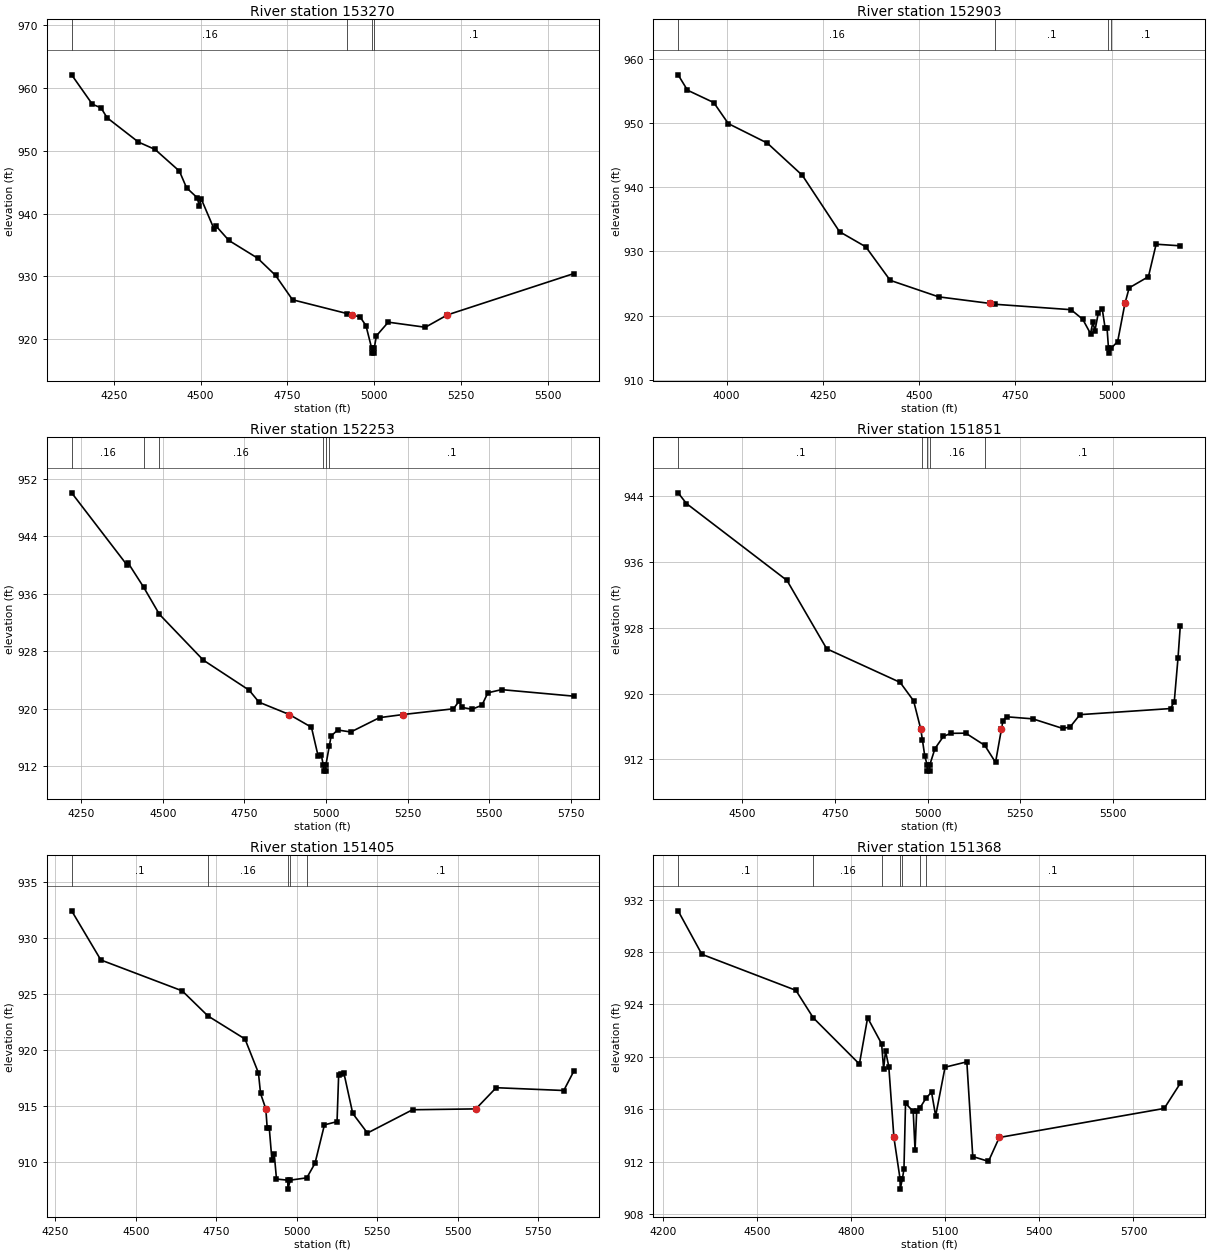
Type RM Length L Ch R = 1 ,153270  ,367,367,367
BEGIN DESCRIPTION:
CHACON CREEK 207.0
END DESCRIPTION:
XS GIS Cut Line= 3
      1987737.41     13676456.32        1987250.     13676569.79
      1986310.34     13676685.48
#Sta/Elev= 30
  4128.2   962.1  4187.8  957.42  4212.8  956.84  4230.4  955.26  4320.7  951.39
  4368.5  950.22  4438.7  946.77  4459.2  944.12    4490  942.53  4496.2   941.2
  4501.3  942.38  4538.8  937.52  4543.9  938.05  4581.4  935.72  4663.9  932.91
  4715.8  930.16  4764.7  926.28    4922  924.08 4936.24923.8728  4959.4  923.53
  4976.3  922.17  4992.7  918.58  4993.3  917.78  4999.6  917.78  5000.2  918.58
  5006.5  920.54  5040.6  922.71  5147.5   921.9 5211.21923.8726  5575.4  930.45
#Mann= 4 ,-1 , 0
  4128.2     .16       0    4922      .1       0  4992.7     .07       0
  5000.2      .1       0
Bank Sta=4936.24,5211.21
XS Rating Curve= 0 ,0
Exp/Cntr=0.3,0.1

Type RM Length L Ch R = 1 ,152903  ,650,650,650
BEGIN DESCRIPTION:
CHACON CREEK 206.0
END DESCRIPTION:
XS GIS Cut Line= 3
      1987773.93     13676206.31        1986675.       13676375.
      1986482.21     13676372.98
#Sta/Elev= 30
    3874  957.49  3898.3   955.1  3966.6  953.17  4004.4   949.9  4105.6  946.87
  4196.7  941.85  4293.3  933.08  4361.6  930.72  4424.9  925.51  4550.8  922.94
 4684.04921.9146  4698.1  921.78  4894.7  920.94  4925.1  919.45  4945.3  917.22
  4951.6     919  4956.7  917.64  4965.6  920.43  4975.7  921.08  4983.3  918.08
  4988.3  918.08    4992  914.98  4992.6  914.18  4999.5  914.98  5015.8  915.97
 5034.78921.9161  5045.8  924.34  5095.8  926.08  5115.8  931.13  5178.6  930.88
#Mann= 4 ,-1 , 0
    3874     .16       0  4698.1      .1       0    4992     .07       0
  4999.5      .1       0
Bank Sta=4684.04,5034.78
XS Rating Curve= 0 ,0
Exp/Cntr=0.3,0.1

Type RM Length L Ch R = 1 ,152253  ,402,402,402
BEGIN DESCRIPTION:
Mapping XS c0e68c0e
END DESCRIPTION:
XS GIS Cut Line= 2
      1987716.62     13675975.41       1986184.5     13675836.52
#Sta/Elev= 30
    4221  950.05    4390  940.03    4395  940.21  4441.5  936.91  4489.8  933.13
  4624.3  926.75  4764.8  922.56    4795  920.89 4887.96919.1694  4955.6   917.4
  4975.7  913.46  4985.7  913.56    4992  912.09  4992.6  911.29    4999  911.29
  4999.6  912.09  5010.1  914.74  5015.9  916.18  5035.9  917.02  5076.1  916.74
  5164.2  918.74  5235.7919.1693  5390.5  919.97  5407.5  921.01  5417.5  920.16
  5447.6  919.91  5477.7  920.46  5496.1   922.2    5538  922.64  5759.4  921.73
#Mann= 6 ,-1 , 0
    4221     .16       0  4441.5      .1       0  4489.8     .16       0
    4992     .07       0  4999.6     .16       0  5010.1      .1       0
Bank Sta=4887.96,5235.7
XS Rating Curve= 0 ,0
Exp/Cntr=0.3,0.1

Type RM Length L Ch R = 1 ,151851  ,446,446,446
BEGIN DESCRIPTION:
Mapping XS 42967364
END DESCRIPTION:
XS GIS Cut Line= 3
       1987777.4     13675641.21      1986519.78     13675511.81
      1986428.82     13675502.45
#Sta/Elev= 30
  4326.2  944.38  4348.7  943.08  4620.1  933.74  4727.3  925.44  4925.5  921.36
  4961.9  919.12 4981.28915.6699  4985.9  914.31  4992.1   912.4  4998.3  911.38
  4998.9  910.58  5005.3  910.58  5005.9  911.38  5019.6  913.32  5042.4   914.8
  5062.5  915.17  5102.7  915.19    5154  913.71  5183.1  911.64    5199915.6699
  5203.2  916.72  5212.8  917.18  5283.6  916.93  5364.1  915.77  5384.2  915.93
    5411  917.44  5655.6  918.18  5665.6  919.03  5675.7  924.32  5681.9  928.26
#Mann= 5 ,-1 , 0
  4326.2      .1       0  4985.9     .16       0  4998.3     .07       0
  5005.9     .16       0    5154      .1       0
Bank Sta=4981.28,5199
XS Rating Curve= 0 ,0
Exp/Cntr=0.3,0.1

Type RM Length L Ch R = 1 ,151405  ,37,37,37
BEGIN DESCRIPTION:
Mapping XS 812cf1c7
END DESCRIPTION:
XS GIS Cut Line= 6
      1987762.65     13675348.68      1987207.94     13675200.24
      1987135.02     13675127.32      1987103.77     13675140.34
      1987098.56      13675304.4      1986413.71     13675288.78
#Sta/Elev= 30
  4300.3   932.4    4391  928.01    4644  925.25  4723.9  923.01  4839.1  920.95
  4880.9  917.92  4887.4  916.09 4903.78914.7078  4908.2  912.96  4914.6  912.98
  4922.9   910.1    4930  910.67    4937  908.44    4972  908.34  4972.6  907.54
  4979.6  908.34  5031.2  908.55  5056.7  909.85    5086  913.28  5125.2  913.57
  5130.2  917.76  5136.7  917.85  5146.8  917.87    5174   914.3  5219.7  912.55
  5359.8  914.63 5556.67914.7067  5619.8   916.6  5829.9  916.35  5861.2  918.08
#Mann= 5 ,-1 , 0
  4300.3      .1       0  4723.9     .16       0    4972     .07       0
  4979.6     .16       0  5031.2      .1       0
Bank Sta=4903.78,5556.67
XS Rating Curve= 0 ,0
Exp/Cntr=0.3,0.1

Type RM Length L Ch R = 1 ,151368  ,26,26,26
BEGIN DESCRIPTION:
CHACON CREEK 205.0
END DESCRIPTION:
XS GIS Cut Line= 6
      1987778.21     13675317.41      1987218.36     13675171.59
      1987168.88     13675103.88      1987093.36     13675098.67
      1987077.73     13675270.55      1986393.72      13675258.4
#Sta/Elev= 30
  4248.8  931.15  4324.5  927.83  4624.1  925.08  4679.5  922.98  4826.5  919.45
  4852.7  922.98  4897.3     921  4903.7  919.08  4909.8  920.45  4920.2  919.26
  4936.5913.8441    4956   910.7  4956.6   909.9  4963.6   910.7  4968.5  911.42
  4973.5  916.45    4998  915.83  5003.9  912.86  5009.1   915.9  5019.1  916.09
  5038.5  916.83  5056.4  917.31  5069.5  915.49  5099.5  919.21  5168.9  919.62
  5187.8  912.39  5237.8  912.02 5272.28913.8433  5797.9  916.06  5849.2  917.98
#Mann= 7 ,-1 , 0
  4248.8      .1       0  4679.5     .16       0  4897.3      .1       0
    4956     .07       0  4963.6      .1       0  5019.1     .16       0
  5038.5      .1       0
Bank Sta=4936.5,5272.28
XS Rating Curve= 0 ,0
Exp/Cntr=0.3,0.1

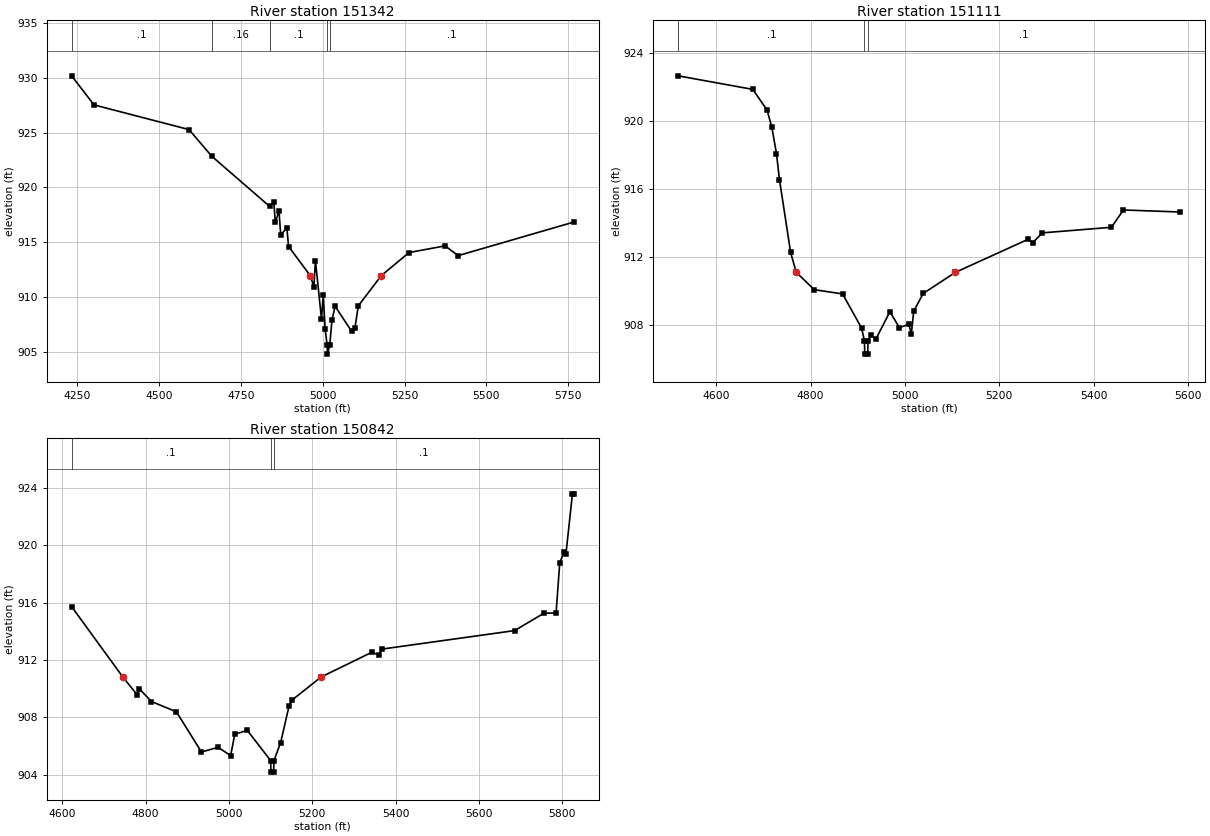
Type RM Length L Ch R = 1 ,151342  ,231,231,231
BEGIN DESCRIPTION:
Mapping XS dce7c50c
END DESCRIPTION:
XS GIS Cut Line= 6
       1987780.9      13675296.6      1987239.19     13675148.15
      1987148.04     13675070.03      1987051.69     13675098.67
      1987041.27     13675223.67      1986421.49     13675231.49
#Sta/Elev= 30
  4232.9  930.18  4301.2  927.53  4591.5  925.28    4661  922.85  4838.2  918.27
  4850.6  918.71  4855.1  916.84  4866.4  917.84  4871.8  915.67  4890.4  916.33
  4895.8  914.62 4961.97 911.968  4973.1  910.95  4977.8  913.33  4996.3  908.02
  5001.8  910.22  5007.4  907.08  5013.8  905.61  5014.4  904.81  5021.4  905.61
  5028.5  907.94    5038  909.17  5088.7  906.88  5098.7  907.23  5108.8  909.21
 5179.07911.9686  5263.9  914.07  5373.9  914.68  5413.9  913.79  5767.4  916.85
#Mann= 5 ,-1 , 0
  4232.9      .1       0    4661     .16       0  4838.2      .1       0
  5013.8     .07       0  5021.4      .1       0
Bank Sta=4961.97,5179.07
XS Rating Curve= 0 ,0
Exp/Cntr=0.3,0.1

Type RM Length L Ch R = 1 ,151111  ,269,269,269
BEGIN DESCRIPTION:
CHACON CREEK 204.0
END DESCRIPTION:
XS GIS Cut Line= 3
      1987582.98     13674903.36        1987125.       13674875.
      1986525.65     13674960.65
#Sta/Elev= 30
  4519.3  922.68  4677.6  921.88  4707.6  920.67  4717.7  919.68  4727.7   918.1
  4734.1  916.56  4757.7  912.27 4769.61 911.094  4807.8  910.07  4867.9  909.82
    4908  907.81  4914.2  907.07  4914.8  906.27  4921.2  906.27  4921.8  907.07
  4928.1  907.38  4938.1  907.14  4968.1  908.77  4988.3  907.83  5008.5  908.03
  5013.5  907.44  5018.6   908.8  5038.8  909.85 5107.05911.0939    5261  913.04
  5271.1  912.85  5291.3  913.42  5437.7  913.75    5463  914.77  5583.6  914.65
#Mann= 3 ,-1 , 0
  4519.3      .1       0  4914.2     .07       0  4921.8      .1       0
Bank Sta=4769.61,5107.05
XS Rating Curve= 0 ,0
Exp/Cntr=0.3,0.1

Type RM Length L Ch R = 1 ,150842  ,283,283,283
BEGIN DESCRIPTION:
Mapping XS 00dcbb2c
END DESCRIPTION:
XS GIS Cut Line= 3
      1987546.46      13674616.9      1987015.23     13674627.32
      1986393.71     13674887.73
#Sta/Elev= 30
  4622.7  915.72 4745.51910.8159  4779.9  909.58  4784.9     910  4814.2  909.11
  4874.2  908.39  4934.2  905.59  4974.2  905.92  5004.2  905.34  5014.2  906.83
  5044.2   907.1  5100.4  904.99    5101  904.19  5107.5  904.19  5108.1  904.99
  5124.3  906.25  5144.3  908.78  5151.6  909.21 5221.32910.8159  5343.1  912.54
  5360.3  912.35  5366.8  912.76  5685.6  914.05  5756.1  915.26  5785.3  915.28
    5794  918.75  5803.6  919.51  5809.1  919.42  5824.5  923.58  5827.9  923.58
#Mann= 3 ,-1 , 0
  4622.7      .1       0  5100.4     .07       0  5108.1      .1       0
Bank Sta=4745.51,5221.32
XS Rating Curve= 0 ,0
Exp/Cntr=0.3,0.1