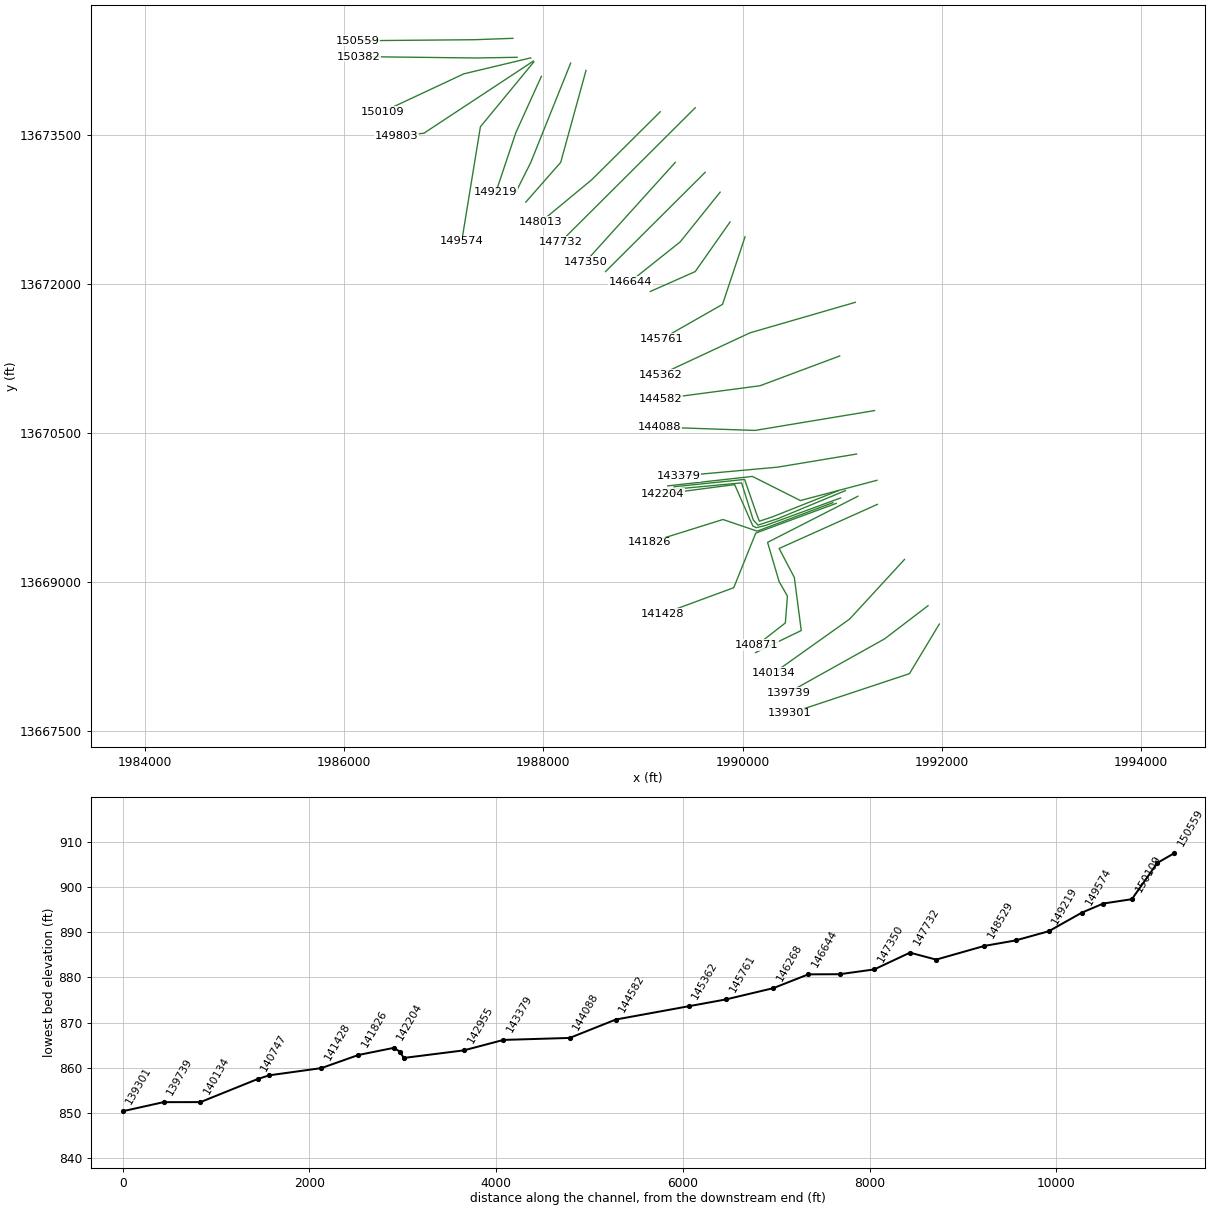
HEC-RAS study CHACON CREEK.prj: CHACON CREEK Base Level Engineering

--- CHACON CREEK.g01 (geometry) --- (continued)

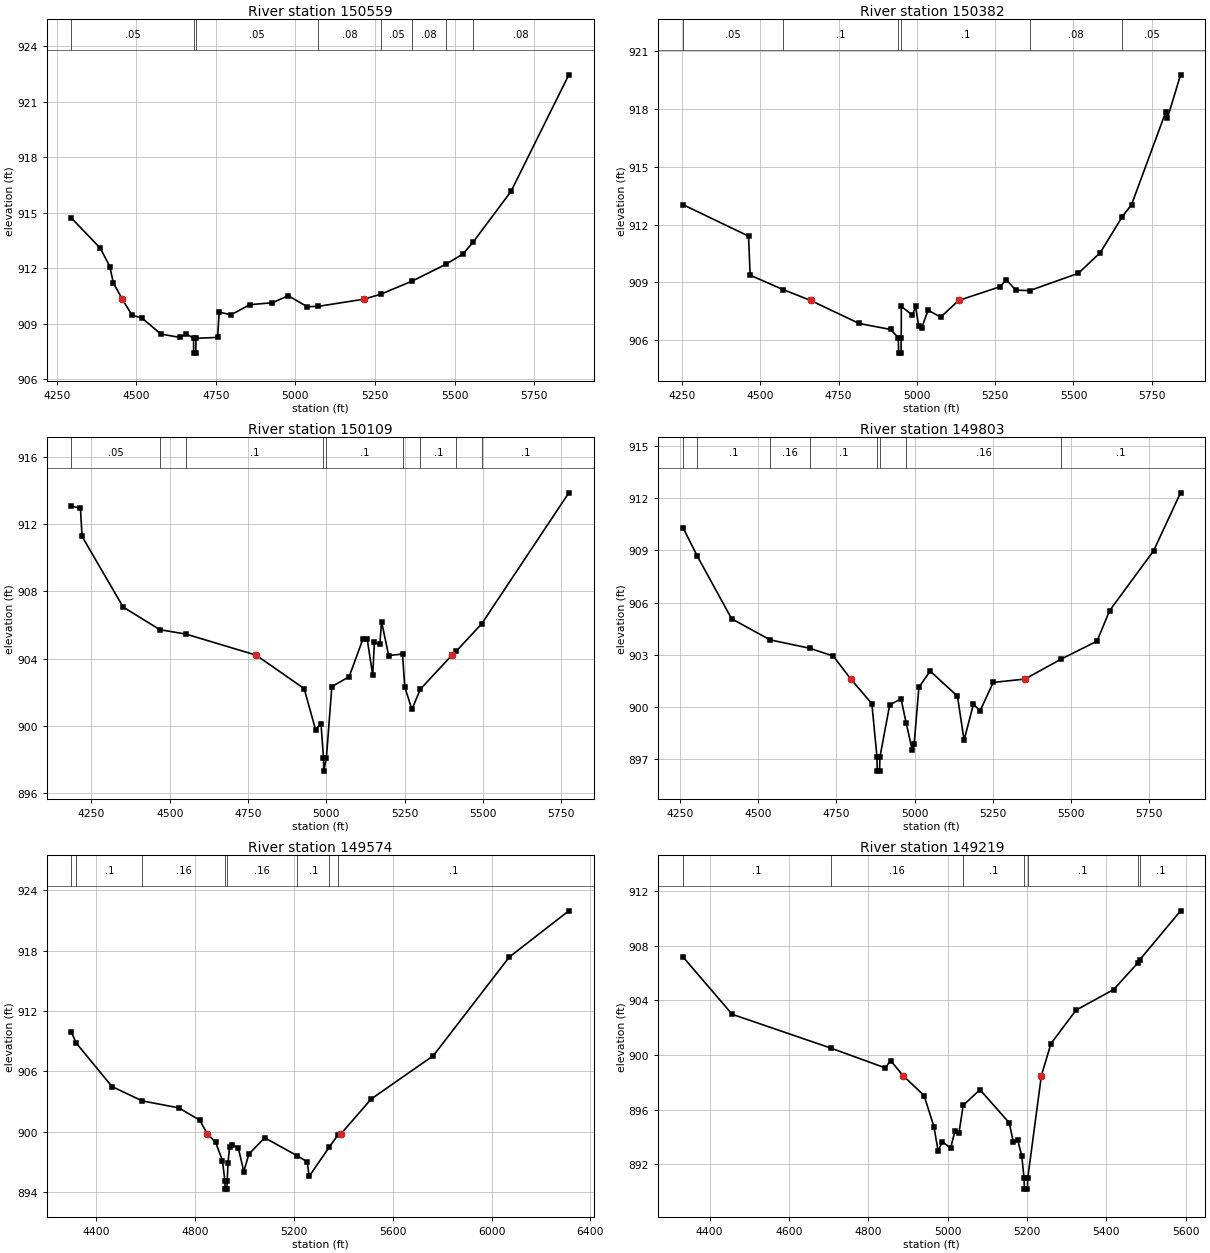
Type RM Length L Ch R = 1 ,150559  ,177,177,177
BEGIN DESCRIPTION:
CHACON CREEK 203.0
END DESCRIPTION:
XS GIS Cut Line= 3
      1987695.79     13674474.54       1987306.9     13674460.65
      1986133.29     13674450.24
#Sta/Elev= 30
  4296.3  914.72  4387.2  913.09  4417.2  912.09  4427.9  911.22 4456.22910.3349
  4487.2  909.46  4517.2  909.33  4577.3  908.45  4637.3  908.27  4657.3  908.46
    4680  908.22  4680.6  907.42  4687.1  907.42  4687.7  908.22  4755.6  908.27
  4760.6  909.64  4797.3  909.49  4857.3  910.04  4927.4  910.14  4977.4  910.52
  5037.4  909.93  5072.5  909.95 5215.11910.3348  5269.3  910.61  5367.7  911.32
  5473.8  912.23  5527.4  912.79  5557.6   913.4  5677.4  916.16  5859.1  922.46
#Mann= 8 ,-1 , 0
  4296.3     .05       0    4680     .04       0  4687.7     .05       0
  5072.5     .08       0  5269.3     .05       0  5367.7     .08       0
  5473.8      .1       0  5557.6     .08       0
Bank Sta=4456.22,5215.11
XS Rating Curve= 0 ,0
Exp/Cntr=0.3,0.1

Type RM Length L Ch R = 1 ,150382  ,273,273,273
BEGIN DESCRIPTION:
CHACON CREEK 202.0
END DESCRIPTION:
XS GIS Cut Line= 3
      1987737.42     13674283.57      1987327.73     13674276.62
      1986148.56      13674290.5
#Sta/Elev= 30
  4253.1  913.03  4462.1   911.4  4467.1  909.37  4572.9  908.62 4660.21908.0593
  4815.6  906.86  4915.6  906.55  4940.6  906.12  4941.5  905.32    4949  905.32
  4949.9  906.12  4950.2  907.75  4985.6  907.29  4995.6  907.75  5005.6  906.71
  5015.6  906.65  5035.6  907.55  5075.6  907.19 5133.53908.0593  5265.6  908.77
  5285.6  909.14  5315.6  908.59  5360.6  908.57  5515.6  909.47  5585.6  910.54
    5656  912.41  5685.7  913.04  5795.3  917.87  5800.3  917.53  5842.1  919.78
#Mann= 6 ,-1 , 0
  4253.1     .05       0  4572.9      .1       0  4940.6     .07       0
  4949.9      .1       0  5360.6     .08       0    5656     .05       0
Bank Sta=4660.21,5133.53
XS Rating Curve= 0 ,0
Exp/Cntr=0.3,0.1

Type RM Length L Ch R = 1 ,150109  ,306,306,306
BEGIN DESCRIPTION:
CHACON CREEK 201.0
END DESCRIPTION:
XS GIS Cut Line= 3
      1987874.27     13674277.63      1987202.73      13674116.9
      1986390.23     13673734.96
#Sta/Elev= 30
    4186   913.1  4214.9  912.95    4220  911.28  4351.3  907.07  4468.6  905.72
  4551.5  905.46 4775.78 904.204  4929.2  902.21  4965.6  899.76  4982.9  900.12
  4990.9  898.09  4991.8  897.29  5000.2  898.09  5017.6  902.33  5072.9  902.92
  5117.1  905.18  5130.7  905.14    5148  903.01  5153.5  904.96  5170.8  904.85
  5176.3   906.2  5199.1  904.18  5243.3  904.27  5250.3  902.32  5273.1  900.97
  5300.4  902.18 5401.09904.2042  5414.4  904.43  5496.3  906.08  5774.3  913.88
#Mann= 9 ,-1 , 0
    4186     .05       0  4468.6     .16       0  4551.5      .1       0
  4990.9     .07       0  5000.2      .1       0  5243.3     .16       0
  5300.4      .1       0  5414.4     .16       0  5496.3      .1       0
Bank Sta=4775.78,5401.09
XS Rating Curve= 0 ,0
Exp/Cntr=0.3,0.1

Type RM Length L Ch R = 1 ,149803  ,229,229,229
BEGIN DESCRIPTION:
Mapping XS 6bc931c8
END DESCRIPTION:
XS GIS Cut Line= 3
      1987900.26     13674245.05       1986801.6     13673518.46
      1986529.12     13673492.51
#Sta/Elev= 30
  4259.8  910.29    4305  908.67    4415  905.07  4538.3  903.86  4665.2  903.38
    4740  902.93 4796.16901.6125  4863.4   900.2  4879.8  897.13  4880.7  896.33
  4888.2  896.33  4889.1  897.13  4920.5  900.13  4956.7  900.48  4973.2  899.09
  4992.8  897.52  4998.8   897.9  5013.8  901.14  5049.9  902.07  5137.2  900.63
  5158.3   898.1  5188.4  900.18  5209.4  899.78  5251.5  901.42 5353.16901.6124
  5467.8  902.75  5583.6  903.79  5623.8  905.54  5764.4  908.97  5850.7   912.3
#Mann= 8 ,-1 , 0
  4259.8     .05       0    4305      .1       0  4538.3     .16       0
  4665.2      .1       0  4879.8     .07       0  4889.1      .1       0
  4973.2     .16       0  5467.8      .1       0
Bank Sta=4796.16,5353.16
XS Rating Curve= 0 ,0
Exp/Cntr=0.3,0.1

Type RM Length L Ch R = 1 ,149574  ,355,355,355
BEGIN DESCRIPTION:
Mapping XS 79a27b46
END DESCRIPTION:
XS GIS Cut Line= 3
      1987904.66     13674236.42      1987369.31     13673583.79
      1987181.81     13672430.14
#Sta/Elev= 30
  4299.6  909.89  4319.5  908.81  4463.9   904.5  4586.2  903.08  4733.7  902.39
  4818.8  901.17 4849.48899.8056  4883.5  898.96    4911  897.13  4920.7  895.12
  4921.5  894.32  4929.1  894.32    4930  895.12  4933.2  896.91  4939.7  898.55
  4947.5   898.7  4974.8  898.44  4997.1  896.07  5017.9   897.8  5081.7  899.42
  5213.6  897.63  5253.9  897.03  5261.5  895.59  5343.4   898.5  5377.4  899.67
 5390.11899.8054  5512.8  903.27  5764.2  907.57    6072  917.37  6312.5  921.95
#Mann= 8 ,-1 , 0
  4299.6     .05       0  4319.5      .1       0  4586.2     .16       0
  4920.7     .07       0    4930     .16       0  5213.6      .1       0
  5343.4     .16       0  5377.4      .1       0
Bank Sta=4849.48,5390.11
XS Rating Curve= 0 ,0
Exp/Cntr=0.3,0.1

Type RM Length L Ch R = 1 ,149219  ,356,356,356
BEGIN DESCRIPTION:
CHACON CREEK 200.0
END DESCRIPTION:
XS GIS Cut Line= 3
       1987981.3     13674091.62        1987725.       13673525.
      1987525.01     13672925.04
#Sta/Elev= 30
  4333.2  907.16  4456.7  902.98  4705.4  900.51  4842.9  899.06  4856.3   899.6
    4888898.4877  4940.8  897.04  4965.6  894.77  4976.2  892.99  4986.7  893.67
  5007.8   893.2  5018.3  894.42  5028.9  894.33  5039.4  896.32  5081.6  897.47
  5155.4  895.05  5165.9  893.65  5176.4  893.82    5187  892.65  5192.9     891
  5193.7   890.2  5201.3   890.2  5202.2     891 5236.51898.4877  5260.8  900.84
    5324  903.28  5418.9  904.79  5479.4  906.72  5485.2  906.98  5587.5  910.54
#Mann= 7 ,-1 , 0
  4333.2      .1       0  4705.4     .16       0  5039.4      .1       0
  5192.9     .07       0  5202.2      .1       0  5479.4     .16       0
  5485.2      .1       0
Bank Sta=4888,5236.51
XS Rating Curve= 0 ,0
Exp/Cntr=0.3,0.1

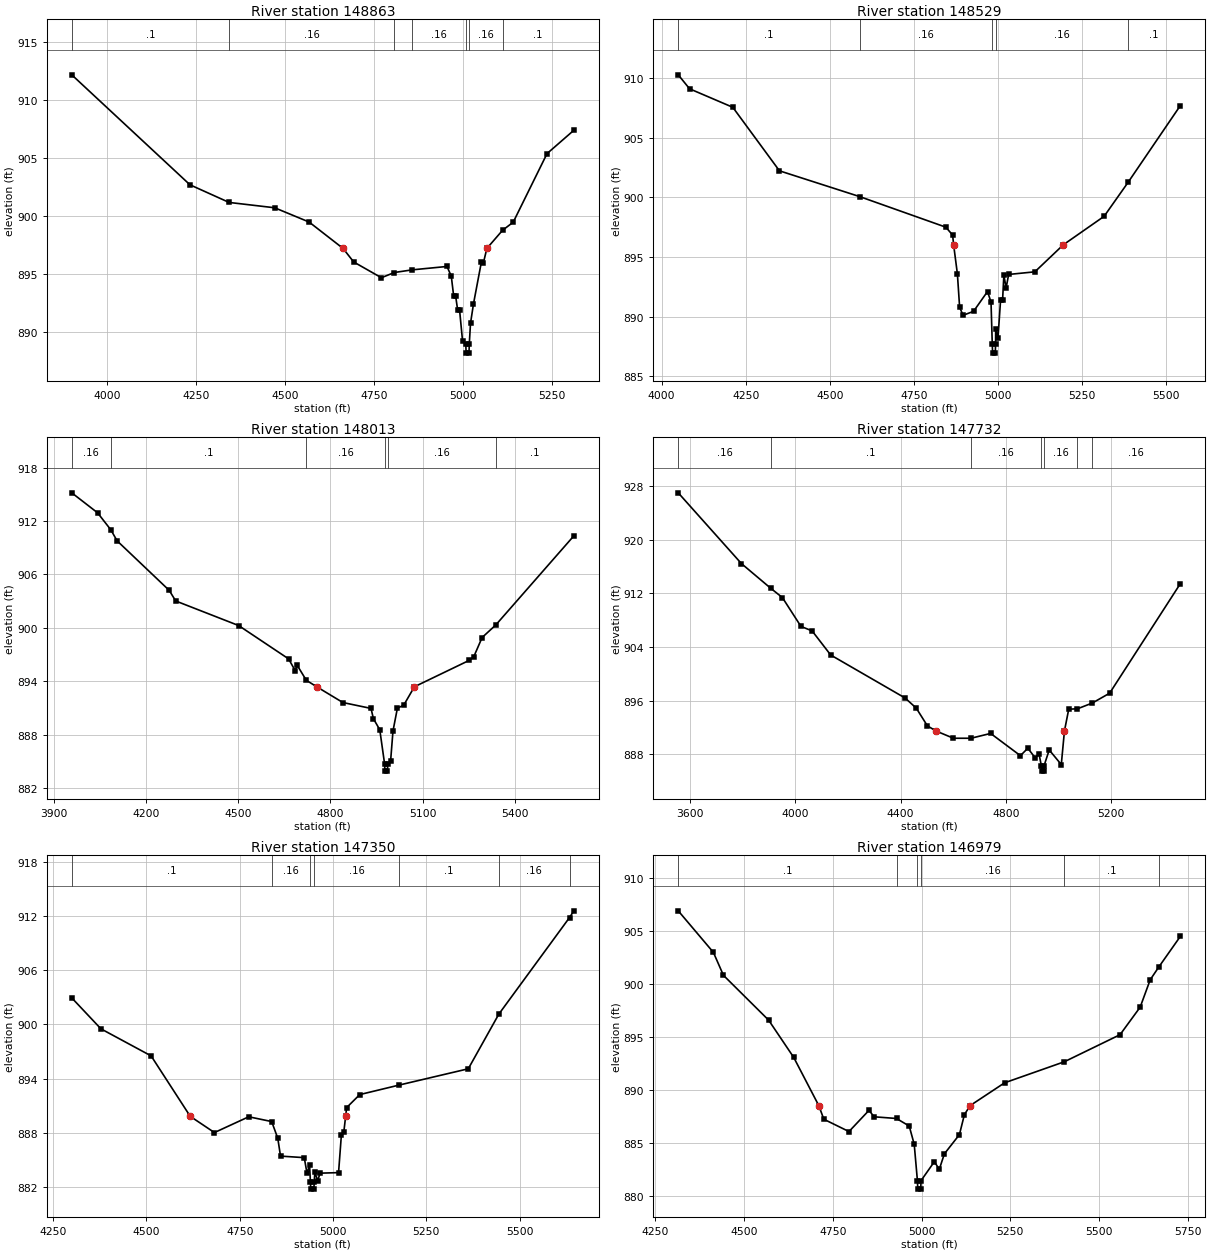
Type RM Length L Ch R = 1 ,148863  ,334,334,334
BEGIN DESCRIPTION:
CHACON CREEK 199.0
END DESCRIPTION:
XS GIS Cut Line= 3
        1988275.     13674224.99        1987875.       13673225.
      1987725.01     13672925.03
#Sta/Elev= 30
  3900.1  912.15  4232.6  902.67  4342.7  901.15  4470.9  900.69  4567.8  899.46
 4663.31897.1847  4693.1  896.02  4771.1  894.66  4807.6  895.11  4858.1  895.34
  4955.6  895.63  4967.7   894.8  4974.4  893.09  4979.9  893.09  4985.5  891.91
  4991.1  891.86  4999.5  889.18  5008.5  888.96  5009.5  888.16  5017.5  888.16
  5018.4  888.96  5021.8  890.73  5030.2  892.41  5052.6  896.05  5058.2  895.95
 5067.77897.1849    5112  898.75    5142  899.45  5237.1  905.36  5312.5  907.37
#Mann= 7 ,-1 , 0
  3900.1      .1       0  4342.7     .16       0  4807.6      .1       0
  4858.1     .16       0  5008.5     .07       0  5018.4     .16       0
    5112      .1       0
Bank Sta=4663.31,5067.77
XS Rating Curve= 0 ,0
Exp/Cntr=0.3,0.1

Type RM Length L Ch R = 1 ,148529  ,516,516,516
BEGIN DESCRIPTION:
CHACON CREEK 198.0
END DESCRIPTION:
XS GIS Cut Line= 3
      1988429.19     13674151.45        1988175.       13673225.
        1987825.       13672825.
#Sta/Elev= 30
  4049.2  910.26  4082.9  909.09  4211.4  907.54    4350  902.22  4588.5  900.06
  4844.5   897.5  4864.7  896.84 4867.66896.0236  4878.9  893.58  4885.5  890.79
  4895.8  890.12  4926.9  890.45  4968.4  892.11  4978.8  891.22  4982.5  887.75
  4983.5  886.95  4991.5  886.95  4992.4  887.75  4992.7     889  4999.5  888.22
  5007.3  891.42  5013.2  891.42    5017  893.47  5023.7  892.42  5031.2  893.54
  5109.1  893.76 5193.67896.0236    5315  898.41  5386.3  901.26  5541.4  907.68
#Mann= 5 ,-1 , 0
  4049.2      .1       0  4588.5     .16       0  4982.5     .07       0
  4992.4     .16       0  5386.3      .1       0
Bank Sta=4867.66,5193.67
XS Rating Curve= 0 ,0
Exp/Cntr=0.3,0.1

Type RM Length L Ch R = 1 ,148013  ,281,281,281
BEGIN DESCRIPTION:
CHACON CREEK 197.0
END DESCRIPTION:
XS GIS Cut Line= 3
      1989174.01     13673734.84       1988489.1     13673052.54
      1987975.01     13672625.01
#Sta/Elev= 30
  3957.4  915.16  4041.4  912.92  4084.6  911.01  4105.1  909.77  4274.8  904.21
    4296  903.02  4501.1  900.26  4663.7  896.52  4684.9  895.21    4692  895.78
  4721.3  894.12 4755.39893.3883  4840.5  891.62  4932.1  890.96  4939.9  889.81
  4960.7  888.56  4976.4  884.72  4977.4  883.92  4985.7  883.92  4986.6  884.72
  4995.9  885.04  5003.7  888.43    5018  890.98  5038.8  891.33 5073.39893.3884
  5252.4  896.36  5266.7  896.75    5294  898.92  5338.6  900.33  5592.8  910.33
#Mann= 6 ,-1 , 0
  3957.4     .16       0  4084.6      .1       0  4721.3     .16       0
  4976.4     .07       0  4986.6     .16       0  5338.6      .1       0
Bank Sta=4755.39,5073.39
XS Rating Curve= 0 ,0
Exp/Cntr=0.3,0.1

Type RM Length L Ch R = 1 ,147732  ,382,382,382
BEGIN DESCRIPTION:
CHACON CREEK 196.0
END DESCRIPTION:
XS GIS Cut Line= 3
        1989525.       13673775.        1988525.       13672775.
      1988174.99     13672424.99
#Sta/Elev= 30
  3554.2  927.02  3794.6  916.45  3905.2  912.79  3950.2  911.38  4020.9  907.07
  4063.3   906.4    4134   902.8  4416.9  896.38  4459.3  894.87  4501.7  892.22
 4534.83891.4494  4600.7  890.37  4667.5  890.37  4742.1  891.09  4855.3  887.77
  4883.6  888.88  4911.8  887.43    4926  888.07    4935  886.26    4936  885.46
  4944.3  885.46  4945.2  886.26  4964.9  888.62  5010.8  886.44 5022.78891.4513
  5039.1  894.71  5072.4  894.77  5128.9  895.63  5194.7   897.1  5463.4  913.45
#Mann= 7 ,-1 , 0
  3554.2     .16       0  3905.2      .1       0  4667.5     .16       0
    4935     .07       0  4945.2     .16       0  5072.4      .1       0
  5128.9     .16       0
Bank Sta=4534.83,5022.78
XS Rating Curve= 0 ,0
Exp/Cntr=0.3,0.1

Type RM Length L Ch R = 1 ,147350  ,371,371,371
BEGIN DESCRIPTION:
CHACON CREEK 195.0
END DESCRIPTION:
XS GIS Cut Line= 3
      1989324.99     13673224.99        1988875.       13672725.
      1988424.97     13672224.96
#Sta/Elev= 30
  4299.8  902.95  4377.9  899.52  4512.4  896.52 4617.31889.8162  4682.1  888.02
    4774  889.77  4835.5  889.24  4851.8  887.39  4859.2  885.41  4922.8  885.24
  4930.2   883.5    4937  884.42  4939.3  882.55  4940.3  881.75  4948.6  881.75
  4949.5  882.55  4951.2  883.66  4958.6  882.69  4965.4  883.52  5014.7  883.58
  5022.2  887.72  5028.9  888.12 5033.66889.8146  5036.4  890.79  5071.5  892.23
  5176.5  893.28  5362.3  895.09  5444.2  901.15  5633.7  911.86  5645.2   912.6
#Mann= 7 ,-1 , 0
  4299.8      .1       0  4835.5     .16       0  4939.3     .07       0
  4949.5     .16       0  5176.5      .1       0  5444.2     .16       0
  5633.7      .1       0
Bank Sta=4617.31,5033.66
XS Rating Curve= 0 ,0
Exp/Cntr=0.3,0.1

Type RM Length L Ch R = 1 ,146979  ,335,335,335
BEGIN DESCRIPTION:
CHACON CREEK 194.0
END DESCRIPTION:
XS GIS Cut Line= 3
      1989625.02     13673125.02        1989125.       13672625.
      1988625.02     13672125.02
#Sta/Elev= 30
  4314.5  906.89  4413.5  902.98  4441.8  900.82  4569.1   896.6  4639.8  893.09
 4710.34888.5576  4724.6  887.27  4795.4  886.11  4851.9  888.11  4866.1   887.5
  4929.3  887.34  4965.1  886.63  4979.2  884.91  4988.2  881.49  4989.2  880.69
  4997.5  880.69  4998.4  881.49  5035.8  883.27  5049.9  882.56  5064.1  884.01
  5106.5  885.82  5120.6  887.71 5136.89888.5578  5233.8   890.7    5402  892.68
    5559  895.23  5615.6  897.82  5643.9   900.4  5668.9  901.64  5728.7  904.48
#Mann= 6 ,-1 , 0
  4314.5      .1       0  4929.3     .16       0  4988.2     .07       0
  4998.4     .16       0    5402      .1       0  5668.9     .16       0
Bank Sta=4710.34,5136.89
XS Rating Curve= 0 ,0
Exp/Cntr=0.3,0.1

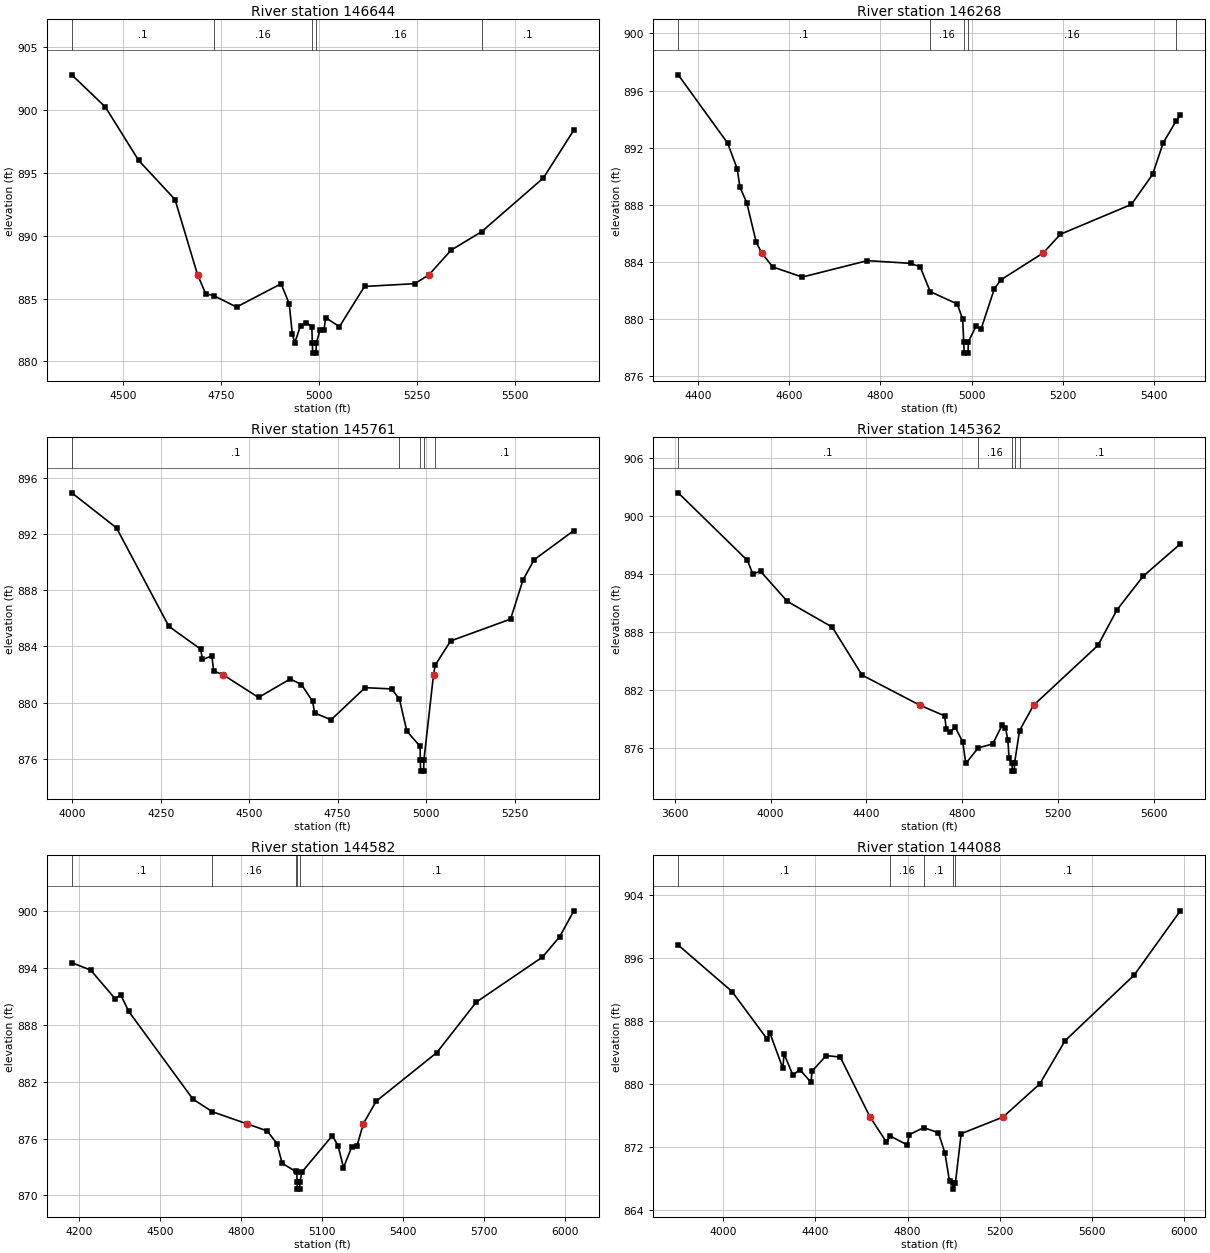
Type RM Length L Ch R = 1 ,146644  ,376,376,376
BEGIN DESCRIPTION:
CHACON CREEK 193.0
END DESCRIPTION:
XS GIS Cut Line= 3
      1989774.98     13672924.98        1989375.       13672425.
        1988875.       13672025.
#Sta/Elev= 30
    4369  902.82  4454.6  900.26  4539.5  896.01  4632.3  892.89 4689.92 886.895
  4710.7  885.38  4731.1  885.24  4789.2  884.33  4902.8  886.18  4923.6   884.6
  4931.6  882.15    4938   881.5  4952.5  882.85  4966.9  883.09  4981.3  882.78
  4982.6  881.46  4983.5  880.66  4991.8  880.66  4992.8  881.46  5002.1   882.5
  5012.5  882.54  5016.5  883.48  5051.7  882.77  5115.7  885.97  5243.8  886.19
 5279.96886.8952  5336.6  888.86  5414.4  890.33    5572  894.61  5649.6  898.42
#Mann= 5 ,-1 , 0
    4369      .1       0  4731.1     .16       0  4982.6     .07       0
  4992.8     .16       0  5414.4      .1       0
Bank Sta=4689.92,5279.96
XS Rating Curve= 0 ,0
Exp/Cntr=0.3,0.1

Type RM Length L Ch R = 1 ,146268  ,507,507,507
BEGIN DESCRIPTION:
CHACON CREEK 192.0
END DESCRIPTION:
XS GIS Cut Line= 3
      1989875.02     13672625.03        1989525.       13672125.
        1989075.       13671925.
#Sta/Elev= 30
  4355.8   897.1  4464.4  892.31  4485.3  890.51  4491.4  889.22  4506.2  888.15
  4527.2  885.36 4539.16884.6228  4563.3  883.64  4628.3  882.93  4771.3  884.08
  4866.3  883.89  4887.3  883.64  4909.2  881.91  4968.9  881.04  4980.5  879.97
  4982.9   878.4  4983.8   877.6  4992.2   877.6  4993.1   878.4  5009.9  879.49
  5020.9  879.28  5050.3  882.12  5064.7  882.74 5157.65884.6232  5195.3  885.93
  5351.2  888.02  5397.7  890.12    5421  892.33  5448.9  893.84  5458.6  894.28
#Mann= 5 ,-1 , 0
  4355.8      .1       0  4909.2     .16       0  4982.9     .07       0
  4993.1     .16       0  5448.9      .1       0
Bank Sta=4539.16,5157.65
XS Rating Curve= 0 ,0
Exp/Cntr=0.3,0.1

Type RM Length L Ch R = 1 ,145761  ,399,399,399
BEGIN DESCRIPTION:
CHACON CREEK 191.0
END DESCRIPTION:
XS GIS Cut Line= 3
      1990024.99     13672474.98        1989799.     13671794.72
      1989189.82     13671445.88
#Sta/Elev= 30
  3998.6  894.95    4125  892.45    4273  885.43  4362.7  883.81    4368  883.07
  4394.4  883.32  4399.7  882.24 4426.25881.9822  4526.3  880.36    4616  881.68
  4647.7  881.28  4679.4  880.08  4684.6  879.26  4731.5  878.77  4827.5  881.06
  4902.3  880.97  4924.4  880.25  4945.5  877.96  4982.9  876.88  4983.5  875.91
  4984.5  875.11  4992.9  875.11  4993.8  875.91 5020.82881.9819  5025.7  882.67
  5069.2  884.39  5238.6  885.95  5273.6  888.73  5305.2  890.18  5417.4  892.26
#Mann= 5 ,-1 , 0
  3998.6      .1       0  4924.4     .16       0  4983.5     .07       0
  4993.8     .16       0  5025.7      .1       0
Bank Sta=4426.25,5020.82
XS Rating Curve= 0 ,0
Exp/Cntr=0.3,0.1

Type RM Length L Ch R = 1 ,145362  ,780,780,780
BEGIN DESCRIPTION:
CHACON CREEK 190.0
END DESCRIPTION:
XS GIS Cut Line= 3
      1991132.33     13671815.56      1990075.04     13671508.27
      1989173.96     13671086.37
#Sta/Elev= 30
  3614.7  902.41  3903.5  895.41  3925.4  894.04  3958.9  894.27  4070.1  891.17
  4257.6  888.51  4382.2  883.54 4624.19880.4135  4726.8  879.32  4733.8  877.97
  4748.9   877.6    4771  878.14  4802.3  876.63  4815.2   874.4  4867.2  876.01
  4927.5  876.41  4967.6   878.4  4980.8  878.08  4990.5  876.86    4996  874.94
  5008.2   874.4  5009.1   873.6  5017.6   873.6  5018.5   874.4  5039.6   877.8
 5097.86880.4136  5366.9  886.62  5446.4   890.3    5555  893.76  5710.7  897.12
#Mann= 5 ,-1 , 0
  3614.7      .1       0  4867.2     .16       0  5008.2     .07       0
  5018.5     .16       0  5039.6      .1       0
Bank Sta=4624.19,5097.86
XS Rating Curve= 0 ,0
Exp/Cntr=0.3,0.1

Type RM Length L Ch R = 1 ,144582  ,494,494,494
BEGIN DESCRIPTION:
CHACON CREEK 189.0
END DESCRIPTION:
XS GIS Cut Line= 3
      1990974.96     13671274.98        1990175.       13670975.
      1989179.79     13670842.84
#Sta/Elev= 30
  4173.2  894.59  4243.5   893.8  4334.2  890.76  4353.8  891.22  4384.1  889.44
  4621.7  880.17  4693.4  878.84 4821.02877.5643  4896.7  876.81  4932.3  875.48
  4951.9  873.39  5001.4  872.54  5006.2  872.52  5007.1  871.46  5007.9  870.66
  5016.9  870.66  5017.8  871.46  5024.9  872.46  5137.5  876.31  5158.7  875.26
  5178.9  872.94  5209.1  875.09  5229.3  875.26 5252.22877.5643  5299.9  879.95
  5524.1  885.08  5670.7  890.43  5915.3  895.18    5979  897.33  6031.5  900.07
#Mann= 5 ,-1 , 0
  4173.2      .1       0  4693.4     .16       0  5001.4      .1       0
  5007.1     .07       0  5017.8      .1       0
Bank Sta=4821.02,5252.22
XS Rating Curve= 0 ,0
Exp/Cntr=0.3,0.1

Type RM Length L Ch R = 1 ,144088  ,709,709,709
BEGIN DESCRIPTION:
CHACON CREEK 188.0
END DESCRIPTION:
XS GIS Cut Line= 3
        1991325.       13670725.        1990125.       13670525.
      1989165.62     13670558.09
#Sta/Elev= 30
  3805.5  897.58  4038.7  891.68  4190.7  885.66  4203.4  886.37  4259.2  881.92
  4264.2  883.79  4302.3  881.06  4332.7  881.77  4380.8  880.16  4385.9  881.58
  4446.7  883.54  4507.6  883.37 4637.01875.7415  4707.8  872.58    4725  873.33
    4799  872.19  4806.6   873.5  4869.6   874.4  4933.3  873.75  4961.2  871.22
  4981.5  867.61  4996.4  867.39  4997.3  866.59  5007.1  867.39  5032.1  873.63
  5213.4875.7416  5372.3  879.94  5482.3  885.43  5782.5  893.79    5982  901.93
#Mann= 5 ,-1 , 0
  3805.5      .1       0    4725     .16       0  4869.6      .1       0
  4996.4     .07       0  5007.1      .1       0
Bank Sta=4637.01,5213.4
XS Rating Curve= 0 ,0
Exp/Cntr=0.3,0.1

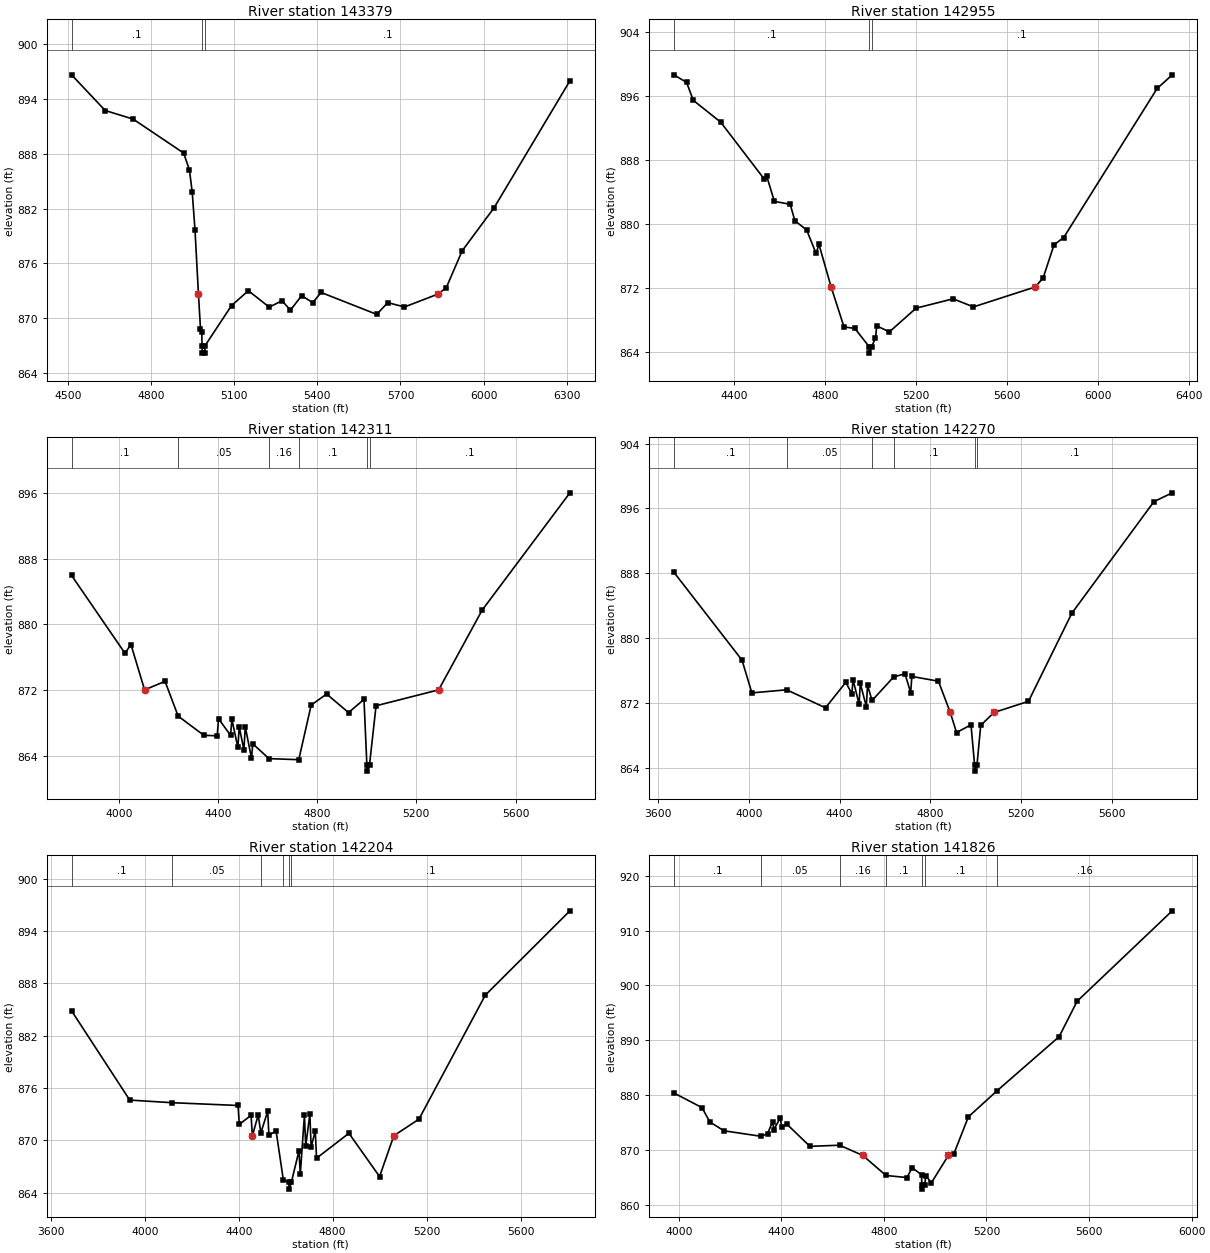
Type RM Length L Ch R = 1 ,143379  ,424,424,424
BEGIN DESCRIPTION:
CHACON CREEK 187.0
END DESCRIPTION:
XS GIS Cut Line= 3
      1991144.78     13670287.25      1990353.16     13670155.31
       1989360.1     13670065.03
#Sta/Elev= 30
  4512.3  896.65  4633.7  892.74  4734.5   891.8  4916.9  888.08  4937.9  886.23
    4948  883.79  4958.1  879.61 4970.51872.6078  4977.8  868.84  4982.8   868.5
  4983.2  866.95    4984  866.15  4993.2  866.15    4994  866.95  5089.9  871.36
  5150.8  872.99  5226.2  871.19  5272.4  871.89  5302.8  870.86  5343.1  872.45
  5383.3  871.68  5413.4   872.8  5614.2   870.4  5654.4  871.68  5714.6  871.21
  5834.5872.6074  5865.3  873.31  5923.1  877.37  6038.6   882.1    6312  895.99
#Mann= 3 ,-1 , 0
  4512.3      .1       0  4983.2     .07       0    4994      .1       0
Bank Sta=4970.51,5834.5
XS Rating Curve= 0 ,0
Exp/Cntr=0.3,0.1

Type RM Length L Ch R = 1 ,142955  ,644,644,644
BEGIN DESCRIPTION:
Mapping XS 22f95d55
END DESCRIPTION:
XS GIS Cut Line= 4
      1991348.79     13670022.78      1990580.59      13669818.8
      1990098.82     13670061.85      1989249.08     13669966.47
#Sta/Elev= 30
  4134.8  898.69  4190.5  897.74  4219.9   895.5  4340.5  892.76    4531  885.66
  4542.2  886.04  4576.3  882.84  4645.7  882.48  4666.4  880.42  4718.1  879.26
  4759.5  876.32  4772.1  877.46 4825.57872.1254  4882.2  867.12  4929.6  866.94
  4992.8  864.64  4993.6  863.84  5003.6  864.64  5020.5  865.74  5026.1  867.25
  5081.5   866.5  5198.9  869.47  5361.5  870.64  5451.1  869.63  5722.5872.1254
  5757.3  873.27  5805.1  877.41  5847.4  878.31    6258  896.98  6324.3  898.68
#Mann= 3 ,-1 , 0
  4134.8      .1       0  4992.8     .07       0  5003.6      .1       0
Bank Sta=4825.57,5722.5
XS Rating Curve= 0 ,0
Exp/Cntr=0.3,0.1

Type RM Length L Ch R = 1 ,142311  ,41,41,41
BEGIN DESCRIPTION:
Mapping XS e3a879ce
END DESCRIPTION:
XS GIS Cut Line= 6
      1990962.53     13669918.62      1990298.48     13669653.87
      1990168.27     13669610.46      1990142.23     13669679.91
       1990020.7     13670031.47      1989313.21     13669957.68
#Sta/Elev= 30
  3809.6  885.96  4024.8   876.5    4049  877.56 4104.07872.0455  4186.5  873.08
  4239.4  868.85  4342.9  866.52  4396.8  866.45  4402.2  868.53  4450.7  866.52
  4456.1  868.44  4480.3  865.04  4485.7  867.54  4504.6  864.74    4510  867.57
  4535.1  863.72  4540.3  865.48  4605.8  863.68  4725.8  863.55  4775.8  870.19
  4838.2  871.54  4926.4  869.28  4988.8  870.88  5000.4  862.96  5001.2  862.16
  5011.2  862.96  5037.5  870.11 5289.95872.0449  5465.5  881.75  5819.2  896.01
#Mann= 6 ,-1 , 0
  3809.6      .1       0  4239.4     .05       0  4605.8     .16       0
  4725.8      .1       0  5000.4     .07       0  5011.2      .1       0
Bank Sta=4104.07,5289.95
XS Rating Curve= 0 ,0
Exp/Cntr=0.3,0.1

Type RM Length L Ch R = 1 ,142270  ,66,66,66
BEGIN DESCRIPTION:
Mapping XS 6db1c506
END DESCRIPTION:
XS GIS Cut Line= 6
      1991031.94     13669918.61       1990354.9     13669636.51
      1990155.25      13669571.4       1990107.5     13669623.48
      1989990.32     13669996.75      1989204.77     13669922.97
#Sta/Elev= 30
  3670.6  888.11  3970.6  877.26    4014  873.22  4167.1   873.6  4338.3  871.38
  4427.6  874.52  4454.3  873.12  4459.6  874.84  4486.2  871.83  4491.5  874.38
  4518.1  871.53  4523.4  874.17  4543.4  872.28  4638.5  875.19  4688.1  875.58
  4713.5  873.26  4718.6  875.25  4835.7  874.66 4887.75870.7999  4915.4  868.32
    4979  869.28  4994.8  864.36  4995.6  863.56  5005.6  864.36  5021.9  869.21
 5080.27870.7999  5232.3  872.18  5423.1  883.05  5784.7  896.83  5865.3  897.92
#Mann= 6 ,-1 , 0
  3670.6      .1       0  4167.1     .05       0  4543.4     .16       0
  4638.5      .1       0  4994.8     .07       0  5005.6      .1       0
Bank Sta=4887.75,5080.27
XS Rating Curve= 0 ,0
Exp/Cntr=0.3,0.1

Type RM Length L Ch R = 1 ,142204  ,378,378,378
BEGIN DESCRIPTION:
Mapping XS 6405e13b
END DESCRIPTION:
XS GIS Cut Line= 6
       1990984.2     13669844.83      1990229.03     13669567.06
      1990137.89     13669545.36      1990103.16     13669562.72
      1989920.87     13669979.39      1989197.99     13669884.16
#Sta/Elev= 30
  3688.6  884.85  3936.2  874.61  4115.5  874.31  4397.1  873.99  4402.4  871.82
  4452.7  872.86 4457.99870.5143  4483.1   872.9  4494.2  870.85  4523.4  873.32
  4528.5  870.58  4559.1  871.06  4590.1  865.43  4613.5  865.19  4614.3  864.39
  4624.3  865.19  4656.6   868.8  4662.1   866.1  4679.7  872.85  4685.2  869.34
  4702.8     873  4708.3  869.21  4725.8  871.08  4731.3  867.94  4869.1   870.8
  4999.6  865.83 5060.25870.5165  5167.2  872.42  5449.6  886.65  5809.7  896.33
#Mann= 6 ,-1 , 0
  3688.6      .1       0  4115.5     .05       0  4494.2     .16       0
  4590.1      .1       0  4613.5     .07       0  4624.3      .1       0
Bank Sta=4457.99,5060.25
XS Rating Curve= 0 ,0
Exp/Cntr=0.3,0.1

Type RM Length L Ch R = 1 ,141826  ,398,398,398
BEGIN DESCRIPTION:
Mapping XS f867484f
END DESCRIPTION:
XS GIS Cut Line= 4
      1990906.16     13669797.11      1990146.57     13669510.64
      1989803.69     13669627.83      1989070.18     13669397.79
#Sta/Elev= 30
  3981.3  880.36  4090.6   877.7  4121.5  875.08  4175.9  873.47  4319.3  872.47
  4346.4  872.92  4365.9  875.14  4371.2  873.69  4396.1  875.84  4401.4   874.2
  4420.7  874.72  4511.6  870.63  4627.3  870.83 4717.51868.9755  4808.1  865.31
  4889.9  864.93  4910.3  866.73  4946.9  865.43  4947.8  863.62  4948.6  862.82
  4958.7  863.62  4963.9  865.27    4985  863.96 5051.61868.9753  5072.1  869.18
  5129.5  876.01  5241.8  880.79  5483.3  890.64  5553.4   897.1  5924.2   913.6
#Mann= 7 ,-1 , 0
  3981.3      .1       0  4319.3     .05       0  4627.3     .16       0
  4808.1      .1       0  4947.8     .07       0  4958.7      .1       0
  5241.8     .16       0
Bank Sta=4717.51,5051.61
XS Rating Curve= 0 ,0
Exp/Cntr=0.3,0.1

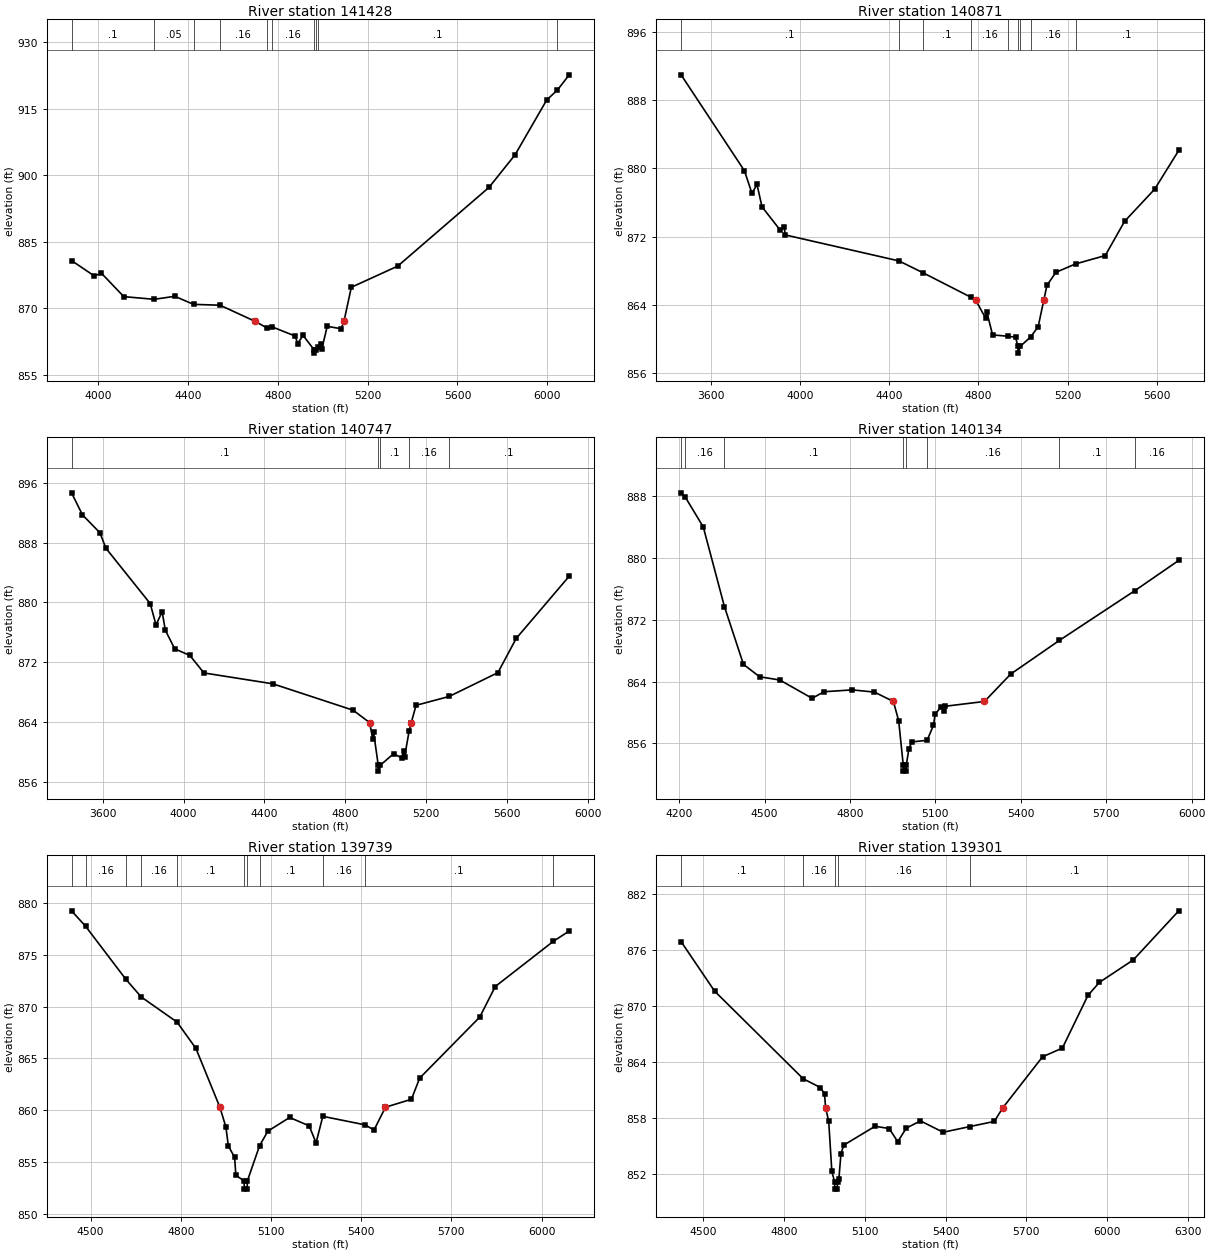
Type RM Length L Ch R = 1 ,141428  ,557,557,557
BEGIN DESCRIPTION:
Mapping XS e66bc23f
END DESCRIPTION:
XS GIS Cut Line= 5
      1990939.95     13669790.14      1990468.62     13669615.67
      1990132.68     13669490.67      1989911.81       13668941.
       1989195.2     13668675.57
#Sta/Elev= 30
  3880.5  880.79  3981.7  877.33  4013.7  877.94  4113.2  872.66  4248.4  872.05
  4340.4  872.73  4424.4  870.91  4542.2  870.72 4699.47867.0552    4750  865.63
  4775.6  865.81    4877  863.76    4888  862.07  4912.2  863.91  4960.5  860.71
  4961.3  859.91  4971.4  860.71  4978.6  861.22  4990.1  862.06  4995.5  860.78
  5019.7  865.96  5081.7  865.41 5094.22867.0554  5127.2  874.77  5333.9  879.54
  5740.5   897.3  5856.7  904.65    5998  917.04  6045.4  919.26  6098.1   922.7
#Mann= 10 ,-1 , 0
  3880.5      .1       0  4248.4     .05       0  4424.4      .1       0
  4542.2     .16       0    4750      .1       0  4775.6     .16       0
  4960.5     .07       0  4971.4     .16       0  4978.6      .1       0
  6045.4     .16       0
Bank Sta=4699.47,5094.22
XS Rating Curve= 0 ,0
Exp/Cntr=0.3,0.1

Type RM Length L Ch R = 1 ,140871  ,124,124,124
BEGIN DESCRIPTION:
Mapping XS 66e06a5b
END DESCRIPTION:
XS GIS Cut Line= 6
      1991157.82     13669862.19      1990251.26     13669397.51
      1990367.05     13669002.54      1990450.39      13668856.7
      1990429.55     13668585.87      1990144.82     13668363.64
#Sta/Elev= 30
  3467.3  890.98  3751.4  879.72  3785.1  877.07  3807.6  878.11  3830.1  875.49
  3912.4  872.73    3929  873.16  3934.6  872.19  4444.3  869.14  4553.4  867.73
  4765.8  864.89 4789.06864.5103  4832.2  862.42  4837.4   863.2  4863.8  860.46
  4933.2   860.3  4966.8  860.19  4977.2  859.12    4978  858.32  4988.1  859.12
  5034.3  860.22  5068.1  861.41 5093.11  864.51  5107.4  866.27  5147.5   867.8
  5235.8  868.79  5368.8  869.77  5455.7  873.79  5590.4  877.56  5698.4  882.11
#Mann= 9 ,-1 , 0
  3467.3      .1       0  4444.3     .16       0  4553.4      .1       0
  4765.8     .16       0  4933.2      .1       0  4977.2     .07       0
  4988.1      .1       0  5034.3     .16       0  5235.8      .1       0
Bank Sta=4789.06,5093.11
XS Rating Curve= 0 ,0
Exp/Cntr=0.3,0.1

Type RM Length L Ch R = 1 ,140747  ,613,613,613
BEGIN DESCRIPTION:
Mapping XS 900697ed
END DESCRIPTION:
XS GIS Cut Line= 5
      1991353.15     13669780.31      1990367.05     13669335.87
      1990519.83      13669044.2      1990589.28     13668509.48
      1990130.91     13668287.24
#Sta/Elev= 30
  3446.5  894.63  3500.4  891.69  3587.1  889.29    3616  887.25  3835.3  879.85
  3863.9  877.01  3894.2  878.76  3910.1  876.29  3956.4  873.82  4031.3  872.93
  4100.7   870.6  4441.1  869.15  4837.9  865.63 4919.71863.9753  4934.3  861.85
  4939.3  862.67  4962.1   858.3  4962.9   857.5    4973   858.3  5038.1  859.83
  5078.4  859.25  5087.6  860.24  5092.6  859.43  5114.6  862.83 5125.45863.9753
    5149  866.28  5312.5  867.46  5553.6  870.64  5643.9   875.2    5906  883.51
#Mann= 5 ,-1 , 0
  3446.5      .1       0  4962.1     .07       0    4973      .1       0
  5114.6     .16       0  5312.5      .1       0
Bank Sta=4919.71,5125.45
XS Rating Curve= 0 ,0
Exp/Cntr=0.3,0.1

Type RM Length L Ch R = 1 ,140134  ,395,395,395
BEGIN DESCRIPTION:
CHACON CREEK 183.0
END DESCRIPTION:
XS GIS Cut Line= 3
        1991625.       13669225.        1991075.       13668625.
      1990314.55     13668082.26
#Sta/Elev= 30
  4206.6  888.46  4221.8  887.88  4284.6  884.03  4358.9  873.71  4425.8  866.22
  4482.5  864.62  4553.4   864.2  4666.9  861.83  4708.8  862.68  4808.1  862.92
  4885.8  862.63 4952.33861.4199  4970.9  858.93    4987  853.19  4987.8  852.39
  4997.2  852.39  4997.9  853.19  5006.7  855.26  5017.1  856.18  5070.9  856.38
  5093.1  858.33  5099.2  859.77  5120.1  860.74  5128.7   860.2  5134.8   860.8
 5272.38  861.42  5364.5  864.97  5535.4  869.33  5801.4   875.8  5954.8   879.7
#Mann= 8 ,-1 , 0
  4206.6      .1       0  4221.8     .16       0  4358.9      .1       0
    4987     .07       0  4997.9      .1       0  5070.9     .16       0
  5535.4      .1       0  5801.4     .16       0
Bank Sta=4952.33,5272.38
XS Rating Curve= 0 ,0
Exp/Cntr=0.3,0.1

Type RM Length L Ch R = 1 ,139739  ,438,438,438
BEGIN DESCRIPTION:
CHACON CREEK 182.0
END DESCRIPTION:
XS GIS Cut Line= 3
      1991861.37     13668759.31        1991425.       13668425.
      1990460.39     13667884.35
#Sta/Elev= 30
  4436.6  879.26  4483.3  877.77  4617.2  872.65  4668.5  870.94  4787.6  868.51
  4850.3  865.97 4930.02860.2893    4950  858.38  4958.2  856.55    4979  855.45
  4983.2  853.71  5010.5  853.18  5011.3  852.38  5020.7  852.38  5021.5  853.18
  5061.9  856.56  5089.5  857.98  5162.1   859.3  5227.1  858.49    5250  856.85
  5272.4  859.41  5412.7  858.59  5442.8  858.09  5480.8  860.29  5567.2  861.06
  5594.6   863.1  5794.3  868.99  5846.1  871.95  6039.5  876.32  6092.1  877.31
#Mann= 11 ,-1 , 0
  4436.6      .1       0  4483.3     .16       0  4617.2      .1       0
  4668.5     .16       0  4787.6      .1       0  5010.5     .07       0
  5021.5      .1       0  5061.9      .1       0  5272.4     .16       0
  5412.7      .1       0  6039.5     .16       0
Bank Sta=4930.02,5480.8
XS Rating Curve= 0 ,0
Exp/Cntr=0.3,0.1

Type RM Length L Ch R = 1 ,139301  ,508,508,508
BEGIN DESCRIPTION:
CHACON CREEK 181.0
END DESCRIPTION:
XS GIS Cut Line= 3
      1991975.02     13668575.03        1991675.       13668075.
      1990475.03     13667675.01
#Sta/Elev= 30
  4417.8  876.92  4542.2  871.61  4871.1  862.21  4934.8  861.27  4950.4  860.59
 4954.51859.0808  4965.9  857.67  4977.6  852.27  4987.7  851.17  4988.5  850.37
  4997.9  850.37  4998.7  851.17  5003.6  851.41  5011.5  854.19    5022  855.09
    5138  857.11  5190.7  856.87  5222.3  855.45  5253.9  856.91  5306.6  857.69
  5390.9  856.47  5490.1  857.08  5580.7  857.63 5612.13 859.079  5759.9  864.56
  5833.7   865.5  5928.5  871.14  5970.7  872.54  6097.2  874.96  6265.8  880.22
#Mann= 5 ,-1 , 0
  4417.8      .1       0  4871.1     .16       0  4987.7     .07       0
  4998.7     .16       0  5490.1      .1       0
Bank Sta=4954.51,5612.13
XS Rating Curve= 0 ,0
Exp/Cntr=0.3,0.1