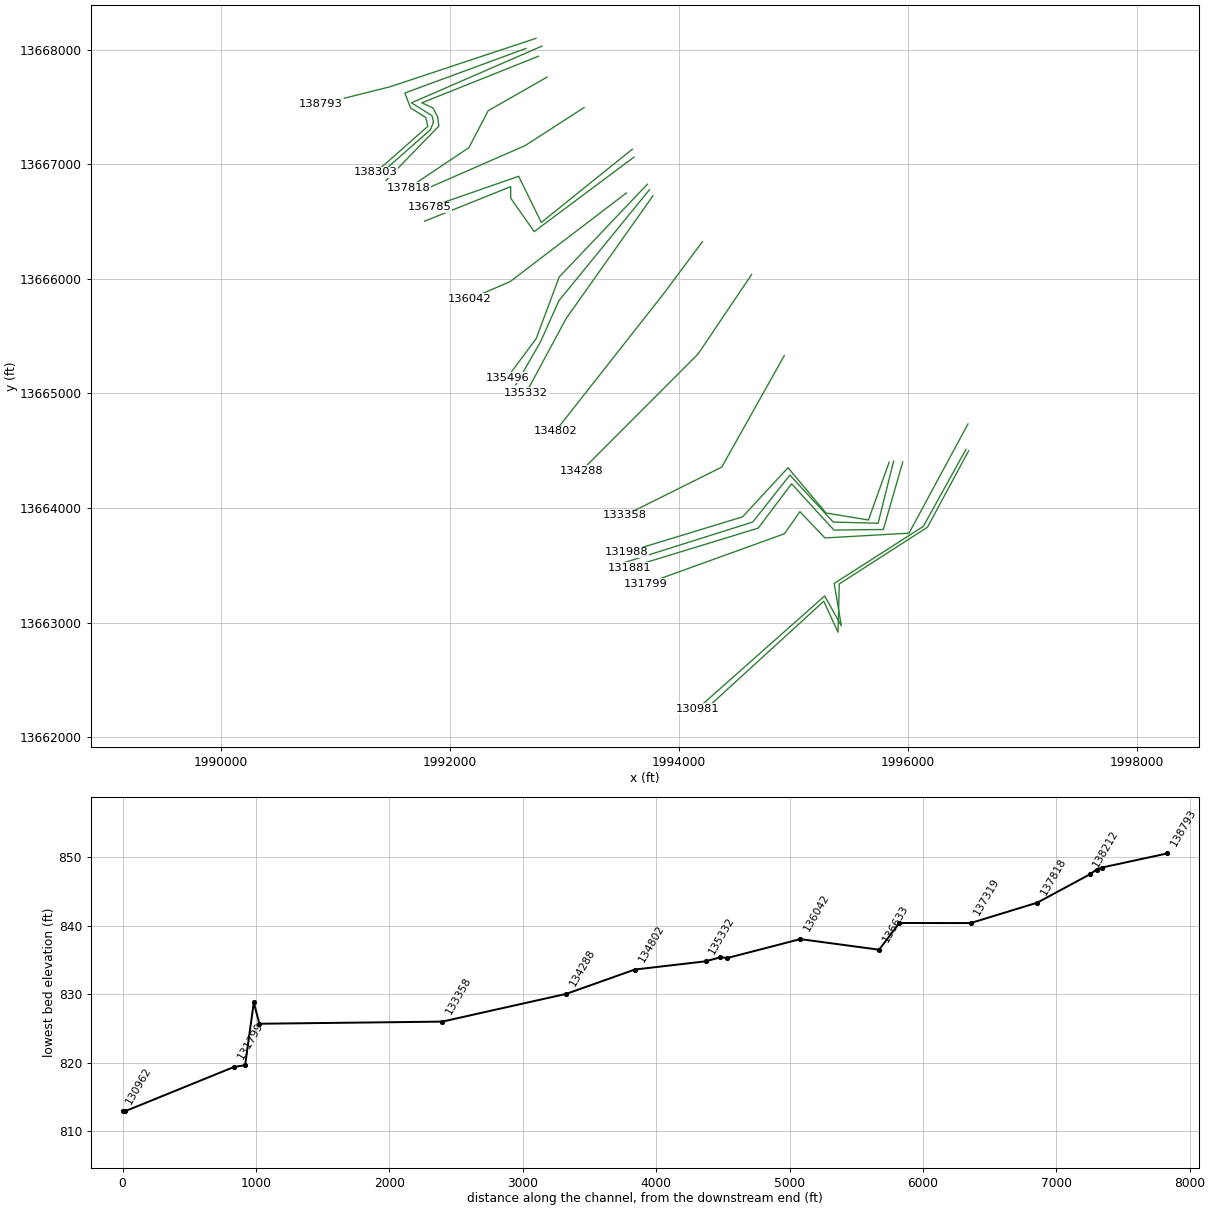
HEC-RAS study CHACON CREEK.prj: CHACON CREEK Base Level Engineering

--- CHACON CREEK.g01 (geometry) --- (continued)

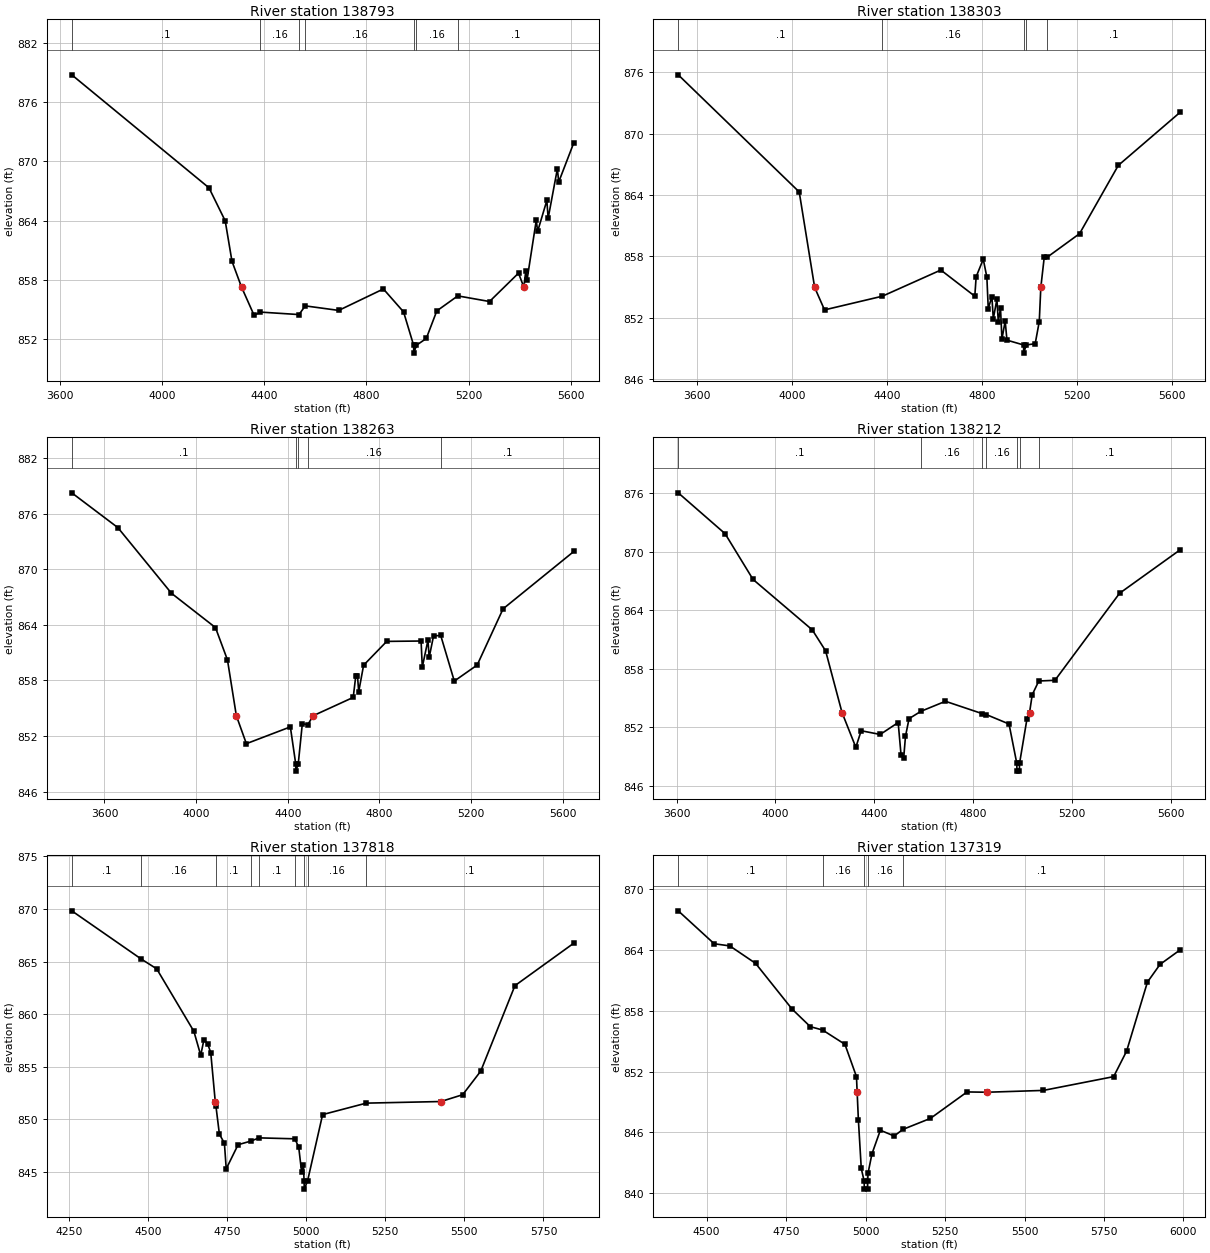
Type RM Length L Ch R = 1 ,138793  ,490,490,490
BEGIN DESCRIPTION:
CHACON CREEK 180.0
END DESCRIPTION:
XS GIS Cut Line= 3
      1992752.06     13668097.89        1991475.       13667675.
      1990875.02     13667525.01
#Sta/Elev= 30
  3647.3  878.74    4184  867.31  4247.4  863.97  4273.9  859.88  4311.2857.2731
  4360.5  854.41  4385.3  854.74    4536  854.49  4560.5  855.37  4691.3  854.91
  4866.1  857.08    4945  854.76  4984.3  851.39    4985  850.59  4995.5  851.39
  5033.8  852.07    5075  854.86  5157.1  856.38  5281.2  855.81  5394.6  858.68
 5415.31857.2728  5422.9  858.85  5428.1  858.02  5464.1  864.04  5469.3   862.9
  5505.4  866.03  5510.5  864.23  5546.6  869.24  5551.8   867.9    5611  871.88
#Mann= 7 ,-1 , 0
  3647.3      .1       0  4385.3     .16       0    4536      .1       0
  4560.5     .16       0  4984.3     .07       0  4995.5     .16       0
  5157.1      .1       0
Bank Sta=4311.2,5415.31
XS Rating Curve= 0 ,0
Exp/Cntr=0.3,0.1

Type RM Length L Ch R = 1 ,138303  ,40,40,40
BEGIN DESCRIPTION:
Mapping XS 96f69788
END DESCRIPTION:
XS GIS Cut Line= 6
      1992663.52     13668009.35       1991606.2     13667621.31
      1991655.68     13667491.11      1991788.49     13667407.77
      1991806.72     13667329.65      1991351.79      13666929.3
#Sta/Elev= 30
  3519.3  875.75    4029  864.29 4094.03854.9442  4135.6  852.75  4379.2  854.09
  4625.6  856.65  4768.7  854.09  4774.4  855.99  4804.3  857.71  4819.5  855.96
  4825.4  852.87  4840.6  854.06  4846.6  851.88  4861.8  853.79  4867.7  851.61
    4877  852.92    4883  849.89  4896.7  851.66  4904.1  849.79  4974.1  849.32
  4974.8  848.52  4985.3  849.32  5023.1  849.44  5040.3  851.61 5046.79854.9435
  5061.2   857.9    5074  857.91  5210.1  860.21  5373.3  866.89  5634.5   872.1
#Mann= 5 ,-1 , 0
  3519.3      .1       0  4379.2     .16       0  4974.1     .07       0
  4985.3     .16       0    5074      .1       0
Bank Sta=4094.03,5046.79
XS Rating Curve= 0 ,0
Exp/Cntr=0.3,0.1

Type RM Length L Ch R = 1 ,138263  ,51,51,51
BEGIN DESCRIPTION:
CHACON CREEK 179.0
END DESCRIPTION:
XS GIS Cut Line= 6
      1992804.12     13668030.17      1991663.49     13667535.38
      1991843.18      13667423.4       1991856.2     13667368.71
      1991830.16       13667301.      1991374.44     13666899.97
#Sta/Elev= 30
  3457.3  878.23  3658.4  874.48  3892.4   867.4  4084.5   863.7  4136.9  860.21
 4175.66854.1944  4219.4  851.18  4411.4  852.99  4434.7  849.02  4435.4  848.22
  4445.9  849.02  4463.7  853.34  4487.3  853.22 4511.07854.1943  4685.8  856.17
  4697.1  858.51  4704.4  858.51  4709.7  856.78  4731.1  859.64    4832  862.21
    4982  862.25  4987.3  859.44    5012  862.34  5017.3  860.48  5036.4   862.8
  5067.7  862.85    5127  857.93  5226.9  859.66  5339.9  865.72  5648.8  871.91
#Mann= 5 ,-1 , 0
  3457.3      .1       0  4434.7     .07       0  4445.9      .1       0
  4487.3     .16       0  5067.7      .1       0
Bank Sta=4175.66,4511.07
XS Rating Curve= 0 ,0
Exp/Cntr=0.3,0.1

Type RM Length L Ch R = 1 ,138212  ,394,394,394
BEGIN DESCRIPTION:
Mapping XS 636e0477
END DESCRIPTION:
XS GIS Cut Line= 6
      1992772.84     13667941.62      1991754.64     13667535.38
      1991850.99     13667491.11      1991892.66     13667412.98
      1991903.08     13667332.25        1991443.     13666859.16
#Sta/Elev= 30
  3606.5  876.05  3796.2  871.86  3909.4  867.17  4149.2     862  4203.1  859.85
 4269.78 853.508  4325.5  849.96  4347.1  851.66  4424.1  851.28  4496.9   852.5
  4508.6  849.15  4519.3  848.89  4526.5  851.09  4540.9   852.9  4588.8  853.65
  4688.2  854.68  4836.4  853.42  4853.5  853.32  4945.7  852.35  4977.1  848.32
  4977.8  847.52  4987.6  847.52  4988.3  848.32  5018.1  852.84 5028.65853.5086
  5039.6  855.35  5066.2  856.76  5131.5  856.83  5393.1  865.75  5639.1  870.22
#Mann= 7 ,-1 , 0
  3606.5      .1       0  4588.8     .16       0  4836.4      .1       0
  4853.5     .16       0  4977.1     .07       0  4988.3     .16       0
  5066.2      .1       0
Bank Sta=4269.78,5028.65
XS Rating Curve= 0 ,0
Exp/Cntr=0.3,0.1

Type RM Length L Ch R = 1 ,137818  ,499,499,499
BEGIN DESCRIPTION:
Mapping XS e5dc93c5
END DESCRIPTION:
XS GIS Cut Line= 4
      1992848.39     13667759.33      1992334.49     13667466.89
       1992166.1     13667144.75      1991640.04     13666793.18
#Sta/Elev= 30
  4258.5  869.82  4477.6  865.25    4527  864.31  4644.6  858.37  4666.2   856.1
  4676.3  857.56  4688.1  857.18  4697.9  856.36 4712.15851.7035  4714.1  851.32
  4725.3   848.6  4741.1  847.75  4746.9  845.31  4784.4   847.6  4825.4  847.95
  4850.6  848.25  4963.6  848.16    4976  847.39  4985.3  844.99    4991  845.63
    4993  844.18  4993.7  843.38  5004.2  844.18  5051.6  850.46  5189.6  851.55
 5425.61851.7028  5494.5  852.35  5551.6  854.59  5659.7  862.71    5846  866.75
#Mann= 9 ,-1 , 0
  4258.5      .1       0  4477.6     .16       0  4714.1      .1       0
  4825.4     .16       0  4850.6      .1       0  4963.6     .16       0
    4993     .07       0  5004.2     .16       0  5189.6      .1       0
Bank Sta=4712.15,5425.61
XS Rating Curve= 0 ,0
Exp/Cntr=0.3,0.1

Type RM Length L Ch R = 1 ,137319  ,534,534,534
BEGIN DESCRIPTION:
CHACON CREEK 178.0
END DESCRIPTION:
XS GIS Cut Line= 3
      1993171.33     13667493.73      1992658.29     13667162.98
      1991770.27     13666774.96
#Sta/Elev= 30
  4410.6  867.86  4523.7  864.61  4572.8   864.4  4653.8  862.68  4768.6  858.17
  4826.1  856.43  4864.7   856.1    4935  854.69  4971.3   851.5 4973.47849.9626
  4977.3  847.25  4986.4  842.44  4995.4   841.2  4996.1   840.4  5006.2   840.4
  5006.8   841.2  5007.6  841.96    5020  843.88  5046.4  846.21  5090.1  845.64
  5117.1  846.29    5204  847.38  5319.3  849.99 5382.09849.9604  5559.3  850.14
  5780.4   851.5  5821.2  854.02  5886.7  860.83  5926.2  862.57  5990.1  864.02
#Mann= 5 ,-1 , 0
  4410.6      .1       0  4864.7     .16       0  4995.4     .07       0
  5006.8     .16       0  5117.1      .1       0
Bank Sta=4973.47,5382.09
XS Rating Curve= 0 ,0
Exp/Cntr=0.3,0.1

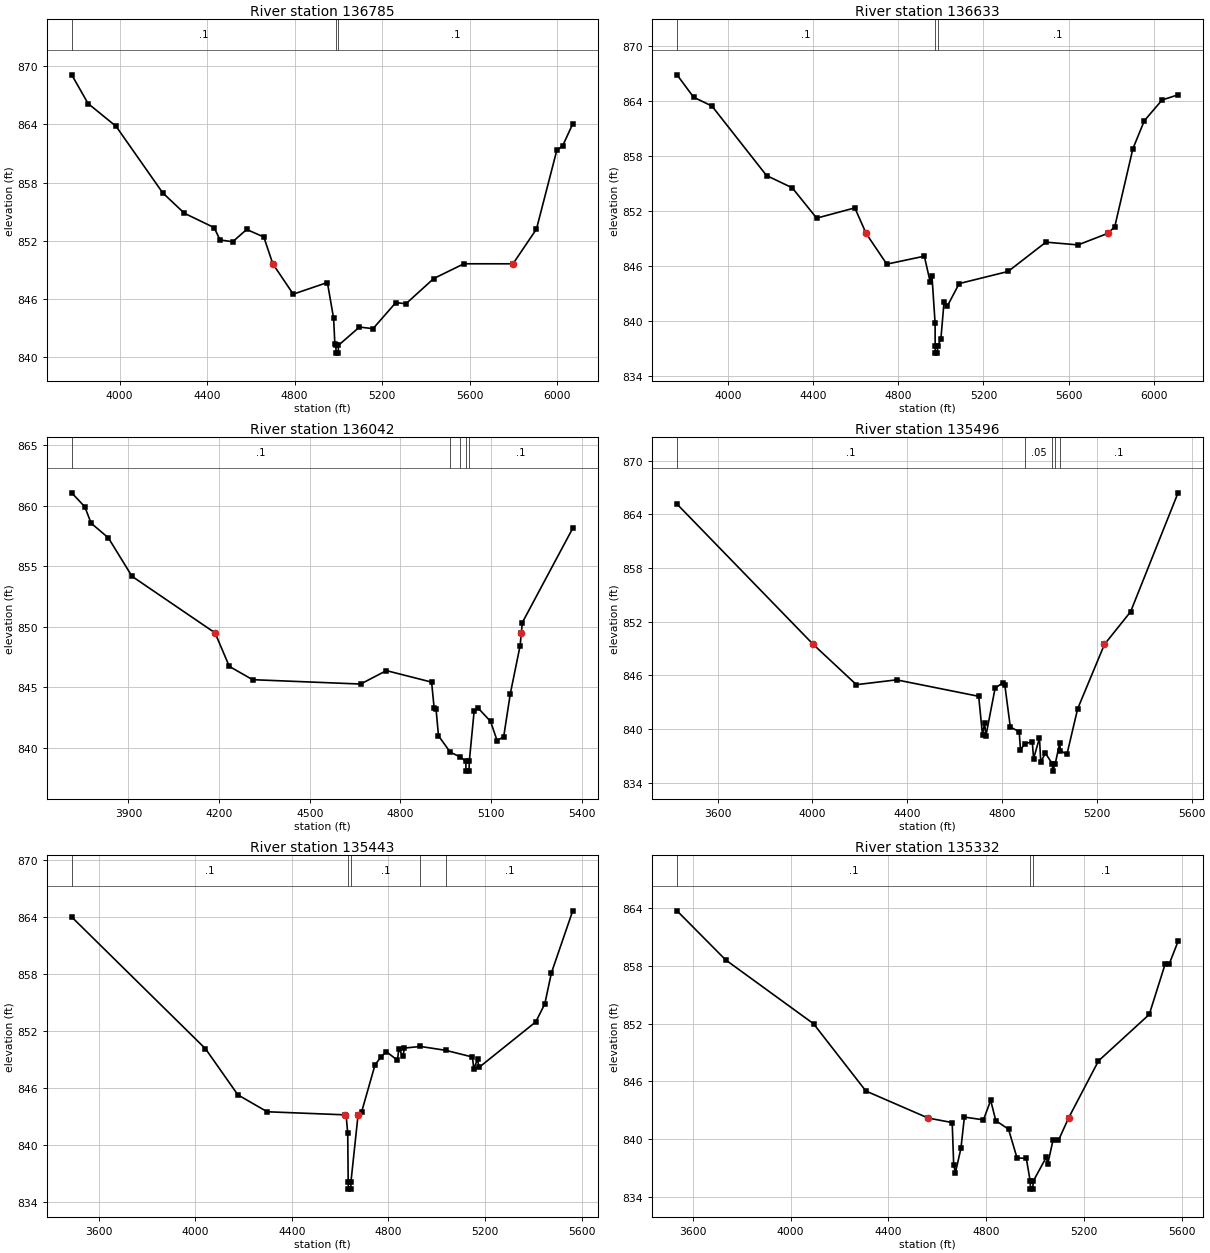
Type RM Length L Ch R = 1 ,136785  ,152,152,152
BEGIN DESCRIPTION:
CHACON CREEK 177.0
END DESCRIPTION:
XS GIS Cut Line= 4
      1993593.53     13667130.66      1992798.37     13666491.76
      1992600.45     13666894.54      1991824.97     13666624.99
#Sta/Elev= 30
  3781.4   869.1  3856.2  866.14  3984.2  863.79    4197  856.94  4296.2  854.83
  4432.2  853.35  4459.4  852.08    4517  851.89    4581  853.16  4659.4  852.38
 4700.44849.6185  4793.8  846.49  4949.9  847.69  4978.4  843.99    4984  841.32
  4988.8  841.21  4989.4  840.41  4999.6  840.41  5000.2  841.21  5096.4   843.1
  5158.3  842.93  5262.7  845.62  5308.9   845.5    5436   848.1  5573.7  849.62
 5798.15849.6182  5905.4   853.2  5998.7  861.35  6024.5  861.75  6071.2  864.04
#Mann= 3 ,-1 , 0
  3781.4      .1       0  4988.8     .07       0  5000.2      .1       0
Bank Sta=4700.44,5798.15
XS Rating Curve= 0 ,0
Exp/Cntr=0.3,0.1

Type RM Length L Ch R = 1 ,136633  ,591,591,591
BEGIN DESCRIPTION:
Mapping XS b31f6884
END DESCRIPTION:
XS GIS Cut Line= 5
      1993607.39     13667061.19      1992735.87      13666411.9
      1992531.01     13666703.56      1992531.01     13666804.26
      1991778.73     13666502.65
#Sta/Elev= 30
  3760.1  866.87  3837.9  864.43  3924.2  863.46  4180.7  855.88  4301.6  854.54
  4416.3  851.23  4595.7  852.35  4648.6849.5629  4745.8  846.21  4922.3  847.08
  4949.3  844.31    4958  844.96  4972.8  839.78  4973.2   837.3  4973.8   836.5
    4984   836.5  4984.7   837.3  4999.9  838.01  5014.7  842.04  5029.5   841.6
  5086.1  844.09  5315.7  845.41  5493.6  848.61  5644.5  848.31 5783.79 849.563
  5816.9  850.28  5902.2   858.8    5956  861.86  6039.4  864.12  6114.5  864.69
#Mann= 3 ,-1 , 0
  3760.1      .1       0  4973.2     .07       0  4984.7      .1       0
Bank Sta=4648.6,5783.79
XS Rating Curve= 0 ,0
Exp/Cntr=0.3,0.1

Type RM Length L Ch R = 1 ,136042  ,546,546,546
BEGIN DESCRIPTION:
CHACON CREEK 176.0
END DESCRIPTION:
XS GIS Cut Line= 3
      1993541.41     13666748.69        1992525.       13665975.
      1992174.97     13665824.99
#Sta/Elev= 30
  3712.4  861.06  3755.8   859.9  3776.6  858.55  3833.6  857.34  3911.8  854.16
 4186.71 849.482    4234  846.71  4311.1  845.61  4668.6  845.25  4753.8  846.36
  4903.5  845.41  4911.8  843.29  4918.1  843.21  4926.3  840.97  4965.3  839.61
  4998.7  839.22  5016.7  838.85  5017.3  838.05  5027.5  838.05  5028.2  838.85
  5044.2     843  5056.9  843.28  5098.6  842.16  5120.3  840.57  5142.1   840.9
  5163.9  844.44  5196.5  848.43 5200.49 849.483  5203.7  850.33  5370.6  858.13
#Mann= 5 ,-1 , 0
  3712.4      .1       0  4965.3     .05       0  4998.7      .1       0
  5016.7     .07       0  5028.2      .1       0
Bank Sta=4186.71,5200.49
XS Rating Curve= 0 ,0
Exp/Cntr=0.3,0.1

Type RM Length L Ch R = 1 ,135496  ,53,53,53
BEGIN DESCRIPTION:
CHACON CREEK 175.0
END DESCRIPTION:
XS GIS Cut Line= 4
      1993725.01     13666825.01      1992954.62     13666016.06
      1992753.23     13665477.87       1992500.8     13665138.99
#Sta/Elev= 30
  3428.4  865.16 4003.11849.4655  4185.3  844.96  4354.9   845.5  4701.4  843.66
  4717.5  839.33  4726.3  840.71  4731.7  839.22  4770.8  844.58  4802.9  845.16
  4811.8   844.9  4834.9  840.22  4872.4   839.7  4877.7  837.67  4895.9  838.34
  4927.6  838.59    4933  836.68  4957.9  838.99  4963.3  836.31  4982.9   837.3
  5012.7  836.09  5013.3  835.29  5024.3  836.09  5043.4  838.46  5046.1  837.59
  5073.7  837.16    5119  842.26 5232.12849.4653  5342.5  853.12  5542.7  866.42
#Mann= 5 ,-1 , 0
  3428.4      .1       0  4895.9     .05       0  5012.7    .033       0
  5024.3     .05       0  5046.1      .1       0
Bank Sta=4003.11,5232.12
XS Rating Curve= 0 ,0
Exp/Cntr=0.3,0.1

Type RM Length L Ch R = 1 ,135443  ,111,111,111
BEGIN DESCRIPTION:
CHACON CREEK 174.0
END DESCRIPTION:
XS GIS Cut Line= 4
      1993742.84     13666776.51      1992951.15     13665807.73
      1992791.42     13665450.09      1992574.98     13665074.97
#Sta/Elev= 30
  3487.8  864.02    4042  850.16  4176.2  845.31  4297.6  843.53    4619843.2071
  4624.9  843.11  4631.4  841.28  4633.3  836.19    4634  835.39  4644.3  835.39
  4644.9  836.19 4674.32 843.206  4688.8   843.5  4744.6  848.47  4767.8  849.25
    4791  849.86  4837.4  848.95  4842.9  850.12  4860.6  849.38  4866.1  850.23
  4932.5   850.4  5038.1  849.99  5147.9  849.29  5153.6  848.08  5169.4  849.04
  5175.2  848.19  5410.7  852.99    5448  854.88  5475.3  858.14  5563.7  864.67
#Mann= 5 ,-1 , 0
  3487.8      .1       0  4633.3    .033       0  4644.9      .1       0
  4932.5     .05       0  5038.1      .1       0
Bank Sta=4619,4674.32
XS Rating Curve= 0 ,0
Exp/Cntr=0.3,0.1

Type RM Length L Ch R = 1 ,135332  ,530,530,530
BEGIN DESCRIPTION:
CHACON CREEK 173.0
END DESCRIPTION:
XS GIS Cut Line= 3
      1993774.08     13666724.42      1993013.65     13665651.48
      1992665.27     13665004.16
#Sta/Elev= 30
    3535  863.73  3734.4  858.62  4093.7  851.99  4307.8     845 4562.84842.1857
    4661  841.72  4667.1  837.34  4674.2  836.52  4696.7  839.03  4710.9  842.29
  4788.9     842  4818.5  844.03  4839.4  841.92  4891.5  841.03  4926.2  838.05
  4964.3  837.99  4980.4   835.6  4981.1   834.8  4991.4   834.8    4992   835.6
  5046.3  838.12  5051.9   837.4  5073.8  839.92  5095.9  839.87 5137.04842.1858
  5259.6  848.13  5467.4  852.96  5533.1  858.25  5549.3  858.22  5585.2  860.55
#Mann= 3 ,-1 , 0
    3535      .1       0  4980.4     .07       0    4992      .1       0
Bank Sta=4562.84,5137.04
XS Rating Curve= 0 ,0
Exp/Cntr=0.3,0.1

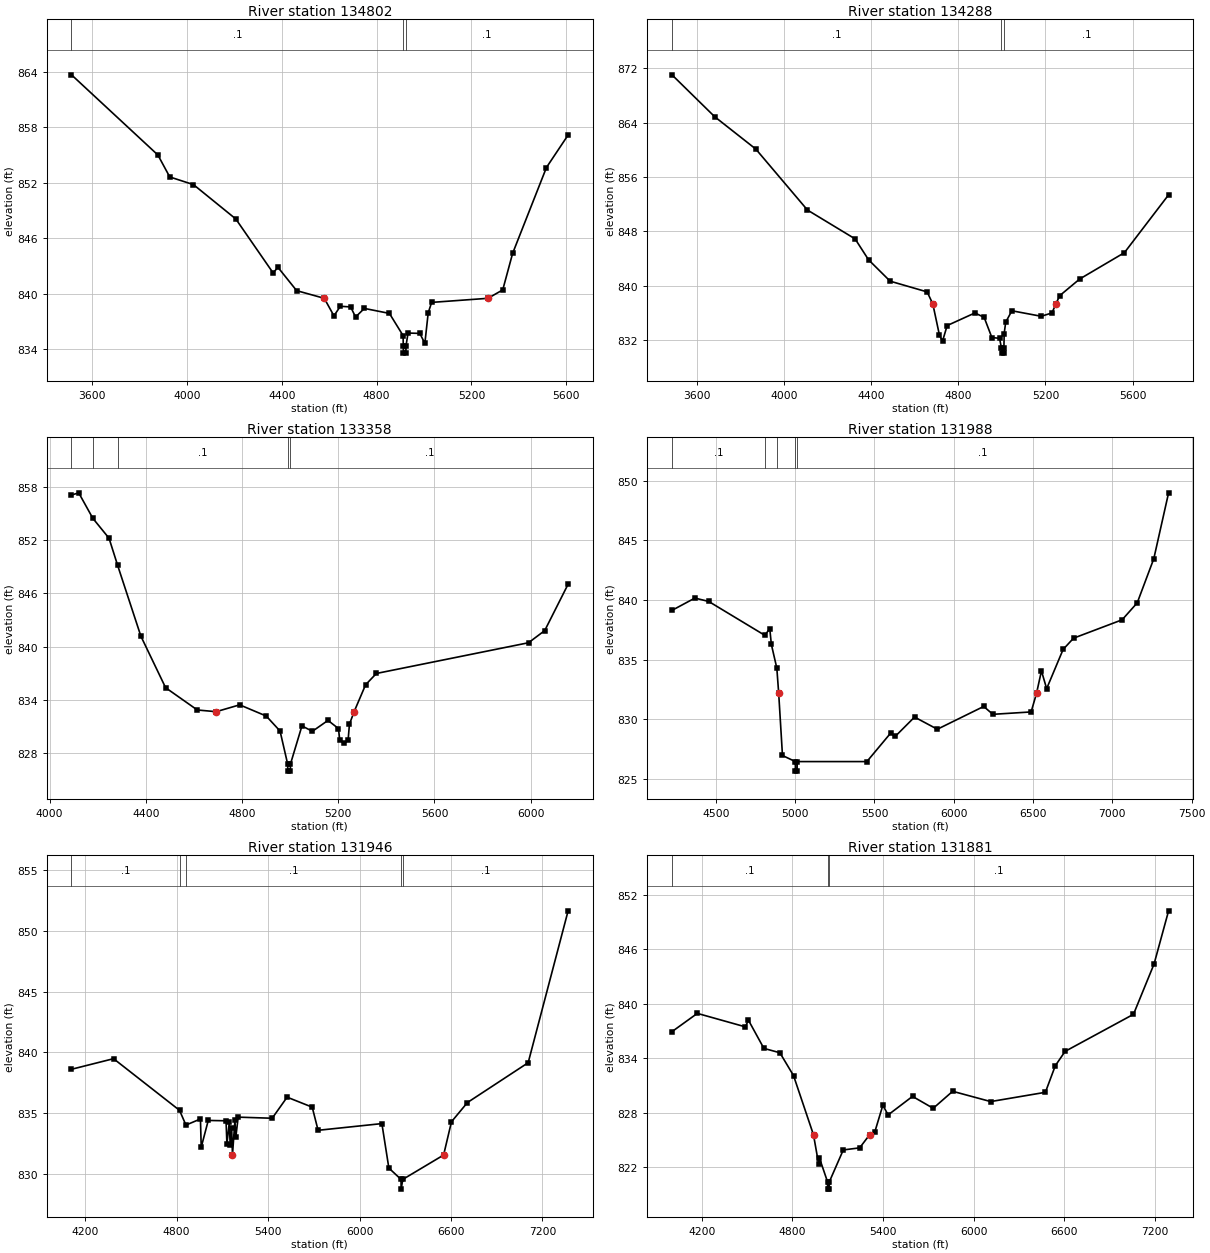
Type RM Length L Ch R = 1 ,134802  ,514,514,514
BEGIN DESCRIPTION:
CHACON CREEK 172.0
END DESCRIPTION:
XS GIS Cut Line= 3
      1994206.34      13666324.2      1993859.13     13665859.81
      1992921.61     13664670.55
#Sta/Elev= 30
  3513.3  863.66  3877.6     855  3927.6  852.63  4027.7   851.8  4206.2  848.09
  4363.3  842.27  4384.1  842.86  4462.7  840.35 4579.19839.5208  4619.9  837.63
  4647.1  838.66  4690.4  838.59  4711.2   837.5  4748.2  838.43  4853.9  837.89
  4911.7  835.49  4912.3   834.4  4912.9   833.6  4923.3   833.6  4923.9   834.4
  4932.5  835.77  4982.2  835.73  5003.4  834.65  5017.4  837.94  5031.9  839.08
 5269.41839.5208  5331.8  840.43  5373.4  844.37  5516.1  853.65  5607.5  857.16
#Mann= 3 ,-1 , 0
  3513.3      .1       0  4912.3     .07       0  4923.9      .1       0
Bank Sta=4579.19,5269.41
XS Rating Curve= 0 ,0
Exp/Cntr=0.3,0.1

Type RM Length L Ch R = 1 ,134288  ,930,930,930
BEGIN DESCRIPTION:
CHACON CREEK 171.0
END DESCRIPTION:
XS GIS Cut Line= 3
      1994636.03     13666037.74      1994167.29     13665343.32
      1993148.65     13664324.67
#Sta/Elev= 30
  3486.7  871.04    3683  864.86  3871.4   860.1  4108.3  851.12  4326.9  846.87
  4388.6  843.79  4487.6  840.64  4657.3  839.06 4683.31837.3006  4713.9  832.68
    4728  831.81  4749.2   834.1  4876.5  835.96  4918.9  835.31  4954.3  832.34
  4989.6  832.22    4998  830.84  4998.6  830.04    5009  830.04  5009.6  830.84
  5010.8  832.93  5017.9  834.61  5046.2  836.28  5180.6  835.47    5230  835.96
 5248.29837.3005  5265.4   838.5  5357.3  840.96  5562.4  844.84  5765.1  853.36
#Mann= 3 ,-1 , 0
  3486.7      .1       0    4998     .07       0  5009.6      .1       0
Bank Sta=4683.31,5248.29
XS Rating Curve= 0 ,0
Exp/Cntr=0.3,0.1

Type RM Length L Ch R = 1 ,133358  ,1370,1370,1370
BEGIN DESCRIPTION:
CHACON CREEK 170.0
END DESCRIPTION:
XS GIS Cut Line= 3
      1994921.61     13665331.13      1994374.76     13664357.21
      1993525.75     13663935.31
#Sta/Elev= 30
  4090.7  857.05  4120.7   857.3  4179.5  854.43  4246.8  852.19  4282.5  849.14
  4379.3  841.16    4482  835.37  4613.8  832.86 4692.26832.6698    4790  833.44
  4900.5  832.18  4957.9  830.49  4989.5  826.78  4990.1  825.98  5000.7  825.98
  5001.2  826.78  5048.9  831.07  5092.3  830.46  5157.3  831.69  5200.7  830.77
    5206  829.52    5224   829.1  5240.8  829.45  5246.4  831.26 5265.85832.6695
  5313.6   835.7  5358.4  836.97  5991.2  840.43  6058.5   841.8  6155.7  847.02
#Mann= 5 ,-1 , 0
  4090.7      .1       0  4179.5     .05       0  4282.5      .1       0
  4989.5     .07       0  5001.2      .1       0
Bank Sta=4692.26,5265.85
XS Rating Curve= 0 ,0
Exp/Cntr=0.3,0.1

Type RM Length L Ch R = 1 ,131988  ,42,42,42
BEGIN DESCRIPTION:
CHACON CREEK 168.0
END DESCRIPTION:
XS GIS Cut Line= 6
      1995837.42     13664399.71      1995656.88     13663896.27
      1995285.78     13663957.04      1994953.75       13664352.
      1994556.18     13663923.18      1993545.74     13663615.88
#Sta/Elev= 30
    4223  839.14  4367.4  840.17  4454.4  839.89  4808.5  837.05  4839.7  837.61
  4849.7  836.29  4884.2   834.3    4896832.1874  4919.8  826.98  5000.9  826.47
  5001.4  825.67    5012  825.67  5012.6  826.47    5452  826.47  5602.8  828.87
  5630.8  828.58  5752.7   830.2  5896.3  829.18  6188.8  831.09  6246.3  830.43
  6487.7  830.63 6521.71832.1874  6552.8  834.07  6585.6  832.58  6689.5  835.87
  6755.2  836.81  7061.4  838.35  7156.7  839.77  7261.2  843.47  7354.5  848.99
#Mann= 5 ,-1 , 0
    4223      .1       0  4808.5     .08       0  4884.2      .1       0
  5000.9     .07       0  5012.6      .1       0
Bank Sta=4896,6521.71
XS Rating Curve= 0 ,0
Exp/Cntr=0.3,0.1

Type RM Length L Ch R = 1 ,131946  ,65,65,65
BEGIN DESCRIPTION:
CHACON CREEK 169.0
END DESCRIPTION:
XS GIS Cut Line= 6
      1995876.49     13664409.28      1995741.08     13663867.63
      1995348.72     13663878.04      1994970.24     13664287.76
      1994645.59     13663878.04      1993524.98     13663524.99
#Sta/Elev= 30
  4109.9  838.62  4385.8  839.49  4818.7  835.25  4860.7  834.04  4955.9  834.54
    4961  832.22  5007.2  834.42  5123.8  834.39  5129.6  832.49  5145.2  834.26
    5151  832.41  5160.7  833.78 5166.06831.5806  5182.1  834.43  5187.9  833.04
  5203.5  834.69  5426.6   834.6  5524.6  836.33  5689.2  835.51  5727.8  833.61
  6146.3  834.16  6192.1  830.51  6271.9  829.58  6272.5  828.78  6283.6  829.58
 6551.25831.5792  6602.8  834.31  6707.7  835.89  7106.1  839.16  7368.2  851.63
#Mann= 5 ,-1 , 0
  4109.9      .1       0  4818.7     .08       0  4860.7      .1       0
  6271.9     .07       0  6283.6      .1       0
Bank Sta=5166.06,6551.25
XS Rating Curve= 0 ,0
Exp/Cntr=0.3,0.1

Type RM Length L Ch R = 1 ,131881  ,82,82,82
BEGIN DESCRIPTION:
CHACON CREEK 167.0
END DESCRIPTION:
XS GIS Cut Line= 6
      1995956.34     13664401.87      1995787.08     13663813.37
      1995354.79     13663808.16        1994985.     13664211.81
      1994693.33     13663825.09      1993569.19      13663481.6
#Sta/Elev= 30
  4002.2  836.92  4170.2  838.93    4488  837.45  4508.8  838.18  4611.1  835.08
    4717   834.6  4807.4  832.09 4939.82825.5656  4973.5   822.4  4978.5  823.05
  5032.8   820.4  5033.3   819.6  5043.9   819.6  5044.5   820.4    5137  823.91
  5245.5  824.14 5310.93825.5651  5345.7  825.88  5399.2  828.83    5434  827.76
  5595.6   829.8  5732.7  828.49  5861.6  830.36  6113.6  829.23  6475.9  830.25
  6541.5  833.17  6606.3  834.75  7059.5  838.83  7195.9  844.37    7292  850.21
#Mann= 3 ,-1 , 0
  4002.2      .1       0  5032.8     .07       0  5044.5      .1       0
Bank Sta=4939.82,5310.93
XS Rating Curve= 0 ,0
Exp/Cntr=0.3,0.1

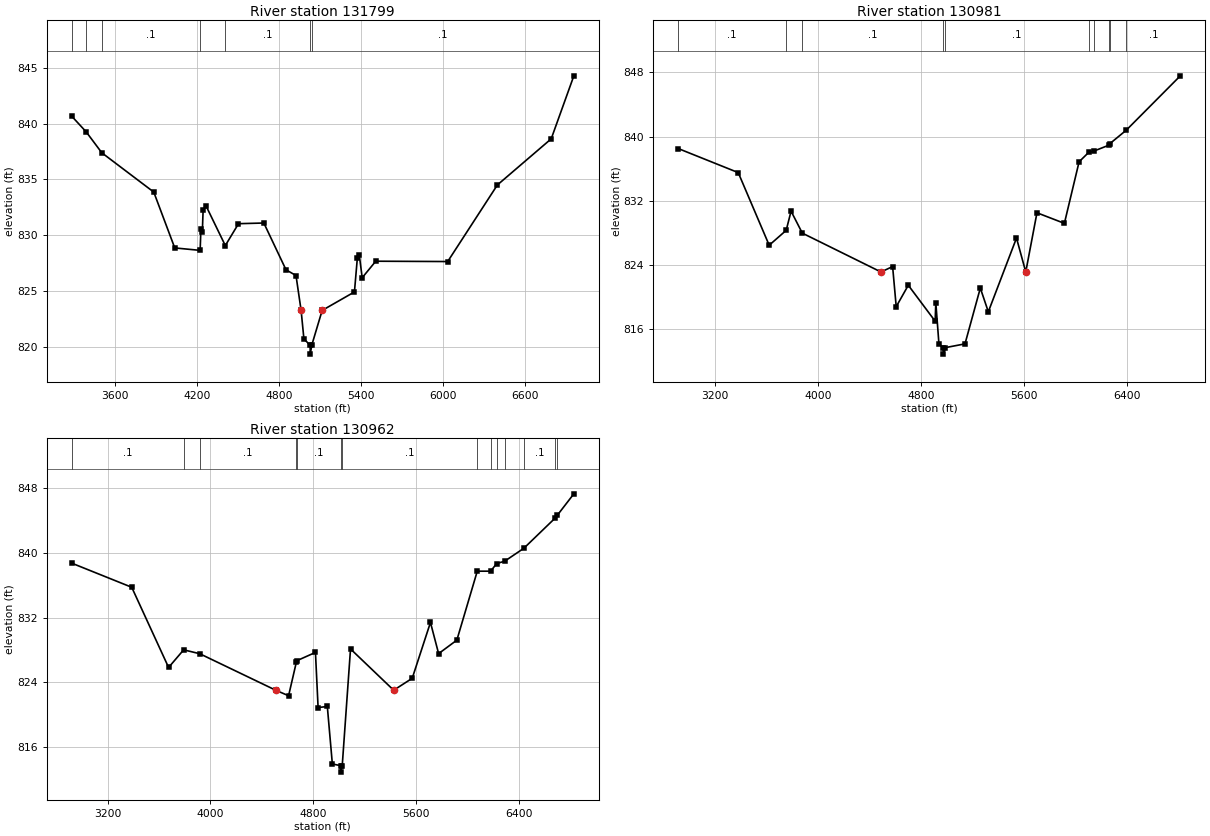
Type RM Length L Ch R = 1 ,131799  ,818,818,818
BEGIN DESCRIPTION:
CHACON CREEK 166.0
END DESCRIPTION:
XS GIS Cut Line= 6
      1996526.67     13664734.22      1996011.04     13663781.08
      1995276.67     13663739.41      1995057.92     13663968.58
       1994922.5     13663775.87      1993709.49     13663338.56
#Sta/Elev= 30
  3284.9  840.66  3390.4  839.26  3504.3  837.39  3884.1  833.87  4037.3  828.87
  4222.9  828.65  4228.5  830.53    4239  830.33  4244.7  832.27  4266.6  832.62
  4406.8  829.08  4503.2  831.04  4688.4   831.1  4850.4  826.91  4923.4   826.4
  4960.7823.2745  4981.2  820.72  5026.7  820.16  5027.3  819.36  5038.5  820.16
 5114.51 823.275  5350.4  824.93  5371.5  827.95  5385.7  828.24    5407   826.2
  5506.1  827.68  6031.8  827.65    6395  834.51  6788.3  838.64  6953.6  844.28
#Mann= 7 ,-1 , 0
  3284.9      .1       0  3390.4     .08       0  3504.3      .1       0
  4222.9     .05       0  4406.8      .1       0  5026.7     .07       0
  5038.5      .1       0
Bank Sta=4960.7,5114.51
XS Rating Curve= 0 ,0
Exp/Cntr=0.3,0.1

Type RM Length L Ch R = 1 ,130981  ,19,19,19
BEGIN DESCRIPTION:
Mapping XS 0049a962
END DESCRIPTION:
XS GIS Cut Line= 6
      1996508.45     13664512.01      1996136.04     13663840.11
       1995357.4     13663342.71       1995419.9     13662972.92
      1995274.06     13663233.34      1994162.69     13662249.48
#Sta/Elev= 30
  2917.1  838.51  3382.4  835.51  3622.5  826.45  3754.4  828.31  3792.2   830.7
  3879.4  827.96 4489.47823.1165  4579.8  823.79  4607.7  818.79  4701.4  821.46
  4909.7  816.98  4914.8   819.3  4938.9  814.17  4973.3  813.67  4973.8  812.87
  4985.4  813.67  5141.2  814.15    5260  821.11    5322  818.15  5540.6  827.35
 5612.33823.1169  5699.3   830.5    5912  829.18  6026.1  836.86    6101  838.04
  6138.4  838.18  6257.2  838.93  6263.2   839.1  6391.9   840.8  6811.1  847.58
#Mann= 10 ,-1 , 0
  2917.1      .1       0  3754.4     .05       0  3879.4      .1       0
  4973.3     .07       0  4985.4      .1       0    6101     .08       0
  6138.4      .1       0  6257.2     .08       0  6263.2     .05       0
  6391.9      .1       0
Bank Sta=4489.47,5612.33
XS Rating Curve= 0 ,0
Exp/Cntr=0.3,0.1

Type RM Length L Ch R = 1 ,130962  ,24,24,24
BEGIN DESCRIPTION:
Mapping XS 30367260
END DESCRIPTION:
XS GIS Cut Line= 6
      1996531.88     13664499.84       1996172.5     13663833.16
      1995401.67     13663338.37      1995391.25      13662916.5
      1995266.25     13663187.33      1994194.31     13662209.06
#Sta/Elev= 30
  2920.9  838.73  3387.5  835.75  3674.4  825.83  3791.7  828.01  3916.6  827.53
 4508.59823.0107  4608.2  822.33  4668.3  826.46  4674.7  826.68  4817.3  827.69
  4837.9  820.87  4909.7     821  4948.8  813.89  5013.5  813.68    5014  812.88
  5025.7  813.68  5090.2  828.12 5426.26823.0106  5570.4  824.49  5712.3   831.4
  5775.8  827.54  5917.7  829.21  6076.6  837.74  6180.5  837.74    6228  838.69
  6289.5  838.97  6439.6  840.58    6682   844.3  6698.6  844.64  6828.2  847.31
#Mann= 14 ,-1 , 0
  2920.9      .1       0  3791.7     .05       0  3916.6      .1       0
  4668.3     .08       0  4674.7      .1       0  5013.5     .07       0
  5025.7      .1       0  6076.6     .08       0  6180.5      .1       0
    6228     .08       0  6289.5     .05       0  6439.6      .1       0
    6682     .05       0  6698.6      .1       0
Bank Sta=4508.59,5426.26
XS Rating Curve= 0 ,0
Exp/Cntr=0.3,0.1