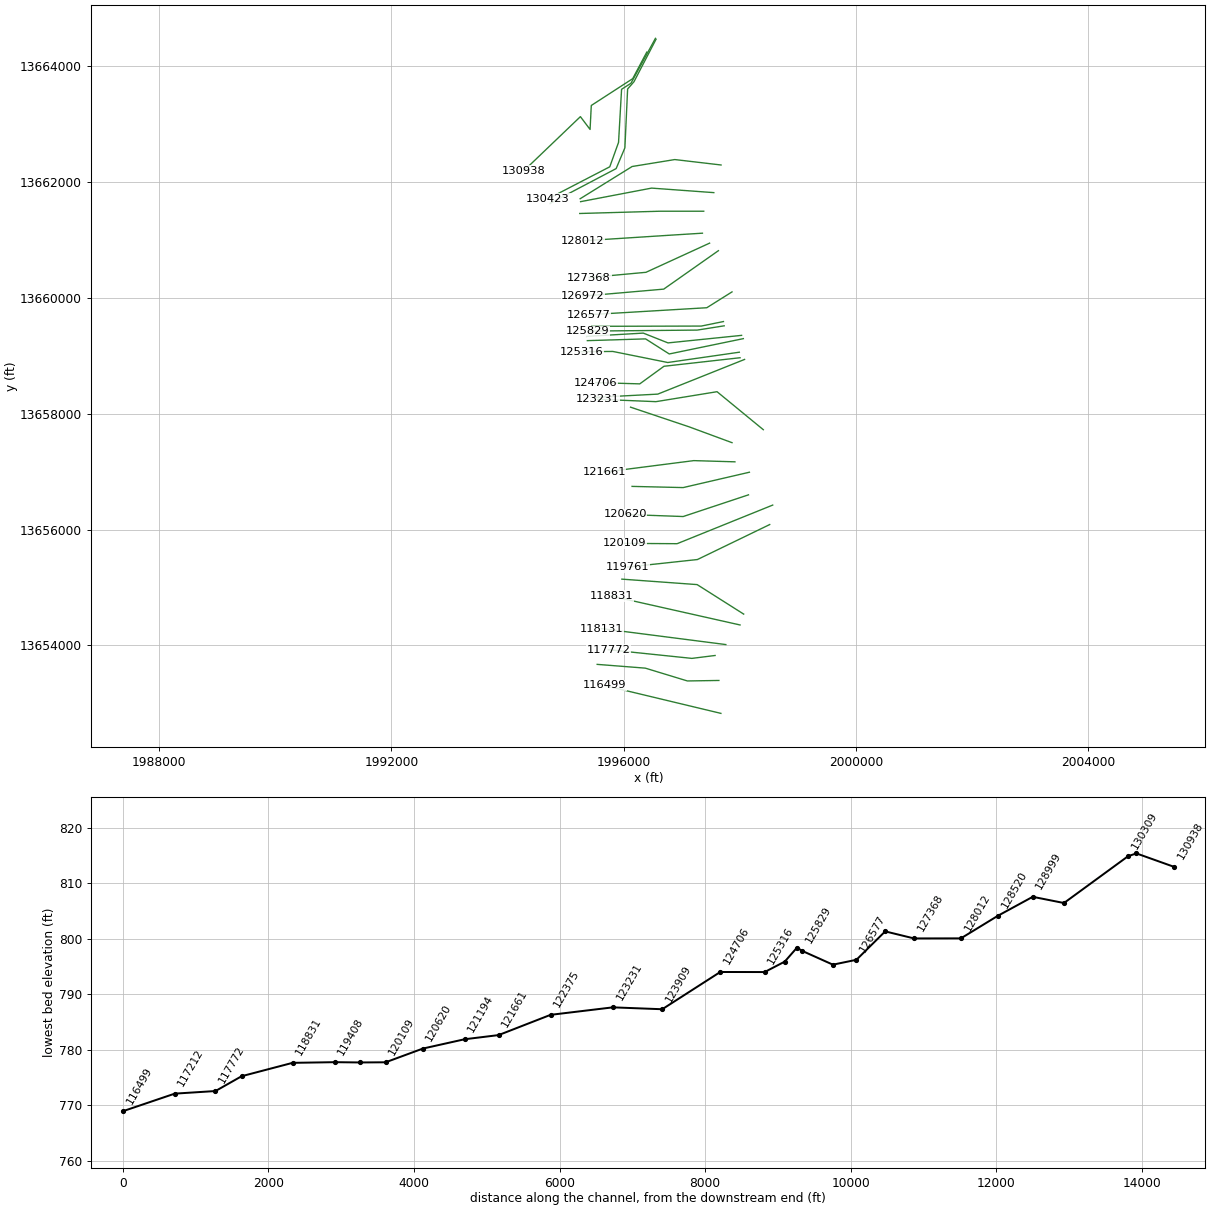
HEC-RAS study CHACON CREEK.prj: CHACON CREEK Base Level Engineering

--- CHACON CREEK.g01 (geometry) --- (continued)

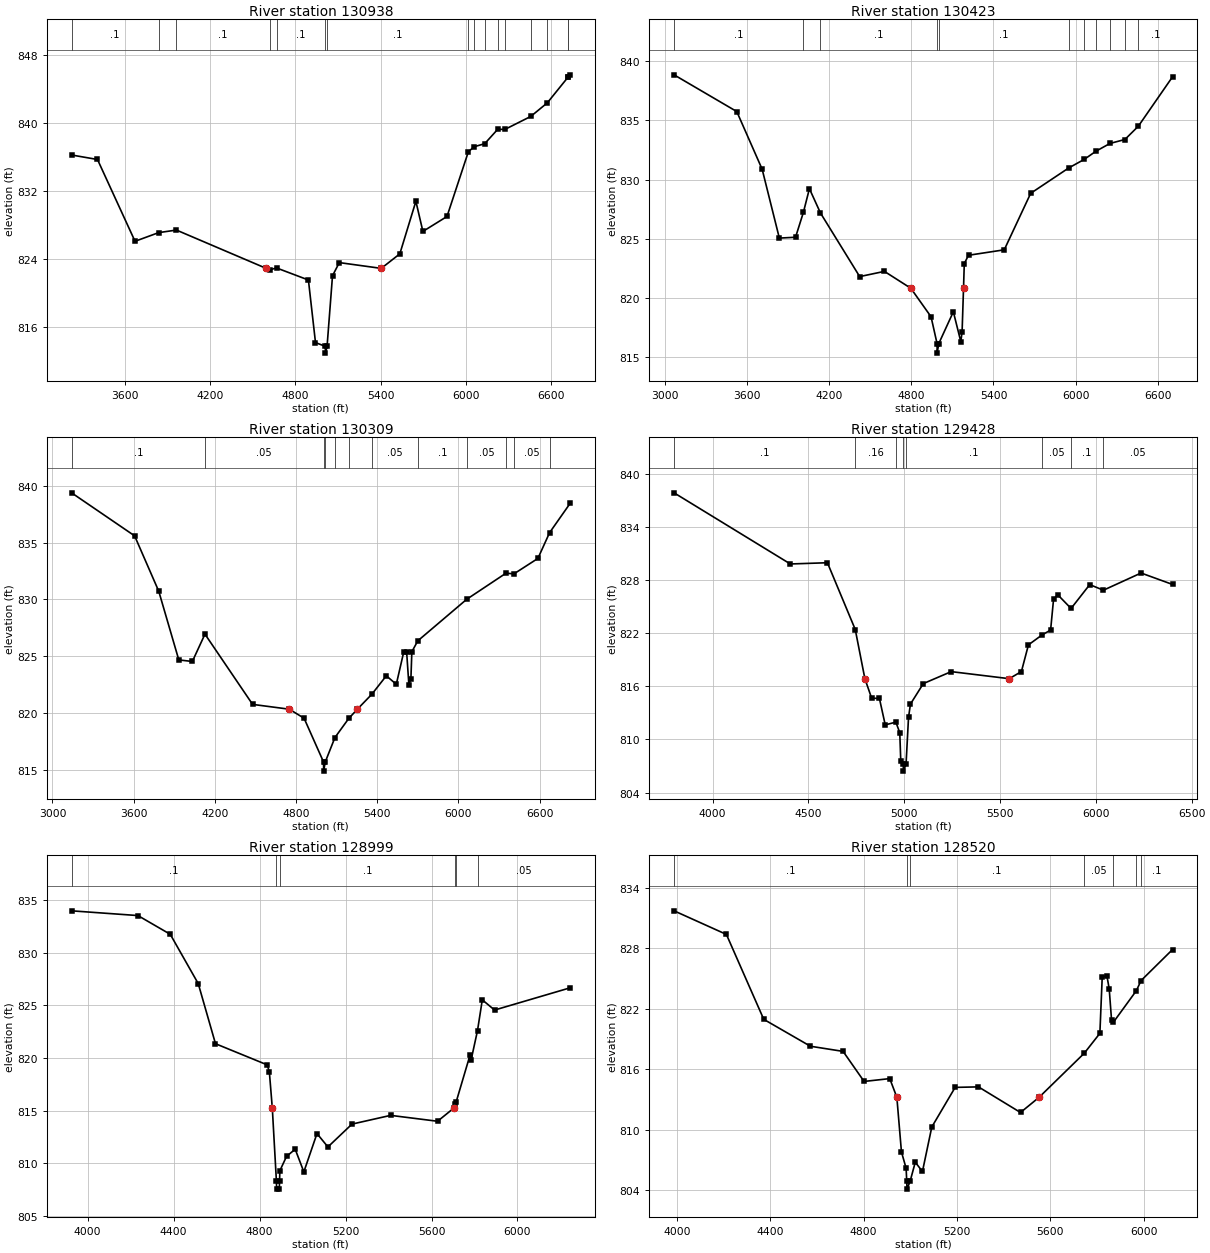
Type RM Length L Ch R = 1 ,130938  ,515,515,515
BEGIN DESCRIPTION:
Mapping XS 93aed11f
END DESCRIPTION:
XS GIS Cut Line= 6
      1996398.35     13664246.32      1996156.18     13663788.02
      1995442.64     13663324.48      1995421.81     13662910.42
      1995255.14     13663131.77      1994284.08     13662199.77
#Sta/Elev= 30
  3222.1  836.28  3404.6  835.75  3669.2  826.12  3835.8  827.14    3961  827.44
 4593.78822.9288  4620.5  822.77  4666.5  822.98  4891.1  821.56    4941  814.19
  5010.4  813.75  5010.9  812.95  5022.6  813.75  5060.9  822.06  5108.8  823.61
 5404.37822.9288  5535.3  824.64  5648.5  830.83  5697.9  827.28  5867.7  829.04
  6018.7  836.68  6060.7  837.26  6133.5  837.61  6225.4  839.31  6275.6  839.29
    6458  840.82  6574.7  842.42    6722  845.47  6722.6  845.51  6734.9  845.72
#Mann= 16 ,-1 , 0
  3222.1      .1       0  3835.8     .05       0    3961      .1       0
  4620.5     .08       0  4666.5      .1       0  5010.4     .07       0
  5022.6      .1       0  6018.7     .05       0  6060.7     .08       0
  6133.5     .05       0  6225.4     .08       0  6275.6     .05       0
    6458      .1       0  6574.7     .05       0    6722     .08       0
  6722.6     .05       0
Bank Sta=4593.78,5404.37
XS Rating Curve= 0 ,0
Exp/Cntr=0.3,0.1

Type RM Length L Ch R = 1 ,130423  ,114,114,114
BEGIN DESCRIPTION:
Mapping XS 8e4667e9
END DESCRIPTION:
XS GIS Cut Line= 6
      1996547.49      13664484.2      1996125.63     13663708.16
      1995964.17       13663604.      1995912.08     13662687.33
      1995761.04     13662265.46       1994699.3     13661713.76
#Sta/Elev= 30
  3068.9  838.85  3526.6  835.75  3711.9  830.88  3837.3  825.07  3955.5  825.14
  4012.8  827.24  4056.8  829.24  4137.3  827.19  4423.8  821.82  4604.1  822.26
 4796.72820.8387  4944.6  818.43  4988.6  816.16  4989.1  815.36  5000.8  816.16
  5107.4  818.85  5161.8  816.33  5171.2  817.15 5181.65820.8371  5187.2  822.92
    5218  823.62  5478.9  824.08  5671.9  828.85  5949.5  830.99  6062.3  831.71
  6149.3  832.41  6250.9  833.06  6359.4  833.39  6457.4  834.51  6707.1  838.68
#Mann= 11 ,-1 , 0
  3068.9      .1       0  4012.8     .05       0  4137.3      .1       0
  4988.6     .07       0  5000.8      .1       0  5949.5     .05       0
  6062.3     .08       0  6149.3     .05       0  6250.9     .08       0
  6359.4     .05       0  6457.4      .1       0
Bank Sta=4796.72,5181.65
XS Rating Curve= 0 ,0
Exp/Cntr=0.3,0.1

Type RM Length L Ch R = 1 ,130309  ,881,881,881
BEGIN DESCRIPTION:
Mapping XS fed527d0
END DESCRIPTION:
XS GIS Cut Line= 6
       1996557.9     13664468.54      1996177.71     13663734.21
      1996068.33     13663609.21      1996021.46     13662593.58
      1995870.42     13662234.21      1994734.96     13661635.23
#Sta/Elev= 30
  3141.4  839.38  3607.1  835.59  3785.5  830.71  3933.6  824.66  4033.7  824.52
  4126.9  826.93    4479  820.74  4750.1 820.316  4859.4  819.52  5003.4  815.66
  5003.9  814.86  5015.6  815.66  5087.4  817.82  5189.5   819.5 5253.11 820.316
  5360.6  821.64  5467.1  823.26  5540.9  822.51  5595.4  825.34  5617.4  825.34
  5633.8  822.47  5648.8  823.02  5655.8  825.38  5699.8  826.34  6061.2     830
  6351.4   832.3  6410.2  832.24  6587.2   833.6  6673.6  835.87  6824.7  838.44
#Mann= 12 ,-1 , 0
  3141.4      .1       0  4126.9     .05       0  5003.4     .04       0
  5015.6     .05       0  5087.4     .08       0  5189.5      .1       0
  5360.6     .05       0  5699.8      .1       0  6061.2     .05       0
  6351.4     .08       0  6410.2     .05       0  6673.6      .1       0
Bank Sta=4750.1,5253.11
XS Rating Curve= 0 ,0
Exp/Cntr=0.3,0.1

Type RM Length L Ch R = 1 ,129428  ,429,429,429
BEGIN DESCRIPTION:
CHACON CREEK 165.0
END DESCRIPTION:
XS GIS Cut Line= 4
      1997677.68     13662296.71      1996880.83     13662390.46
      1996146.46     13662270.66      1995250.58     13661713.35
#Sta/Elev= 30
  3798.6  837.83  4405.4   829.8    4599  829.94  4744.3   822.4 4794.48 816.855
  4829.8  814.65  4870.3  814.63  4900.7  811.64  4956.3  811.95  4976.6  810.75
  4981.7  807.61  4994.6  807.22  4995.8  806.42  5009.4  807.22  5022.3   812.5
  5032.4  813.99  5099.5   816.3  5245.2  817.65 5547.92 816.854  5611.5  817.66
  5648.1  820.67  5718.4  821.78  5763.8  822.34  5779.2  825.81  5800.4  826.34
  5870.6  824.78    5968  827.47  6039.4  826.84    6236  828.78  6400.1  827.49
#Mann= 8 ,-1 , 0
  3798.6      .1       0  4744.3     .16       0  4956.3      .1       0
  4994.6     .07       0  5009.4      .1       0  5718.4     .05       0
  5870.6      .1       0  6039.4     .05       0
Bank Sta=4794.48,5547.92
XS Rating Curve= 0 ,0
Exp/Cntr=0.3,0.1

Type RM Length L Ch R = 1 ,128999  ,479,479,479
BEGIN DESCRIPTION:
CHACON CREEK 164.0
END DESCRIPTION:
XS GIS Cut Line= 3
      1997552.86     13661819.28      1996480.83      13661897.4
      1995258.41     13661663.32
#Sta/Elev= 30
  3925.1  833.99  4233.8  833.54  4384.2  831.76  4514.5  827.07  4594.7  821.36
  4835.4  819.35  4845.4  818.68 4859.17815.2244  4878.1  808.34  4879.3  807.54
  4891.7  807.54  4892.9  808.34  4894.3  809.29  4925.6  810.66  4965.7  811.33
  5005.9  809.18    5067  812.82  5117.9  811.55  5229.9  813.72  5409.8  814.55
  5628.1  813.99 5702.85815.2253  5710.4   815.6  5714.3   815.8  5779.2  820.28
  5784.3  819.82    5814  822.61  5836.3  825.53  5893.4  824.56  6244.6  826.67
#Mann= 6 ,-1 , 0
  3925.1      .1       0  4878.1     .07       0  4892.9      .1       0
  5710.4     .08       0  5714.3      .1       0    5814     .05       0
Bank Sta=4859.17,5702.85
XS Rating Curve= 0 ,0
Exp/Cntr=0.3,0.1

Type RM Length L Ch R = 1 ,128520  ,508,508,508
BEGIN DESCRIPTION:
CHACON CREEK 163.0
END DESCRIPTION:
XS GIS Cut Line= 3
      1997379.28     13661498.09       1996628.4     13661498.09
      1995243.83     13661459.03
#Sta/Elev= 30
  3987.6  831.72  4211.9  829.38  4371.9  820.96  4571.9  818.29  4711.9  817.78
  4801.9   814.8  4911.9  815.08 4942.26813.2319    4962  807.81    4982  806.19
  4984.6  804.92  4985.8  804.12  4999.4  804.92  5021.2  806.79    5052  805.87
    5092  810.28  5192.1  814.21  5292.1  814.26  5472.2  811.72 5552.11813.2321
  5745.5   817.6  5812.3  819.57  5822.3  825.12  5842.3  825.29  5852.3  823.98
  5862.3   820.9  5870.2  820.67  5968.6   823.8  5988.7   824.8  6123.6  827.88
#Mann= 7 ,-1 , 0
  3987.6      .1       0  4984.6     .07       0  4999.4      .1       0
  5745.5     .05       0  5870.2      .1       0  5968.6     .05       0
  5988.7      .1       0
Bank Sta=4942.26,5552.11
XS Rating Curve= 0 ,0
Exp/Cntr=0.3,0.1

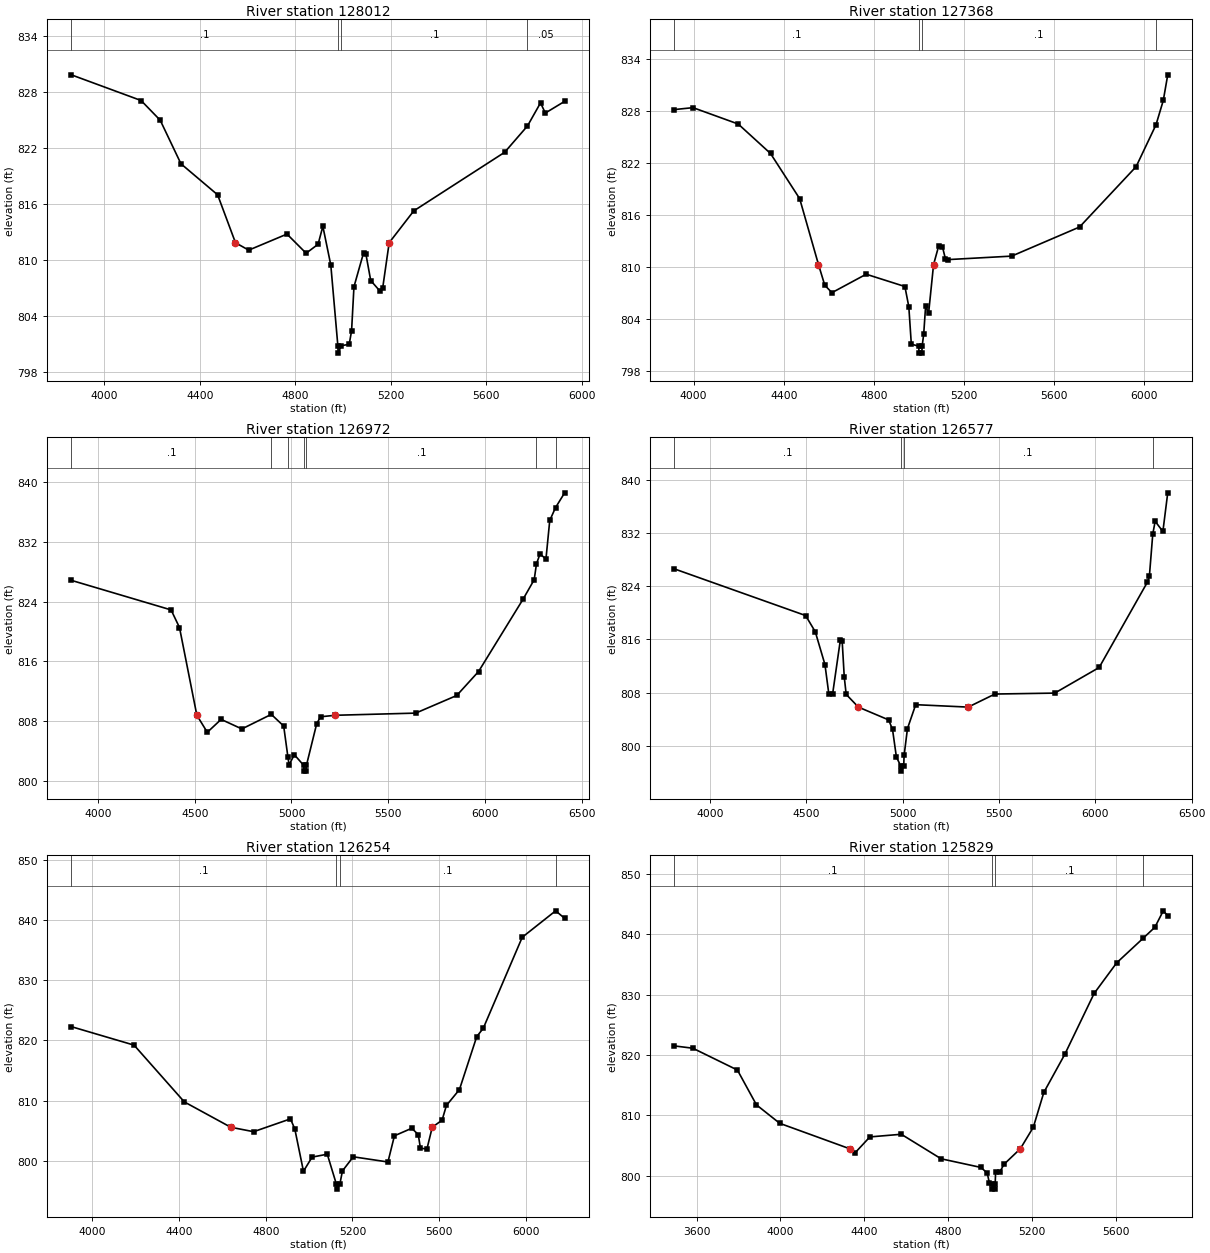
Type RM Length L Ch R = 1 ,128012  ,644,644,644
BEGIN DESCRIPTION:
CHACON CREEK 162.0
END DESCRIPTION:
XS GIS Cut Line= 3
      1997356.72     13661118.76      1996801.15     13661084.03
      1995294.24     13660986.81
#Sta/Elev= 30
  3861.2  829.83  4153.5  827.08  4233.6  824.97  4320.5  820.31  4474.1  816.99
 4548.93 811.862  4604.4  811.07  4764.7  812.79  4844.9  810.74    4895   811.7
    4915  813.62  4948.3  809.47  4977.8  800.85    4979  800.05  4992.6  800.85
  5025.3  800.99  5035.3  802.43  5045.3  807.15  5085.4  810.77  5095.4  810.64
  5115.5  807.82  5155.5  806.65  5165.6  807.01 5192.78811.8624  5295.8  815.27
  5676.6  821.54  5772.3  824.36  5826.9  826.83    5847  825.74  5927.9  826.99
#Mann= 4 ,-1 , 0
  3861.2      .1       0  4977.8     .07       0  4992.6      .1       0
  5772.3     .05       0
Bank Sta=4548.93,5192.78
XS Rating Curve= 0 ,0
Exp/Cntr=0.3,0.1

Type RM Length L Ch R = 1 ,127368  ,396,396,396
BEGIN DESCRIPTION:
CHACON CREEK 161.0
END DESCRIPTION:
XS GIS Cut Line= 3
      1997479.99     13660946.89       1996384.2     13660443.06
      1995405.27     13660352.26
#Sta/Elev= 30
    3915  828.16  3997.5  828.38    4198  826.49  4341.3  823.09  4470.8  817.87
 4554.25 810.262  4582.1  807.88  4613.9  807.02  4765.9  809.15  4937.7  807.73
  4955.1   805.4  4966.2  801.08  4999.1  800.84  5000.5  800.04  5012.9  800.04
  5014.2  800.84  5021.1  802.21  5029.6  805.44  5043.1   804.7 5064.94810.2609
  5087.2  812.37  5104.1  812.34  5117.9  810.89  5130.3  810.84  5411.5  811.24
  5712.8   814.6  5963.9  821.57  6052.2  826.41  6084.4  829.21  6104.2  832.17
#Mann= 4 ,-1 , 0
    3915      .1       0  4999.1     .07       0  5014.2      .1       0
  6052.2     .08       0
Bank Sta=4554.25,5064.94
XS Rating Curve= 0 ,0
Exp/Cntr=0.3,0.1

Type RM Length L Ch R = 1 ,126972  ,395,395,395
BEGIN DESCRIPTION:
CHACON CREEK 160.0
END DESCRIPTION:
XS GIS Cut Line= 3
      1997631.87     13660816.67      1996690.03     13660152.61
      1995298.42     13660031.22
#Sta/Elev= 30
  3862.4  826.86  4377.9   822.9  4421.4  820.54 4511.07808.7901  4565.1  806.51
  4636.5  808.24  4743.7  806.96  4895.8  808.91  4959.8  807.35  4981.6  803.22
  4987.5  802.14  5014.8  803.51  5062.5  802.11  5063.8  801.31  5076.2  801.31
  5077.6  802.11  5130.3  807.65  5150.3  808.59 5227.33808.7904  5642.2  809.08
  5854.2  811.44  5966.9  814.65  6197.5  824.36  6254.5  826.95  6266.2  829.07
  6284.6   830.4  6315.2  829.71  6334.8  834.88  6364.7   836.6  6411.7  838.58
#Mann= 7 ,-1 , 0
  3862.4      .1       0  4895.8     .05       0  4981.6      .1       0
  5062.5     .07       0  5077.6      .1       0  6266.2     .05       0
  6364.7     .08       0
Bank Sta=4511.07,5227.33
XS Rating Curve= 0 ,0
Exp/Cntr=0.3,0.1

Type RM Length L Ch R = 1 ,126577  ,323,323,323
BEGIN DESCRIPTION:
Mapping XS 8950381b
END DESCRIPTION:
XS GIS Cut Line= 3
      1997866.28     13660104.88      1997432.22     13659831.43
      1995389.84     13659710.01
#Sta/Elev= 30
  3816.9  826.59  4497.4  819.58  4547.5  817.14  4597.6  812.22  4617.6  807.83
  4637.7  807.85  4677.7  815.94  4686.9  815.79  4697.8  810.35  4707.8  807.73
 4771.04805.8161  4928.2  803.89  4948.2  802.46  4968.3  798.31  4990.5  796.99
  4992.1  796.19  5006.2  796.99  5008.3  798.55  5025.7  802.59  5068.4  806.18
 5340.65 805.816  5479.2  807.78  5789.7  807.92  6020.1  811.77  6270.6  824.61
  6280.6  825.48  6298.2  831.82  6310.6  833.75  6350.7  832.22  6375.9  838.03
#Mann= 4 ,-1 , 0
  3816.9      .1       0  4990.5     .07       0  5006.2      .1       0
  6298.2     .05       0
Bank Sta=4771.04,5340.65
XS Rating Curve= 0 ,0
Exp/Cntr=0.3,0.1

Type RM Length L Ch R = 1 ,126254  ,425,425,425
BEGIN DESCRIPTION:
Mapping XS edab6692
END DESCRIPTION:
XS GIS Cut Line= 3
       1997718.7     13659592.72      1997336.74     13659514.59
      1995449.32     13659510.25
#Sta/Elev= 30
  3902.3   822.3  4191.9  819.23  4423.9   809.8 4638.62805.5862  4743.9  804.85
  4913.9  806.98  4933.9  805.31  4973.9  798.28  5013.9  800.63  5083.9  801.11
  5126.1  796.11  5127.7  795.31  5141.8  796.11  5153.9  798.34  5203.9  800.68
  5363.9  799.82  5393.9  804.17  5473.9  805.42  5503.9  804.37  5513.9  802.11
  5543.9  801.97 5568.41805.5865  5613.9  806.77  5633.9  809.21  5693.9  811.84
  5773.9  820.65  5803.9  822.02  5983.9  837.15  6138.1  841.54  6179.6   840.3
#Mann= 4 ,-1 , 0
  3902.3      .1       0  5126.1     .07       0  5141.8      .1       0
  6138.1     .05       0
Bank Sta=4638.62,5568.41
XS Rating Curve= 0 ,0
Exp/Cntr=0.3,0.1

Type RM Length L Ch R = 1 ,125829  ,68,68,68
BEGIN DESCRIPTION:
Mapping XS c59d68f6
END DESCRIPTION:
XS GIS Cut Line= 3
      1997731.69     13659518.93      1997267.29     13659445.14
       1995383.6     13659427.78
#Sta/Elev= 30
  3494.3  821.51  3582.1  821.13  3794.7  817.52  3885.8  811.75  3996.8   808.7
 4330.34804.4961  4356.8  803.84  4426.8  806.45  4576.8  806.89  4766.9  802.83
  4956.9   801.4  4986.9  800.47  4996.9  798.87    5009  798.61  5010.6  797.81
  5023.2  797.81  5024.8  798.61  5026.9  800.64  5046.9  800.64  5066.9  801.92
 5144.97 804.496  5206.9  808.06  5256.9  813.81  5356.9  820.11  5496.9  830.19
  5604.8  835.27  5731.8  839.36  5786.9  841.15  5826.9  843.87  5848.3  843.06
#Mann= 4 ,-1 , 0
  3494.3      .1       0    5009     .07       0  5024.8      .1       0
  5731.8     .05       0
Bank Sta=4330.34,5144.97
XS Rating Curve= 0 ,0
Exp/Cntr=0.3,0.1

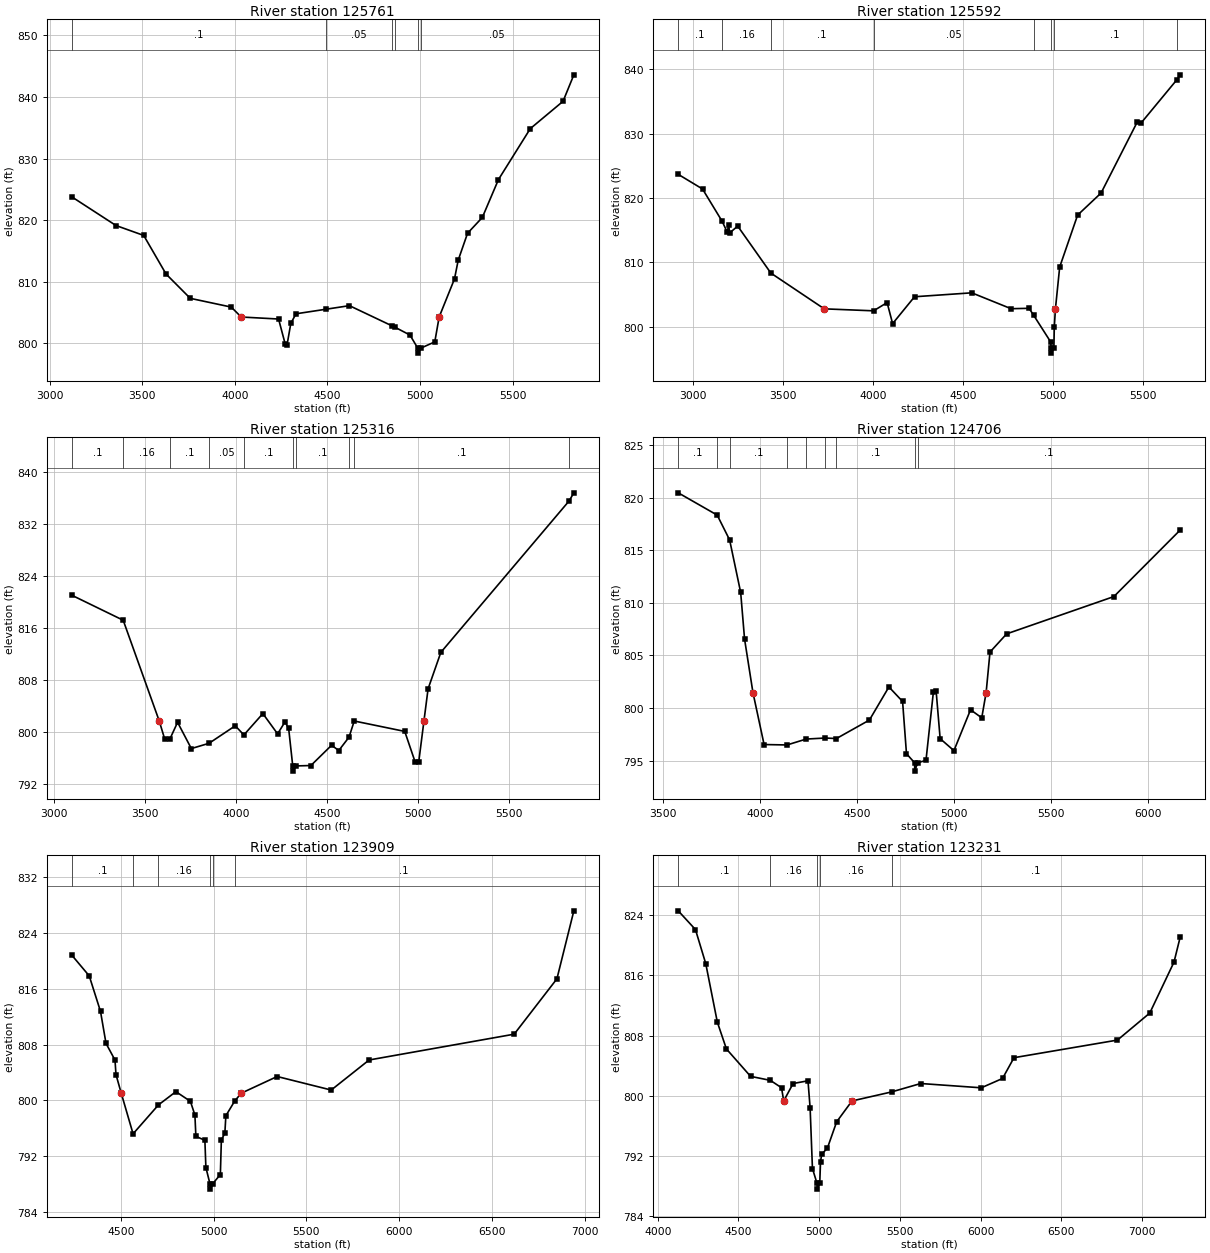
Type RM Length L Ch R = 1 ,125761  ,169,169,169
BEGIN DESCRIPTION:
Mapping XS 3140d6f9
END DESCRIPTION:
XS GIS Cut Line= 4
      1998031.23       13659354.      1996763.82     13659223.79
      1996338.47     13659393.06      1995361.87     13659336.63
#Sta/Elev= 30
  3120.2  823.78  3358.9  819.12  3508.5  817.51  3629.1  811.24  3759.8  807.29
  3980.9  805.87 4034.98804.2561  4236.5  803.93  4272.5  799.84  4282.5  799.78
  4302.6  803.23  4330.6  804.78  4492.2  805.52    4619   806.1  4848.1  802.83
  4865.2  802.59  4945.7  801.33  4987.9  799.19  4989.5  798.39  5003.7  799.19
  5079.7  800.22 5103.25804.2573  5186.1  810.45  5206.1  813.49  5256.5  817.86
  5336.3  820.43  5423.4  826.59  5595.2  834.86    5772   839.3  5830.3   843.6
#Mann= 6 ,-1 , 0
  3120.2      .1       0  4492.2     .05       0  4848.1      .1       0
  4865.2     .05       0  4987.9     .04       0  5003.7     .05       0
Bank Sta=4034.98,5103.25
XS Rating Curve= 0 ,0
Exp/Cntr=0.3,0.1

Type RM Length L Ch R = 1 ,125592  ,276,276,276
BEGIN DESCRIPTION:
Mapping XS 00cad8bb
END DESCRIPTION:
XS GIS Cut Line= 4
      1998061.56     13659297.57      1996785.52     13659032.82
      1996377.53     13659293.23      1995374.92     13659262.85
#Sta/Elev= 30
  2915.9  823.67  3050.9  821.39  3159.6  816.38  3188.1  814.69  3196.3  815.79
  3201.4  814.55  3246.4  815.62  3430.7  808.31 3727.33802.7487  4001.4  802.44
  4076.7  803.72  4107.3  800.45  4229.1  804.63  4547.2  805.24  4765.7  802.77
  4865.7  802.83  4890.9  801.76  4985.8   797.6  4987.9  796.66  4989.5  795.86
  5003.7  796.66  5005.8  799.89 5012.17802.7502  5035.8  809.25  5135.4  817.33
  5265.9  820.77  5465.6  831.74    5486  831.58  5685.1  838.32  5706.2  839.15
#Mann= 8 ,-1 , 0
  2915.9      .1       0  3159.6     .16       0  3430.7      .1       0
  4001.4     .05       0  4890.9      .1       0  4987.9     .07       0
  5003.7      .1       0  5685.1     .05       0
Bank Sta=3727.33,5012.17
XS Rating Curve= 0 ,0
Exp/Cntr=0.3,0.1

Type RM Length L Ch R = 1 ,125316  ,610,610,610
BEGIN DESCRIPTION:
Mapping XS 6d834481
END DESCRIPTION:
XS GIS Cut Line= 4
      1997992.11      13659063.2      1996759.48     13658885.25
       1995813.3     13659076.22      1995270.79     13659071.88
#Sta/Elev= 30
  3100.1  821.04  3382.1  817.19 3579.62 801.705  3609.9  798.89    3639  798.97
  3680.3  801.49  3755.7  797.45  3852.8  798.26  3996.4  800.95    4044  799.55
    4148  802.83  4228.8  799.71  4269.2  801.55  4289.4  800.55  4311.8  794.78
  4313.4  793.98  4327.6  794.78  4411.3  794.84  4524.9  797.96  4564.3  797.15
  4620.6  799.21    4649  801.69    4926  800.09  4982.6  795.42    5003  795.46
 5031.35801.7037    5054  806.64    5124  812.25  5827.2  835.54  5853.3  836.79
#Mann= 10 ,-1 , 0
  3100.1      .1       0  3382.1     .16       0    3639      .1       0
  3852.8     .05       0    4044      .1       0  4311.8     .07       0
  4327.6      .1       0  4620.6     .16       0    4649      .1       0
  5827.2     .05       0
Bank Sta=3579.62,5031.35
XS Rating Curve= 0 ,0
Exp/Cntr=0.3,0.1

Type RM Length L Ch R = 1 ,124706  ,797,797,797
BEGIN DESCRIPTION:
Mapping XS 4e6761f9
END DESCRIPTION:
XS GIS Cut Line= 4
       1998005.1     13658967.71      1996694.38     13658820.14
      1996277.71     13658516.32      1995522.49     13658538.03
#Sta/Elev= 30
  3576.9  820.47  3777.9  818.35    3842  815.99    3899  810.99  3919.1  806.55
 3962.37801.4612  4019.8  796.52  4138.1  796.48  4236.8  797.04  4335.5  797.14
    4393  797.09  4563.2  798.85  4663.8     802  4734.3  800.62  4754.4  795.65
  4795.8  794.79  4797.4  793.99  4811.6  794.79    4855  795.01  4893.1   801.5
  4907.2  801.65  4928.1  797.08  4999.2  795.94  5084.9  799.83  5142.7  799.06
 5165.27801.4607  5185.3  805.32  5271.1  807.05  5824.5   810.6  6167.1  816.94
#Mann= 9 ,-1 , 0
  3576.9      .1       0  3777.9     .16       0    3842      .1       0
  4138.1     .05       0  4236.8     .08       0  4335.5     .05       0
    4393      .1       0  4795.8     .07       0  4811.6      .1       0
Bank Sta=3962.37,5165.27
XS Rating Curve= 0 ,0
Exp/Cntr=0.3,0.1

Type RM Length L Ch R = 1 ,123909  ,678,678,678
BEGIN DESCRIPTION:
Mapping XS 50baa693
END DESCRIPTION:
XS GIS Cut Line= 3
      1998082.35     13658938.18       1996587.6     13658339.24
      1995493.88     13658281.95
#Sta/Elev= 30
  4235.7  820.84  4329.8  817.86  4390.6  812.76  4420.2  808.18  4468.6  805.79
    4474   803.7 4502.35801.0322    4566  795.21  4702.9  799.36  4796.9  801.26
  4874.9  799.87  4899.2  797.91  4904.5  794.85    4953  794.28  4958.4  790.38
    4980  788.08  4981.7  787.28  4995.9  788.08  5036.4  789.37  5041.8  794.35
  5060.6  795.29    5066   797.8  5113.4   799.9 5148.55801.0318  5342.5  803.43
  5633.8  801.49    5838   805.8  6619.6   809.5    6850  817.44  6941.2  827.19
#Mann= 6 ,-1 , 0
  4235.7      .1       0    4566     .05       0  4702.9     .16       0
    4980     .07       0  4995.9     .16       0  5113.4      .1       0
Bank Sta=4502.35,5148.55
XS Rating Curve= 0 ,0
Exp/Cntr=0.3,0.1

Type RM Length L Ch R = 1 ,123231  ,856,856,856
BEGIN DESCRIPTION:
Mapping XS 8da30f22
END DESCRIPTION:
XS GIS Cut Line= 4
      1998405.33     13657724.65      1997608.44     13658380.91
      1996556.35     13658209.03      1995545.97      13658250.7
#Sta/Elev= 30
    4127  824.59  4233.7   822.1  4297.5  817.57  4369.2   809.8  4425.4  806.24
  4575.1   802.6  4697.4  802.07  4766.7  801.09 4780.25799.3319  4838.4  801.65
  4930.6  802.01  4943.9  798.38  4958.2  790.36    4986  788.42  4988.3  787.62
  5003.5  788.42  5008.3  791.27  5015.6  792.26  5050.7  793.06  5108.1  796.56
 5203.03799.3323  5447.9  800.53  5628.9  801.65  6003.8  801.08  6135.5  802.32
  6206.5  805.08  6847.2  807.42  7047.4  811.01  7197.5  817.78  7236.6  821.17
#Mann= 5 ,-1 , 0
    4127      .1       0  4697.4     .16       0    4986     .07       0
  5003.5     .16       0  5447.9      .1       0
Bank Sta=4780.25,5203.03
XS Rating Curve= 0 ,0
Exp/Cntr=0.3,0.1

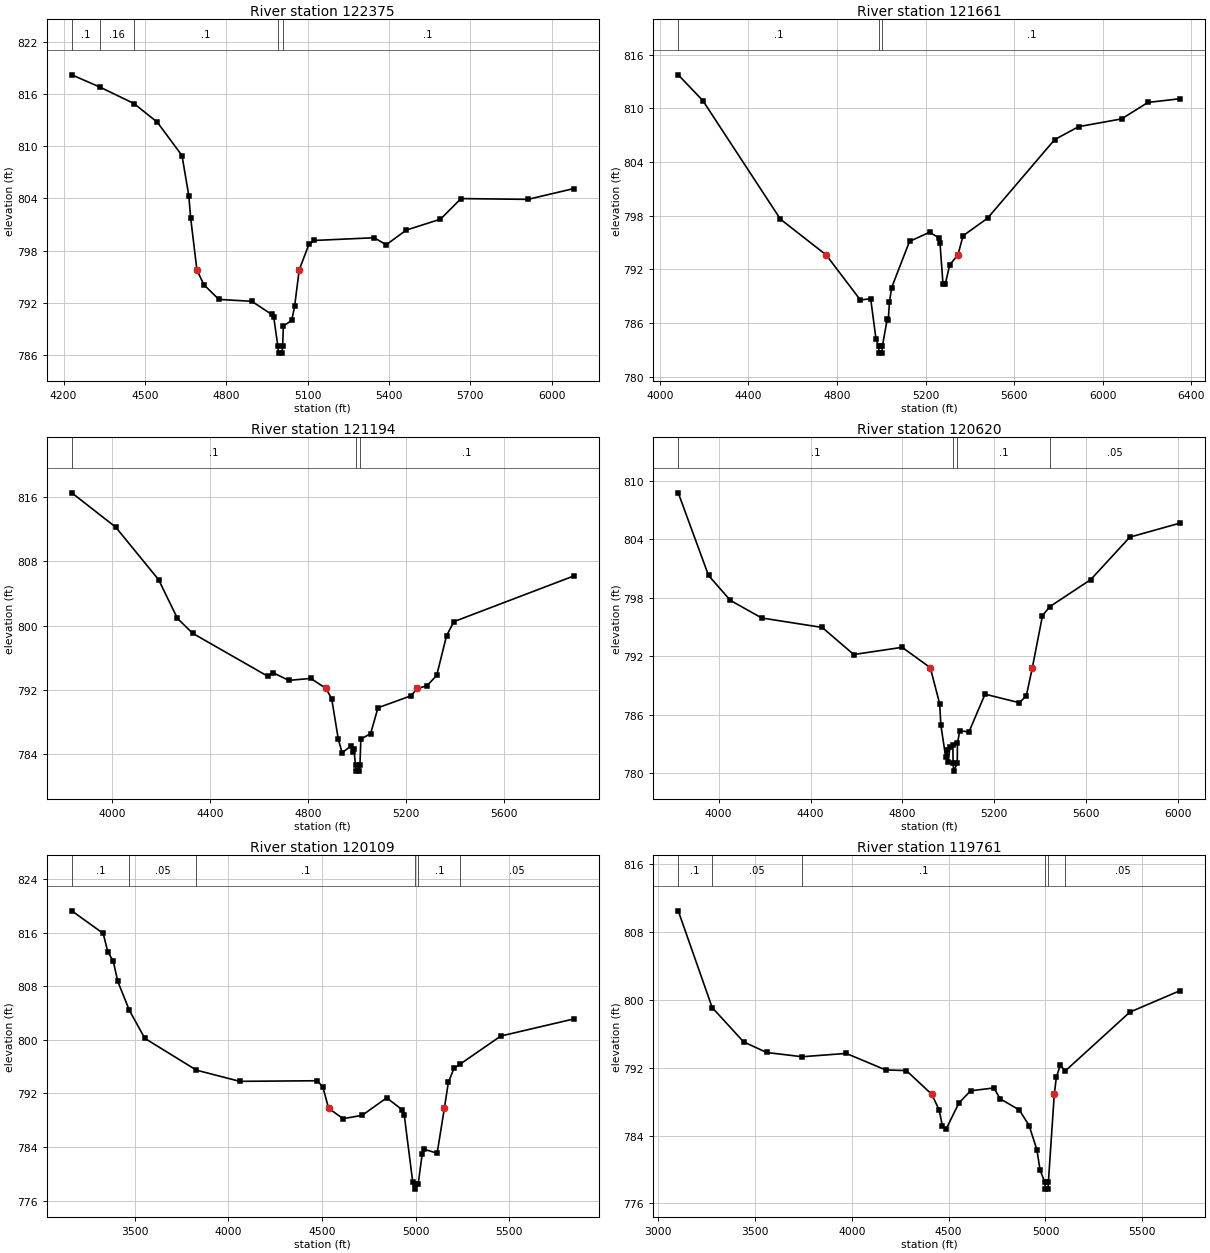
Type RM Length L Ch R = 1 ,122375  ,714,714,714
BEGIN DESCRIPTION:
CHACON CREEK 159.0
END DESCRIPTION:
XS GIS Cut Line= 3
      1997866.22     13657500.71        1997125.       13657775.
      1996118.88     13658113.88
#Sta/Elev= 30
  4230.1  818.18  4335.6  816.75  4459.4  814.89  4545.5  812.75  4636.7  808.92
  4661.7  804.34  4668.6  801.78 4691.64795.8267  4717.2  794.12  4772.7  792.43
  4894.3  792.21  4967.1  790.72  4974.8  790.45  4990.3  787.07  4992.7  786.27
  5005.6  786.27  5007.9  787.07  5010.6  789.38  5041.5  790.02  5052.1  791.64
 5069.11795.8271  5104.9  798.74  5125.4  799.19  5345.8   799.5  5389.8  798.69
  5463.6  800.37  5590.2  801.63    5666  803.99  5912.7   803.9  6082.1  805.14
#Mann= 5 ,-1 , 0
  4230.1      .1       0  4335.6     .16       0  4459.4      .1       0
  4990.3     .07       0  5007.9      .1       0
Bank Sta=4691.64,5069.11
XS Rating Curve= 0 ,0
Exp/Cntr=0.3,0.1

Type RM Length L Ch R = 1 ,121661  ,467,467,467
BEGIN DESCRIPTION:
CHACON CREEK 158.0
END DESCRIPTION:
XS GIS Cut Line= 3
       1997916.4      13657169.8      1997208.09     13657190.63
      1995662.06     13656991.68
#Sta/Elev= 30
  4082.9  813.75  4194.4  810.85  4544.5   797.6 4750.83 793.608  4905.5  788.56
    4952  788.71  4976.1  784.17  4987.5  783.42  4989.8  782.62  5002.7  782.62
  5005.1  783.42  5026.5  786.41  5031.5  786.32  5036.6  788.29  5046.7  789.95
  5127.4  795.12  5218.1  796.14  5258.4  795.54    5265  794.97  5278.6  790.31
  5288.7  790.33  5308.8  792.49 5345.95 793.608  5369.3  795.75  5480.2  797.72
  5782.7   806.5    5891  807.95  6085.2  808.82    6204  810.66  6350.3  811.08
#Mann= 3 ,-1 , 0
  4082.9      .1       0  4987.5     .07       0  5005.1      .1       0
Bank Sta=4750.83,5345.95
XS Rating Curve= 0 ,0
Exp/Cntr=0.3,0.1

Type RM Length L Ch R = 1 ,121194  ,574,574,574
BEGIN DESCRIPTION:
CHACON CREEK 157.0
END DESCRIPTION:
XS GIS Cut Line= 3
      1998165.71     13656990.28        1997025.       13656725.
      1996144.89     13656745.49
#Sta/Elev= 30
  3834.8  816.52  4013.9  812.26  4189.5  805.71  4266.7  800.88  4328.3  799.04
  4636.3  793.67  4656.9  794.13  4721.3  793.17  4811.7  793.41 4873.54792.1656
  4896.9  790.87  4923.8  785.86  4939.5  784.15  4975.2     785  4982.1   784.2
  4987.2  784.58  4994.3  782.67  4996.8  781.87  5009.9  781.87  5012.4  782.67
    5016  785.85    5056  786.55    5086  789.76  5220.9  791.25 5246.92792.1658
    5286  792.49    5326   793.8  5366.1  798.72  5396.1  800.48  5886.3  806.17
#Mann= 3 ,-1 , 0
  3834.8      .1       0  4994.3     .07       0  5012.4      .1       0
Bank Sta=4873.54,5246.92
XS Rating Curve= 0 ,0
Exp/Cntr=0.3,0.1

Type RM Length L Ch R = 1 ,120620  ,511,511,511
BEGIN DESCRIPTION:
CHACON CREEK 156.0
END DESCRIPTION:
XS GIS Cut Line= 3
      1998150.15     13656599.67        1997025.       13656225.
      1996025.14     13656261.11
#Sta/Elev= 30
    3824  808.76  3955.9  800.28  4050.8  797.72  4187.8  795.91    4451  794.94
  4588.3  792.16    4799   792.9  4921.6790.8112  4962.4  787.11  4967.7  784.91
  4988.8  781.61  4994.1  782.37  4999.4   781.1  5007.3  782.64  5019.9  782.92
  5020.9  780.99  5023.4  780.19    5039  780.99  5039.9  783.03  5049.9  784.34
  5089.9  784.21    5160  788.09  5310.1  787.21  5340.1  787.95 5366.04790.8115
  5410.2  796.15  5441.7  797.07  5620.3  799.85  5790.4  804.21  6010.4  805.66
#Mann= 4 ,-1 , 0
    3824      .1       0  5020.9     .07       0    5039      .1       0
  5441.7     .05       0
Bank Sta=4921.6,5366.04
XS Rating Curve= 0 ,0
Exp/Cntr=0.3,0.1

Type RM Length L Ch R = 1 ,120109  ,348,348,348
BEGIN DESCRIPTION:
CHACON CREEK 155.0
END DESCRIPTION:
XS GIS Cut Line= 3
      1998566.77     13656422.57      1996920.94     13655755.91
      1996014.68     13655761.12
#Sta/Elev= 30
  3163.6  819.24  3331.5  815.87  3355.6  813.17  3385.1  811.73  3409.2  808.72
  3471.5  804.38  3553.9  800.21  3829.4  795.47    4061   793.8    4476  793.89
  4505.5   792.9 4535.42789.7882  4612.7  788.23  4714.6  788.73  4845.9  791.34
    4929  789.55  4939.3  788.84  4985.3  778.72  4996.2  778.52  4998.7  777.72
  5014.3  778.52  5035.3  782.94  5045.3  783.67  5115.3  783.08 5153.99789.7883
  5175.3  793.66  5205.3  795.73  5239.3  796.39  5455.3  800.56  5845.6  803.11
#Mann= 6 ,-1 , 0
  3163.6      .1       0  3471.5     .05       0  3829.4      .1       0
  4996.2     .07       0  5014.3      .1       0  5239.3     .05       0
Bank Sta=4535.42,5153.99
XS Rating Curve= 0 ,0
Exp/Cntr=0.3,0.1

Type RM Length L Ch R = 1 ,119761  ,353,353,353
BEGIN DESCRIPTION:
Mapping XS 8b5c0227
END DESCRIPTION:
XS GIS Cut Line= 3
       1998515.4     13656086.47      1997270.59      13655482.3
      1996068.69     13655352.22
#Sta/Elev= 30
  3103.7  810.44  3278.9  799.06  3441.2  795.02  3559.9  793.77  3743.4  793.27
  3971.3  793.66  4174.4  791.72  4281.7  791.64 4413.01788.8439  4450.8  787.01
  4467.8  785.12  4487.4  784.78  4553.4  787.84  4613.7  789.26  4734.4   789.6
  4764.6  788.34  4865.2     787  4915.5  785.17  4955.7  782.33  4972.1  779.93
  4996.9  778.49  4999.4  777.69  5012.5  777.69    5015  778.49 5045.49788.8443
  5056.3  790.87  5076.4  792.27  5102.3   791.6  5435.8  798.52  5696.3  801.06
#Mann= 6 ,-1 , 0
  3103.7      .1       0  3278.9     .05       0  3743.4      .1       0
  4996.9     .07       0    5015      .1       0  5102.3     .05       0
Bank Sta=4413.01,5045.49
XS Rating Curve= 0 ,0
Exp/Cntr=0.3,0.1

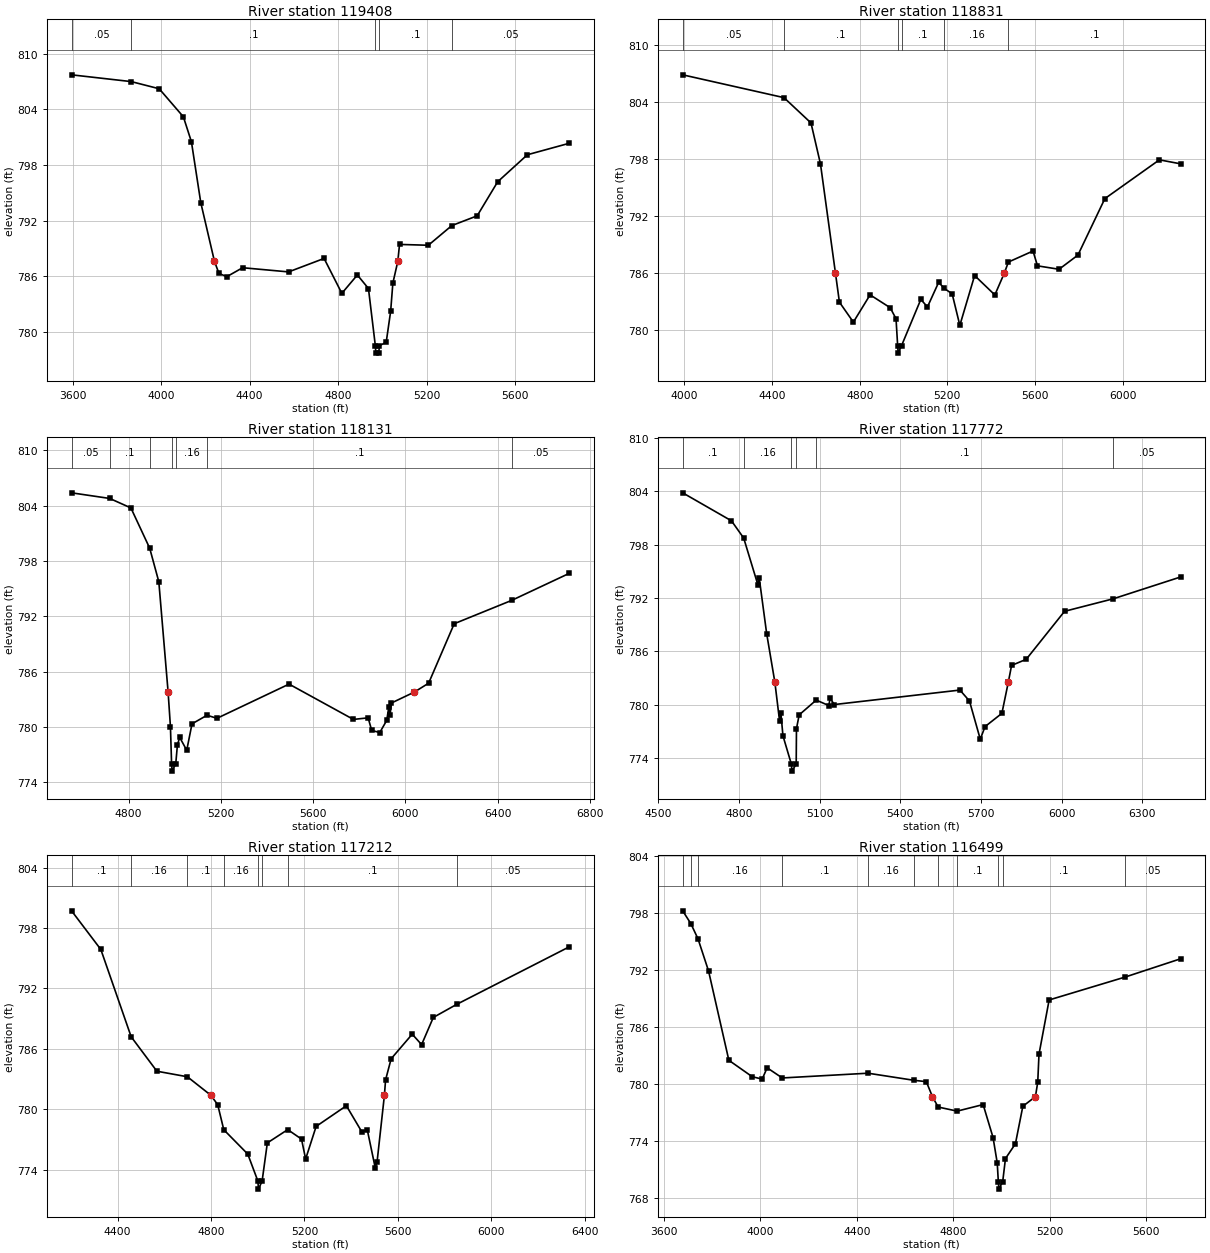
Type RM Length L Ch R = 1 ,119408  ,577,577,577
BEGIN DESCRIPTION:
Mapping XS 3403d2ee
END DESCRIPTION:
XS GIS Cut Line= 3
      1998067.45      13654539.6      1997265.71     13655049.32
      1995969.29      13655143.7
#Sta/Elev= 30
  3595.4  807.72  3865.2  806.99  3991.4  806.22  4100.7   803.2  4137.1  800.51
  4179.4  793.95  4241.2787.6292  4261.6  786.32  4297.4  785.98  4368.5  786.94
  4576.2  786.49  4736.7  787.94  4816.9  784.18  4887.1  786.16  4937.2   784.7
  4968.3  778.54  4970.8  777.74  4983.9  777.74  4986.4  778.54  5017.4  778.91
  5037.5  782.24  5047.5  785.28  5069.9787.6279  5077.6  789.45  5207.9  789.36
  5313.9  791.48  5428.5  792.53  5521.3   796.2  5655.4  799.11  5845.3  800.35
#Mann= 5 ,-1 , 0
  3595.4     .05       0  3865.2      .1       0  4968.3     .07       0
  4986.4      .1       0  5313.9     .05       0
Bank Sta=4241.2,5069.9
XS Rating Curve= 0 ,0
Exp/Cntr=0.3,0.1

Type RM Length L Ch R = 1 ,118831  ,700,700,700
BEGIN DESCRIPTION:
Mapping XS 586b35d8
END DESCRIPTION:
XS GIS Cut Line= 2
        1998005.     13654352.08      1995788.09     13654851.66
#Sta/Elev= 30
    3992  806.89  4454.3  804.49  4577.6  801.83  4620.9  797.52 4689.35786.0286
  4707.4  782.98  4771.1  780.88  4847.4  783.75    4939   782.4  4965.8  781.24
  4973.2  778.42  4975.7  777.62  4991.3  778.42    5079  783.27  5109.3  782.48
  5160.3  785.06  5186.7  784.42  5222.1  783.85  5257.1  780.54  5324.6  785.78
  5416.9  783.74 5460.03786.0291  5478.8   787.2  5591.1  788.36  5611.6   786.8
    5710  786.44  5796.1  787.93  5919.1  793.87  6168.1  797.95  6264.5  797.53
#Mann= 6 ,-1 , 0
    3992     .05       0  4454.3      .1       0  4973.2     .07       0
  4991.3      .1       0  5186.7     .16       0  5478.8      .1       0
Bank Sta=4689.35,5460.03
XS Rating Curve= 0 ,0
Exp/Cntr=0.3,0.1

Type RM Length L Ch R = 1 ,118131  ,359,359,359
BEGIN DESCRIPTION:
Mapping XS 2fa80730
END DESCRIPTION:
XS GIS Cut Line= 2
      1997760.19     13654013.54      1995619.81     13654289.55
#Sta/Elev= 30
  4553.1   805.4  4718.6  804.79  4810.4  803.76  4891.9  799.39  4931.4  795.75
 4971.64783.7896  4981.8  780.01  4986.7  776.01  4989.2  775.21  5004.8  776.01
  5012.1  778.09  5022.1  778.86  5052.4  777.47  5075.2  780.34  5140.3  781.27
  5183.5  780.94    5496  784.65  5774.9  780.82  5838.8  780.99  5854.3  779.62
  5889.3   779.4  5919.5  780.72  5928.7  782.21  5933.7  781.26  5939.7   782.6
 6039.35783.7884    6101  784.75  6211.9   791.2  6460.8  793.73  6711.2  796.67
#Mann= 7 ,-1 , 0
  4553.1     .05       0  4718.6      .1       0  4891.9     .16       0
  4986.7     .07       0  5004.8     .16       0  5140.3      .1       0
  6460.8     .05       0
Bank Sta=4971.64,6039.35
XS Rating Curve= 0 ,0
Exp/Cntr=0.3,0.1

Type RM Length L Ch R = 1 ,117772  ,560,560,560
BEGIN DESCRIPTION:
CHACON CREEK 154.0
END DESCRIPTION:
XS GIS Cut Line= 3
        1997575.       13653825.        1997175.       13653775.
       1995734.1     13653925.01
#Sta/Elev= 30
  4590.4  803.85  4771.8   800.7  4817.3  798.76  4870.1   793.5  4875.1  794.26
  4902.8     788 4933.28782.5368  4950.7   778.2  4955.7  779.05  4963.3  776.52
  4994.5  773.34    4997  772.54  5012.6  773.34  5013.6  777.32  5023.7  778.87
    5087  780.53  5133.8  779.92  5138.8  780.73  5154.4  780.03  5621.6  781.66
  5657.1  780.43  5697.3  776.13  5715.1  777.55  5777.7  779.04 5801.57 782.538
  5813.7  784.43  5868.2  785.12  6010.8  790.52  6192.1  791.93  6442.2  794.38
#Mann= 6 ,-1 , 0
  4590.4      .1       0  4817.3     .16       0  4994.5     .07       0
  5012.6     .16       0    5087      .1       0  6192.1     .05       0
Bank Sta=4933.28,5801.57
XS Rating Curve= 0 ,0
Exp/Cntr=0.3,0.1

Type RM Length L Ch R = 1 ,117212  ,713,713,713
BEGIN DESCRIPTION:
CHACON CREEK 153.0
END DESCRIPTION:
XS GIS Cut Line= 4
      1997640.43     13653393.75      1997097.85     13653385.07
      1996373.02     13653606.43      1995543.99     13653671.53
#Sta/Elev= 30
  4202.8  799.71  4328.2  795.87  4458.1   787.2  4568.3  783.78  4698.8  783.23
  4799.8781.3839  4828.8  780.45  4854.7  777.97  4957.5  775.55  5000.8  772.87
  5003.3  772.07  5018.9  772.87  5041.3  776.66  5128.6  777.98  5187.6  777.04
  5205.3  775.06  5250.3   778.3  5379.8  780.35  5445.4  777.78  5469.9   777.9
  5503.3   774.2  5511.4   774.8 5542.66781.3837  5547.7  782.92  5571.6  785.02
  5661.8  787.46    5702  786.42  5752.1  789.12    5853  790.43  6334.9  796.14
#Mann= 8 ,-1 , 0
  4202.8      .1       0  4458.1     .16       0  4698.8      .1       0
  4854.7     .16       0  5000.8     .07       0  5018.9     .16       0
  5128.6      .1       0    5853     .05       0
Bank Sta=4799.8,5542.66
XS Rating Curve= 0 ,0
Exp/Cntr=0.3,0.1

Type RM Length L Ch R = 1 ,116499  ,240,240,240
BEGIN DESCRIPTION:
Mapping XS 6838d5f3
END DESCRIPTION:
XS GIS Cut Line= 2
      1997675.15     13652825.17      1995669.91     13653306.94
#Sta/Elev= 30
  3679.1  798.19  3712.9  796.84  3742.7  795.23  3786.3  791.85  3870.3  782.46
  3967.2  780.73  4008.4  780.48  4028.9  781.67  4091.6   780.6  4446.9   781.1
  4635.3  780.36  4688.3  780.21 4713.73778.6307  4737.3  777.54  4816.2  777.11
  4923.7   777.8  4964.8  774.33  4982.1  771.66  4986.6   769.7  4989.1   768.9
  5004.8   769.7  5016.2  772.12  5057.4  773.67  5088.2  777.62 5140.28778.6315
  5149.9  780.15  5155.1   783.1  5197.1  788.81  5511.9  791.22  5741.4  793.14
#Mann= 11 ,-1 , 0
  3679.1     .16       0  3712.9      .1       0  3742.7     .16       0
  4091.6      .1       0  4446.9     .16       0  4635.3      .1       0
  4737.3     .16       0  4816.2      .1       0  4986.6     .07       0
  5004.8      .1       0  5511.9     .05       0
Bank Sta=4713.73,5140.28
XS Rating Curve= 0 ,0
Exp/Cntr=0.3,0.1