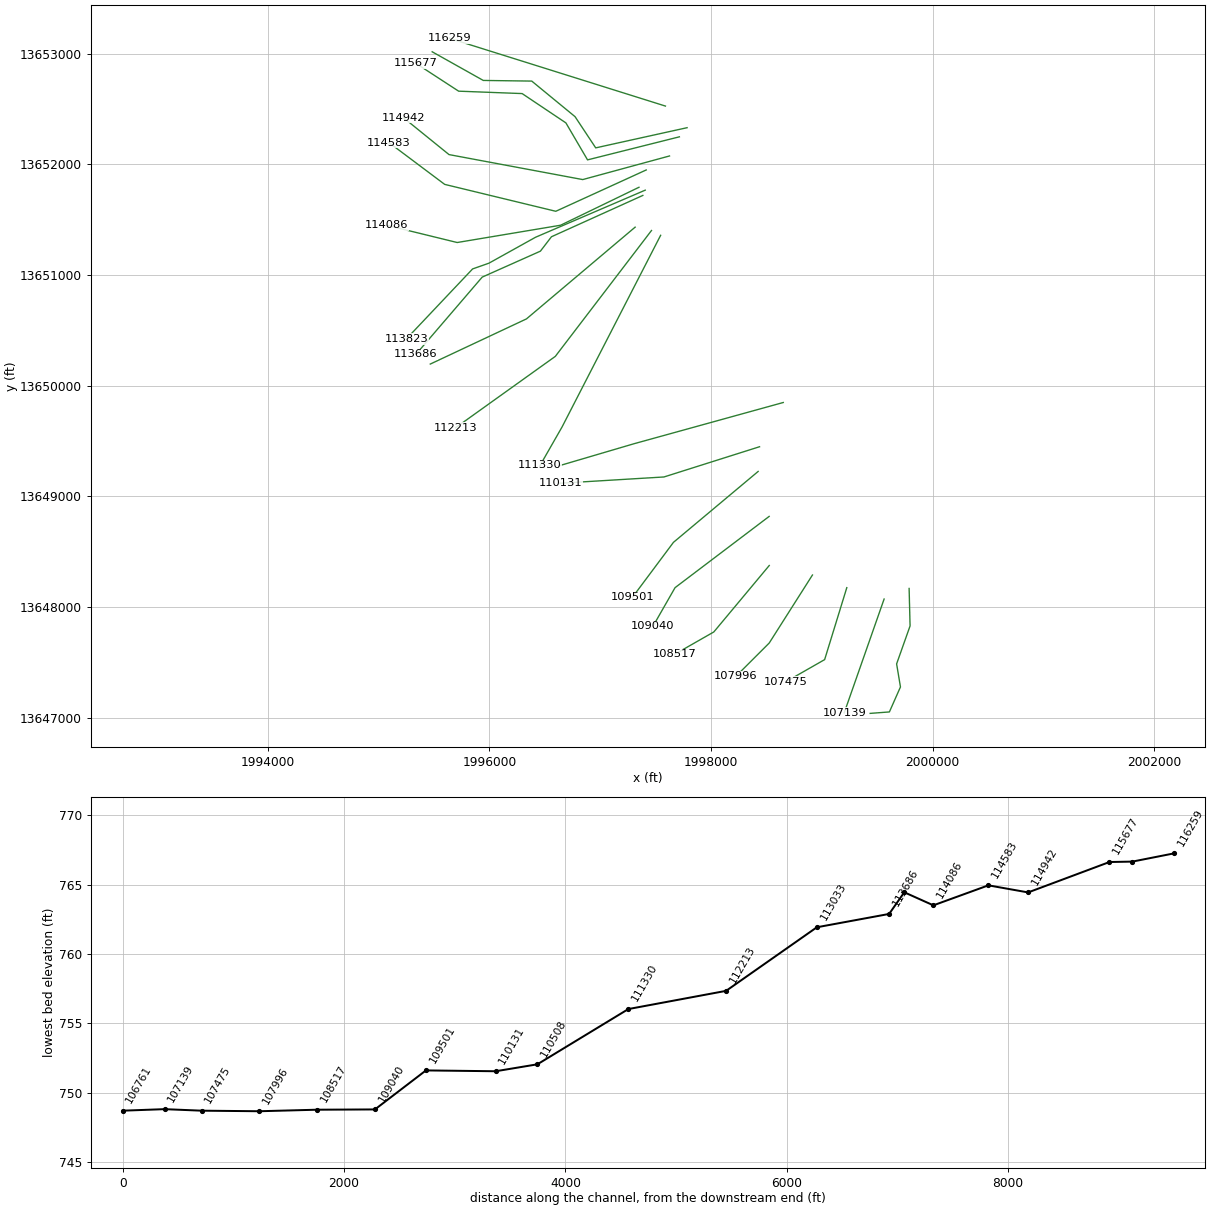
HEC-RAS study CHACON CREEK.prj: CHACON CREEK Base Level Engineering

--- CHACON CREEK.g01 (geometry) --- (continued)

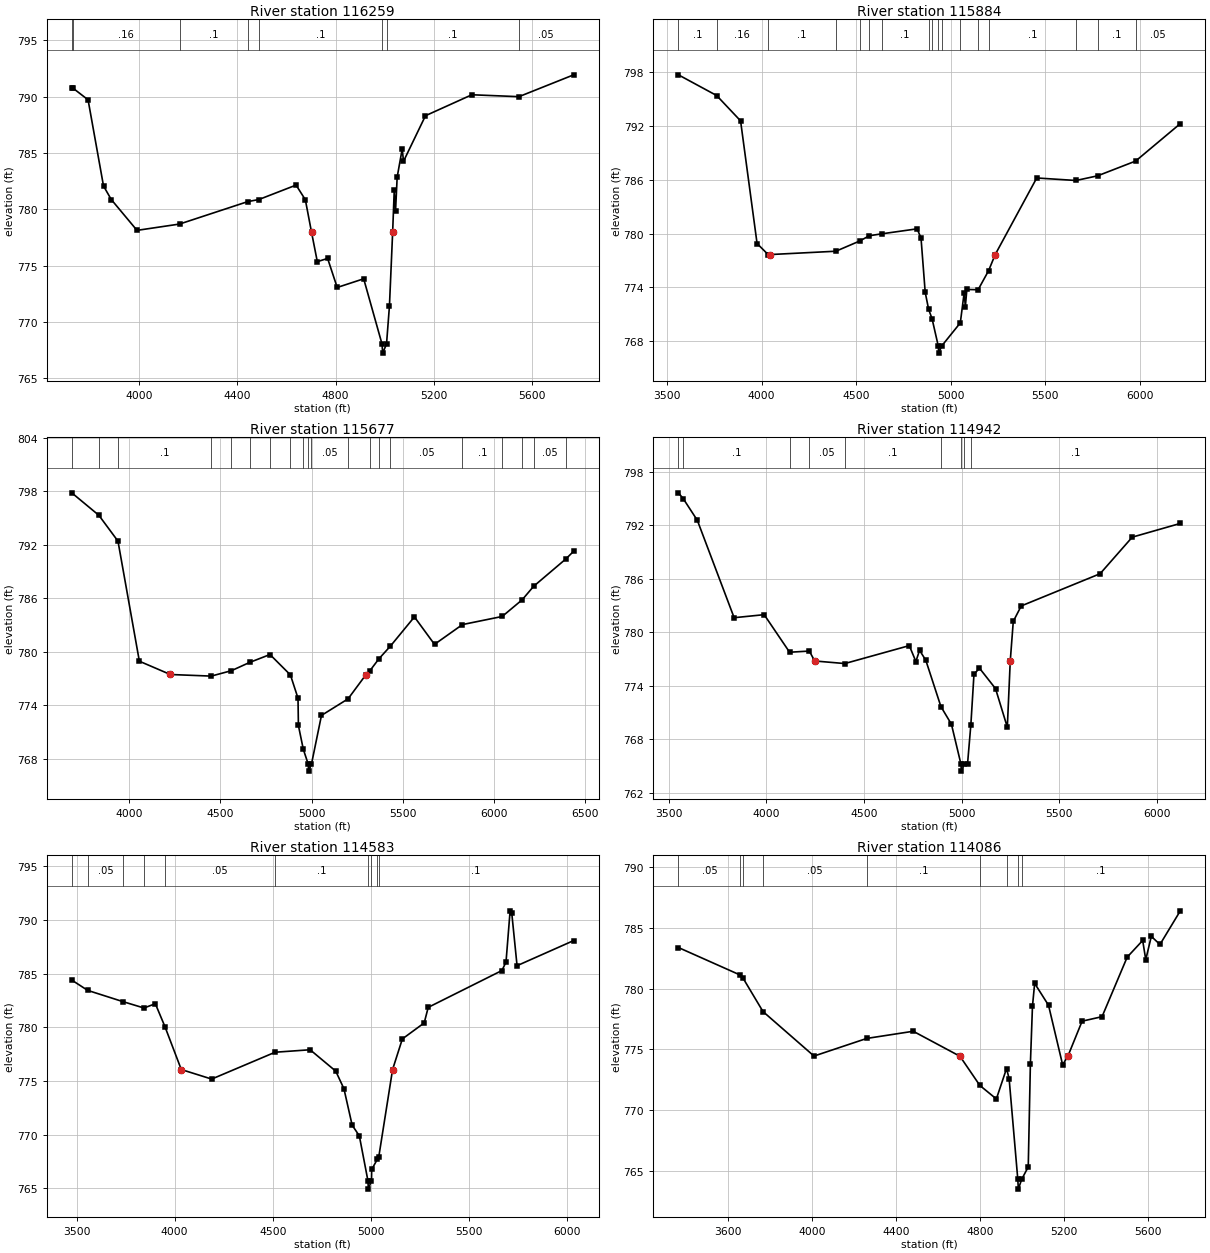
Type RM Length L Ch R = 1 ,116259  ,375,375,375
BEGIN DESCRIPTION:
Mapping XS ca3491b5
END DESCRIPTION:
XS GIS Cut Line= 2
      1997588.31      13652525.7      1995639.73     13653137.61
#Sta/Elev= 30
  3726.6  790.79  3731.4  790.77    3793  789.73  3855.8  782.08  3887.3  780.88
  3992.1  778.14  4165.1   778.7  4442.4  780.69  4488.2  780.88  4639.4  782.16
  4677.1  780.86 4702.38777.9628  4725.8  775.36  4767.7  775.65  4806.7  773.07
  4914.5  773.84  4989.2  768.04  4991.7  767.24  5007.4  768.04  5019.3  771.42
 5032.31777.9592  5038.8  781.68  5044.1  779.84  5050.7  782.86  5071.3  785.37
  5076.5  784.27    5166  788.32  5354.7  790.18  5546.2  790.01    5769  791.95
#Mann= 8 ,-1 , 0
  3726.6      .1       0  3731.4     .16       0  4165.1      .1       0
  4442.4     .16       0  4488.2      .1       0  4989.2     .07       0
  5007.4      .1       0  5546.2     .05       0
Bank Sta=4702.38,5032.31
XS Rating Curve= 0 ,0
Exp/Cntr=0.3,0.1

Type RM Length L Ch R = 1 ,115884  ,207,207,207
BEGIN DESCRIPTION:
CHACON CREEK 152.0
END DESCRIPTION:
XS GIS Cut Line= 6
      1997783.65      13652330.4      1996958.96     13652148.09
      1996772.33     13652430.21       1996381.7     13652751.39
      1995944.21      13652757.3      1995483.23     13653016.17
#Sta/Elev= 30
  3560.4  797.73  3762.7  795.42  3889.2  792.59  3976.5  778.89  4034.8  777.66
 4042.65 777.655  4393.3  778.03  4519.2  779.17  4570.3  779.76  4634.9  779.97
  4822.8  780.53  4843.6  779.52  4865.8  773.44    4884  771.53  4902.1  770.49
  4934.9  767.45  4937.4  766.65  4953.1  767.45  5051.5  770.03  5071.8  773.38
  5078.2  771.85  5086.1  773.76  5145.6  773.73  5200.9  775.85 5235.99777.6548
  5455.7  786.21  5663.5  785.93  5777.6  786.45  5978.9   788.1  6215.2  792.28
#Mann= 17 ,-1 , 0
  3560.4      .1       0  3762.7     .16       0  4034.8      .1       0
  4393.3     .05       0  4519.2      .1       0  4570.3     .08       0
  4634.9      .1       0    4884     .05       0  4902.1     .08       0
  4934.9     .07       0  4953.1     .08       0  5051.5      .1       0
  5145.6     .08       0  5200.9      .1       0  5663.5     .08       0
  5777.6      .1       0  5978.9     .05       0
Bank Sta=4042.65,5235.99
XS Rating Curve= 0 ,0
Exp/Cntr=0.3,0.1

Type RM Length L Ch R = 1 ,115677  ,735,735,735
BEGIN DESCRIPTION:
CHACON CREEK 151.0
END DESCRIPTION:
XS GIS Cut Line= 6
      1997714.21     13652247.93      1996885.17     13652039.59
      1996689.86     13652373.79       1996294.9     13652638.55
      1995721.98     13652660.25       1995337.2     13652911.01
#Sta/Elev= 30
  3686.1  797.84  3834.6  795.32  3939.3  792.42  4056.5  778.95 4226.23777.4598
  4450.1  777.28  4561.2  777.89  4660.2  778.81  4772.2   779.7  4884.2  777.41
  4925.7   774.8  4927.9  771.74  4954.7  769.07  4981.4  767.42  4983.9  766.62
  4999.6  767.42  5054.2  772.87    5200  774.73 5298.63 777.459  5317.7  777.83
    5369  779.22  5432.2  780.65  5563.5  783.92  5673.6  780.84  5826.6  783.06
  6044.4  783.97  6153.9  785.84  6216.5  787.35  6393.7  790.43  6436.1  791.29
#Mann= 20 ,-1 , 0
  3686.1      .1       0  3834.6     .16       0  3939.3      .1       0
  4450.1     .08       0  4561.2      .1       0  4660.2     .08       0
  4772.2     .05       0  4884.2     .08       0  4954.7     .05       0
  4981.4     .04       0  4999.6     .05       0    5200     .05       0
  5317.7      .1       0    5369     .08       0  5432.2     .05       0
  5826.6      .1       0  6044.4     .05       0  6153.9      .1       0
  6216.5     .05       0  6393.7     .16       0
Bank Sta=4226.23,5298.63
XS Rating Curve= 0 ,0
Exp/Cntr=0.3,0.1

Type RM Length L Ch R = 1 ,114942  ,359,359,359
BEGIN DESCRIPTION:
CHACON CREEK 150.0
END DESCRIPTION:
XS GIS Cut Line= 4
      1997624.97     13652074.99      1996841.77     13651861.64
      1995635.17     13652087.33      1995223.79     13652420.76
#Sta/Elev= 30
  3550.3  795.63  3575.2  794.97  3647.1  792.55  3835.5  781.63  3989.3  781.97
  4119.4  777.76  4220.5  777.89 4247.67776.7795  4401.9  776.49    4732   778.5
  4765.7  776.72  4784.6  777.98  4816.6  776.85  4893.9  771.66  4947.6  769.69
  4996.2  765.23  4998.7  764.43  5014.4  765.23  5030.2  765.27  5047.1  769.64
    5063  775.29  5091.2  775.97  5173.3  773.68  5233.7  769.35 5248.71776.7813
  5264.2  781.22  5304.9  782.95  5708.5  786.56    5873  790.66  6119.1   792.2
#Mann= 9 ,-1 , 0
  3550.3     .16       0  3575.2      .1       0  4119.4     .08       0
  4220.5     .05       0  4401.9      .1       0  4893.9     .16       0
  4996.2     .07       0  5014.4     .16       0  5047.1      .1       0
Bank Sta=4247.67,5248.71
XS Rating Curve= 0 ,0
Exp/Cntr=0.3,0.1

Type RM Length L Ch R = 1 ,114583  ,497,497,497
BEGIN DESCRIPTION:
Mapping XS ddcc5303
END DESCRIPTION:
XS GIS Cut Line= 4
      1997414.72     13651948.46      1996598.72     13651575.18
      1995596.11     13651818.23      1995092.65     13652195.83
#Sta/Elev= 30
  3475.5  784.41  3556.7  783.45  3736.9   782.4  3843.6  781.81  3901.5  782.21
  3950.3  780.08 4033.72776.0786  4188.7  775.19  4511.9  777.69  4690.4  777.92
    4821  775.93  4862.8  774.29  4904.6   770.9  4941.3   769.9  4984.9  765.74
  4987.4  764.94  5003.2  765.74  5004.3  766.77  5033.1  767.72  5040.5  767.96
 5110.75776.0779  5160.6  778.93  5271.9  780.42  5292.4  781.87  5668.1   785.3
  5688.9  786.09  5709.8  790.86  5718.1  790.67  5745.2  785.75  6033.8  788.09
#Mann= 10 ,-1 , 0
  3475.5      .1       0  3556.7     .05       0  3736.9     .08       0
  3843.6      .1       0  3950.3     .05       0  4511.9      .1       0
  4984.9     .07       0  5003.2      .1       0  5033.1     .16       0
  5040.5      .1       0
Bank Sta=4033.72,5110.75
XS Rating Curve= 0 ,0
Exp/Cntr=0.3,0.1

Type RM Length L Ch R = 1 ,114086  ,263,263,263
BEGIN DESCRIPTION:
Mapping XS 201691d3
END DESCRIPTION:
XS GIS Cut Line= 4
      1997349.55     13651792.18      1996642.12     13651449.31
      1995708.96     13651293.06      1995070.91     13651449.32
#Sta/Elev= 30
  3363.6  783.38  3658.6  781.11  3671.7  780.85  3766.3  778.11  4009.1  774.45
  4260.1   775.9  4481.4  776.49 4703.88774.4324  4798.6  772.03  4877.1  770.92
  4925.5  773.42  4937.8   772.6  4979.2   764.3  4981.7   763.5  4997.5   764.3
  5028.9  765.33  5039.1   773.8    5049  778.55  5059.4  780.43  5125.4  778.63
  5192.6  773.73 5217.39 774.432  5285.3  777.32  5380.2  777.69  5499.9  782.59
  5573.6  783.96  5588.3  782.38  5614.7   784.3  5655.9  783.63  5752.8   786.4
#Mann= 9 ,-1 , 0
  3363.6     .05       0  3658.6      .1       0  3671.7     .08       0
  3766.3     .05       0  4260.1      .1       0  4798.6     .16       0
  4925.5      .1       0  4979.2     .07       0  4997.5      .1       0
Bank Sta=4703.88,5217.39
XS Rating Curve= 0 ,0
Exp/Cntr=0.3,0.1

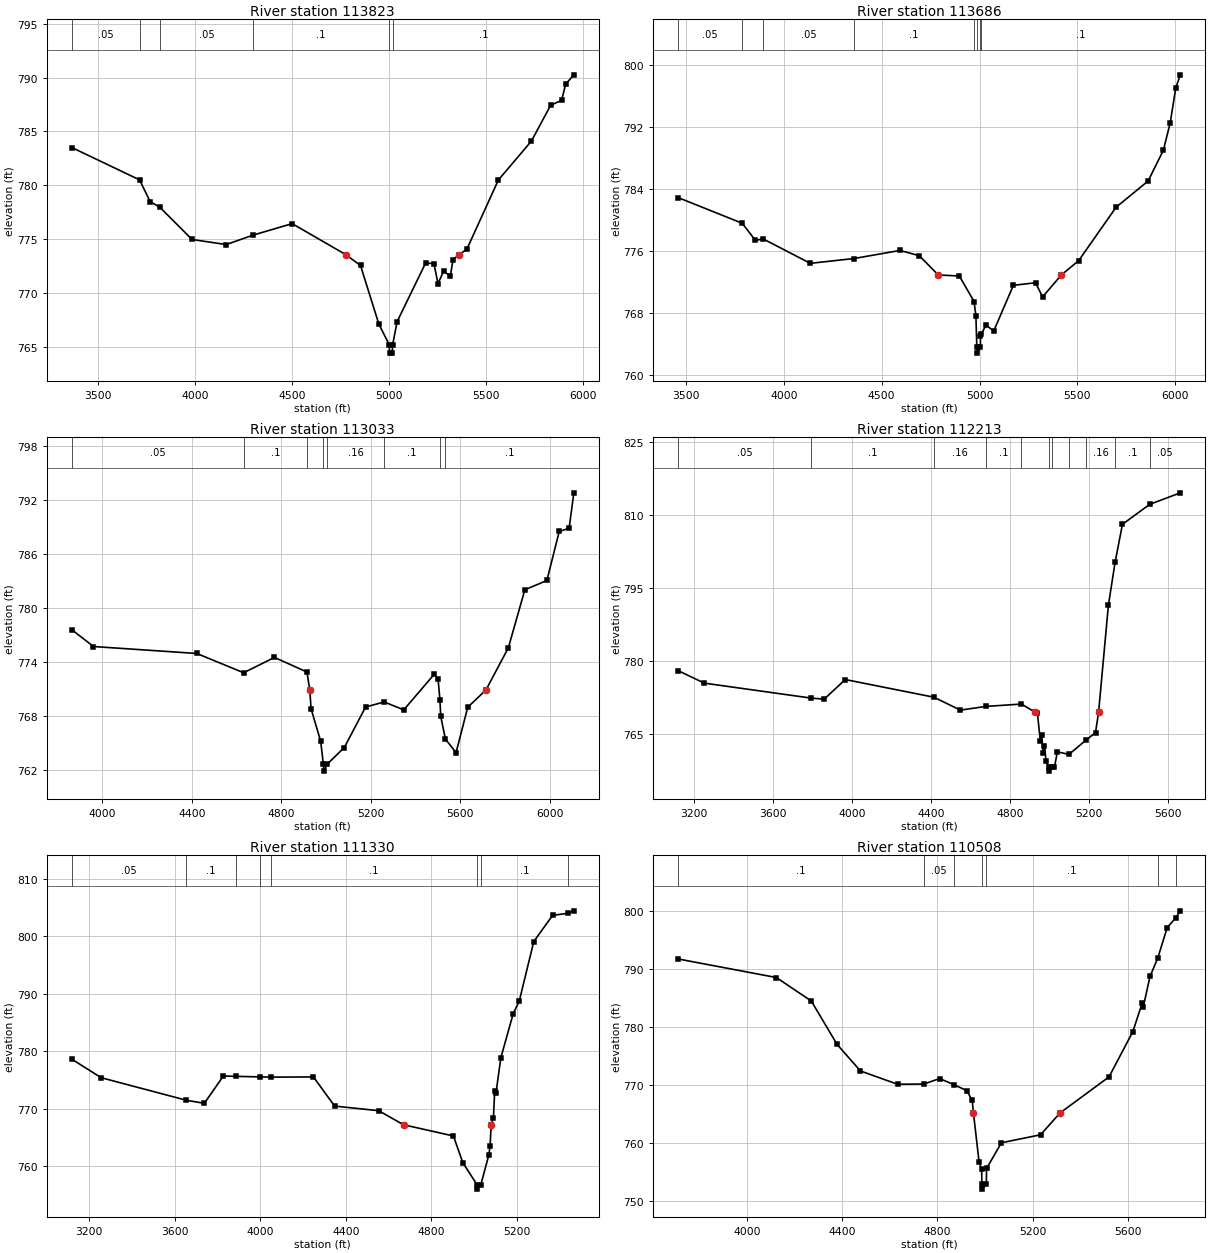
Type RM Length L Ch R = 1 ,113823  ,137,137,137
BEGIN DESCRIPTION:
Mapping XS 23960321
END DESCRIPTION:
XS GIS Cut Line= 5
      1997405.99     13651766.14      1996416.42      13651340.8
      1995995.42     13651106.43      1995847.85     13651054.34
      1995249.44     13650421.24
#Sta/Elev= 30
  3365.4  783.51  3714.5  780.51  3769.2   778.5  3820.2  777.95  3985.1  774.98
  4160.8  774.51  4300.6  775.39  4500.7  776.45 4776.92 773.577  4852.9  772.57
  4947.5  767.13  5000.5  765.24    5003  764.44  5016.3  764.44  5018.8  765.24
  5041.4  767.36  5188.7  772.81  5231.1  772.74  5252.2  770.89  5280.5  772.02
  5315.7  771.61  5329.9  773.12 5361.27773.5767  5400.6  774.07  5563.3   780.5
  5733.2   784.1  5832.3  787.42  5888.9  787.89    5910  789.39    5952  790.25
#Mann= 6 ,-1 , 0
  3365.4     .05       0  3714.5     .08       0  3820.2     .05       0
  4300.6      .1       0  5000.5     .07       0  5018.8      .1       0
Bank Sta=4776.92,5361.27
XS Rating Curve= 0 ,0
Exp/Cntr=0.3,0.1

Type RM Length L Ch R = 1 ,113686  ,653,653,653
BEGIN DESCRIPTION:
Mapping XS fe4deaf3
END DESCRIPTION:
XS GIS Cut Line= 5
      1997384.32     13651718.41      1996559.65     13651345.14
      1996459.83     13651214.93      1995934.65     13650980.56
      1995335.72      13650281.8
#Sta/Elev= 30
  3460.9   782.9  3787.7   779.6  3855.3  777.39  3894.2  777.59  4135.7  774.44
  4359.1  775.06  4593.5   776.1  4691.9  775.43  4789.1772.9446  4896.8  772.81
  4972.2  769.52  4981.5  767.61  4986.2  763.68  4988.7  762.88  5004.5  763.68
  5004.7  765.09  5009.9  765.38  5033.4  766.51  5072.1  765.71  5172.9  771.61
  5285.9  771.94  5322.2  770.12 5418.14772.9444  5506.5  774.79  5697.5  781.66
  5861.1  785.04    5939     789  5974.1  792.54  6002.6  797.05  6025.6  798.71
#Mann= 8 ,-1 , 0
  3460.9     .05       0  3787.7     .08       0  3894.2     .05       0
  4359.1      .1       0  4972.2     .16       0  4986.2     .07       0
  5004.5     .16       0  5009.9      .1       0
Bank Sta=4789.1,5418.14
XS Rating Curve= 0 ,0
Exp/Cntr=0.3,0.1

Type RM Length L Ch R = 1 ,113033  ,820,820,820
BEGIN DESCRIPTION:
CHACON CREEK 149.0
END DESCRIPTION:
XS GIS Cut Line= 3
      1997314.87     13651431.95      1996333.96     13650602.96
      1995465.95     13650194.99
#Sta/Elev= 30
  3863.6  777.62  3960.6  775.75  4422.1  774.98  4631.5  772.84  4769.3  774.54
  4914.5  772.92 4927.04770.9275    4933  768.83  4975.9  765.22  4987.6  762.72
  4990.1  761.92  5005.9  762.72  5081.3  764.54  5176.4  769.03  5259.3   769.6
    5347  768.72  5483.9  772.69  5500.3  772.15  5508.7   769.8  5512.2  767.99
  5533.1  765.48  5580.6  763.97  5632.9  769.01 5714.24770.9275  5814.2   775.6
  5888.1  782.05  5986.5  783.08  6041.7  788.52  6085.9  788.88    6107  792.81
#Mann= 8 ,-1 , 0
  3863.6     .05       0  4631.5      .1       0  4914.5     .16       0
  4987.6     .07       0  5005.9     .16       0  5259.3      .1       0
  5508.7     .05       0  5533.1      .1       0
Bank Sta=4927.04,5714.24
XS Rating Curve= 0 ,0
Exp/Cntr=0.3,0.1

Type RM Length L Ch R = 1 ,112213  ,883,883,883
BEGIN DESCRIPTION:
CHACON CREEK 148.0
END DESCRIPTION:
XS GIS Cut Line= 3
       1997462.4     13651401.53      1996594.38     13650264.41
       1995693.2     13649618.86
#Sta/Elev= 30
  3122.2  777.99    3254  775.43  3791.9  772.37  3860.1  772.13  3966.9  776.17
    4415  772.54  4549.2  769.88  4676.9  770.64  4857.9  771.13 4928.24 769.429
  4938.8  769.21  4953.5  763.46  4959.7   764.8  4968.3  761.04  4974.4  762.58
  4982.5  759.33  4994.7  758.14  4997.2  757.34  5013.1  758.14  5024.8  758.14
  5039.5  761.31  5098.2  760.78  5186.5  763.79  5232.4  765.26 5247.99769.4285
  5297.5  791.42  5331.5  800.29  5368.7  808.09  5506.1  812.18  5661.3  814.56
#Mann= 11 ,-1 , 0
  3122.2     .05       0  3791.9      .1       0    4415     .16       0
  4676.9      .1       0  4857.9     .16       0  4994.7     .07       0
  5013.1     .16       0  5098.2      .1       0  5186.5     .16       0
  5331.5      .1       0  5506.1     .05       0
Bank Sta=4928.24,5247.99
XS Rating Curve= 0 ,0
Exp/Cntr=0.3,0.1

Type RM Length L Ch R = 1 ,111330  ,822,822,822
BEGIN DESCRIPTION:
CHACON CREEK 147.0
END DESCRIPTION:
XS GIS Cut Line= 3
      1997544.89     13651358.15      1996655.56     13649627.26
      1996456.36     13649278.66
#Sta/Elev= 30
  3118.4  778.65  3255.8  775.42  3653.8   771.5  3738.2  770.96    3827  775.71
  3884.7  775.66  3997.3  775.56  4048.8  775.52  4248.4  775.55  4347.4  770.48
  4553.4  769.68 4669.52767.2325  4902.7  765.28  4947.1  760.61  5012.8  756.83
  5015.3  756.03  5031.2  756.83  5068.6  762.01  5074.2  763.52 5079.49767.2325
    5090  768.49  5095.8  773.14  5101.6   772.7  5124.6  778.89  5182.2  786.54
    5211   788.8  5278.6  799.12  5366.5  803.67  5439.7  804.04  5465.9  804.46
#Mann= 8 ,-1 , 0
  3118.4     .05       0  3653.8      .1       0  3884.7     .05       0
  3997.3     .08       0  4048.8      .1       0  5012.8     .07       0
  5031.2      .1       0  5439.7      .1       0
Bank Sta=4669.52,5079.49
XS Rating Curve= 0 ,0
Exp/Cntr=0.3,0.1

Type RM Length L Ch R = 1 ,110508  ,377,377,377
BEGIN DESCRIPTION:
CHACON CREEK 146.0
END DESCRIPTION:
XS GIS Cut Line= 3
      1998651.63     13649847.74      1997301.84     13649474.48
      1996624.97     13649274.99
#Sta/Elev= 30
  3712.6  791.66  4124.1  788.47  4270.7  784.43  4378.9  776.96  4476.9  772.39
  4632.5   770.1  4743.3  770.14  4808.9  771.08  4870.7  770.01    4923  768.99
  4945.6  767.34 4950.89765.1742  4974.7  756.69  4985.3  755.47  4986.3  752.85
  4988.8  752.05  5004.9  752.85    5006  755.61  5068.3  760.03  5232.3   761.4
 5314.53765.1747  5519.8  771.37  5619.8  779.18  5658.3  784.01  5663.5  783.45
  5691.6  788.66  5724.4  791.85  5763.5  797.05  5800.6   798.8  5818.7  799.95
#Mann= 7 ,-1 , 0
  3712.6      .1       0  4743.3     .05       0  4870.7      .1       0
  4986.3     .07       0  5004.9      .1       0  5724.4     .16       0
  5800.6      .1       0
Bank Sta=4950.89,5314.53
XS Rating Curve= 0 ,0
Exp/Cntr=0.3,0.1

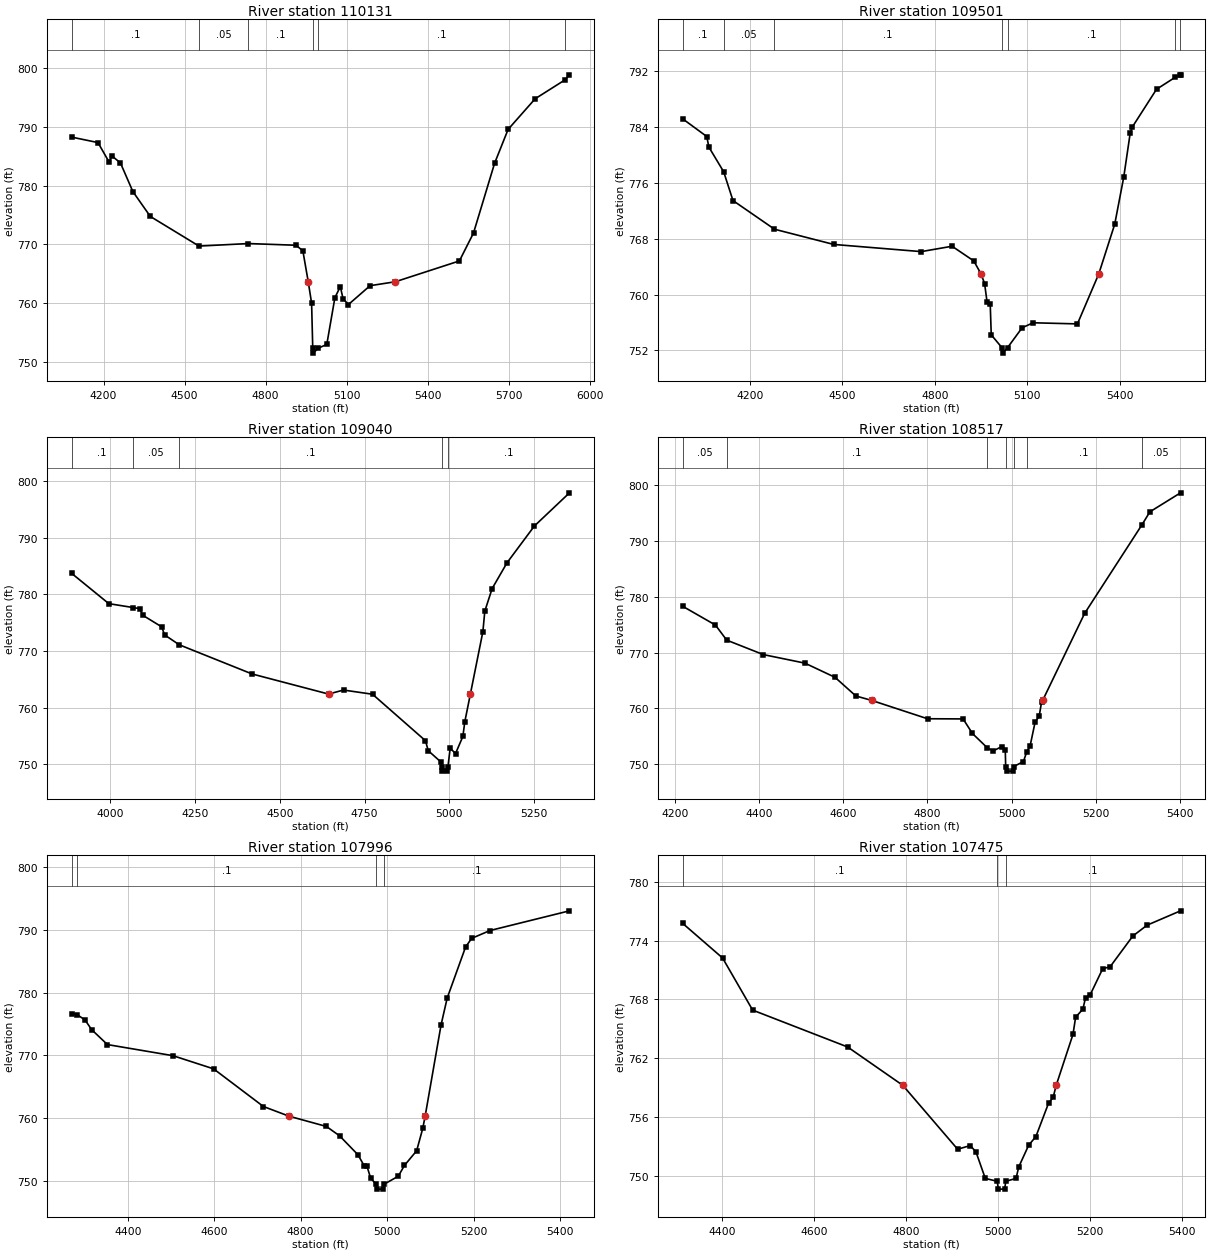
Type RM Length L Ch R = 1 ,110131  ,630,630,630
BEGIN DESCRIPTION:
CHACON CREEK 145.0
END DESCRIPTION:
XS GIS Cut Line= 3
      1998437.58     13649448.16        1997575.       13649175.
       1996638.2      13649118.4
#Sta/Elev= 30
  4081.6  788.22  4179.4  787.29  4220.7  783.97  4231.2  785.02  4262.6  783.83
  4308.6  778.97  4373.2  774.75  4553.4  769.72  4736.4  770.15    4913  769.86
    4938  768.89 4957.76763.6624  4970.2  760.04  4974.5  752.35    4977  751.55
  4993.1  752.35  5026.5  753.03  5056.5  760.97  5076.6  762.84  5086.6  760.79
  5106.6   759.8  5186.8     763 5280.01763.6628  5517.4   767.2  5569.6  771.94
  5647.6  783.77  5697.7  789.53  5797.9  794.73  5908.6  797.94  5924.9  798.79
#Mann= 6 ,-1 , 0
  4081.6      .1       0  4553.4     .05       0  4736.4      .1       0
  4974.5     .07       0  4993.1      .1       0  5908.6     .05       0
Bank Sta=4957.76,5280.01
XS Rating Curve= 0 ,0
Exp/Cntr=0.3,0.1

Type RM Length L Ch R = 1 ,109501  ,461,461,461
BEGIN DESCRIPTION:
CHACON CREEK 144.0
END DESCRIPTION:
XS GIS Cut Line= 3
      1998424.98     13649224.98      1997660.64     13648584.44
      1997291.86     13648089.84
#Sta/Elev= 30
  3982.7   785.2    4061  782.66  4067.9  781.14  4115.9   777.6    4146  773.48
  4280.6  769.37  4472.5  767.19  4756.2  766.16  4856.3  766.93  4926.6  764.83
 4950.16762.9612  4961.7  761.59  4969.5  759.01    4980  758.61  4983.3  754.23
  5017.7  752.41  5020.2  751.61  5036.4  752.41  5083.3  755.24  5118.8  755.96
  5262.7   755.8 5331.85762.9608  5383.6  770.09  5412.8  776.83  5433.6   783.1
  5440.8  784.03  5519.1  789.43  5579.4  791.14  5595.7  791.47  5596.9   791.5
#Mann= 7 ,-1 , 0
  3982.7      .1       0  4115.9     .05       0  4280.6      .1       0
  5017.7     .07       0  5036.4      .1       0  5579.4     .16       0
  5595.7      .1       0
Bank Sta=4950.16,5331.85
XS Rating Curve= 0 ,0
Exp/Cntr=0.3,0.1

Type RM Length L Ch R = 1 ,109040  ,523,523,523
BEGIN DESCRIPTION:
CHACON CREEK 143.0
END DESCRIPTION:
XS GIS Cut Line= 3
      1998524.38     13648818.83        1997675.       13648175.
      1997475.02     13647825.03
#Sta/Elev= 30
  3885.4  783.72  3995.3  778.36  4066.2  777.68  4086.9  777.48  4095.2  776.32
  4151.4  774.26  4159.7  772.85  4203.1   771.1  4417.9  765.95  4643.5762.4044
  4687.7  763.11  4773.3  762.37  4929.4  754.17  4937.7   752.4  4974.3  750.45
  4977.1   749.6  4979.6   748.8  4993.3   748.8  4995.8   749.6  5002.3  752.83
  5018.2  751.91  5039.8  754.92  5045.5  757.52 5061.94762.4045  5098.8  773.41
  5104.5  777.03  5126.1  781.02  5170.1  785.58  5250.7  792.06  5354.3  797.92
#Mann= 5 ,-1 , 0
  3885.4      .1       0  4066.2     .05       0  4203.1      .1       0
  4977.1     .07       0  4995.8      .1       0
Bank Sta=4643.5,5061.94
XS Rating Curve= 0 ,0
Exp/Cntr=0.3,0.1

Type RM Length L Ch R = 1 ,108517  ,521,521,521
BEGIN DESCRIPTION:
CHACON CREEK 142.0
END DESCRIPTION:
XS GIS Cut Line= 3
      1998525.01     13648375.01        1998025.       13647775.
      1997674.96     13647574.98
#Sta/Elev= 30
  4217.6  778.31  4295.7  774.94  4322.5  772.24  4409.6  769.65  4508.5  768.12
  4580.1  765.58  4629.6  762.24 4666.93761.4536  4800.1  758.16  4884.7  758.13
  4906.9  755.52  4942.6  752.93  4956.3  752.41  4977.2  753.19    4985  752.55
    4986  749.58  4988.5  748.78  5002.2  748.78  5004.7  749.58  5028.2   750.5
  5035.9   752.2    5044  753.27  5056.2  757.64  5065.6  758.58  5071.3  761.16
    5074761.4536  5173.6  777.01  5309.5  792.83    5329  795.22  5401.8  798.62
#Mann= 7 ,-1 , 0
  4217.6     .05       0  4322.5      .1       0  4942.6     .16       0
    4986     .07       0  5004.7     .16       0  5035.9      .1       0
  5309.5     .05       0
Bank Sta=4666.93,5074
XS Rating Curve= 0 ,0
Exp/Cntr=0.3,0.1

Type RM Length L Ch R = 1 ,107996  ,521,521,521
BEGIN DESCRIPTION:
CHACON CREEK 141.0
END DESCRIPTION:
XS GIS Cut Line= 3
      1998914.97     13648289.29        1998525.       13647675.
      1998224.99     13647374.99
#Sta/Elev= 30
    4270  776.64  4283.3  776.47  4301.3  775.62  4316.6  774.08    4353  771.71
  4504.6  769.94  4598.6  767.84  4713.8  761.84 4773.29760.2931  4859.5  758.66
    4890  757.17  4932.4  754.16  4947.6  752.32  4953.6  752.28  4962.1  750.38
  4974.7  749.47  4977.2  748.67  4990.9  748.67  4993.4  749.47  5025.9  750.73
    5040  752.44  5068.3  754.78  5082.5  758.36 5087.97760.2921  5124.9  774.88
    5139  779.13  5181.5  787.26  5195.6  788.64    5238  789.89  5421.9  793.03
#Mann= 4 ,-1 , 0
    4270     .05       0  4283.3      .1       0  4974.7     .07       0
  4993.4      .1       0
Bank Sta=4773.29,5087.97
XS Rating Curve= 0 ,0
Exp/Cntr=0.3,0.1

Type RM Length L Ch R = 1 ,107475  ,336,336,336
BEGIN DESCRIPTION:
CHACON CREEK 140.0
END DESCRIPTION:
XS GIS Cut Line= 3
        1999225.     13648175.01        1999025.       13647525.
        1998675.       13647325.
#Sta/Elev= 30
  4314.6  775.75  4401.6  772.22    4467  766.92  4673.6  763.17 4793.62759.2698
  4912.9  752.77  4940.4  753.14  4952.8   752.5  4973.1   749.8    4999  749.51
  5001.5  748.71  5015.2  748.71  5017.7  749.51    5040   749.8  5045.8  750.96
  5067.4  753.17  5083.2  754.06  5110.6  757.44  5120.7  758.04 5127.33759.2703
  5163.9  764.46  5169.6   766.2  5185.4  767.02  5191.2  768.19  5201.3  768.48
  5228.6  771.14  5244.5  771.32  5294.1  774.46  5325.1  775.56  5397.8  777.02
#Mann= 3 ,-1 , 0
  4314.6      .1       0    4999     .07       0  5017.7      .1       0
Bank Sta=4793.62,5127.33
XS Rating Curve= 0 ,0
Exp/Cntr=0.3,0.1

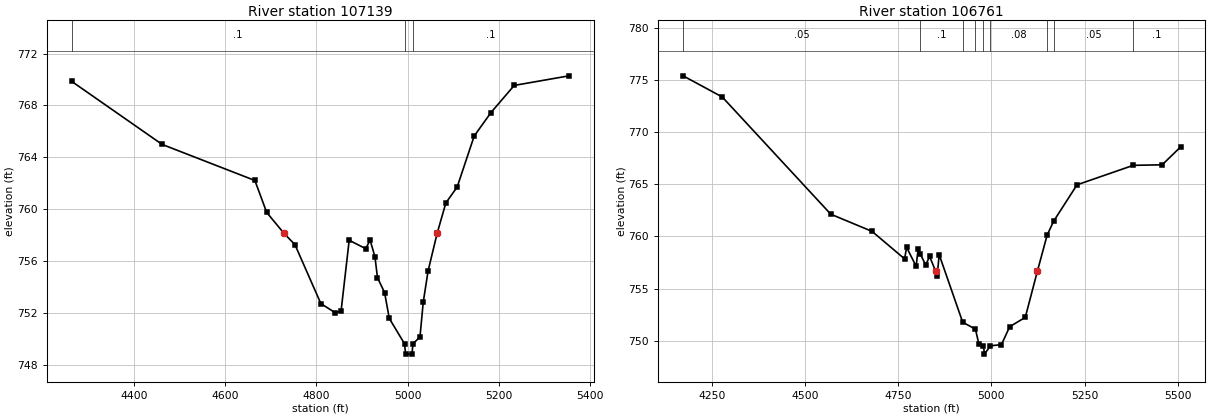
Type RM Length L Ch R = 1 ,107139  ,378,378,378
BEGIN DESCRIPTION:
Mapping XS 1e663800
END DESCRIPTION:
XS GIS Cut Line= 2
      1999561.69      13648072.3      1999201.44     13647043.66
#Sta/Elev= 30
  4263.5  769.86    4462  764.99  4665.2  762.21    4691  759.75 4729.16 758.125
    4753  757.26  4809.7  752.72  4840.8  752.02    4854  752.13  4871.8   757.6
  4908.1  756.95  4917.6  757.62  4928.2  756.33  4933.8  754.72  4949.4  753.56
  4959.6  751.58    4993  749.62  4995.5  748.82  5009.2  748.82  5011.7  749.62
  5026.9  750.15  5034.1  752.84  5044.7  755.24 5064.43758.1246  5083.6  760.48
  5108.3   761.7  5145.7  765.64  5182.5  767.45  5233.4  769.54  5353.4  770.28
#Mann= 3 ,-1 , 0
  4263.5      .1       0    4993     .07       0  5011.7      .1       0
Bank Sta=4729.16,5064.43
XS Rating Curve= 0 ,0
Exp/Cntr=0.3,0.1

Type RM Length L Ch R = 1 ,106761  ,96,96,96
BEGIN DESCRIPTION:
Mapping XS 6791bdb5
END DESCRIPTION:
XS GIS Cut Line= 6
      1999787.37     13648167.74      1999796.05     13647829.23
      1999674.53     13647486.35      1999709.25     13647278.01
      1999609.42     13647052.32       1999435.8      13647039.3
#Sta/Elev= 30
  4172.9  775.42    4278  773.39  4569.1  762.14  4679.9  760.49  4767.2  757.85
  4772.5  758.96  4798.1  757.14  4803.4  758.76  4809.8  758.28  4823.7  757.27
  4834.3  758.08 4850.24756.6849  4854.6  756.24  4859.9  758.26    4923  751.77
  4957.1  751.11  4966.1  749.73  4978.8  749.51  4981.3  748.71  4997.5  749.51
    5027  749.62    5049  751.34  5090.9  752.24 5123.49756.6855  5149.5  760.13
    5167  761.47  5229.7  764.96  5380.6  766.83  5458.1  766.88  5507.4  768.59
#Mann= 9 ,-1 , 0
  4172.9     .05       0  4809.8      .1       0    4923     .05       0
  4957.1     .08       0  4978.8     .07       0  4997.5     .08       0
  5149.5      .1       0    5167     .05       0  5380.6      .1       0
Bank Sta=4850.24,5123.49
XS Rating Curve= 0 ,0
Exp/Cntr=0.3,0.1