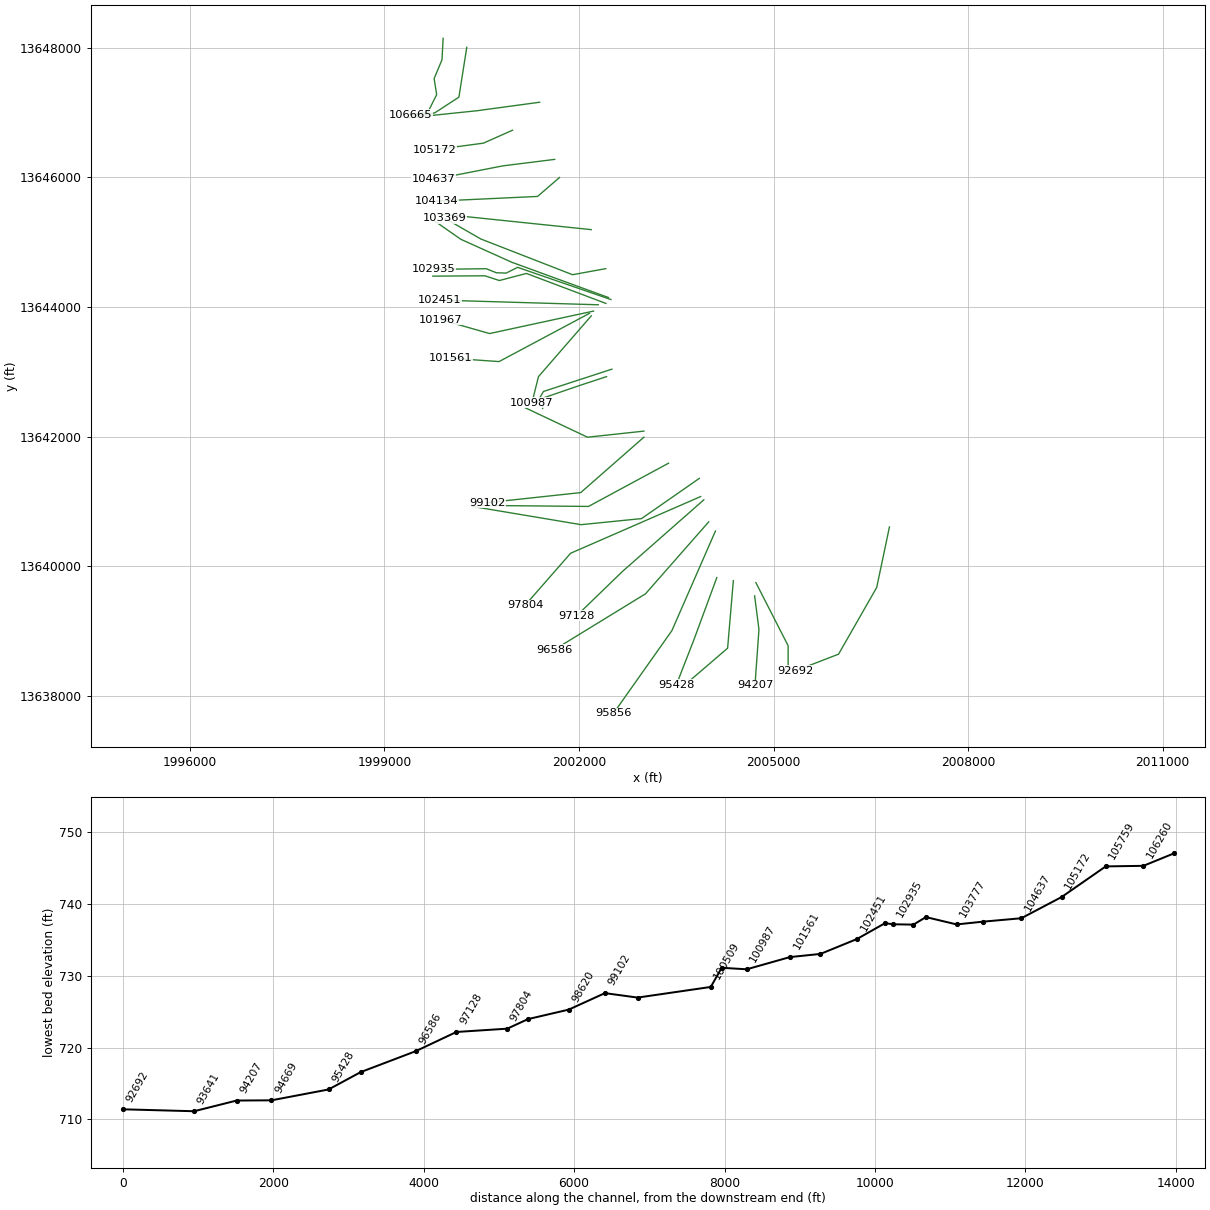
HEC-RAS study CHACON CREEK.prj: CHACON CREEK Base Level Engineering

--- CHACON CREEK.g01 (geometry) --- (continued)

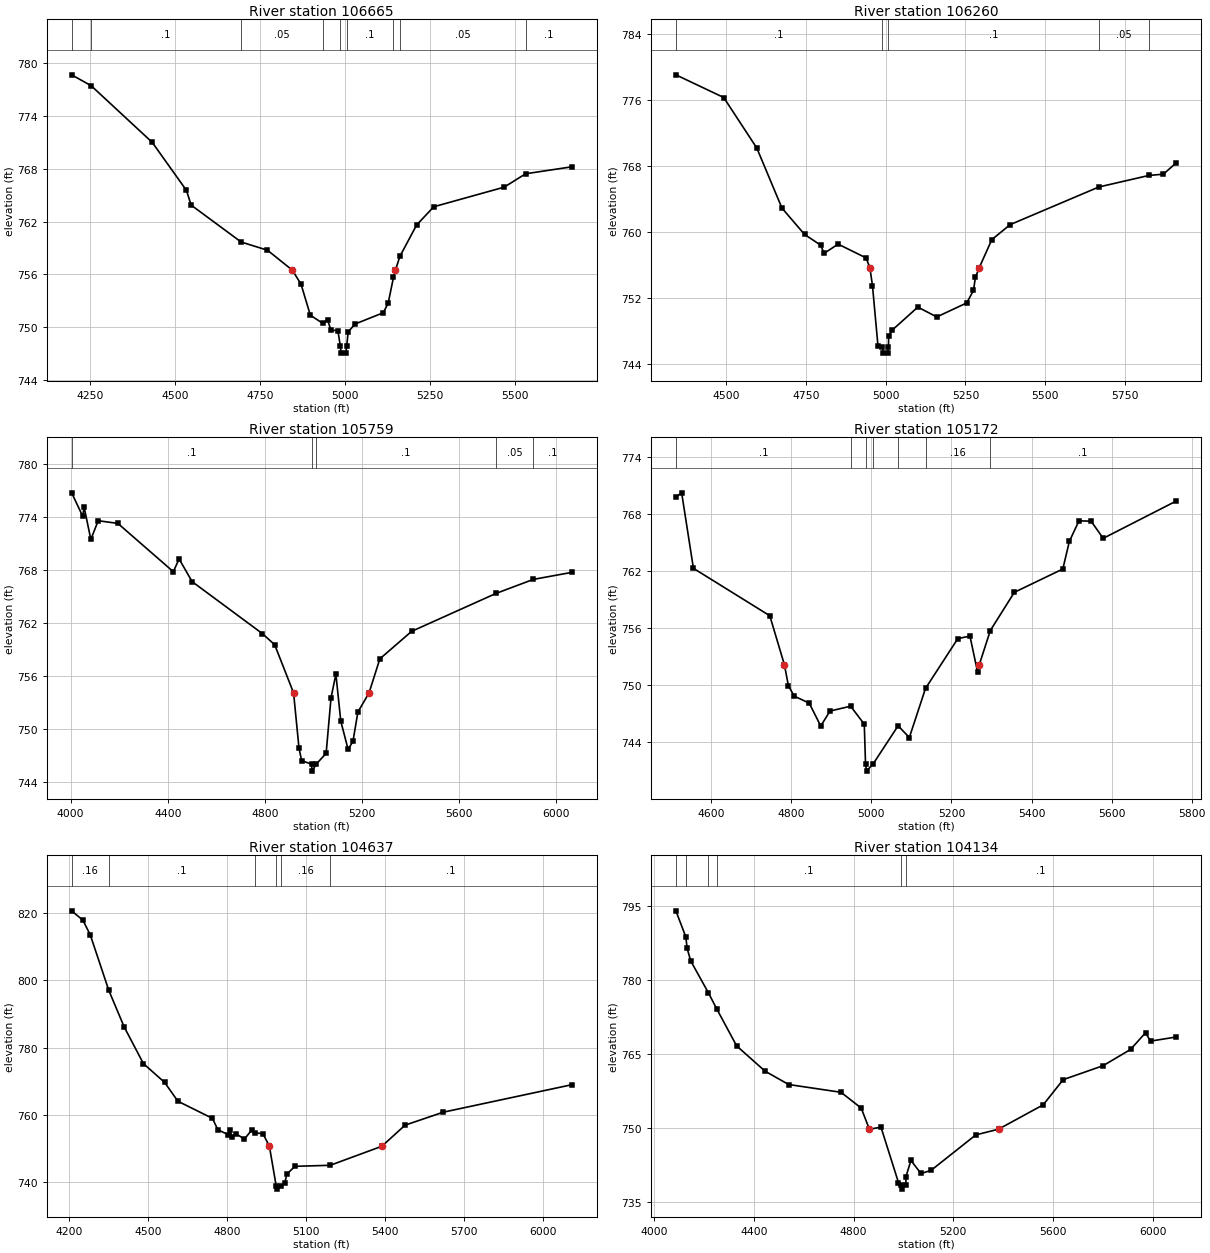
Type RM Length L Ch R = 1 ,106665  ,405,405,405
BEGIN DESCRIPTION:
Mapping XS 09be6367
END DESCRIPTION:
XS GIS Cut Line= 6
      1999904.56     13648141.77       1999887.2     13647811.87
      1999765.67     13647521.07      1999804.73     13647273.67
      1999670.19     13647004.58       1999398.4     13646965.75
#Sta/Elev= 30
    4196   778.7  4253.4  777.46  4433.1  771.02  4533.8  765.56  4547.5  763.89
  4694.8  759.69  4772.2  758.76 4845.47 756.487  4871.1  754.88  4898.3  751.37
  4934.4  750.46  4948.9  750.85    4959  749.66  4979.3  749.63  4986.6  747.86
  4989.1  747.06  5002.8  747.06  5005.3  747.86  5009.7  749.48  5029.9  750.37
  5112.9  751.65  5127.3  752.73    5143  755.68 5148.65756.4866  5161.7  758.05
  5211.1  761.63  5261.5   763.7  5468.8  765.93  5531.7  767.45  5667.4  768.24
#Mann= 9 ,-1 , 0
    4196     .05       0  4253.4      .1       0  4694.8     .05       0
  4934.4      .1       0  4986.6     .07       0  5005.3      .1       0
    5143     .08       0  5161.7     .05       0  5531.7      .1       0
Bank Sta=4845.47,5148.65
XS Rating Curve= 0 ,0
Exp/Cntr=0.3,0.1

Type RM Length L Ch R = 1 ,106260  ,501,501,501
BEGIN DESCRIPTION:
Mapping XS b2927231
END DESCRIPTION:
XS GIS Cut Line= 4
      2000269.15     13648002.88      2000147.62     13647234.61
      1999774.35     13646991.55      1999435.84     13646943.82
#Sta/Elev= 30
  4343.6  779.08  4493.3  776.33  4596.9   770.2  4675.6  762.92  4746.4  759.72
    4797  758.42  4807.2  757.42  4851.4  758.55  4938.8  756.88 4950.75755.7118
    4959  753.49  4976.2  746.18  4990.1  746.13  4992.6  745.33  5006.4  745.33
  5008.9  746.13  5009.7  747.36  5019.8  748.09  5100.8  750.91  5160.3  749.72
    5254  751.42  5275.1  752.94  5281.1  754.52 5293.38755.7126  5332.4  759.09
  5389.7  760.91  5667.6  765.48  5824.5  766.88  5869.3  767.03  5908.7  768.37
#Mann= 5 ,-1 , 0
  4343.6      .1       0  4990.1     .07       0  5008.9      .1       0
  5667.6     .05       0  5824.5      .1       0
Bank Sta=4950.75,5293.38
XS Rating Curve= 0 ,0
Exp/Cntr=0.3,0.1

Type RM Length L Ch R = 1 ,105759  ,587,587,587
BEGIN DESCRIPTION:
CHACON CREEK 138.0
END DESCRIPTION:
XS GIS Cut Line= 3
      2001393.23     13647156.48        2000425.       13647025.
      1999349.48     13646913.48
#Sta/Elev= 30
  4004.7  776.77  4050.6  774.09  4055.6   775.2  4083.6  771.49  4113.9  773.61
  4194.7  773.31  4423.1  767.84    4447  769.28  4500.6  766.71  4790.1  760.82
  4840.5  759.56 4918.17754.1123  4940.5  747.86  4951.5  746.43  4992.1  746.05
  4994.6  745.25  5011.7  746.05  5052.2  747.26  5072.3  753.54  5092.4  756.24
  5112.5  750.92  5142.7   747.7  5162.8  748.64  5182.9  751.94 5228.86754.1126
  5273.4  757.97  5404.1  761.08    5751  765.37  5904.4  766.96  6063.1  767.76
#Mann= 5 ,-1 , 0
  4004.7      .1       0  4992.1     .07       0  5011.7      .1       0
    5751     .05       0  5904.4      .1       0
Bank Sta=4918.17,5228.86
XS Rating Curve= 0 ,0
Exp/Cntr=0.3,0.1

Type RM Length L Ch R = 1 ,105172  ,535,535,535
BEGIN DESCRIPTION:
CHACON CREEK 137.0
END DESCRIPTION:
XS GIS Cut Line= 3
        2000975.       13646725.        2000525.       13646525.
      1999774.98       13646425.
#Sta/Elev= 30
  4511.6  769.79    4526  770.21  4555.4  762.28  4746.2   757.3 4782.64752.1597
  4792.7  749.95  4807.1  748.86  4844.7  748.12  4873.4  745.72  4896.7  747.29
  4948.1   747.8  4982.2  745.91  4985.3  741.78  4987.8  740.98    5005  741.78
  5066.7  745.74  5094.8  744.51  5135.2  749.67  5215.9   754.9  5246.2  755.16
  5265.1  751.42  5269.5752.1592  5297.1  755.75  5357.1  759.76  5478.2  762.21
  5494.6  765.12  5518.6  767.27  5548.8  767.23  5579.1  765.43  5760.7  769.33
#Mann= 7 ,-1 , 0
  4511.6      .1       0  4948.1     .16       0  4985.3     .07       0
    5005     .16       0  5066.7      .1       0  5135.2     .16       0
  5297.1      .1       0
Bank Sta=4782.64,5269.5
XS Rating Curve= 0 ,0
Exp/Cntr=0.3,0.1

Type RM Length L Ch R = 1 ,104637  ,503,503,503
BEGIN DESCRIPTION:
CHACON CREEK 136.0
END DESCRIPTION:
XS GIS Cut Line= 3
      2001625.01       13646275.        2000825.       13646175.
      1999754.59     13645965.83
#Sta/Elev= 30
  4210.2  820.57    4253  817.76  4280.8  813.43    4351  796.99  4409.3  786.15
  4482.3  775.27  4562.9  769.67  4613.3  764.09  4744.3  759.02  4764.5  755.67
  4804.8  754.13  4812.4  755.45  4817.4   753.5    4835  754.43  4865.3  752.83
    4893  755.56  4907.3   754.7  4935.8  754.49 4960.27750.7388  4986.4  738.83
  4988.9  738.03  5006.1  738.83    5019  739.95  5026.6   742.5  5057.2  744.79
    5191   745.1 5386.88750.7407    5475     757  5619.4  760.84  6107.1  768.99
#Mann= 6 ,-1 , 0
  4210.2     .16       0    4351      .1       0  4907.3     .16       0
  4986.4     .07       0  5006.1     .16       0    5191      .1       0
Bank Sta=4960.27,5386.88
XS Rating Curve= 0 ,0
Exp/Cntr=0.3,0.1

Type RM Length L Ch R = 1 ,104134  ,357,357,357
BEGIN DESCRIPTION:
Mapping XS 323d9dfd
END DESCRIPTION:
XS GIS Cut Line= 3
      2001699.07     13645995.36      2001360.51     13645703.68
       1999803.2     13645630.76
#Sta/Elev= 30
  4087.3  794.01  4127.2  788.71  4132.5  786.38  4146.8  783.85  4217.4  777.41
  4250.6  774.17  4331.1  766.61  4445.2  761.48  4539.7  758.78  4749.9   757.2
  4830.8  753.99 4863.49749.7172  4910.1  750.12  4980.2   738.9  4990.4  738.36
  4992.9  737.56  5010.1  738.36  5010.2  740.09  5030.2  743.38  5070.3  740.74
  5110.3  741.34  5290.5  748.56 5381.57749.7172  5560.8  754.66  5640.9  759.76
  5801.1   762.6  5911.2  765.89  5971.3  769.28  5991.3  767.58  6093.2  768.41
#Mann= 6 ,-1 , 0
  4087.3     .16       0  4127.2      .1       0  4217.4     .16       0
  4250.6      .1       0  4990.4     .07       0  5010.1      .1       0
Bank Sta=4863.49,5381.57
XS Rating Curve= 0 ,0
Exp/Cntr=0.3,0.1

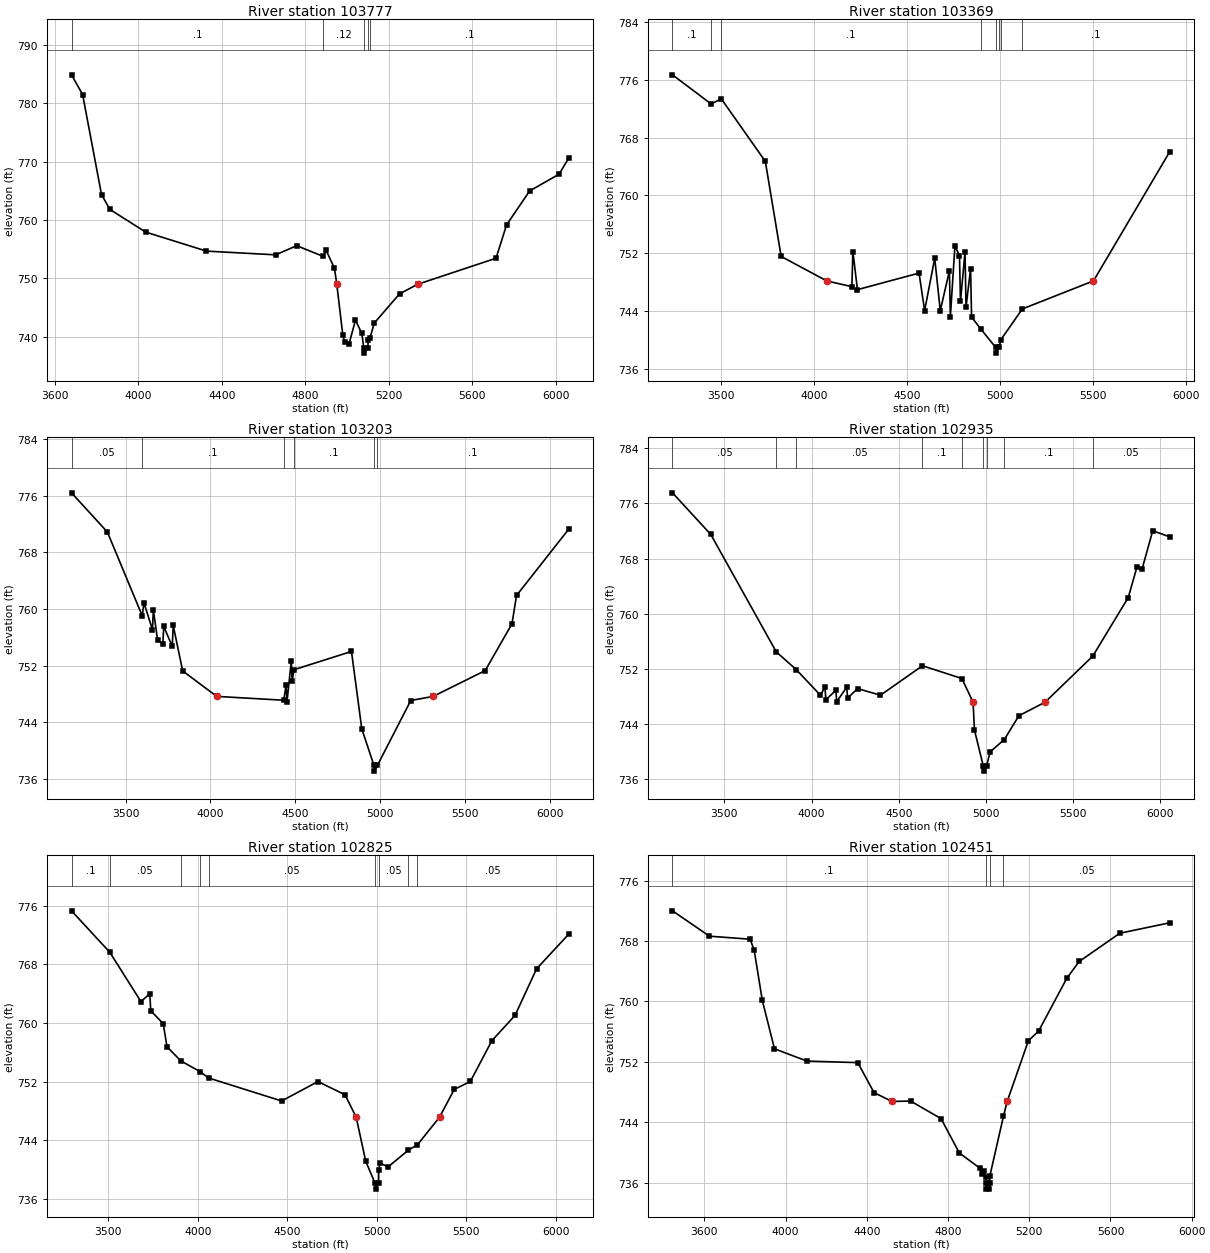
Type RM Length L Ch R = 1 ,103777  ,408,408,408
BEGIN DESCRIPTION:
Mapping XS 5ff62e7c
END DESCRIPTION:
XS GIS Cut Line= 2
      2002187.91     13645191.68      1999819.39       13645438.
#Sta/Elev= 30
  3679.9  784.91  3733.1  781.53  3823.6  764.36  3863.8  761.82  4034.7  757.94
  4326.3  754.67  4658.1  754.03  4758.6   755.6  4886.9  753.75  4899.4  754.82
  4939.6  751.73 4950.68748.9813  4979.8   740.2  4989.8  739.03  5009.9  738.81
  5040.1  742.82  5070.3  740.58  5080.5  737.97    5083  737.17  5100.2  737.97
  5100.4  739.41  5109.6  739.78  5130.6  742.34  5251.2  747.33 5338.15748.9813
  5713.7  753.45    5764  759.17  5874.6  764.99  6015.3  767.86  6061.2  770.58
#Mann= 5 ,-1 , 0
  3679.9      .1       0  4886.9     .12       0  5080.5     .07       0
  5100.2     .12       0  5109.6      .1       0
Bank Sta=4950.68,5338.15
XS Rating Curve= 0 ,0
Exp/Cntr=0.3,0.1

Type RM Length L Ch R = 1 ,103369  ,166,166,166
BEGIN DESCRIPTION:
Mapping XS 385b225a
END DESCRIPTION:
XS GIS Cut Line= 4
       2002411.8     13644590.11      2001900.42     13644496.36
      2000485.51     13645047.43      1999933.44     13645365.13
#Sta/Elev= 30
  3237.9  776.68  3445.4  772.66    3501  773.35  3737.6  764.71  3822.8  751.56
 4068.15748.1792  4203.5  747.38  4208.8  752.24  4233.4  746.97    4565  749.26
  4594.9  744.07  4649.3  751.31  4679.2  744.06  4728.2  749.57  4733.5  743.21
  4758.1  753.02  4782.6  751.68  4787.9  745.34  4812.4  752.18  4817.8  744.57
  4842.3  749.83  4847.7  743.18  4897.2  741.53  4977.1  738.99  4979.6  738.19
  4996.9  738.99  5004.1     740  5120.8   744.3  5503.8  748.18  5913.2     766
#Mann= 8 ,-1 , 0
  3237.9      .1       0  3445.4     .16       0    3501      .1       0
  4897.2     .12       0  4977.1     .07       0  4996.9     .12       0
  5004.1     .16       0  5120.8      .1       0
Bank Sta=4068.15,5503.8
XS Rating Curve= 0 ,0
Exp/Cntr=0.3,0.1

Type RM Length L Ch R = 1 ,103203  ,268,268,268
BEGIN DESCRIPTION:
Mapping XS bc4395f0
END DESCRIPTION:
XS GIS Cut Line= 4
      2002453.56     13644144.79      2000964.67     13644688.05
      2000178.21     13645042.22      1999782.39     13645318.26
#Sta/Elev= 30
  3181.3   776.4  3392.7  770.87  3598.5  759.03  3607.9  760.92  3658.4  757.09
  3663.7  759.86  3688.9   755.6  3719.5  755.06  3724.8  757.55  3775.3  754.74
  3780.6   757.7  3836.4  751.28 4037.11 747.684  4432.3  747.14  4446.1  749.28
  4451.4  746.92  4476.6  752.64    4482  749.82  4492.5  751.45  4831.6  754.02
  4892.3  743.09  4964.3  737.94  4966.8  737.14  4984.1  737.94    5181   747.1
 5313.18747.6839  5619.6  751.32  5777.5  757.92  5804.5  761.92  6111.3  771.25
#Mann= 6 ,-1 , 0
  3181.3     .05       0  3598.5      .1       0  4432.3     .05       0
  4492.5      .1       0  4964.3     .07       0  4984.1      .1       0
Bank Sta=4037.11,5313.18
XS Rating Curve= 0 ,0
Exp/Cntr=0.3,0.1

Type RM Length L Ch R = 1 ,102935  ,110,110,110
BEGIN DESCRIPTION:
Mapping XS afe08db5
END DESCRIPTION:
XS GIS Cut Line= 6
      2002492.57     13644113.56      2001053.21     13644609.93
      2000876.13     13644521.39      2000725.09      13644526.6
      2000568.84      13644589.1      1999758.15      13644578.7
#Sta/Elev= 30
  3202.3  777.52  3421.9  771.49  3797.5  754.48  3913.3  751.87  4050.8  748.19
  4076.7  749.38    4082  747.54  4139.1  748.89  4144.4  747.27  4201.5  749.34
  4206.8  747.78  4263.9  749.15    4395  748.19    4636  752.46  4861.9  750.61
 4926.25747.1785    4934  743.16  4984.1  737.99  4986.6  737.19  5003.9  737.99
    5024  739.99  5105.2  741.76    5189  745.22 5339.25747.1808  5612.7  753.86
  5816.1  762.35  5866.1  766.77  5896.1  766.54  5956.5  772.02    6053  771.15
#Mann= 9 ,-1 , 0
  3202.3     .05       0  3797.5      .1       0  3913.3     .05       0
    4636      .1       0  4861.9     .05       0  4984.1     .04       0
  5003.9     .05       0  5105.2      .1       0  5612.7     .05       0
Bank Sta=4926.25,5339.25
XS Rating Curve= 0 ,0
Exp/Cntr=0.3,0.1

Type RM Length L Ch R = 1 ,102825  ,374,374,374
BEGIN DESCRIPTION:
Mapping XS bd99392a
END DESCRIPTION:
XS GIS Cut Line= 5
      2002414.48     13644053.65      2001188.63     13644516.18
      2000771.96      13644406.8      2000548.01     13644479.72
      1999745.94     13644474.51
#Sta/Elev= 30
  3294.5  775.29  3508.4  769.64  3682.4  762.92  3732.1  763.96  3737.4  761.67
    3807   759.9  3828.4  756.75  3905.4  754.83  4011.9  753.38  4060.5   752.5
  4469.1  749.36    4672  752.01  4823.2  750.21 4885.62747.1557  4939.1  741.14
  4991.4  738.14  4993.9  737.34  5011.2  738.14  5011.7  739.99  5019.9  740.89
  5063.8  740.36  5177.5  742.66  5228.4  743.39 5351.69747.1561    5434  750.94
    5524  752.02    5644  757.57    5774  761.04    5894  767.38  6073.1  772.09
#Mann= 9 ,-1 , 0
  3294.5      .1       0  3508.4     .05       0  3905.4     .08       0
  4011.9      .1       0  4060.5     .05       0  4991.4     .04       0
  5011.2     .05       0  5177.5      .1       0  5228.4     .05       0
Bank Sta=4885.62,5351.69
XS Rating Curve= 0 ,0
Exp/Cntr=0.3,0.1

Type RM Length L Ch R = 1 ,102451  ,484,484,484
BEGIN DESCRIPTION:
Mapping XS 5aef5992
END DESCRIPTION:
XS GIS Cut Line= 2
      2002297.23     13644032.83      1999850.08     13644104.72
#Sta/Elev= 30
  3442.9     772  3625.2  768.64  3825.3  768.24  3845.3  766.79  3885.3  760.13
  3945.3  753.72  4105.4  752.09  4355.5  751.89  4435.6  747.92 4523.92746.7434
  4615.6   746.8  4765.7  744.47  4855.7  739.92  4955.8  737.93  4965.8  737.11
  4975.8  737.49  4985.8  736.79  4985.9  735.93  4988.4  735.13  5003.2  735.13
  5005.7  735.93  5005.8  736.85  5072.9  744.77 5091.26746.7432  5195.9  754.79
  5245.9  756.06  5385.4  763.08    5446  765.29  5646.1  769.03  5891.1  770.41
#Mann= 4 ,-1 , 0
  3442.9      .1       0  4985.9     .07       0  5005.7      .1       0
  5072.9     .05       0
Bank Sta=4523.92,5091.26
XS Rating Curve= 0 ,0
Exp/Cntr=0.3,0.1

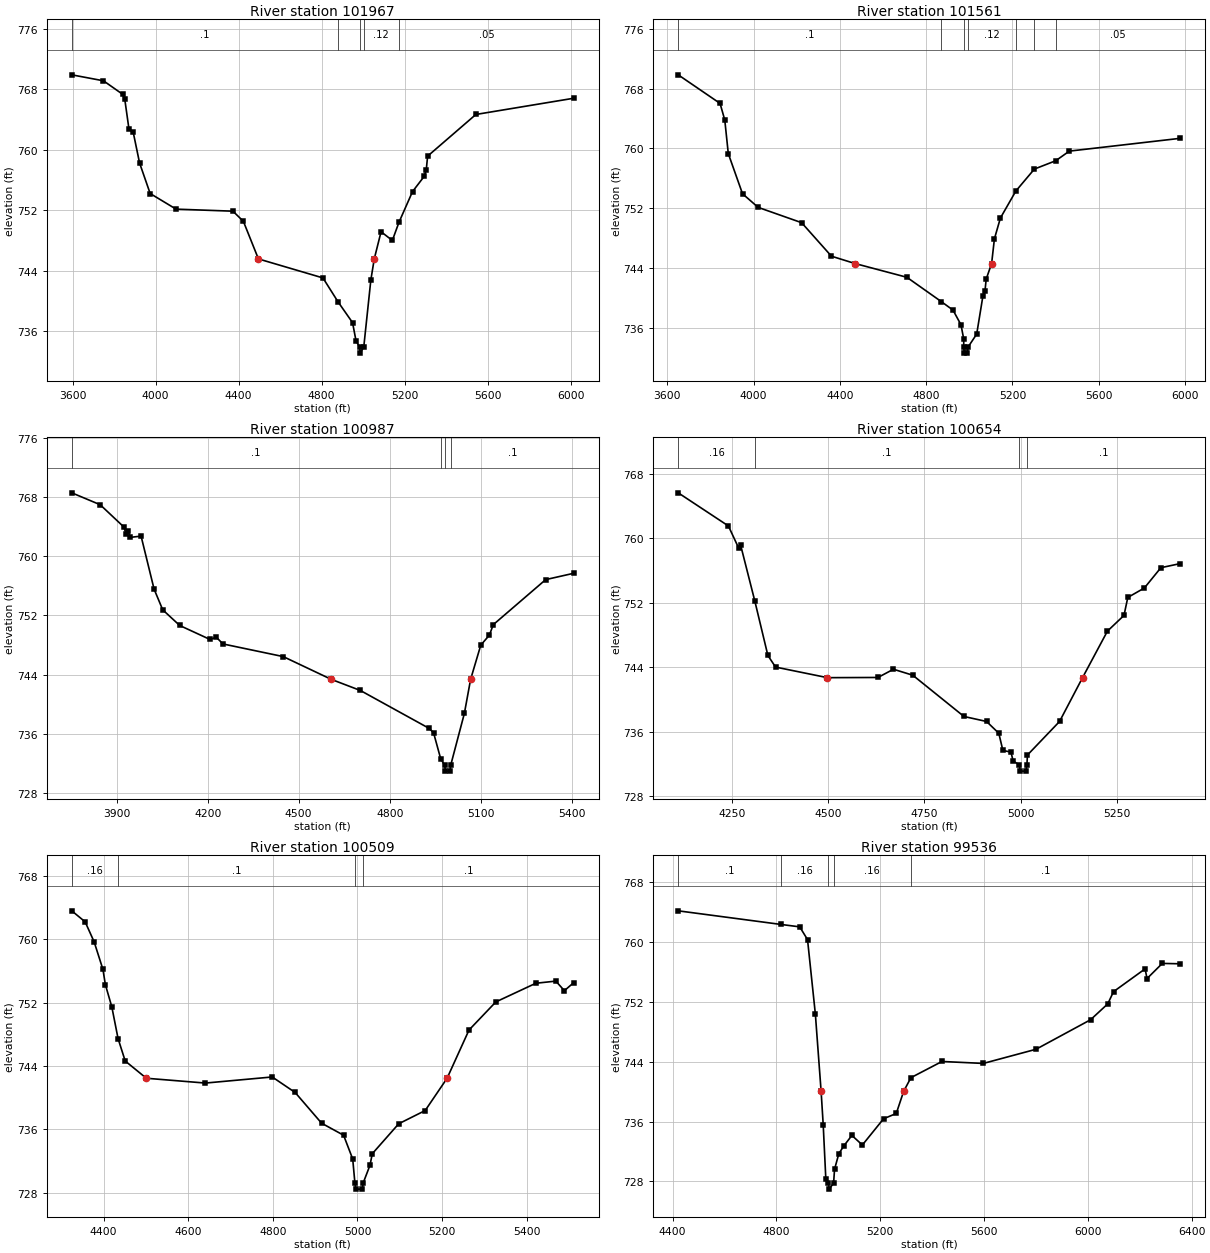
Type RM Length L Ch R = 1 ,101967  ,406,406,406
BEGIN DESCRIPTION:
Mapping XS 84fae4c3
END DESCRIPTION:
XS GIS Cut Line= 3
      2002224.39     13643935.61      2000620.92      13643589.1
      1999870.91     13643802.64
#Sta/Elev= 30
  3595.5  769.92  3748.3  769.13  3840.4  767.35  3850.6  766.77  3871.1  762.76
  3891.6  762.33  3922.3  758.25  3973.4   754.2  4098.4  752.13  4372.4  751.86
  4422.7  750.52 4495.31 745.538  4806.4  743.02  4879.2  739.85  4949.1   737.1
  4965.8  734.69  4983.3  733.86  4985.8  733.06  5003.1  733.86  5037.3  742.75
 5053.73745.5386  5086.6  749.14  5140.9  747.98  5172.6  750.37  5238.1  754.45
  5294.1  756.46  5304.5  757.35    5311  759.15  5543.7  764.67  6015.8  766.82
#Mann= 5 ,-1 , 0
  3595.5      .1       0  4879.2     .12       0  4983.3     .07       0
  5003.1     .12       0  5172.6     .05       0
Bank Sta=4495.31,5053.73
XS Rating Curve= 0 ,0
Exp/Cntr=0.3,0.1

Type RM Length L Ch R = 1 ,101561  ,574,574,574
BEGIN DESCRIPTION:
Mapping XS c80c9af6
END DESCRIPTION:
XS GIS Cut Line= 3
      2002161.88     13643900.89      2000766.76      13643156.8
      2000021.92     13643208.89
#Sta/Elev= 30
  3650.1  769.83  3844.1  766.01    3866  763.79  3882.3   759.3  3948.2  753.93
  4020.6  752.11  4222.3  750.06  4360.6  745.58 4469.66744.6017  4710.4  742.76
  4870.4   739.5  4924.3  738.37  4961.2  736.41  4973.9  734.51    4974  733.42
  4976.5  732.62  4991.3  732.62  4993.8  733.42  5034.1  735.17  5063.2  740.31
  5072.3  740.87    5078  742.51 5103.24744.6015  5116.2   747.9  5143.9  750.68
  5215.8   754.3  5301.5  757.23  5400.3  758.34  5463.6  759.63  5977.9  761.34
#Mann= 7 ,-1 , 0
  3650.1      .1       0  4870.4     .12       0    4974     .07       0
  4993.8     .12       0  5215.8     .05       0  5301.5      .1       0
  5400.3     .05       0
Bank Sta=4469.66,5103.24
XS Rating Curve= 0 ,0
Exp/Cntr=0.3,0.1

Type RM Length L Ch R = 1 ,100987  ,333,333,333
BEGIN DESCRIPTION:
CHACON CREEK 129.0
END DESCRIPTION:
XS GIS Cut Line= 3
      2002189.62     13643862.68        2001375.       13642925.
      2001275.01     13642525.03
#Sta/Elev= 30
  3752.3   768.6  3845.9  766.99  3923.8  763.98  3931.4  763.03    3938   763.4
  3945.6  762.57  3980.7  762.74  4023.5  755.57    4052  752.76    4108  750.64
  4207.7  748.75  4228.6  749.05  4250.4  748.14  4448.9  746.43 4607.53743.3434
  4703.3  741.84  4930.3   736.7  4944.6   736.1    4968  732.59  4981.2  731.72
  4983.7  730.92  4998.5  730.92    5001  731.72    5046  738.73 5066.57743.3427
  5100.1  747.98  5128.4  749.33  5141.3  750.75    5314  756.85  5406.7  757.71
#Mann= 4 ,-1 , 0
  3752.3      .1       0    4968     .12       0  4981.2     .07       0
    5001      .1       0
Bank Sta=4607.53,5066.57
XS Rating Curve= 0 ,0
Exp/Cntr=0.3,0.1

Type RM Length L Ch R = 1 ,100654  ,145,145,145
BEGIN DESCRIPTION:
Mapping XS 7e54f5e3
END DESCRIPTION:
XS GIS Cut Line= 3
      2002506.31     13643039.61      2001451.65     13642695.87
      2001353.67     13642528.27
#Sta/Elev= 30
  4110.8  765.66  4241.1  761.55  4267.8   758.8    4273  759.14  4309.5  752.27
  4343.6  745.48  4363.5  744.04 4498.19742.7262  4629.3  742.75  4669.6  743.77
  4719.8  743.03  4852.7  737.91  4911.3  737.29  4943.1  735.83  4953.7  733.69
  4974.6   733.5  4980.4  732.37  4996.3  731.93  4998.8  731.13  5013.6  731.13
  5016.1  731.93  5017.5  733.13  5100.8  737.29 5160.48742.7261  5225.1   748.5
  5268.1  750.45    5278  752.68    5321  753.85  5363.9  756.37  5414.2  756.88
#Mann= 4 ,-1 , 0
  4110.8     .16       0  4309.5      .1       0  4996.3     .07       0
  5016.1      .1       0
Bank Sta=4498.19,5160.48
XS Rating Curve= 0 ,0
Exp/Cntr=0.3,0.1

Type RM Length L Ch R = 1 ,100509  ,973,973,973
BEGIN DESCRIPTION:
CHACON CREEK 128.0
END DESCRIPTION:
XS GIS Cut Line= 4
      2002424.98     13642924.99      2002006.34     13642787.01
      2001459.46     13642599.51      2001438.63     13642432.83
#Sta/Elev= 30
  4324.6  763.62  4356.2  762.23  4377.5   759.7  4398.3  756.21    4404   754.3
  4419.3  751.48    4434  747.49  4450.9  744.65 4500.93742.4677  4640.5  741.86
  4798.5  742.63  4852.7  740.67  4915.2  736.79  4967.2  735.27  4988.8  732.26
  4993.9  729.26  4996.4  728.46  5011.2  728.46  5013.7  729.26  5029.7  731.49
    5035  732.93  5097.6  736.72  5160.1  738.39  5211.9742.4683  5263.7  748.56
  5327.1  752.11  5421.7  754.47    5469  754.74  5489.2  753.53  5511.5  754.56
#Mann= 4 ,-1 , 0
  4324.6     .16       0    4434      .1       0  4993.9     .07       0
  5013.7      .1       0
Bank Sta=4500.93,5211.9
XS Rating Curve= 0 ,0
Exp/Cntr=0.3,0.1

Type RM Length L Ch R = 1 ,99536   ,434,434,434
BEGIN DESCRIPTION:
Mapping XS d2652c94
END DESCRIPTION:
XS GIS Cut Line= 3
      2003000.58      13642084.4      2002130.82     13641990.66
      2001172.44      13642443.8
#Sta/Elev= 30
  4421.3  764.13    4818  762.31  4889.6  761.99  4919.7  760.29  4949.9  750.34
 4972.06740.0239  4980.1  735.59  4990.2  728.34  5000.3  727.78  5002.8  726.98
  5020.2  727.78  5023.8  729.63  5040.4  731.72  5060.6   732.8  5090.7  734.15
    5131  732.87  5212.7  736.37  5261.7  737.08  5290.1740.0266  5318.2  741.86
  5437.9  744.02  5597.2  743.76  5800.3  745.65  6010.5  749.59  6076.8  751.71
    6099  753.34  6220.6  756.38  6228.2  755.09    6287  757.11  6356.2  757.06
#Mann= 5 ,-1 , 0
  4421.3      .1       0    4818     .16       0  5000.3     .07       0
  5020.2     .16       0  5318.2      .1       0
Bank Sta=4972.06,5290.1
XS Rating Curve= 0 ,0
Exp/Cntr=0.3,0.1

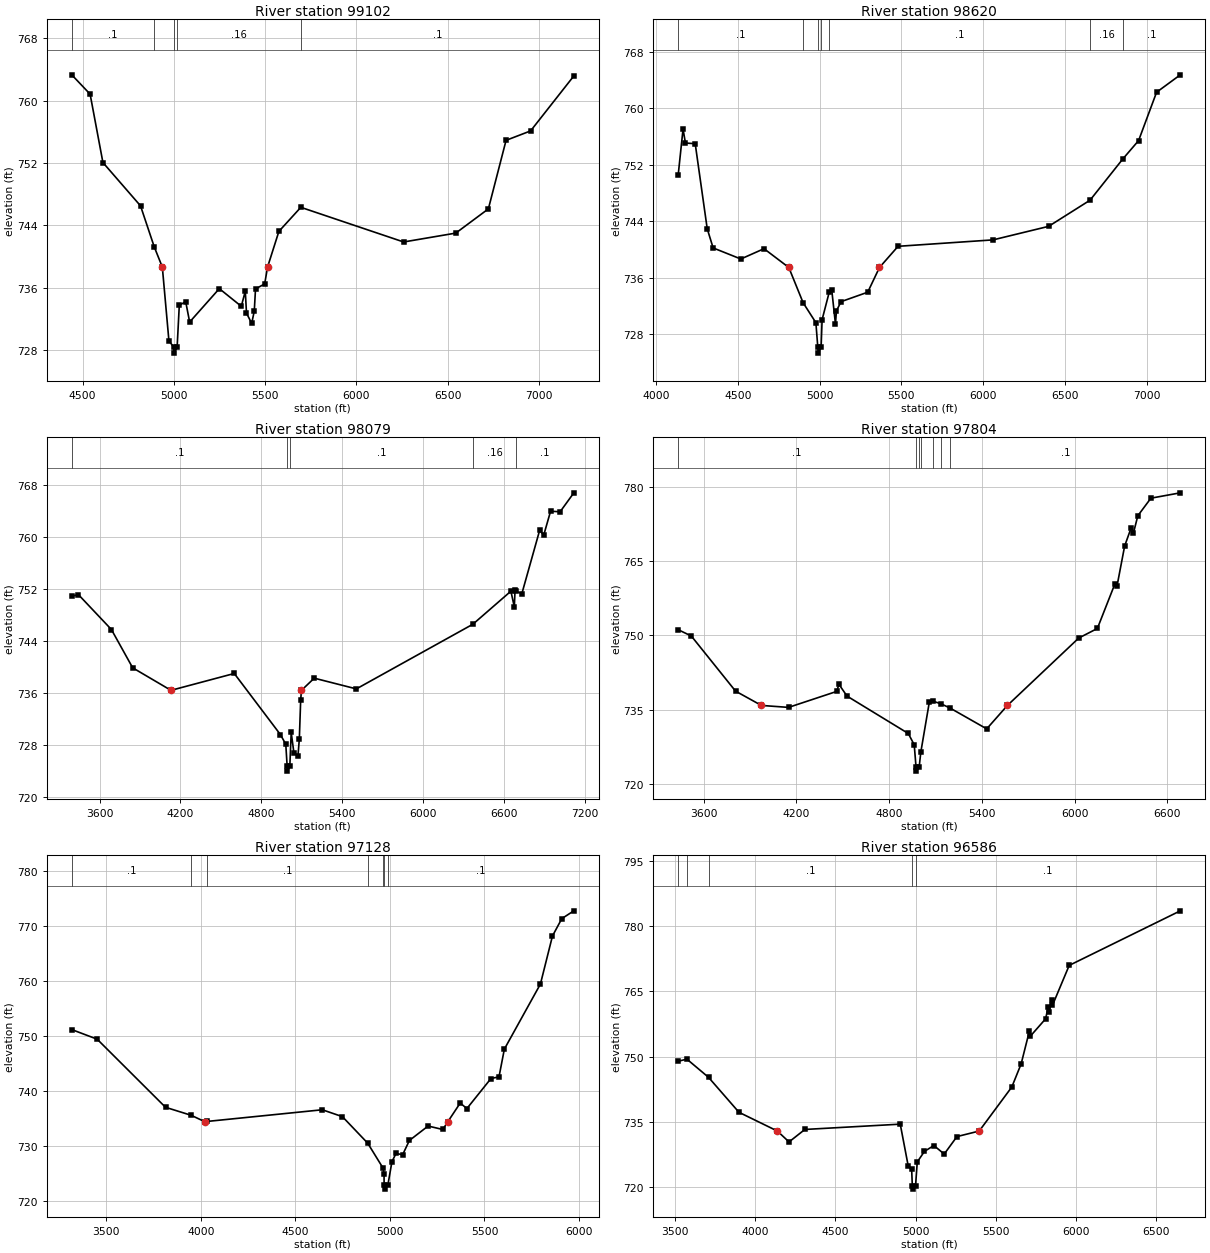
Type RM Length L Ch R = 1 ,99102   ,482,482,482
BEGIN DESCRIPTION:
Mapping XS f559ba59
END DESCRIPTION:
XS GIS Cut Line= 3
      2003000.58     13641990.64      2002026.65     13641136.49
      2000579.37     13640980.31
#Sta/Elev= 30
  4441.2  763.33  4541.7  760.85  4611.9  752.07  4817.9  746.51    4893  741.25
 4937.42 738.647  4973.5  729.19  4998.7   728.4  5001.2   727.6  5018.6   728.4
  5030.4  733.76  5065.6  734.19  5087.1  731.59  5249.7  735.88  5370.2  733.61
    5392  735.56  5398.6  732.73  5427.1  731.42  5441.3  733.01    5448  735.84
  5498.3  736.49 5513.95738.6473  5576.1  743.23  5696.3  746.32  6259.7  741.87
  6545.4  743.01    6724  746.12  6820.9  754.92  6955.3  756.13  7192.3  763.19
#Mann= 5 ,-1 , 0
  4441.2      .1       0    4893     .16       0  4998.7     .07       0
  5018.6     .16       0  5696.3      .1       0
Bank Sta=4937.42,5513.95
XS Rating Curve= 0 ,0
Exp/Cntr=0.3,0.1

Type RM Length L Ch R = 1 ,98620   ,541,541,541
BEGIN DESCRIPTION:
CHACON CREEK 125.0
END DESCRIPTION:
XS GIS Cut Line= 3
      2003380.83     13641589.62      2002146.44     13640922.95
      2000479.93     13640938.57
#Sta/Elev= 30
  4136.2  750.62  4165.6  757.08  4180.1   755.1    4240     755  4313.3  742.95
  4349.5  740.22  4518.9  738.65  4660.7  740.11 4812.28737.4449  4899.6  732.45
  4977.7  729.62  4989.6   726.1  4992.1   725.3  5009.5   726.1  5015.8  730.05
  5060.1  734.02  5074.8  734.24  5097.5  729.41  5103.3  731.29  5131.6   732.6
  5294.6  733.94 5366.39737.4449  5480.2  740.45  6060.6  741.36  6400.6  743.28
  6653.9  746.99  6854.3  752.84  6950.6  755.44  7060.6   762.3  7205.7  764.77
#Mann= 7 ,-1 , 0
  4136.2      .1       0  4899.6     .16       0  4989.6     .07       0
  5009.5     .16       0  5060.1      .1       0  6653.9     .16       0
  6854.3      .1       0
Bank Sta=4812.28,5366.39
XS Rating Curve= 0 ,0
Exp/Cntr=0.3,0.1

Type RM Length L Ch R = 1 ,98079   ,275,275,275
BEGIN DESCRIPTION:
CHACON CREEK 124.0
END DESCRIPTION:
XS GIS Cut Line= 4
      2003854.78     13641355.24      2002964.15     13640735.45
      2002031.86      13640641.7      2000354.73     13640922.96
#Sta/Elev= 30
  3394.1  750.88  3443.5  751.11  3687.9  745.75  3845.8  739.86 4129.86736.3989
  4598.9  738.99  4940.6  729.61  4980.8  728.12  4990.9  724.78  4993.4  723.98
    5011  724.78    5021  729.92  5041.1  726.81  5071.3  726.34  5081.3  728.91
  5091.4  734.96 5097.16736.4001  5191.9  738.27  5504.2  736.62    6368  746.56
    6650  751.64  6675.5   749.2  6680.5  751.79  6687.8  751.65  6731.1  751.25
  6862.9  760.98  6893.4  760.26  6944.1  763.93    7015  763.85  7116.7  766.76
#Mann= 5 ,-1 , 0
  3394.1      .1       0  4990.9     .07       0    5011      .1       0
    6368     .16       0  6687.8      .1       0
Bank Sta=4129.86,5097.16
XS Rating Curve= 0 ,0
Exp/Cntr=0.3,0.1

Type RM Length L Ch R = 1 ,97804   ,676,676,676
BEGIN DESCRIPTION:
CHACON CREEK 123.0
END DESCRIPTION:
XS GIS Cut Line= 3
      2003874.97     13641074.99      2001870.83     13640201.04
      2001170.84     13639401.05
#Sta/Elev= 30
  3435.4  751.16  3520.1  749.89  3806.3  738.78 3973.66735.8966  4149.2   735.5
  4460.9  738.72  4475.4  740.15  4527.7  737.78  4924.2  730.24  4962.7  727.96
  4974.5  723.45    4977  722.65  4994.6  723.45  5005.4  726.49  5060.9  736.65
  5082.8  736.76  5135.7  736.23  5196.9  735.33  5431.8  731.17 5565.95735.8962
  6027.4  749.48    6148  751.41  6260.9  760.36  6275.2  759.97  6324.5  768.03
  6367.2  771.75  6381.5  770.66  6409.9  774.14  6494.4  777.68  6684.8  778.76
#Mann= 7 ,-1 , 0
  3435.4      .1       0  4974.5     .07       0  4994.6      .1       0
  5005.4     .12       0  5082.8      .1       0  5135.7     .12       0
  5196.9      .1       0
Bank Sta=3973.66,5565.95
XS Rating Curve= 0 ,0
Exp/Cntr=0.3,0.1

Type RM Length L Ch R = 1 ,97128   ,542,542,542
BEGIN DESCRIPTION:
CHACON CREEK 122.0
END DESCRIPTION:
XS GIS Cut Line= 3
      2003924.98     13641024.98        2002675.       13639925.
      2001963.48     13639236.73
#Sta/Elev= 30
  3317.5  751.14  3451.7   749.4  3813.2  737.04  3948.7  735.59 4020.78734.4324
    4035  734.48  4642.4  736.59  4748.7  735.34  4882.4  730.53  4964.2  725.97
  4968.8   724.9  4969.2  722.99  4971.7  722.19  4989.3  722.99  5010.7  727.18
  5032.1  728.66  5067.3  728.44  5102.8  731.02  5201.9  733.64  5279.5  733.01
 5306.31 734.432  5371.6  737.81  5406.9  736.81  5534.2  742.26  5576.7  742.56
    5605  747.59  5795.8  759.41  5859.4  768.12    5909  771.28  5972.5  772.69
#Mann= 7 ,-1 , 0
  3317.5      .1       0  3948.7     .05       0    4035      .1       0
  4882.4     .07       0  4964.2      .1       0  4969.2     .07       0
  4989.3      .1       0
Bank Sta=4020.78,5306.31
XS Rating Curve= 0 ,0
Exp/Cntr=0.3,0.1

Type RM Length L Ch R = 1 ,96586   ,730,730,730
BEGIN DESCRIPTION:
CHACON CREEK 121.0
END DESCRIPTION:
XS GIS Cut Line= 3
      2003999.95     13640684.65        2003025.       13639575.
      2001614.55     13638710.72
#Sta/Elev= 30
  3519.5  748.94  3573.5  749.42  3708.3  745.24  3898.3  737.19 4137.71732.8786
  4210.5  730.37  4309.2  733.24  4904.1  734.46  4954.4  724.73  4975.3  724.06
  4979.4  720.31  4981.9  719.51  4999.6  720.31  5010.2  725.76  5055.2   728.2
  5113.9  729.54  5178.4  727.58  5257.7   731.6 5396.64732.8787  5600.1  743.02
  5658.1  748.33  5710.2  755.97  5716.1  754.73  5810.9  758.71  5826.3   761.4
  5832.2  760.25  5847.6  762.97  5853.5  761.81  5957.8  770.99  6650.8  783.55
#Mann= 5 ,-1 , 0
  3519.5      .1       0  3573.5     .08       0  3708.3      .1       0
  4979.4     .07       0  4999.6      .1       0
Bank Sta=4137.71,5396.64
XS Rating Curve= 0 ,0
Exp/Cntr=0.3,0.1

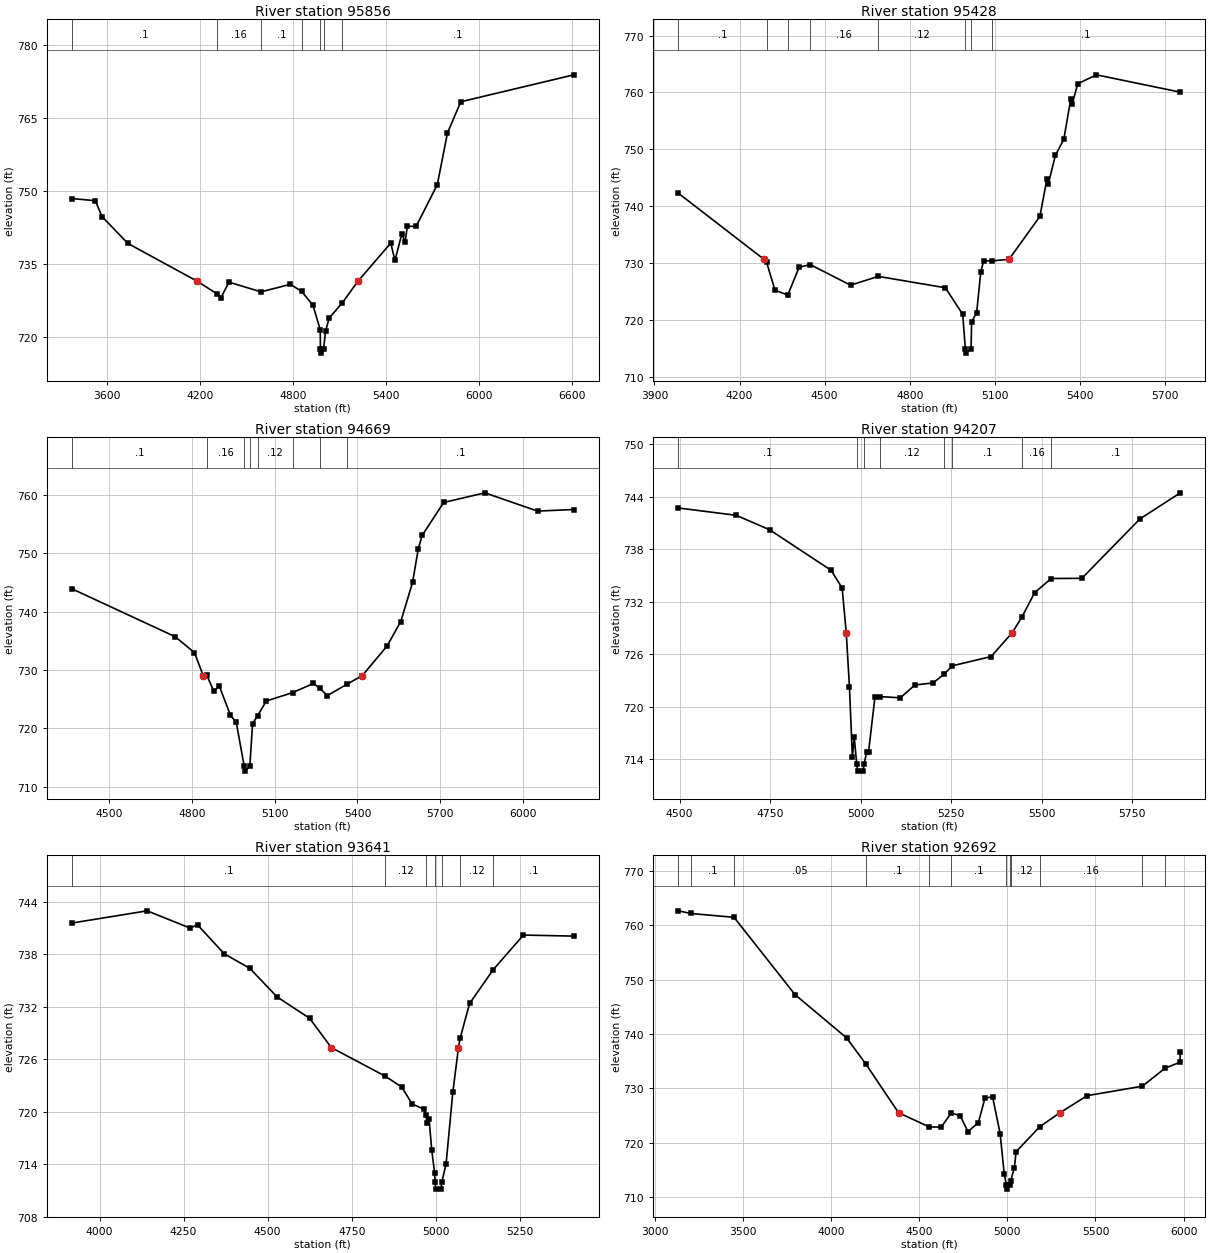
Type RM Length L Ch R = 1 ,95856   ,428,428,428
BEGIN DESCRIPTION:
CHACON CREEK 120.0
END DESCRIPTION:
XS GIS Cut Line= 3
      2004104.13     13640544.04      2003432.25     13639007.59
      2002531.23     13637731.58
#Sta/Elev= 30
  3372.8  748.38  3524.6  747.93  3568.2  744.66    3735  739.15 4182.76 731.367
  4307.2  728.84  4334.6  727.96  4386.9  731.19  4593.6   729.2    4783  730.74
  4855.6  729.29  4928.8  726.44  4975.6  721.44    4977   717.4  4979.5   716.6
  4997.2   717.4  5009.9  721.12  5033.3   723.8  5118.5  726.95 5218.64731.3669
  5430.7  739.22  5457.7  735.65  5502.1   741.1    5523  739.48  5537.8  742.68
  5594.4  742.66    5731  751.23  5796.3  761.84  5882.5  768.27  6611.8  773.81
#Mann= 7 ,-1 , 0
  3372.8      .1       0  4307.2     .16       0  4593.6      .1       0
  4855.6     .12       0    4977     .07       0  4997.2     .12       0
  5118.5      .1       0
Bank Sta=4182.76,5218.64
XS Rating Curve= 0 ,0
Exp/Cntr=0.3,0.1

Type RM Length L Ch R = 1 ,95428   ,759,759,759
BEGIN DESCRIPTION:
CHACON CREEK 119.0
END DESCRIPTION:
XS GIS Cut Line= 3
      2004124.99     13639824.98        2003775.       13638875.
      2003500.16     13638169.55
#Sta/Elev= 30
    3984  742.31 4286.25 730.663  4295.4  730.16    4325  725.24    4370   724.4
  4410.3   729.3  4449.8  729.73  4591.4  726.12  4688.6  727.67  4925.6  725.67
  4986.5     721  4995.9  714.98  4998.4  714.18  5016.1  714.98  5017.9  719.66
  5035.8  721.32  5050.1  728.37  5060.3  730.42  5089.8  730.39 5149.77730.6627
  5258.7  738.22  5283.2  744.73  5288.6  743.98  5313.1  748.93    5343  751.79
  5367.5  758.87  5372.8  758.01    5392  761.52  5457.9   763.1  5753.5  760.05
#Mann= 8 ,-1 , 0
    3984      .1       0  4295.4     .16       0    4370     .12       0
  4449.8     .16       0  4688.6     .12       0  4995.9     .07       0
  5016.1     .12       0  5089.8      .1       0
Bank Sta=4286.25,5149.77
XS Rating Curve= 0 ,0
Exp/Cntr=0.3,0.1

Type RM Length L Ch R = 1 ,94669   ,462,462,462
BEGIN DESCRIPTION:
CHACON CREEK 118.0
END DESCRIPTION:
XS GIS Cut Line= 3
      2004380.17     13639778.45      2004291.63     13638736.75
      2003703.08     13638231.54
#Sta/Elev= 30
  4363.8  743.93  4738.6  735.72  4808.9  732.98 4840.49729.0456  4853.7  729.09
  4879.1  726.36  4899.2  727.23  4939.3  722.23  4960.3  721.05  4989.4  713.47
  4991.9  712.67  5009.6  713.47  5019.6   720.8    5038  722.18  5069.5  724.69
  5164.8  726.13  5240.4   727.7    5264  726.84  5290.6   725.6  5363.1   727.6
 5417.82729.0463  5507.7  734.14  5557.1  738.31  5599.9  745.01  5620.7   750.8
    5635   753.1  5712.9  758.72  5862.2  760.37  6053.1  757.24  6184.9  757.51
#Mann= 8 ,-1 , 0
  4363.8      .1       0  4853.7     .16       0  4989.4     .07       0
  5009.6     .16       0    5038     .12       0  5164.8     .16       0
    5264     .12       0  5363.1      .1       0
Bank Sta=4840.49,5417.82
XS Rating Curve= 0 ,0
Exp/Cntr=0.3,0.1

Type RM Length L Ch R = 1 ,94207   ,566,566,566
BEGIN DESCRIPTION:
CHACON CREEK 117.0
END DESCRIPTION:
XS GIS Cut Line= 3
       2004708.3     13639544.03        2004775.       13639025.
       2004713.5     13638163.79
#Sta/Elev= 30
  4496.4  742.71  4656.7  741.87  4748.8  740.22  4918.9  735.58  4949.1  733.56
  4960.4728.4725  4969.3  722.26  4977.4  714.21  4982.4  716.56  4989.4  713.44
  4991.9  712.64  5007.1  712.64  5009.6  713.44  5017.2  714.88  5022.2  714.88
  5039.7  721.11  5054.4  721.15  5109.9  721.02    5150  722.48  5200.2  722.72
  5229.7  723.69  5253.8  724.68  5360.6  725.73 5419.09728.4705    5446  730.27
  5480.9  733.04  5526.6  734.65  5611.2  734.67  5771.6  741.46  5883.1  744.44
#Mann= 8 ,-1 , 0
  4496.4      .1       0  4989.4     .07       0  5009.6      .1       0
  5054.4     .12       0  5229.7     .16       0  5253.8      .1       0
    5446     .16       0  5526.6      .1       0
Bank Sta=4960.4,5419.09
XS Rating Curve= 0 ,0
Exp/Cntr=0.3,0.1

Type RM Length L Ch R = 1 ,93641   ,949,949,949
BEGIN DESCRIPTION:
CHACON CREEK 116.0
END DESCRIPTION:
XS GIS Cut Line= 3
      2004727.42     13639748.41        2005225.       13638775.
        2005225.     13638375.01
#Sta/Elev= 30
  3917.5  741.56  4141.6  742.96  4269.3  740.99  4291.5  741.36  4370.6  738.06
    4447  736.39  4527.8  733.13  4624.7  730.68 4689.47727.3295  4850.3  724.05
  4898.4  722.83  4930.1  720.87  4965.8  720.28  4969.9  719.57  4974.6  718.76
  4980.2  719.11  4988.2  715.57  4996.8  712.94  4997.8  711.95  5000.3  711.15
  5015.5  711.15    5018  711.95  5030.7  714.02  5050.7  722.21 5067.64727.3305
  5072.3  728.38  5100.7  732.37  5170.8  736.23  5260.7  740.19  5410.7  740.07
#Mann= 7 ,-1 , 0
  3917.5      .1       0  4850.3     .12       0  4969.9     .16       0
  4997.8     .07       0    5018     .16       0  5072.3     .12       0
  5170.8      .1       0
Bank Sta=4689.47,5067.64
XS Rating Curve= 0 ,0
Exp/Cntr=0.3,0.1

Type RM Length L Ch R = 1 ,92692   ,457,457,457
BEGIN DESCRIPTION:
CHACON CREEK 115.0
END DESCRIPTION:
XS GIS Cut Line= 4
      2006787.31     13640606.04      2006590.78     13639672.97
      2006002.56     13638644.52      2005339.29     13638388.75
#Sta/Elev= 30
  3132.4  762.69  3204.8   762.2  3449.1  761.49  3795.6  747.24  4088.4  739.26
  4196.1  734.51 4382.91 725.485  4557.6  722.87    4625  722.85  4682.6  725.49
  4733.3  724.88  4776.4  722.01  4835.5  723.67  4872.9  728.17  4916.1  728.45
  4959.2  721.64  4982.2  714.23    4995  712.22  4997.5  711.42  5015.4  712.22
  5018.9  712.91  5039.9   715.4  5049.9  718.32  5183.3   722.9 5298.17725.4849
  5452.9  728.64    5766  730.38  5895.8  733.71  5979.5  734.79  5981.6  736.73
#Mann= 12 ,-1 , 0
  3132.4     .08       0  3204.8      .1       0  3449.1     .05       0
  4196.1      .1       0  4557.6     .07       0  4682.6      .1       0
    4995     .07       0  5015.4      .1       0  5018.9     .12       0
  5183.3     .16       0    5766      .1       0  5895.8     .08       0
Bank Sta=4382.91,5298.17
XS Rating Curve= 0 ,0
Exp/Cntr=0.3,0.1