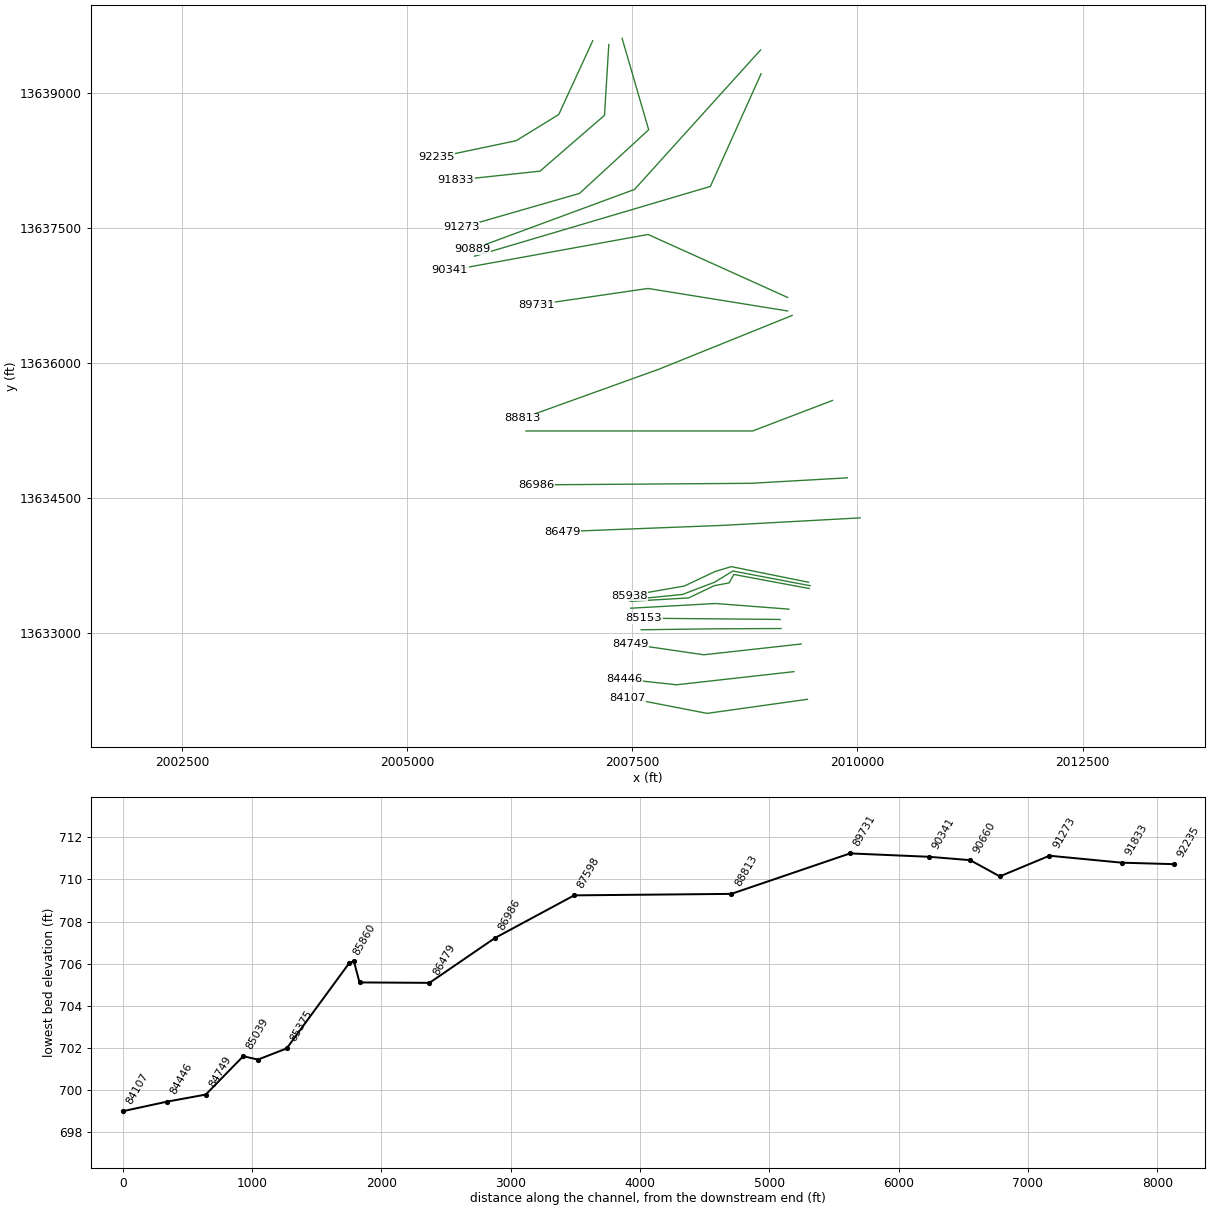
HEC-RAS study CHACON CREEK.prj: CHACON CREEK Base Level Engineering

--- CHACON CREEK.g01 (geometry) --- (continued)

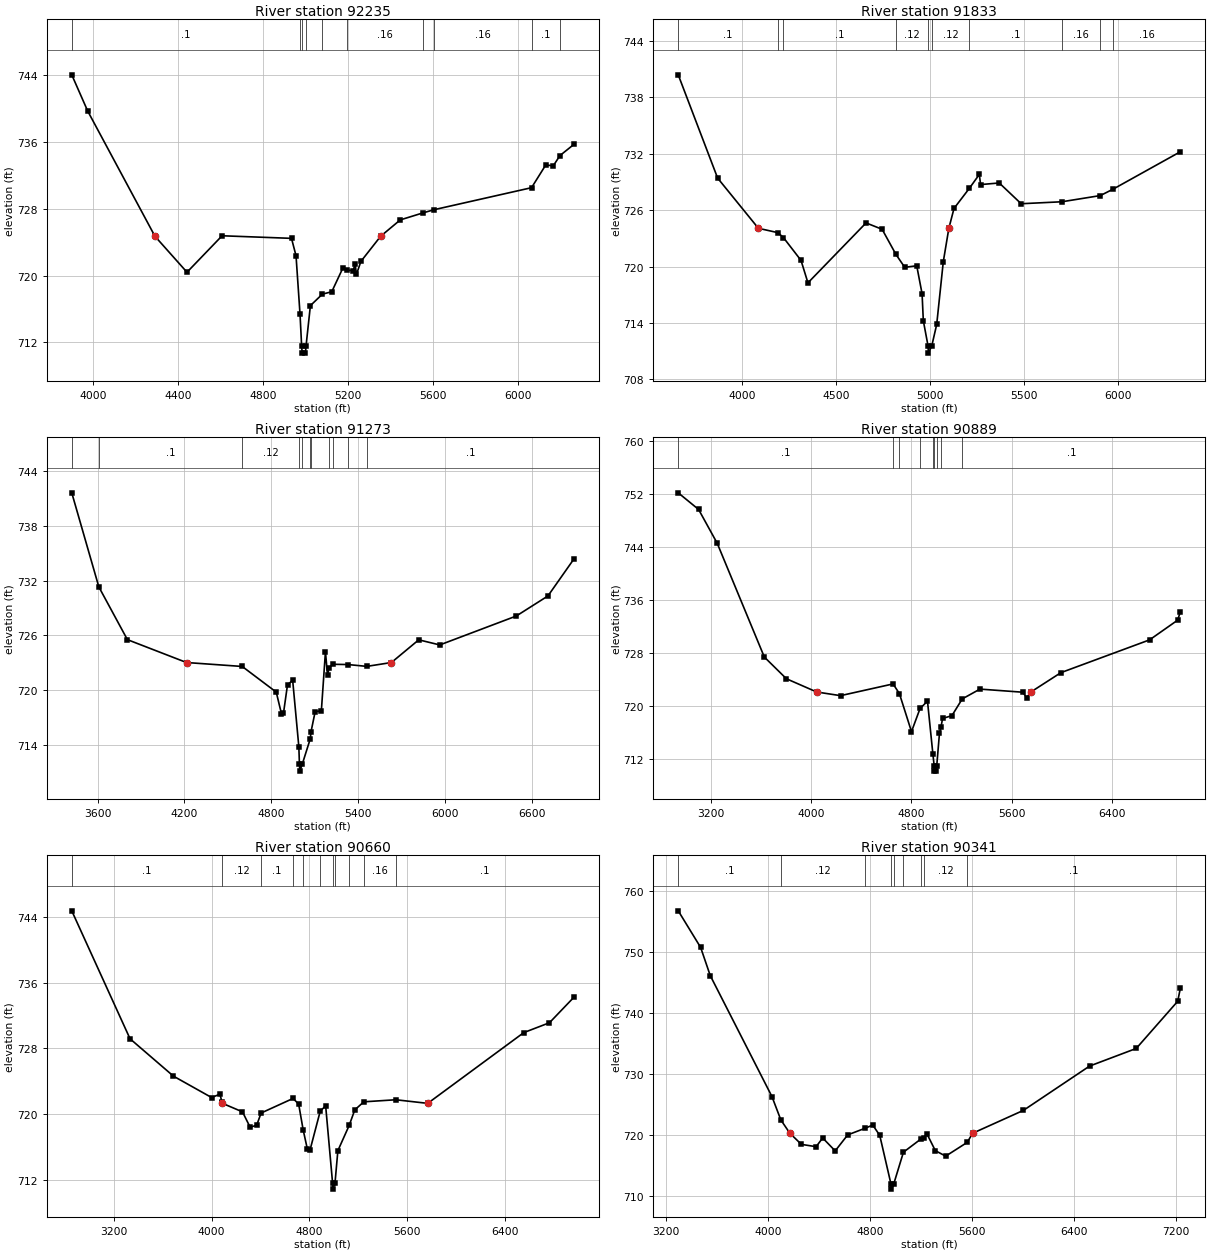
Type RM Length L Ch R = 1 ,92235   ,402,402,402
BEGIN DESCRIPTION:
Mapping XS 19dd5329
END DESCRIPTION:
XS GIS Cut Line= 4
      2007061.58     13639577.65      2006683.99     13638757.37
       2006210.9     13638466.57      2005325.58     13638279.96
#Sta/Elev= 30
  3901.1  744.06  3976.1  739.72 4292.66 724.717  4443.4  720.41  4608.6  724.78
  4935.3  724.47  4956.6  722.39  4975.5  715.35  4983.1  711.52  4985.6  710.72
    5001  710.72  5003.5  711.52  5024.2  716.41  5080.7  717.79  5124.7  718.07
  5176.8   720.9    5197  720.67  5225.5  720.59  5234.8  721.44  5240.7  720.14
    5262  721.71 5354.77724.7173  5447.2  726.68    5554  727.52    5606   727.9
  6065.1  730.54  6131.9  733.26  6167.4  733.16  6198.9  734.39  6264.2  735.72
#Mann= 10 ,-1 , 0
  3901.1      .1       0  4975.5     .12       0  4983.1     .07       0
  5003.5     .12       0  5080.7     .12       0    5197     .16       0
    5554      .1       0    5606     .16       0  6065.1      .1       0
  6198.9     .08       0
Bank Sta=4292.66,5354.77
XS Rating Curve= 0 ,0
Exp/Cntr=0.3,0.1

Type RM Length L Ch R = 1 ,91833   ,560,560,560
BEGIN DESCRIPTION:
CHACON CREEK 114.0
END DESCRIPTION:
XS GIS Cut Line= 4
      2007239.55     13639534.32       2007191.8     13638748.69
      2006475.65     13638128.03      2005542.53     13638028.21
#Sta/Elev= 30
  3659.6  740.41  3869.3  729.42 4086.36724.0768  4190.6  723.61    4220  723.08
  4313.3  720.66  4350.2  718.27  4659.6  724.65  4745.1  723.97  4818.9  721.29
  4865.7  719.92  4929.4  720.09  4957.9  717.11  4964.5  714.24  4989.4  711.59
  4991.9  710.79  5009.8  711.59  5035.7  713.84  5070.9  720.53 5100.41 724.076
  5127.9  726.19  5209.2  728.32  5262.7  729.81  5269.4  728.73  5368.8   728.9
  5485.5  726.69  5702.4   726.9  5907.1  727.56  5975.6  728.25  6332.8  732.22
#Mann= 10 ,-1 , 0
  3659.6      .1       0  4190.6     .07       0    4220      .1       0
  4818.9     .12       0  4989.4     .07       0  5009.8     .12       0
  5209.2      .1       0  5702.4     .16       0  5907.1      .1       0
  5975.6     .16       0
Bank Sta=4086.36,5100.41
XS Rating Curve= 0 ,0
Exp/Cntr=0.3,0.1

Type RM Length L Ch R = 1 ,91273   ,384,384,384
BEGIN DESCRIPTION:
Mapping XS 68332674
END DESCRIPTION:
XS GIS Cut Line= 4
      2007387.12     13639603.71      2007682.25      13638588.1
      2006914.02     13637880.63      2005603.22     13637503.02
#Sta/Elev= 30
  3422.2  741.62    3609  731.31  3806.2  725.53 4214.43723.0222    4599  722.59
  4833.8  719.78  4869.6  717.42  4883.7  717.46  4911.5  720.58  4947.2  721.07
  4989.8  713.79  4993.8  711.92  4996.3  711.12  5014.2  711.92    5069  714.68
  5073.8  715.43  5102.6  717.65  5145.2  717.72  5173.5  724.21  5187.7  721.63
    5199  722.45  5224.4  722.83    5329   722.8    5459   722.6 5628.94723.0224
  5817.6  725.51  5962.7  724.95    6491  728.12  6709.5  730.32  6888.3  734.36
#Mann= 11 ,-1 , 0
  3422.2     .05       0    3609      .1       0    4599     .12       0
  4993.8     .07       0  5014.2     .12       0    5069     .07       0
  5073.8      .1       0    5199     .16       0  5224.4      .1       0
    5329     .16       0    5459      .1       0
Bank Sta=4214.43,5628.94
XS Rating Curve= 0 ,0
Exp/Cntr=0.3,0.1

Type RM Length L Ch R = 1 ,90889   ,229,229,229
BEGIN DESCRIPTION:
CHACON CREEK 113.0
END DESCRIPTION:
XS GIS Cut Line= 3
        2008925.       13639475.        2007525.       13637925.
      2005724.86       13637260.
#Sta/Elev= 30
  2939.7  752.14  3102.2  749.63    3251  744.52  3626.8  727.36  3803.2  724.08
 4044.81722.0826  4235.1  721.53  4654.6   723.3  4705.1  721.84  4801.6   716.1
  4870.1   719.6  4929.3   720.7    4972  712.79  4982.6  710.94  4985.1  710.14
  5000.6  710.14  5003.1  710.94    5025  715.86  5036.6  716.75  5049.7  718.09
  5124.2  718.51  5206.9  721.04  5348.2  722.52  5689.3  722.05  5721.3  721.24
 5754.61722.0823  5994.1     725  6702.1  729.95  6925.9  732.92  6947.4  734.16
#Mann= 9 ,-1 , 0
  2939.7      .1       0  4654.6     .12       0  4705.1     .07       0
  4870.1     .12       0    4972     .07       0  4982.6     .07       0
  5003.1     .07       0  5036.6     .12       0  5206.9      .1       0
Bank Sta=4044.81,5754.61
XS Rating Curve= 0 ,0
Exp/Cntr=0.3,0.1

Type RM Length L Ch R = 1 ,90660   ,319,319,319
BEGIN DESCRIPTION:
Mapping XS 70170794
END DESCRIPTION:
XS GIS Cut Line= 3
      2008929.96     13639209.23      2008367.65     13637958.52
      2005748.83     13637183.51
#Sta/Elev= 30
  2858.1  744.73  3334.2  729.18  3688.9  724.64  4000.9  722.04  4068.8  722.45
    4086  721.44 4089.49721.3326    4253   720.3  4315.6  718.43  4369.1  718.68
  4405.2  720.16  4666.2  721.93  4711.9  721.25  4748.4  718.14  4783.8  715.73
  4805.7  715.71  4887.9  720.37  4932.5  721.04  4988.8  711.71  4991.3  710.91
  5009.3  711.71  5032.3  715.58    5125  718.66  5170.6  720.54  5244.4  721.52
  5505.9  721.77 5766.42721.3328  6551.3  729.93  6761.3  731.13  6960.5  734.22
#Mann= 11 ,-1 , 0
  2858.1      .1       0    4086     .12       0  4405.2      .1       0
  4666.2     .12       0  4748.4     .07       0  4887.9     .12       0
  4988.8     .07       0  5009.3     .12       0    5125     .12       0
  5244.4     .16       0  5505.9      .1       0
Bank Sta=4089.49,5766.42
XS Rating Curve= 0 ,0
Exp/Cntr=0.3,0.1

Type RM Length L Ch R = 1 ,90341   ,610,610,610
BEGIN DESCRIPTION:
CHACON CREEK 112.0
END DESCRIPTION:
XS GIS Cut Line= 3
      2009224.99       13636725.        2007675.       13637425.
        2005475.       13637025.
#Sta/Elev= 30
    3295  756.71  3470.6  750.71    3546  746.09  4030.2  726.23  4099.5  722.42
 4170.37720.2357  4260.6  718.41    4376  718.03  4427.7  719.46  4525.7  717.34
  4623.6  719.96  4763.3  721.08  4820.2  721.58    4875  719.89  4963.5  711.87
    4966  711.07    4984  711.87  5060.9  717.13    5201  719.34    5219   719.5
    5246   720.1  5310.8  717.38  5392.1  716.48  5560.5  718.73 5603.79720.2357
    6002  723.99  6520.3  731.25  6886.2  734.14  7211.5  741.88  7231.8  743.99
#Mann= 9 ,-1 , 0
    3295      .1       0  4099.5     .12       0  4763.3     .07       0
  4963.5     .07       0    4984     .07       0  5060.9     .12       0
    5201     .16       0    5219     .12       0  5560.5      .1       0
Bank Sta=4170.37,5603.79
XS Rating Curve= 0 ,0
Exp/Cntr=0.3,0.1

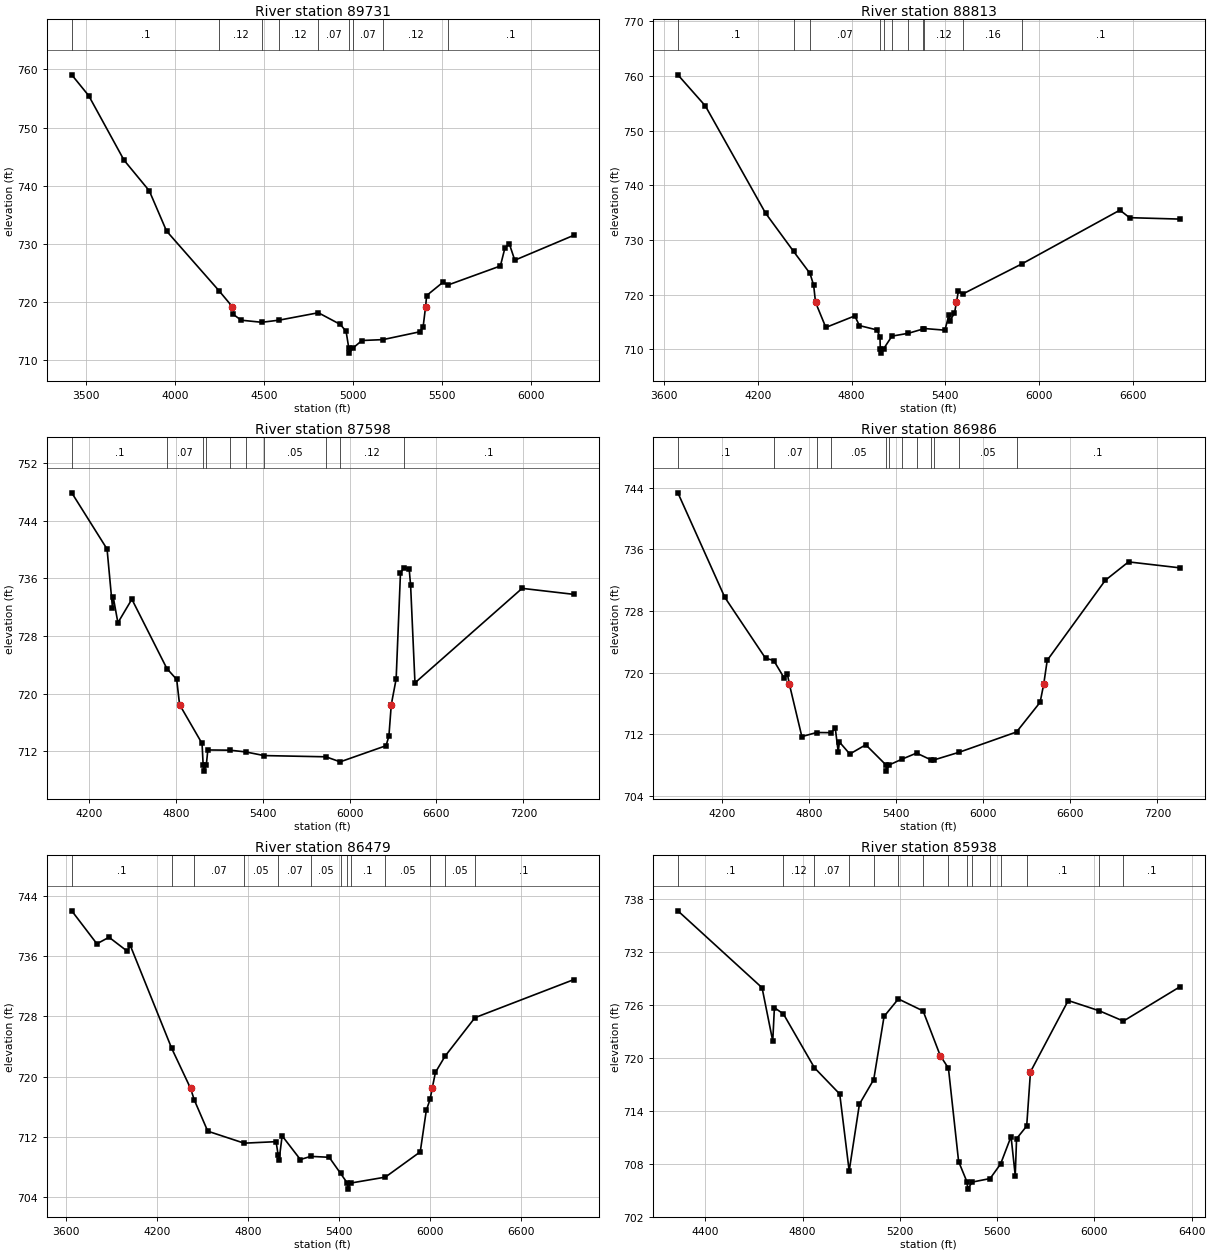
Type RM Length L Ch R = 1 ,89731   ,918,918,918
BEGIN DESCRIPTION:
CHACON CREEK 111.0
END DESCRIPTION:
XS GIS Cut Line= 3
      2009225.02       13636575.        2007675.       13636825.
      2006438.34     13636644.55
#Sta/Elev= 30
  3418.6  759.06  3513.8  755.48  3712.4  744.39  3854.2  739.13  3951.4  732.21
  4246.2  721.95 4320.11719.2381  4327.2  717.87  4370.8  716.89  4486.7  716.53
  4584.4   716.9  4804.4  718.17  4927.9  716.16  4960.3  714.97  4975.9  712.03
  4978.4  711.23  4996.4  712.03  5049.3   713.4  5167.2  713.55  5373.6  714.89
  5392.9  715.65 5407.13719.2385  5413.1  721.13  5503.5  723.38  5535.8  722.97
  5827.4  726.21  5853.5  729.38    5878  729.98  5908.3   727.2  6238.4  731.46
#Mann= 9 ,-1 , 0
  3418.6      .1       0  4246.2     .12       0  4486.7     .07       0
  4584.4     .12       0  4804.4     .07       0  4975.9     .07       0
  4996.4     .07       0  5167.2     .12       0  5535.8      .1       0
Bank Sta=4320.11,5407.13
XS Rating Curve= 0 ,0
Exp/Cntr=0.3,0.1

Type RM Length L Ch R = 1 ,88813   ,1215,1215,1215
BEGIN DESCRIPTION:
CHACON CREEK 110.0
END DESCRIPTION:
XS GIS Cut Line= 3
      2009274.96     13636524.98      2007795.65      13635927.7
      2006278.32     13635381.46
#Sta/Elev= 30
  3689.9  760.22  3865.6  754.53  4250.6  734.91  4429.8  727.91  4534.6  723.89
    4558  721.72 4569.85718.6107  4635.8  714.01  4820.9  716.12  4850.5  714.35
  4963.2  713.55  4981.9  712.24  4984.1  710.11  4986.7  709.31  5005.4  710.11
  5058.6  712.42  5163.4  712.94    5258  713.73  5266.6  713.81    5397  713.51
  5422.4  716.23  5427.7  715.16  5458.4  716.63 5470.93718.6095  5483.8  720.76
  5509.6   720.1  5892.1  725.68    6516  735.47  6577.4  734.09  6897.9  733.83
#Mann= 11 ,-1 , 0
  3689.9      .1       0  4429.8     .12       0  4534.6     .07       0
  4984.1     .07       0  5005.4     .07       0  5058.6     .05       0
  5163.4     .07       0    5258     .05       0  5266.6     .12       0
  5509.6     .16       0  5892.1      .1       0
Bank Sta=4569.85,5470.93
XS Rating Curve= 0 ,0
Exp/Cntr=0.3,0.1

Type RM Length L Ch R = 1 ,87598   ,612,612,612
BEGIN DESCRIPTION:
CHACON CREEK 109.0
END DESCRIPTION:
XS GIS Cut Line= 3
      2009722.71     13635580.47      2008837.32     13635241.94
      2006320.02     13635241.94
#Sta/Elev= 30
  4081.3   747.9  4325.1  740.09  4362.6  731.95  4367.9   733.4    4400  729.85
  4496.4  733.12  4738.2  723.49  4806.1  721.97 4825.79718.4813  4981.1  713.08
  4988.9  710.04  4991.5  709.24  5010.2  710.04    5021  712.18  5173.5  712.15
  5281.9  711.91  5409.6   711.4  5836.6  711.23    5935  710.53  6251.5  712.77
  6271.5  714.09 6287.95718.4818  6321.5  722.03  6351.5   736.8  6376.4  737.49
  6411.5  737.34  6421.5  735.03  6451.5   721.5  7191.5  734.63  7546.5   733.8
#Mann= 10 ,-1 , 0
  4081.3      .1       0  4738.2     .07       0  4988.9     .07       0
  5010.2     .07       0  5173.5     .05       0  5281.9     .07       0
  5409.6     .05       0  5836.6     .07       0    5935     .12       0
  6376.4      .1       0
Bank Sta=4825.79,6287.95
XS Rating Curve= 0 ,0
Exp/Cntr=0.3,0.1

Type RM Length L Ch R = 1 ,86986   ,507,507,507
BEGIN DESCRIPTION:
CHACON CREEK 108.0
END DESCRIPTION:
XS GIS Cut Line= 3
      2009887.63      13634721.1      2008819.96     13634660.34
      2006432.82     13634642.98
#Sta/Elev= 30
    3897  743.33  4220.2  729.77  4500.6  721.87  4557.4  721.57  4630.8  719.25
  4650.8  719.87 4665.47718.4664    4751   711.7  4852.6  712.23    4951  712.21
  4981.4  712.77  5001.4  709.74  5009.8     711  5081.4  709.44  5191.4  710.64
  5330.7  708.02  5333.3  707.22  5352.1  708.02  5442.9  708.79  5541.3  709.56
  5639.7  708.69  5662.4  708.68  5836.4  709.68  6229.9   712.3  6392.3  716.15
 6416.89718.4669  6441.4   721.6  6841.4  731.98  7001.4  734.37  7353.6   733.6
#Mann= 12 ,-1 , 0
    3897      .1       0  4557.4     .07       0  4852.6     .12       0
    4951     .05       0  5330.7    .033       0  5352.1     .05       0
  5442.9     .05       0  5541.3     .07       0  5639.7     .05       0
  5662.4     .07       0  5836.4     .05       0  6229.9      .1       0
Bank Sta=4665.47,6416.89
XS Rating Curve= 0 ,0
Exp/Cntr=0.3,0.1

Type RM Length L Ch R = 1 ,86479   ,541,541,541
BEGIN DESCRIPTION:
CHACON CREEK 107.0
END DESCRIPTION:
XS GIS Cut Line= 3
      2010030.46     13634276.23      2008502.68     13634192.89
      2006724.88     13634123.45
#Sta/Elev= 30
  3635.7  741.97  3801.4   737.6  3881.5  738.47  4001.7  736.62  4021.7  737.38
  4295.2  723.73 4418.94718.4587  4443.7  716.91  4532.5  712.77  4772.4  711.18
  4983.2  711.38  4996.9  709.61  5003.2  708.97  5023.2  712.15  5143.4  709.01
    5212  709.43  5333.6  709.31  5408.7  707.17    5453  705.89  5455.6  705.09
  5474.4  705.89  5703.8  706.68    5934  710.03    5974  715.52  5998.9  716.99
 6012.94718.4586  6034.1  720.56  6097.2  722.69  6294.8  727.81  6944.9  732.84
#Mann= 13 ,-1 , 0
  3635.7      .1       0  4295.2     .12       0  4443.7     .07       0
  4772.4     .05       0  4996.9     .07       0    5212     .05       0
  5408.7      .1       0    5453     .07       0  5474.4      .1       0
  5703.8     .05       0  5998.9      .1       0  6097.2     .05       0
  6294.8      .1       0
Bank Sta=4418.94,6012.94
XS Rating Curve= 0 ,0
Exp/Cntr=0.3,0.1

Type RM Length L Ch R = 1 ,85938   ,43,43,43
BEGIN DESCRIPTION:
Mapping XS b2d23f18
END DESCRIPTION:
XS GIS Cut Line= 5
      2009457.58     13633560.94      2008599.91     13633734.56
      2008415.88       13633679.      2008079.07     13633519.28
      2007464.49     13633411.64
#Sta/Elev= 30
  4286.7  736.66    4633  727.94    4677  721.89  4683.7  725.68  4720.8  724.97
  4848.4  718.87  4952.5  715.89  4991.3  707.17  5033.5  714.75  5092.3  717.53
  5134.9  724.69  5193.6  726.67  5295.4  725.31    5366  720.24  5399.6  718.82
  5441.5  708.24  5476.2  705.91  5478.9  705.11  5497.7  705.91  5571.1  706.31
  5614.2  707.96  5657.2  711.07  5674.4  706.65  5679.9  710.83  5721.5  712.26
 5737.12718.4086  5892.4  726.49    6020  725.33  6119.3  724.16  6350.7  728.03
#Mann= 15 ,-1 , 0
  4286.7      .1       0  4720.8     .12       0  4848.4     .07       0
  4991.3     .12       0  5092.3     .08       0  5193.6     .05       0
  5295.4      .1       0  5399.6     .05       0  5476.2     .07       0
  5497.7     .05       0  5571.1     .08       0  5614.2     .12       0
  5721.5      .1       0    6020     .05       0  6119.3      .1       0
Bank Sta=5366,5737.12
XS Rating Curve= 0 ,0
Exp/Cntr=0.3,0.1

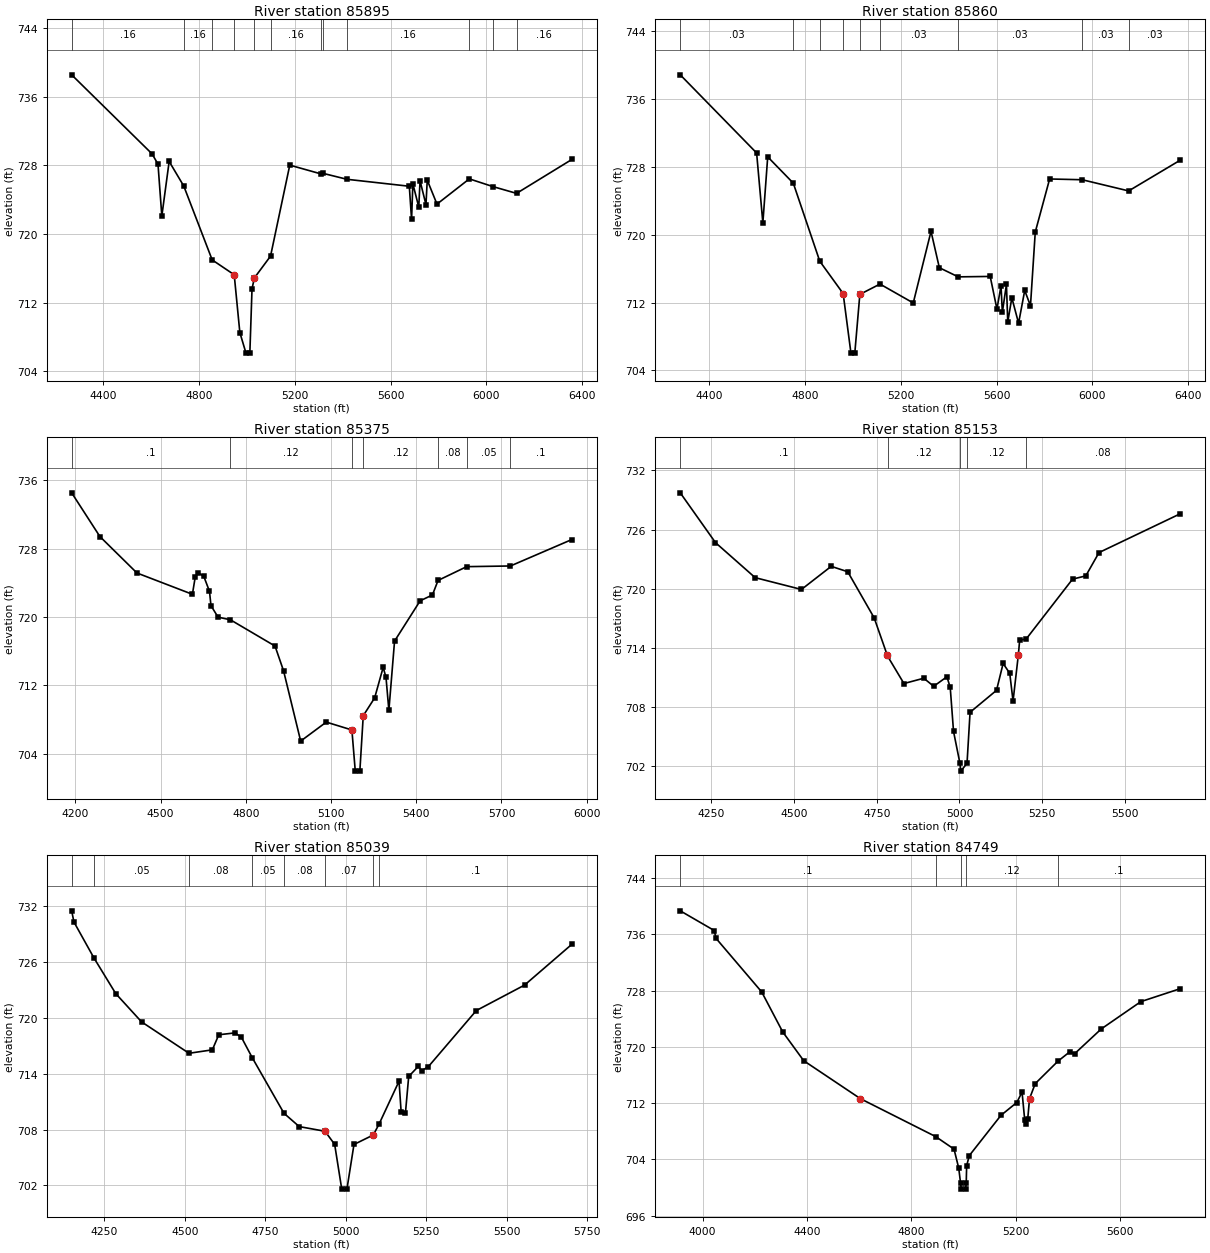
Type RM Length L Ch R = 1 ,85895   ,35,35,35
BEGIN DESCRIPTION:
Mapping XS 03f40d93
END DESCRIPTION:
XS GIS Cut Line= 5
      2009474.89     13633522.76      2008617.27     13633685.95
      2008412.41     13633560.95      2008058.24     13633425.53
      2007464.54     13633366.51
#Sta/Elev= 30
  4268.5  738.53  4604.3  729.32    4629  728.12    4645  722.08  4675.6  728.44
  4736.7  725.57  4855.3  716.97  4947.3  715.24  4970.8  708.51  4996.5  706.11
  5012.6  706.11  5021.7  713.62  5031.8  714.88    5099  717.41  5179.3  728.01
  5308.2     727  5318.6  727.05  5418.1  726.36  5678.5  725.55    5688  721.68
  5693.4  725.84  5718.1  723.12  5723.4  726.19  5748.1  723.41  5753.5  726.26
  5794.1  723.47  5929.2  726.41  6027.8  725.51  6126.4  724.72  6357.3  728.67
#Mann= 12 ,-1 , 0
  4268.5     .16       0  4736.7     .16       0  4855.3     .16       0
  4947.3     .07       0  5031.8     .16       0    5099     .16       0
  5308.2     .16       0  5318.6     .16       0  5418.1     .16       0
  5929.2     .16       0  6027.8     .16       0  6126.4     .16       0
Bank Sta=4947.3,5031.8
XS Rating Curve= 0 ,0
Exp/Cntr=0.3,0.1

Type RM Length L Ch R = 1 ,85860   ,485,485,485
BEGIN DESCRIPTION:
Mapping XS d4af8924
END DESCRIPTION:
XS GIS Cut Line= 6
      2009464.52      13633491.5      2008627.68     13633647.75
       2008575.6       13633554.      2008408.93     13633522.75
      2008127.68     13633387.34      2007479.16     13633349.19
#Sta/Elev= 30
  4277.7  738.88    4597  729.66  4623.1  721.41  4643.4   729.2  4750.3   726.1
    4861  716.89  4958.8  713.07  4991.4  706.04  5007.5  706.04  5028.6  712.97
  5112.8  714.19  5251.9  711.96  5326.2  720.41    5361  716.12  5439.9  715.04
  5573.6  715.09  5601.8  711.24  5618.9  713.99  5624.4  710.86  5641.5  714.14
    5647  709.71  5664.1  712.57  5692.3  709.57    5718  713.44    5742  711.62
    5762  720.32  5822.1  726.59  5958.4   726.5  6152.5  725.18  6368.9  728.82
#Mann= 9 ,-1 , 0
  4277.7     .03       0  4750.3     .03       0    4861     .03       0
  4958.8     .07       0  5028.6     .16       0  5112.8     .03       0
  5439.9     .03       0  5958.4     .03       0  6152.5     .03       0
Bank Sta=4958.8,5028.6
XS Rating Curve= 0 ,0
Exp/Cntr=0.3,0.1

Type RM Length L Ch R = 1 ,85375   ,222,222,222
BEGIN DESCRIPTION:
CHACON CREEK 106.0
END DESCRIPTION:
XS GIS Cut Line= 3
      2009238.79     13633262.34        2008425.       13633325.
      2007481.85     13633272.75
#Sta/Elev= 30
    4187  734.51  4286.4   729.4  4416.8  725.14    4612  722.65  4622.1  724.69
  4632.1  725.18  4652.2  724.74  4672.2  722.99  4677.4  721.32  4702.3  719.98
  4745.8  719.67  4902.9   716.6    4933   713.7  4993.2  705.49  5083.3  707.71
  5173.5  706.79  5185.4  701.98  5201.5  701.98  5213.5  708.46  5253.6  710.54
  5283.6  714.11  5293.6  712.93  5303.7  709.08  5323.7  717.18  5413.8  721.89
    5457  722.57  5476.8  724.27  5577.5  725.88  5731.7  725.96  5947.8  729.05
#Mann= 7 ,-1 , 0
    4187      .1       0  4745.8     .12       0  5173.5     .07       0
  5213.5     .12       0  5476.8     .08       0  5577.5     .05       0
  5731.7      .1       0
Bank Sta=5173.5,5213.5
XS Rating Curve= 0 ,0
Exp/Cntr=0.3,0.1

Type RM Length L Ch R = 1 ,85153   ,114,114,114
BEGIN DESCRIPTION:
Mapping XS e54092ca
END DESCRIPTION:
XS GIS Cut Line= 2
      2009141.58     13633147.75      2007628.85     13633161.63
#Sta/Elev= 30
  4155.5  729.73  4262.1  724.67  4382.1  721.11  4522.1  719.91  4612.1  722.26
  4662.1  721.71  4742.1  717.02 4781.13713.2767  4782.5  713.14  4832.1  710.35
  4892.1  710.89  4922.1  710.07  4962.1  711.04  4972.1  709.95  4982.1  705.48
  5001.4  702.25  5004.1  701.45  5022.9  702.25  5032.1  707.43  5112.1  709.66
  5132.1  712.39  5152.1  711.39  5162.1  708.57 5178.16713.2765  5182.1  714.75
  5201.9  714.88  5342.1  720.96  5382.1  721.29  5422.1  723.66  5668.3  727.61
#Mann= 5 ,-1 , 0
  4155.5      .1       0  4782.5     .12       0  5001.4     .07       0
  5022.9     .12       0  5201.9     .08       0
Bank Sta=4781.13,5178.16
XS Rating Curve= 0 ,0
Exp/Cntr=0.3,0.1

Type RM Length L Ch R = 1 ,85039   ,290,290,290
BEGIN DESCRIPTION:
CHACON CREEK 105.0
END DESCRIPTION:
XS GIS Cut Line= 3
      2009151.98     13633047.06      2008405.46     13633043.59
      2007598.26     13633033.19
#Sta/Elev= 30
  4148.2  731.52  4155.2  730.32  4217.5  726.45  4285.2  722.62  4365.2  719.59
  4512.7  716.21  4585.2  716.58  4605.2   718.2  4655.2   718.4  4675.2  717.95
  4709.4  715.72  4807.8  709.76  4855.2  708.33  4935.2  707.83  4965.2  706.42
  4987.2  701.61  5003.3  701.61  5025.2  706.41  5085.2  707.43    5103  708.59
  5165.2  713.21  5171.8  709.86  5185.2  709.84  5195.2  713.72  5225.2  714.81
  5235.2  714.35  5255.2  714.73  5405.2   720.8  5555.2  723.54    5702  727.92
#Mann= 8 ,-1 , 0
  4148.2     .08       0  4217.5     .05       0  4512.7     .08       0
  4709.4     .05       0  4807.8     .08       0  4935.2     .07       0
  5085.2     .08       0    5103      .1       0
Bank Sta=4935.2,5085.2
XS Rating Curve= 0 ,0
Exp/Cntr=0.3,0.1

Type RM Length L Ch R = 1 ,84749   ,303,303,303
BEGIN DESCRIPTION:
CHACON CREEK 104.0
END DESCRIPTION:
XS GIS Cut Line= 3
      2009374.98       13632875.      2008294.35     13632755.39
      2007474.96     13632875.01
#Sta/Elev= 30
  3914.6  739.32  4045.4  736.51  4050.7  735.45  4226.5   727.8    4307  722.12
  4387.4  718.03 4604.49712.6393  4892.9  707.25    4963  705.47  4981.1  702.76
  4988.2  700.59  4990.9  699.79    5007  699.79  5009.7  700.59  5011.3  703.11
  5021.4  704.55  5142.7  710.27  5203.3  712.09  5223.5  713.57  5233.6  709.66
    5240  709.02  5245.1   709.7 5252.12712.6372    5274  714.78  5360.9  717.96
  5405.4  719.27  5425.6  719.05  5526.7  722.54  5678.3  726.42  5829.9  728.27
#Mann= 5 ,-1 , 0
  3914.6      .1       0  4892.9     .12       0  4988.2     .07       0
  5009.7     .12       0  5360.9      .1       0
Bank Sta=4604.49,5252.12
XS Rating Curve= 0 ,0
Exp/Cntr=0.3,0.1

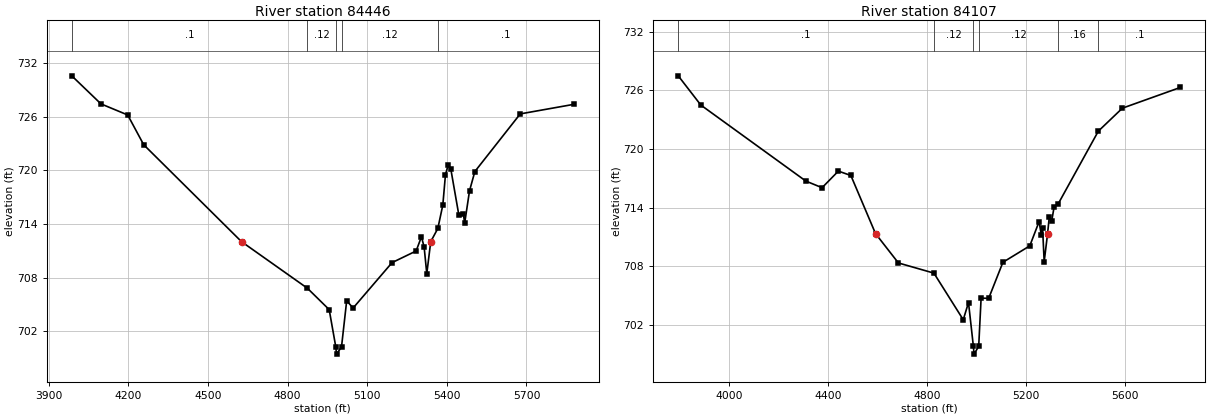
Type RM Length L Ch R = 1 ,84446   ,339,339,339
BEGIN DESCRIPTION:
Mapping XS 12e23814
END DESCRIPTION:
XS GIS Cut Line= 3
      2009294.34     13632567.89      2007992.27     13632422.06
      2007414.15     13632484.56
#Sta/Elev= 30
  3986.8  730.59  4096.8  727.45  4197.5  726.21  4257.8  722.88 4626.36712.0345
  4874.7  706.82  4956.7  704.43  4981.6  700.25  4984.3  699.45  5003.1  700.25
  5022.6  705.42  5046.9  704.61  5193.6  709.69  5284.2  710.99  5304.3  712.58
  5314.4  711.44  5324.4  708.45  5339.3712.0352    5366  713.51  5384.8  716.13
  5394.8  719.53  5404.9  720.61    5415  720.15  5445.1  715.03  5462.1  715.18
  5467.1  714.09  5485.4  717.72  5505.5  719.88  5676.5  726.33  5878.5   727.4
#Mann= 5 ,-1 , 0
  3986.8      .1       0  4874.7     .12       0  4981.6     .07       0
  5003.1     .12       0    5366      .1       0
Bank Sta=4626.36,5339.3
XS Rating Curve= 0 ,0
Exp/Cntr=0.3,0.1

Type RM Length L Ch R = 1 ,84107   ,576,576,576
BEGIN DESCRIPTION:
CHACON CREEK 103.0
END DESCRIPTION:
XS GIS Cut Line= 3
      2009445.35     13632260.59      2008330.81     13632104.35
      2007445.38     13632276.23
#Sta/Elev= 30
  3795.7  727.48  3886.9  724.49    4311  716.71  4376.5  716.03  4442.3  717.73
  4492.8  717.28 4592.33711.3344  4684.7  708.33  4828.1  707.29  4946.6  702.52
  4967.8  704.28  4987.5   699.8  4990.2     699    5009   699.8  5018.7  704.73
  5049.3  704.71  5106.8   708.4  5215.3  710.08    5253  712.57  5261.9  711.15
    5267  711.86  5273.4  708.46 5287.18 711.335  5293.8  712.99    5304  712.66
  5313.6  714.08  5330.5   714.4  5492.1  721.82  5589.2  724.17  5823.1  726.29
#Mann= 6 ,-1 , 0
  3795.7      .1       0  4828.1     .12       0  4987.5     .07       0
    5009     .12       0  5330.5     .16       0  5492.1      .1       0
Bank Sta=4592.33,5287.18
XS Rating Curve= 0 ,0
Exp/Cntr=0.3,0.1