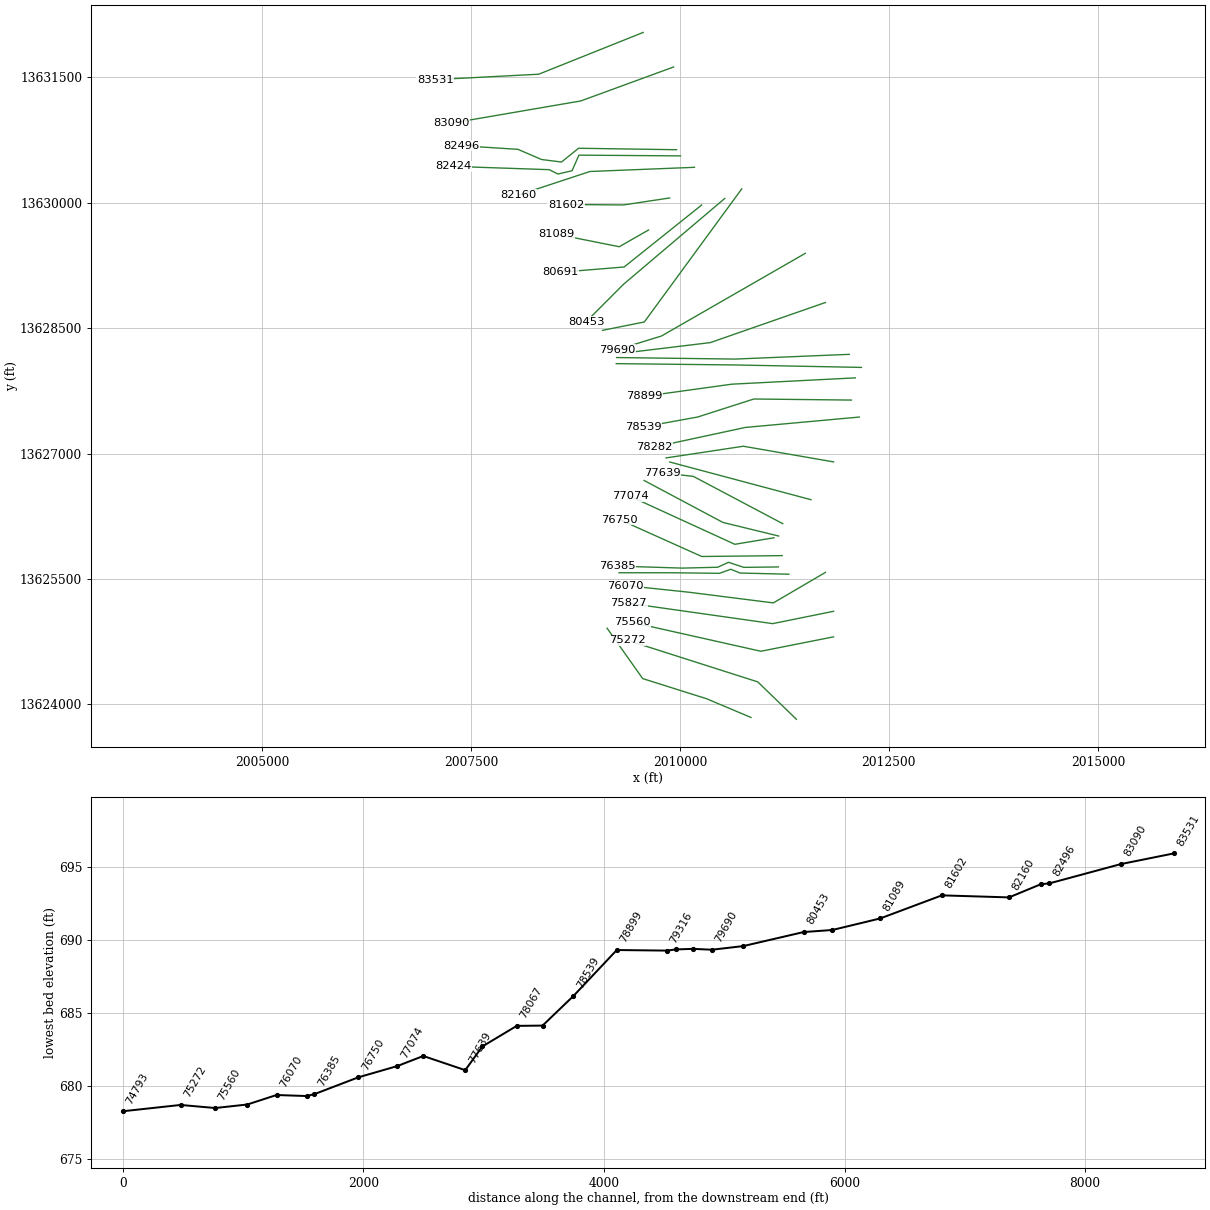
HEC-RAS study CHACON CREEK.prj: CHACON CREEK Base Level Engineering

--- CHACON CREEK.g01 (geometry) --- (continued)

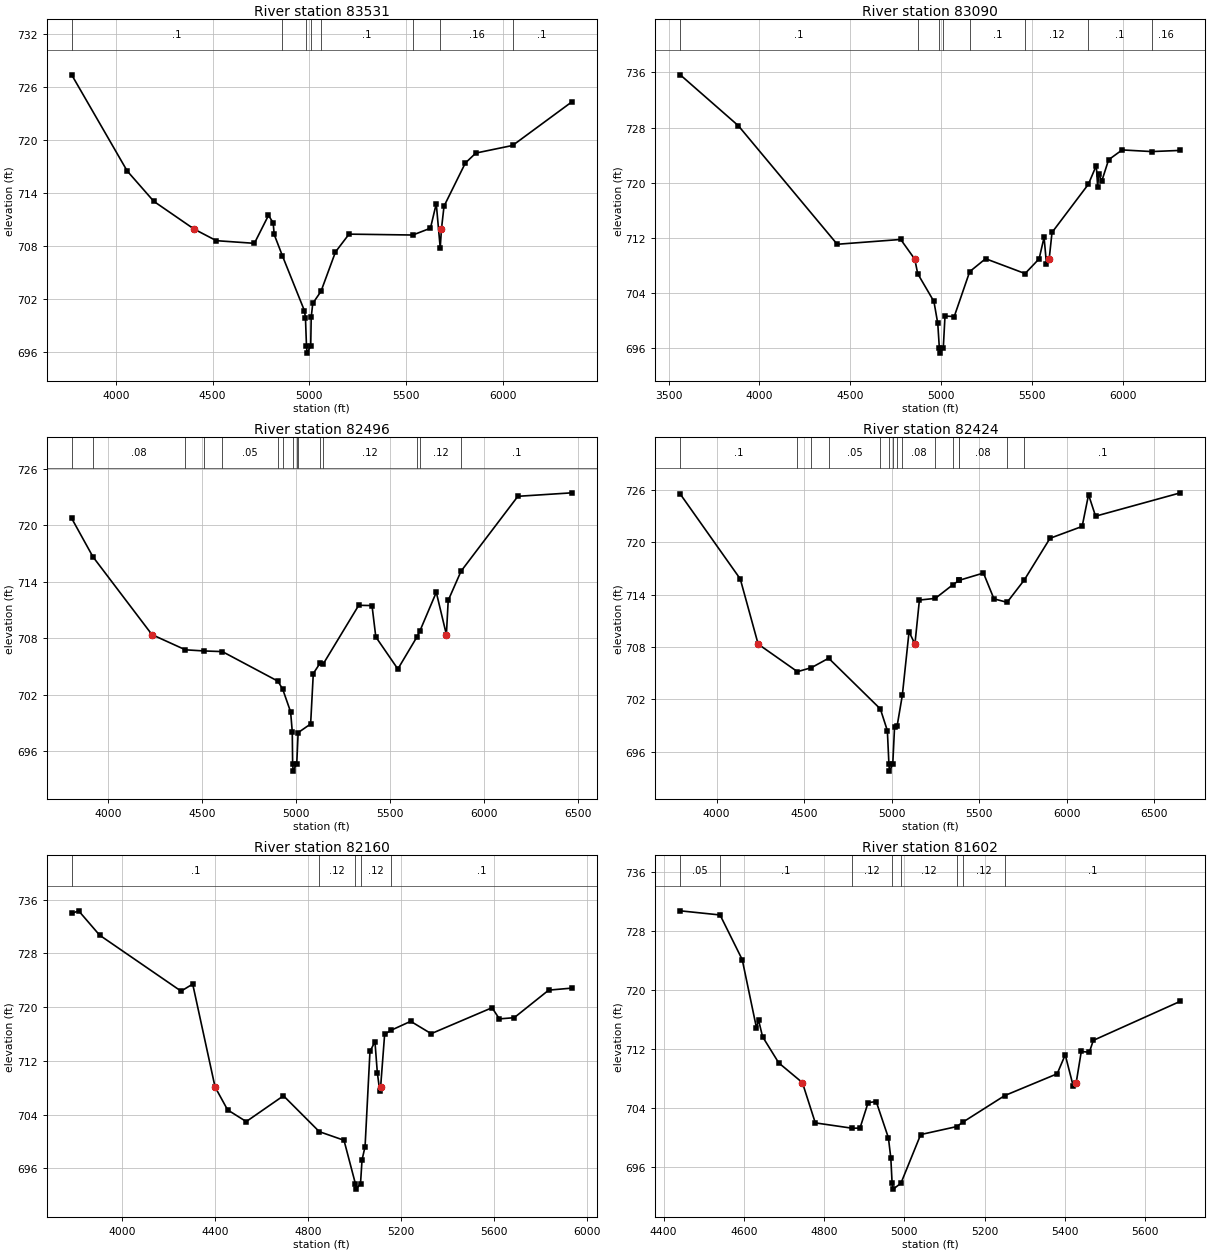
Type RM Length L Ch R = 1 ,83531   ,441,441,441
BEGIN DESCRIPTION:
CHACON CREEK 102.0
END DESCRIPTION:
XS GIS Cut Line= 3
      2009561.41     13632038.52      2008311.46     13631538.54
      2007075.58     13631474.14
#Sta/Elev= 30
  3771.8   727.4  4058.7  716.52    4196  713.09    4404709.9552  4519.1  708.64
  4715.7  708.34  4788.4   711.5  4812.6  710.67    4818  709.34  4860.4  706.93
  4974.2  700.72  4979.5  699.92  4984.8  696.72  4987.7  695.92  5006.7  696.72
  5009.2  699.99  5017.3  701.55  5059.8  702.91  5134.5  707.36  5204.6  709.38
    5534  709.28  5625.2  710.05  5655.2  712.83  5675.7  707.82 5682.03709.9563
  5695.3  712.54  5805.4  717.42  5859.6  718.55  6049.6  719.41  6355.6  724.34
#Mann= 8 ,-1 , 0
  3771.8      .1       0  4860.4     .12       0  4984.8     .07       0
  5006.7     .12       0  5059.8      .1       0    5534     .12       0
  5675.7     .16       0  6049.6      .1       0
Bank Sta=4404,5682.03
XS Rating Curve= 0 ,0
Exp/Cntr=0.3,0.1

Type RM Length L Ch R = 1 ,83090   ,594,594,594
BEGIN DESCRIPTION:
CHACON CREEK 101.0
END DESCRIPTION:
XS GIS Cut Line= 3
      2009925.01     13631625.01      2008815.18     13631218.93
       2007269.2     13630953.46
#Sta/Elev= 30
  3564.4  735.66  3883.9  728.26  4427.6  711.02  4776.8  711.72 4854.19708.8497
  4870.2  706.74  4959.4   702.7  4980.5  699.51  4989.1  695.99  4991.9  695.19
    5011  695.99  5020.3  700.58  5071.1  700.51  5156.1  707.04  5243.5  708.92
  5460.7  706.76  5537.8   708.9  5565.1  712.02  5578.4  708.17 5593.07708.8488
  5608.8  712.74  5808.8  719.75  5852.3  722.47    5860  719.29    5865  721.23
  5882.8  720.24    5920  723.31  5994.4  724.74  6156.9   724.5  6314.8  724.67
#Mann= 8 ,-1 , 0
  3564.4      .1       0  4870.2     .12       0  4989.1     .07       0
    5011     .12       0  5156.1      .1       0  5460.7     .12       0
  5808.8      .1       0  6156.9     .16       0
Bank Sta=4854.19,5593.07
XS Rating Curve= 0 ,0
Exp/Cntr=0.3,0.1

Type RM Length L Ch R = 1 ,82496   ,72,72,72
BEGIN DESCRIPTION:
Mapping XS 444041ae
END DESCRIPTION:
XS GIS Cut Line= 6
       2009960.2      13630635.6      2008788.27     13630652.96
      2008584.28     13630488.03      2008345.57     13630518.41
      2008063.45     13630639.94      2007388.19     13630683.23
#Sta/Elev= 30
  3804.6  720.73  3917.9  716.64 4232.01708.3736    4410  706.76  4508.4  706.64
  4606.8  706.57  4902.5  703.43  4928.2  702.57  4970.2  700.17    4979  698.07
    4981  694.67  4983.9  693.87  5002.9  694.67  5010.3  697.96  5076.8  698.88
    5091  704.24  5127.7  705.36  5145.2   705.3  5332.9  711.49  5403.6  711.46
  5423.8  708.13  5541.2  704.72  5643.2  708.14  5658.9  708.78  5745.8  712.87
 5799.58708.3748  5809.3  712.01  5877.5  715.11  6180.1  723.07  6467.5  723.44
#Mann= 15 ,-1 , 0
  3804.6     .05       0  3917.9     .08       0    4410     .05       0
  4508.4     .08       0  4606.8     .05       0  4902.5     .08       0
  4928.2      .1       0    4981     .07       0  5002.9      .1       0
  5010.3     .05       0  5127.7     .08       0  5145.2     .12       0
  5643.2     .08       0  5658.9     .12       0  5877.5      .1       0
Bank Sta=4232.01,5799.58
XS Rating Curve= 0 ,0
Exp/Cntr=0.3,0.1

Type RM Length L Ch R = 1 ,82424   ,264,264,264
BEGIN DESCRIPTION:
Mapping XS 490c1cf2
END DESCRIPTION:
XS GIS Cut Line= 6
      2010007.94     13630561.82      2008792.62      13630570.5
      2008710.15     13630383.86      2008540.88      13630344.8
      2008436.71     13630396.89       2007290.9     13630435.95
#Sta/Elev= 30
    3792  725.49  4134.9  715.78    4237 708.334  4461.4  705.18  4541.3  705.64
  4639.7  706.72    4935  700.92    4975  698.44    4984  694.61  4986.9  693.81
  5005.9  694.61  5016.1  698.83    5031     699  5060.6  702.49  5098.9  709.75
 5132.51708.3344  5158.1  713.37  5248.8  713.56  5349.1  715.12    5385  715.62
    5386  715.63  5523.9  716.46  5583.9  713.51  5658.9  713.11  5757.3  715.67
    5904  720.43  6087.7  721.79  6124.2  725.42  6164.3  722.96  6648.9  725.63
#Mann= 15 ,-1 , 0
    3792      .1       0  4461.4     .05       0  4541.3     .08       0
  4639.7     .05       0    4935     .08       0    4984     .07       0
  5005.9     .08       0    5031     .12       0  5060.6     .08       0
  5248.8     .05       0  5349.1     .08       0    5385      .1       0
    5386     .08       0  5658.9     .05       0  5757.3      .1       0
Bank Sta=4237,5132.51
XS Rating Curve= 0 ,0
Exp/Cntr=0.3,0.1

Type RM Length L Ch R = 1 ,82160   ,558,558,558
BEGIN DESCRIPTION:
CHACON CREEK 100.0
END DESCRIPTION:
XS GIS Cut Line= 3
        2010175.       13630425.        2008925.       13630375.
      2008070.43     13630093.95
#Sta/Elev= 30
    3783  733.93    3813  734.32  3903.1   730.7  4253.4  722.37  4303.4  723.42
 4399.47 708.111  4453.5   704.7  4533.6  702.96  4693.7   706.8  4847.8  701.46
  4953.9  700.18    5003  693.71  5005.9  692.91  5024.9  693.71  5031.5  697.26
  5044.5  699.23  5065.6  713.39    5087  714.86  5097.2  710.25  5107.7  707.51
 5111.41708.1113  5128.7  715.96  5157.8  716.57  5240.7  717.88  5328.8  716.04
  5590.4   719.9  5622.2  718.24  5685.8  718.42  5834.1  722.52  5933.6  722.82
#Mann= 5 ,-1 , 0
    3783      .1       0  4847.8     .12       0    5003     .07       0
  5024.9     .12       0  5157.8      .1       0
Bank Sta=4399.47,5111.41
XS Rating Curve= 0 ,0
Exp/Cntr=0.3,0.1

Type RM Length L Ch R = 1 ,81602   ,513,513,513
BEGIN DESCRIPTION:
CHACON CREEK 99.0
END DESCRIPTION:
XS GIS Cut Line= 3
      2009877.69     13630058.34        2009325.       13629975.
      2008638.15     13629980.21
#Sta/Elev= 30
  4441.6  730.69  4540.8  730.13    4596  724.09  4631.5  714.86  4636.6  715.93
  4646.6  713.67    4687  710.12 4745.85 707.456    4778  702.01  4869.4  701.29
  4889.3   701.3  4909.5  704.75  4929.7  704.89  4960.1  699.99  4966.1  697.26
  4969.3  693.85  4972.2  693.05  4991.3  693.85  5040.5  700.43  5130.4  701.51
  5145.3   702.1  5249.8   705.7  5380.5  708.65  5400.5  711.22  5420.5  706.97
 5427.87707.4564  5440.5  711.67  5460.5  711.56  5470.5  713.17  5687.4  718.46
#Mann= 8 ,-1 , 0
  4441.6     .05       0  4540.8      .1       0  4869.4     .12       0
  4969.3     .07       0  4991.3     .12       0  5130.4     .05       0
  5145.3     .12       0  5249.8      .1       0
Bank Sta=4745.85,5427.87
XS Rating Curve= 0 ,0
Exp/Cntr=0.3,0.1

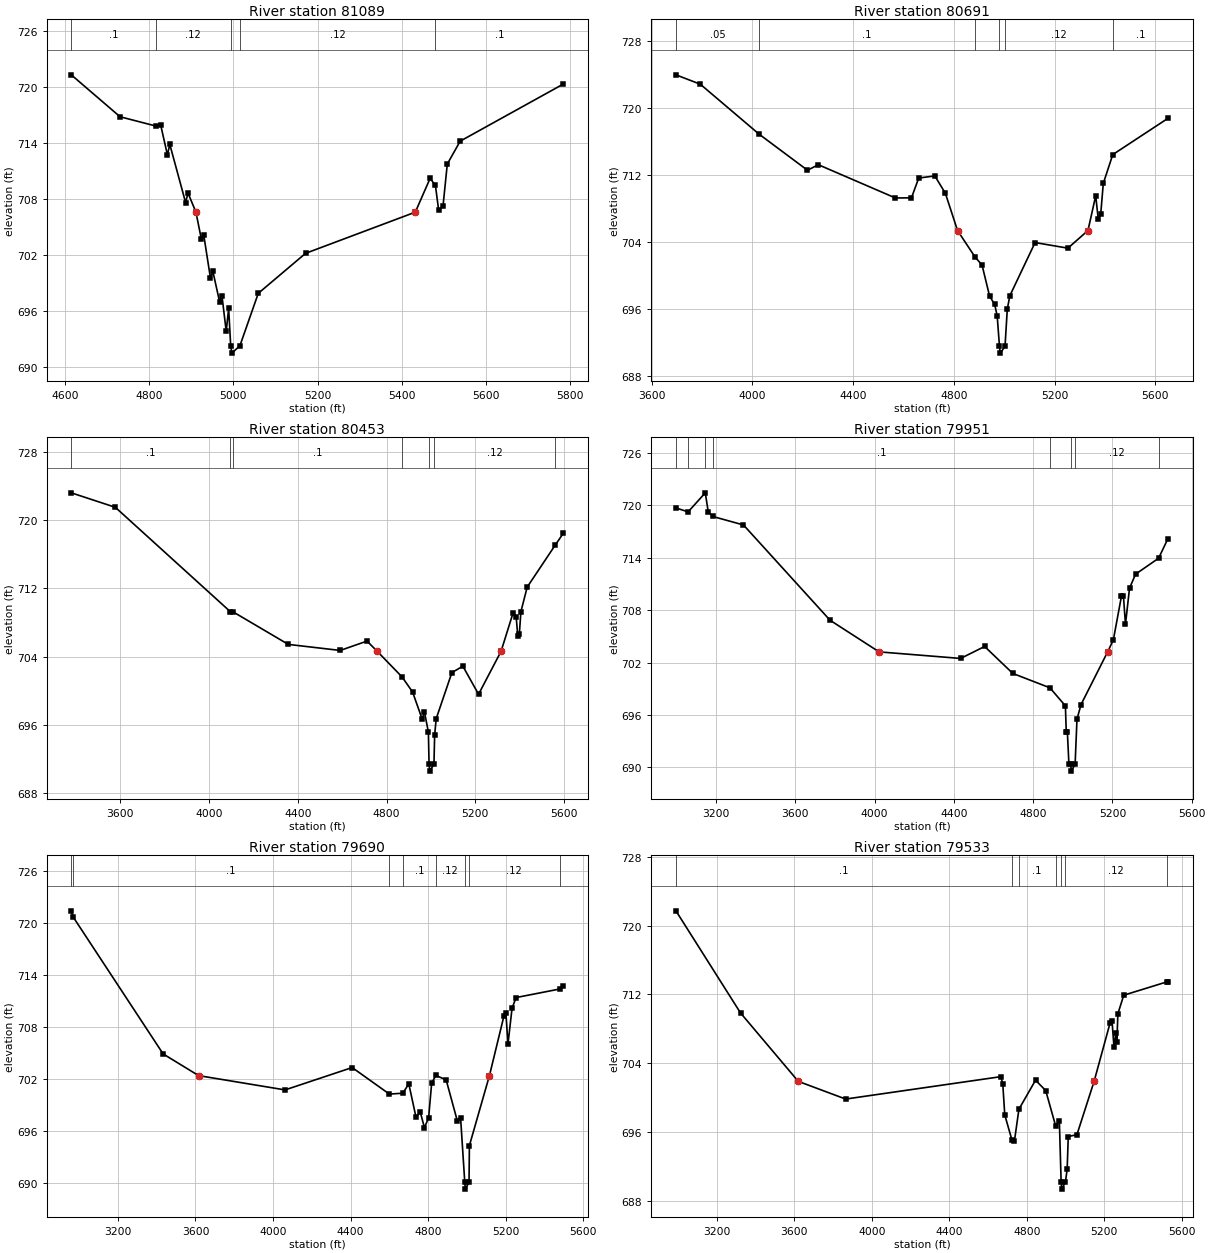
Type RM Length L Ch R = 1 ,81089   ,398,398,398
BEGIN DESCRIPTION:
CHACON CREEK 98.0
END DESCRIPTION:
XS GIS Cut Line= 3
      2009624.99     13629674.99        2009275.       13629475.
      2008525.05     13629624.99
#Sta/Elev= 30
  4615.1  721.26    4731  716.77  4815.8  715.78  4827.4  715.88  4843.3   712.7
    4849  713.81  4886.5  707.59  4892.2  708.61 4911.02706.5605  4923.9  703.67
  4929.7  704.08  4945.5   699.5  4951.3  700.21  4967.1  696.98  4972.8  697.61
  4982.9  693.81  4988.7  696.26  4993.5  692.27  4996.4  691.47  5015.5  692.27
    5059  697.87  5171.2  702.15 5431.77706.5602  5466.9  710.18  5479.5  709.42
  5487.3  706.74  5497.5  707.19  5507.7  711.71  5538.3  714.16    5783  720.27
#Mann= 5 ,-1 , 0
  4615.1      .1       0  4815.8     .12       0  4993.5     .07       0
  5015.5     .12       0  5479.5      .1       0
Bank Sta=4911.02,5431.77
XS Rating Curve= 0 ,0
Exp/Cntr=0.3,0.1

Type RM Length L Ch R = 1 ,80691   ,238,238,238
BEGIN DESCRIPTION:
Mapping XS 95d88f00
END DESCRIPTION:
XS GIS Cut Line= 3
      2010260.86     13629974.25       2009333.7     13629232.75
      2008569.04     13629170.33
#Sta/Elev= 30
    3696  723.93  3792.8  722.81  4026.9  716.83  4218.6  712.53  4261.8  713.19
  4567.6  709.22  4631.6  709.23  4660.5   711.6  4724.5  711.85  4766.3  709.78
 4814.64 705.329  4883.8  702.18    4912   701.2  4942.1  697.48  4962.2   696.5
  4972.2  695.13  4981.3  691.48  4984.2  690.68  5003.3  691.48  5012.3  695.93
  5022.4  697.53  5122.7  703.89  5253.1  703.22 5332.79705.3295  5363.5  709.48
  5373.5  706.72  5383.6  707.34  5393.6  710.95  5431.3   714.4  5650.4  718.73
#Mann= 6 ,-1 , 0
    3696     .05       0  4026.9      .1       0  4883.8     .12       0
  4981.3     .07       0  5003.3     .12       0  5431.3      .1       0
Bank Sta=4814.64,5332.79
XS Rating Curve= 0 ,0
Exp/Cntr=0.3,0.1

Type RM Length L Ch R = 1 ,80453   ,502,502,502
BEGIN DESCRIPTION:
CHACON CREEK 97.0
END DESCRIPTION:
XS GIS Cut Line= 3
      2010536.87     13630052.35        2009325.       13629025.
      2008880.53     13628579.42
#Sta/Elev= 30
  3378.7  723.24  3577.3  721.54  4095.2  709.29  4107.7  709.26  4357.2  705.43
  4591.2  704.72    4712  705.82 4757.85 704.624  4869.9  701.61  4917.4  699.84
  4960.3  696.68    4971  697.48  4988.7  695.13  4991.8  691.34  4994.7  690.54
  5013.8  691.34  5016.9  694.78    5024  696.71  5094.7  702.12  5144.2  702.87
  5214.9  699.57 5316.42 704.624  5370.5  709.13  5384.6  708.63  5391.7  706.45
  5398.8  706.66  5405.8  709.27  5434.1  712.16  5559.8  717.07  5596.8  718.48
#Mann= 7 ,-1 , 0
  3378.7      .1       0  4095.2     .05       0  4107.7      .1       0
  4869.9     .12       0  4991.8     .07       0  5013.8     .12       0
  5559.8      .1       0
Bank Sta=4757.85,5316.42
XS Rating Curve= 0 ,0
Exp/Cntr=0.3,0.1

Type RM Length L Ch R = 1 ,79951   ,261,261,261
BEGIN DESCRIPTION:
CHACON CREEK 96.0
END DESCRIPTION:
XS GIS Cut Line= 3
      2010739.99     13630166.93        2009575.       13628575.
      2009074.98       13628475.
#Sta/Elev= 30
  2997.6  719.71  3059.2  719.26  3145.7  721.44  3160.9  719.24  3184.2  718.73
  3338.5  717.76  3775.5  706.85 4022.87703.2323  4434.1  702.48  4555.3  703.85
  4697.7  700.76  4884.7  699.12  4962.9  697.05  4967.2  694.05  4972.8  694.05
  4980.5  690.45  4989.9  690.38  4992.7  689.58  5011.9  690.38  5021.3  695.52
  5041.7   697.2 5175.96703.2322  5204.8   704.6  5245.6  709.59  5255.8   709.6
    5266  706.38  5286.4  710.52    5317  712.13  5433.1  713.95  5480.2  716.19
#Mann= 8 ,-1 , 0
  2997.6      .1       0  3059.2     .08       0  3145.7     .05       0
  3184.2      .1       0  4884.7     .12       0  4989.9     .07       0
  5011.9     .12       0  5433.1      .1       0
Bank Sta=4022.87,5175.96
XS Rating Curve= 0 ,0
Exp/Cntr=0.3,0.1

Type RM Length L Ch R = 1 ,79690   ,157,157,157
BEGIN DESCRIPTION:
Mapping XS 1fafe012
END DESCRIPTION:
XS GIS Cut Line= 3
      2011500.43     13629396.12      2009780.46      13628407.3
      2009252.67      13628244.1
#Sta/Elev= 30
  2959.9  721.42  2968.2  720.76  3433.5  704.92 3616.44702.4186    4062  700.77
    4408  703.35  4599.8  700.29  4669.5  700.39  4699.9  701.48  4737.3   697.6
  4758.8  698.24  4780.4  696.43    4802  697.53  4817.8  701.54  4839.2  702.44
  4892.5  701.93  4949.6  697.24  4966.9  697.58  4988.5  690.13  4991.4  689.33
  5010.5  690.13  5012.4  694.35 5115.71702.4183  5190.3  709.28  5200.5  709.64
  5211.2  706.05  5232.2  710.18  5253.1  711.42    5477   712.4  5496.3  712.73
#Mann= 8 ,-1 , 0
  2959.9     .08       0  2968.2      .1       0  4599.8     .12       0
  4669.5      .1       0  4839.2     .12       0  4988.5     .07       0
  5010.5     .12       0    5477      .1       0
Bank Sta=3616.44,5115.71
XS Rating Curve= 0 ,0
Exp/Cntr=0.3,0.1

Type RM Length L Ch R = 1 ,79533   ,142,142,142
BEGIN DESCRIPTION:
Mapping XS 28a1ffe2
END DESCRIPTION:
XS GIS Cut Line= 3
      2011740.03     13628807.58      2010365.01      13628328.4
      2009288.45     13628198.38
#Sta/Elev= 30
  2988.5  721.71  3322.1  709.85  3620.4701.9049  3864.9  699.85  4666.2  702.45
  4676.3   701.6  4686.5  698.01  4722.8  695.15  4736.7  695.01  4759.6  698.67
  4845.4  702.04  4897.9  700.84  4948.9  696.76  4968.4  697.34  4977.6  690.19
  4980.4  689.39  4999.6  690.19  5008.7   691.7  5014.4   695.5  5059.1  695.71
  5147.8701.9047  5230.3  708.69  5240.4  708.94  5250.4  705.89  5260.4  707.57
  5265.4  706.52  5270.6  709.75  5300.8  711.91  5523.8  713.46    5529  713.43
#Mann= 7 ,-1 , 0
  2988.5      .1       0  4722.8     .12       0  4759.6      .1       0
  4948.9     .12       0  4977.6     .07       0  4999.6     .12       0
  5523.8      .1       0
Bank Sta=3620.4,5147.8
XS Rating Curve= 0 ,0
Exp/Cntr=0.3,0.1

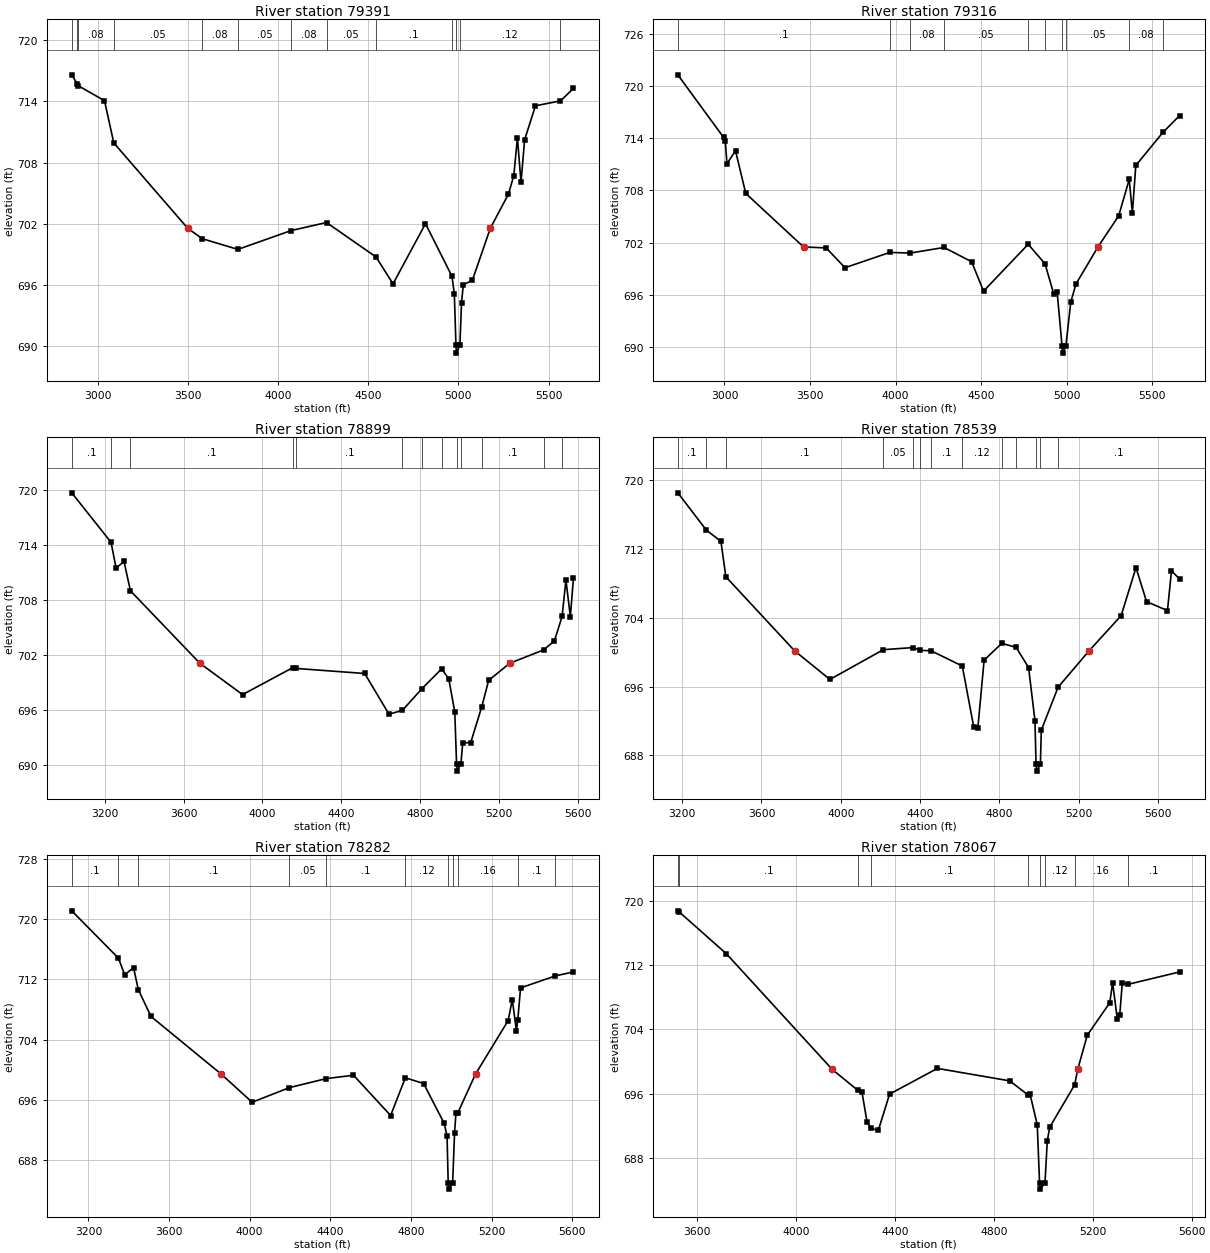
Type RM Length L Ch R = 1 ,79391   ,75,75,75
BEGIN DESCRIPTION:
CHACON CREEK 95.0
END DESCRIPTION:
XS GIS Cut Line= 3
      2012026.44     13628187.78      2010658.93     13628131.26
      2009244.02     13628149.49
#Sta/Elev= 30
  2854.7  716.58  2886.4  715.66  2891.2  715.51  3036.3  714.05  3087.9  709.92
 3498.24701.5607  3579.7  700.54  3776.4   699.5  4071.5  701.34  4268.3  702.13
  4542.9  698.76  4637.3  696.13  4817.4  702.02  4964.5  696.86  4977.4  695.15
  4986.4  690.15  4989.2  689.35  5008.4  690.15  5017.4   694.3  5027.4  696.05
  5077.4  696.47    5177701.5608  5277.4   704.9  5307.4  706.71  5327.4  710.43
  5347.4  706.06  5367.4  710.22  5427.4  713.55  5566.4  714.03  5638.4  715.25
#Mann= 13 ,-1 , 0
  2854.7      .1       0  2886.4     .05       0  2891.2     .08       0
  3087.9     .05       0  3579.7     .08       0  3776.4     .05       0
  4071.5     .08       0  4268.3     .05       0  4542.9      .1       0
  4964.5     .12       0  4986.4     .07       0  5008.4     .12       0
  5566.4      .1       0
Bank Sta=3498.24,5177
XS Rating Curve= 0 ,0
Exp/Cntr=0.3,0.1

Type RM Length L Ch R = 1 ,79316   ,417,417,417
BEGIN DESCRIPTION:
CHACON CREEK 94.0
END DESCRIPTION:
XS GIS Cut Line= 3
      2012172.26     13628031.53      2010650.25     13628060.95
      2009239.43     13628076.57
#Sta/Elev= 30
  2727.2   721.3  2994.5  714.11  3004.5  713.73  3014.5  711.07  3064.5  712.55
  3124.5  707.65 3462.12701.4898  3594.6  701.38  3704.6   699.1  3966.4  700.86
  4086.5  700.79  4283.5  701.43  4444.8  699.79  4514.8  696.41  4775.7   701.8
  4874.1  699.55  4924.8   696.1  4944.8  696.33  4973.8  690.07  4976.6  689.27
  4995.8  690.07  5024.8  695.16  5054.8  697.22 5183.54701.4898  5304.8  705.08
  5366.3  709.26  5384.8  705.41  5404.8  710.87  5563.2  714.67  5660.4   716.6
#Mann= 10 ,-1 , 0
  2727.2      .1       0  3966.4     .05       0  4086.5     .08       0
  4283.5     .05       0  4775.7     .08       0  4874.1     .05       0
  4973.8     .04       0  4995.8     .05       0  5366.3     .08       0
  5563.2     .05       0
Bank Sta=3462.12,5183.54
XS Rating Curve= 0 ,0
Exp/Cntr=0.3,0.1

Type RM Length L Ch R = 1 ,78899   ,360,360,360
BEGIN DESCRIPTION:
CHACON CREEK 93.0
END DESCRIPTION:
XS GIS Cut Line= 3
      2012099.34     13627906.52      2010620.74     13627830.91
      2009569.32     13627685.17
#Sta/Elev= 30
  3033.7  719.64  3232.7  714.25  3258.3  711.44  3298.4  712.16  3331.1  708.96
 3682.73701.0696  3899.2  697.65  4154.5   700.6  4171.3   700.5  4517.9  699.95
  4641.2  695.51  4709.3  695.94  4808.2   698.3  4908.3  700.46    4944  699.35
  4974.3  695.77  4983.5  690.11  4986.4  689.31  5005.5  690.11  5014.7  692.39
  5055.1  692.42  5111.1  696.32    5146   699.2 5252.99701.0696  5424.5  702.52
  5479.1   703.5  5518.2  706.17  5537.6  710.14  5559.9  706.14  5575.7  710.37
#Mann= 13 ,-1 , 0
  3033.7      .1       0  3232.7     .08       0  3331.1      .1       0
  4154.5     .05       0  4171.3      .1       0  4709.3     .12       0
  4808.2      .1       0  4908.3     .12       0  4983.5     .07       0
  5005.5     .12       0  5111.1      .1       0  5424.5     .12       0
  5518.2      .1       0
Bank Sta=3682.73,5252.99
XS Rating Curve= 0 ,0
Exp/Cntr=0.3,0.1

Type RM Length L Ch R = 1 ,78539   ,257,257,257
BEGIN DESCRIPTION:
CHACON CREEK 92.0
END DESCRIPTION:
XS GIS Cut Line= 4
      2012052.54      13627640.9      2010885.13     13627653.54
      2010214.49     13627438.55      2009565.17     13627320.49
#Sta/Elev= 30
  3177.8   718.5  3321.8  714.17  3395.4  712.86  3420.2  708.75 3766.89700.1538
  3945.4  696.82    4215  700.28  4364.2  700.52  4400.7  700.21  4456.8  700.14
  4613.3  698.38    4671  691.31    4692  691.22  4723.5  699.06  4812.9  701.02
  4885.3  700.54  4947.9   698.2    4980  692.03  4985.5  686.97  4988.3  686.17
  5007.5  686.97  5012.1  690.93  5096.7  695.92 5253.42 700.154  5414.9  704.23
  5489.9  709.81  5543.3  705.86  5648.7  704.82    5669  709.44  5709.5  708.49
#Mann= 13 ,-1 , 0
  3177.8      .1       0  3321.8     .08       0  3420.2      .1       0
    4215     .05       0  4364.2      .1       0  4400.7     .05       0
  4456.8      .1       0  4613.3     .12       0  4812.9      .1       0
  4885.3     .12       0  4985.5     .07       0  5007.5     .12       0
  5096.7      .1       0
Bank Sta=3766.89,5253.42
XS Rating Curve= 0 ,0
Exp/Cntr=0.3,0.1

Type RM Length L Ch R = 1 ,78282   ,215,215,215
BEGIN DESCRIPTION:
Mapping XS ccbd3299
END DESCRIPTION:
XS GIS Cut Line= 3
      2012146.23     13627437.77      2010783.93     13627313.55
      2009688.36      13627077.8
#Sta/Elev= 30
  3117.4  721.11    3349  714.82  3379.7  712.64  3424.1  713.54  3447.5  710.65
  3510.3  707.08 3858.81699.4162  4012.3  695.68  4196.5  697.62  4379.3  698.82
  4514.9  699.27  4699.1  693.92  4772.1  698.93  4862.7  698.17    4965  692.86
    4979  691.17  4984.7  684.94  4987.6  684.14  5006.7  684.94  5016.2  691.62
  5023.2  694.23  5031.9  694.25 5120.14699.4162  5282.1  706.53  5302.6  709.33
    5323  705.19    5330  706.66  5343.5  710.87  5516.7  712.47    5606  712.99
#Mann= 11 ,-1 , 0
  3117.4      .1       0    3349     .08       0  3447.5      .1       0
  4196.5     .05       0  4379.3      .1       0  4772.1     .12       0
  4984.7     .07       0  5006.7     .12       0  5031.9     .16       0
    5330      .1       0  5516.7     .05       0
Bank Sta=3858.81,5120.14
XS Rating Curve= 0 ,0
Exp/Cntr=0.3,0.1

Type RM Length L Ch R = 1 ,78067   ,286,286,286
BEGIN DESCRIPTION:
Mapping XS 2b596d01
END DESCRIPTION:
XS GIS Cut Line= 3
      2011838.98     13626901.32       2010759.3     13627088.57
      2009835.99     13626948.96
#Sta/Elev= 30
  3521.4  718.77  3527.2  718.63  3718.3  713.41 4146.07699.0229  4249.7  696.42
  4266.3  696.22  4286.6  692.53  4302.2  691.68  4332.6  691.44    4378  695.95
  4571.5  699.15  4864.3   697.6  4936.2  695.89  4946.2  695.96  4975.5  692.13
  4984.8  684.92  4987.6  684.12  5006.8  684.92    5016  690.12  5026.1  691.84
  5126.7   697.1 5139.16699.0223  5177.8  703.28  5268.8  707.32  5280.3  709.83
  5299.2  705.33  5309.3  705.84  5319.4  709.79    5343  709.62    5551  711.16
#Mann= 9 ,-1 , 0
  3521.4     .08       0  3527.2      .1       0  4249.7     .05       0
  4302.2      .1       0  4936.2     .12       0  4984.8     .07       0
  5006.8     .12       0  5126.7     .16       0    5343      .1       0
Bank Sta=4146.07,5139.16
XS Rating Curve= 0 ,0
Exp/Cntr=0.3,0.1

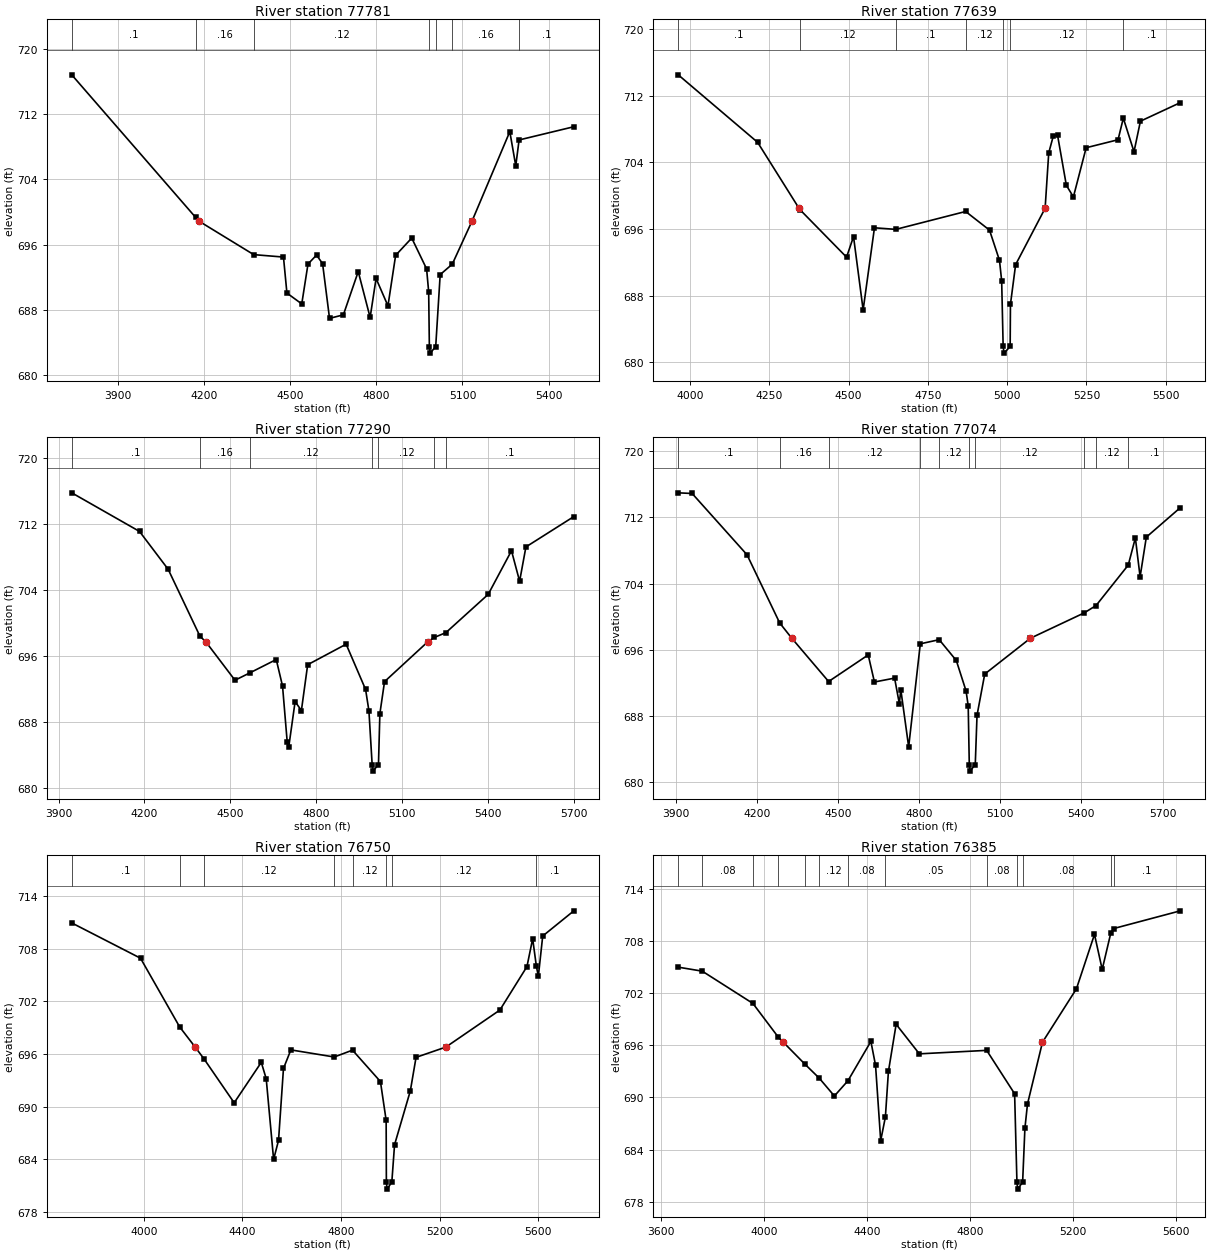
Type RM Length L Ch R = 1 ,77781   ,142,142,142
BEGIN DESCRIPTION:
Mapping XS 7e24561a
END DESCRIPTION:
XS GIS Cut Line= 2
      2011568.95     13626448.92       2009879.5     13626899.87
#Sta/Elev= 30
  3739.2  716.81  4170.6  699.34 4182.13698.8835  4372.8  694.78  4476.5  694.48
  4488.5  690.07  4540.2  688.74  4561.9  693.63  4591.6  694.72  4612.7  693.68
  4636.9  686.97  4685.1   687.4  4736.9   692.7  4778.3  687.08    4799  691.86
  4840.4   688.5  4867.1  694.69  4923.2  696.81    4975  693.03  4982.2  690.22
  4984.6  683.51  4987.5  682.71  5006.7  683.51  5022.3  692.33  5064.4  693.61
 5133.12698.8831  5264.8  709.85  5285.5  705.66  5297.1  708.83  5487.8  710.45
#Mann= 7 ,-1 , 0
  3739.2      .1       0  4170.6     .16       0  4372.8     .12       0
  4984.6     .07       0  5006.7     .12       0  5064.4     .16       0
  5297.1      .1       0
Bank Sta=4182.13,5133.12
XS Rating Curve= 0 ,0
Exp/Cntr=0.3,0.1

Type RM Length L Ch R = 1 ,77639   ,349,349,349
BEGIN DESCRIPTION:
Mapping XS 9bb0de28
END DESCRIPTION:
XS GIS Cut Line= 3
      2011230.33     13626162.49      2010161.39     13626728.05
      2009789.95     13626769.71
#Sta/Elev= 30
    3963  714.53  4213.3  706.42 4343.77698.4964  4346.5  698.34  4493.7  692.62
  4515.7  695.09    4546  686.28  4581.7  696.15    4649  695.96  4869.2  698.11
  4944.5  695.87  4975.9  692.24  4982.8  689.79  4987.5  681.89  4990.4  681.09
  5009.6  681.89  5010.5  686.95  5026.8  691.72 5119.83698.4983  5131.2  705.15
  5145.6  707.18  5158.9   707.3  5186.8  701.25    5209  699.86  5249.2  705.77
  5349.8  706.73  5366.4  709.32  5400.1  705.29  5420.3  708.96  5546.1  711.19
#Mann= 7 ,-1 , 0
    3963      .1       0  4346.5     .12       0    4649      .1       0
  4869.2     .12       0  4987.5     .07       0  5009.6     .12       0
  5366.4      .1       0
Bank Sta=4343.77,5119.83
XS Rating Curve= 0 ,0
Exp/Cntr=0.3,0.1

Type RM Length L Ch R = 1 ,77290   ,216,216,216
BEGIN DESCRIPTION:
CHACON CREEK 91.0
END DESCRIPTION:
XS GIS Cut Line= 3
      2011182.22     13626014.51      2010515.56     13626177.01
      2009572.65     13626679.01
#Sta/Elev= 30
  3945.9   715.8  4182.6  711.12  4282.7  706.53  4393.9  698.41 4414.41 697.735
  4516.2  693.08  4568.6  693.98  4660.4  695.59  4682.4  692.37  4698.7  685.59
  4704.3  685.04  4726.3  690.49  4748.3  689.41  4770.2  694.96  4904.6  697.45
  4972.6  691.96  4984.2  689.38  4995.5  682.86  4998.4  682.06  5017.6  682.86
  5022.5  689.03  5038.8  692.91 5189.78 697.735  5212.9  698.27  5253.2  698.85
    5401  703.49  5482.4  708.78  5510.8  705.08  5532.8  709.24  5700.3  712.92
#Mann= 7 ,-1 , 0
  3945.9      .1       0  4393.9     .16       0  4568.6     .12       0
  4995.5     .07       0  5017.6     .12       0  5212.9     .16       0
  5253.2      .1       0
Bank Sta=4414.41,5189.78
XS Rating Curve= 0 ,0
Exp/Cntr=0.3,0.1

Type RM Length L Ch R = 1 ,77074   ,324,324,324
BEGIN DESCRIPTION:
CHACON CREEK 90.0
END DESCRIPTION:
XS GIS Cut Line= 3
       2011125.7     13625993.75      2010657.92     13625915.55
      2009402.38     13626490.77
#Sta/Elev= 30
  3910.1  714.97  3961.5  714.89  4164.3  707.49    4285  699.26 4329.77697.4131
  4465.8  692.19  4612.1   695.4  4635.1  692.13  4709.6   692.6  4727.1  689.52
  4732.6   691.2  4761.6   684.3  4804.6  696.74  4874.4  697.24  4937.6  694.73
  4973.7  691.05  4981.6  689.25  4985.6  682.17  4988.5  681.37  5007.7  682.17
  5014.2  688.11  5042.7  693.09 5211.45697.4132    5410  700.47    5454  701.36
  5573.1  706.25  5599.3  709.53  5616.8  704.83  5639.8  709.62  5765.4  713.18
#Mann= 10 ,-1 , 0
  3910.1      .1       0    4285     .16       0  4465.8     .12       0
  4804.6     .16       0  4874.4     .12       0  4985.6     .07       0
  5007.7     .12       0    5410      .1       0    5454     .12       0
  5573.1      .1       0
Bank Sta=4329.77,5211.45
XS Rating Curve= 0 ,0
Exp/Cntr=0.3,0.1

Type RM Length L Ch R = 1 ,76750   ,365,365,365
BEGIN DESCRIPTION:
Mapping XS 801ea791
END DESCRIPTION:
XS GIS Cut Line= 3
      2011223.86     13625780.13      2010262.09     13625769.72
      2009281.26     13626210.14
#Sta/Elev= 30
  3707.9  710.94  3986.8  706.92  4145.6  699.09 4208.47696.7916    4244  695.46
  4366.8  690.44  4476.8  695.05  4496.8  693.18  4526.8  683.98  4546.8  686.16
  4566.8  694.35  4596.8  696.47  4772.7  695.66  4846.9  696.44  4960.2  692.86
  4983.4  688.44  4984.3   681.4  4987.2   680.6  5006.4   681.4  5017.5  685.66
  5081.5   691.8  5104.7  695.62 5225.76696.7916  5444.8  701.01  5554.6  705.96
  5577.8  709.14  5592.9     706  5600.9  704.86  5618.6  709.45  5744.9  712.32
#Mann= 8 ,-1 , 0
  3707.9      .1       0  4145.6     .16       0    4244     .12       0
  4772.7     .16       0  4846.9     .12       0  4984.3     .07       0
  5006.4     .12       0  5592.9      .1       0
Bank Sta=4208.47,5225.76
XS Rating Curve= 0 ,0
Exp/Cntr=0.3,0.1

Type RM Length L Ch R = 1 ,76385   ,65,65,65
BEGIN DESCRIPTION:
CHACON CREEK 89.0
END DESCRIPTION:
XS GIS Cut Line= 6
      2011178.76     13625644.72      2010765.58     13625639.72
      2010581.53     13625700.27      2010453.06     13625641.24
      2010029.45     13625630.83      2009251.71     13625655.13
#Sta/Elev= 30
  3667.9  704.98  3761.2  704.52  3957.9  700.81  4056.3  696.94 4076.06 696.347
  4159.4  693.84  4215.4  692.22  4274.4  690.16  4327.2  691.92  4416.2  696.44
  4434.3  693.69  4454.3  685.03  4472.5  687.74  4484.3  692.98  4514.3  698.41
  4604.4  695.01    4866  695.41  4974.5  690.42  4983.5  680.25  4986.4  679.45
  5005.6  680.25  5014.5  686.46  5024.5  689.24 5082.71696.3474  5214.6  702.49
  5284.7  708.75  5314.7  704.72  5347.8  708.87    5359  709.42  5618.1  711.46
#Mann= 13 ,-1 , 0
  3667.9      .1       0  3761.2     .08       0  3957.9     .05       0
  4056.3     .08       0  4159.4     .05       0  4215.4     .12       0
  4327.2     .08       0  4472.5     .05       0    4866     .08       0
  4983.5     .07       0  5005.6     .08       0  5347.8     .12       0
    5359      .1       0
Bank Sta=4076.06,5082.71
XS Rating Curve= 0 ,0
Exp/Cntr=0.3,0.1

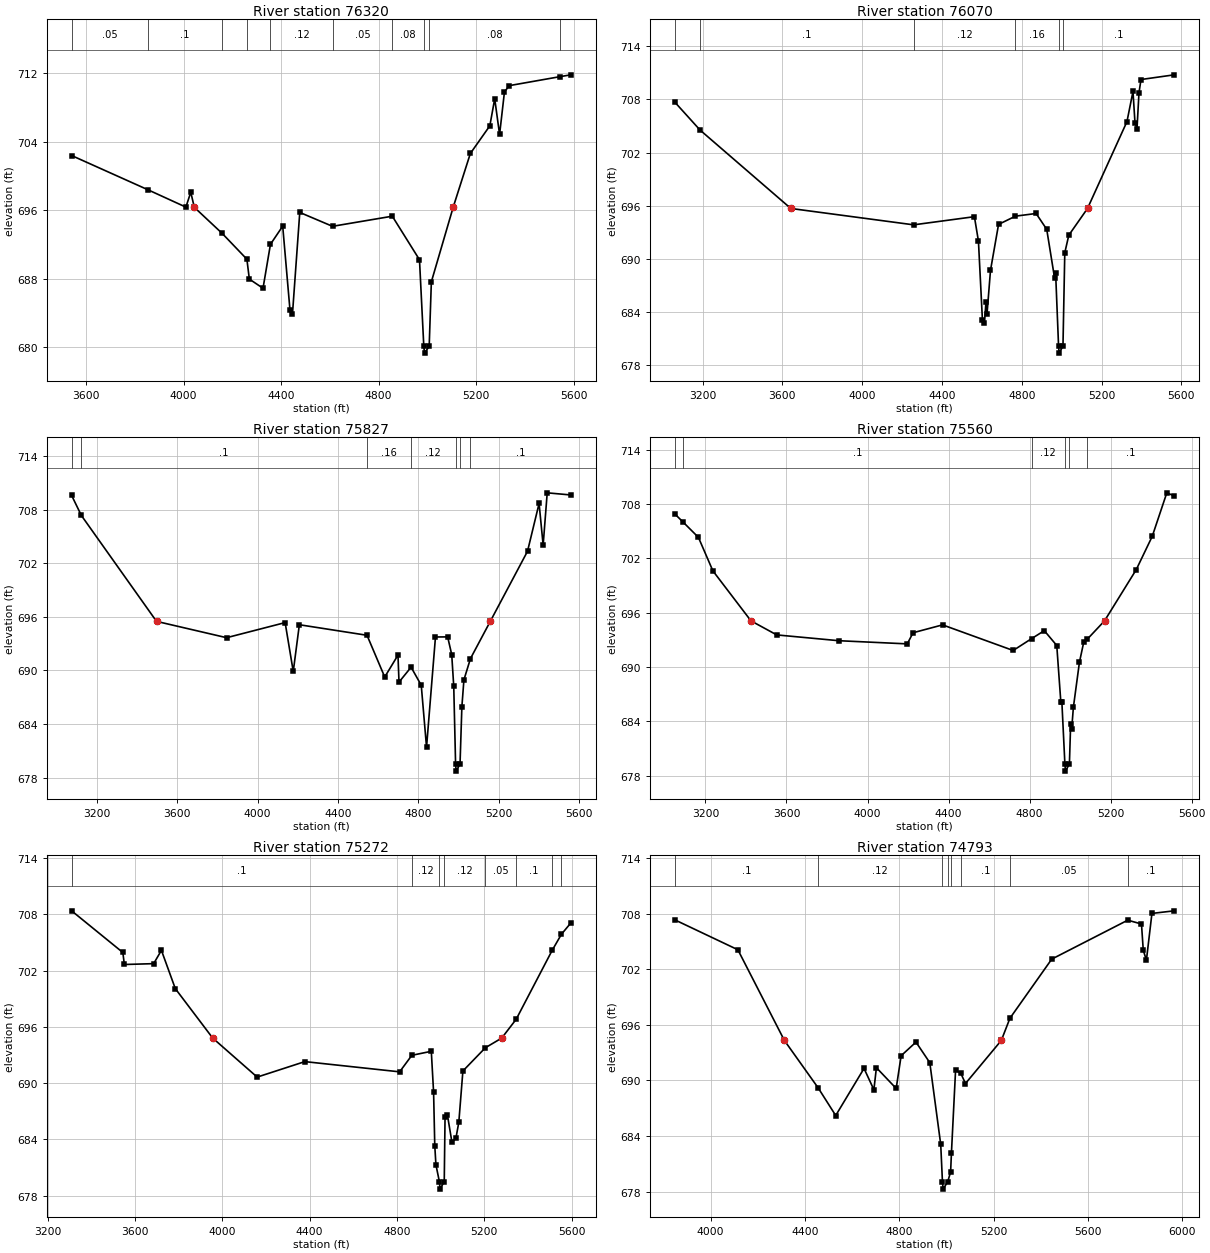
Type RM Length L Ch R = 1 ,76320   ,250,250,250
BEGIN DESCRIPTION:
Mapping XS 853e672f
END DESCRIPTION:
XS GIS Cut Line= 6
      2011303.74     13625557.91      2010720.42      13625571.8
      2010609.31     13625616.94      2010473.89     13625568.33
      2009897.51     13625575.27      2009272.53     13625575.27
#Sta/Elev= 30
  3540.3  702.38  3854.6  698.37  4009.2  696.36  4029.2   698.1  4043.7696.3386
  4158.2  693.29  4259.5  690.28  4269.6  687.96  4325.7  686.89  4356.2  692.02
  4406.5  694.14  4436.5   684.3  4446.5  683.86  4476.5  695.74  4610.9  694.12
  4856.2   695.3  4967.8  690.22  4985.5  680.12  4988.4  679.32  5007.6  680.12
  5016.5  687.64 5105.98696.3383  5176.5  702.62  5256.5  705.85  5276.5  709.01
  5296.5  704.84  5316.5  709.81  5336.5  710.54  5545.1  711.59    5589   711.8
#Mann= 10 ,-1 , 0
  3540.3     .05       0  3854.6      .1       0  4158.2     .05       0
  4259.5     .08       0  4356.2     .12       0  4610.9     .05       0
  4856.2     .08       0  4985.5     .07       0  5007.6     .08       0
  5545.1     .05       0
Bank Sta=4043.7,5105.98
XS Rating Curve= 0 ,0
Exp/Cntr=0.3,0.1

Type RM Length L Ch R = 1 ,76070   ,243,243,243
BEGIN DESCRIPTION:
CHACON CREEK 88.0
END DESCRIPTION:
XS GIS Cut Line= 4
       2011741.2      13625579.4      2011118.41     13625214.64
      2010105.84     13625342.63      2009349.41     13625422.44
#Sta/Elev= 30
  3061.5  707.68  3187.3  704.55 3642.36695.7064  4258.2  693.86  4562.8  694.78
    4583  692.02  4603.1  683.08  4613.2  682.76  4620.8  685.19  4625.9  683.79
  4643.4  688.72  4683.8  693.91  4768.8  694.84  4872.1  695.14  4925.4  693.35
    4965  687.82    4970  688.41  4984.7  680.19  4987.6  679.39  5006.8  680.19
  5015.9  690.71    5036  692.69 5129.82695.7064  5327.6   705.5  5357.8   708.9
  5367.8   705.4  5377.9  704.68  5387.9  708.75    5398  710.25  5564.5  710.78
#Mann= 6 ,-1 , 0
  3061.5     .05       0  3187.3      .1       0  4258.2     .12       0
  4768.8     .16       0  4984.7     .07       0  5006.8      .1       0
Bank Sta=3642.36,5129.82
XS Rating Curve= 0 ,0
Exp/Cntr=0.3,0.1

Type RM Length L Ch R = 1 ,75827   ,267,267,267
BEGIN DESCRIPTION:
Mapping XS 6dc50488
END DESCRIPTION:
XS GIS Cut Line= 3
      2011838.43     13625114.14      2011110.04     13624966.61
      2009388.51     13625210.49
#Sta/Elev= 30
  3075.9  709.59  3124.2  707.35 3497.95695.4968  3846.4  693.67  4137.3  695.36
  4177.7  689.89    4208  695.12  4544.4  693.94  4632.4  689.27  4698.3  691.72
  4703.4   688.7  4763.5  690.37    4814  688.35  4840.3  681.42  4884.7  693.75
  4945.3  693.76  4965.5  691.78  4975.6  688.21  4984.7  679.54  4987.6  678.74
  5006.8  679.54    5016  685.95  5026.1  688.95  5058.6  691.33  5157.2695.4971
  5342.3  703.34  5399.8  708.69    5420  704.03  5440.2  709.88  5557.8  709.64
#Mann= 7 ,-1 , 0
  3075.9     .08       0  3124.2      .1       0  4544.4     .16       0
  4763.5     .12       0  4984.7     .07       0  5006.8     .12       0
  5058.6      .1       0
Bank Sta=3497.95,5157.2
XS Rating Curve= 0 ,0
Exp/Cntr=0.3,0.1

Type RM Length L Ch R = 1 ,75560   ,288,288,288
BEGIN DESCRIPTION:
Mapping XS 277155f8
END DESCRIPTION:
XS GIS Cut Line= 3
      2011838.48      13624808.6      2010969.11     13624636.15
      2009429.35     13624981.39
#Sta/Elev= 30
  3049.6   706.9  3088.2  706.05  3165.3  704.33  3236.7  700.63 3424.83695.1033
    3552  693.55  3858.5  692.91  4196.3  692.56  4224.8  693.79  4370.5  694.66
    4719  691.83  4810.7  693.15  4872.7  694.02  4934.2  692.38  4954.3  686.13
  4959.4  686.14  4974.3   679.3  4977.3   678.5  4996.6   679.3  5002.8  683.75
  5007.9  683.17  5016.2  685.55  5046.1  690.53  5067.4  692.76  5084.9  693.08
 5169.96695.1031  5326.7  700.77  5405.6  704.45  5477.4  709.25  5513.9  708.91
#Mann= 6 ,-1 , 0
  3049.6     .05       0  3088.2      .1       0  4810.7     .12       0
  4974.3     .07       0  4996.6     .12       0  5084.9      .1       0
Bank Sta=3424.83,5169.96
XS Rating Curve= 0 ,0
Exp/Cntr=0.3,0.1

Type RM Length L Ch R = 1 ,75272   ,479,479,479
BEGIN DESCRIPTION:
CHACON CREEK 87.0
END DESCRIPTION:
XS GIS Cut Line= 3
      2011394.02     13623822.48      2010932.23     13624269.72
      2009365.99     13624769.44
#Sta/Elev= 30
  3309.7  708.37  3544.3  703.93  3551.2  702.65  3685.5  702.74    3721  704.16
  3784.6  700.08 3955.96694.8085  4159.6  690.65    4378   692.3  4812.3  691.21
  4868.1  692.97  4957.3   693.4  4967.8  689.03  4973.2  683.34  4978.5   681.3
  4994.3  679.51  4997.3  678.71  5016.6  679.51  5020.3  686.44  5030.8  686.66
  5051.8  683.71  5069.8  684.11  5083.3  685.83    5102   691.3  5205.1  693.78
 5279.96 694.809  5346.3  696.82    5511  704.16  5553.6  705.88  5596.6  707.08
#Mann= 8 ,-1 , 0
  3309.7      .1       0  4868.1     .12       0  4994.3     .07       0
  5016.6     .12       0  5205.1     .05       0  5346.3      .1       0
    5511     .05       0  5553.6      .1       0
Bank Sta=3955.96,5279.96
XS Rating Curve= 0 ,0
Exp/Cntr=0.3,0.1

Type RM Length L Ch R = 1 ,74793   ,926,926,926
BEGIN DESCRIPTION:
CHACON CREEK 86.0
END DESCRIPTION:
XS GIS Cut Line= 4
      2010850.65     13623844.36      2010319.38     13624068.33
      2009555.27     13624309.22      2009129.12     13624912.08
#Sta/Elev= 30
  3849.3  707.32  4115.9   704.1 4313.06694.3178  4456.5  689.19  4530.6  686.22
  4650.6   691.3  4692.4     689  4703.1  691.38  4786.9  689.14  4807.9  692.67
  4870.8  694.14  4929.4  691.92  4975.7   683.1    4983  679.08    4986  678.28
  5005.3  679.08  5017.6  680.13  5021.2  682.23  5038.6  691.09  5060.1  690.82
  5080.5  689.67 5232.51694.3184    5269  696.71  5446.2  703.09  5768.3  707.29
  5826.6  706.88  5834.2  704.04  5847.5  702.98  5870.9  708.02  5965.3   708.3
#Mann= 8 ,-1 , 0
  3849.3      .1       0  4456.5     .12       0    4983     .07       0
  5005.3     .12       0  5021.2     .07       0  5060.1      .1       0
    5269     .05       0  5768.3      .1       0
Bank Sta=4313.06,5232.51
XS Rating Curve= 0 ,0
Exp/Cntr=0.3,0.1