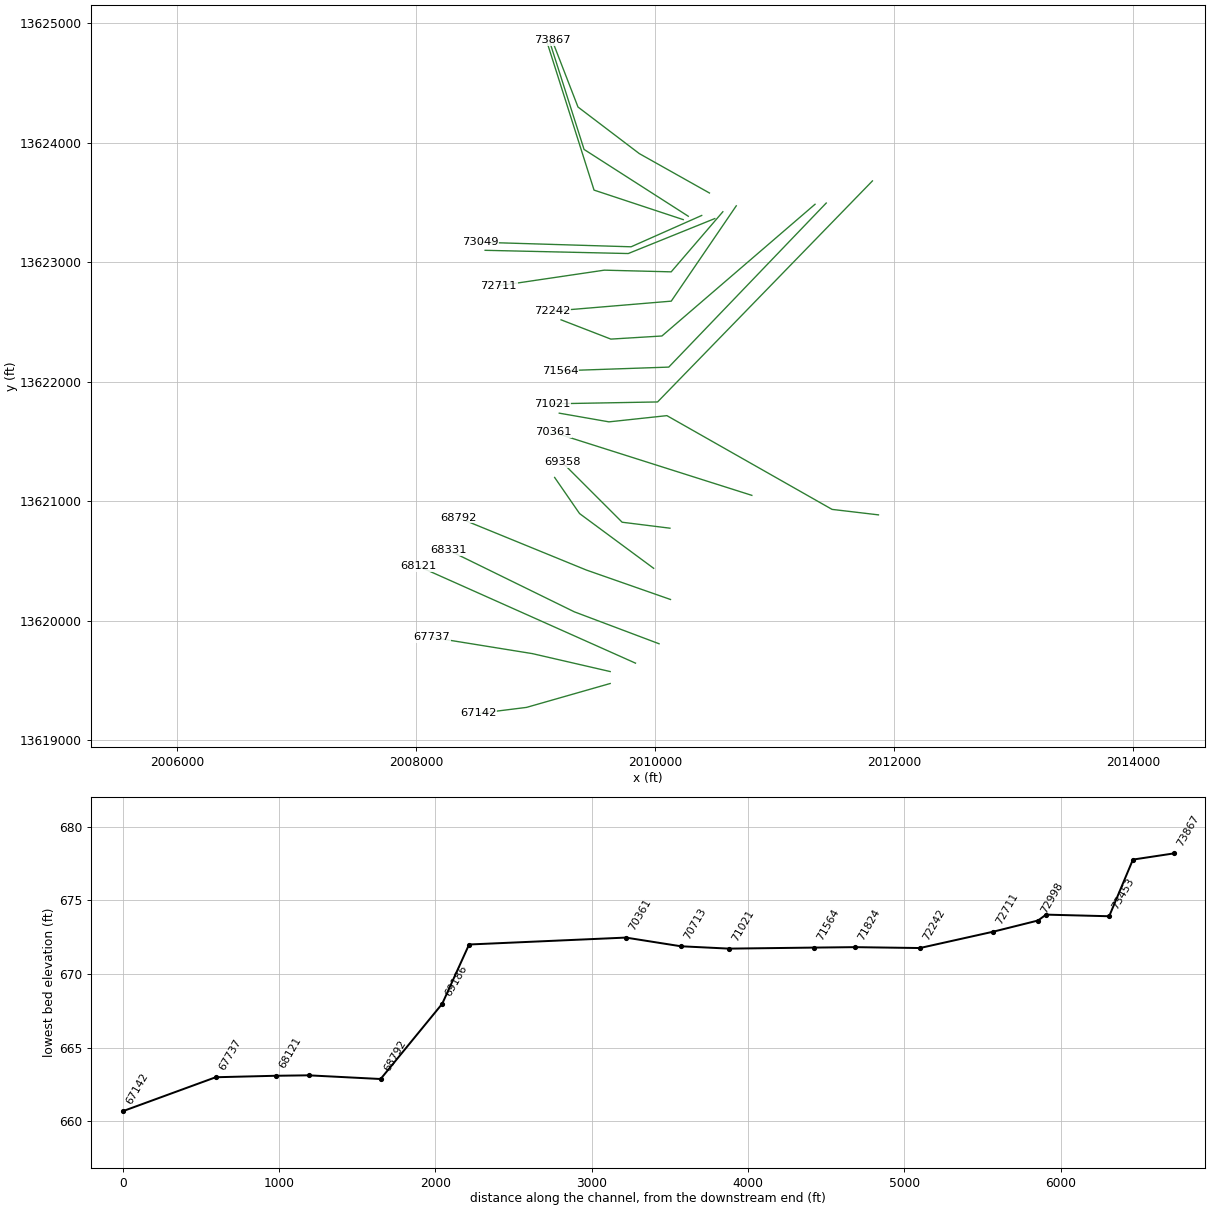
HEC-RAS study CHACON CREEK.prj: CHACON CREEK Base Level Engineering

--- CHACON CREEK.g01 (geometry) --- (continued)

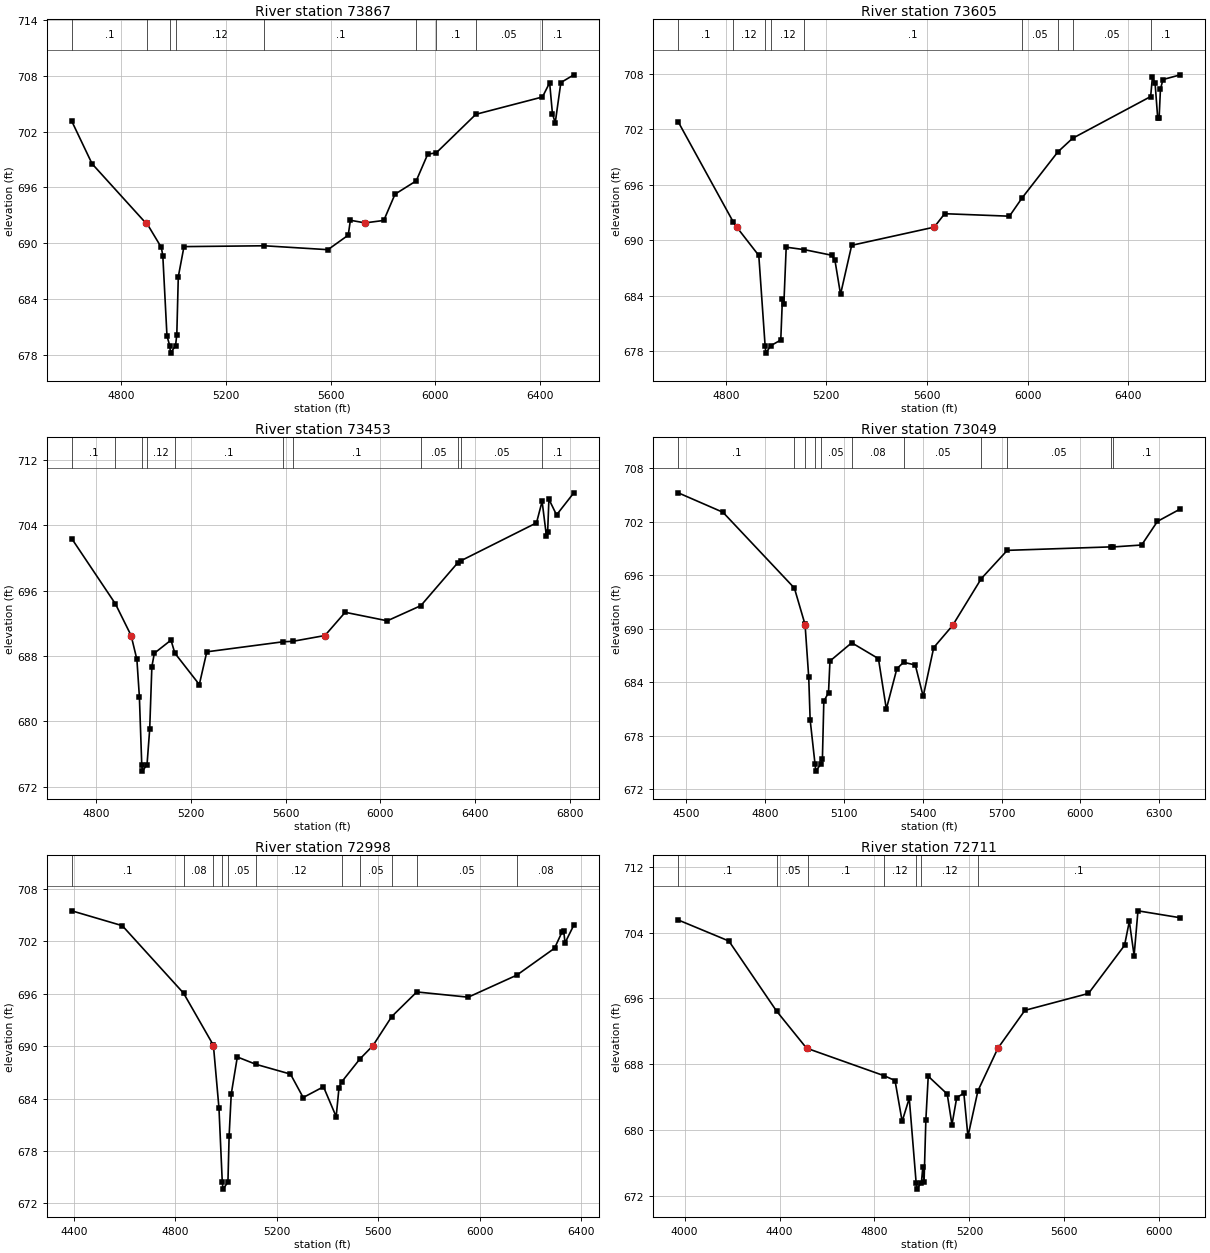
Type RM Length L Ch R = 1 ,73867   ,262,262,262
BEGIN DESCRIPTION:
Mapping XS 6cfc4dd8
END DESCRIPTION:
XS GIS Cut Line= 4
      2010455.19     13623580.65      2009868.43     13623910.49
      2009355.79     13624300.21      2009138.62     13624861.27
#Sta/Elev= 30
  4610.4  703.11  4687.9  698.54 4892.82692.1877  4896.9  692.16  4952.5  689.56
  4958.3  688.67  4974.2  680.06  4984.7     679  4987.7   678.2    5007     679
  5011.8   680.2  5017.5   686.4  5039.2  689.64  5346.6  689.73  5589.3  689.31
  5666.9  690.87  5675.1  692.47 5731.12692.1874  5802.8  692.45  5845.7  695.27
  5926.7   696.7  5970.7  699.57  6003.2  699.71  6154.7  703.85  6409.1  705.71
  6436.6  707.24  6447.4  703.88    6458  702.95  6479.5  707.26  6529.1  708.09
#Mann= 9 ,-1 , 0
  4610.4      .1       0  4896.9     .12       0  4984.7     .07       0
    5007     .12       0  5346.6      .1       0  5926.7     .05       0
  6003.2      .1       0  6154.7     .05       0  6409.1      .1       0
Bank Sta=4892.82,5731.12
XS Rating Curve= 0 ,0
Exp/Cntr=0.3,0.1

Type RM Length L Ch R = 1 ,73605   ,152,152,152
BEGIN DESCRIPTION:
Mapping XS 0b758969
END DESCRIPTION:
XS GIS Cut Line= 3
      2010278.14     13623386.18      2009406.62     13623945.21
      2009114.52     13624860.63
#Sta/Elev= 30
  4611.1  702.79  4830.4  691.94 4843.77 691.406  4931.4  688.34  4956.5  678.58
  4959.5  677.78  4978.8  678.58  5018.8   679.2  5025.2  683.59  5031.1  683.12
  5040.4  689.24  5112.6  688.97  5220.7  688.37    5234  687.85  5256.4  684.14
  5300.7  689.44 5628.92691.4064  5670.4  692.86    5928  692.59  5977.6  694.54
  6120.4  699.54  6178.8  701.01  6489.5  705.53  6496.5  707.65    6507  707.01
  6517.5  703.21  6523.2  703.25  6528.4  706.33  6538.5  707.37  6607.4  707.88
#Mann= 9 ,-1 , 0
  4611.1      .1       0  4830.4     .12       0  4956.5     .07       0
  4978.8     .12       0  5112.6      .1       0  5977.6     .05       0
  6120.4      .1       0  6178.8     .05       0  6489.5      .1       0
Bank Sta=4843.77,5628.92
XS Rating Curve= 0 ,0
Exp/Cntr=0.3,0.1

Type RM Length L Ch R = 1 ,73453   ,404,404,404
BEGIN DESCRIPTION:
Mapping XS 47134716
END DESCRIPTION:
XS GIS Cut Line= 3
      2010235.86     13623357.83      2009489.95     13623604.93
      2009086.51     13624875.23
#Sta/Elev= 30
  4697.9  702.34  4882.1  694.37 4948.28690.5013  4972.7  687.58  4983.2  683.02
  4993.2  674.73  4996.2  673.93  5015.5  674.73  5026.7  679.05  5035.9  686.71
  5046.4  688.34  5116.6  689.94  5132.8  688.35  5236.1  684.51  5267.7  688.51
  5590.3  689.74  5629.8  689.79 5766.25690.5015  5851.6  693.34  6029.3   692.3
  6170.8  694.15  6325.7  699.36  6341.4  699.66  6658.9  704.27  6682.6   706.9
  6700.7  702.68    6706   703.2  6711.3  707.16  6743.5  705.24  6816.5  707.94
#Mann= 11 ,-1 , 0
  4697.9      .1       0  4882.1     .12       0  4993.2     .07       0
  5015.5     .12       0  5132.8      .1       0  5590.3     .16       0
  5629.8      .1       0  6170.8     .05       0  6325.7      .1       0
  6341.4     .05       0  6682.6      .1       0
Bank Sta=4948.28,5766.25
XS Rating Curve= 0 ,0
Exp/Cntr=0.3,0.1

Type RM Length L Ch R = 1 ,73049   ,51,51,51
BEGIN DESCRIPTION:
CHACON CREEK 85.0
END DESCRIPTION:
XS GIS Cut Line= 3
      2010390.35     13623392.56      2009799.85     13623130.39
      2008538.11     13623168.54
#Sta/Elev= 30
    4471  705.24    4641  703.06  4912.5  694.56  4952.9  690.49 4953.32690.3679
    4967  684.56  4972.4  679.79  4990.9  674.84  4993.9  674.04  5013.2  674.84
    5019  675.41  5024.4  681.87  5042.2  682.84  5047.7  686.38  5130.4  688.43
    5232  686.65    5262     681    5302  685.52  5327.5  686.24    5372  685.94
  5402.1  682.42  5442.1  687.89  5513.8690.3674  5623.1  695.63  5721.6  698.79
  6115.7  699.18  6122.8  699.17  6232.4  699.39  6292.5  702.04  6379.4  703.43
#Mann= 11 ,-1 , 0
    4471      .1       0  4912.5     .12       0  4952.9     .05       0
  4990.9     .04       0  5013.2     .05       0  5130.4     .08       0
  5327.5     .05       0  5623.1     .08       0  5721.6     .05       0
  6115.7     .08       0  6122.8      .1       0
Bank Sta=4953.32,5513.8
XS Rating Curve= 0 ,0
Exp/Cntr=0.3,0.1

Type RM Length L Ch R = 1 ,72998   ,287,287,287
BEGIN DESCRIPTION:
CHACON CREEK 84.0
END DESCRIPTION:
XS GIS Cut Line= 3
      2010499.68      13623366.5      2009775.98     13623073.97
      2008578.97     13623100.87
#Sta/Elev= 30
  4392.1  705.48  4591.1  703.78  4832.5  696.06    4950   690.1  4950.2690.0462
    4972   682.9    4985  674.44    4988  673.64  5007.3  674.44    5012  679.74
  5020.3  684.51  5044.3  688.76  5117.5  687.92  5253.7   686.8  5303.7  684.12
  5383.7  685.35  5433.7  681.93  5444.9  685.25  5454.9  685.89  5527.1  688.53
 5578.28690.0464  5652.8  693.39  5751.3   696.2  5953.9   695.6  6145.2  698.12
    6294   701.2    6324  703.09  6330.2  703.18  6335.2  701.81    6370  703.85
#Mann= 11 ,-1 , 0
  4392.1      .1       0  4832.5     .08       0    4950     .05       0
    4985     .04       0  5007.3     .05       0  5117.5     .12       0
  5454.9      .1       0  5527.1     .05       0  5652.8     .08       0
  5751.3     .05       0  6145.2     .08       0
Bank Sta=4950.2,5578.28
XS Rating Curve= 0 ,0
Exp/Cntr=0.3,0.1

Type RM Length L Ch R = 1 ,72711   ,469,469,469
BEGIN DESCRIPTION:
CHACON CREEK 83.0
END DESCRIPTION:
XS GIS Cut Line= 4
      2010567.42      13623423.8      2010135.19     13622920.66
       2009575.6     13622934.79       2008692.4     13622804.01
#Sta/Elev= 30
    3973  705.52  4186.4  702.97  4387.5  694.47 4513.94689.9666    4521   689.9
  4840.9  686.63  4886.6  686.05  4916.6   681.1  4946.6   683.9  4975.5  673.68
  4978.5  672.88  4997.8  673.68  5003.9  675.61  5008.9  673.69  5016.6  681.31
  5026.6  686.57  5106.6  684.41  5126.6   680.7  5146.7  683.98  5176.7  684.51
  5193.9  679.27    5236   684.8 5320.09689.9666  5433.9  694.56  5701.9  696.61
  5853.8  702.44    5874  705.35  5894.2  701.21  5910.4  706.63  6088.9  705.79
#Mann= 7 ,-1 , 0
    3973      .1       0  4387.5     .05       0    4521      .1       0
  4840.9     .12       0  4975.5     .07       0  4997.8     .12       0
    5236      .1       0
Bank Sta=4513.94,5320.09
XS Rating Curve= 0 ,0
Exp/Cntr=0.3,0.1

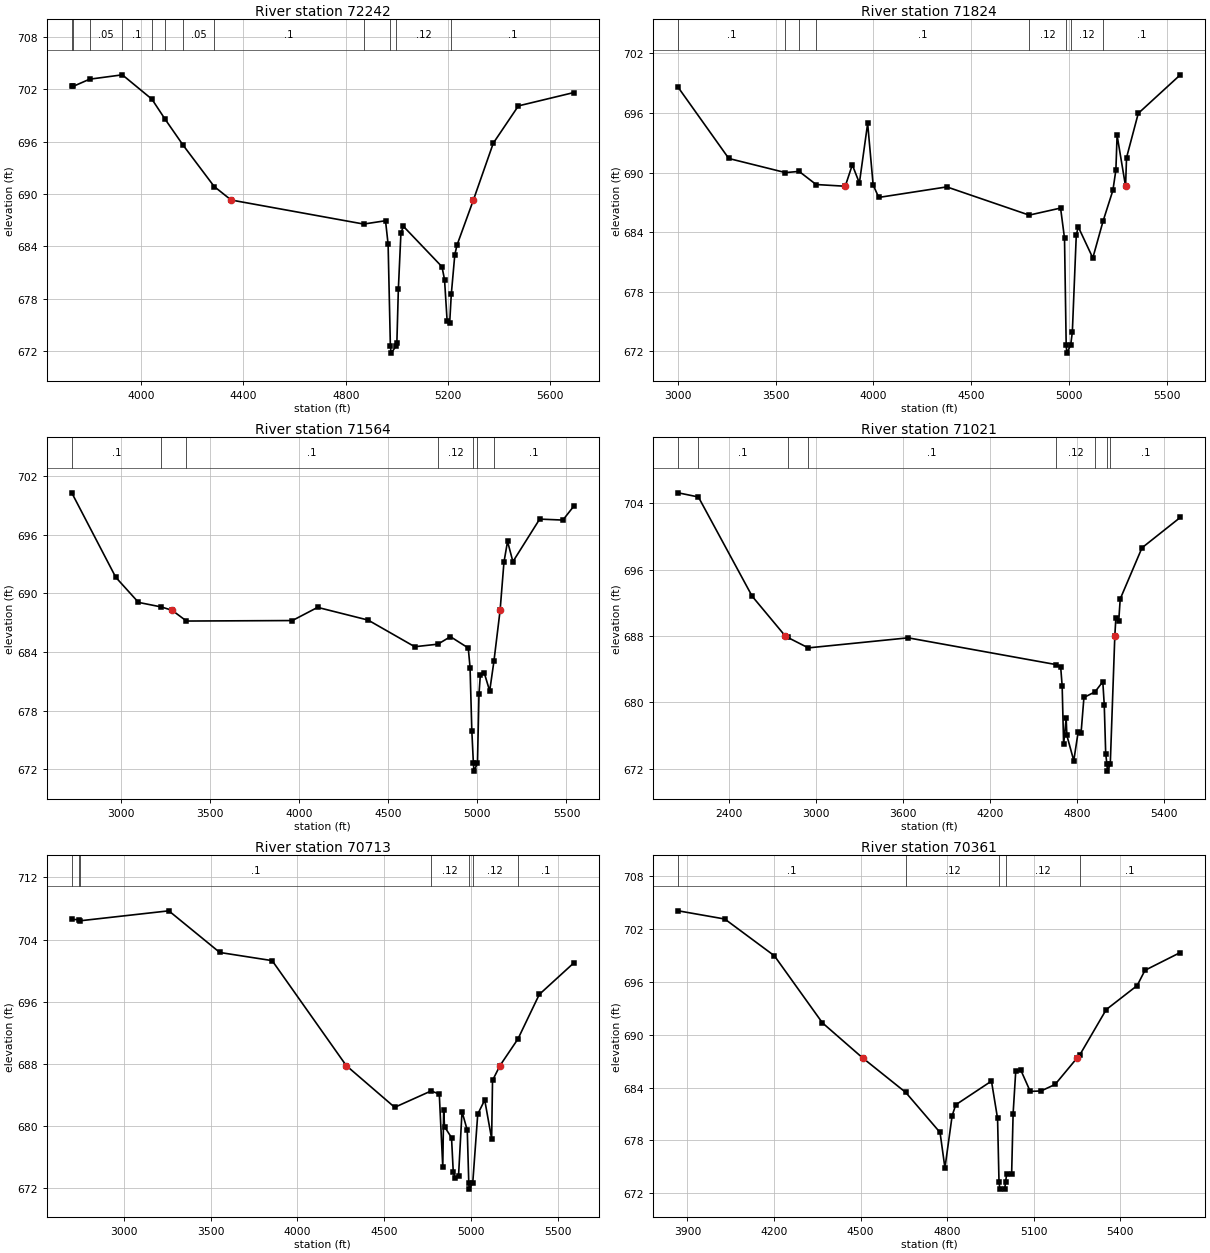
Type RM Length L Ch R = 1 ,72242   ,418,418,418
BEGIN DESCRIPTION:
CHACON CREEK 82.0
END DESCRIPTION:
XS GIS Cut Line= 3
       2010679.5     13623473.36      2010135.79     13622675.46
      2009141.01     13622592.13
#Sta/Elev= 30
  3728.4   702.4  3734.8  702.35  3798.2  703.16  3926.2  703.66  4041.8  700.87
  4093.3  698.58  4163.6  695.61  4285.5  690.86 4351.69689.3151  4870.1  686.56
  4955.6  686.94  4965.7  684.25  4974.6  672.57  4977.6  671.77  4996.9  672.57
  4999.9  672.88  5005.8  679.11  5015.9  685.57  5025.9  686.29  5176.4  681.67
  5186.4   680.2  5196.5  675.48  5206.5  675.23  5212.8  678.49  5226.6  683.05
  5235.1  684.14  5299.3689.3147  5377.1  695.83  5475.3   700.1  5692.2  701.63
#Mann= 12 ,-1 , 0
  3728.4     .05       0  3734.8      .1       0  3798.2     .05       0
  3926.2      .1       0  4041.8     .05       0  4093.3      .1       0
  4163.6     .05       0  4285.5      .1       0  4870.1     .12       0
  4974.6     .07       0  4996.9     .12       0  5212.8      .1       0
Bank Sta=4351.69,5299.3
XS Rating Curve= 0 ,0
Exp/Cntr=0.3,0.1

Type RM Length L Ch R = 1 ,71824   ,260,260,260
BEGIN DESCRIPTION:
Mapping XS f1407246
END DESCRIPTION:
XS GIS Cut Line= 4
      2011338.22     13623486.28      2010057.66     13622383.79
      2009630.58     13622357.75      2009213.91     13622519.21
#Sta/Elev= 30
  3002.8  698.57    3261  691.42  3550.4     690  3620.2  690.12  3707.1   688.8
 3855.86 688.627  3891.9  690.78  3928.1  688.95  3970.3  694.95  3998.3  688.76
  4026.9   687.5  4374.7  688.56  4795.3  685.72  4955.7  686.43  4975.8   683.4
  4984.4  672.63  4987.6  671.83  5007.2  672.63  5015.8  673.95  5035.9   683.7
  5045.9  684.54  5120.4  681.41    5173  685.13  5222.9  688.21  5238.2  690.25
  5244.4  693.75 5287.63688.6276  5292.7  691.51  5352.5  695.96  5567.3  699.84
#Mann= 8 ,-1 , 0
  3002.8      .1       0  3550.4     .05       0  3620.2     .08       0
  3707.1      .1       0  4795.3     .12       0  4984.4     .07       0
  5007.2     .12       0    5173      .1       0
Bank Sta=3855.86,5287.63
XS Rating Curve= 0 ,0
Exp/Cntr=0.3,0.1

Type RM Length L Ch R = 1 ,71564   ,543,543,543
BEGIN DESCRIPTION:
CHACON CREEK 81.0
END DESCRIPTION:
XS GIS Cut Line= 3
      2011431.99      13623496.7      2010114.95     13622123.38
      2009203.47     13622092.13
#Sta/Elev= 30
  2726.7   700.3  2973.4  691.65  3100.7  689.08  3229.1  688.61 3289.09688.2699
  3369.9  687.17  3963.4  687.22  4104.9  688.57  4387.9  687.27  4649.5  684.54
  4779.1   684.8  4849.6  685.57  4949.6  684.41  4959.6  682.41  4969.6  675.91
  4978.3   672.6  4981.5   671.8  5001.1   672.6  5009.7  679.68  5017.3  681.65
  5039.7  681.83  5069.7  680.01  5093.3  683.03 5128.08688.2695  5149.7   693.2
  5169.8  695.33  5199.8  693.25  5349.9  697.61  5479.9  697.51  5541.5  698.94
#Mann= 7 ,-1 , 0
  2726.7      .1       0  3229.1     .05       0  3369.9      .1       0
  4779.1     .12       0  4978.3     .07       0  5001.1     .12       0
  5093.3      .1       0
Bank Sta=3289.09,5128.08
XS Rating Curve= 0 ,0
Exp/Cntr=0.3,0.1

Type RM Length L Ch R = 1 ,71021   ,308,308,308
BEGIN DESCRIPTION:
Mapping XS ab3f1643
END DESCRIPTION:
XS GIS Cut Line= 3
      2011818.41     13623681.71       2010021.2     13621831.71
      2009140.98     13621816.08
#Sta/Elev= 30
  2050.3  705.24  2189.1  704.74  2559.6  692.79 2789.39687.9689  2804.7  687.83
  2946.4  686.57  3634.6  687.78  4653.2  684.56  4685.7  684.24  4695.8  681.97
  4705.8  674.95  4723.3  678.09  4728.3  676.02  4775.8  672.99  4805.8  676.42
  4825.8  676.27  4845.8   680.6  4921.9  681.27  4975.8   682.5  4985.8  679.71
  4995.8  673.83  5004.4  672.53  5007.6  671.73  5027.2  672.53 5058.54687.9676
  5065.8  690.16  5085.8  689.86  5095.8  692.46  5245.8  698.62  5509.9  702.28
#Mann= 8 ,-1 , 0
  2050.3     .05       0  2189.1      .1       0  2804.7     .05       0
  2946.4      .1       0  4653.2     .12       0  4921.9     .16       0
  5004.4     .07       0  5027.2      .1       0
Bank Sta=2789.39,5058.54
XS Rating Curve= 0 ,0
Exp/Cntr=0.3,0.1

Type RM Length L Ch R = 1 ,70713   ,352,352,352
BEGIN DESCRIPTION:
Mapping XS 5b1cc7f0
END DESCRIPTION:
XS GIS Cut Line= 5
      2011868.75     13620886.54      2011480.78     13620932.41
      2010099.33     13621717.13      2009614.95     13621665.04
      2009199.18      13621737.8
#Sta/Elev= 30
  2701.7  706.61  2742.4  706.57  2746.3  706.42    3260  707.71  3553.2  702.35
  3854.6   701.3 4280.83687.7939  4559.6  682.42  4769.6  684.53  4816.2  684.12
  4836.3  674.74  4841.4  682.05  4846.4  679.92  4886.6  678.52  4896.7  674.06
  4906.8  673.38  4926.9  673.58    4947  681.87  4977.2  679.47  4985.9  672.69
  4989.1  671.89  5008.7  672.69  5037.5  681.55  5077.7  683.36  5117.4  678.37
  5122.5  685.88  5165.5687.7935  5268.8  691.22  5391.6  696.95  5590.4  701.01
#Mann= 7 ,-1 , 0
  2701.7     .05       0  2742.4     .08       0  2746.3      .1       0
  4769.6     .12       0  4985.9     .07       0  5008.7     .12       0
  5268.8      .1       0
Bank Sta=4280.83,5165.5
XS Rating Curve= 0 ,0
Exp/Cntr=0.3,0.1

Type RM Length L Ch R = 1 ,70361   ,1003,1003,1003
BEGIN DESCRIPTION:
Mapping XS c088f722
END DESCRIPTION:
XS GIS Cut Line= 2
      2010809.71     13621049.92      2009151.41      13621576.5
#Sta/Elev= 30
    3868  704.06  4029.3  703.13  4201.1  698.96  4367.6  691.35 4506.99687.3702
  4656.5  683.45  4775.3  678.91  4792.2  674.88  4817.2  680.81  4829.7  682.05
  4953.5  684.74  4974.6   680.5  4979.6  673.28  4982.8  672.48  4999.2  672.48
  5002.4  673.28  5006.1  674.19  5023.3  674.14  5028.5  681.05  5037.6  685.88
  5055.5  685.96  5087.8  683.57  5125.3  683.62    5174  684.36  5250.4  687.37
  5260.3  687.75  5351.1  692.85  5458.4  695.58  5485.4  697.31  5607.9  699.33
#Mann= 5 ,-1 , 0
    3868      .1       0  4656.5     .12       0  4979.6     .07       0
  5002.4     .12       0  5260.3      .1       0
Bank Sta=4506.99,5250.4
XS Rating Curve= 0 ,0
Exp/Cntr=0.3,0.1

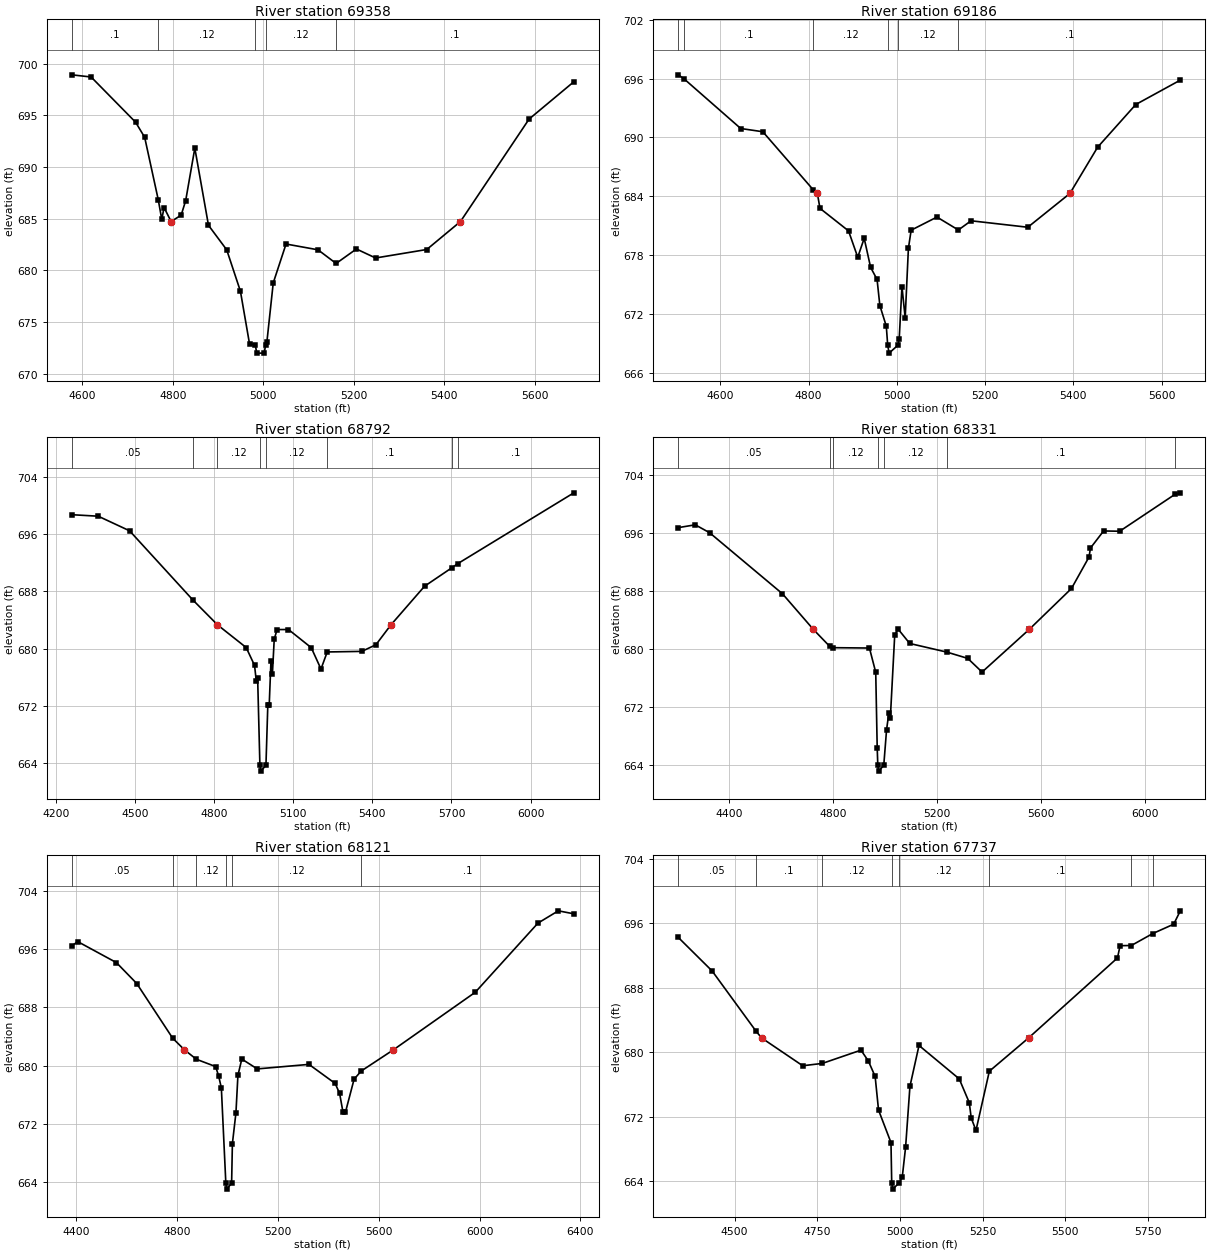
Type RM Length L Ch R = 1 ,69358   ,172,172,172
BEGIN DESCRIPTION:
CHACON CREEK 80.0
END DESCRIPTION:
XS GIS Cut Line= 3
        2010125.       13620775.        2009725.       13620825.
      2009225.02     13621324.98
#Sta/Elev= 30
  4576.8  698.92  4619.6  698.71  4717.9  694.34    4738  692.88  4768.1  686.83
  4775.8  684.94  4780.9  686.09 4796.43684.7358  4818.7  685.35  4828.7  686.76
  4848.9  691.83  4879.1  684.37  4919.4     682  4949.7     678  4969.8  672.92
  4982.6  672.81  4985.8  672.01  5002.3  672.01  5005.5  672.81  5008.2  673.07
  5022.3   678.8  5050.6  682.56  5121.3     682  5161.3  680.68  5206.2  682.08
  5248.6  681.21  5361.8  682.03 5436.34684.7361    5588  694.64    5687  698.25
#Mann= 5 ,-1 , 0
  4576.8      .1       0  4768.1     .12       0  4982.6     .07       0
  5005.5     .12       0  5161.3      .1       0
Bank Sta=4796.43,5436.34
XS Rating Curve= 0 ,0
Exp/Cntr=0.3,0.1

Type RM Length L Ch R = 1 ,69186   ,394,394,394
BEGIN DESCRIPTION:
Mapping XS 11453a5e
END DESCRIPTION:
XS GIS Cut Line= 3
      2009988.53     13620439.25      2009368.75     13620897.57
      2009160.41     13621199.67
#Sta/Elev= 30
  4504.5  696.39  4517.9  695.97  4646.1  690.91  4696.2  690.58  4810.9  684.63
 4819.82684.2775  4825.7  682.76  4890.4  680.46  4911.3  677.77  4925.9   679.7
  4940.5  676.73  4955.1   675.5  4961.4  672.84    4976  670.73  4979.2  668.78
  4982.4  667.98  5002.1  668.78  5005.2  669.38  5011.5  674.78  5018.8  671.57
  5026.1  678.67  5032.3  680.53  5090.8  681.87  5139.3  680.55  5168.1  681.49
  5296.7  680.83 5392.08684.2783  5454.9     689  5541.4  693.36  5642.3  695.85
#Mann= 6 ,-1 , 0
  4504.5     .05       0  4517.9      .1       0  4810.9     .12       0
  4979.2     .07       0  5002.1     .12       0  5139.3      .1       0
Bank Sta=4819.82,5392.08
XS Rating Curve= 0 ,0
Exp/Cntr=0.3,0.1

Type RM Length L Ch R = 1 ,68792   ,461,461,461
BEGIN DESCRIPTION:
CHACON CREEK 79.0
END DESCRIPTION:
XS GIS Cut Line= 3
      2010129.21     13620178.38        2009425.       13620425.
      2008353.21     13620863.32
#Sta/Elev= 30
    4260  698.74  4360.4  698.53  4479.2  696.49  4719.3  686.81  4812.3  683.35
 4812.61 683.335  4921.4  680.16  4953.2  677.66  4959.6  675.52  4964.9   675.9
  4973.5  663.67  4976.7  662.87  4996.4  663.67  5003.5  672.11  5008.8  672.11
  5015.4  678.26  5020.9  676.48  5027.8  681.32  5038.6  682.67  5081.8  682.68
  5168.2  680.14  5205.1  677.15  5228.8  679.54    5360  679.62  5413.5  680.55
 5470.51683.3348  5597.8  688.73  5702.4  691.34  5723.7  691.89  6164.1   701.8
#Mann= 8 ,-1 , 0
    4260     .05       0  4719.3      .1       0  4812.3     .12       0
  4973.5     .07       0  4996.4     .12       0  5228.8      .1       0
  5702.4     .05       0  5723.7      .1       0
Bank Sta=4812.61,5470.51
XS Rating Curve= 0 ,0
Exp/Cntr=0.3,0.1

Type RM Length L Ch R = 1 ,68331   ,210,210,210
BEGIN DESCRIPTION:
CHACON CREEK 78.0
END DESCRIPTION:
XS GIS Cut Line= 3
       2010033.7     13619807.78        2009325.       13620075.
      2008269.87     13620592.48
#Sta/Elev= 30
  4204.5  696.77    4270  697.16  4325.1  696.07  4605.7  687.63 4724.74682.6971
  4787.1  680.38  4801.9  680.18  4940.5  680.13  4964.7  676.77  4970.4   666.3
  4972.7  663.92  4975.9  663.12  4995.6  663.92  5006.5  668.87  5015.4  671.18
  5020.9  670.44  5037.8  681.94    5051  682.74  5095.6  680.76  5239.4  679.56
  5318.9   678.7    5374  676.81 5555.33682.6974  5718.2  688.36  5785.7  692.71
  5791.3  693.95  5841.8  696.31  5903.7  696.27  6116.2  701.36  6137.1  701.58
#Mann= 7 ,-1 , 0
  4204.5     .05       0  4787.1      .1       0  4801.9     .12       0
  4972.7     .07       0  4995.6     .12       0  5239.4      .1       0
  6116.2     .05       0
Bank Sta=4724.74,5555.33
XS Rating Curve= 0 ,0
Exp/Cntr=0.3,0.1

Type RM Length L Ch R = 1 ,68121   ,384,384,384
BEGIN DESCRIPTION:
Mapping XS 791b0f3f
END DESCRIPTION:
XS GIS Cut Line= 2
      2009836.67     13619645.45      2008018.62     13620457.33
#Sta/Elev= 30
    4383  696.43  4406.7  697.02  4560.1  694.14  4640.8  691.27  4783.2  683.78
 4829.83682.1882  4877.2  680.89  4953.5  679.89  4965.3  678.62  4976.2  676.97
    4994  663.89  4997.2  663.09  5016.9  663.89    5020  669.33  5034.1  673.57
  5041.9  678.68  5057.3  680.92  5118.6  679.57  5323.7  680.19  5427.5  677.58
  5445.2  676.21  5458.1  673.73  5468.4  673.64  5502.6  678.16  5530.9  679.28
 5658.56682.1882  5983.3  690.08  6231.9  699.56  6312.5  701.24  6374.1  700.83
#Mann= 6 ,-1 , 0
    4383     .05       0  4783.2      .1       0  4877.2     .12       0
    4994     .07       0  5016.9     .12       0  5530.9      .1       0
Bank Sta=4829.83,5658.56
XS Rating Curve= 0 ,0
Exp/Cntr=0.3,0.1

Type RM Length L Ch R = 1 ,67737   ,595,595,595
BEGIN DESCRIPTION:
CHACON CREEK 77.0
END DESCRIPTION:
XS GIS Cut Line= 3
      2009624.96     13619575.01        2008975.       13619725.
      2008135.24     13619860.74
#Sta/Elev= 30
  4329.7  694.27  4432.3  690.09  4563.7  682.68 4581.64681.7775    4706  678.32
  4765.1  678.61  4882.1  680.26  4904.4  678.91  4924.9  676.99  4935.2  672.81
  4972.8  668.77    4975  663.79  4978.2  662.99  4997.9  663.79  5006.9  664.49
    5017  668.21  5030.1  675.76  5057.5  680.84  5179.1  676.69  5209.5  673.73
  5215.3  671.84  5229.7  670.28  5270.1  677.64 5388.76681.7776  5657.5  691.72
  5665.3  693.24  5699.3  693.26  5764.3  694.75  5827.4  695.91  5847.4  697.57
#Mann= 8 ,-1 , 0
  4329.7     .05       0  4563.7      .1       0  4765.1     .12       0
    4975     .07       0  4997.9     .12       0  5270.1      .1       0
  5699.3     .05       0  5764.3      .1       0
Bank Sta=4581.64,5388.76
XS Rating Curve= 0 ,0
Exp/Cntr=0.3,0.1

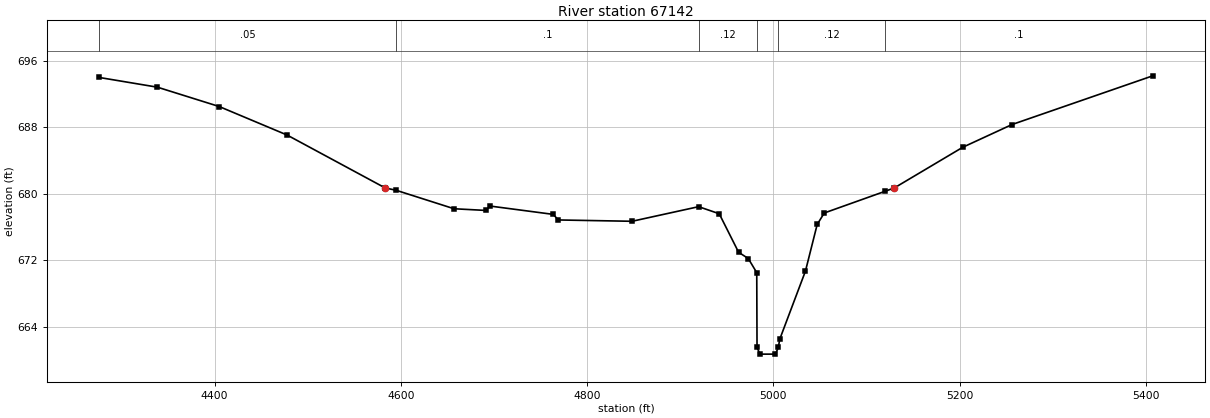
Type RM Length L Ch R = 1 ,67142   ,278,278,278
BEGIN DESCRIPTION:
CHACON CREEK 76.0
END DESCRIPTION:
XS GIS Cut Line= 3
      2009625.01       13619475.        2008925.       13619275.
      2008525.03       13619225.
#Sta/Elev= 30
  4276.3  694.02  4338.7  692.85    4405  690.52  4477.8  687.09 4583.17680.7119
  4594.9  680.43  4657.2   678.2    4691     678  4696.2  678.52  4763.8  677.52
    4769  676.85  4848.3  676.69  4919.8  678.45  4941.9   677.6  4962.7  672.96
  4973.1   672.2  4982.2   670.5  4982.5  661.48  4985.7  660.68  5002.2  660.68
  5005.4  661.48  5006.8  662.45  5034.5  670.69  5047.1  676.31  5054.7  677.69
  5119.4  680.28 5129.95 680.712  5203.4  685.61  5256.3  688.35  5407.4  694.22
#Mann= 6 ,-1 , 0
  4276.3     .05       0  4594.9      .1       0  4919.8     .12       0
  4982.5     .07       0  5005.4     .12       0  5119.4      .1       0
Bank Sta=4583.17,5129.95
XS Rating Curve= 0 ,0
Exp/Cntr=0.3,0.1