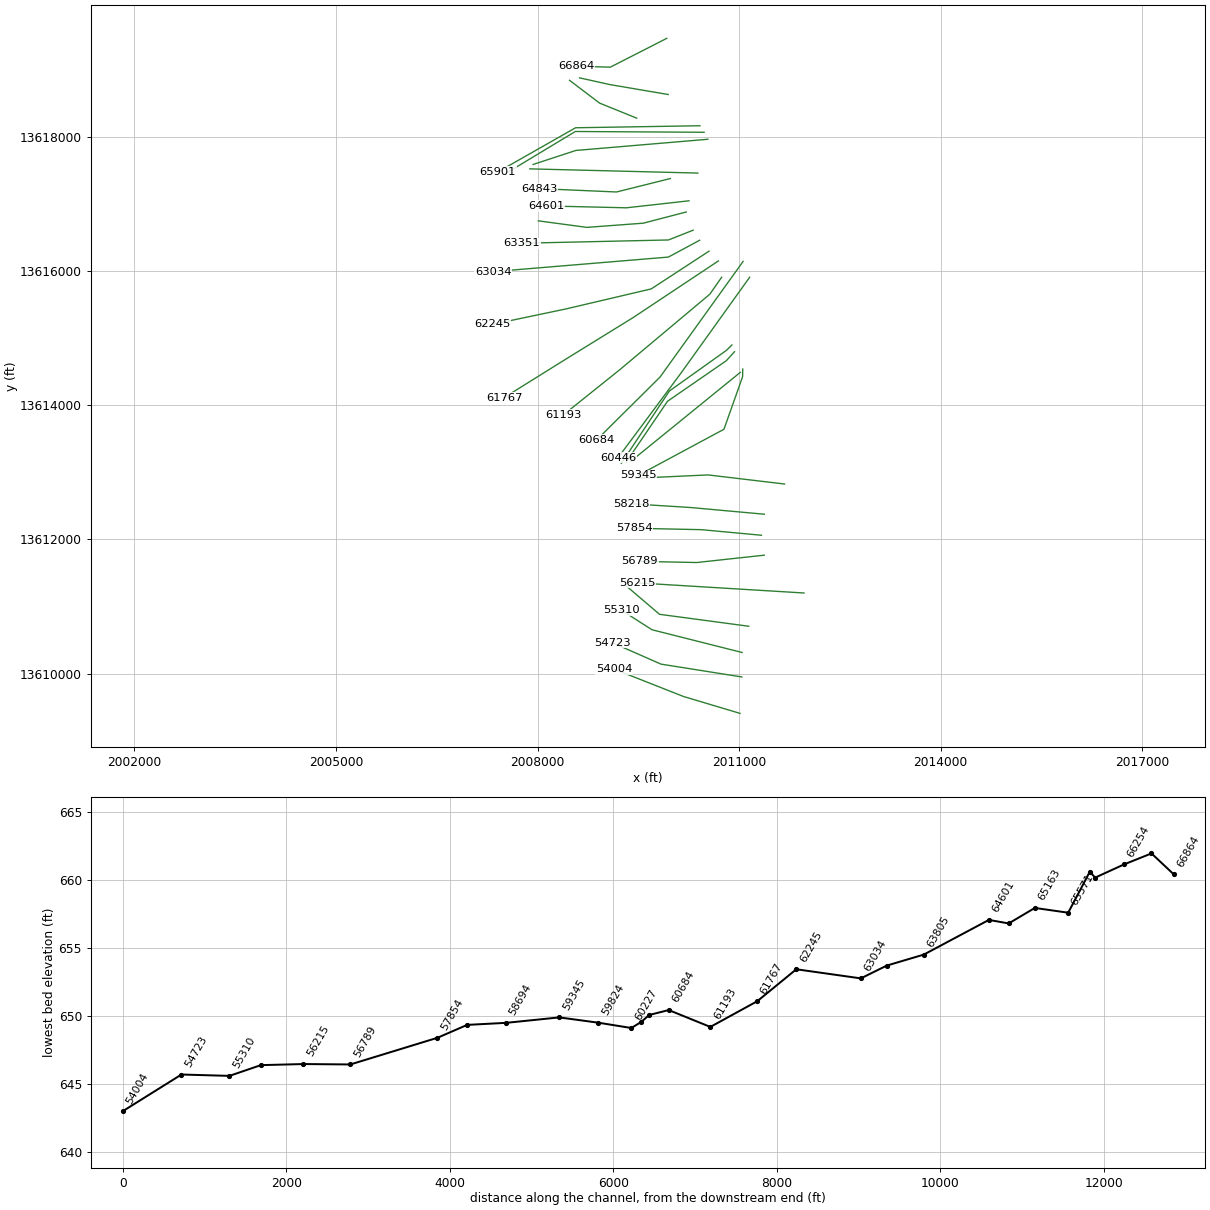
HEC-RAS study CHACON CREEK.prj: CHACON CREEK Base Level Engineering

--- CHACON CREEK.g01 (geometry) --- (continued)

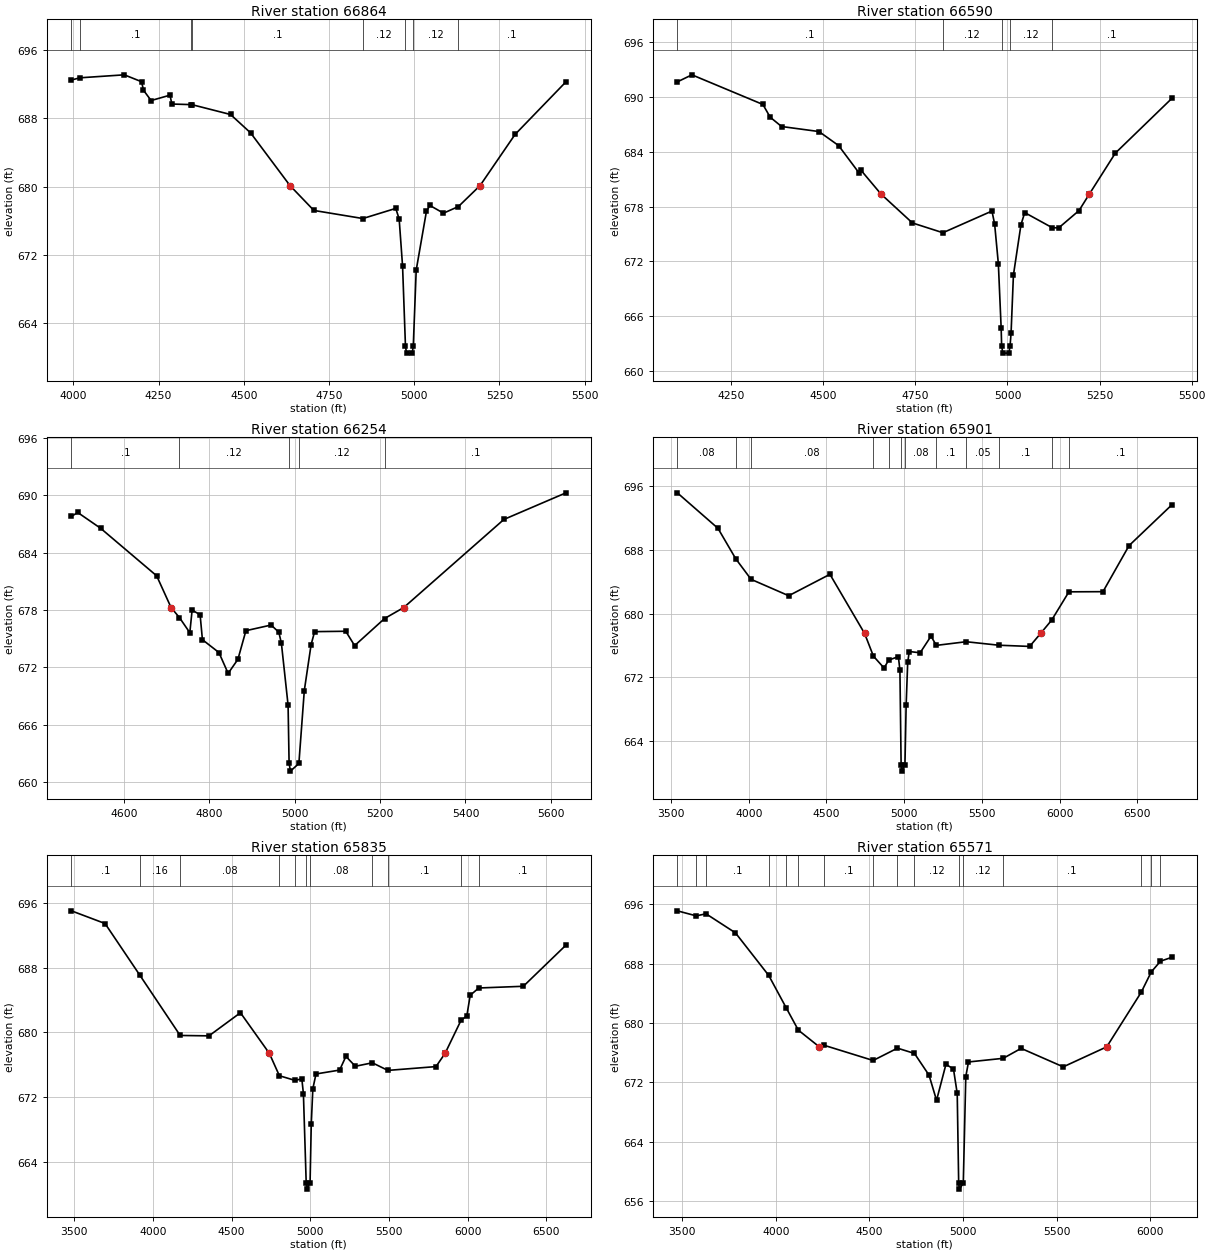
Type RM Length L Ch R = 1 ,66864   ,274,274,274
BEGIN DESCRIPTION:
Mapping XS e784ad2f
END DESCRIPTION:
XS GIS Cut Line= 3
      2009923.26     13619463.73      2009082.73     13619034.36
      2008575.77     13619048.25
#Sta/Elev= 30
  3994.2  692.51  4019.2  692.77  4149.4  693.12  4200.1  692.31  4205.7  691.31
  4228.1   690.1  4283.4  690.73    4289  689.69  4345.6  689.62  4347.5  689.62
  4461.1  688.46    4520   686.3 4635.44680.1144  4705.6  677.19  4849.3  676.24
  4945.8  677.43  4955.8  676.19  4965.8  670.65  4974.3  661.23  4977.5  660.43
    4994  660.43  4997.2  661.23  5005.8  670.18  5035.8  677.08  5045.8  677.78
  5085.8  676.87  5129.7  677.65 5193.24680.1144  5295.9  686.12  5445.2   692.3
#Mann= 8 ,-1 , 0
  3994.2     .05       0  4019.2      .1       0  4345.6     .05       0
  4347.5      .1       0  4849.3     .12       0  4974.3     .07       0
  4997.2     .12       0  5129.7      .1       0
Bank Sta=4635.44,5193.24
XS Rating Curve= 0 ,0
Exp/Cntr=0.3,0.1

Type RM Length L Ch R = 1 ,66590   ,336,336,336
BEGIN DESCRIPTION:
CHACON CREEK 75.0
END DESCRIPTION:
XS GIS Cut Line= 3
      2009944.02     13618626.91        2009075.       13618775.
      2008625.03     13618874.99
#Sta/Elev= 30
  4103.9  691.63  4143.5   692.4  4336.2  689.16  4355.9  687.77  4386.9  686.75
  4488.4   686.2  4541.6  684.67  4596.7   681.7  4601.8     682 4656.84679.3638
    4742  676.21  4824.8  675.14  4957.9  677.51  4965.2  676.09  4975.3  671.75
  4982.9  664.72  4984.2  662.78  4987.4  661.98  5003.9  661.98  5007.1  662.78
  5009.8  664.16  5016.2  670.51  5036.7  676.02  5046.9  677.34  5121.6  675.69
  5139.1  675.67  5194.2  677.56 5222.28679.3636  5292.8  683.84  5446.4  689.83
#Mann= 5 ,-1 , 0
  4103.9      .1       0  4824.8     .12       0  4984.2     .07       0
  5007.1     .12       0  5121.6      .1       0
Bank Sta=4656.84,5222.28
XS Rating Curve= 0 ,0
Exp/Cntr=0.3,0.1

Type RM Length L Ch R = 1 ,66254   ,353,353,353
BEGIN DESCRIPTION:
CHACON CREEK 74.0
END DESCRIPTION:
XS GIS Cut Line= 3
      2009474.98     13618275.01      2008922.48     13618499.11
      2008475.33     13618838.69
#Sta/Elev= 30
  4477.5  687.77  4492.2  688.19  4545.8  686.54  4677.1  681.57 4710.81678.2573
  4730.4  677.21  4754.7  675.63  4760.1  677.99  4778.8   677.5  4784.2   674.9
  4822.8  673.56  4844.4  671.38  4867.3  672.85    4886  675.84    4945  676.43
  4963.1  675.68  4969.1  674.51  4984.7  668.07  4987.1  661.97  4990.3  661.17
    5010  661.97  5022.7  669.59  5038.6  674.38  5046.8  675.74  5119.7  675.78
  5140.5  674.28  5210.6  677.11 5255.45678.2568  5489.9  687.46  5635.2  690.24
#Mann= 5 ,-1 , 0
  4477.5      .1       0  4730.4     .12       0  4987.1     .07       0
    5010     .12       0  5210.6      .1       0
Bank Sta=4710.81,5255.45
XS Rating Curve= 0 ,0
Exp/Cntr=0.3,0.1

Type RM Length L Ch R = 1 ,65901   ,66,66,66
BEGIN DESCRIPTION:
CHACON CREEK 73.0
END DESCRIPTION:
XS GIS Cut Line= 3
       2010416.3     13618161.63      2008565.37     13618131.58
      2007409.67     13617474.32
#Sta/Elev= 30
  3540.9  695.17  3802.2  690.71  3916.7  686.88  4015.1   684.3  4257.2  682.24
  4522.3  684.93 4745.35677.4968  4801.9  674.65  4870.3  673.16  4900.3  674.15
  4962.4  674.59  4972.4  672.89  4980.1     661  4983.9   660.2  5004.7     661
  5012.4  668.48  5022.4  673.85  5032.4  675.23  5102.4  675.07  5172.4  677.16
  5206.4     676  5398.1  676.46    5609  676.02  5806.6  675.87 5877.11677.4966
  5948.1  679.17  6059.3  682.73  6278.3  682.75  6446.1  688.54  6721.6  693.67
#Mann= 12 ,-1 , 0
  3540.9     .08       0  3916.7     .05       0  4015.1     .08       0
  4801.9     .05       0  4900.3     .08       0  4980.1     .07       0
  5004.7     .08       0  5206.4      .1       0  5398.1     .05       0
    5609      .1       0  5948.1     .05       0  6059.3      .1       0
Bank Sta=4745.35,5877.11
XS Rating Curve= 0 ,0
Exp/Cntr=0.3,0.1

Type RM Length L Ch R = 1 ,65835   ,264,264,264
BEGIN DESCRIPTION:
Mapping XS a5566a08
END DESCRIPTION:
XS GIS Cut Line= 3
      2010478.81      13618064.4      2008561.89     13618076.02
       2007513.5     13617442.88
#Sta/Elev= 30
  3482.9  695.04  3696.7  693.47  3918.4  687.06  4173.8  679.63  4356.7  679.58
  4556.7  682.44 4740.35677.4167  4804.1  674.65  4902.5  674.08  4946.7  674.26
  4956.7  672.44  4974.4  661.43  4978.3  660.63    4999  661.43  5006.7  668.73
  5016.7  673.05  5036.7  674.87  5186.7  675.35  5226.7  677.04  5286.7  675.82
  5394.6  676.25  5493.5  675.31  5798.8  675.78 5856.71 677.417  5957.9   681.5
  5994.8  682.05  6016.2   684.6  6070.7   685.5  6353.8  685.71  6624.6   690.8
#Mann= 11 ,-1 , 0
  3482.9      .1       0  3918.4     .16       0  4173.8     .08       0
  4804.1     .05       0  4902.5     .08       0  4974.4     .07       0
    4999     .08       0  5394.6     .05       0  5493.5      .1       0
  5957.9     .05       0  6070.7      .1       0
Bank Sta=4740.35,5856.71
XS Rating Curve= 0 ,0
Exp/Cntr=0.3,0.1

Type RM Length L Ch R = 1 ,65571   ,408,408,408
BEGIN DESCRIPTION:
Mapping XS ad8c13a0
END DESCRIPTION:
XS GIS Cut Line= 3
      2010534.29     13617960.23       2008569.5     13617793.59
      2007933.61     13617585.23
#Sta/Elev= 30
  3474.3  695.13  3575.4  694.45  3627.5  694.73  3784.7  692.16  3962.4  686.42
  4055.8  682.05  4120.4  679.05  4232.4676.7978  4257.8  677.01  4519.9  674.96
  4649.9  676.62  4740.5  675.91  4818.4  672.98  4858.5  669.59  4908.7  674.44
  4948.9  673.81  4968.9  670.51  4976.7  658.42  4980.6  657.62  5001.3  658.42
  5014.7   672.8  5029.1  674.76  5214.4  675.25  5310.2  676.59  5535.1   674.1
 5767.29676.7977  5951.8  684.17  6004.9  686.89  6054.3  688.34  6115.3  688.87
#Mann= 16 ,-1 , 0
  3474.3      .1       0  3575.4     .16       0  3627.5      .1       0
  3962.4     .16       0  4055.8      .1       0  4120.4     .16       0
  4257.8      .1       0  4519.9     .12       0  4649.9      .1       0
  4740.5     .12       0  4976.7     .07       0  5001.3     .12       0
  5214.4      .1       0  5951.8     .05       0  6004.9     .08       0
  6054.3      .1       0
Bank Sta=4232.4,5767.29
XS Rating Curve= 0 ,0
Exp/Cntr=0.3,0.1

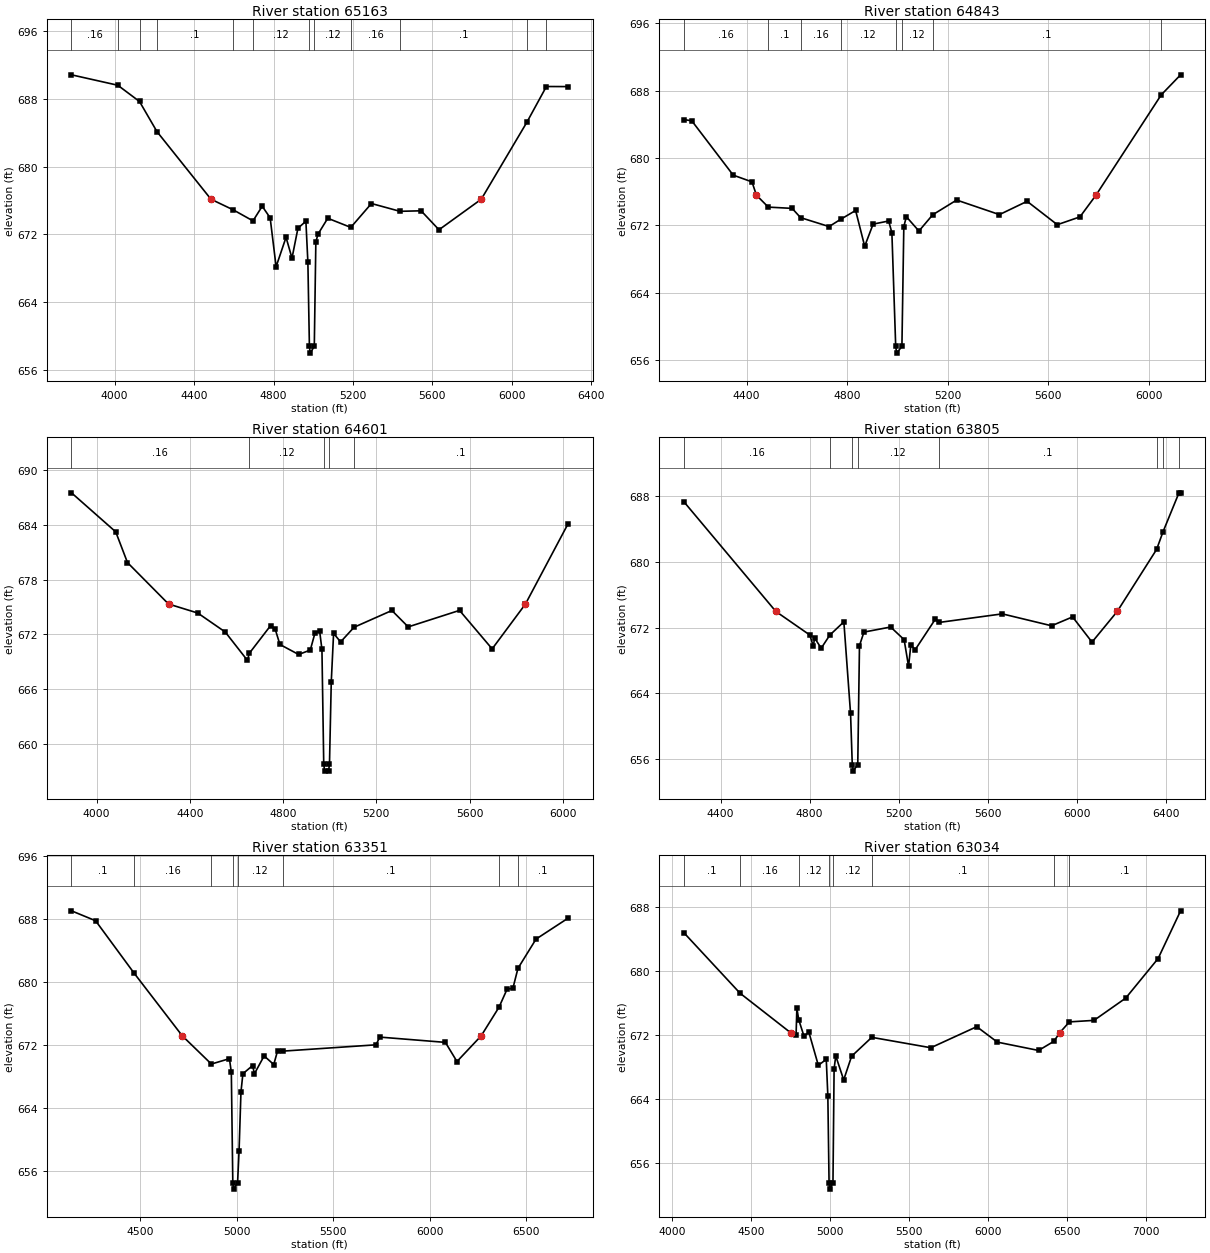
Type RM Length L Ch R = 1 ,65163   ,320,320,320
BEGIN DESCRIPTION:
Mapping XS 1a79b19d
END DESCRIPTION:
XS GIS Cut Line= 2
      2010385.07     13617456.76      2007885.05     13617519.26
#Sta/Elev= 30
  3782.7  690.84  4015.8  689.61  4125.2  687.69  4213.2  684.13 4485.05676.1477
  4598.2  674.88  4696.7  673.59  4743.1  675.32  4783.1  673.95  4813.1  668.18
  4863.1  671.65  4893.1  669.19  4923.1  672.73  4963.1  673.54  4973.1  668.71
  4980.8  658.77  4984.7  657.97  5005.4  658.77  5013.2  671.06  5023.2  671.99
  5073.2   673.9  5189.2  672.82  5293.2  675.64  5436.8  674.72  5543.3  674.78
  5633.3  672.54 5846.35676.1479  6075.7  685.23  6174.2  689.46  6283.5  689.45
#Mann= 12 ,-1 , 0
  3782.7     .16       0  4015.8      .1       0  4125.2     .16       0
  4213.2      .1       0  4598.2     .16       0  4696.7     .12       0
  4980.8     .07       0  5005.4     .12       0  5189.2     .16       0
  5436.8      .1       0  6075.7     .05       0  6174.2      .1       0
Bank Sta=4485.05,5846.35
XS Rating Curve= 0 ,0
Exp/Cntr=0.3,0.1

Type RM Length L Ch R = 1 ,64843   ,242,242,242
BEGIN DESCRIPTION:
CHACON CREEK 72.0
END DESCRIPTION:
XS GIS Cut Line= 3
      2009974.96     13617374.99        2009175.       13617175.
      2008024.96       13617225.
#Sta/Elev= 30
  4151.2  684.58  4182.1  684.44    4347  677.98  4421.7  677.18 4439.41675.5991
  4486.6  674.18  4581.5  674.03    4615  672.93  4728.4  671.87    4775  672.74
    4834  673.78  4870.1  669.53  4903.6  672.16  4965.5  672.53  4978.3  671.14
  4993.5  657.63  4997.4  656.83  5018.2  657.63  5025.8  671.86  5035.8  673.04
  5085.9  671.34  5140.7  673.27    5236  675.02  5406.2  673.29  5516.3  674.87
  5636.4  672.09  5726.5  673.02  5790.3675.5991  6049.9  687.52  6126.9   689.9
#Mann= 8 ,-1 , 0
  4151.2     .16       0  4486.6      .1       0    4615     .16       0
    4775     .12       0  4993.5     .07       0  5018.2     .12       0
  5140.7      .1       0  6049.9     .05       0
Bank Sta=4439.41,5790.3
XS Rating Curve= 0 ,0
Exp/Cntr=0.3,0.1

Type RM Length L Ch R = 1 ,64601   ,796,796,796
BEGIN DESCRIPTION:
Mapping XS 5c12628c
END DESCRIPTION:
XS GIS Cut Line= 3
      2010253.58     13617043.59      2009322.98     13616939.42
      2008129.31     13616967.18
#Sta/Elev= 30
  3892.5  687.46  4082.3   683.2  4132.6  679.85 4308.72675.3281  4434.4  674.34
  4552.1  672.27  4647.4  669.17  4654.8  669.93  4746.4  672.96  4766.5  672.57
  4786.6  670.91  4866.9  669.82  4916.9   670.3  4936.9  672.15  4956.9  672.41
  4966.9  670.37  4974.6  657.89  4978.5  657.09  4995.4  657.09  4999.3  657.89
  5006.9  666.82  5016.9  672.12    5047  671.19  5104.7  672.79    5267  674.62
    5337  672.83  5557.1  674.63  5697.1  670.43 5840.05675.3282  6022.9  684.09
#Mann= 5 ,-1 , 0
  3892.5     .16       0  4654.8     .12       0  4974.6     .07       0
  4999.3     .12       0  5104.7      .1       0
Bank Sta=4308.72,5840.05
XS Rating Curve= 0 ,0
Exp/Cntr=0.3,0.1

Type RM Length L Ch R = 1 ,63805   ,454,454,454
BEGIN DESCRIPTION:
Mapping XS 81372451
END DESCRIPTION:
XS GIS Cut Line= 4
      2010211.89     13616876.93      2009572.98     13616710.25
       2008732.7     13616647.75      2008010.51     13616744.97
#Sta/Elev= 30
  4235.2  687.33 4648.06673.9842  4800.4  671.12  4816.6  669.73  4821.8  670.76
  4851.9  669.51  4890.6  671.11  4953.6  672.72  4983.7  661.57  4991.4  655.34
  4995.3  654.54  5016.1  655.34  5023.8  669.83  5043.9  671.47  5163.9  672.09
  5224.4  670.55  5244.4   667.3  5254.5  669.87  5274.5  669.34  5364.8  673.05
    5380  672.64  5665.6  673.69  5887.1  672.24  5981.4  673.32  6068.8  670.25
 6182.08673.9842  6359.1  681.54  6387.8  683.68  6458.8  688.38  6466.8  688.43
#Mann= 8 ,-1 , 0
  4235.2     .16       0  4890.6     .12       0  4991.4     .07       0
  5016.1     .12       0    5380      .1       0  6359.1     .05       0
  6387.8     .08       0  6458.8      .1       0
Bank Sta=4648.06,6182.08
XS Rating Curve= 0 ,0
Exp/Cntr=0.3,0.1

Type RM Length L Ch R = 1 ,63351   ,317,317,317
BEGIN DESCRIPTION:
CHACON CREEK 71.0
END DESCRIPTION:
XS GIS Cut Line= 3
      2010316.06      13616606.1      2009947.98     13616460.25
      2007768.75     13616411.67
#Sta/Elev= 30
  4142.2  689.06  4267.2   687.8    4465  681.21 4716.72673.1931  4867.7  669.61
  4961.2  670.29  4971.2  668.57  4978.9  654.53  4982.8  653.73  5003.6  654.53
  5011.2  658.51  5021.2  666.07  5031.2  668.38  5081.2  669.41  5091.2  668.39
  5141.3  670.64  5191.3  669.55  5211.3  671.31  5239.6  671.25  5721.4  672.05
  5741.4  673.03  6081.5  672.36  6141.5  669.93 6267.19673.1931  6359.5  676.82
  6401.6  679.12  6431.6  679.22  6457.9  681.76  6551.6  685.47  6717.9  688.13
#Mann= 8 ,-1 , 0
  4142.2      .1       0    4465     .16       0  4867.7     .12       0
  4978.9     .07       0  5003.6     .12       0  5239.6      .1       0
  6359.5     .08       0  6457.9      .1       0
Bank Sta=4716.72,6267.19
XS Rating Curve= 0 ,0
Exp/Cntr=0.3,0.1

Type RM Length L Ch R = 1 ,63034   ,789,789,789
BEGIN DESCRIPTION:
Mapping XS 002ba5a4
END DESCRIPTION:
XS GIS Cut Line= 3
      2010411.92     13616455.46      2009946.65     13616205.46
      2007338.46     13615988.16
#Sta/Elev= 30
  4074.6  684.82  4429.8  677.27 4749.39672.3488  4784.5     672  4789.5   675.4
  4801.4  673.96  4835.2  671.87  4865.3  672.42  4925.5  668.26  4975.7  669.01
  4985.7  664.49  4993.5  653.59  4997.4  652.79  5018.2  653.59  5025.4  667.83
  5035.9  669.44  5086.1  666.44  5136.3   669.4  5264.1  671.76    5638  670.46
    5929  673.09  6059.5  671.16  6320.4  670.12  6417.3  671.26 6455.16672.3488
  6515.7  673.69  6671.6  673.88  6872.3  676.66  7077.7  681.61    7220  687.57
#Mann= 8 ,-1 , 0
  4074.6      .1       0  4429.8     .16       0  4801.4     .12       0
  4993.5     .07       0  5018.2     .12       0  5264.1      .1       0
  6417.3     .08       0  6515.7      .1       0
Bank Sta=4749.39,6455.16
XS Rating Curve= 0 ,0
Exp/Cntr=0.3,0.1

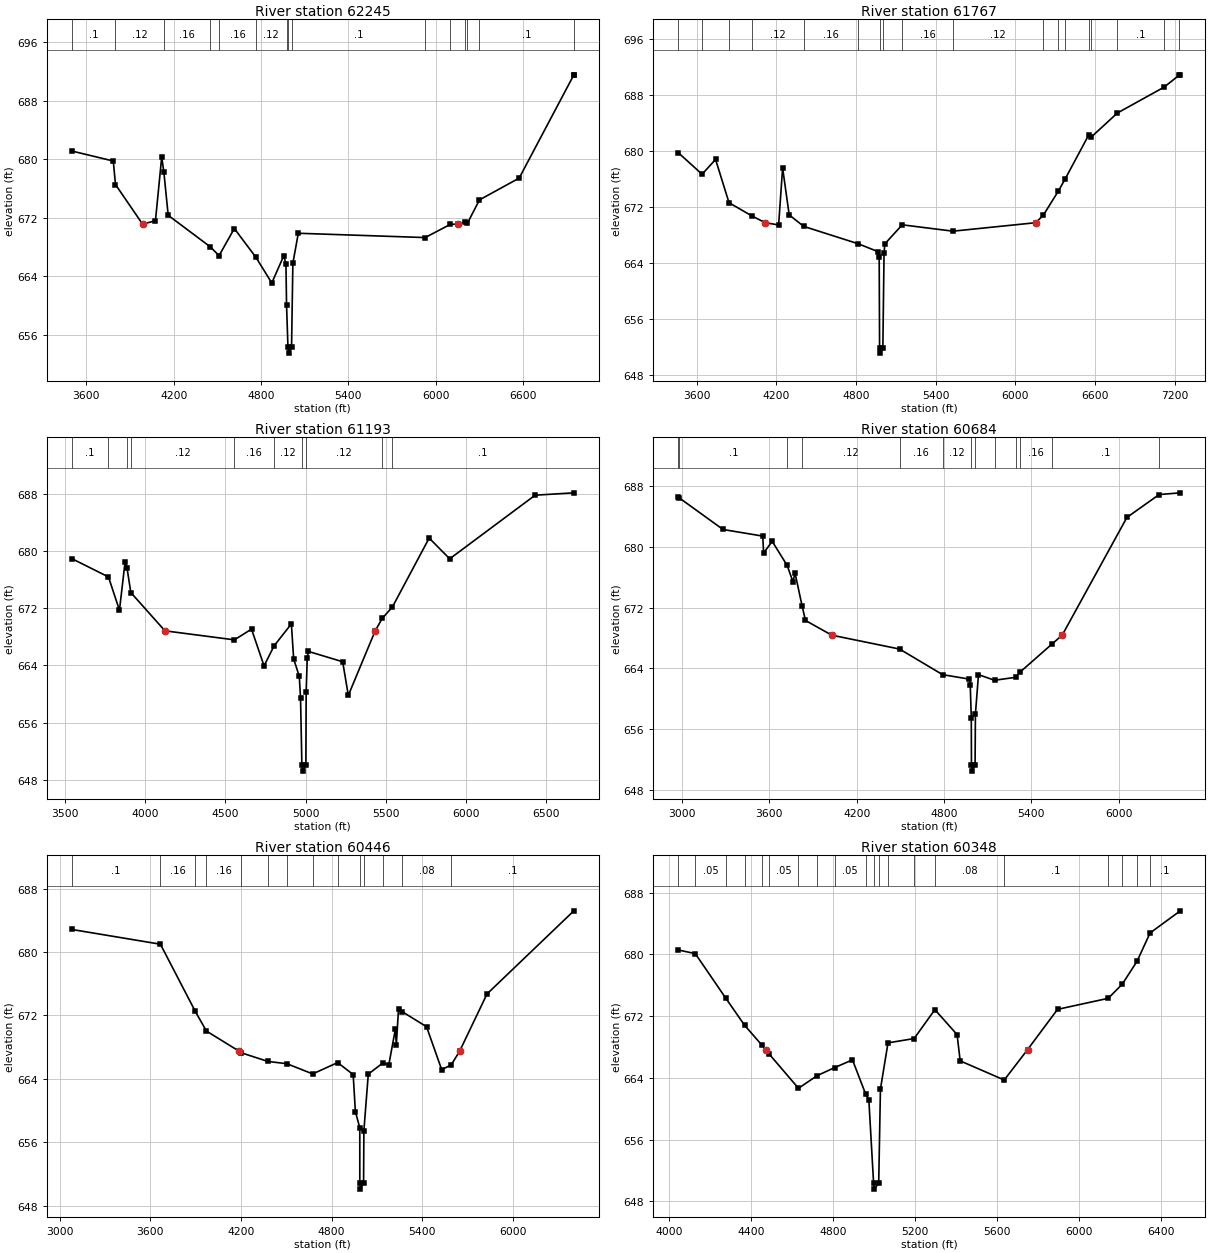
Type RM Length L Ch R = 1 ,62245   ,478,478,478
BEGIN DESCRIPTION:
Mapping XS af5a872c
END DESCRIPTION:
XS GIS Cut Line= 4
      2010552.15     13616293.59      2009691.03     13615731.09
       2008420.2     13615432.48      2007329.92     13615203.31
#Sta/Elev= 30
    3500  681.13    3785  679.76  3800.3  676.54 3986.08671.1246  4074.7  671.58
  4117.7  680.32  4132.7  678.19  4162.2  672.33  4452.2     668  4511.4   666.8
  4616.3  670.52    4765  666.57  4873.7  663.06  4955.9  666.79  4970.9  665.66
    4975  660.09  4984.7  654.26  4988.6  653.46  5009.4  654.26  5018.4  665.76
  5055.7  669.87  5926.7  669.28  6100.3  671.09  6151.6671.1248  6200.2  671.47
  6217.2  671.24    6300  674.44  6572.6  677.42  6946.9  691.51  6948.1  691.56
#Mann= 15 ,-1 , 0
    3500      .1       0  3800.3     .12       0  4132.7     .16       0
  4452.2     .12       0  4511.4     .16       0    4765     .12       0
    4975      .1       0  4984.7     .07       0  5009.4      .1       0
  5926.7     .12       0  6100.3     .08       0  6200.2      .1       0
  6217.2     .08       0    6300      .1       0  6946.9     .05       0
Bank Sta=3986.08,6151.6
XS Rating Curve= 0 ,0
Exp/Cntr=0.3,0.1

Type RM Length L Ch R = 1 ,61767   ,574,574,574
BEGIN DESCRIPTION:
Mapping XS 8af18a44
END DESCRIPTION:
XS GIS Cut Line= 4
      2010691.03     13616147.76      2009427.14     13615307.48
      2008427.14     13614689.42      2007503.54     13614113.04
#Sta/Elev= 30
    3461  679.78  3640.6  676.69  3742.2  678.81  3843.5  672.62  4018.7   670.7
 4116.62669.7618  4217.2  669.44  4247.2   677.6  4296.8  670.88  4405.6  669.24
  4818.3  666.74  4968.7   665.6  4974.7  664.87  4977.7  651.91  4981.6  651.11
  5002.4  651.91  5011.3   665.4  5017.2  666.73  5148.2  669.46  5530.2  668.55
 6153.86 669.762  6211.2  670.84  6324.9   674.3  6377.1  676.07  6552.5  682.29
  6573.1  682.03    6769  685.45  7121.2  689.15    7235  690.87    7243  690.91
#Mann= 18 ,-1 , 0
    3461      .1       0  3640.6     .12       0  3843.5     .05       0
  4018.7     .12       0  4405.6     .16       0  4818.3     .12       0
  4977.7     .07       0  5002.4     .12       0  5148.2     .16       0
  5530.2     .12       0  6211.2      .1       0  6324.9     .16       0
  6377.1      .1       0  6552.5     .05       0  6573.1     .08       0
    6769      .1       0  7121.2     .08       0    7235      .1       0
Bank Sta=4116.62,6153.86
XS Rating Curve= 0 ,0
Exp/Cntr=0.3,0.1

Type RM Length L Ch R = 1 ,61193   ,509,509,509
BEGIN DESCRIPTION:
Mapping XS 52d49fba
END DESCRIPTION:
XS GIS Cut Line= 4
      2010739.63     13615904.68      2010563.84     13615652.51
      2009225.75      13614529.7      2008385.48     13613856.09
#Sta/Elev= 30
    3542  678.91  3770.8  676.35  3839.4   671.7  3874.7   678.5  3886.2  677.66
  3910.2  674.17  4123.1668.8206  4556.1  667.56    4663  669.06  4741.1  663.92
  4803.7  666.72  4911.5  669.79  4925.8  664.89  4960.9  662.46  4968.7  659.43
  4977.1  650.02  4981.1  649.22  5001.9  650.02  5003.8  660.26  5010.4  664.97
  5018.2  665.94  5231.5   664.5  5266.6   659.8 5434.21668.8204  5478.6  670.57
  5541.8  672.16  5770.8  681.78  5898.9  678.88  6431.8  687.77  6673.1   688.1
#Mann= 10 ,-1 , 0
    3542      .1       0  3770.8     .12       0  3886.2     .16       0
  3910.2     .12       0  4556.1     .16       0  4803.7     .12       0
  4977.1     .07       0  5001.9     .12       0  5478.6     .16       0
  5541.8      .1       0
Bank Sta=4123.1,5434.21
XS Rating Curve= 0 ,0
Exp/Cntr=0.3,0.1

Type RM Length L Ch R = 1 ,60684   ,238,238,238
BEGIN DESCRIPTION:
CHACON CREEK 67.0
END DESCRIPTION:
XS GIS Cut Line= 3
      2011059.07     13616140.79      2009822.98     13614418.59
      2008879.26     13613481.82
#Sta/Elev= 30
  2973.6  686.59  2981.6  686.44  3281.5  682.29  3554.1  681.42  3560.3   679.2
  3619.2  680.73  3721.7  677.56  3761.6  675.42  3776.4  676.53  3824.5  672.23
  3847.6  670.31 4028.06668.3709  4494.6  666.54  4789.8  663.17  4973.6  662.58
  4979.8  661.87  4987.1  657.46  4988.2  651.26  4992.1  650.46  5013.1  651.26
  5015.4  657.96  5036.4  663.17  5146.9  662.43  5292.8  662.82  5324.4  663.54
  5543.8  667.24 5611.76668.3709  6056.3  683.88  6277.5  686.89  6423.2  687.12
#Mann= 13 ,-1 , 0
  2973.6     .05       0  2981.6      .1       0  3721.7     .16       0
  3824.5     .12       0  4494.6     .16       0  4789.8     .12       0
  4988.2     .07       0  5013.1     .12       0  5146.9     .16       0
  5292.8     .12       0  5324.4     .16       0  5543.8      .1       0
  6277.5     .05       0
Bank Sta=4028.06,5611.76
XS Rating Curve= 0 ,0
Exp/Cntr=0.3,0.1

Type RM Length L Ch R = 1 ,60446   ,98,98,98
BEGIN DESCRIPTION:
CHACON CREEK 66.0
END DESCRIPTION:
XS GIS Cut Line= 3
      2011156.32     13615904.71      2010142.42     13614488.03
      2009197.96     13613217.17
#Sta/Elev= 30
  3079.1  682.85  3666.2  680.99  3897.4  672.51  3970.8  670.04 4188.71667.4789
  4202.4  667.29    4379   666.2  4503.7  665.92  4674.9  664.63  4840.3  666.06
    4943  664.55  4957.6  659.87  4986.8  657.83  4986.9   650.9  4990.9   650.1
  5011.9   650.9  5013.9  657.47  5043.1  664.61  5141.3  666.03  5178.7  665.75
  5222.5  670.27  5228.8  668.32  5243.4  672.82    5267  672.49    5429  670.58
  5529.2  665.17    5592  665.76 5647.59667.4787  5829.6  674.72  6404.6   685.2
#Mann= 14 ,-1 , 0
  3079.1      .1       0  3666.2     .16       0  3897.4      .1       0
  3970.8     .16       0  4202.4     .12       0    4379     .16       0
  4503.7     .12       0  4674.9     .16       0  4840.3     .12       0
  4986.9     .07       0  5011.9     .12       0  5141.3     .05       0
    5267     .08       0    5592      .1       0
Bank Sta=4188.71,5647.59
XS Rating Curve= 0 ,0
Exp/Cntr=0.3,0.1

Type RM Length L Ch R = 1 ,60348   ,121,121,121
BEGIN DESCRIPTION:
Mapping XS bce2777a
END DESCRIPTION:
XS GIS Cut Line= 4
       2010892.6      13614895.9      2010809.09     13614814.42
      2009961.86     13614210.25       2009246.6     13613133.89
#Sta/Elev= 30
  4045.8  680.56    4129  680.09  4277.4  674.33  4369.2  670.82  4454.9  668.21
 4471.78667.6653  4487.4  667.15  4632.4  662.65  4723.8  664.29  4809.9  665.34
  4895.9  666.33  4960.3  661.89  4975.8  661.13  4998.9  650.39  5002.9  649.59
  5023.9  650.39  5032.3  662.54  5069.2  668.53  5196.7  669.09  5297.9  672.83
  5406.3   669.6  5421.4   666.2  5636.3  663.72  5750.4667.6656  5896.4  672.87
  6143.7   674.3  6212.6  676.15  6284.4   679.1  6347.7  682.76  6495.4  685.63
#Mann= 20 ,-1 , 0
  4045.8     .08       0    4129     .05       0  4277.4     .05       0
  4369.2     .16       0  4454.9     .08       0  4487.4     .05       0
  4632.4     .05       0  4723.8     .16       0  4809.9     .05       0
  4960.3     .12       0  4998.9     .07       0  5023.9     .12       0
  5069.2     .08       0  5196.7     .05       0  5297.9     .08       0
  5636.3      .1       0  6143.7     .08       0  6212.6      .1       0
  6284.4     .08       0  6347.7      .1       0
Bank Sta=4471.78,5750.4
XS Rating Curve= 0 ,0
Exp/Cntr=0.3,0.1

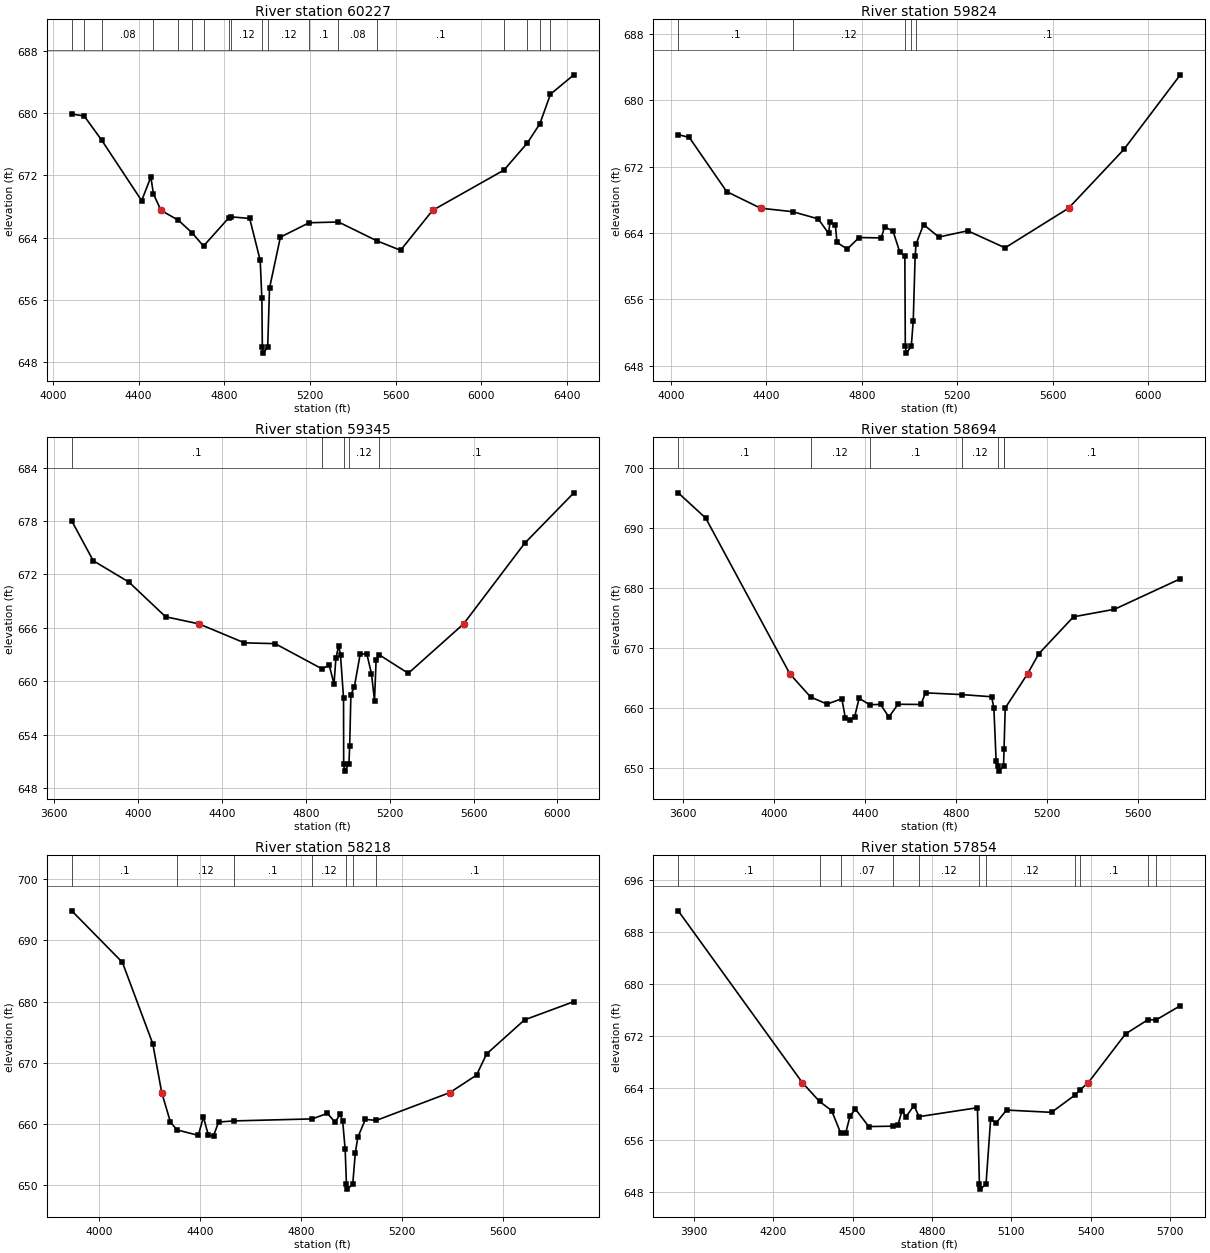
Type RM Length L Ch R = 1 ,60227   ,403,403,403
BEGIN DESCRIPTION:
Mapping XS 56d31ea5
END DESCRIPTION:
XS GIS Cut Line= 4
       2010931.7     13614796.11      2010809.09     13614661.64
      2009934.09     13614057.48      2009316.82     13613148.91
#Sta/Elev= 30
  4088.1   679.9  4146.1  679.64  4227.8  676.53  4414.3  668.75  4457.3   671.8
  4469.3  669.62 4504.52667.5056  4586.1  666.23    4651  664.58  4703.1  662.91
  4820.2  666.52  4832.6  666.67  4918.6  666.46  4967.7  661.07  4975.4  656.23
  4977.7  649.94  4981.7  649.14  5002.7  649.94  5011.2   657.5  5061.9  664.06
  5195.9  665.91    5333  666.01  5510.6  663.61  5622.9  662.37 5772.38667.5059
  6105.8  672.69    6215  676.18  6273.2  678.65  6322.7  682.45  6431.8  684.94
#Mann= 18 ,-1 , 0
  4088.1     .08       0  4146.1      .1       0  4227.8     .08       0
  4469.3      .1       0  4586.1     .08       0    4651      .1       0
  4703.1     .08       0  4820.2     .05       0  4832.6     .12       0
  4977.7     .07       0  5002.7     .12       0  5195.9      .1       0
    5333     .08       0  5510.6      .1       0  6105.8     .08       0
    6215      .1       0  6273.2     .08       0  6322.7      .1       0
Bank Sta=4504.52,5772.38
XS Rating Curve= 0 ,0
Exp/Cntr=0.3,0.1

Type RM Length L Ch R = 1 ,59824   ,479,479,479
BEGIN DESCRIPTION:
Mapping XS d6bc1ba1
END DESCRIPTION:
XS GIS Cut Line= 2
       2011017.4     13614488.02      2009385.44     13613161.62
#Sta/Elev= 30
  4031.5  675.84  4077.8   675.5  4234.4  668.98 4376.24666.9828    4511  666.56
    4618  665.69  4661.1  663.95  4667.5  665.35  4689.8  664.92  4696.3  662.86
  4739.4  662.06  4788.9  663.45  4881.6   663.4    4896  664.73  4931.1  664.23
  4959.9  661.66  4980.7  661.24  4982.6  650.33  4986.6  649.53  5007.6  650.33
  5015.9  653.45  5023.8  661.23  5027.7  662.68    5059  665.01  5122.9  663.51
  5244.3  664.26  5400.5  662.21 5666.54666.9828    5898  674.05  6134.5  683.04
#Mann= 5 ,-1 , 0
  4031.5      .1       0    4511     .12       0  4982.6     .07       0
  5007.6     .12       0  5027.7      .1       0
Bank Sta=4376.24,5666.54
XS Rating Curve= 0 ,0
Exp/Cntr=0.3,0.1

Type RM Length L Ch R = 1 ,59345   ,651,651,651
BEGIN DESCRIPTION:
Mapping XS 89a59f03
END DESCRIPTION:
XS GIS Cut Line= 4
      2011053.53     13614537.25      2011051.52     13614423.43
      2010774.36     13613640.81      2009498.33     13612954.24
#Sta/Elev= 30
  3684.9     678  3787.2  673.54  3957.3  671.14    4132  667.25 4291.28666.4473
  4507.8  664.32  4654.2  664.23  4876.9  661.41  4912.2   661.8  4934.9  659.71
  4943.9  662.63  4957.6  664.02  4965.8  662.94  4980.3   658.1  4980.9  650.72
  4984.9  649.92  5005.9  650.72  5009.6  652.75  5015.3  658.52  5031.5  659.34
  5059.8  663.09  5091.6  663.05  5113.5  660.84  5127.9  657.84  5135.4  662.35
  5151.5  662.96  5288.8   660.9 5552.57666.4475  5843.3  675.49    6078  681.16
#Mann= 5 ,-1 , 0
  3684.9      .1       0  4876.9     .12       0  4980.9     .07       0
  5005.9     .12       0  5151.5      .1       0
Bank Sta=4291.28,5552.57
XS Rating Curve= 0 ,0
Exp/Cntr=0.3,0.1

Type RM Length L Ch R = 1 ,58694   ,476,476,476
BEGIN DESCRIPTION:
CHACON CREEK 65.0
END DESCRIPTION:
XS GIS Cut Line= 3
      2011674.99       13612825.      2010538.25     13612960.25
      2009475.72     13612911.64
#Sta/Elev= 30
  3577.5  695.81  3698.3  691.61 4068.56665.6951  4159.3  661.86  4232.1  660.67
  4297.2  661.56  4312.6  658.32  4332.8  658.03  4352.9  658.48  4373.1  661.63
  4419.6  660.57  4467.5  660.61    4504  658.52  4544.3  660.64    4645  660.61
  4665.1  662.54  4826.1  662.25  4955.8  661.89  4965.8  660.06  4975.8  651.19
  4983.3  650.32  4987.3  649.52  5008.3  650.32  5010.5  653.17  5015.8  660.02
 5113.92665.6955  5163.2  669.03  5316.1  675.19  5496.3  676.44  5785.9  681.51
#Mann= 7 ,-1 , 0
  3577.5      .1       0  4159.3     .12       0  4419.6      .1       0
  4826.1     .12       0  4983.3     .07       0  5008.3     .12       0
  5010.5      .1       0
Bank Sta=4068.56,5113.92
XS Rating Curve= 0 ,0
Exp/Cntr=0.3,0.1

Type RM Length L Ch R = 1 ,58218   ,364,364,364
BEGIN DESCRIPTION:
CHACON CREEK 63.0
END DESCRIPTION:
XS GIS Cut Line= 3
      2011374.95       13612375.        2010275.       13612475.
      2009389.72     13612530.34
#Sta/Elev= 30
  3891.3  694.82  4092.1  686.41  4212.6  673.12 4248.07665.1431  4282.9  660.29
    4309  659.04  4393.3  658.15  4413.4  661.14  4433.5  658.14  4453.6  658.07
  4473.6  660.33  4535.3  660.51  4845.3  660.84  4905.4  661.75  4935.5   660.3
  4955.6  661.56  4965.7  660.55  4975.7  655.86  4980.8  650.17  4984.8  649.37
  5005.8  650.17  5015.8  655.22  5025.8  657.82  5055.9  660.76  5098.9  660.59
 5391.22665.1436  5496.8  667.99  5536.8  671.45  5687.1  677.01  5882.8  679.99
#Mann= 7 ,-1 , 0
  3891.3      .1       0    4309     .12       0  4535.3      .1       0
  4845.3     .12       0  4980.8     .07       0  5005.8     .12       0
  5098.9      .1       0
Bank Sta=4248.07,5391.22
XS Rating Curve= 0 ,0
Exp/Cntr=0.3,0.1

Type RM Length L Ch R = 1 ,57854   ,1065,1065,1065
BEGIN DESCRIPTION:
CHACON CREEK 59.0
END DESCRIPTION:
XS GIS Cut Line= 3
      2011332.18      13612061.6      2010436.31     13612144.94
      2009438.17     13612165.73
#Sta/Elev= 30
  3840.5  691.26 4309.71664.8097  4374.8  661.91  4420.2  660.52    4454  657.12
  4473.2  656.99  4490.5  659.74  4510.6  660.72  4560.8  658.05  4652.2  658.11
  4671.3  658.34  4686.6  660.46  4701.4  659.55  4731.5  661.27  4751.2  659.58
  4971.6  660.95  4979.1  649.22  4983.1  648.42  5004.1  649.22  5021.6  659.19
  5041.6  658.57  5081.6  660.59  5251.7  660.24  5342.1  662.95  5357.7  663.64
  5390.7  664.81  5531.7  672.32  5616.3   674.5  5647.1  674.47  5738.6  676.65
#Mann= 11 ,-1 , 0
  3840.5      .1       0  4374.8     .12       0    4454     .07       0
  4652.2      .1       0  4751.2     .12       0  4979.1     .07       0
  5004.1     .12       0  5342.1     .16       0  5357.7      .1       0
  5616.3     .16       0  5647.1      .1       0
Bank Sta=4309.71,5390.7
XS Rating Curve= 0 ,0
Exp/Cntr=0.3,0.1

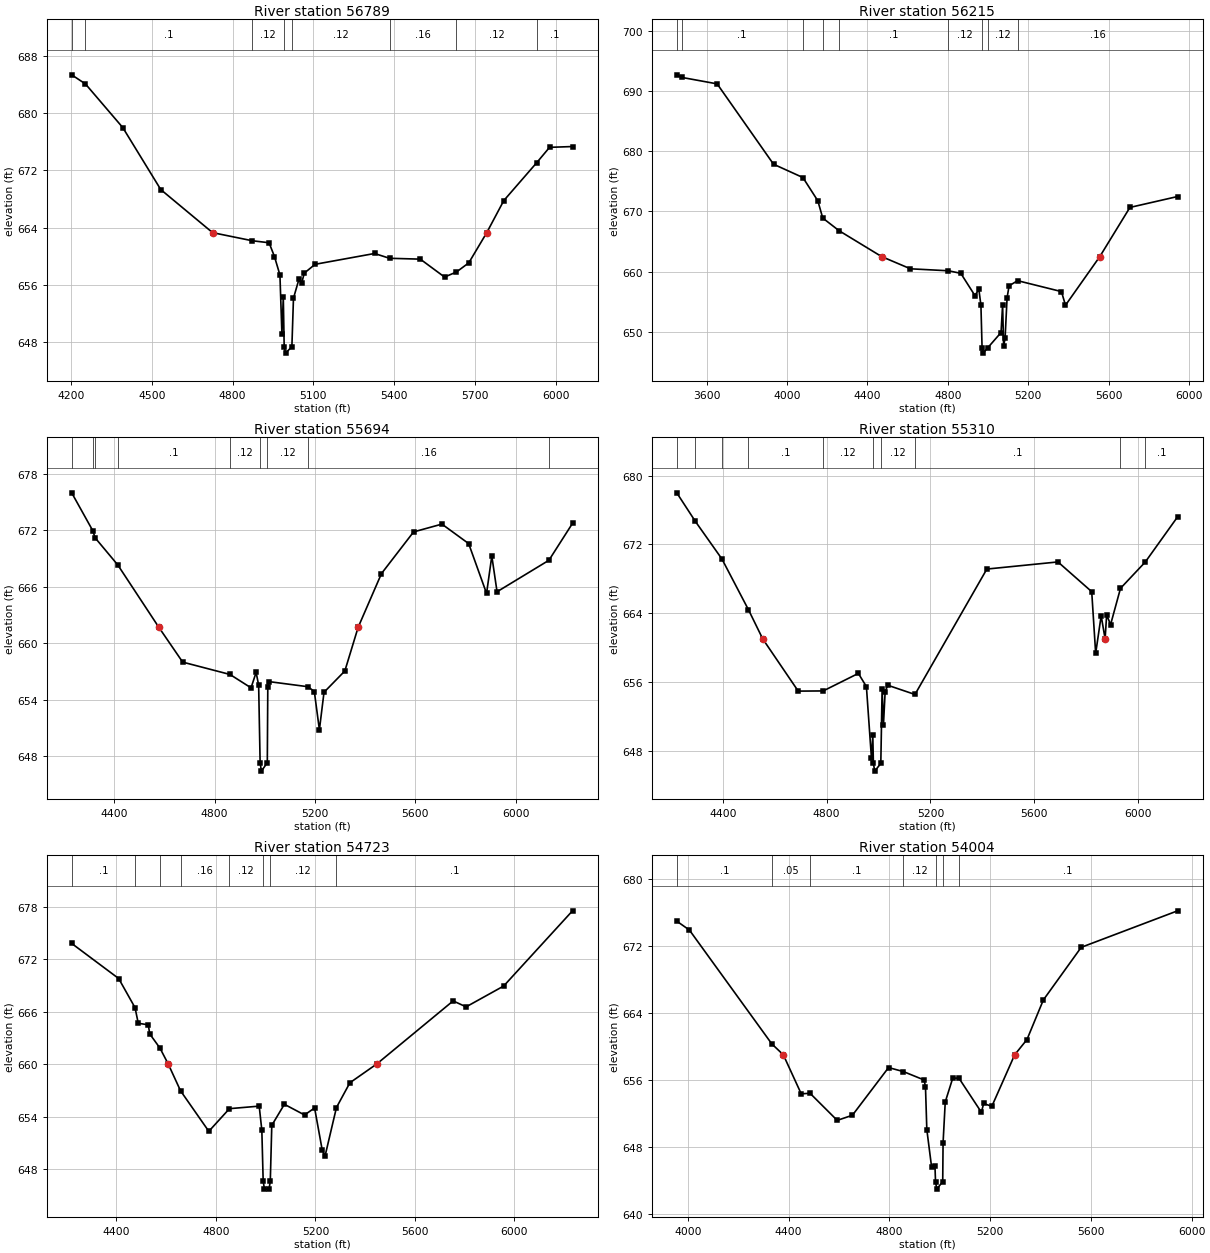
Type RM Length L Ch R = 1 ,56789   ,574,574,574
BEGIN DESCRIPTION:
CHACON CREEK 58.0
END DESCRIPTION:
XS GIS Cut Line= 3
      2011373.82     13611764.73       2010368.6     13611655.35
      2009519.83     13611672.71
#Sta/Elev= 30
  4202.3  685.34  4253.5  684.06  4392.2  677.96  4533.1  669.31 4725.64663.2912
  4873.1  662.16  4935.4  661.88  4955.5  659.94  4975.7  657.38  4983.1  649.11
  4988.2  654.28  4991.5  647.36  4996.7  646.46  5020.1  647.36    5026  654.13
  5046.1  656.75  5056.1  656.21  5066.2  657.64  5106.4  658.87  5327.1  660.38
  5382.7  659.71  5497.1  659.59  5587.1  657.09  5631.2  657.79  5677.1  659.07
 5743.89663.2914  5807.2  667.77  5929.1  673.05  5977.2  675.21  6062.4  675.32
#Mann= 8 ,-1 , 0
  4202.3     .05       0  4253.5      .1       0  4873.1     .12       0
  4991.5     .07       0  5020.1     .12       0  5382.7     .16       0
  5631.2     .12       0  5929.1      .1       0
Bank Sta=4725.64,5743.89
XS Rating Curve= 0 ,0
Exp/Cntr=0.3,0.1

Type RM Length L Ch R = 1 ,56215   ,521,521,521
BEGIN DESCRIPTION:
Mapping XS 5200ba81
END DESCRIPTION:
XS GIS Cut Line= 2
      2011965.57     13611201.47      2009478.36     13611352.65
#Sta/Elev= 30
  3451.5  692.66  3475.1  692.24  3652.4  691.16    3933  677.83  4079.1  675.62
  4153.4  671.76  4177.8   668.9  4259.1   666.8 4470.67662.5088  4614.2  660.48
  4803.5  660.15  4864.7  659.73  4934.8  656.05  4954.8  657.05  4964.9  654.42
  4970.6  647.39  4975.7  646.49  4999.2  647.39    5065  649.91  5072.8  654.53
  5077.8  647.64  5085.1  648.96  5095.1   655.7  5105.1  657.66  5147.3  658.51
  5365.6   656.7  5385.6  654.43 5556.44662.5088  5706.2  670.66  5943.3  672.47
#Mann= 9 ,-1 , 0
  3451.5     .16       0  3475.1      .1       0  4079.1     .08       0
  4177.8     .05       0  4259.1      .1       0  4803.5     .12       0
  4970.6     .07       0  4999.2     .12       0  5147.3     .16       0
Bank Sta=4470.67,5556.44
XS Rating Curve= 0 ,0
Exp/Cntr=0.3,0.1

Type RM Length L Ch R = 1 ,55694   ,384,384,384
BEGIN DESCRIPTION:
Mapping XS d73ec65b
END DESCRIPTION:
XS GIS Cut Line= 3
      2011143.38     13610706.05      2009815.25       13610884.
      2009316.11     13611309.35
#Sta/Elev= 30
  4230.6  675.95  4314.4  671.94    4324  671.17  4414.1   668.3 4577.96661.6707
  4672.9  657.98  4861.4  656.67  4945.3  655.25  4965.5  656.89  4975.6  655.54
  4981.5  647.31  4986.6  646.41  5010.1  647.31  5012.1  655.37  5017.2  655.91
  5172.1  655.37  5197.5  654.86  5217.7   650.8  5236.1  654.78  5319.1  657.04
 5372.05661.6703  5465.1  667.38    5593   671.8    5706  672.63  5812.6  670.56
  5883.9  665.27  5904.8  669.24  5925.7  665.45  6132.4  668.79  6226.4  672.71
#Mann= 9 ,-1 , 0
  4230.6      .1       0  4314.4     .08       0    4324     .05       0
  4414.1      .1       0  4861.4     .12       0  4981.5     .07       0
  5010.1     .12       0  5172.1     .16       0  6132.4      .1       0
Bank Sta=4577.96,5372.05
XS Rating Curve= 0 ,0
Exp/Cntr=0.3,0.1

Type RM Length L Ch R = 1 ,55310   ,587,587,587
BEGIN DESCRIPTION:
Mapping XS d0634bda
END DESCRIPTION:
XS GIS Cut Line= 3
      2011043.55     13610315.42       2009702.4     13610653.96
      2009242.34     13610949.09
#Sta/Elev= 30
  4222.4     678  4294.2  674.67  4396.5   670.3  4498.8  664.39 4553.72661.0029
  4690.4  654.93  4786.6  654.95  4922.2  656.99  4953.2  655.45  4972.6  647.13
  4977.8  649.79  4980.1  646.52  4985.3  645.62  5008.7  646.52  5013.7  655.19
  5018.8  650.96  5025.4  654.88  5035.7  655.61  5140.3  654.54  5417.3  669.13
  5691.3  669.96  5821.4   666.5  5836.6  659.32  5857.8   663.7 5873.01661.0046
  5878.9  663.79  5894.1  662.67  5932.3  666.89  6027.8  669.95  6152.2   675.2
#Mann= 10 ,-1 , 0
  4222.4      .1       0  4294.2     .08       0  4396.5     .05       0
  4498.8      .1       0  4786.6     .12       0  4980.1     .07       0
  5008.7     .12       0  5140.3      .1       0  5932.3     .16       0
  6027.8      .1       0
Bank Sta=4553.72,5873.01
XS Rating Curve= 0 ,0
Exp/Cntr=0.3,0.1

Type RM Length L Ch R = 1 ,54723   ,719,719,719
BEGIN DESCRIPTION:
Mapping XS 4413753b
END DESCRIPTION:
XS GIS Cut Line= 3
      2011039.23     13609950.83      2009836.95     13610141.81
       2009108.9      13610462.5
#Sta/Elev= 30
  4220.5  673.81  4409.3   669.8    4475  666.47    4488  664.68  4528.5  664.51
  4533.8  663.48  4575.1  661.85  4608.3660.0343    4658  656.96  4771.6  652.33
  4854.5  654.92  4974.1  655.21  4984.7  652.46  4990.1  646.62  4995.3  645.72
  5013.6  645.72  5018.7  646.62  5024.7  653.01  5075.3  655.42  5156.3   654.2
  5196.8     655  5227.2  650.22  5238.7  649.49  5284.6  655.05  5338.6  657.88
 5446.87660.0341  5753.6  667.24  5805.8  666.56  5956.7  668.94  6233.4  677.54
#Mann= 8 ,-1 , 0
  4220.5      .1       0    4475     .05       0  4575.1      .1       0
    4658     .16       0  4854.5     .12       0  4990.1     .07       0
  5018.7     .12       0  5284.6      .1       0
Bank Sta=4608.3,5446.87
XS Rating Curve= 0 ,0
Exp/Cntr=0.3,0.1

Type RM Length L Ch R = 1 ,54004   ,410,410,410
BEGIN DESCRIPTION:
Mapping XS 0d6372c5
END DESCRIPTION:
XS GIS Cut Line= 3
      2011013.13     13609408.31      2010171.15     13609660.04
      2009139.04     13610067.68
#Sta/Elev= 30
  3955.6  674.94  4005.8  673.88    4333  660.32 4378.67659.0203  4449.8  654.37
  4484.7  654.44  4592.7  651.21    4653  651.82  4796.6   657.5  4855.6  657.02
  4937.8  656.02  4943.2  655.18  4948.5  650.11  4967.5  645.64  4980.8  645.79
    4983  643.92  4988.1  643.02  5011.6  643.92    5013  648.52  5021.6   653.4
  5051.4  656.24    5076  656.24    5165  652.18  5174.3  653.22  5206.6  652.88
  5297.3  659.02  5346.2  660.84  5411.1  665.55  5561.4  671.82  5944.1  676.17
#Mann= 7 ,-1 , 0
  3955.6      .1       0    4333     .05       0  4484.7      .1       0
  4855.6     .12       0    4983     .07       0  5011.6     .12       0
    5076      .1       0
Bank Sta=4378.67,5297.3
XS Rating Curve= 0 ,0
Exp/Cntr=0.3,0.1