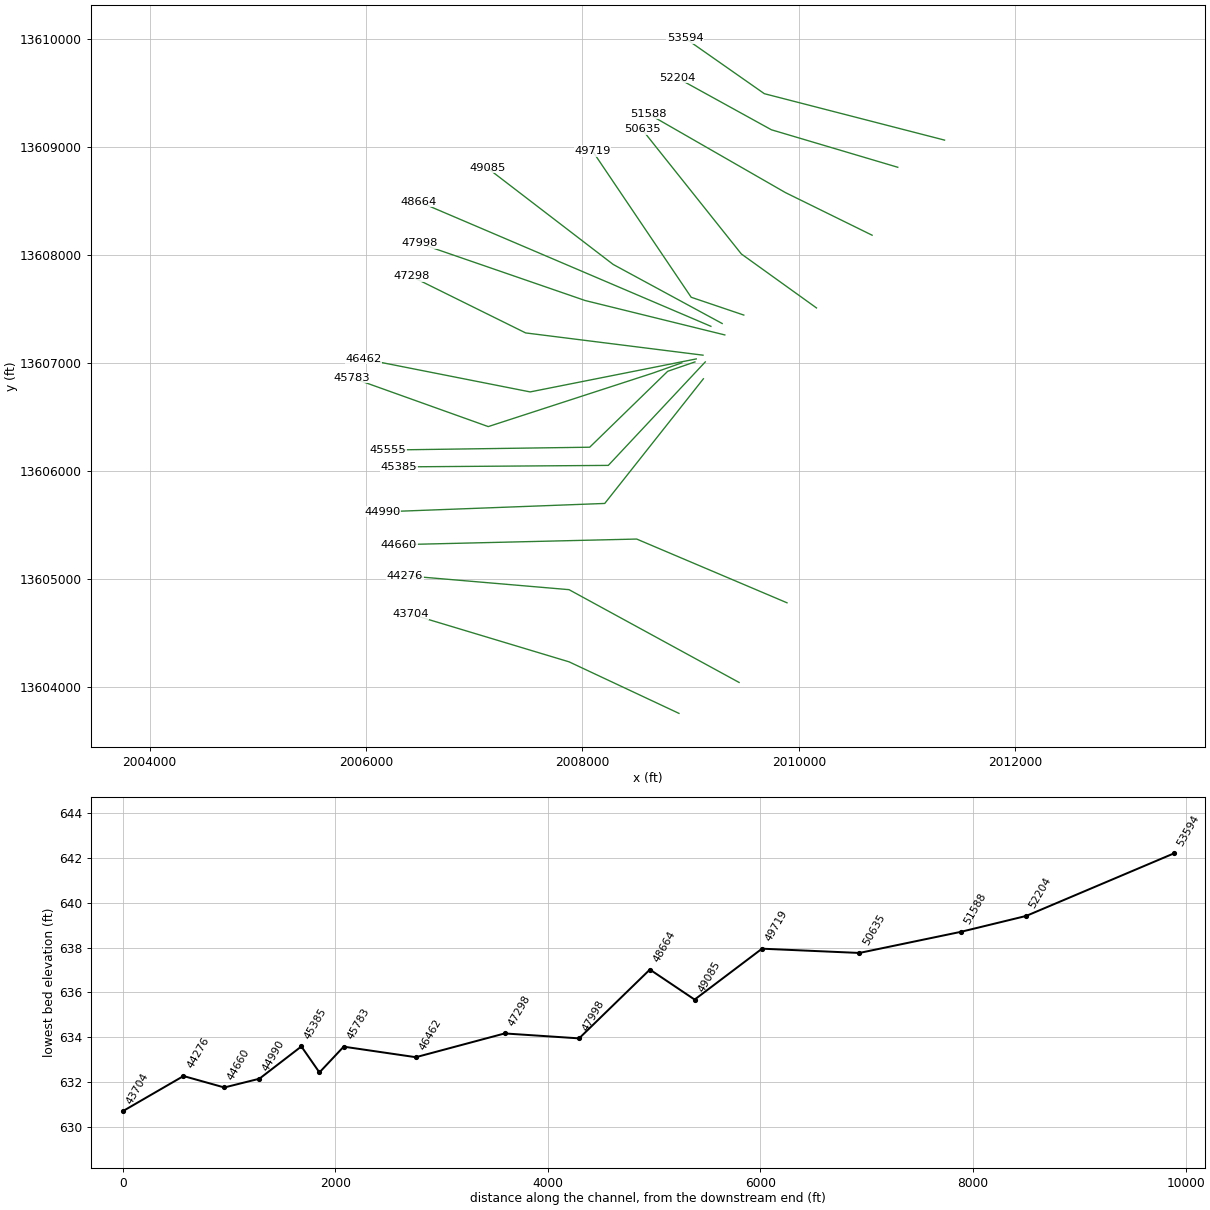
HEC-RAS study CHACON CREEK.prj: CHACON CREEK Base Level Engineering

--- CHACON CREEK.g01 (geometry) --- (continued)

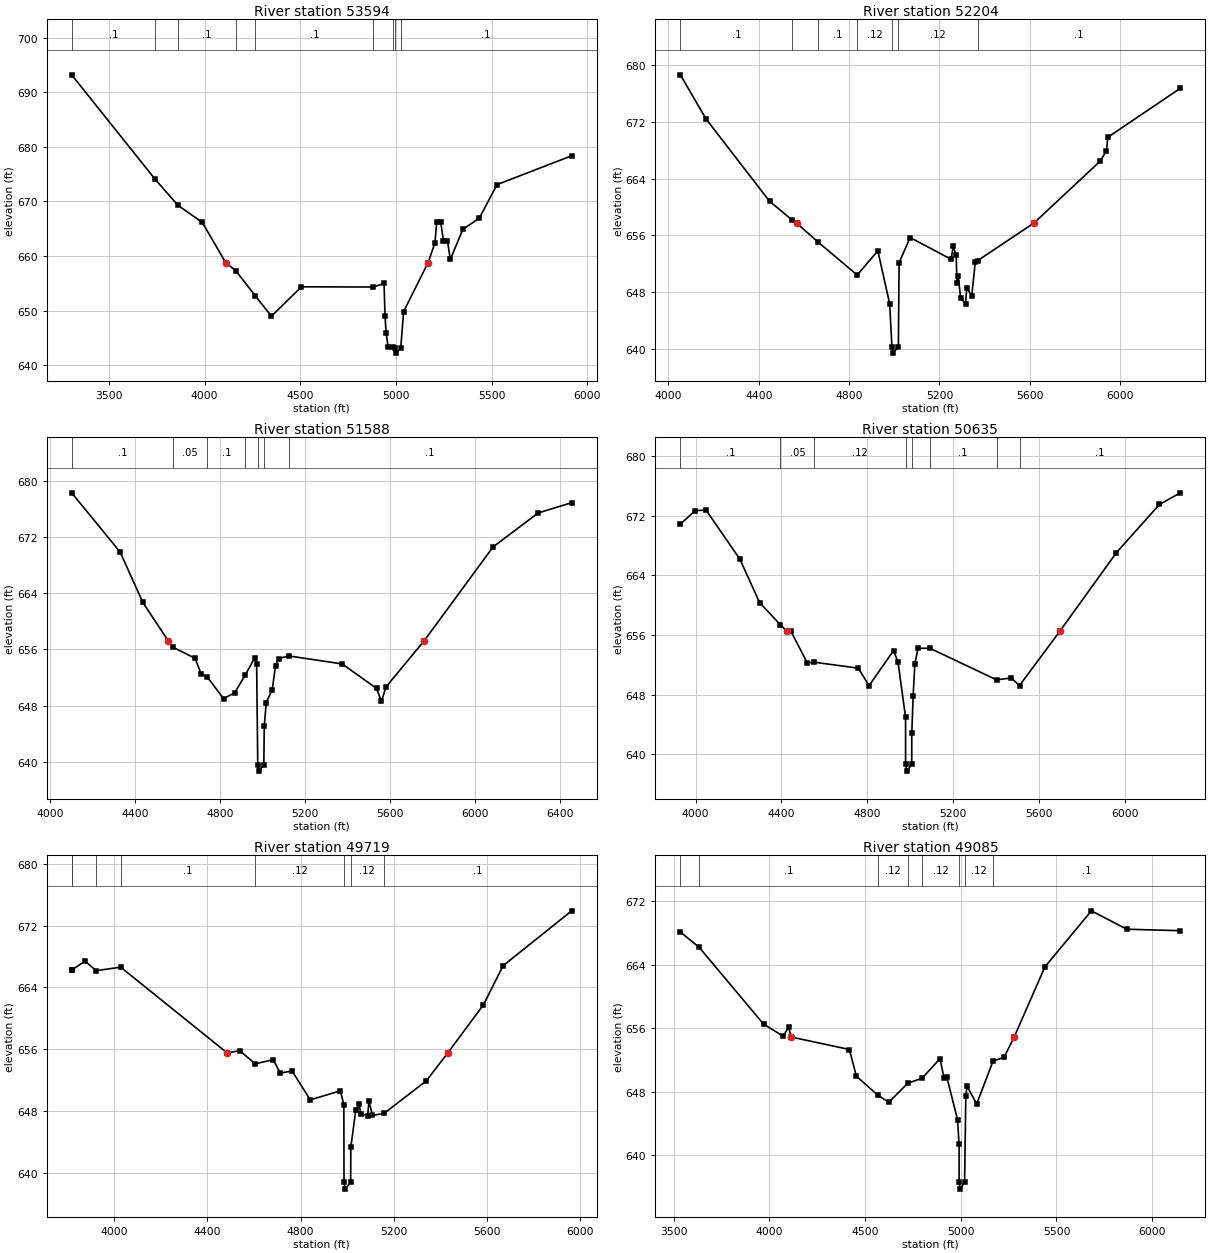
Type RM Length L Ch R = 1 ,53594   ,1390,1390,1390
BEGIN DESCRIPTION:
Mapping XS 431e7652
END DESCRIPTION:
XS GIS Cut Line= 3
      2011345.72     13609060.85       2009680.7     13609490.77
      2008949.97     13610003.51
#Sta/Elev= 30
  3305.3  693.22  3741.4  674.07    3861  669.29  3987.7  666.17 4110.38658.7643
  4163.2   657.3  4265.6  652.65  4349.2  648.97  4505.6  654.36  4880.3  654.32
  4937.3  654.97  4942.4  649.01  4948.2  645.95  4958.5  643.36  4982.7  643.24
  4995.9   643.1    5001   642.2  5024.5   643.1  5039.5  649.82 5167.07658.7648
  5203.4  662.42  5212.1   666.2    5233  666.32  5247.8  662.77  5268.7  662.82
  5283.5  659.38  5348.9  664.88    5435  666.95  5527.6  673.09  5917.6  678.38
#Mann= 9 ,-1 , 0
  3305.3      .1       0  3741.4     .05       0    3861      .1       0
  4163.2     .05       0  4265.6      .1       0  4880.3     .12       0
  4982.7      .1       0  4995.9     .07       0  5024.5      .1       0
Bank Sta=4110.38,5167.07
XS Rating Curve= 0 ,0
Exp/Cntr=0.3,0.1

Type RM Length L Ch R = 1 ,52204   ,616,616,616
BEGIN DESCRIPTION:
Mapping XS 7fd87bac
END DESCRIPTION:
XS GIS Cut Line= 3
      2010913.38     13608809.33       2009745.8     13609156.57
      2008873.41     13609638.34
#Sta/Elev= 30
  4052.9  678.62    4166  672.42  4447.7  660.81  4547.9  658.16 4567.49657.7364
  4664.2  655.02    4836  650.41  4927.3  653.83  4979.7  646.38  4989.8  640.31
    4995  639.41  5018.4  640.31  5021.5  652.15  5070.5   655.7  5252.1  652.63
  5261.4   654.5  5274.3  653.21  5277.9  649.27  5283.6  650.32  5293.9  647.23
  5315.7  646.32  5321.4  648.62  5343.2  647.46  5359.2  652.31  5369.2  652.44
 5618.74657.7365  5911.6  666.44  5940.1  667.91  5945.9  669.82  6267.6  676.73
#Mann= 7 ,-1 , 0
  4052.9      .1       0  4547.9     .08       0  4664.2      .1       0
    4836     .12       0  4989.8     .07       0  5018.4     .12       0
  5369.2      .1       0
Bank Sta=4567.49,5618.74
XS Rating Curve= 0 ,0
Exp/Cntr=0.3,0.1

Type RM Length L Ch R = 1 ,51588   ,953,953,953
BEGIN DESCRIPTION:
CHACON CREEK 57.0
END DESCRIPTION:
XS GIS Cut Line= 3
      2010676.39     13608179.99        2009875.       13608575.
      2008608.43     13609304.13
#Sta/Elev= 30
  4101.7  678.27  4329.9  669.85  4436.6   662.7 4556.54657.2204  4579.8   656.3
    4683  654.74  4711.6   652.5  4739.7  652.12  4816.8  649.02  4868.8  649.82
  4919.9  652.39  4964.3  654.84  4972.9  653.87  4978.1   639.6  4983.2   638.7
  5006.7   639.6  5008.8  645.12  5018.2  648.45  5046.2  650.29    5062   653.7
  5075.9   654.7    5124  655.08  5375.9  653.94  5537.5  650.46  5560.5  648.62
  5582.1  650.67 5761.55657.2207  6086.5  670.58    6299  675.41  6456.6  676.87
#Mann= 7 ,-1 , 0
  4101.7      .1       0  4579.8     .05       0  4739.7      .1       0
  4919.9     .12       0  4978.1     .07       0  5006.7     .12       0
    5124      .1       0
Bank Sta=4556.54,5761.55
XS Rating Curve= 0 ,0
Exp/Cntr=0.3,0.1

Type RM Length L Ch R = 1 ,50635   ,916,916,916
BEGIN DESCRIPTION:
Mapping XS 3e7c2b3e
END DESCRIPTION:
XS GIS Cut Line= 3
      2010162.44     13607506.42      2009468.02     13608006.39
      2008551.35     13609159.18
#Sta/Elev= 30
  3929.5  670.85  3999.1  672.67  4049.4  672.71  4206.5  666.15  4298.6  660.33
  4394.2  657.39    4425656.5059  4443.4  656.54  4520.7  652.25  4553.7  652.35
  4757.6  651.55  4808.3  649.22  4922.1  653.91  4942.9  652.36  4978.1  644.96
  4978.2  638.66  4983.4  637.76  5006.8  638.66    5007  642.84  5013.4  647.89
  5021.4  652.13  5035.8  654.21  5091.3  654.22  5401.8  649.99  5469.9  650.24
  5508.7  649.23 5696.63656.5065    5960  667.03  6160.3  673.48    6258  675.04
#Mann= 8 ,-1 , 0
  3929.5      .1       0  4394.2     .05       0  4553.7     .12       0
  4978.2     .07       0  5006.8     .12       0  5091.3      .1       0
  5401.8     .12       0  5508.7      .1       0
Bank Sta=4425,5696.63
XS Rating Curve= 0 ,0
Exp/Cntr=0.3,0.1

Type RM Length L Ch R = 1 ,49719   ,634,634,634
BEGIN DESCRIPTION:
Mapping XS 76a2e6c7
END DESCRIPTION:
XS GIS Cut Line= 3
       2009490.6     13607440.42      2009004.48     13607605.35
      2008093.01     13608959.54
#Sta/Elev= 30
  3817.8  666.25  3818.2  666.26    3875   667.4  3923.2  666.17  4028.2  666.62
 4485.04655.5458  4538.9  655.83  4605.7  654.14  4682.9  654.67  4712.8  652.95
  4763.8   653.2  4841.8  649.48  4970.8  650.65  4985.8  648.87  4986.5  638.85
  4991.6  637.95  5015.1  638.85  5015.7  643.34  5036.8  648.11  5051.7  648.92
  5057.8  647.71  5087.7  647.42  5093.8   649.3  5108.7  647.48  5157.9  647.72
  5339.7  651.94 5431.87 655.546  5584.3  661.74  5669.6  666.82  5963.5   673.9
#Mann= 8 ,-1 , 0
  3817.8      .1       0  3818.2     .08       0  3923.2     .05       0
  4028.2      .1       0  4605.7     .12       0  4986.5     .07       0
  5015.1     .12       0  5157.9      .1       0
Bank Sta=4485.04,5431.87
XS Rating Curve= 0 ,0
Exp/Cntr=0.3,0.1

Type RM Length L Ch R = 1 ,49085   ,421,421,421
BEGIN DESCRIPTION:
Mapping XS 07f20c99
END DESCRIPTION:
XS GIS Cut Line= 3
      2009290.92     13607362.31        2008284.     13607909.17
      2007120.77     13608803.29
#Sta/Elev= 30
  3534.8  668.12  3632.6   666.2  3969.1  656.51  4072.7  654.97  4100.3  656.14
 4113.76654.8756  4417.8   653.3  4454.8  649.92  4565.2  647.56  4623.9  646.64
  4722.8  649.04  4797.5  649.67  4891.4  652.14  4912.2  649.74  4926.7  649.86
  4982.9  644.45  4991.1  641.36  4991.3  636.58  4996.4  635.68  5019.9  636.58
  5026.4  647.43  5032.7  648.67    5083  646.42  5168.7  651.85  5225.8   652.3
 5278.99654.8752  5439.6  663.72  5682.5   670.8  5867.4  668.48  6147.8  668.29
#Mann= 8 ,-1 , 0
  3534.8     .05       0  3632.6      .1       0  4565.2     .12       0
  4722.8     .16       0  4797.5     .12       0  4991.3     .07       0
  5019.9     .12       0  5168.7      .1       0
Bank Sta=4113.76,5278.99
XS Rating Curve= 0 ,0
Exp/Cntr=0.3,0.1

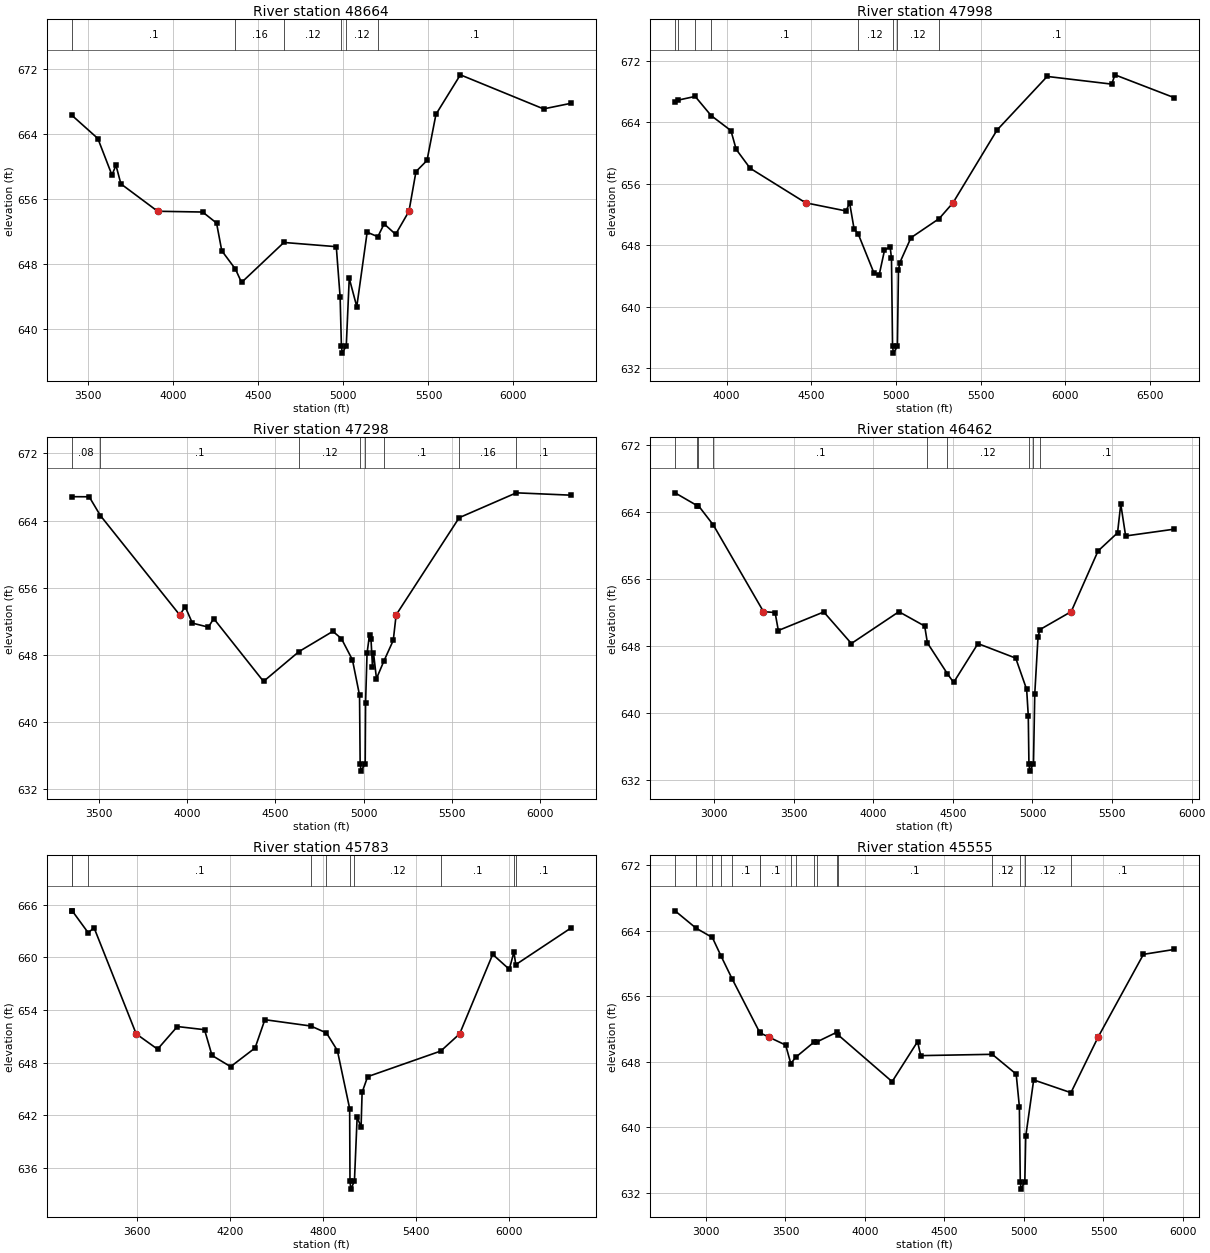
Type RM Length L Ch R = 1 ,48664   ,666,666,666
BEGIN DESCRIPTION:
Mapping XS 235e2033
END DESCRIPTION:
XS GIS Cut Line= 2
      2009186.76     13607336.26      2006487.16     13608490.75
#Sta/Elev= 30
  3401.8  666.36    3556  663.47  3638.9  658.97  3662.5  660.17  3691.5  657.88
 3907.68654.5037  4172.4  654.41    4254  653.05  4284.7  649.64  4365.2  647.37
    4401  645.73    4650  650.66  4958.1  650.14  4980.7  643.92  4988.2  637.92
  4993.3  637.02  5016.8  637.92  5034.3  646.24  5078.6  642.75  5139.6  651.92
  5202.4  651.37  5239.4  652.95    5307  651.66 5385.46654.5038  5426.7  659.39
  5491.6  660.77  5544.2  666.45  5687.7  671.32  6177.1  667.12  6337.9  667.81
#Mann= 6 ,-1 , 0
  3401.8      .1       0  4365.2     .16       0    4650     .12       0
  4988.2     .07       0  5016.8     .12       0  5202.4      .1       0
Bank Sta=3907.68,5385.46
XS Rating Curve= 0 ,0
Exp/Cntr=0.3,0.1

Type RM Length L Ch R = 1 ,47998   ,700,700,700
BEGIN DESCRIPTION:
CHACON CREEK 56.0
END DESCRIPTION:
XS GIS Cut Line= 3
      2009315.28     13607256.39        2008025.       13607575.
      2006495.82     13608103.61
#Sta/Elev= 30
  3696.1  666.63  3712.8  666.87  3814.9  667.36  3908.9  664.87    4026  662.91
  4056.9  660.47  4139.3  658.01 4467.13 653.512  4705.8  652.45  4726.4  653.52
  4753.1  650.09  4776.6   649.5  4870.6  644.35  4901.5  644.18  4932.4  647.33
  4965.5  647.81  4973.6  646.31  4979.9  634.85  4985.1  633.95  5008.5  634.85
  5014.8  644.75  5022.6  645.71  5088.6  648.97  5255.2  651.46 5336.68653.5118
  5596.6  662.98  5892.5  669.96  6273.6  668.96  6292.4  670.17  6643.1  667.19
#Mann= 8 ,-1 , 0
  3696.1      .1       0  3712.8     .08       0  3814.9     .05       0
  3908.9      .1       0  4776.6     .12       0  4979.9     .07       0
  5008.5     .12       0  5255.2      .1       0
Bank Sta=4467.13,5336.68
XS Rating Curve= 0 ,0
Exp/Cntr=0.3,0.1

Type RM Length L Ch R = 1 ,47298   ,836,836,836
BEGIN DESCRIPTION:
CHACON CREEK 55.0
END DESCRIPTION:
XS GIS Cut Line= 3
      2009113.87     13607068.89        2007475.       13607275.
      2006419.73      13607797.9
#Sta/Elev= 30
  3345.2  666.84  3444.8  666.83  3507.9   664.6  3957.4652.7694  3989.1  653.73
  4029.4  651.79  4120.1  651.31  4150.4  652.33  4432.6  644.85  4633.5   648.4
  4825.6  650.81  4873.9  649.95  4936.5  647.42  4976.8   643.2  4980.2  635.07
  4985.3  634.17  5008.8  635.07    5011  642.32  5019.3   648.2  5033.4  650.41
  5041.6  649.92  5050.2  646.58  5055.8  648.27  5072.7  645.18  5114.9  647.28
  5167.9  649.74 5184.14 652.769  5541.5  664.34  5865.4   667.3  6174.7  667.02
#Mann= 8 ,-1 , 0
  3345.2     .08       0  3507.9      .1       0  4633.5     .12       0
  4980.2     .07       0  5008.8     .12       0  5114.9      .1       0
  5541.5     .16       0  5865.4      .1       0
Bank Sta=3957.4,5184.14
XS Rating Curve= 0 ,0
Exp/Cntr=0.3,0.1

Type RM Length L Ch R = 1 ,46462   ,679,679,679
BEGIN DESCRIPTION:
CHACON CREEK 54.0
END DESCRIPTION:
XS GIS Cut Line= 3
      2009051.36     13607034.17      2007516.64     13606728.62
      2005974.97     13607034.17
#Sta/Elev= 30
  2754.7  666.28  2894.7  664.74  2901.6  664.75    2995  662.45 3310.24652.1213
  3383.2  652.01  3403.5  649.87    3689  652.08  3862.4  648.32    4161  652.11
  4322.9   650.4  4340.1  648.39  4465.9  644.71  4504.7  643.68  4657.6  648.31
  4894.8  646.58  4963.5  642.85  4973.7  639.72  4977.8  634.01    4983  633.11
  5006.4  634.01  5014.4   642.3  5034.8  649.05    5046  649.97 5243.35652.1207
    5412  659.35  5534.4  661.51  5554.7  664.94  5585.3  661.14  5891.2  661.95
#Mann= 9 ,-1 , 0
  2754.7     .08       0  2894.7      .1       0  2901.6     .05       0
    2995      .1       0  4340.1     .16       0  4465.9     .12       0
  4977.8     .07       0  5006.4     .12       0    5046      .1       0
Bank Sta=3310.24,5243.35
XS Rating Curve= 0 ,0
Exp/Cntr=0.3,0.1

Type RM Length L Ch R = 1 ,45783   ,228,228,228
BEGIN DESCRIPTION:
Mapping XS 1f9bbcba
END DESCRIPTION:
XS GIS Cut Line= 4
      2008917.63      13606997.7      2008648.58     13606902.23
      2007129.48     13606407.44      2005870.81     13606858.82
#Sta/Elev= 30
  3179.2  665.28  3183.3  665.27  3286.5  662.77  3323.5  663.37 3595.66651.2638
  3733.4  649.52  3861.1   652.1  4036.4  651.74  4084.5  648.81  4204.7  647.53
  4362.4  649.66  4425.5  652.88    4722  652.16  4822.8  651.37  4893.1  649.37
  4972.4  642.75  4974.5  634.48  4979.7  633.58  5003.1  634.48  5020.7  641.79
    5046  640.63  5052.7   644.6  5088.3  646.39  5560.1  649.31 5681.74651.2637
  5894.9  660.32    6002  658.62  6031.9  660.59  6043.7  659.15  6399.5  663.32
#Mann= 10 ,-1 , 0
  3179.2     .08       0  3183.3     .05       0  3286.5      .1       0
    4722     .16       0  4822.8     .12       0  4974.5     .07       0
  5003.1     .12       0  5560.1      .1       0  6031.9     .07       0
  6043.7      .1       0
Bank Sta=3595.66,5681.74
XS Rating Curve= 0 ,0
Exp/Cntr=0.3,0.1

Type RM Length L Ch R = 1 ,45555   ,170,170,170
BEGIN DESCRIPTION:
Mapping XS 7f7c7458
END DESCRIPTION:
XS GIS Cut Line= 4
      2009039.23      13607006.4      2008787.47     13606919.59
      2008066.98     13606216.46       2006200.7     13606190.42
#Sta/Elev= 30
  2805.9  666.45  2937.5  664.34  3040.5  663.19  3096.5  660.87  3164.5  658.15
  3338.3  651.58  3342.9  651.51 3393.64651.0334  3501.5  650.04  3533.8  647.78
  3564.7  648.55  3679.5   650.4  3698.1  650.43  3825.3  651.63  3831.5  651.28
  4170.9  645.57  4330.9  650.46  4350.9  648.75  4800.6  648.91    4951  646.49
    4971  642.52  4976.7  633.33  4981.9  632.43  5005.3  633.33    5011  638.87
    5061  645.78  5295.2  644.22 5466.65651.0334  5751.1  661.13  5945.4  661.73
#Mann= 17 ,-1 , 0
  2805.9     .08       0  2937.5     .05       0  3040.5      .1       0
  3096.5     .05       0  3164.5      .1       0  3338.3     .05       0
  3342.9      .1       0  3533.8     .08       0  3564.7      .1       0
  3679.5     .05       0  3698.1      .1       0  3825.3     .05       0
  3831.5      .1       0  4800.6     .12       0  4976.7     .07       0
  5005.3     .12       0  5295.2      .1       0
Bank Sta=3393.64,5466.65
XS Rating Curve= 0 ,0
Exp/Cntr=0.3,0.1

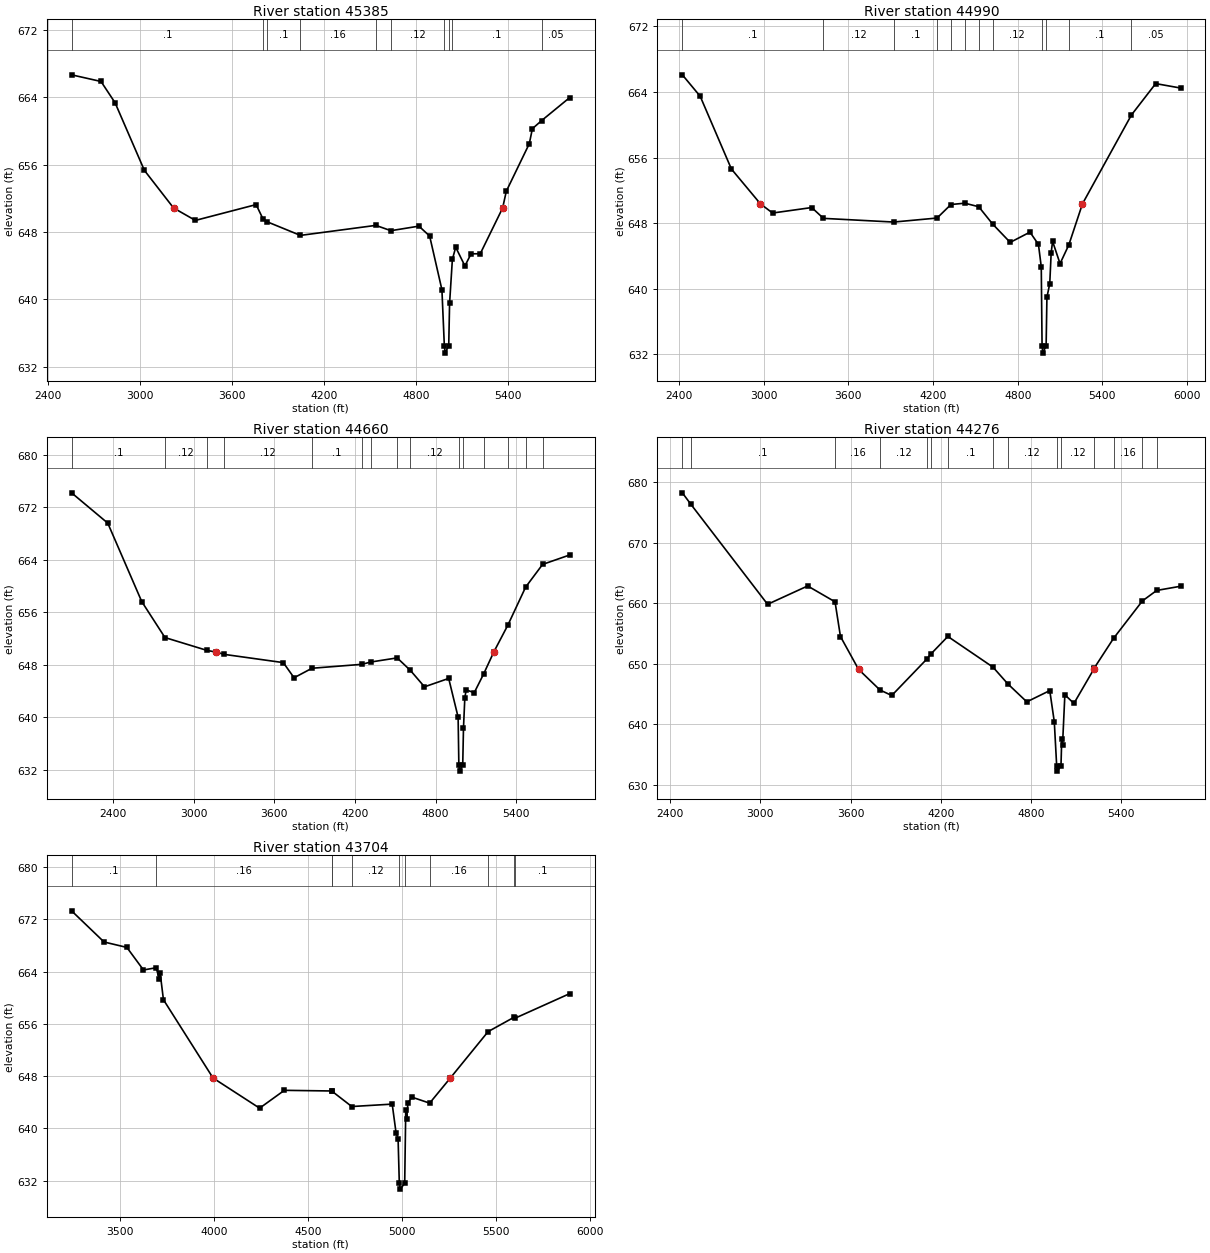
Type RM Length L Ch R = 1 ,45385   ,395,395,395
BEGIN DESCRIPTION:
CHACON CREEK 53.0
END DESCRIPTION:
XS GIS Cut Line= 3
      2009134.69     13607006.39      2008238.86     13606048.06
      2006301.34     13606034.17
#Sta/Elev= 30
  2554.1  666.66  2746.1  665.87  2837.9  663.34  3028.9  655.31 3219.36650.8395
  3361.6  649.36  3757.8  651.24  3802.6  649.54  3830.6  649.19  4046.8  647.58
  4538.6  648.77    4637  648.14  4819.8  648.68  4889.8   647.5  4969.8  641.12
  4985.5  634.49  4990.7  633.59  5014.2  634.49  5019.8  639.52    5038  644.73
  5059.8  646.17  5119.8  643.95  5159.8  645.39  5219.8   645.4 5365.83650.8394
  5389.8  652.83  5539.8  658.48  5559.8  660.26  5620.6  661.23  5803.5  663.96
#Mann= 10 ,-1 , 0
  2554.1      .1       0  3802.6     .12       0  3830.6      .1       0
  4046.8     .16       0  4538.6     .08       0    4637     .12       0
  4985.5     .07       0  5014.2     .12       0    5038      .1       0
  5620.6     .05       0
Bank Sta=3219.36,5365.83
XS Rating Curve= 0 ,0
Exp/Cntr=0.3,0.1

Type RM Length L Ch R = 1 ,44990   ,330,330,330
BEGIN DESCRIPTION:
Mapping XS 267de710
END DESCRIPTION:
XS GIS Cut Line= 3
      2009117.36     13606850.18      2008205.87     13605695.63
      2006149.34     13605617.53
#Sta/Elev= 30
  2424.2   666.1  2550.4  663.49  2771.7  654.61 2977.24 650.363  3063.5  649.24
  3340.8  649.91  3423.7  648.59  3921.5  648.14  4228.7  648.63    4327  650.28
  4425.3  650.44  4523.7  650.01    4622   647.9  4746.7  645.66  4886.8  646.91
  4946.8  645.41  4966.8  642.68  4972.5  633.05  4977.6  632.15  5001.2  633.05
  5006.9  638.98  5026.9  640.61  5036.9  644.37  5046.9  645.79  5099.8  643.07
    5162  645.35 5258.69 650.363  5605.4   661.2  5777.4  665.03  5953.2  664.49
#Mann= 12 ,-1 , 0
  2424.2      .1       0  3423.7     .12       0  3921.5      .1       0
  4228.7     .16       0    4327     .12       0  4425.3      .1       0
  4523.7     .05       0    4622     .12       0  4972.5     .07       0
  5001.2     .12       0    5162      .1       0  5605.4     .05       0
Bank Sta=2977.24,5258.69
XS Rating Curve= 0 ,0
Exp/Cntr=0.3,0.1

Type RM Length L Ch R = 1 ,44660   ,384,384,384
BEGIN DESCRIPTION:
CHACON CREEK 52.0
END DESCRIPTION:
XS GIS Cut Line= 3
      2009889.86     13604775.51      2008501.01     13605365.77
       2006304.8     13605313.69
#Sta/Elev= 30
  2092.7  674.18    2362  669.56  2614.8   657.6  2787.5  652.12  3100.3  650.16
 3167.48649.9082  3226.6  649.56  3667.8   648.3  3747.8  645.99  3881.1  647.44
  4252.1  648.04  4318.3  648.39    4515  649.02  4613.3  647.11  4718.1  644.61
  4898.1  645.89  4968.2  639.99  4973.8  632.66    4979  631.76  5002.5  632.66
  5008.2  638.35  5018.2  642.94  5028.2  644.14  5088.2  643.72  5157.4  646.54
 5233.41649.9084  5338.2  654.01  5470.6  659.81  5596.7  663.27  5798.6  664.71
#Mann= 15 ,-1 , 0
  2092.7      .1       0  2787.5     .12       0  3100.3      .1       0
  3226.6     .12       0  3881.1      .1       0  4252.1     .16       0
  4318.3     .12       0    4515     .05       0  4613.3     .12       0
  4973.8     .07       0  5002.5     .12       0  5157.4      .1       0
  5338.2     .16       0  5470.6      .1       0  5596.7     .05       0
Bank Sta=3167.48,5233.41
XS Rating Curve= 0 ,0
Exp/Cntr=0.3,0.1

Type RM Length L Ch R = 1 ,44276   ,572,572,572
BEGIN DESCRIPTION:
CHACON CREEK 51.0
END DESCRIPTION:
XS GIS Cut Line= 3
      2009447.17     13604037.66      2007876.01     13604897.02
       2006358.5     13605027.09
#Sta/Elev= 30
  2480.7  678.23  2535.5   676.4  3047.8  659.82  3314.3  662.85  3496.4  660.23
  3532.5   654.5 3652.87649.0786  3795.3  645.67  3873.7  644.76  4110.2  650.86
  4132.8  651.58  4246.9  654.51  4547.2  649.44  4646.2  646.67  4772.1  643.71
  4924.9  645.57    4955  640.42  4970.8  633.17  4975.9  632.27  4999.5  633.17
  5004.6  637.65  5009.6  636.51  5025.3  644.88  5085.5  643.45 5217.32649.0783
  5218.9  649.22  5348.9  654.19  5541.1  660.38  5636.3  662.11  5794.6   662.8
#Mann= 15 ,-1 , 0
  2480.7     .05       0  2535.5      .1       0  3496.4     .16       0
  3795.3     .12       0  4110.2     .16       0  4132.8     .12       0
  4246.9      .1       0  4547.2     .05       0  4646.2     .12       0
  4970.8     .07       0  4999.5     .12       0  5218.9      .1       0
  5348.9     .16       0  5541.1      .1       0  5636.3     .05       0
Bank Sta=3652.87,5217.32
XS Rating Curve= 0 ,0
Exp/Cntr=0.3,0.1

Type RM Length L Ch R = 1 ,43704   ,652,652,652
BEGIN DESCRIPTION:
CHACON CREEK 50.0
END DESCRIPTION:
XS GIS Cut Line= 3
      2008891.62     13603751.19      2007876.01     13604228.62
      2006409.46     13604671.18
#Sta/Elev= 30
  3240.6  673.29  3413.7  668.52  3535.2  667.69  3623.6  664.24  3691.5  664.58
  3707.2  662.89  3712.7  663.74    3730  659.69  3994.3647.7067  4242.4  643.09
  4374.3  645.82  4626.4  645.72  4629.6  645.65  4733.4  643.34  4948.8  643.71
  4969.7  639.25  4980.2  638.43  4986.7   631.6  4991.9   630.7  5015.4   631.6
    5021  642.77  5026.2  641.48  5032.4  643.86  5053.3  644.78  5148.4  643.86
  5258.6647.7068  5459.6   654.8  5596.6  656.98  5604.4  656.87  5894.7  660.62
#Mann= 11 ,-1 , 0
  3240.6      .1       0  3691.5     .16       0  4626.4      .1       0
  4629.6     .08       0  4733.4     .12       0  4986.7     .07       0
  5015.4     .12       0  5148.4     .16       0  5459.6      .1       0
  5596.6     .16       0  5604.4      .1       0
Bank Sta=3994.3,5258.6
XS Rating Curve= 0 ,0
Exp/Cntr=0.3,0.1