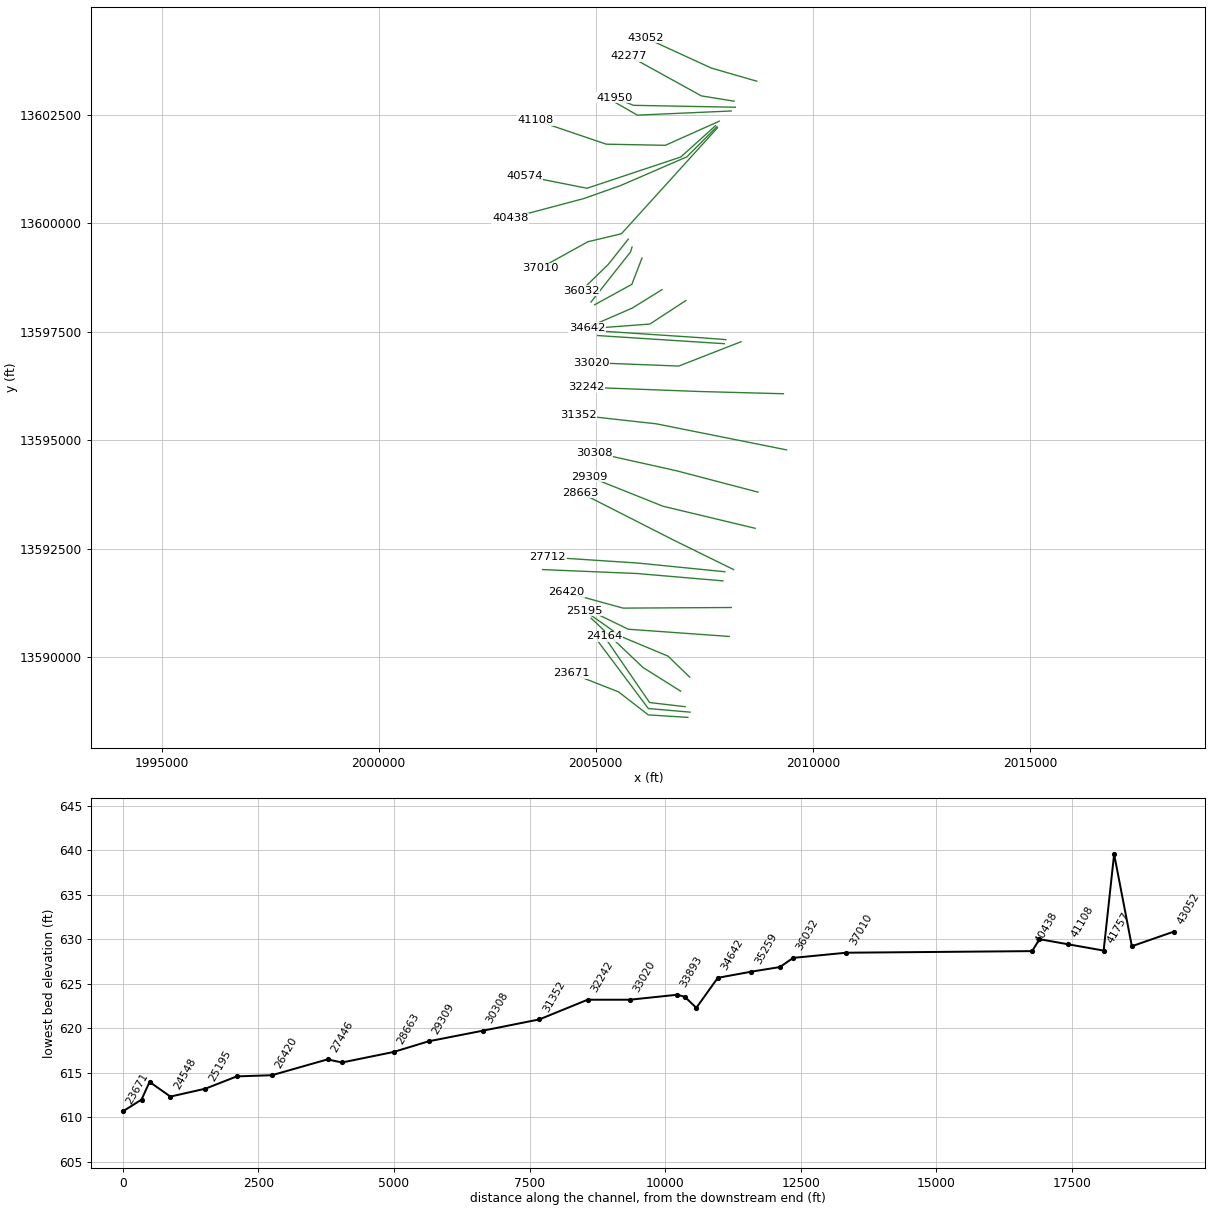
HEC-RAS study CHACON CREEK.prj: CHACON CREEK Base Level Engineering

--- CHACON CREEK.g01 (geometry) --- (continued)

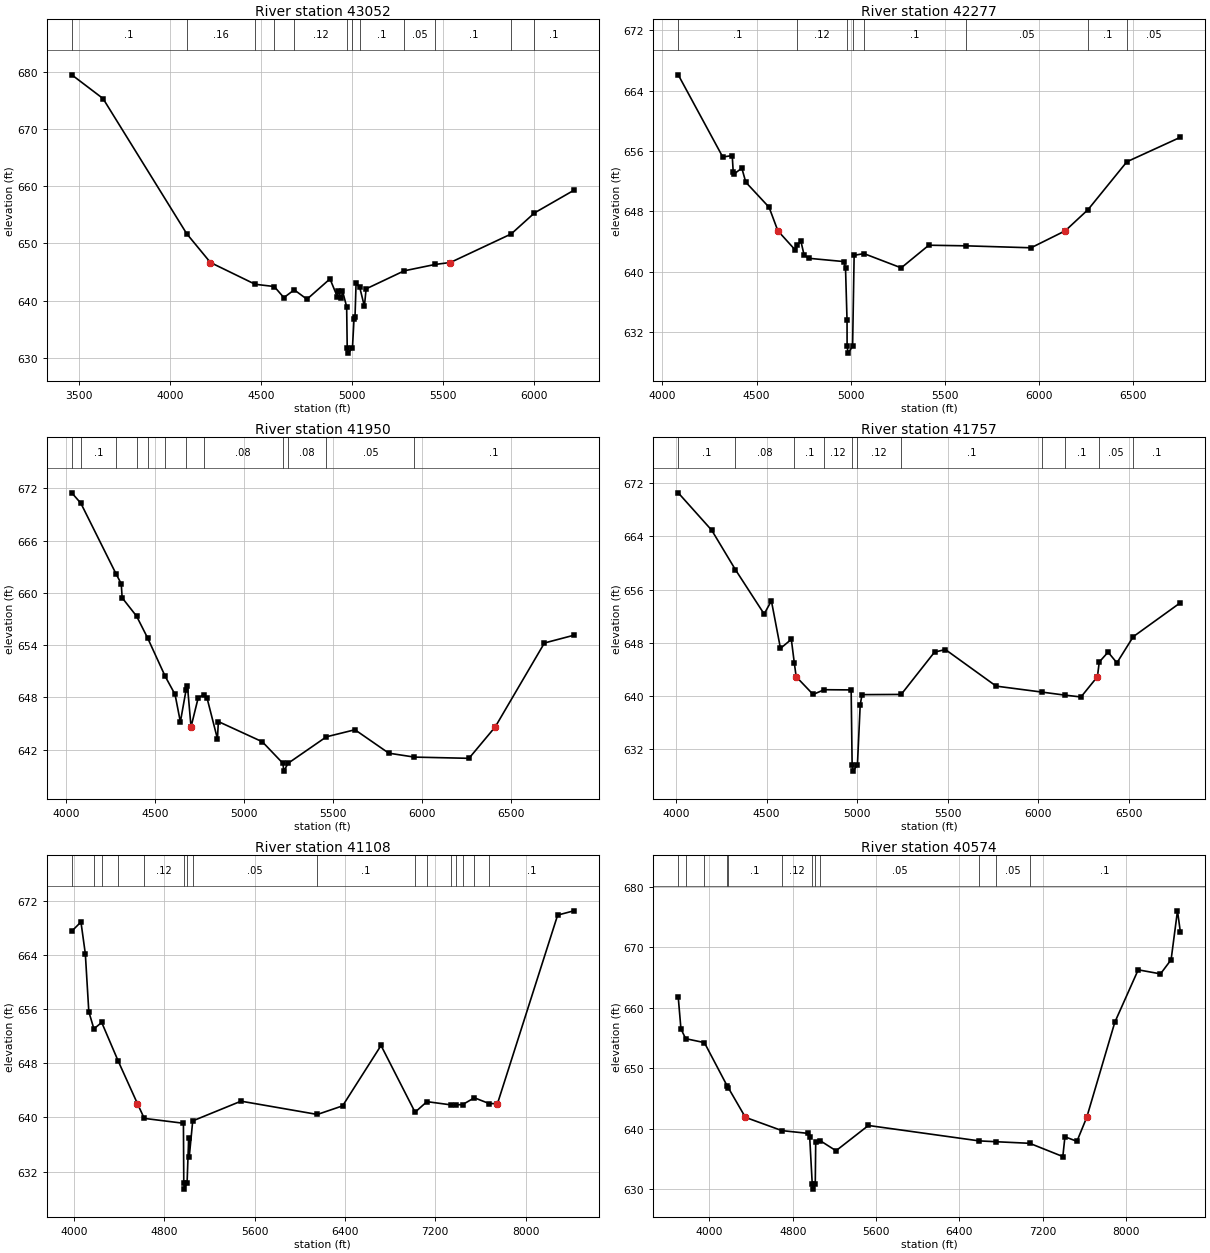
Type RM Length L Ch R = 1 ,43052   ,775,775,775
BEGIN DESCRIPTION:
CHACON CREEK 49.0
END DESCRIPTION:
XS GIS Cut Line= 3
      2008709.36     13603273.75        2007659.     13603577.57
      2006149.25     13604271.71
#Sta/Elev= 30
  3461.2  679.43  3632.6  675.29  4091.9  651.69 4222.05 646.662  4467.7  642.86
  4572.1  642.47  4625.1  640.53  4681.9  641.89  4751.8  640.25  4878.2   643.8
  4918.1  640.71  4923.6  641.76  4941.1   640.4  4946.6  641.72  4969.6  638.95
  4972.7  631.74  4977.8  630.84  5001.4  631.74    5010   636.8  5015.5  637.18
  5021.3  643.06  5041.6   642.3    5067     639  5076.3  642.06  5285.4  645.21
  5456.3  646.33  5538.6 646.662  5872.6  651.65  6000.3  655.32  6216.3  659.27
#Mann= 12 ,-1 , 0
  3461.2      .1       0  4091.9     .16       0  4467.7     .12       0
  4572.1     .05       0  4681.9     .12       0  4972.7     .07       0
  5001.4     .12       0  5041.6      .1       0  5285.4     .05       0
  5456.3      .1       0  5872.6     .16       0  6000.3      .1       0
Bank Sta=4222.05,5538.6
XS Rating Curve= 0 ,0
Exp/Cntr=0.3,0.1

Type RM Length L Ch R = 1 ,42277   ,327,327,327
BEGIN DESCRIPTION:
Mapping XS b12b7929
END DESCRIPTION:
XS GIS Cut Line= 3
       2008188.5     13602813.69       2007433.3     13602935.21
       2005768.3     13603854.43
#Sta/Elev= 30
  4083.7  666.08  4320.2  655.19  4370.5  655.38  4375.6  653.26    4381  652.96
  4421.5  653.71  4442.5  651.85  4566.2  648.53 4612.84645.4114  4705.1  642.87
  4714.5  643.55  4735.5  644.01  4751.8  642.24    4776  641.77  4964.3  641.33
  4972.3  640.42  4980.3  633.53  4980.6   630.1  4985.9   629.2  5009.8   630.1
    5018  642.16    5070  642.39    5268   640.5  5414.6   643.5  5610.8  643.42
  5957.7  643.16 6139.45645.4117  6260.5  648.22  6466.7  654.56  6750.5   657.8
#Mann= 8 ,-1 , 0
  4083.7      .1       0  4714.5     .12       0  4980.6     .07       0
  5009.8     .12       0    5070      .1       0  5610.8     .05       0
  6260.5      .1       0  6466.7     .05       0
Bank Sta=4612.84,6139.45
XS Rating Curve= 0 ,0
Exp/Cntr=0.3,0.1

Type RM Length L Ch R = 1 ,41950   ,193,193,193
BEGIN DESCRIPTION:
CHACON CREEK 48.0
END DESCRIPTION:
XS GIS Cut Line= 3
      2008214.57      13602674.8       2005870.8      13602718.2
      2005429.03     13602891.44
#Sta/Elev= 30
  4032.5  671.49  4083.6  670.29  4280.5  662.21  4310.3  661.05  4315.3  659.44
  4396.4  657.33  4458.7  654.81  4557.3  650.41  4612.2  648.35  4642.2  645.19
  4674.3  648.87  4682.2  649.26 4702.04644.6201  4742.2  647.95  4772.8  648.31
  4792.2  647.91  4850.4  643.24  4855.4  645.23  5102.3  642.91  5217.7  640.44
    5223  639.54  5246.9  640.44    5462  643.48  5622.3  644.29  5812.4   641.6
    5956  641.15  6262.5  641.01 6409.99644.6207    6686  654.25  6851.2  655.14
#Mann= 12 ,-1 , 0
  4032.5     .08       0  4083.6      .1       0  4280.5     .08       0
  4396.4     .05       0  4458.7     .08       0  4557.3     .15       0
  4674.3      .1       0  4772.8     .08       0  5217.7     .07       0
  5246.9     .08       0    5462     .05       0    5956      .1       0
Bank Sta=4702.04,6409.99
XS Rating Curve= 0 ,0
Exp/Cntr=0.3,0.1

Type RM Length L Ch R = 1 ,41757   ,649,649,649
BEGIN DESCRIPTION:
CHACON CREEK 47.0
END DESCRIPTION:
XS GIS Cut Line= 3
      2008119.04     13602587.99      2005957.61     13602492.51
      2005429.07     13602795.77
#Sta/Elev= 30
  4011.6  670.55  4196.7  664.92  4327.1  659.01  4486.1  652.33  4526.1  654.32
  4576.2  647.16  4636.2  648.52  4652.8  644.94 4662.92 642.908  4756.4  640.24
    4818  640.95  4966.6  640.92    4972  629.61  4977.3  628.71  5001.2  629.61
  5016.6  638.66  5026.6  640.21  5242.9  640.24    5427   646.6  5487.1  646.99
  5767.3  641.49    6018   640.6  6145.7  640.14    6236  639.86  6326.8642.9081
  6336.7  645.11  6385.5   646.6  6434.4  644.99  6524.5  648.92  6784.5  654.02
#Mann= 11 ,-1 , 0
  4011.6      .1       0  4327.1     .08       0  4652.8      .1       0
    4818     .12       0    4972    .035       0  5001.2     .12       0
  5242.9      .1       0    6018     .05       0  6145.7      .1       0
  6336.7     .05       0  6524.5      .1       0
Bank Sta=4662.92,6326.8
XS Rating Curve= 0 ,0
Exp/Cntr=0.3,0.1

Type RM Length L Ch R = 1 ,41108   ,534,534,534
BEGIN DESCRIPTION:
Mapping XS d4e872ba
END DESCRIPTION:
XS GIS Cut Line= 4
      2007844.65       13602353.      2006603.29     13601797.43
      2005240.44     13601823.47      2003609.28     13602378.76
#Sta/Elev= 30
  3980.9  667.48  4062.2  668.83    4101  664.14  4131.8   655.6  4176.9  653.06
  4245.9  654.01  4393.6  648.25 4562.61642.0238  4622.8  639.85  4969.7  639.13
  4972.8  630.31  4978.1  629.41    5002  630.31  5016.1  636.92  5021.6  634.22
    5052  639.48  5479.8  642.39  6155.8  640.43  6379.4   641.7  6719.6  650.61
    7021  640.76  7126.1  642.32  7336.2  641.85    7382  641.86  7441.2  641.88
  7546.3  642.89  7676.8  642.04 7750.67642.0237  8283.7  669.85  8427.1  670.48
#Mann= 16 ,-1 , 0
  3980.9     .08       0  4176.9      .1       0  4245.9     .08       0
  4393.6      .1       0  4622.8     .12       0  4972.8     .07       0
    5002     .12       0    5052     .05       0  6155.8      .1       0
    7021     .12       0  7126.1     .16       0  7336.2      .1       0
    7382     .05       0  7441.2      .1       0  7546.3     .16       0
  7676.8      .1       0
Bank Sta=4562.61,7750.67
XS Rating Curve= 0 ,0
Exp/Cntr=0.3,0.1

Type RM Length L Ch R = 1 ,40574   ,136,136,136
BEGIN DESCRIPTION:
Mapping XS dd135c82
END DESCRIPTION:
XS GIS Cut Line= 4
      2007757.79     13602248.81      2006959.19     13601528.33
      2004797.73     13600807.85      2003358.34     13601093.99
#Sta/Elev= 30
  3699.9  661.75  3725.9   656.5  3771.4  654.88  3950.9  654.23  4171.2  647.02
  4181.9  646.72 4344.89641.8656  4695.3  639.67  4948.5  639.21  4962.1  638.65
  4986.6  630.89  4991.9  629.99  5015.8  630.89  5020.1  637.74  5064.5  637.99
  5215.1  636.34  5526.1  640.52  6589.9  637.97  6754.9  637.83    7075  637.57
  7393.1  635.38  7413.5  638.65  7528.6   637.9 7622.81641.8655  7892.7  657.61
    8117  666.27  8331.1   665.6    8433  667.94  8494.2  676.03  8521.4  672.59
#Mann= 12 ,-1 , 0
  3699.9     .08       0  3771.4      .1       0  3950.9     .08       0
  4171.2     .05       0  4181.9      .1       0  4695.3     .12       0
  4986.6     .07       0  5015.8     .12       0  5064.5     .05       0
  6589.9      .1       0  6754.9     .05       0    7075      .1       0
Bank Sta=4344.89,7622.81
XS Rating Curve= 0 ,0
Exp/Cntr=0.3,0.1

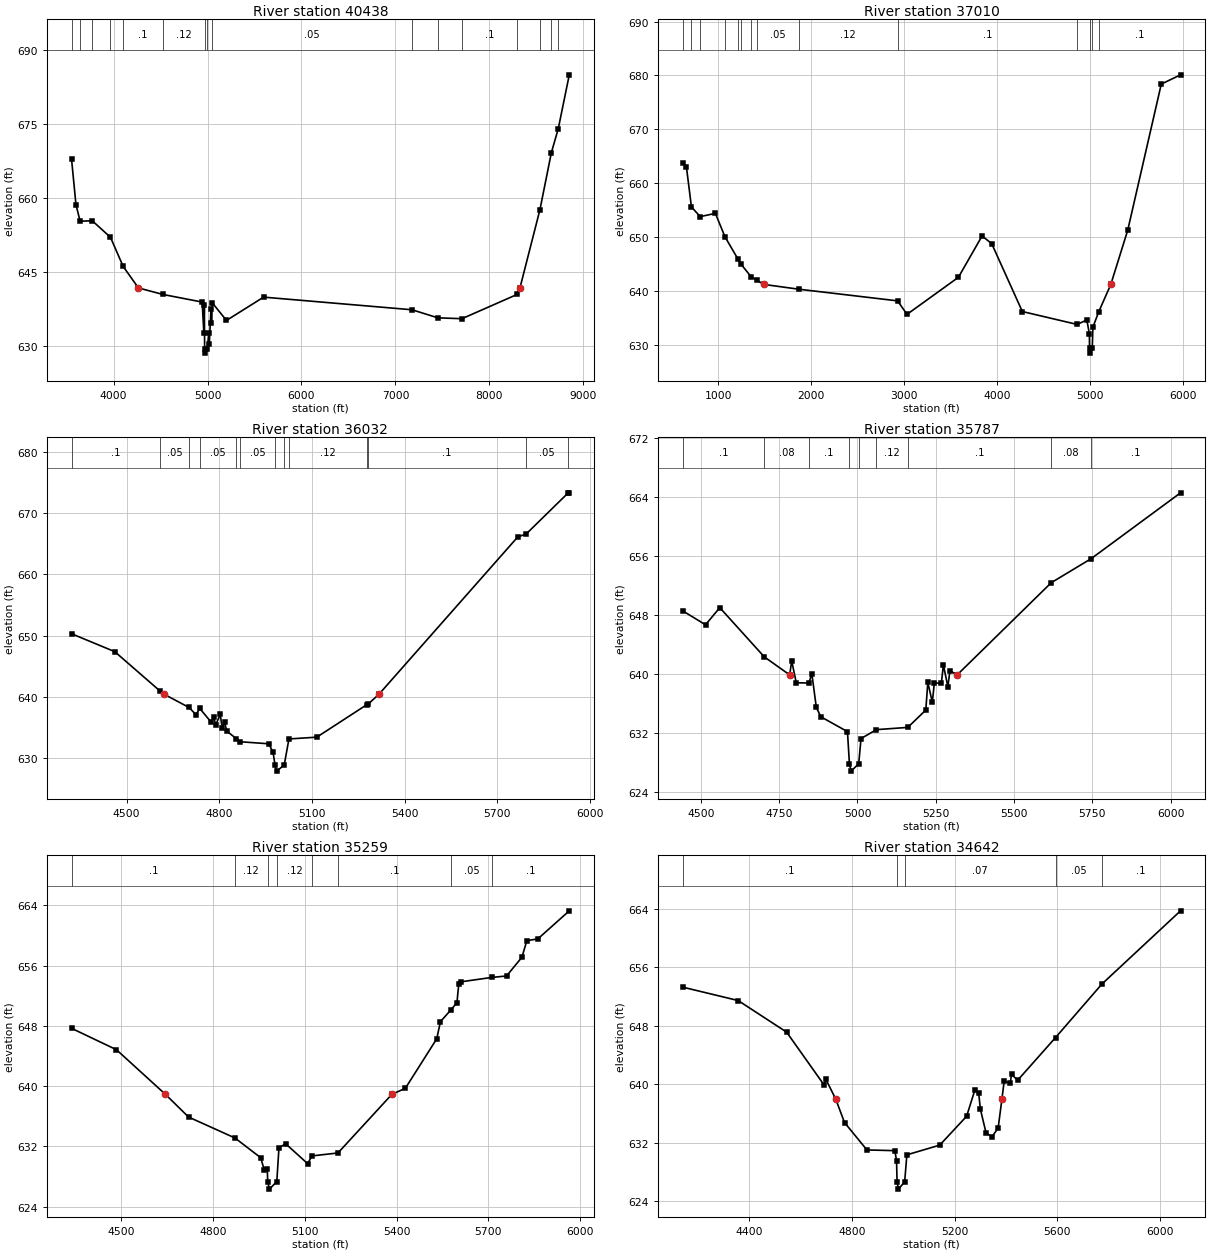
Type RM Length L Ch R = 1 ,40438   ,3428,3428,3428
BEGIN DESCRIPTION:
Mapping XS f517f074
END DESCRIPTION:
XS GIS Cut Line= 5
      2007790.28     13602226.41      2007098.63     13601531.99
      2005572.04     13600870.35      2004728.29     13600571.74
      2003028.44     13600120.76
#Sta/Elev= 30
  3552.9  667.92    3600  658.69  3644.1  655.37  3773.7  655.45    3967  652.11
  4102.2  646.21 4264.49641.8527    4526  640.53    4943  638.99    4961  632.77
  4966.5  638.43  4969.2  629.55  4974.5  628.65  4998.4  629.55  5013.4   632.8
  5018.9  630.51  5036.9  637.58  5042.3  634.84    5052  638.81  5201.8  635.27
  5596.9  639.99  7176.9  637.43    7451   635.8  7707.9  635.62  8294.7  640.53
 8325.37641.8527  8537.9  657.68    8660  669.27    8733  674.08  8850.5  685.01
#Mann= 16 ,-1 , 0
  3552.9     .08       0  3644.1      .1       0  3773.7     .08       0
    3967     .05       0  4102.2      .1       0    4526     .12       0
  4969.2     .07       0  4998.4     .12       0    5052     .05       0
  7176.9      .1       0    7451     .12       0  7707.9      .1       0
  8294.7     .16       0  8537.9      .1       0    8660     .16       0
    8733      .1       0
Bank Sta=4264.49,8325.37
XS Rating Curve= 0 ,0
Exp/Cntr=0.3,0.1

Type RM Length L Ch R = 1 ,37010   ,978,978,978
BEGIN DESCRIPTION:
Mapping XS 9066d730
END DESCRIPTION:
XS GIS Cut Line= 4
      2007804.18     13602200.96      2005591.31     13599760.36
      2004818.08     13599575.97      2003713.87     13598964.84
#Sta/Elev= 30
   617.3   663.8   656.2  663.04   710.1  655.61   804.2   653.8   967.7  654.41
  1069.9  650.09  1211.5  645.89    1246  644.92  1353.1  642.62  1410.9  642.02
 1487.08641.2245  1865.9  640.33  2926.3  638.17  3028.1  635.67  3580.5  642.54
  3835.2  650.22  3938.8  648.78  4267.8  636.19  4856.1   633.8  4961.3  634.62
  4988.8  632.04    4990  629.47  4995.5  628.47  5019.7  629.47  5026.6  633.28
  5087.7  636.08 5219.08641.2242  5401.1  651.29  5761.7   678.4  5968.7  680.12
#Mann= 14 ,-1 , 0
   617.3     .08       0   710.1      .1       0   804.2     .08       0
  1069.9     .05       0  1211.5      .1       0    1246     .05       0
  1353.1      .1       0  1410.9     .05       0  1865.9     .12       0
  2926.3      .1       0  4856.1     .12       0    4990     .07       0
  5019.7     .12       0  5087.7      .1       0
Bank Sta=1487.08,5219.08
XS Rating Curve= 0 ,0
Exp/Cntr=0.3,0.1

Type RM Length L Ch R = 1 ,36032   ,245,245,245
BEGIN DESCRIPTION:
CHACON CREEK 46.0
END DESCRIPTION:
XS GIS Cut Line= 3
      2005749.27      13599636.6       2005289.2     13599055.01
      2004665.53     13598448.66
#Sta/Elev= 30
  4321.6   650.3  4461.5  647.38    4608  640.96 4622.46640.4047  4702.1  638.27
  4724.3   637.1  4736.8  638.11    4774  635.85  4782.1  636.64  4788.4  635.45
  4802.9  637.13  4809.3  634.99  4817.3  635.88  4823.7  634.43  4854.6  633.21
  4865.7  632.69    4960  632.35  4973.9  630.98  4980.4  628.89  4985.8  627.89
  5010.1  628.89  5025.4  633.14  5115.6  633.43  5277.5  638.73  5280.6  638.77
 5316.36 640.405  5766.3   666.1  5793.6  666.58  5927.6  673.19    5933  673.29
#Mann= 13 ,-1 , 0
  4321.6      .1       0    4608     .05       0  4702.1      .1       0
  4736.8     .05       0  4854.6      .1       0  4865.7     .05       0
  4980.4     .07       0  5010.1     .05       0  5025.4     .12       0
  5277.5     .05       0  5280.6      .1       0  5793.6     .05       0
  5927.6      .1       0
Bank Sta=4622.46,5316.36
XS Rating Curve= 0 ,0
Exp/Cntr=0.3,0.1

Type RM Length L Ch R = 1 ,35787   ,528,528,528
BEGIN DESCRIPTION:
CHACON CREEK 45.0
END DESCRIPTION:
XS GIS Cut Line= 3
      2005836.08      13599454.3      2005801.36     13599341.46
       2004889.9     13598186.95
#Sta/Elev= 30
  4442.3  648.56  4514.8  646.68  4560.4     649  4702.3  642.34 4783.43 639.892
    4790  641.78  4804.5  638.83    4845  638.79  4854.2  640.08  4868.6  635.48
    4883  634.22    4968  632.21  4974.2  627.86  4979.6  626.86  5003.9  627.86
  5011.3  631.27  5060.3  632.48  5160.5  632.78  5218.1  635.13  5224.5  638.88
  5238.9  636.19  5245.3  638.79  5267.8  638.77  5274.2  641.24  5288.6  638.29
    5295  640.46  5318.1639.8904  5618.6  652.38  5746.2  655.64  6031.3  664.55
#Mann= 9 ,-1 , 0
  4442.3      .1       0  4702.3     .08       0    4845      .1       0
  4974.2     .07       0  5003.9      .1       0  5060.3     .12       0
  5160.5      .1       0  5618.6     .08       0  5746.2      .1       0
Bank Sta=4783.43,5318.1
XS Rating Curve= 0 ,0
Exp/Cntr=0.3,0.1

Type RM Length L Ch R = 1 ,35259   ,617,617,617
BEGIN DESCRIPTION:
CHACON CREEK 44.0
END DESCRIPTION:
XS GIS Cut Line= 3
       2006065.1     13599201.96      2005830.72     13598594.31
      2004975.04     13598125.02
#Sta/Elev= 30
  4337.4  647.69  4484.2  644.85 4643.78638.9426    4720  635.91  4871.7  633.13
  4955.8  630.51  4967.4  628.88  4977.2  629.02  4978.7  627.34  4984.2  626.34
  5008.4  627.34  5015.4  631.81  5037.2  632.37  5109.3  629.72  5123.4  630.75
  5208.3  631.14 5385.03638.9429  5428.6  639.72  5531.3   646.3  5543.3  648.57
  5577.6  650.14  5597.4   651.1  5603.1  653.52  5611.1  653.87  5711.9  654.45
  5759.4  654.64  5809.7  657.12  5825.8  659.32    5862  659.57  5964.6  663.29
#Mann= 8 ,-1 , 0
  4337.4      .1       0  4871.7     .12       0  4978.7     .07       0
  5008.4     .12       0  5123.4     .07       0  5208.3      .1       0
  5577.6     .05       0  5711.9      .1       0
Bank Sta=4643.78,5385.03
XS Rating Curve= 0 ,0
Exp/Cntr=0.3,0.1

Type RM Length L Ch R = 1 ,34642   ,396,396,396
BEGIN DESCRIPTION:
CHACON CREEK 43.0
END DESCRIPTION:
XS GIS Cut Line= 3
      2006525.17     13598472.78       2005839.4     13598047.43
      2004798.87     13597596.54
#Sta/Elev= 30
  4140.2  653.27  4356.1  651.44  4545.1  647.12  4691.6  639.87  4697.5  640.71
 4736.49637.9724  4770.8  634.76  4858.2  631.01  4967.1  630.91  4973.8  629.51
  4975.7  626.65  4981.2  625.65  5005.4  626.65    5014  630.34  5142.3  631.67
  5247.1  635.62  5278.9  639.18    5294  638.81  5300.7  636.59    5323   633.3
  5346.4  632.84  5369.9  633.99 5384.69 637.972  5393.4   640.4  5416.9  640.14
  5422.3  641.36  5445.8  640.53  5593.8  646.38  5774.7   653.7  6081.2  663.71
#Mann= 5 ,-1 , 0
  4140.2      .1       0  4975.7     .07       0  5005.4     .07       0
  5593.8     .05       0  5774.7      .1       0
Bank Sta=4736.49,5384.69
XS Rating Curve= 0 ,0
Exp/Cntr=0.3,0.1

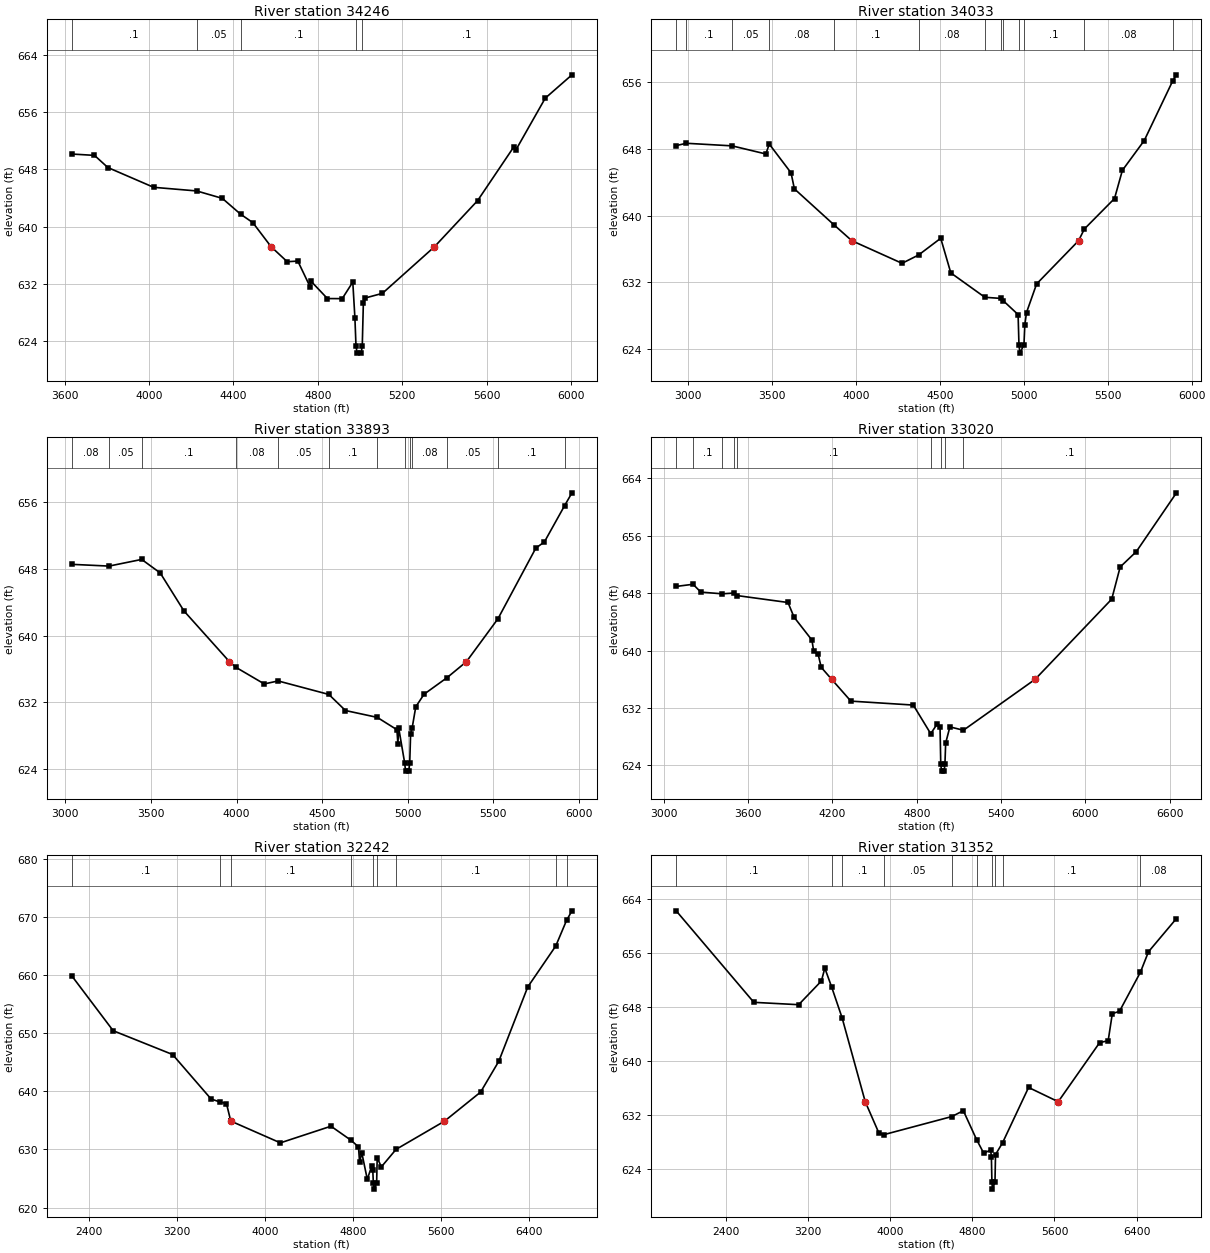
Type RM Length L Ch R = 1 ,34246   ,213,213,213
BEGIN DESCRIPTION:
CHACON CREEK 42.0
END DESCRIPTION:
XS GIS Cut Line= 3
      2007075.61      13598222.5      2006247.46     13597680.82
      2004868.65     13597576.76
#Sta/Elev= 30
  3632.7  650.16  3740.9  649.97  3804.2  648.27  4021.3   645.5  4225.6  644.99
  4347.1  643.95  4433.5  641.74  4491.8  640.55 4578.47637.1761  4654.8  635.08
    4705  635.17  4763.1  631.58  4768.1  632.33  4845.4  629.92  4915.6  629.91
  4965.7  632.23  4975.7  627.24  4980.9  623.28  4986.4  622.28  5005.2  622.28
  5010.6  623.28  5015.8  629.27  5025.9  630.01  5106.1  630.65 5353.02637.1761
  5557.4  643.63  5727.9   651.1  5737.9  650.67  5878.3  657.98    6005  661.25
#Mann= 5 ,-1 , 0
  3632.7      .1       0  4225.6     .05       0  4433.5      .1       0
  4980.9     .07       0  5010.6      .1       0
Bank Sta=4578.47,5353.02
XS Rating Curve= 0 ,0
Exp/Cntr=0.3,0.1

Type RM Length L Ch R = 1 ,34033   ,140,140,140
BEGIN DESCRIPTION:
CHACON CREEK 41.0
END DESCRIPTION:
XS GIS Cut Line= 3
      2007997.45     13597321.45      2007455.79     13597363.11
       2005023.5     13597524.57
#Sta/Elev= 30
  2928.6  648.38  2988.9  648.66  3261.8  648.35  3462.6  647.38  3483.4  648.56
    3613  645.12    3633   643.2  3868.3   638.9 3975.12636.9893  4274.4  634.28
  4372.6  635.27  4504.9  637.28    4565  633.13  4767.8  630.21  4866.6  630.07
  4878.3  629.78  4965.9  628.14  4971.1  624.52  4976.6  623.52  5000.8  624.52
    5006  626.92    5016  628.38  5076.2  631.81 5326.41636.9896  5360.7  638.39
  5540.4  642.04  5587.3  645.42  5717.6  648.99  5888.3  656.18  5909.5  656.86
#Mann= 13 ,-1 , 0
  2928.6     .05       0  2988.9      .1       0  3261.8     .05       0
  3483.4     .08       0  3868.3      .1       0  4372.6     .08       0
  4767.8     .05       0  4866.6     .08       0  4878.3      .1       0
  4971.1     .07       0  5000.8      .1       0  5360.7     .08       0
  5888.3      .1       0
Bank Sta=3975.12,5326.41
XS Rating Curve= 0 ,0
Exp/Cntr=0.3,0.1

Type RM Length L Ch R = 1 ,33893   ,873,873,873
BEGIN DESCRIPTION:
Mapping XS 66bb1174
END DESCRIPTION:
XS GIS Cut Line= 2
      2007961.04      13597227.7      2005044.36      13597415.2
#Sta/Elev= 30
  3036.6  648.56  3254.9  648.35  3445.6  649.15  3553.7  647.53  3692.5  642.97
 3958.47636.8767    3994  636.23  4161.8  634.21  4242.7  634.57    4539  632.95
  4636.1  631.02  4821.7   630.2  4936.6  628.72  4942.3  627.04  4947.3  628.91
  4981.8  624.75  4987.3  623.75  5006.1  623.75  5011.5  624.75  5016.7  628.24
    5026  628.97  5046.8  631.47  5095.4  632.98  5230.5  634.98 5342.49636.8767
  5526.9  642.03  5748.2  650.51  5798.3  651.25  5916.5  655.61  5959.3  657.14
#Mann= 13 ,-1 , 0
  3036.6     .08       0  3254.9     .05       0  3445.6      .1       0
    3994     .08       0  4242.7     .05       0    4539      .1       0
  4821.7     .12       0  4981.8     .07       0  5011.5     .12       0
    5026     .08       0  5230.5     .05       0  5526.9      .1       0
  5916.5     .08       0
Bank Sta=3958.47,5342.49
XS Rating Curve= 0 ,0
Exp/Cntr=0.3,0.1

Type RM Length L Ch R = 1 ,33020   ,778,778,778
BEGIN DESCRIPTION:
CHACON CREEK 40.0
END DESCRIPTION:
XS GIS Cut Line= 3
      2008345.57     13597272.85      2006913.26     13596712.94
      2004895.03     13596791.07
#Sta/Elev= 30
  3089.4  648.94  3209.5  649.24  3264.6  648.15  3416.3  647.91  3503.8  648.02
  3520.7  647.67  3884.5   646.7  3927.5  644.66  4054.8  641.46  4067.1  639.92
  4099.3  639.46  4120.8  637.66 4195.45635.9833  4331.7  632.95  4775.6   632.4
  4899.4  628.41  4945.8  629.77  4965.8  629.31  4970.9  624.19  4976.4  623.19
  4995.2  623.19  5000.6  624.19  5005.8   627.1  5035.8  629.36    5132  628.89
  5641.6635.9837  6186.7  647.17  6246.7  651.65  6361.4  653.79    6647  661.99
#Mann= 9 ,-1 , 0
  3089.4     .08       0  3209.5      .1       0  3416.3     .08       0
  3503.8     .05       0  3520.7      .1       0  4899.4     .12       0
  4970.9     .07       0  5000.6     .12       0    5132      .1       0
Bank Sta=4195.45,5641.6
XS Rating Curve= 0 ,0
Exp/Cntr=0.3,0.1

Type RM Length L Ch R = 1 ,32242   ,890,890,890
BEGIN DESCRIPTION:
CHACON CREEK 39.0
END DESCRIPTION:
XS GIS Cut Line= 3
      2009322.14     13596074.92      2007382.01       13596127.
      2004774.98       13596225.
#Sta/Elev= 30
  2244.1  659.86  2621.4  650.41  3161.6  646.32  3511.7  638.68  3591.4  638.17
  3651.8  637.89  3689.9  634.96 3694.32634.8572  4141.9  631.14  4602.2     634
  4786.4  631.56  4852.4  630.45  4862.4   627.8  4882.4  629.45  4932.5  624.87
  4972.5  627.15  4982.5   626.4  4987.7  624.19  4993.1  623.19  5017.4  624.19
  5022.5  628.58  5060.5  627.02  5194.1  630.02 5633.82634.8572  5963.2  639.87
  6128.3  645.16  6391.5  657.92  6646.5  664.97  6745.1  669.39  6793.8  671.01
#Mann= 9 ,-1 , 0
  2244.1      .1       0  3591.4     .08       0  3689.9      .1       0
  4786.4     .12       0  4987.7     .07       0  5017.4     .12       0
  5194.1      .1       0  6646.5     .08       0  6745.1      .1       0
Bank Sta=3694.32,5633.82
XS Rating Curve= 0 ,0
Exp/Cntr=0.3,0.1

Type RM Length L Ch R = 1 ,31352   ,1044,1044,1044
BEGIN DESCRIPTION:
CHACON CREEK 38.0
END DESCRIPTION:
XS GIS Cut Line= 3
      2009394.24      13594782.3      2006394.27     13595382.29
      2004594.23      13595582.3
#Sta/Elev= 30
    1917  662.31  2673.1  648.72  3109.4  648.37  3330.8  651.89  3364.3   653.8
  3431.4  650.96  3532.4  646.42 3757.59633.9613  3891.7  629.27  3941.8  629.08
  4600.9  631.76  4712.7  632.63  4842.4  628.31  4911.5  626.31  4978.5  626.79
  4985.7   625.8    4991  621.98  4996.4  620.98  5020.7  621.98    5026  626.11
  5094.1  627.85  5347.9  636.08 5636.41633.9614  6039.7  642.74  6122.7  643.02
  6162.9  647.03  6233.3   647.4  6436.2  653.18  6515.1  656.23  6787.5  661.17
#Mann= 10 ,-1 , 0
    1917      .1       0  3431.4     .08       0  3532.4      .1       0
  3941.8     .05       0  4600.9      .1       0  4842.4     .12       0
    4991     .07       0  5020.7     .12       0  5094.1      .1       0
  6436.2     .08       0
Bank Sta=3757.59,5636.41
XS Rating Curve= 0 ,0
Exp/Cntr=0.3,0.1

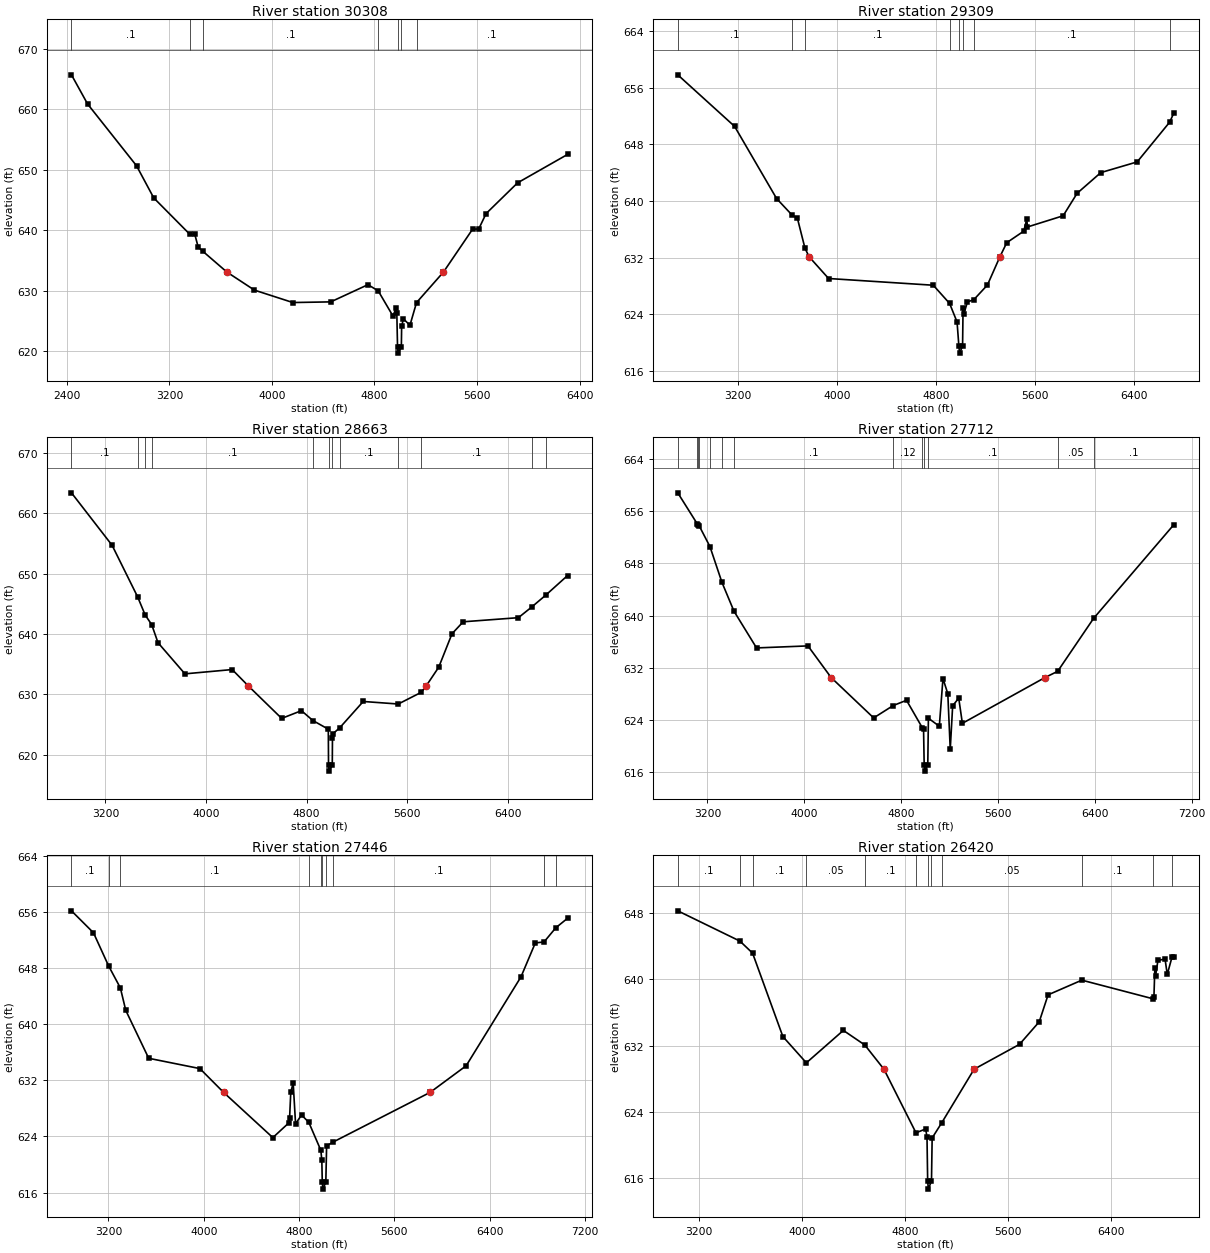
Type RM Length L Ch R = 1 ,30308   ,999,999,999
BEGIN DESCRIPTION:
CHACON CREEK 37.0
END DESCRIPTION:
XS GIS Cut Line= 3
      2008736.15      13593809.3      2006848.15     13594304.09
       2004974.8     13594720.39
#Sta/Elev= 30
  2435.4   665.7  2561.2  660.88  2943.1  650.67  3077.5  645.36  3358.4  639.36
    3398  639.32  3424.1  637.25    3461  636.53    3648633.1116  3863.3  630.12
    4163  628.07  4458.7  628.18  4748.9  631.02  4828.7  630.01  4943.6  625.86
  4968.4  627.12  4974.3  626.28  4979.9  620.71  4985.3  619.71  5009.6  620.71
  5011.9  624.12  5025.5  625.38  5076.7  624.31    5128  628.06 5338.45633.1115
  5565.1  640.18  5613.7  640.24  5670.9  642.77  5916.7  647.85  6306.2  652.54
#Mann= 7 ,-1 , 0
  2435.4      .1       0  3358.4     .08       0    3461      .1       0
  4828.7     .12       0  4979.9     .07       0  5009.6     .12       0
    5128      .1       0
Bank Sta=3648,5338.45
XS Rating Curve= 0 ,0
Exp/Cntr=0.3,0.1

Type RM Length L Ch R = 1 ,29309   ,646,646,646
BEGIN DESCRIPTION:
CHACON CREEK 36.0
END DESCRIPTION:
XS GIS Cut Line= 3
       2008671.1     13592975.95      2006548.67     13593483.77
      2004857.02     13594160.43
#Sta/Elev= 30
  2716.1  657.83  3174.8  650.55  3514.1  640.35    3641  637.98  3681.3  637.61
  3742.9  633.34    3777632.1168  3933.7  629.06  4778.8  628.11  4910.5  625.54
  4970.7  622.92  4985.4  619.52  4990.9  618.52  5015.2  619.52  5019.2  624.84
  5024.6  623.98  5054.2  625.75    5106  626.07  5215.8  628.14 5316.21632.1168
  5371.9  634.12  5509.2  635.75  5533.5  637.44  5538.9  636.34    5827  637.92
  5940.1   641.1  6131.2  644.02  6424.7  645.53  6686.3  651.13  6720.4  652.42
#Mann= 8 ,-1 , 0
  2716.1      .1       0    3641     .08       0  3742.9      .1       0
  4910.5     .12       0  4985.4     .07       0  5015.2     .12       0
    5106      .1       0  6686.3     .05       0
Bank Sta=3777,5316.21
XS Rating Curve= 0 ,0
Exp/Cntr=0.3,0.1

Type RM Length L Ch R = 1 ,28663   ,951,951,951
BEGIN DESCRIPTION:
CHACON CREEK 35.0
END DESCRIPTION:
XS GIS Cut Line= 3
      2008175.04     13592024.98      2006770.03     13592715.55
      2004648.84     13593795.66
#Sta/Elev= 30
    2930  663.35  3253.2  654.67  3456.6  646.13  3516.4  643.14    3568  641.56
  3618.4  638.56  3832.6  633.41  4208.4  634.12 4337.59631.3981  4602.2  626.04
  4759.3  627.32    4851  625.68  4973.1  624.26  4974.9  618.32  4980.3  617.32
  5004.7  618.32  5006.2  622.75    5012  623.54  5064.1  624.49    5251  628.84
  5529.6  628.42  5713.1  630.36  5751.3631.3983  5851.6  634.51  5957.1  640.04
  6046.1  642.02  6485.3   642.7  6589.8  644.44    6702  646.41  6875.9  649.66
#Mann= 12 ,-1 , 0
    2930      .1       0  3456.6     .08       0  3516.4     .05       0
    3568      .1       0    4851     .12       0  4974.9     .07       0
  5004.7     .12       0  5064.1      .1       0  5529.6     .05       0
  5713.1      .1       0  6589.8     .05       0    6702      .1       0
Bank Sta=4337.59,5751.3
XS Rating Curve= 0 ,0
Exp/Cntr=0.3,0.1

Type RM Length L Ch R = 1 ,27712   ,266,266,266
BEGIN DESCRIPTION:
CHACON CREEK 34.0
END DESCRIPTION:
XS GIS Cut Line= 3
      2007974.99       13591975.        2005975.       13592175.
      2003892.46      13592311.9
#Sta/Elev= 30
  2955.1  658.81  3117.8     654  3121.8  653.86  3132.9  653.72    3221  650.56
  3320.2  645.07  3419.4  640.66  3605.8  635.03  4030.4  635.34 4222.05 630.484
  4573.1   624.3    4734  626.19  4844.5     627  4975.9  622.76  4985.1  622.65
  4990.3  617.14  4995.7  616.14  5020.1  617.14  5025.2  624.25  5115.4  623.02
  5145.5  630.34  5185.5  628.01  5205.6  619.49  5225.6  626.16  5275.7  627.33
  5305.8  623.47 5987.48630.4838  6092.8  631.44  6389.2  639.55  7052.1  653.92
#Mann= 13 ,-1 , 0
  2955.1      .1       0  3117.8     .05       0  3121.8     .08       0
  3132.9      .1       0    3221     .08       0  3320.2     .05       0
  3419.4      .1       0    4734     .12       0  4975.9      .1       0
  4990.3     .07       0  5020.1      .1       0  6092.8     .05       0
  6389.2      .1       0
Bank Sta=4222.05,5987.48
XS Rating Curve= 0 ,0
Exp/Cntr=0.3,0.1

Type RM Length L Ch R = 1 ,27446   ,1026,1026,1026
BEGIN DESCRIPTION:
CHACON CREEK 33.0
END DESCRIPTION:
XS GIS Cut Line= 3
      2007928.89     13591765.02      2005949.72      13591934.3
      2003775.01       13592025.
#Sta/Elev= 30
  2889.5   656.2  3074.1  653.07  3200.9  648.35  3299.9   645.2  3345.1     642
  3537.7  635.16  3967.3  633.69 4165.73630.3027  4579.5  623.84  4711.6  625.91
  4720.1  626.65  4730.1  630.31  4750.2  631.65  4770.2  625.81  4820.4  627.07
  4881.1  626.03  4982.5  622.02  4990.7  620.58  4994.4  617.49  4999.8  616.49
  5024.2  617.49  5030.8  622.66  5081.1  623.17 5900.35630.3025  6201.8  634.09
  6662.2  646.78  6782.3  651.62  6855.7  651.76  6954.3  653.78  7052.5  655.13
#Mann= 10 ,-1 , 0
  2889.5      .1       0  3200.9     .08       0  3299.9      .1       0
  4881.1     .05       0  4982.5     .07       0  4994.4     .07       0
  5024.2     .07       0  5081.1      .1       0  6855.7     .08       0
  6954.3      .1       0
Bank Sta=4165.73,5900.35
XS Rating Curve= 0 ,0
Exp/Cntr=0.3,0.1

Type RM Length L Ch R = 1 ,26420   ,648,648,648
BEGIN DESCRIPTION:
CHACON CREEK 32.0
END DESCRIPTION:
XS GIS Cut Line= 3
      2008121.55     13591151.31      2005628.53     13591137.42
      2004316.06     13591498.52
#Sta/Elev= 30
  3033.4  648.27  3516.3  644.62  3614.6  643.17    3850  633.11  4032.6  629.94
    4320  633.85  4486.9  632.09 4635.35629.1711  4884.4   621.5    4960  621.97
    4970  620.95  4975.1  615.71  4980.5  614.71  5004.9  615.71    5010  620.88
  5084.9  622.72 5336.03629.1715  5688.9  632.17  5842.1  634.89  5910.9  638.14
  6173.1  639.91  6729.4  637.65  6733.2  637.83  6740.4  641.41  6745.6  640.37
  6764.3  642.29  6819.6  642.46  6836.9   640.6  6873.6  642.69  6887.7  642.73
#Mann= 12 ,-1 , 0
  3033.4      .1       0  3516.3     .08       0  3614.6      .1       0
  4032.6     .05       0  4486.9      .1       0  4884.4     .12       0
  4975.1     .07       0  5004.9     .12       0  5084.9     .05       0
  6173.1      .1       0  6729.4     .08       0  6873.6      .1       0
Bank Sta=4635.35,5336.03
XS Rating Curve= 0 ,0
Exp/Cntr=0.3,0.1

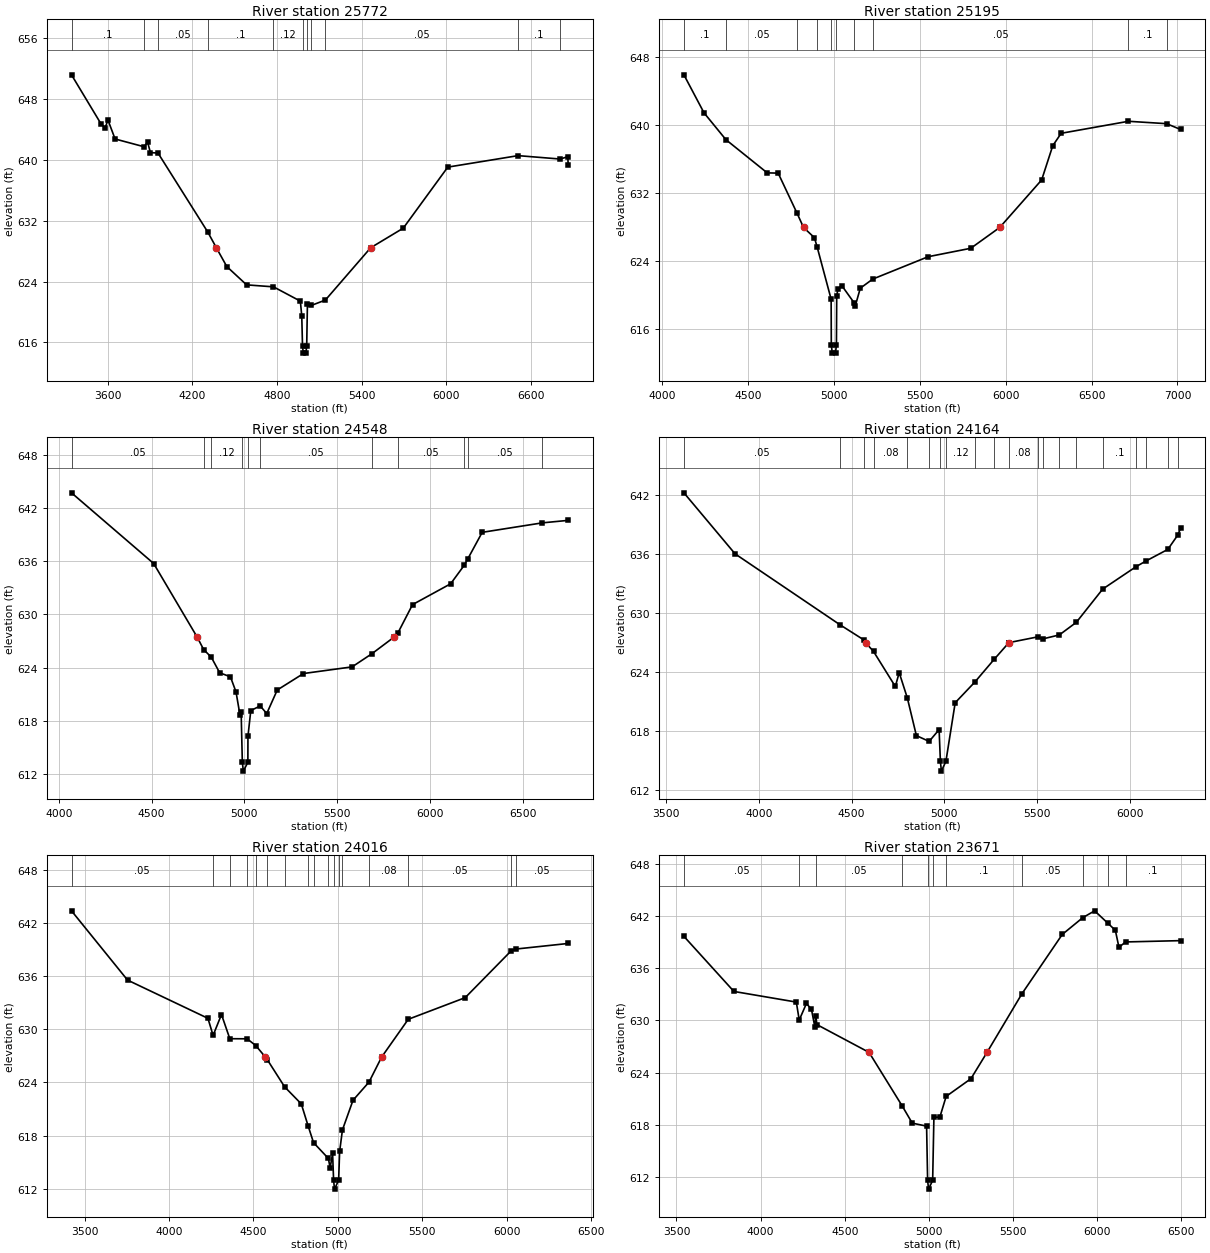
Type RM Length L Ch R = 1 ,25772   ,577,577,577
BEGIN DESCRIPTION:
CHACON CREEK 31.0
END DESCRIPTION:
XS GIS Cut Line= 3
      2008072.96     13590484.64      2005746.59     13590651.31
      2004678.55     13591171.46
#Sta/Elev= 30
  3343.6  651.19  3552.1  644.76  3582.2  644.24  3602.2  645.24  3652.4  642.75
  3857.9  641.73  3882.9  642.34    3903  640.96  3956.8   640.9  4310.1  630.49
 4370.27628.4408  4444.4  625.97  4584.7  623.56  4775.2   623.3  4965.7  621.42
  4975.7  619.45  4980.9  615.58  4986.3  614.58  5005.2  614.58  5010.7  615.58
  5015.8  620.99  5044.1  620.86    5143  621.56  5464.1 628.441  5695.1  631.02
  6010.7  639.05  6508.9  640.56  6808.6  640.11  6861.4  640.43  6863.9  639.34
#Mann= 11 ,-1 , 0
  3343.6      .1       0  3857.9     .08       0  3956.8     .05       0
  4310.1      .1       0  4775.2     .12       0  4980.9     .07       0
  5010.7     .12       0  5044.1      .1       0    5143     .05       0
  6508.9      .1       0  6808.6     .08       0
Bank Sta=4370.27,5464.1
XS Rating Curve= 0 ,0
Exp/Cntr=0.3,0.1

Type RM Length L Ch R = 1 ,25195   ,647,647,647
BEGIN DESCRIPTION:
Mapping XS 0b3e2ed7
END DESCRIPTION:
XS GIS Cut Line= 4
      2007163.26     13589547.72      2006663.26      13590032.1
      2005590.34     13590480.01      2004746.62     13591073.74
#Sta/Elev= 30
  4127.8   645.9  4244.9  641.43  4372.3  638.28  4612.7  634.38  4676.3  634.35
  4785.7  629.66 4824.13627.9621  4887.1  626.77  4902.7  625.71  4984.6  619.53
  4985.6   614.2  4991.1   613.2    5010   613.2  5015.4   614.2  5017.1  619.91
  5024.4  620.77  5048.2  621.09  5118.8   619.1    5125  618.74  5154.3  620.83
  5226.8   621.9  5549.4  624.53  5797.3  625.52 5965.62627.9619  6209.8  633.55
  6274.4  637.57  6323.3  639.03  6714.9  640.44  6936.9  640.16  7018.3  639.48
#Mann= 10 ,-1 , 0
  4127.8      .1       0  4372.3     .05       0  4785.7      .1       0
  4902.7     .12       0  4985.6     .07       0  5015.4     .12       0
  5118.8      .1       0  5226.8     .05       0  6714.9      .1       0
  6936.9     .08       0
Bank Sta=4824.13,5965.62
XS Rating Curve= 0 ,0
Exp/Cntr=0.3,0.1

Type RM Length L Ch R = 1 ,24548   ,384,384,384
BEGIN DESCRIPTION:
Mapping XS fe855d9a
END DESCRIPTION:
XS GIS Cut Line= 3
      2006954.91     13589224.81      2006085.13     13589771.68
      2004892.46     13590907.06
#Sta/Elev= 30
  4068.9  643.73  4511.3  635.75 4744.86627.4648  4780.6  626.03  4821.3  625.18
  4866.9  623.41  4924.6  622.96  4954.7  621.25  4976.4   618.6  4982.3  618.94
  4988.7  613.31  4994.1  612.31  5018.5  613.31  5018.9  616.23  5034.2  619.15
    5085  619.67  5120.1  618.81  5176.7  621.47  5317.9  623.33  5579.7  624.08
    5686  625.56 5807.13627.4649  5827.5  627.96  5905.1  631.11  6110.2  633.46
  6184.1  635.57  6202.2  636.26  6280.1  639.27    6604  640.34    6743  640.62
#Mann= 11 ,-1 , 0
  4068.9     .05       0  4780.6      .1       0  4821.3     .12       0
  4988.7     .07       0  5018.5     .12       0    5085     .05       0
    5686      .1       0  5827.5     .05       0  6184.1      .1       0
  6202.2     .05       0    6604      .1       0
Bank Sta=4744.86,5807.13
XS Rating Curve= 0 ,0
Exp/Cntr=0.3,0.1

Type RM Length L Ch R = 1 ,24164   ,148,148,148
BEGIN DESCRIPTION:
CHACON CREEK 30.0
END DESCRIPTION:
XS GIS Cut Line= 3
      2007059.05     13588866.59      2006239.65     13588962.65
      2005191.59     13590490.77
#Sta/Elev= 30
  3596.1  642.24    3872  636.04  4436.3  628.85  4567.5  627.28 4575.37627.0258
  4618.5  626.12    4736  622.56  4756.9  623.97  4800.8  621.39  4849.6  617.57
  4918.4  616.98  4972.1  618.18    4979  614.96  4984.4  613.96  5008.8  614.96
  5058.8  620.91  5165.2  623.02  5269.4  625.33  5347.5     627 5350.56627.0259
  5503.3   627.6  5529.7  627.39  5620.3   627.8    5712  629.08  5854.2  632.46
  6035.2  634.75  6088.2  635.32  6205.2  636.49  6258.7  637.94  6274.1  638.65
#Mann= 20 ,-1 , 0
  3596.1     .05       0  4436.3     .08       0  4567.5      .1       0
  4618.5     .08       0  4800.8      .1       0  4918.4     .12       0
    4979     .07       0  5008.8     .12       0  5165.2     .08       0
  5269.4      .1       0  5347.5     .08       0  5503.3      .1       0
  5529.7     .08       0  5620.3      .1       0    5712     .05       0
  5854.2      .1       0  6035.2     .08       0  6088.2     .05       0
  6205.2      .1       0  6258.7     .08       0
Bank Sta=4575.37,5350.56
XS Rating Curve= 0 ,0
Exp/Cntr=0.3,0.1

Type RM Length L Ch R = 1 ,24016   ,345,345,345
BEGIN DESCRIPTION:
CHACON CREEK 29.0
END DESCRIPTION:
XS GIS Cut Line= 3
      2007170.19     13588741.59      2006211.87     13588823.76
      2005024.39     13590408.23
#Sta/Elev= 30
    3422  643.35    3754  635.54  4230.1  631.23  4260.7   629.3  4310.4  631.66
  4359.7  628.93  4462.3  628.92  4513.4  628.16 4570.17626.8636  4582.6  626.54
  4684.5   623.5  4783.1  621.58  4823.2  619.12  4855.7  617.21  4943.6  615.43
  4953.9  614.35  4968.5     616  4974.5  612.97  4979.9  611.97  5004.3  612.97
  5010.2  616.22  5026.9  618.65  5089.4  621.99  5184.2  624.04  5259.1626.8638
  5416.7  631.12    5754  633.56  6026.4  638.84    6054  639.04  6363.9  639.67
#Mann= 17 ,-1 , 0
    3422     .05       0  4260.7     .08       0  4359.7     .05       0
  4462.3     .08       0  4513.4     .05       0  4582.6     .08       0
  4684.5     .05       0  4823.2      .1       0  4855.7     .12       0
  4943.6     .08       0  4974.5     .07       0  5004.3     .08       0
  5026.9      .1       0  5184.2     .08       0  5416.7     .05       0
  6026.4     .08       0    6054     .05       0
Bank Sta=4570.17,5259.1
XS Rating Curve= 0 ,0
Exp/Cntr=0.3,0.1

Type RM Length L Ch R = 1 ,23671   ,337,337,337
BEGIN DESCRIPTION:
Mapping XS 784b9d90
END DESCRIPTION:
XS GIS Cut Line= 4
      2007121.56     13588620.64      2006210.13     13588677.93
      2005522.63     13589209.18      2004434.08     13589636.27
#Sta/Elev= 30
  3544.2  639.65  3841.3  633.33  4212.1  632.11  4229.5  630.05  4272.2  631.95
  4302.2  631.28  4322.3  629.25  4328.3  630.52  4334.2  629.53 4644.47626.3387
  4841.7  620.18  4901.1  618.22  4986.3  617.88  4992.4  611.65  4997.9  610.65
  5022.3  611.65  5029.8  618.89  5065.1  618.91  5102.5  621.29  5249.8  623.32
 5345.37626.3389    5553  633.07  5792.5  639.87  5914.6   641.8    5985  642.58
  6061.6  641.19  6107.9  640.35  6129.4  638.39  6168.6  639.01  6495.6  639.16
#Mann= 11 ,-1 , 0
  3544.2     .05       0  4229.5     .08       0  4328.3     .05       0
  4841.7     .12       0  4992.4     .07       0  5022.3     .12       0
  5102.5      .1       0    5553     .05       0  5914.6      .1       0
  6061.6     .08       0  6168.6      .1       0
Bank Sta=4644.47,5345.37
XS Rating Curve= 0 ,0
Exp/Cntr=0.3,0.1