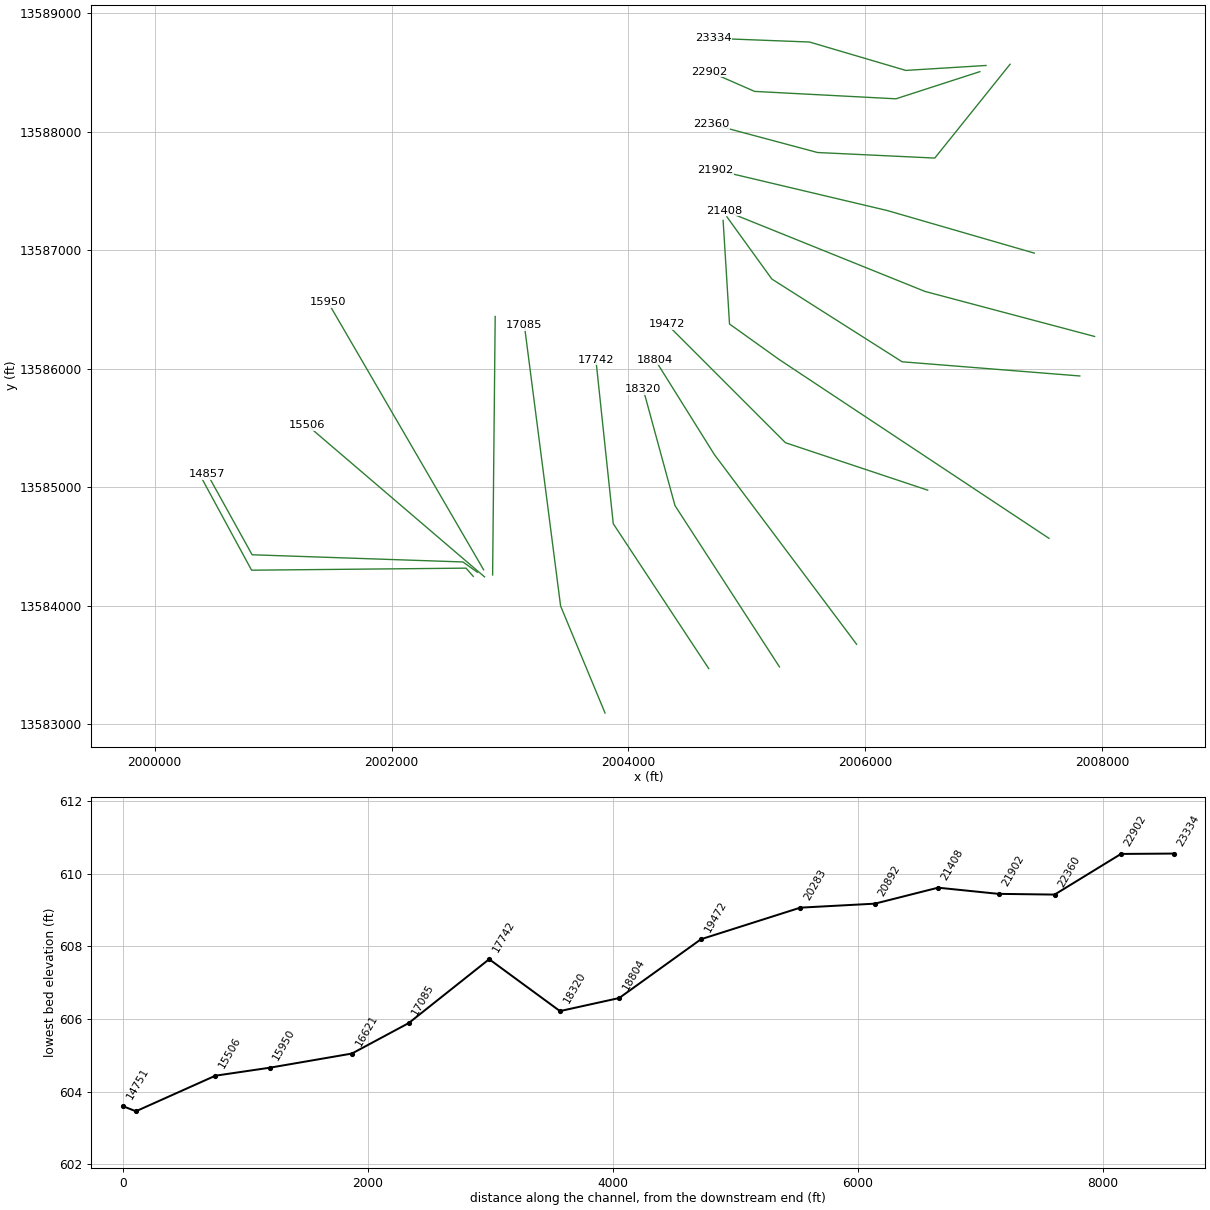
HEC-RAS study CHACON CREEK.prj: CHACON CREEK Base Level Engineering

--- CHACON CREEK.g01 (geometry) --- (continued)

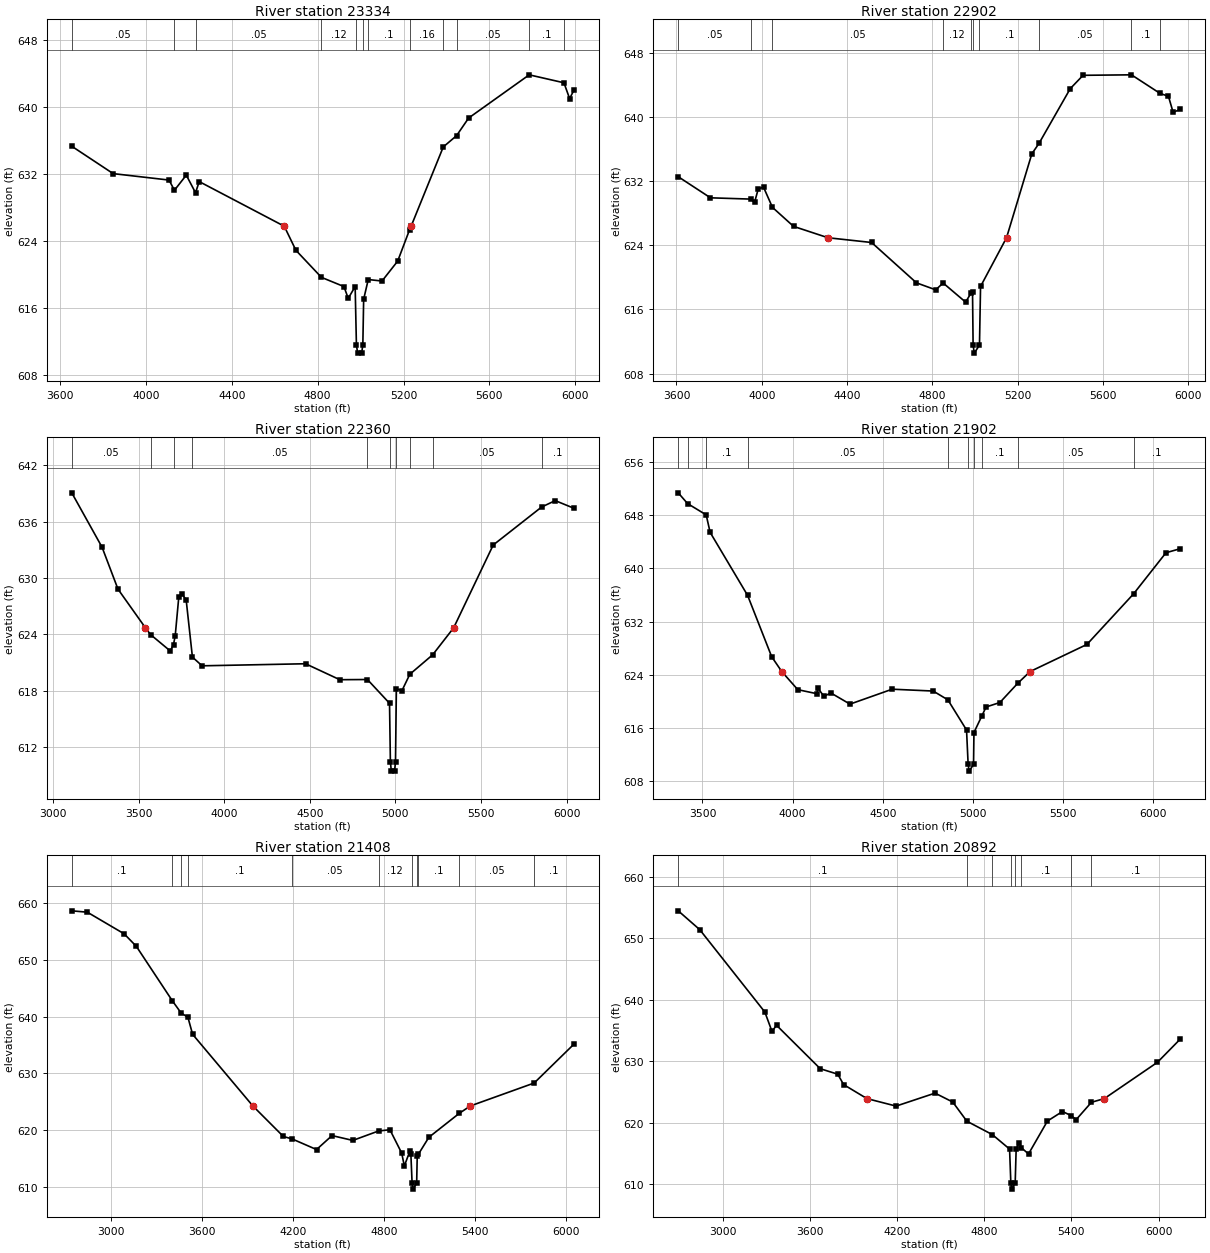
Type RM Length L Ch R = 1 ,23334   ,432,432,432
BEGIN DESCRIPTION:
Mapping XS 974b4d57
END DESCRIPTION:
XS GIS Cut Line= 4
      2007017.39     13588558.14      2006340.34     13588516.47
      2005527.84     13588756.05      2004715.36      13588787.3
#Sta/Elev= 30
  3654.9  635.27  3847.7     632  4108.1  631.23    4133  630.01  4188.3  631.82
  4231.4  629.71  4248.4  631.05 4644.53625.7188  4698.9  622.84  4817.8  619.61
  4922.6  618.51  4942.5   617.1  4974.8  618.51  4980.7  611.56  4986.2  610.56
  5005.1  610.56  5010.6  611.56  5014.4  616.99  5035.8  619.35  5099.9  619.17
  5172.9  621.55  5228.3   625.3  5235.5625.7188  5385.3  635.19    5447  636.53
  5503.4  638.64  5785.5   643.8  5947.3  642.85  5973.7  640.96  5993.4  641.95
#Mann= 12 ,-1 , 0
  3654.9     .05       0    4133     .08       0  4231.4     .05       0
  4817.8     .12       0  4980.7     .07       0  5010.6     .12       0
  5035.8      .1       0  5228.3     .16       0  5385.3      .1       0
    5447     .05       0  5785.5      .1       0  5947.3     .05       0
Bank Sta=4644.53,5235.5
XS Rating Curve= 0 ,0
Exp/Cntr=0.3,0.1

Type RM Length L Ch R = 1 ,22902   ,542,542,542
BEGIN DESCRIPTION:
Mapping XS 84049724
END DESCRIPTION:
XS GIS Cut Line= 4
      2006965.36     13588506.06      2006257.01     13588276.89
       2005064.3     13588339.39      2004684.08     13588506.06
#Sta/Elev= 30
  3608.4  632.54  3759.6  629.91  3947.7  629.75  3966.1  629.33  3983.7  631.03
  4008.2  631.24  4050.1  628.72    4149  626.35 4310.82624.9313  4515.1  624.34
  4725.4  619.31  4815.5  618.44  4850.4  619.29  4955.7  616.91  4982.1  618.07
  4988.2  618.17  4990.9  611.55  4996.4  610.55  5020.8  611.55  5025.8  618.86
  5147.6624.9316  5266.2  635.39    5300   636.7  5446.4  643.52  5506.5  645.18
  5733.4  645.24  5867.1  642.93  5906.8  642.56  5928.6  640.57  5962.4  640.93
#Mann= 10 ,-1 , 0
  3608.4     .05       0  3947.7     .08       0  4050.1     .05       0
  4850.4     .12       0  4982.1      .1       0  4990.9     .07       0
  5020.8      .1       0    5300     .05       0  5733.4      .1       0
  5867.1     .08       0
Bank Sta=4310.82,5147.6
XS Rating Curve= 0 ,0
Exp/Cntr=0.3,0.1

Type RM Length L Ch R = 1 ,22360   ,458,458,458
BEGIN DESCRIPTION:
CHACON CREEK 28.0
END DESCRIPTION:
XS GIS Cut Line= 4
      2007220.52     13588568.52      2006585.13     13587776.89
      2005595.55     13587823.76      2004699.91      13588063.3
#Sta/Elev= 30
  3109.6  639.08  3286.7  633.28  3379.5  628.82 3539.83624.7014  3569.6  623.98
  3685.1  622.23  3703.9  622.92  3713.9  623.86  3734.8  627.99  3755.6  628.26
  3777.9  627.66  3814.4  621.58  3870.7  620.65  4475.2  620.87  4675.4  619.17
  4836.6  619.19  4965.8  616.66  4970.8  610.43  4976.3  609.43  4995.2  609.43
  5000.7  610.43  5005.8  618.21  5038.3     618  5084.4  619.75  5217.6  621.82
 5340.57624.7015  5571.4  633.52  5853.6  637.56  5933.7  638.25  6042.5  637.44
#Mann= 10 ,-1 , 0
  3109.6     .05       0  3569.6      .1       0  3703.9     .08       0
  3814.4     .05       0  4836.6     .12       0  4970.8     .07       0
  5000.7     .12       0  5084.4      .1       0  5217.6     .05       0
  5853.6      .1       0
Bank Sta=3539.83,5340.57
XS Rating Curve= 0 ,0
Exp/Cntr=0.3,0.1

Type RM Length L Ch R = 1 ,21902   ,494,494,494
BEGIN DESCRIPTION:
CHACON CREEK 27.0
END DESCRIPTION:
XS GIS Cut Line= 3
      2007424.96     13586975.01      2006184.09     13587334.18
        2004731.     13587677.92
#Sta/Elev= 30
  3365.7   651.4  3417.4  649.78  3520.7  648.08  3542.6  645.44  3750.5  635.94
  3884.1  626.69 3940.09624.4576  4028.9  621.73  4134.9  621.12  4140.1  621.97
  4173.7  620.73  4212.5  621.23  4318.5  619.55  4552.5   621.8  4779.9  621.52
  4861.2   620.2  4964.9  615.65  4973.8  610.45  4979.3  609.45  5003.7  610.45
    5006  615.27    5049  617.72  5073.3  619.12  5149.8  619.79  5248.9  622.69
 5317.32624.4578  5632.8  628.55  5891.1  636.16  6071.2  642.37  6150.7  642.98
#Mann= 10 ,-1 , 0
  3365.7      .1       0  3417.4     .05       0  3520.7      .1       0
  3750.5     .05       0  4861.2     .12       0  4973.8     .07       0
  5003.7     .12       0    5049      .1       0  5248.9     .05       0
  5891.1      .1       0
Bank Sta=3940.09,5317.32
XS Rating Curve= 0 ,0
Exp/Cntr=0.3,0.1

Type RM Length L Ch R = 1 ,21408   ,516,516,516
BEGIN DESCRIPTION:
CHACON CREEK 26.0
END DESCRIPTION:
XS GIS Cut Line= 3
      2007934.05     13586271.69       2006501.8     13586651.89
      2004809.55     13587333.99
#Sta/Elev= 30
    2743  658.64  2845.5   658.4  3087.9  654.59  3168.3  652.38  3405.1   642.8
  3463.5  640.63  3507.8   639.9  3538.7  636.89 3935.57624.2717  4136.6  618.89
  4193.4  618.47  4354.9  616.59  4456.9  619.05  4593.8   618.2  4763.3  619.86
  4838.2  620.08    4916  615.95    4933  613.69  4969.7  616.33  4976.1  615.78
  4984.3  610.62  4989.8  609.62  5014.2  610.62  5018.1  615.54  5025.3  615.75
  5094.7  618.75  5295.9  622.99 5367.91624.2719  5788.1  628.31  6049.4  635.14
#Mann= 11 ,-1 , 0
    2743      .1       0  3405.1     .08       0  3463.5     .05       0
  3507.8      .1       0  4193.4     .05       0  4763.3     .12       0
  4984.3     .07       0  5014.2     .12       0  5025.3      .1       0
  5295.9     .05       0  5788.1      .1       0
Bank Sta=3935.57,5367.91
XS Rating Curve= 0 ,0
Exp/Cntr=0.3,0.1

Type RM Length L Ch R = 1 ,20892   ,609,609,609
BEGIN DESCRIPTION:
Mapping XS fe0033fc
END DESCRIPTION:
XS GIS Cut Line= 4
      2007809.06     13585938.35      2006309.09     13586058.14
      2005210.13     13586756.05      2004830.71       13587281.
#Sta/Elev= 30
  2694.9  654.46  2842.8   651.4  3290.9  637.99  3339.9  634.84  3371.1  635.84
  3672.1  628.77  3792.4  627.88  3832.6  626.19 3993.16623.9089  4193.7  622.69
  4461.7   624.8  4583.6  623.35  4680.8  620.23    4856  618.05  4974.5   615.7
  4983.2  610.18  4988.7  609.18  5013.1  610.18  5019.9  615.78  5041.1  616.74
  5055.2  615.93  5104.8   614.9  5235.1  620.26  5338.4  621.81  5397.6  621.15
  5432.4  620.48  5537.7  623.31 5626.38 623.909  5992.2  629.82  6149.2   633.6
#Mann= 8 ,-1 , 0
  2694.9      .1       0  4680.8     .16       0    4856     .12       0
  4983.2     .07       0  5013.1     .12       0  5055.2      .1       0
  5397.6     .05       0  5537.7      .1       0
Bank Sta=3993.16,5626.38
XS Rating Curve= 0 ,0
Exp/Cntr=0.3,0.1

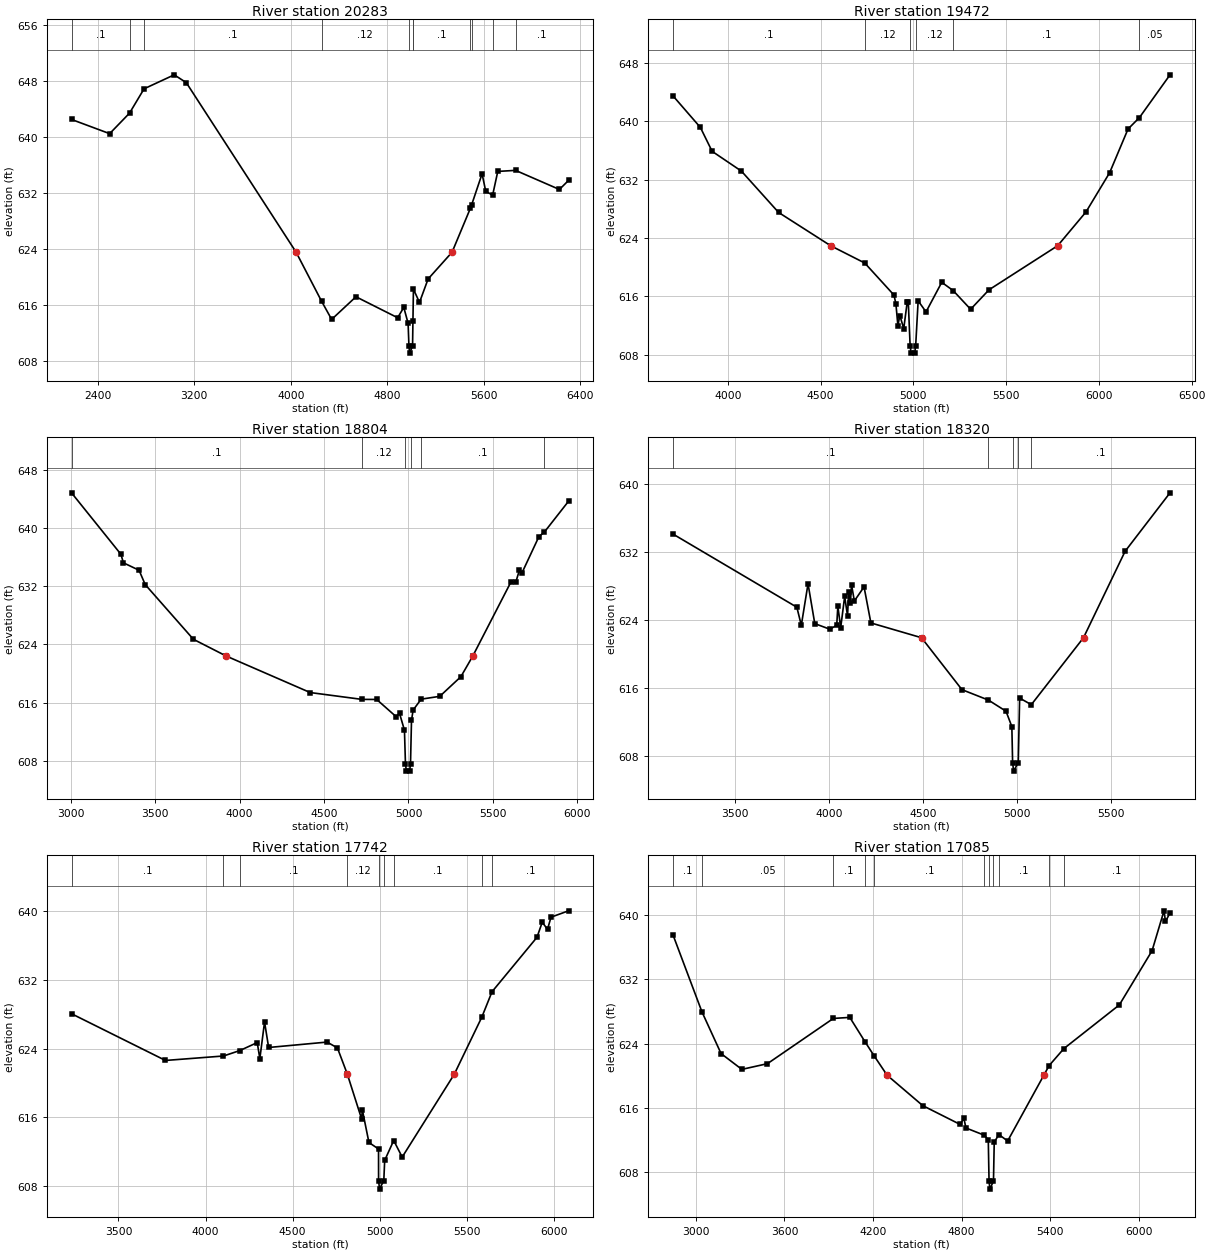
Type RM Length L Ch R = 1 ,20283   ,811,811,811
BEGIN DESCRIPTION:
CHACON CREEK 25.0
END DESCRIPTION:
XS GIS Cut Line= 4
      2007548.65     13584568.57        2005275.       13586075.
      2004852.78     13586376.59       2004798.7     13587250.43
#Sta/Elev= 30
  2181.4  642.48  2497.7  640.45  2662.4  643.38    2783  646.86  3033.2  648.86
  3133.4  647.74 4044.09623.4989  4255.2  616.49  4338.8  613.89  4540.3  617.13
  4886.2  614.13  4937.1  615.61  4972.7  613.34  4979.9  610.07  4985.3  609.07
  5009.8  610.07    5013  613.69    5017  618.22  5067.3  616.32  5138.6  619.67
 5337.47623.4993  5490.1  629.81  5499.7  630.27  5586.4  634.71  5616.5  632.22
  5673.8  631.65  5716.6  635.05    5864   635.2  6227.6  632.47  6303.2  633.76
#Mann= 11 ,-1 , 0
  2181.4      .1       0  2662.4     .08       0    2783      .1       0
  4255.2     .12       0  4979.9     .07       0  5009.8     .12       0
    5013      .1       0  5490.1     .05       0  5499.7      .1       0
  5673.8     .05       0    5864      .1       0
Bank Sta=4044.09,5337.47
XS Rating Curve= 0 ,0
Exp/Cntr=0.3,0.1

Type RM Length L Ch R = 1 ,19472   ,668,668,668
BEGIN DESCRIPTION:
CHACON CREEK 24.0
END DESCRIPTION:
XS GIS Cut Line= 3
      2006524.96     13584975.01        2005325.       13585375.
      2004324.99     13586375.01
#Sta/Elev= 30
  3704.2  643.51  3851.7  639.18    3915   635.9  4073.1  633.18  4273.4  627.51
 4553.92622.9439  4737.7  620.57  4895.3  616.17  4905.8  614.96  4916.4  611.98
  4926.9  613.36    4948  611.57  4966.4  615.16  4972.6  615.16  4982.4   609.2
  4987.9   608.2  5006.9   608.2  5012.3   609.2  5025.6  615.38  5068.1  613.86
  5152.9  617.92  5214.2  616.79  5308.5  614.22  5407.5  616.89 5777.88 622.944
  5930.7  627.59    6058  632.97    6157  638.96  6218.7  640.54  6383.3   646.4
#Mann= 6 ,-1 , 0
  3704.2      .1       0  4737.7     .12       0  4982.4     .07       0
  5012.3     .12       0  5214.2      .1       0  6218.7     .05       0
Bank Sta=4553.92,5777.88
XS Rating Curve= 0 ,0
Exp/Cntr=0.3,0.1

Type RM Length L Ch R = 1 ,18804   ,484,484,484
BEGIN DESCRIPTION:
CHACON CREEK 23.0
END DESCRIPTION:
XS GIS Cut Line= 3
      2005924.98     13583675.02        2004725.       13585275.
      2004224.98     13586075.03
#Sta/Elev= 30
  3004.5  644.83  3297.2  636.38  3311.8  635.21  3404.5  634.19  3440.9  632.22
  3726.3   624.7 3920.06622.4054    4418  617.38  4724.5  616.44  4811.8  616.43
  4926.3  614.08  4947.2  614.51  4976.3   612.2  4982.2  607.58  4987.7  606.58
  5006.7  606.58  5012.1  607.58    5018  613.54  5027.5  614.97  5075.2  616.47
  5185.5  616.86  5310.5  619.56  5381.2622.4056  5605.9  632.53    5636  632.57
  5657.2  634.21  5672.5  633.84  5772.8  638.82  5805.4  639.45  5947.9  643.67
#Mann= 6 ,-1 , 0
  3004.5      .1       0  4724.5     .12       0  4982.2     .07       0
  5012.1     .12       0  5075.2      .1       0  5805.4     .05       0
Bank Sta=3920.06,5381.2
XS Rating Curve= 0 ,0
Exp/Cntr=0.3,0.1

Type RM Length L Ch R = 1 ,18320   ,578,578,578
BEGIN DESCRIPTION:
CHACON CREEK 22.0
END DESCRIPTION:
XS GIS Cut Line= 3
      2005274.35     13583483.52      2004392.42      13584844.6
      2004125.01     13585824.95
#Sta/Elev= 30
  3173.3  634.15  3830.7  625.53  3854.3   623.4    3890   628.3  3925.8   623.6
    4006  622.94  4042.3  623.41  4048.2  625.65  4063.4  623.14  4084.5   626.8
  4099.7  624.51  4105.6  627.35  4114.8     626  4120.8  628.18  4135.9  626.27
  4187.3  627.93  4223.6  623.68 4492.31621.9384  4706.9  615.82  4847.5  614.59
  4940.7  613.28  4971.8  611.47  4975.9  607.22  4981.3  606.22  5005.8  607.22
  5013.2  614.83  5075.1  614.05 5352.16621.9383  5572.9  632.12  5811.3  639.01
#Mann= 5 ,-1 , 0
  3173.3      .1       0  4847.5     .12       0  4975.9     .07       0
  5005.8     .12       0  5075.1      .1       0
Bank Sta=4492.31,5352.16
XS Rating Curve= 0 ,0
Exp/Cntr=0.3,0.1

Type RM Length L Ch R = 1 ,17742   ,657,657,657
BEGIN DESCRIPTION:
CHACON CREEK 21.0
END DESCRIPTION:
XS GIS Cut Line= 3
      2004677.16     13583469.58      2003871.59     13584691.82
        2003725.     13586075.04
#Sta/Elev= 30
  3230.3  628.07    3770  622.63  4103.3  623.15  4196.8  623.78    4297  624.71
  4312.1  622.84  4339.1  627.11  4362.6  624.14  4698.2  624.77  4757.7  624.09
 4814.75621.0288  4815.3  620.99  4896.2  615.85  4901.2  616.84  4938.7  613.08
  4993.9  612.32  4994.1  608.65  4999.6  607.65  5024.1  608.65  5029.2     611
    5081  613.31  5129.7  611.38    5429621.0288  5587.5  627.69  5645.7  630.63
  5904.1  636.97  5934.2  638.73  5964.4  637.89  5984.5  639.31  6085.1  640.05
#Mann= 9 ,-1 , 0
  3230.3      .1       0  4103.3     .05       0  4196.8      .1       0
  4815.3     .12       0  4994.1     .07       0  5024.1     .12       0
    5081      .1       0  5587.5     .08       0  5645.7      .1       0
Bank Sta=4814.75,5429
XS Rating Curve= 0 ,0
Exp/Cntr=0.3,0.1

Type RM Length L Ch R = 1 ,17085   ,464,464,464
BEGIN DESCRIPTION:
CHACON CREEK 20.0
END DESCRIPTION:
XS GIS Cut Line= 3
      2003802.14      13583094.6      2003427.15     13583997.37
       2003121.6     13586365.38
#Sta/Elev= 30
  2845.6  637.52  3041.5  627.95  3170.9  622.76  3311.7  620.79  3484.9   621.5
  3931.4  627.13  4042.6  627.26  4145.3  624.24  4207.1  622.48 4295.21620.0657
  4536.7  616.28  4788.7  613.95  4815.3  614.68  4829.1   613.5  4954.5  612.59
  4980.3  612.01  4985.5  606.89    4991  605.89  5015.5  606.89  5020.6  611.73
  5052.2  612.68  5111.4  611.88 5356.54620.0657  5392.5  621.27  5492.4  623.38
  5867.6  628.81  6089.4  635.56  6170.1  640.52  6180.2   639.2  6210.8  640.26
#Mann= 11 ,-1 , 0
  2845.6      .1       0  3041.5     .05       0  3931.4      .1       0
  4145.3     .05       0  4207.1      .1       0  4954.5     .12       0
  4985.5     .07       0  5015.5     .12       0  5052.2      .1       0
  5392.5     .05       0  5492.4      .1       0
Bank Sta=4295.21,5356.54
XS Rating Curve= 0 ,0
Exp/Cntr=0.3,0.1

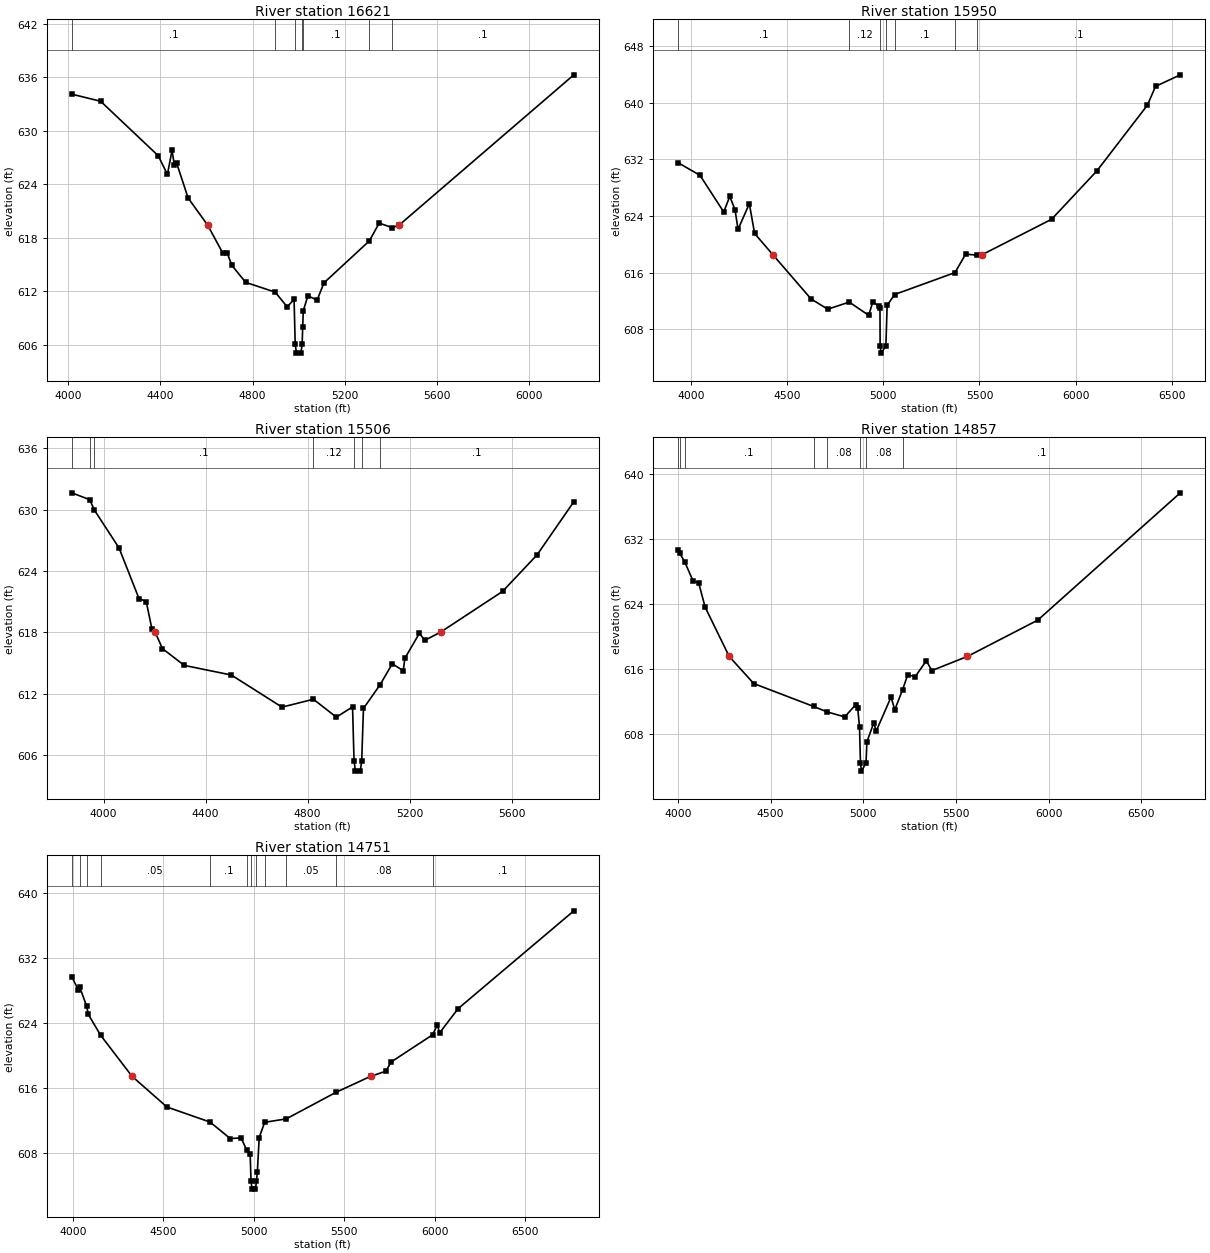
Type RM Length L Ch R = 1 ,16621   ,671,671,671
BEGIN DESCRIPTION:
Mapping XS dfac37f3
END DESCRIPTION:
XS GIS Cut Line= 2
      2002853.36     13584259.49      2002875.06     13586440.28
#Sta/Elev= 30
  4014.9  634.12  4140.4  633.32  4390.4  627.21  4430.4  625.11  4450.4  627.81
  4460.4   626.2  4470.4  626.38  4520.4  622.46 4605.27619.4149  4670.4   616.3
  4690.4  616.26  4710.4   614.9  4770.5  612.99  4898.3   611.9  4950.5  610.25
  4980.5  611.07  4985.5  606.05    4991  605.05    5010  605.05  5015.5  606.05
  5018.1  608.01  5020.5  609.81  5040.5  611.48  5080.5     611  5110.5  612.94
  5307.2  617.64  5350.5  619.65  5406.8  619.13 5436.58 619.415  6195.8  636.29
#Mann= 7 ,-1 , 0
  4014.9      .1       0  4898.3     .12       0  4985.5     .07       0
  5015.5     .12       0  5018.1      .1       0  5307.2     .05       0
  5406.8      .1       0
Bank Sta=4605.27,5436.58
XS Rating Curve= 0 ,0
Exp/Cntr=0.3,0.1

Type RM Length L Ch R = 1 ,15950   ,444,444,444
BEGIN DESCRIPTION:
Mapping XS 2807bbf7
END DESCRIPTION:
XS GIS Cut Line= 2
      2002777.43     13584302.89      2001464.47     13586559.88
#Sta/Elev= 30
  3933.4  631.51  4046.7  629.74    4170  624.57  4201.4  626.77  4228.7  624.89
  4244.4  622.12  4303.2  625.74  4330.5  621.54 4424.91618.5613  4624.3   612.3
    4711  610.86  4822.7  611.86  4923.8     610  4945.3  611.88  4976.8  611.28
  4982.6  611.04  4983.3  605.66  4988.8  604.66  5013.3  605.66  5019.8   611.4
  5058.9  612.93  5372.6  616.02  5428.2  618.63  5488.9  618.47 5514.89618.5615
  5875.4  623.55  6110.4  630.36  6372.8  639.62  6415.8  642.29  6544.5  643.92
#Mann= 7 ,-1 , 0
  3933.4      .1       0  4822.7     .12       0  4983.3     .07       0
  5013.3     .12       0  5058.9      .1       0  5372.6     .05       0
  5488.9      .1       0
Bank Sta=4424.91,5514.89
XS Rating Curve= 0 ,0
Exp/Cntr=0.3,0.1

Type RM Length L Ch R = 1 ,15506   ,649,649,649
BEGIN DESCRIPTION:
Mapping XS a2e7410b
END DESCRIPTION:
XS GIS Cut Line= 2
      2002785.29     13584243.15      2001288.93     13585522.64
#Sta/Elev= 30
  3875.2  631.66  3945.6  630.99  3963.7  629.98  4060.7  626.26  4138.7  621.32
  4167.2  621.03  4189.1  618.39 4201.76618.0527  4230.8  616.42  4316.5  614.78
  4500.9  613.84  4699.6   610.7  4822.8  611.47  4912.6  609.72  4976.2  610.72
  4982.1  605.44  4987.6  604.44  5006.6  604.44  5012.1  605.44    5019  610.57
    5084  612.88  5132.1  614.94  5174.9  614.26  5181.5  615.48  5238.6  617.93
  5259.4  617.23 5322.67618.0524  5564.6  622.02  5699.7  625.59    5844  630.79
#Mann= 7 ,-1 , 0
  3875.2      .1       0  3945.6     .05       0  3963.7      .1       0
  4822.8     .12       0  4982.1     .07       0  5012.1     .12       0
    5084      .1       0
Bank Sta=4201.76,5322.67
XS Rating Curve= 0 ,0
Exp/Cntr=0.3,0.1

Type RM Length L Ch R = 1 ,14857   ,106,106,106
BEGIN DESCRIPTION:
Mapping XS a5912e8c
END DESCRIPTION:
XS GIS Cut Line= 4
      2002724.55      13584282.2      2002602.98     13584369.03
      2000823.47     13584429.79       2000446.2     13585110.61
#Sta/Elev= 30
  4001.4  630.62  4009.9   630.2    4037  629.12  4082.2  626.77  4111.4   626.6
  4146.5  623.59 4276.45617.5363  4408.9  614.21  4731.5   611.4  4806.4  610.72
  4899.2  610.12  4959.2  611.62  4969.3  611.25  4979.3  608.86  4984.3  604.46
  4989.8  603.46  5014.3  604.46  5019.3  607.07  5056.3   609.4  5069.3  608.38
  5149.4  612.55  5169.4  610.99  5211.7  613.46  5239.4  615.29  5279.4  615.05
  5339.5  617.01  5369.5  615.81 5560.76617.5363  5940.8     622  6709.7  637.63
#Mann= 8 ,-1 , 0
  4001.4      .1       0  4009.9     .05       0    4037      .1       0
  4731.5     .05       0  4806.4     .08       0  4984.3     .07       0
  5014.3     .08       0  5211.7      .1       0
Bank Sta=4276.45,5560.76
XS Rating Curve= 0 ,0
Exp/Cntr=0.3,0.1

Type RM Length L Ch R = 1 ,14751   ,627,627,627
BEGIN DESCRIPTION:
Mapping XS 61b51acc
END DESCRIPTION:
XS GIS Cut Line= 4
      2002689.78     13584247.51      2002629.02     13584316.94
      2000819.13     13584299.58      2000402.46     13585067.82
#Sta/Elev= 30
  3993.1  629.72  4029.7  628.09  4036.5  628.47  4074.6  626.16  4084.6  625.09
  4152.2  622.54 4326.55617.4727  4519.4   613.7  4757.8  611.85  4869.4  609.82
  4929.4   609.9  4961.5  608.36  4979.4  607.88  4984.4   604.6  4989.9   603.6
  5008.9   603.6  5014.4   604.6  5019.4  605.75  5029.4  609.95  5059.7  611.82
  5179.1  612.24  5452.6  615.49 5645.29617.4727  5729.5   618.1  5759.5  619.25
  5988.1  622.58  6014.5  623.81  6026.6  622.81  6129.5   625.8  6769.3  637.83
#Mann= 12 ,-1 , 0
  3993.1      .1       0  4036.5     .05       0  4074.6      .1       0
  4152.2     .05       0  4757.8      .1       0  4961.5     .12       0
  4984.4     .07       0  5014.4     .12       0  5059.7      .1       0
  5179.1     .05       0  5452.6     .08       0  5988.1      .1       0
Bank Sta=4326.55,5645.29
XS Rating Curve= 0 ,0
Exp/Cntr=0.3,0.1