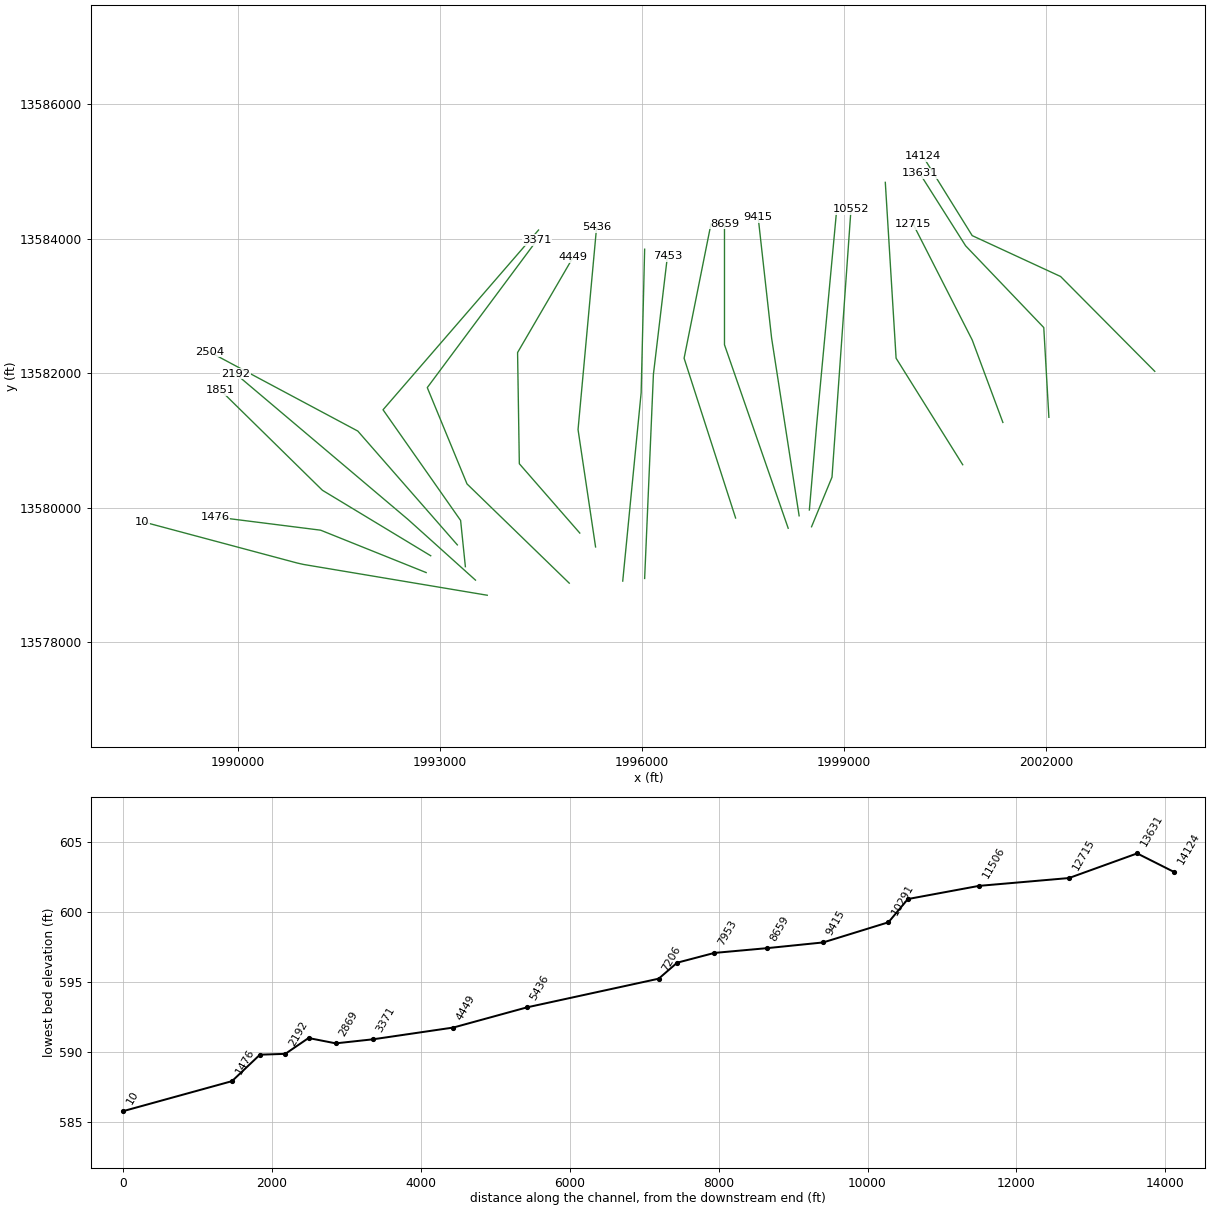
HEC-RAS study CHACON CREEK.prj: CHACON CREEK Base Level Engineering

--- CHACON CREEK.g01 (geometry) --- (continued)

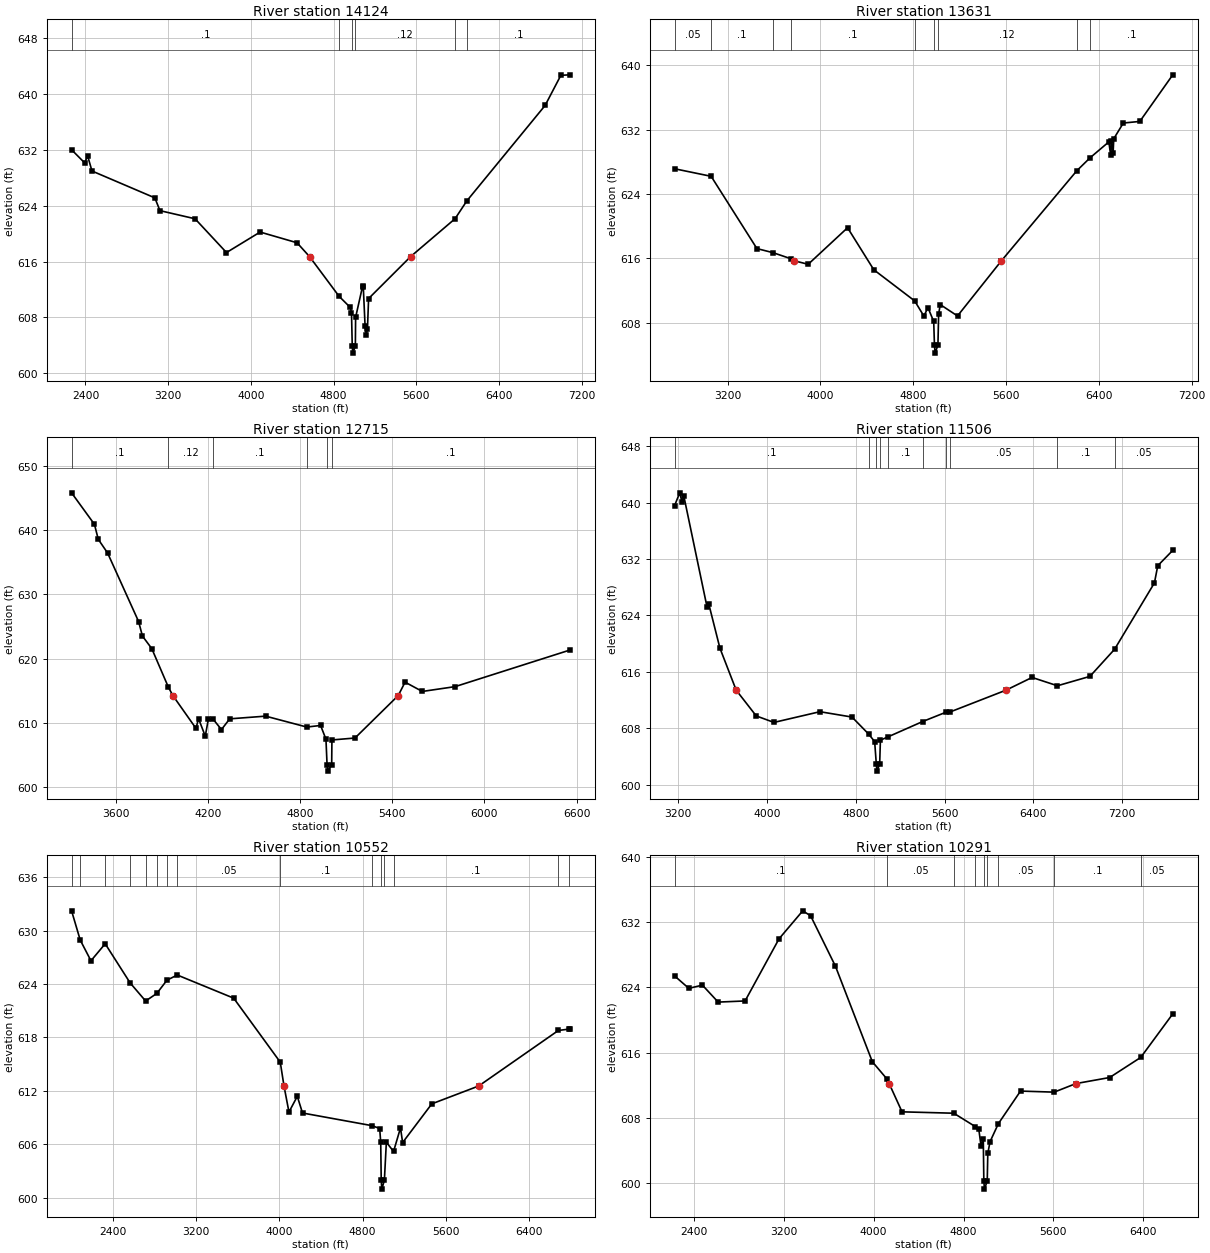
Type RM Length L Ch R = 1 ,14124   ,493,493,493
BEGIN DESCRIPTION:
CHACON CREEK 17.0
END DESCRIPTION:
XS GIS Cut Line= 4
      2003618.62     13582029.61      2002218.87     13583440.21
      2000905.93     13584047.85      2000174.99     13585225.01
#Sta/Elev= 30
  2265.6  631.98  2392.2   630.1  2420.5  631.12  2462.9  628.94    3071   625.1
  3120.5  623.27  3459.9  622.11    3764  617.28  4089.3  620.21  4446.4  618.68
 4567.13 616.705  4853.4  611.02  4961.7  609.43  4973.3   608.7  4980.6   603.9
  4986.1   602.9  5010.6   603.9  5013.1  608.01  5081.8  612.55  5087.3  612.38
  5104.8  606.75  5116.6  605.54  5127.6  606.33  5138.7   610.7 5545.66 616.705
  5975.3  622.12  6089.1  624.67  6846.1  638.31  6998.4  642.62  7085.2  642.69
#Mann= 6 ,-1 , 0
  2265.6      .1       0  4853.4     .12       0  4980.6     .07       0
  5010.6     .12       0  5975.3     .05       0  6089.1      .1       0
Bank Sta=4567.13,5545.66
XS Rating Curve= 0 ,0
Exp/Cntr=0.3,0.1

Type RM Length L Ch R = 1 ,13631   ,916,916,916
BEGIN DESCRIPTION:
CHACON CREEK 16.0
END DESCRIPTION:
XS GIS Cut Line= 4
      2002045.26     13581345.98       2001969.3     13582680.66
      2000808.28     13583895.94      2000124.99     13584975.02
#Sta/Elev= 30
    2742  627.13  3057.6  626.19  3452.2  617.21  3591.5   616.7  3746.8  615.94
 3772.58615.6981  3894.2  615.26  4233.6   619.8  4459.7  614.58    4812  610.71
  4891.2  608.83  4926.7  609.86  4976.1  608.16  4982.5  605.22    4988  604.22
  5012.5  605.22  5018.6  609.08  5032.7  610.25  5181.2  608.84 5559.96615.6979
  6209.5  626.88  6323.8  628.49  6485.9  630.47  6501.1  628.85  6507.1  630.63
  6522.3  629.05  6528.2  630.86  6610.5  632.81  6752.8  633.01  7036.8   638.8
#Mann= 9 ,-1 , 0
    2742     .05       0  3057.6      .1       0  3591.5     .05       0
  3746.8      .1       0    4812     .12       0  4982.5     .07       0
  5012.5     .12       0  6209.5     .08       0  6323.8      .1       0
Bank Sta=3772.58,5559.96
XS Rating Curve= 0 ,0
Exp/Cntr=0.3,0.1

Type RM Length L Ch R = 1 ,12715   ,1209,1209,1209
BEGIN DESCRIPTION:
CHACON CREEK 15.0
END DESCRIPTION:
XS GIS Cut Line= 3
      2001361.66     13581270.07      2000905.93      13582496.2
       2000027.4     13584220.73
#Sta/Elev= 30
  3312.2  645.84    3461  640.93    3486  638.59  3546.7  636.46  3748.5  625.78
  3773.5  623.51  3834.3  621.56  3942.1  615.56 3971.39614.2463  4121.8  609.13
  4138.9  610.63  4182.5  607.91  4202.2  610.52  4231.5  610.62  4287.9  608.94
  4341.6  610.61  4575.5  611.03  4843.5  609.33  4933.2  609.58  4968.1  607.44
  4975.4  603.46  4980.9  602.46  5005.4  603.46    5007  607.32  5157.1  607.62
 5438.92614.2465  5483.1  616.33  5595.3  614.88  5808.6  615.63  6555.7  621.33
#Mann= 6 ,-1 , 0
  3312.2      .1       0  3942.1     .12       0  4231.5      .1       0
  4843.5     .12       0  4975.4     .07       0  5005.4      .1       0
Bank Sta=3971.39,5438.92
XS Rating Curve= 0 ,0
Exp/Cntr=0.3,0.1

Type RM Length L Ch R = 1 ,11506   ,954,954,954
BEGIN DESCRIPTION:
CHACON CREEK 14.0
END DESCRIPTION:
XS GIS Cut Line= 3
      2000764.85     13580640.77        1999775.       13582225.
       1999614.7     13584839.95
#Sta/Elev= 30
  3168.1  639.54  3214.7  641.38  3235.9  640.07  3251.2  640.97  3461.2  625.16
  3476.5  625.62  3576.7  619.36 3723.43613.3879  3904.2  609.73  4063.8  608.81
  4477.7  610.33  4766.7  609.57  4916.5  607.16  4970.7  606.09  4985.7   602.9
  4991.2   601.9  5015.9   602.9  5022.6  606.29    5095  606.79  5403.8  608.94
  5609.1  610.23    5648  610.28 6154.32613.3881  6388.7  615.19  6617.2  614.01
  6909.7  615.34    7132  619.19  7490.7   628.6  7520.8  631.04    7656  633.22
#Mann= 10 ,-1 , 0
  3168.1      .1       0  4916.5     .12       0  4985.7     .07       0
  5015.9     .12       0    5095      .1       0  5403.8     .05       0
  5609.1      .1       0    5648     .05       0  6617.2      .1       0
    7132     .05       0
Bank Sta=3723.43,6154.32
XS Rating Curve= 0 ,0
Exp/Cntr=0.3,0.1

Type RM Length L Ch R = 1 ,10552   ,261,261,261
BEGIN DESCRIPTION:
Mapping XS 6c87584a
END DESCRIPTION:
XS GIS Cut Line= 3
      1998518.77      13579718.4       1998822.6     13580456.27
      1999104.72     13584438.51
#Sta/Elev= 30
  2001.8  632.22  2084.8  628.94  2188.1  626.61  2324.9  628.52    2565  624.12
  2713.7  622.09    2821  622.94  2918.9  624.43  3017.9  625.01  3560.4  622.41
  4008.1  615.22 4043.99612.5438  4091.7  609.62  4171.9  611.38  4222.1  609.51
  4889.7  608.09  4963.9  607.77  4973.9  606.22  4978.8  601.96  4984.4  600.96
  5009.1  601.96  5028.1  606.23  5097.3  605.19    5164  607.84  5184.5  606.19
  5465.2  610.54 5915.62612.5435  6681.6  618.78  6780.6  618.93    6792  618.97
#Mann= 15 ,-1 , 0
  2001.8      .1       0  2084.8     .05       0  2324.9     .08       0
    2565     .05       0  2713.7      .1       0    2821     .05       0
  2918.9      .1       0  3017.9     .05       0  4008.1      .1       0
  4889.7     .12       0  4978.8     .07       0  5009.1     .12       0
  5097.3      .1       0  6681.6     .08       0  6780.6      .1       0
Bank Sta=4043.99,5915.62
XS Rating Curve= 0 ,0
Exp/Cntr=0.3,0.1

Type RM Length L Ch R = 1 ,10291   ,876,876,876
BEGIN DESCRIPTION:
CHACON CREEK 13.0
END DESCRIPTION:
XS GIS Cut Line= 3
      1998486.23     13579967.98      1998594.73     13581237.52
      1998887.71     13584384.25
#Sta/Elev= 30
  2227.7   625.4  2355.2  623.87  2475.6  624.27  2616.1  622.19  2855.6  622.33
  3158.1  629.94  3368.9  633.36  3439.1  632.75    3660  626.58  3988.3  614.89
  4117.6  612.79 4137.99612.2167  4252.6  608.76  4713.2  608.59  4903.8  606.96
  4935.5  606.66  4955.6  604.59  4975.7  605.45  4980.6   600.3  4986.2   599.3
  5010.9   600.3  5015.9  603.67    5036  605.11  5110.3  607.32  5307.1   611.3
  5606.6  611.17 5800.15612.2166  6100.5  612.96  6377.2  615.42  6662.2  620.75
#Mann= 9 ,-1 , 0
  2227.7      .1       0  4117.6     .05       0  4713.2      .1       0
  4903.8     .12       0  4980.6     .07       0  5010.9     .12       0
  5110.3     .05       0  5606.6      .1       0  6377.2     .05       0
Bank Sta=4137.99,5800.15
XS Rating Curve= 0 ,0
Exp/Cntr=0.3,0.1

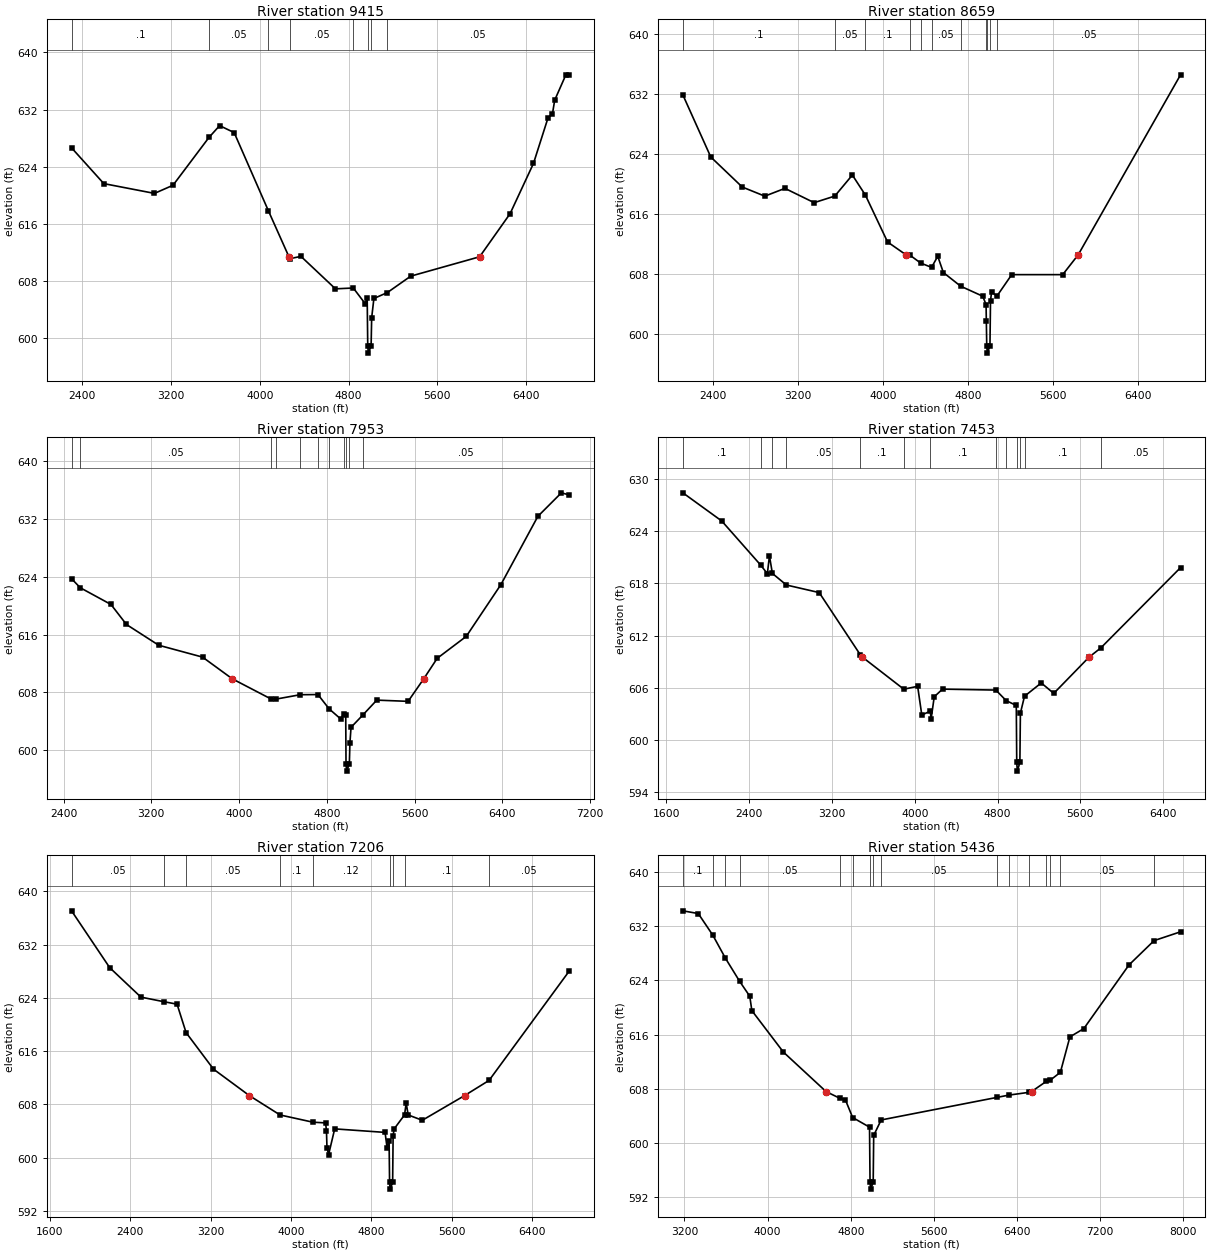
Type RM Length L Ch R = 1 ,9415    ,756,756,756
BEGIN DESCRIPTION:
CHACON CREEK 12.0
END DESCRIPTION:
XS GIS Cut Line= 3
      1998334.32     13579881.19        1997925.       13582525.
        1997725.     13584325.02
#Sta/Elev= 30
  2303.2  626.64  2594.1  621.62  3050.6  620.25  3217.8  621.39  3542.4   628.1
  3638.2  629.75  3769.3  628.77  4077.5  617.82 4263.03611.3646  4276.4  611.12
  4371.4  611.42  4682.2  606.87    4843  606.99  4949.5  604.81  4968.4  605.54
  4973.4  598.86    4979  597.86  5003.7  598.86  5008.7  602.81  5028.8  605.52
  5150.3  606.35  5360.8  608.65 5981.95611.3646  6256.3   617.4  6467.6  624.46
  6598.4  630.83  6638.7  631.43  6658.8  633.32  6759.4  636.87  6789.6  636.81
#Mann= 8 ,-1 , 0
  2303.2      .1       0  3542.4     .05       0  4077.5      .1       0
  4276.4     .05       0    4843     .12       0  4973.4     .07       0
  5003.7     .12       0  5150.3     .05       0
Bank Sta=4263.03,5981.95
XS Rating Curve= 0 ,0
Exp/Cntr=0.3,0.1

Type RM Length L Ch R = 1 ,8659    ,706,706,706
BEGIN DESCRIPTION:
CHACON CREEK 11.0
END DESCRIPTION:
XS GIS Cut Line= 3
      1998171.55     13579696.75        1997225.       13582425.
        1997225.     13584225.01
#Sta/Elev= 30
  2112.7  631.93  2375.5  623.64  2671.9  619.63  2884.5  618.41  3074.1  619.45
  3349.3  617.54  3543.7  618.42  3709.2  621.23  3831.6  618.56    4041  612.29
 4214.66610.5756  4248.9  610.56  4352.1  609.48  4455.3   608.9  4513.6  610.38
  4566.5  608.21  4729.1  606.39    4937  605.05  4968.7  603.94  4971.2   601.8
  4975.1  598.45  4980.7  597.45  5005.4  598.45  5010.5  604.43  5020.5  605.61
  5071.1  605.07  5210.5  607.93  5690.5  607.93 5836.41610.5754  6800.5  634.61
#Mann= 11 ,-1 , 0
  2112.7      .1       0  3543.7     .05       0  3831.6      .1       0
  4248.9     .05       0  4352.1      .1       0  4455.3     .05       0
  4729.1     .12       0  4971.2      .1       0  4975.1     .07       0
  5005.4      .1       0  5071.1     .05       0
Bank Sta=4214.66,5836.41
XS Rating Curve= 0 ,0
Exp/Cntr=0.3,0.1

Type RM Length L Ch R = 1 ,7953    ,500,500,500
BEGIN DESCRIPTION:
CHACON CREEK 10.0
END DESCRIPTION:
XS GIS Cut Line= 3
      1997390.31     13579848.62        1996625.       13582225.
        1997025.     13584225.01
#Sta/Elev= 30
  2473.3  623.72    2553  622.47  2832.6  620.16  2973.8  617.39  3267.9  614.52
  3667.2  612.88 3938.36 609.877  4288.8  607.11  4340.2  607.08  4558.1  607.68
  4719.2   607.7  4821.7  605.71  4927.9  604.31  4954.6  605.08  4972.4  604.91
  4975.1  598.11  4980.7  597.11  5005.4  598.11  5010.7  601.01  5020.9  603.17
  5127.1  604.85  5255.4  606.93    5541  606.76 5683.48609.8771  5806.1  612.71
  6071.3  615.75  6387.4  622.92  6723.9  632.35  6938.1   635.6  7009.5  635.31
#Mann= 11 ,-1 , 0
  2473.3      .1       0    2553     .05       0  4288.8      .1       0
  4340.2     .05       0  4558.1      .1       0  4719.2     .05       0
  4821.7     .12       0  4954.6      .1       0  4975.1     .07       0
  5005.4      .1       0  5127.1     .05       0
Bank Sta=3938.36,5683.48
XS Rating Curve= 0 ,0
Exp/Cntr=0.3,0.1

Type RM Length L Ch R = 1 ,7453    ,247,247,247
BEGIN DESCRIPTION:
CHACON CREEK 9.0
END DESCRIPTION:
XS GIS Cut Line= 3
      1996038.74     13578949.74      1996168.95     13581983.61
      1996377.21     13583740.75
#Sta/Elev= 30
    1761  628.41  2136.6  625.17  2511.8  620.11    2577  619.11    2597  621.16
  2625.6  619.14  2760.9  617.81  3077.5  616.94    3475  609.78 3495.57609.5104
  3894.7  605.83  4028.3  606.16  4068.4  602.86  4149.9  603.31  4158.5  602.42
  4188.5  604.96  4268.6  605.84  4783.6  605.73  4883.1  604.52  4980.9  603.96
  4985.3  597.41  4990.9  596.41  5015.6  597.41  5020.6  603.07  5060.3  605.02
    5222  606.55  5342.8  605.35  5683.2609.5104  5796.6  610.57  6567.1  619.81
#Mann= 13 ,-1 , 0
    1761      .1       0  2511.8     .05       0  2625.6      .1       0
  2760.9     .05       0    3475      .1       0  3894.7     .05       0
  4149.9      .1       0  4783.6     .08       0  4883.1     .12       0
  4985.3     .07       0  5015.6     .12       0  5060.3      .1       0
  5796.6     .05       0
Bank Sta=3495.57,5683.2
XS Rating Curve= 0 ,0
Exp/Cntr=0.3,0.1

Type RM Length L Ch R = 1 ,7206    ,1770,1770,1770
BEGIN DESCRIPTION:
CHACON CREEK 8.0
END DESCRIPTION:
XS GIS Cut Line= 3
      1995713.23     13578910.74      1995986.66     13581710.17
      1996038.74     13583845.58
#Sta/Elev= 30
  1817.9  637.07  2197.6  628.53  2507.6  624.11  2735.8  623.42  2867.1  623.05
  2956.8  618.78  3229.4  613.29  3585.5609.3233  3891.2  606.41  4218.8  605.32
  4344.1  605.22  4352.8  604.03  4357.8   601.5  4374.3  600.47  4434.6  604.32
  4935.6  603.79  4955.6  601.46  4975.6  602.52  4980.4  596.27    4986  595.27
  5010.8  596.27  5015.6  603.28  5025.6  604.31  5128.8  606.41  5145.6  608.17
  5165.6  606.41  5305.7  605.61 5726.62609.3233  5969.8   611.6  6766.7  628.02
#Mann= 9 ,-1 , 0
  1817.9     .05       0  2735.8      .1       0  2956.8     .05       0
  3891.2      .1       0  4218.8     .12       0  4980.4     .07       0
  5010.8     .12       0  5128.8      .1       0  5969.8     .05       0
Bank Sta=3585.5,5726.62
XS Rating Curve= 0 ,0
Exp/Cntr=0.3,0.1

Type RM Length L Ch R = 1 ,5436    ,987,987,987
BEGIN DESCRIPTION:
CHACON CREEK 7.0
END DESCRIPTION:
XS GIS Cut Line= 3
      1995309.58     13579418.48      1995049.16      13581163.3
        1995325.     13584175.05
#Sta/Elev= 30
  3184.4  634.22  3332.5  633.82  3472.7  630.63  3594.2  627.23  3730.4  623.84
    3828  621.64  3848.2  619.52  4151.5  613.41 4562.31607.5909  4692.6  606.62
  4748.1  606.38  4817.9  603.77  4980.4  602.35  4985.3  594.22  4990.9  593.22
  5015.7  594.22  5020.5  601.13  5092.3  603.41  6205.1  606.73  6320.6  607.07
  6519.1  607.49  6539.3607.5908    6681  609.09  6717.6  609.25  6816.8  610.43
  6908.4  615.65  7042.4  616.87  7477.6  626.26  7718.4  629.83  7972.9  631.13
#Mann= 16 ,-1 , 0
  3184.4      .1       0  3472.7     .05       0  3594.2      .1       0
  3730.4     .05       0  4692.6      .1       0  4817.9     .12       0
  4985.3     .07       0  5015.7     .12       0  5092.3     .05       0
  6205.1      .1       0  6320.6     .05       0  6519.1      .1       0
    6681     .05       0  6717.6      .1       0  6816.8     .05       0
  7718.4      .1       0
Bank Sta=4562.31,6539.3
XS Rating Curve= 0 ,0
Exp/Cntr=0.3,0.1

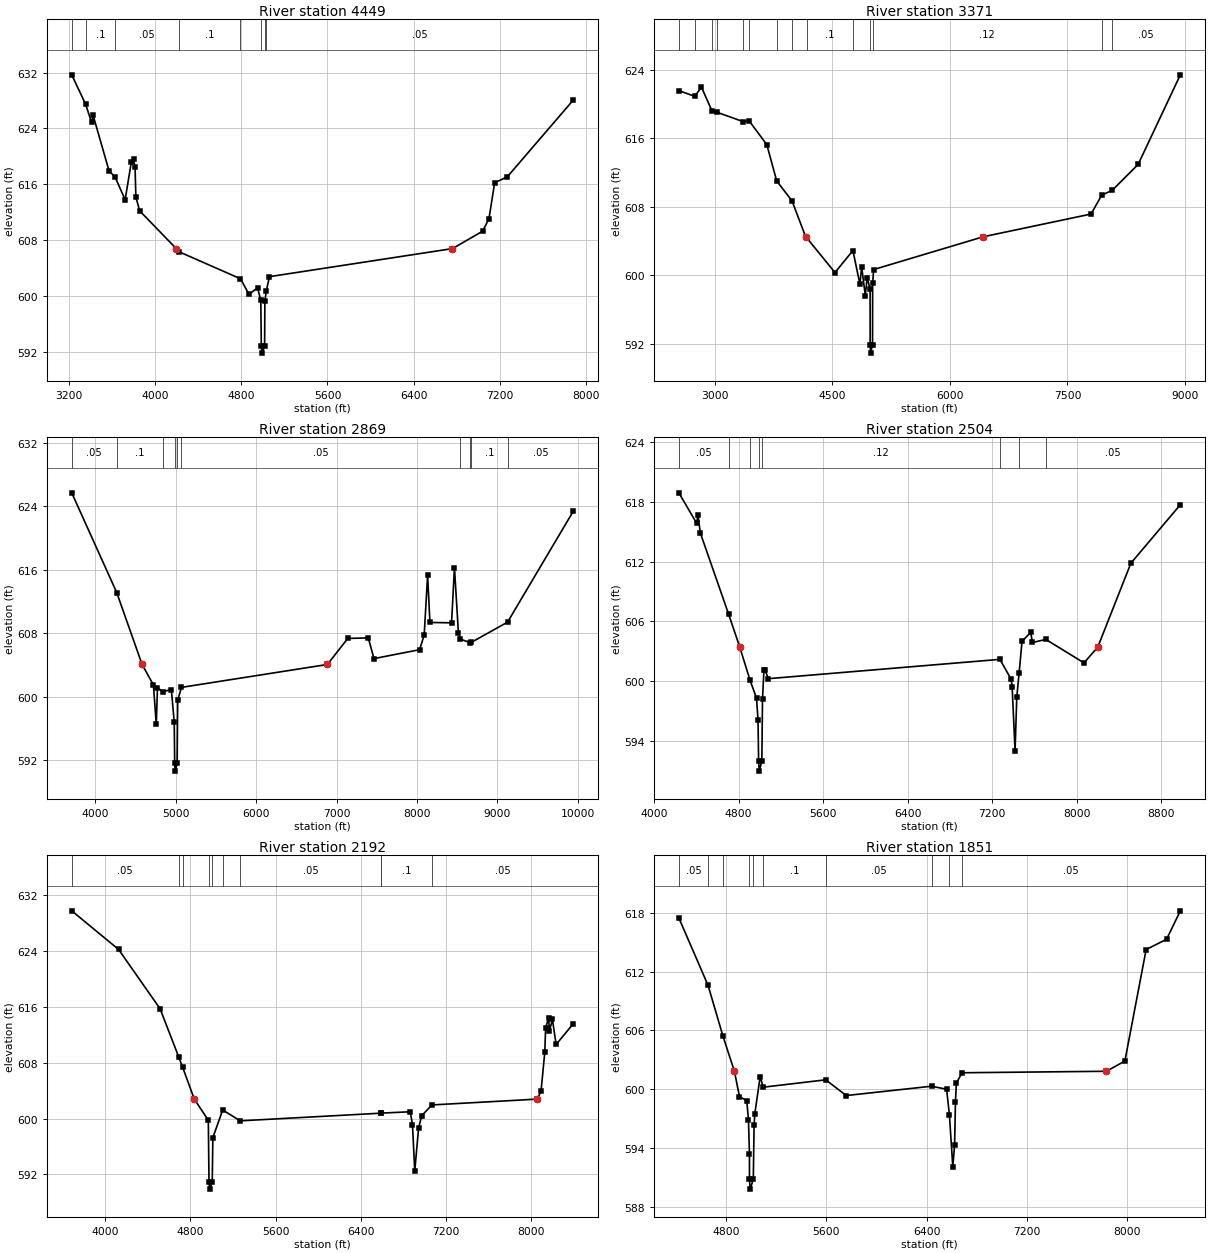
Type RM Length L Ch R = 1 ,4449    ,1078,1078,1078
BEGIN DESCRIPTION:
CHACON CREEK 6.0
END DESCRIPTION:
XS GIS Cut Line= 4
      1995074.97     13579625.04      1994176.77     13580655.49
      1994150.72     13582309.13      1994974.98     13583724.96
#Sta/Elev= 30
  3224.4  631.67  3352.5  627.48    3409  624.84  3423.3  625.85  3571.3  617.89
    3627  617.03  3720.4  613.76  3777.4  619.11  3798.2  619.54  3812.5  618.51
  3820.1  614.15  3855.2  612.18 4195.33 606.762  4223.7  606.29  4791.9  602.44
  4870.9  600.21  4950.9  601.14  4980.9  599.33  4985.7  592.78  4991.3  591.78
  5016.2  592.78  5018.5  599.19  5031.1  600.64  5060.9  602.74 6761.35606.7622
  7041.7  609.26  7100.5  611.05  7153.4  616.21  7270.3  617.04  7883.5  628.05
#Mann= 8 ,-1 , 0
  3224.4     .05       0  3352.5      .1       0    3627     .05       0
  4223.7      .1       0  4791.9     .12       0  4985.7     .07       0
  5016.2     .12       0  5031.1     .05       0
Bank Sta=4195.33,6761.35
XS Rating Curve= 0 ,0
Exp/Cntr=0.3,0.1

Type RM Length L Ch R = 1 ,3371    ,502,502,502
BEGIN DESCRIPTION:
CHACON CREEK 5.0
END DESCRIPTION:
XS GIS Cut Line= 4
      1994918.37     13578879.84       1993399.3      13580355.5
      1992809.03     13581787.79      1994440.49     13583983.33
#Sta/Elev= 30
  2539.4  621.57  2742.6   620.9  2828.3  621.98  2961.9  619.21  3030.5  619.03
  3357.9  617.96    3437  618.04  3662.7  615.26    3789  611.02  3984.6   608.7
 4158.32604.5164  4175.1  604.36  4532.6  600.34  4761.9  602.91  4851.4  598.96
    4873  601.04  4919.7  597.66  4943.7  599.74  4981.1  598.43  4981.7  591.94
  4987.4  590.94  5012.2  591.94  5013.6  599.08  5026.3  600.69 6425.57604.5164
  7802.3  607.17  7937.8  609.37  8072.6  609.94  8403.1  612.96  8941.7  623.41
#Mann= 14 ,-1 , 0
  2539.4      .1       0  2742.6     .05       0  2961.9      .1       0
  3030.5     .05       0  3357.9      .1       0    3437     .05       0
    3789      .1       0  3984.6     .05       0  4175.1      .1       0
  4761.9     .12       0  4981.7    .035       0  5012.2     .12       0
  7937.8      .1       0  8072.6     .05       0
Bank Sta=4158.32,6425.57
XS Rating Curve= 0 ,0
Exp/Cntr=0.3,0.1

Type RM Length L Ch R = 1 ,2869    ,365,365,365
BEGIN DESCRIPTION:
CHACON CREEK 4.0
END DESCRIPTION:
XS GIS Cut Line= 4
        1993375.     13579125.02      1993304.37     13579812.26
      1992151.59     13581458.09      1994462.31     13584130.99
#Sta/Elev= 30
    3709  625.67  4268.5  613.11 4583.48604.0715    4724   601.5  4759.7  596.57
  4774.6  601.13  4840.2  600.66  4947.2   600.9  4982.9  596.82  4988.6  591.65
  4994.2  590.65  5019.1  591.65  5025.9  599.56  5072.9  601.19 6886.98604.0714
  7139.8  607.35  7395.3  607.41  7465.6  604.81  8032.7  605.93  8089.7  607.77
  8132.4  615.31    8161  609.36  8429.7  609.31  8465.9  616.27  8515.2  608.04
  8539.5  607.26  8661.6  606.81  8673.4  606.84  9126.2   609.4  9942.5  623.35
#Mann= 10 ,-1 , 0
    3709     .05       0  4268.5      .1       0  4840.2     .12       0
  4988.6     .07       0  5019.1     .12       0  5072.9     .05       0
  8539.5     .08       0  8661.6     .05       0  8673.4      .1       0
  9126.2     .05       0
Bank Sta=4583.48,6886.98
XS Rating Curve= 0 ,0
Exp/Cntr=0.3,0.1

Type RM Length L Ch R = 1 ,2504    ,312,312,312
BEGIN DESCRIPTION:
Mapping XS c8f951f2
END DESCRIPTION:
XS GIS Cut Line= 3
      1993255.76      13579448.8      1991776.59     13581141.51
      1989573.46      13582318.6
#Sta/Elev= 30
  4234.1  618.87  4401.7  615.85  4415.8  616.64  4437.7  614.85  4704.3  606.76
 4810.83603.4345  4907.4  600.14  4969.2  598.33  4983.4  596.15  4989.1  592.03
  4994.7  591.03  5019.6  592.03  5025.9  598.24  5039.4   601.1    5047  601.18
  5082.2  600.28    7272  602.21  7379.5  600.22  7388.3  599.45  7415.9  593.06
  7432.2  598.46  7454.1  600.83  7481.7  604.01  7563.8  604.92  7580.1   603.9
  7707.8   604.2  8067.9  601.86  8198.5603.4345  8511.8  611.83  8979.9  617.68
#Mann= 8 ,-1 , 0
  4234.1     .05       0  4704.3      .1       0  4907.4     .12       0
  4989.1     .07       0  5019.6     .12       0    7272     .16       0
  7454.1      .1       0  7707.8     .05       0
Bank Sta=4810.83,8198.5
XS Rating Curve= 0 ,0
Exp/Cntr=0.3,0.1

Type RM Length L Ch R = 1 ,2192    ,341,341,341
BEGIN DESCRIPTION:
CHACON CREEK 3.0
END DESCRIPTION:
XS GIS Cut Line= 3
        1993525.       13578925.        1992525.       13579825.
      1989959.44     13581995.21
#Sta/Elev= 30
  3687.4   629.8  4126.5  624.27  4515.9  615.77  4690.8  608.87  4727.3   607.4
 4837.38602.8048  4968.9  599.78  4975.3   590.9  4980.9   589.9  5005.8   590.9
  5011.5  597.28  5103.8  601.25  5267.8  599.69  6588.9  600.79  6590.8   600.8
  6863.8  600.99  6884.6  599.13  6905.8  592.49  6941.8  598.64  6970.3  600.41
  7066.8  601.97 8056.34602.8049    8091  603.97  8126.1  609.54  8133.9  613.01
  8162.4  614.47    8169  612.56  8197.6  614.22  8232.7  610.64  8393.1  613.61
#Mann= 10 ,-1 , 0
  3687.4     .05       0  4690.8      .1       0  4727.3     .12       0
  4975.3     .07       0  5005.8     .12       0  5103.8      .1       0
  5267.8     .05       0  6588.9     .16       0  6590.8      .1       0
  7066.8     .05       0
Bank Sta=4837.38,8056.34
XS Rating Curve= 0 ,0
Exp/Cntr=0.3,0.1

Type RM Length L Ch R = 1 ,1851    ,375,375,375
BEGIN DESCRIPTION:
Mapping XS 9cfdfc82
END DESCRIPTION:
XS GIS Cut Line= 3
      1992859.93     13579287.33      1991250.55      13580261.3
      1989740.11      13581745.7
#Sta/Elev= 30
  4423.2  617.46  4656.5  610.58  4773.7  605.48 4866.28601.8415  4906.8  599.26
    4965  598.85  4978.3  596.91  4986.3  593.43  4986.5  590.84  4992.1  589.84
    5017  590.84  5023.2  596.35    5029  597.51  5071.8   601.3  5095.9  600.22
  5594.2  600.97  5758.3  599.37  6438.2  600.32  6558.4  600.01  6580.5  597.43
  6607.8  592.12    6622  594.31  6629.1  598.76  6636.1  600.62  6680.8  601.69
 7832.48601.8416  7979.8  602.88  8149.4  614.24  8312.1  615.28  8422.1  618.18
#Mann= 10 ,-1 , 0
  4423.2     .05       0  4656.5      .1       0  4773.7     .12       0
  4986.5     .07       0    5017     .12       0  5095.9      .1       0
  5594.2     .05       0  6438.2     .16       0  6580.5     .07       0
  6680.8     .05       0
Bank Sta=4866.28,7832.48
XS Rating Curve= 0 ,0
Exp/Cntr=0.3,0.1

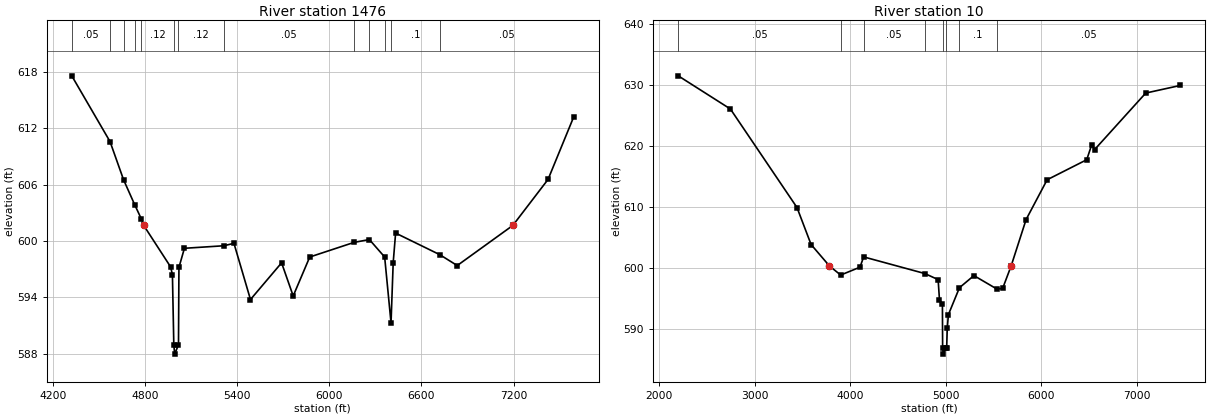
Type RM Length L Ch R = 1 ,1476    ,1466,1466,1466
BEGIN DESCRIPTION:
Mapping XS f23cf950
END DESCRIPTION:
XS GIS Cut Line= 3
      1992792.25     13579037.33      1991224.51     13579667.55
      1989658.41     13579865.26
#Sta/Elev= 30
  4324.2  617.61  4573.3   610.6  4661.2  606.54  4734.7  603.84  4777.6  602.34
 4792.69601.6653  4967.9  597.24  4979.4  596.41  4988.4  588.95    4994  587.95
  5018.9  588.95  5021.8  597.19  5057.4  599.23  5314.5   599.5  5379.9  599.76
  5487.4  593.77    5690  597.68  5765.5  594.15  5873.2   598.3  6161.9  599.86
  6261.4  600.16  6360.9   598.3  6402.4  591.28  6416.5  597.71  6432.2  600.85
  6719.7  598.55  6833.3  597.39 7195.24601.6656  7424.5  606.57  7592.4  613.27
#Mann= 13 ,-1 , 0
  4324.2     .05       0  4573.3      .1       0  4661.2     .05       0
  4734.7      .1       0  4777.6     .12       0  4988.4     .07       0
  5018.9     .12       0  5314.5     .05       0  6161.9      .1       0
  6261.4     .12       0  6360.9     .07       0  6402.4      .1       0
  6719.7     .05       0
Bank Sta=4792.69,7195.24
XS Rating Curve= 0 ,0
Exp/Cntr=0.3,0.1

Type RM Length L Ch R = 1 ,10      ,0,0,0
BEGIN DESCRIPTION:
CHACON CREEK 2.0
END DESCRIPTION:
XS GIS Cut Line= 6
      1993700.24       13578700.      1991942.33     13578994.85
      1990974.49     13579157.21      1990930.99      13579166.7
      1990871.47      13579180.4      1988569.13      13579796.2
#Sta/Elev= 30
  2201.7  631.51  2747.6  626.06  3444.1  609.88  3591.6   603.8 3783.15600.2899
  3901.2  598.79  4103.1  600.08  4141.5  601.77  4780.6  599.04  4920.7  598.04
  4934.6  594.76  4965.5  594.08  4967.8   586.8  4975.1   585.8  5003.2   586.8
  5010.1  586.85  5016.2  590.06  5028.2  592.29  5143.7  596.71  5295.2   598.7
  5534.5   596.5  5595.4  596.58 5684.64600.2897  5841.1  607.91  6061.2  614.44
  6475.3  617.73    6527  620.17  6558.1   619.4  7092.7  628.68  7454.4  629.93
#Mann= 8 ,-1 , 0
  2201.7     .05       0  3901.2     .12       0  4141.5     .05       0
  4780.6     .12       0  4967.8     .07       0  5003.2     .12       0
  5143.7      .1       0  5534.5     .05       0
Bank Sta=3783.15,5684.64
XS Rating Curve= 0 ,0
Exp/Cntr=0.3,0.1
LCMann Table=0

Chan Stop Cuts=-1
Use User Specified Reach Order=0
Composite Channel Slope=5