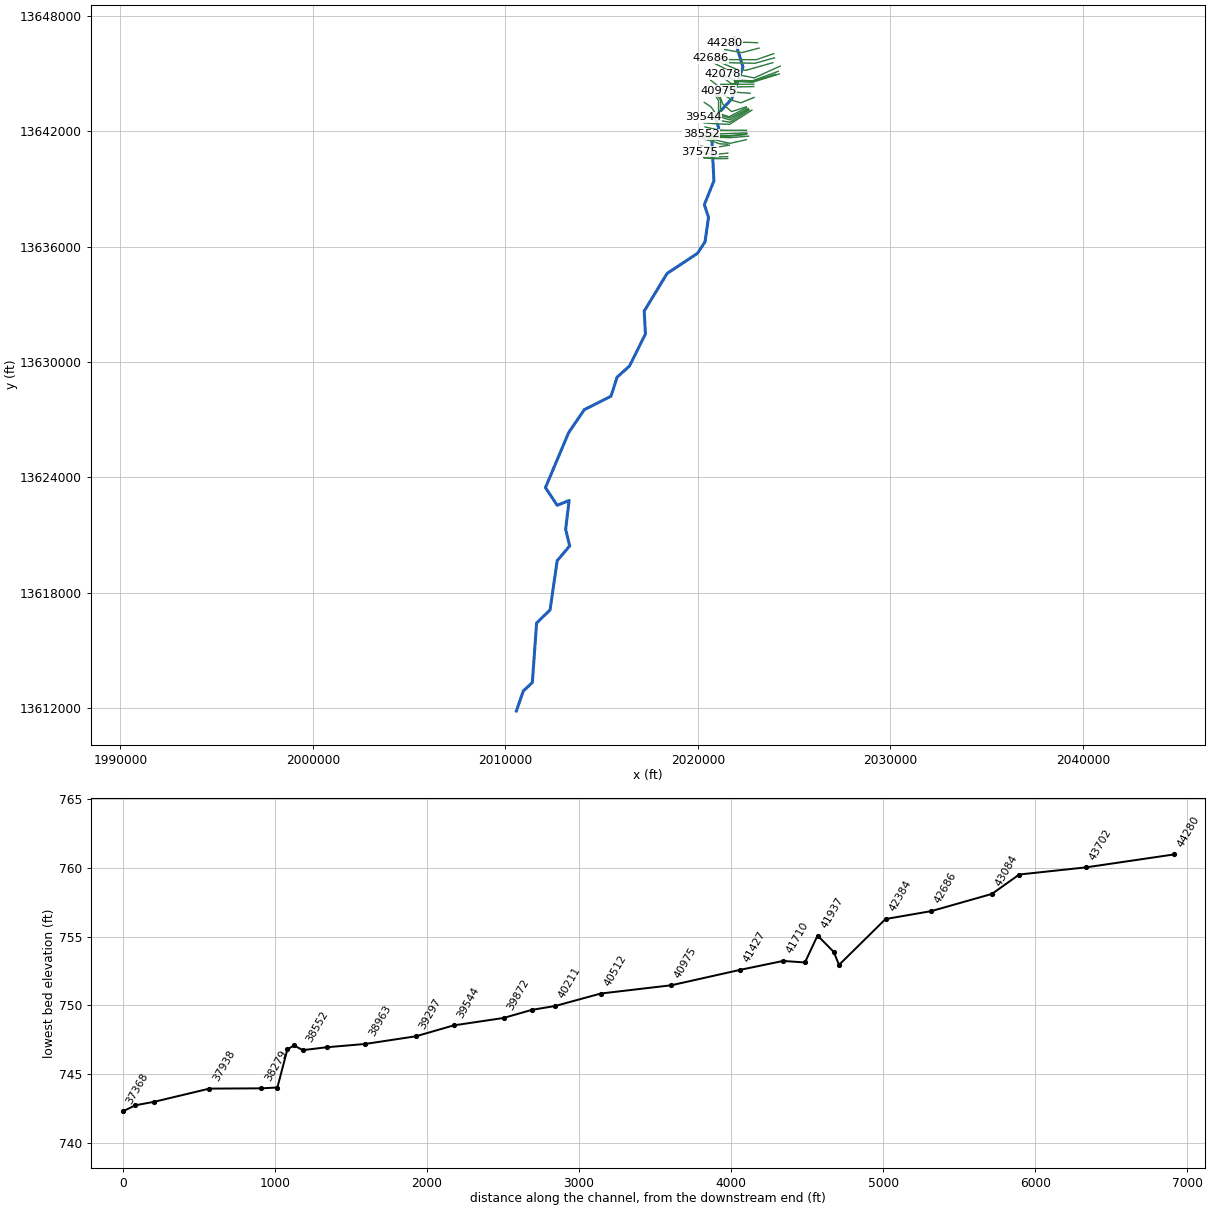
--- FORT EWELL CREEK.prj (project) ---

Proj Title=FORT EWELL CREEK Base Level Engineering
Current Plan=p01
Default Exp/Contr=0.3,0.1
English Units
Geom File=g01
Flow File=f01
Plan File=p01
Y Axis Title=Elevation
X Axis Title(PF)=Main Channel Distance
X Axis Title(XS)=Station
BEGIN DESCRIPTION:
FORT EWELL CREEK
END DESCRIPTION:
DSS Export Rating Curves= 0
DSS Export Rating Curve Sorted= 0
DSS Export Volume Flow Curves= 0
DXF OffsetX= 0
DXF OffsetY= 0
DXF ScaleX= 1
DXF ScaleY= 10

--- FORT EWELL CREEK.p01 (plan) ---

Plan Title=Multiple Run
Short Identifier=Multiple
Geom File=g01
Flow File=f01
Subcritical Flow
K Sum by GR= 0
Std Step Tol= 0.01
Critical Tol= 0.01
Num of Std Step Trials= 20
Max Error Tol= 0.3
Flow Tol Ratio= 0.001
Split Flow NTrial= 30
Split Flow Tol= 0.02
Split Flow Ratio= 0.02
Log Output Level= 0
Friction Slope Method= 1
Unsteady Friction Slope Method= 2
Unsteady Bridges Friction Slope Method= 1
Parabolic Critical Depth
Global Vel Dist=  1 , 1 , 1
Global Log Level= 0
CheckData=True
Encroach Param= -1, 0, 0, 0
BEGIN DESCRIPTION:
Multiple Run
END DESCRIPTION:

--- FORT EWELL CREEK.f01 (steady flow) ---

Flow Title=Multiple
Program Version=5.05
Number of Profiles= 7
Profile Names=10-year,25-year,50-year,1pct_min,100-year,1pct_plu,500-year
River Rch & RM=FORT EWELL CREEK,Reach-1         ,44280
     601     844    1047     644    1284    2562    1937
River Rch & RM=FORT EWELL CREEK,Reach-1         ,43263
     718    1015    1264     779    1554    3101    2358
River Rch & RM=FORT EWELL CREEK,Reach-1         ,40058
    1147    1656    2091    1304    2601    5190    4042
River Rch & RM=FORT EWELL CREEK,Reach-1         ,34717
    1035    1449    1790    1089    2173    4336    3218
River Rch & RM=FORT EWELL CREEK,Reach-1         ,34338
    1035    1449    1790    1089    2173    4336    3218
River Rch & RM=FORT EWELL CREEK,Reach-1         ,31915
    1220    1726    2147    1316    2625    5237    3942
River Rch & RM=FORT EWELL CREEK,Reach-1         ,28853
    2779    4190    5448    3490    6963   13892   11426
River Rch & RM=FORT EWELL CREEK,Reach-1         ,25799
    2961    4470    5818    3729    7441   14846   12228
River Rch & RM=FORT EWELL CREEK,Reach-1         ,24156
    3173    4796    6245    4004    7989   15939   13135
River Rch & RM=FORT EWELL CREEK,Reach-1         ,19737
    3293    4964    6450    4126    8232   16424   13469
River Rch & RM=FORT EWELL CREEK,Reach-1         ,7243
    3701    5599    7295    4676    9330   18615   15333
Boundary for River Rch & Prof#=FORT EWELL CREEK,Reach-1         , 1
Up Type= 0
Dn Type= 3
Dn Slope=0.00029
Boundary for River Rch & Prof#=FORT EWELL CREEK,Reach-1         , 2
Up Type= 0
Dn Type= 3
Dn Slope=0.00029
Boundary for River Rch & Prof#=FORT EWELL CREEK,Reach-1         , 3
Up Type= 0
Dn Type= 3
Dn Slope=0.00029
Boundary for River Rch & Prof#=FORT EWELL CREEK,Reach-1         , 4
Up Type= 0
Dn Type= 3
Dn Slope=0.00029
Boundary for River Rch & Prof#=FORT EWELL CREEK,Reach-1         , 5
Up Type= 0
Dn Type= 3
Dn Slope=0.00029
Boundary for River Rch & Prof#=FORT EWELL CREEK,Reach-1         , 6
Up Type= 0
Dn Type= 3
Dn Slope=0.00029
Boundary for River Rch & Prof#=FORT EWELL CREEK,Reach-1         , 7
Up Type= 0
Dn Type= 3
Dn Slope=0.00029
DSS Import GetInterval= 0
DSS Import GetPeak= 0
DSS Import FillOption= 0

--- FORT EWELL CREEK.g01 (geometry) ---

Geom Title=Existing Conditions
Program Version=5.05

River Reach=FORT EWELL CREEK,Reach-1
Reach XY= 30
       2021880.8     13646824.54       2022340.8     13645334.54
       2021760.8     13643674.54      2020893.77     13642734.94
      2021086.48     13642152.91       2020730.8      13641437.2
       2020831.7     13639411.16      2020335.39     13638176.13
      2020551.32     13637518.58       2020370.8     13636244.54
      2019976.45     13635645.53      2018401.31     13634601.49
       2017210.8     13632644.54      2017274.65     13631458.39
       2016450.8     13629794.54      2015801.23     13629208.25
      2015486.34     13628221.84       2014100.8     13627524.54
      2013285.46     13626329.45      2012081.47     13623473.55
       2012690.8     13622554.54       2013310.8     13622804.54
       2013130.8     13621304.54       2013340.8     13620444.54
       2012690.8     13619674.54       2012320.8     13617114.54
       2011620.8     13616434.54       2011400.8     13613344.54
       2010930.8     13612904.54       2010570.8     13611864.54

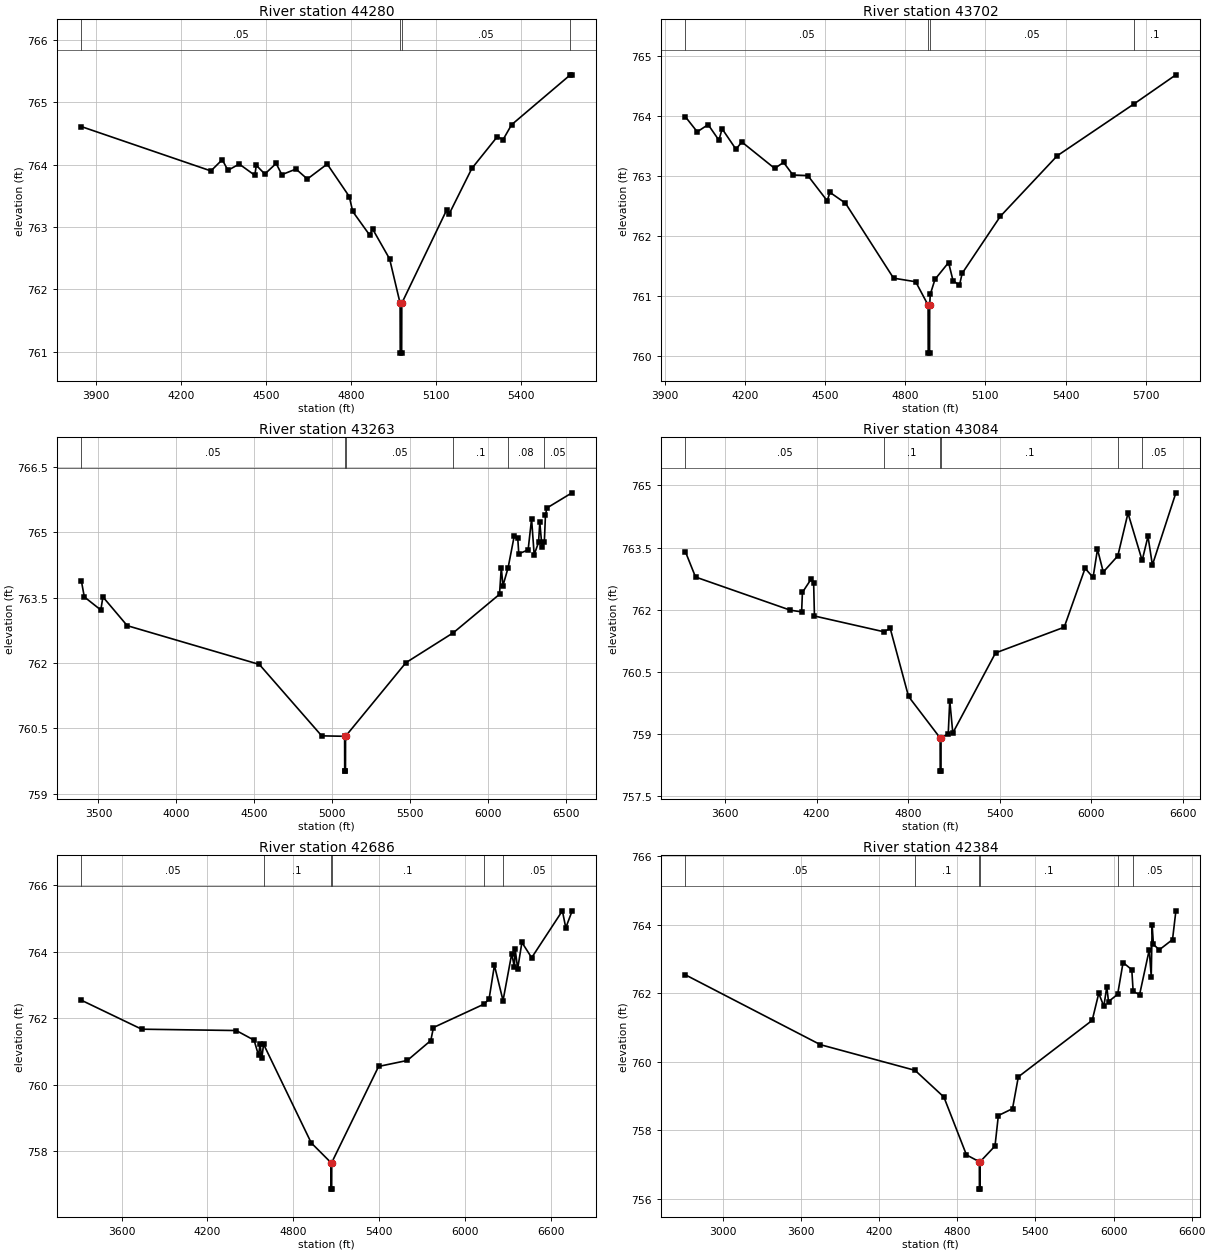
Type RM Length L Ch R = 1 ,44280   ,578,578,578
BEGIN DESCRIPTION:
FORT EWELL CREEK 55.0
END DESCRIPTION:
XS GIS Cut Line= 3
      2023101.35     13646590.61      2022538.85     13646611.44
      2021372.15     13646576.72
#Sta/Elev= 30
  3848.8  764.61  4305.5   763.9  4345.5  764.08  4365.5  763.91  4405.5  764.01
  4460.3  763.83  4465.6  763.99  4495.6  763.85  4535.6  764.02  4555.6  763.84
  4605.6  763.93  4645.6  763.77  4715.7  764.01  4793.5  763.49  4805.7  763.25
  4865.7  762.87  4875.7  762.97  4935.8  762.49  4972.8  761.78  4973.3  760.98
  4978.3  760.98  4978.8  761.78  5136.6  763.27  5145.9  763.21  5225.9  763.94
  5315.9  764.45  5335.9   764.4    5366  764.64  5573.3  765.44  5578.9  765.44
#Mann= 4 ,-1 , 0
  3848.8     .05       0  4972.8    .035       0  4978.8     .05       0
  5573.3      .1       0
Bank Sta=4972.8,4978.8
XS Rating Curve= 0 ,0
Exp/Cntr=0.3,0.1

Type RM Length L Ch R = 1 ,43702   ,439,439,439
BEGIN DESCRIPTION:
FORT EWELL CREEK 54.0
END DESCRIPTION:
XS GIS Cut Line= 3
      2023177.74     13646312.83      2022281.91     13646076.72
      2021388.03     13646236.09
#Sta/Elev= 30
  3978.1  763.98  4022.3  763.73  4063.1  763.85  4103.4  763.59  4115.4  763.78
  4167.1  763.44  4189.2  763.56  4311.9  763.12  4345.2  763.22  4380.3  763.01
    4436     763  4508.3  762.58  4518.7  762.72  4576.7  762.54  4756.5  761.29
  4839.3  761.23  4885.7  760.84  4886.2  760.04  4891.2  760.04  4891.7  760.84
  4893.9  761.02  4911.5  761.27  4962.3  761.55  4978.9  761.25    5003  761.17
  5013.1  761.37  5155.8  762.32  5368.6  763.33  5657.5   764.2  5812.5  764.68
#Mann= 4 ,-1 , 0
  3978.1     .05       0  4885.7    .035       0  4891.7     .05       0
  5657.5      .1       0
Bank Sta=4885.7,4891.7
XS Rating Curve= 0 ,0
Exp/Cntr=0.3,0.1

Type RM Length L Ch R = 1 ,43263   ,179,179,179
BEGIN DESCRIPTION:
Mapping XS 3abf346f
END DESCRIPTION:
XS GIS Cut Line= 4
      2023942.41     13646024.23      2023030.94     13645708.94
      2021499.65     13645713.53      2020921.55     13646008.58
#Sta/Elev= 30
    3391  763.88  3409.4  763.52  3515.2  763.22  3528.7  763.52  3684.5  762.86
  4531.4  761.97  4931.4  760.33  5078.4  760.32  5078.9  759.52  5083.9  759.52
  5084.4  760.32  5471.4  762.01  5776.4   762.7  6071.5  763.58  6082.8  764.19
  6093.7  763.78  6126.6  764.19    6166  764.92  6188.2  764.88  6195.1  764.51
  6254.9   764.6  6277.1  765.31  6293.7  764.49  6321.6  764.77  6329.8  765.23
  6343.8  764.67  6358.9  764.78    6366  765.39  6374.7  765.56  6535.8  765.91
#Mann= 6 ,-1 , 0
    3391     .05       0  5078.4    .035       0  5084.4     .05       0
  5776.4      .1       0  6126.6     .08       0  6358.9     .05       0
Bank Sta=5078.4,5084.4
XS Rating Curve= 0 ,0
Exp/Cntr=0.3,0.1

Type RM Length L Ch R = 1 ,43084   ,398,398,398
BEGIN DESCRIPTION:
Mapping XS f6550461
END DESCRIPTION:
XS GIS Cut Line= 4
      2023978.86     13645805.47      2022968.22     13645524.32
      2021499.59     13645551.35      2020890.29     13645888.79
#Sta/Elev= 30
  3340.8   763.4  3407.1  762.79  4028.7  761.99  4102.4  761.95  4107.6  762.42
  4164.8  762.74  4181.2  762.65  4186.4  761.85  4641.6  761.47  4683.1  761.55
  4803.1  759.91  5010.1  758.91  5010.6  758.11  5015.6  758.11  5016.1  758.91
  5063.2  759.01  5073.2  759.81  5093.2  759.03  5373.2  760.96  5823.3  761.58
  5960.1     763  6012.5  762.78  6041.4  763.46  6079.2  762.91  6174.6   763.3
  6241.2  764.33  6334.1  763.19  6372.3  763.77  6401.2  763.08  6555.2  764.82
#Mann= 6 ,-1 , 0
  3340.8     .05       0  4641.6      .1       0  5010.1     .07       0
  5016.1      .1       0  6174.6     .08       0  6334.1     .05       0
Bank Sta=5010.1,5016.1
XS Rating Curve= 0 ,0
Exp/Cntr=0.3,0.1

Type RM Length L Ch R = 1 ,42686   ,302,302,302
BEGIN DESCRIPTION:
Mapping XS 88611ad3
END DESCRIPTION:
XS GIS Cut Line= 4
      2023895.53     13645555.47      2022498.92     13645156.58
       2022086.6     13645178.28      2020645.52     13645784.62
#Sta/Elev= 30
  3319.1  762.54  3740.2  761.67  4401.2  761.63    4526  761.34  4557.2  760.88
  4567.6  761.22  4580.1  760.79  4592.2  761.22  4925.7  758.25  5062.8  757.66
  5063.3  756.86  5068.4  756.86  5068.9  757.66  5396.5  760.55  5597.2  760.73
  5761.4  761.33  5779.7  761.72  6131.2  762.42  6168.4  762.57    6206  763.59
  6266.3  762.53  6327.1  763.94  6345.4  763.54  6350.8  764.08  6368.7  763.49
  6398.3  764.28  6466.4  763.82  6681.2  765.23  6704.9  764.72  6747.9  765.21
#Mann= 6 ,-1 , 0
  3319.1     .05       0  4592.2      .1       0  5062.8     .07       0
  5068.9      .1       0  6131.2     .08       0  6266.3     .05       0
Bank Sta=5062.8,5068.9
XS Rating Curve= 0 ,0
Exp/Cntr=0.3,0.1

Type RM Length L Ch R = 1 ,42384   ,306,306,306
BEGIN DESCRIPTION:
Mapping XS 13721f02
END DESCRIPTION:
XS GIS Cut Line= 4
      2024275.66     13645378.36      2022919.92     13644761.12
      2021993.71     13644951.72      2020801.77     13645545.03
#Sta/Elev= 30
  2712.3  762.54  3748.7   760.5  4475.8  759.75  4697.3  758.97  4870.6  757.28
  4969.6  757.08  4970.1  756.28  4975.2  756.28  4975.7  757.08  5089.8  757.54
  5115.6  758.43  5224.3  758.63    5269  759.56  5836.2  761.21  5886.6     762
  5925.8  761.62  5948.2  762.19  5961.6  761.76  6031.6  761.97  6073.3   762.9
  6140.3  762.69  6150.7  762.06  6200.1  761.96  6274.3  763.27  6289.6  762.49
  6296.7  763.99  6306.4  763.43  6351.2  763.27  6453.1  763.57    6479  764.41
#Mann= 6 ,-1 , 0
  2712.3     .05       0  4475.8      .1       0  4969.6     .07       0
  4975.7      .1       0  6031.6     .08       0  6150.7     .05       0
Bank Sta=4969.6,4975.7
XS Rating Curve= 0 ,0
Exp/Cntr=0.3,0.1

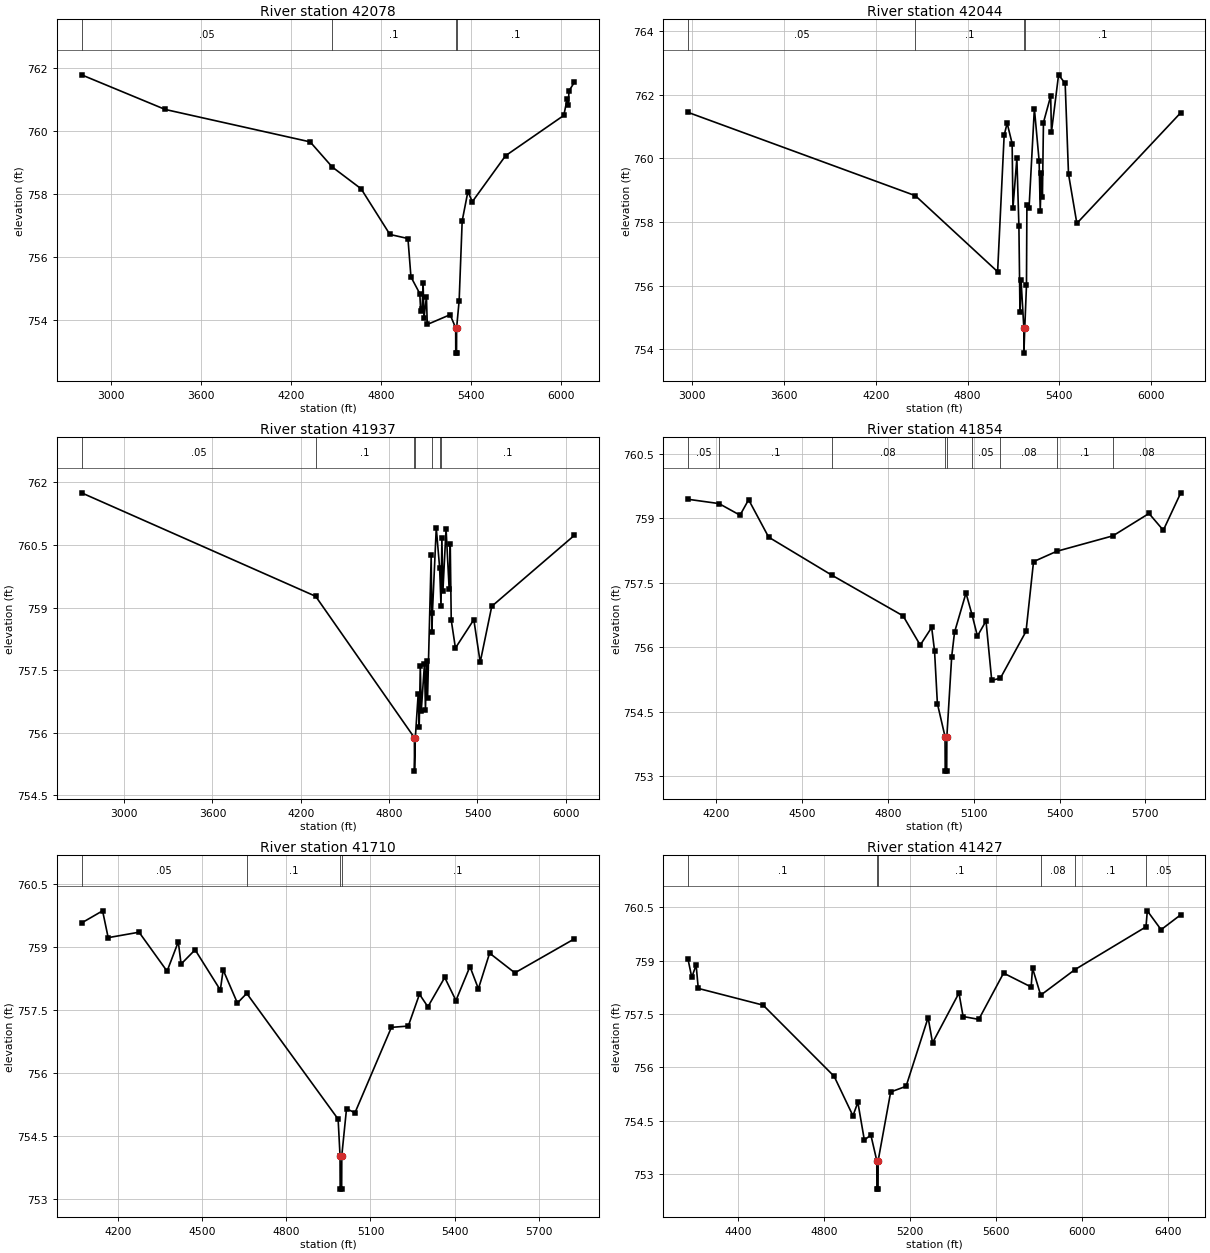
Type RM Length L Ch R = 1 ,42078   ,34,34,34
BEGIN DESCRIPTION:
Mapping XS 3bad11b4
END DESCRIPTION:
XS GIS Cut Line= 6
      2024176.73     13645107.54      2022837.92     13644611.37
      2022024.96     13644646.16      2021952.05     13644528.11
      2021938.16     13644670.47       2021261.1     13644944.76
#Sta/Elev= 30
  2807.1  761.78  3363.5  760.68  4327.9  759.65  4475.3  758.85  4666.9  758.16
  4858.4  756.71  4978.5  756.58  4998.5  755.36  5057.4  754.83  5063.1  754.28
  5072.5  754.34  5079.4  755.16  5085.1  754.05  5101.5  754.73  5107.1  753.85
  5259.1  754.16  5296.1  753.74  5296.6  752.94  5301.8  752.94  5302.3  753.74
  5319.2  754.61  5339.3  757.14  5377.3  758.07  5406.8  757.75  5627.9  759.21
  6015.2  760.49  6037.9  761.01  6044.7  760.82    6050  761.27  6085.3  761.54
#Mann= 4 ,-1 , 0
  2807.1     .05       0  4475.3      .1       0  5296.1     .07       0
  5302.3      .1       0
Bank Sta=5296.1,5302.3
XS Rating Curve= 0 ,0
Exp/Cntr=0.3,0.1

Type RM Length L Ch R = 1 ,42044   ,107,107,107
BEGIN DESCRIPTION:
Mapping XS 65d89609
END DESCRIPTION:
XS GIS Cut Line= 6
      2024041.37     13644956.52      2022848.86     13644582.96
      2022038.85     13644611.44      2021913.85     13644469.08
      2021899.96     13644656.58      2021205.52     13644923.94
#Sta/Elev= 30
    2972  761.45  4458.3  758.83  4996.1  756.44  5038.9  760.73  5058.4  761.11
  5091.1  760.47  5096.3  758.44    5122  760.01  5135.3  757.87  5142.3  755.16
  5149.4  756.17  5167.5  754.68    5168  753.88  5173.7  754.68  5184.8  756.01
  5187.6  758.53  5201.5  758.43  5236.4  761.57  5267.4  759.93  5274.8  758.35
  5281.6  759.55    5289  758.79  5295.8  761.13    5343  761.96  5348.1  760.83
  5394.6  762.63  5437.7  762.36  5459.6  759.51  5514.2  757.96  6193.6  761.44
#Mann= 4 ,-1 , 0
    2972     .05       0  4458.3      .1       0  5167.5     .07       0
  5173.7      .1       0
Bank Sta=5167.5,5173.7
XS Rating Curve= 0 ,0
Exp/Cntr=0.3,0.1

Type RM Length L Ch R = 1 ,41937   ,83,83,83
BEGIN DESCRIPTION:
Mapping XS 68232596
END DESCRIPTION:
XS GIS Cut Line= 6
      2024223.64     13644966.93      2022828.34     13644533.83
      2022083.99     13644576.72      2021910.38     13644451.72
       2021695.1     13644486.44       2021178.9     13644884.85
#Sta/Elev= 30
  2710.6  761.75  4300.8  759.27  4971.6  755.88  4972.1  755.08  4977.9  755.88
  4997.4  756.94  5004.1  756.14  5011.6  757.59  5018.3  756.53    5040  757.65
  5046.7  756.55  5054.2  757.73  5060.9  756.84  5085.6  760.25  5090.6  758.41
  5093.9  758.87  5120.1  760.91  5142.8  759.96  5152.4  759.04  5158.3  760.67
  5165.1  759.39  5186.6  760.89  5207.6  759.45    5215  760.53  5221.8   758.7
  5250.2  758.03  5375.2  758.71  5418.5  757.69    5497  759.03  6057.8  760.73
#Mann= 7 ,-1 , 0
  2710.6     .05       0  4300.8      .1       0  4971.6     .07       0
  4977.9      .1       0  5093.9     .08       0  5142.8     .05       0
  5152.4      .1       0
Bank Sta=4971.6,4977.9
XS Rating Curve= 0 ,0
Exp/Cntr=0.3,0.1

Type RM Length L Ch R = 1 ,41854   ,144,144,144
BEGIN DESCRIPTION:
Mapping XS c0bda877
END DESCRIPTION:
XS GIS Cut Line= 2
      2022906.95     13644436.09      2021183.87     13644427.41
#Sta/Elev= 30
  4100.9  759.44  4209.2  759.34  4282.8  759.07  4312.8  759.43  4382.8  758.56
  4602.7  757.68  4852.9  756.73  4912.9  756.05  4952.9  756.46  4962.9  755.92
  4972.9  754.69  4999.7  753.92  5000.2  753.12  5005.5  753.12    5006  753.92
  5022.9  755.78  5032.9  756.35  5072.9  757.26  5094.7  756.74  5112.9  756.26
  5142.9  756.61  5162.9  755.23  5193.1  755.28  5282.9  756.37  5309.1  757.99
  5389.9  758.23  5586.7  758.59  5712.9  759.11  5762.9  758.72    5824  759.59
#Mann= 9 ,-1 , 0
  4100.9     .05       0  4209.2      .1       0  4602.7     .08       0
  4999.7     .07       0    5006     .08       0  5094.7     .05       0
  5193.1     .08       0  5389.9      .1       0  5586.7     .08       0
Bank Sta=4999.7,5006
XS Rating Curve= 0 ,0
Exp/Cntr=0.3,0.1

Type RM Length L Ch R = 1 ,41710   ,283,283,283
BEGIN DESCRIPTION:
FORT EWELL CREEK 53.0
END DESCRIPTION:
XS GIS Cut Line= 3
        2022900.     13644312.83      2022004.13       13644292.
      2021143.04     13644326.72
#Sta/Elev= 30
  4069.2  759.58  4144.2  759.87  4164.2  759.23  4274.3  759.36  4374.3  758.43
  4414.3  759.13  4424.3   758.6  4474.3  758.94  4564.3  757.98  4574.3  758.46
  4625.2  757.67  4658.5   757.9  4984.5   754.9  4991.3  754.03  4991.8  753.23
  4997.1  753.23  4997.6  754.03  5014.5  755.15  5044.5  755.05  5174.6  757.09
  5234.7  757.12  5274.7  757.88  5304.7  757.58  5364.8  758.28  5404.8  757.73
  5454.8  758.54  5484.9  758.01  5524.9  758.86    5615  758.39  5827.1   759.2
#Mann= 4 ,-1 , 0
  4069.2     .05       0  4658.5      .1       0  4991.3     .07       0
  4997.6      .1       0
Bank Sta=4991.3,4997.6
XS Rating Curve= 0 ,0
Exp/Cntr=0.3,0.1

Type RM Length L Ch R = 1 ,41427   ,452,452,452
BEGIN DESCRIPTION:
FORT EWELL CREEK 52.0
END DESCRIPTION:
XS GIS Cut Line= 4
      2022712.46     13643965.61        2021875.       13644025.
        2021280.     13644155.69      2020620.73     13644678.74
#Sta/Elev= 30
  4167.9  759.04  4185.4  758.53  4205.5  758.88  4215.5  758.22    4517  757.75
  4847.1  755.75  4934.5  754.64  4957.3  755.02  4987.4  753.96  5017.7   754.1
  5045.3  753.38  5045.8  752.58  5051.1  752.58  5051.6  753.38  5109.8  755.31
  5181.5  755.47  5283.9   757.4  5304.4  756.69  5427.2  758.09  5446.4  757.43
  5519.4  757.35  5634.5  758.65  5762.7  758.26  5769.1  758.79  5807.1  758.03
  5966.6  758.75  6296.5  759.95  6302.6   760.4  6366.7  759.87  6458.2  760.29
#Mann= 6 ,-1 , 0
  4167.9      .1       0  5045.3     .07       0  5051.6      .1       0
  5807.1     .08       0  5966.6      .1       0  6296.5     .05       0
Bank Sta=5045.3,5051.6
XS Rating Curve= 0 ,0
Exp/Cntr=0.3,0.1

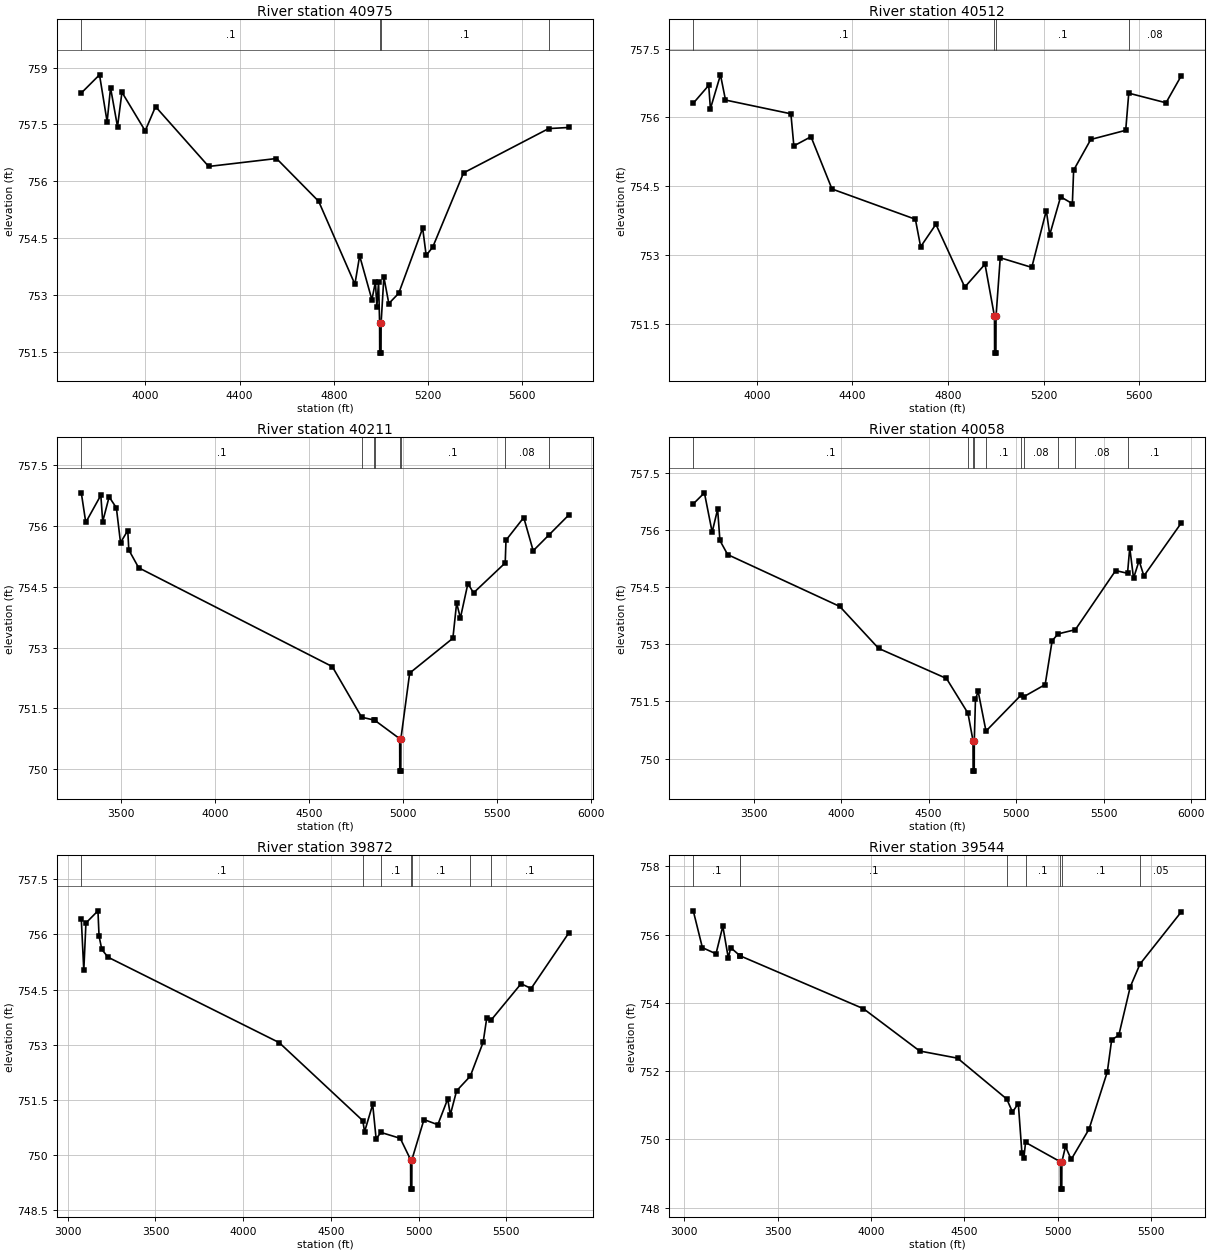
Type RM Length L Ch R = 1 ,40975   ,463,463,463
BEGIN DESCRIPTION:
Mapping XS 4e5dea67
END DESCRIPTION:
XS GIS Cut Line= 4
      2022916.72     13643745.55      2022225.59     13643468.41
      2021774.96     13643597.55      2021066.74     13644080.12
#Sta/Elev= 30
  3728.2  758.33  3805.5  758.81  3837.8  757.57  3852.3  758.47  3881.9  757.44
  3900.7  758.35  3999.4  757.33  4043.3  757.97  4268.8  756.39  4556.7   756.6
  4735.7  755.47  4889.5  753.28  4909.7  754.03  4961.7  752.87  4976.6  753.34
  4982.7  752.69    4990  753.34  4994.4  752.26  4994.9  751.46  5000.3  751.46
  5000.8  752.26  5012.5  753.47  5033.5  752.77  5075.5  753.04  5177.2  754.76
  5192.1  754.04  5219.9  754.26  5350.7  756.22  5711.9  757.39  5798.6  757.42
#Mann= 4 ,-1 , 0
  3728.2      .1       0  4994.4     .07       0  5000.8      .1       0
  5711.9     .08       0
Bank Sta=4994.4,5000.8
XS Rating Curve= 0 ,0
Exp/Cntr=0.3,0.1

Type RM Length L Ch R = 1 ,40512   ,301,301,301
BEGIN DESCRIPTION:
Mapping XS eea5b932
END DESCRIPTION:
XS GIS Cut Line= 4
      2022513.15     13643259.47      2021751.23      13643010.9
      2021302.74     13643389.22      2021066.62     13643996.87
#Sta/Elev= 30
  3734.4  756.31    3799   756.7  3806.1  756.19  3848.2  756.93  3869.2  756.38
  4142.7  756.08  4155.1  755.38  4226.8  755.58  4314.6  754.44  4663.4  753.78
  4685.4  753.18  4749.2  753.67  4870.1   752.3  4954.6   752.8  4994.3  751.66
  4994.8  750.86  5000.2  750.86  5000.7  751.66  5018.4  752.94  5150.2  752.73
  5211.1  753.97  5225.3  753.44  5270.9  754.27    5320  754.12  5325.3  754.85
    5397  755.52  5543.1  755.72  5555.9  756.53  5711.7  756.32  5774.5   756.9
#Mann= 4 ,-1 , 0
  3734.4      .1       0  4994.3     .07       0  5000.7      .1       0
  5555.9     .08       0
Bank Sta=4994.3,5000.7
XS Rating Curve= 0 ,0
Exp/Cntr=0.3,0.1

Type RM Length L Ch R = 1 ,40211   ,153,153,153
BEGIN DESCRIPTION:
Mapping XS 16cb8032
END DESCRIPTION:
XS GIS Cut Line= 5
       2022526.1     13643216.03      2021612.44     13642740.79
       2021170.8     13642892.69      2021181.21     13643601.02
       2020952.2     13643920.26
#Sta/Elev= 30
  3286.6  756.82  3310.4  756.09  3390.6  756.76  3400.6  756.11  3434.8  756.72
  3473.4  756.45  3495.5  755.59  3534.1  755.89  3539.7  755.41  3592.2  754.97
  4623.6  752.53  4780.2  751.28  4847.4  751.21  4851.3   751.2  4982.6  750.75
  4983.1  749.95  4988.5  749.95    4989  750.75  5035.8  752.37  5265.9  753.23
  5285.9   754.1  5305.9  753.73  5345.9  754.58  5375.9  754.35  5544.7  755.09
  5548.8  755.65  5643.4  756.21  5693.7  755.39  5775.4  755.77  5884.8  756.28
#Mann= 8 ,-1 , 0
  3286.6      .1       0  4780.2     .08       0  4847.4     .05       0
  4851.3      .1       0  4982.6     .07       0    4989      .1       0
  5544.7     .08       0  5775.4      .1       0
Bank Sta=4982.6,4989
XS Rating Curve= 0 ,0
Exp/Cntr=0.3,0.1

Type RM Length L Ch R = 1 ,40058   ,186,186,186
BEGIN DESCRIPTION:
Mapping XS 7e924a1e
END DESCRIPTION:
XS GIS Cut Line= 5
      2022608.58     13643168.29      2021662.55     13642678.32
       2021070.1     13642844.08      2021073.58      13643566.3
      2020883.49     13643901.55
#Sta/Elev= 30
  3154.5  756.68  3218.2  756.97  3262.5  755.94  3293.7  756.54  3306.8  755.72
    3351  755.35  3991.9  753.99  4213.9  752.89    4602   752.1  4724.7  751.19
  4753.6  750.47  4754.2  749.67  4760.5  749.67    4761  750.47  4767.7  751.56
  4783.1  751.76  4827.8  750.72  5027.2  751.66    5043  751.62    5166  751.94
    5206  753.09    5240  753.27  5338.5  753.38  5568.8  754.93  5636.9  754.86
  5649.6  755.53  5671.2  754.73    5703  755.19  5730.4  754.79  5942.7  756.17
#Mann= 10 ,-1 , 0
  3154.5      .1       0  4724.7     .08       0  4753.6     .07       0
    4761     .08       0  4827.8      .1       0  5027.2     .05       0
    5043     .08       0    5240     .05       0  5338.5     .08       0
  5636.9      .1       0
Bank Sta=4753.6,4761
XS Rating Curve= 0 ,0
Exp/Cntr=0.3,0.1

Type RM Length L Ch R = 1 ,39872   ,328,328,328
BEGIN DESCRIPTION:
Mapping XS 44a249b8
END DESCRIPTION:
XS GIS Cut Line= 5
      2022617.32     13643120.58      2021669.78       13642578.
      2021021.49     13642774.63      2020677.74     13643260.75
      2020330.56     13643489.89
#Sta/Elev= 30
  3077.2  756.41  3091.4  755.02  3103.6  756.31  3172.1  756.64  3178.4  755.95
  3194.2  755.59  3229.7  755.38  4205.3  753.06  4681.9  750.94  4692.1  750.64
  4738.4  751.38  4757.9  750.45  4785.7  750.62  4895.5  750.46  4954.5  749.88
    4955  749.08  4961.3  749.08  4961.9  749.88  5030.7  750.97  5109.6  750.83
  5166.2  751.53    5181   751.1  5216.7  751.75    5295  752.15  5368.1  753.07
    5389  753.74  5413.1  753.67  5584.4  754.66  5641.6  754.53  5857.9  756.05
#Mann= 7 ,-1 , 0
  3077.2      .1       0  4681.9     .08       0  4785.7      .1       0
  4954.5     .07       0  4961.9      .1       0    5295     .08       0
  5413.1      .1       0
Bank Sta=4954.5,4961.9
XS Rating Curve= 0 ,0
Exp/Cntr=0.3,0.1

Type RM Length L Ch R = 1 ,39544   ,247,247,247
BEGIN DESCRIPTION:
Mapping XS cba6e7e6
END DESCRIPTION:
XS GIS Cut Line= 4
      2022673.73     13643094.54      2021663.44     13642458.08
      2020750.66     13642614.91      2020269.06     13642718.86
#Sta/Elev= 30
  3048.3   756.7  3097.2  755.62  3170.1  755.44  3206.6  756.25  3235.9  755.32
    3249  755.62    3297  755.39  3299.6  755.38    3960  753.83  4261.1  752.59
    4464  752.38  4727.9  751.18  4758.2   750.8  4789.5  751.05    4809  749.59
  4819.1  749.44  4828.3  749.91  5015.4  749.34    5016  748.54  5022.3  748.54
  5022.9  749.34  5042.3  749.79  5072.8  749.41  5168.5   750.3  5266.4  751.98
  5289.7  752.92  5327.8  753.05  5389.1  754.47  5441.5  755.14  5661.2  756.66
#Mann= 8 ,-1 , 0
  3048.3      .1       0    3297     .05       0  3299.6      .1       0
  4727.9     .05       0  4828.3      .1       0  5015.4     .07       0
  5022.9      .1       0  5441.5     .05       0
Bank Sta=5015.4,5022.9
XS Rating Curve= 0 ,0
Exp/Cntr=0.3,0.1

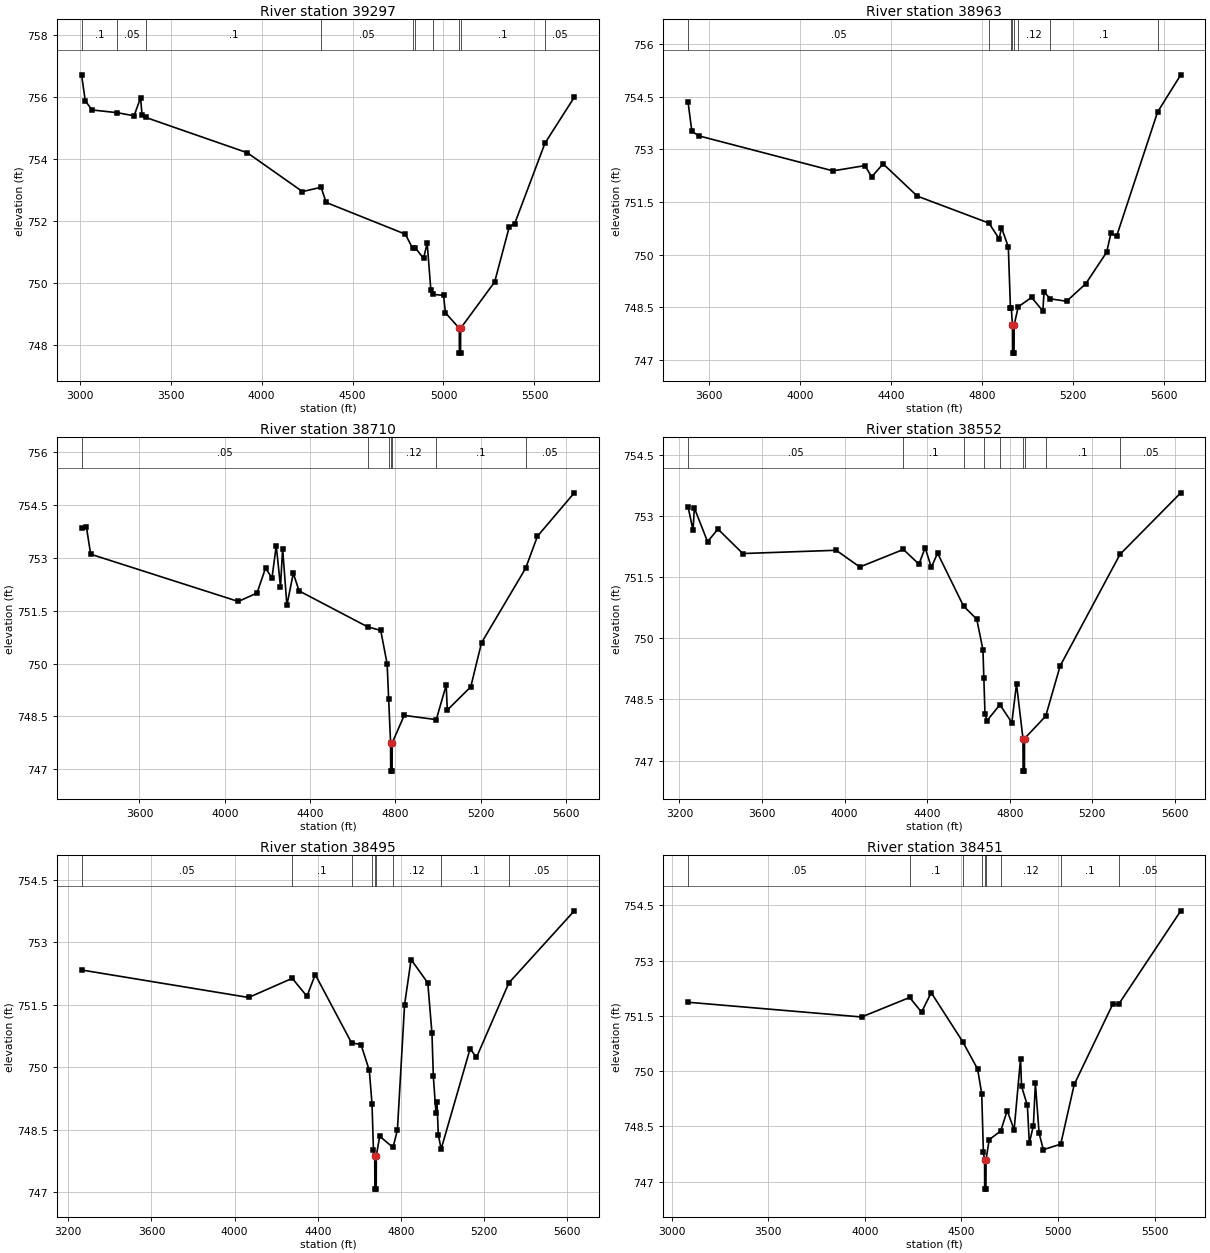
Type RM Length L Ch R = 1 ,39297   ,334,334,334
BEGIN DESCRIPTION:
FORT EWELL CREEK 51.0
END DESCRIPTION:
XS GIS Cut Line= 4
      2022808.27     13643090.19      2021649.17     13642350.37
        2020975.       13642375.      2020318.32     13642423.81
#Sta/Elev= 30
  3010.8  756.71  3031.1  755.88  3067.5  755.58  3208.1  755.49  3299.4  755.39
    3335  755.97  3343.3  755.41  3362.8  755.34  3922.1   754.2    4225  752.95
  4327.1  753.09  4355.3   752.6  4790.3  751.58  4829.7  751.13    4845  751.14
  4890.4   750.8  4910.4  751.29  4930.4  749.79  4943.6  749.64  5000.5  749.61
  5010.5  749.05  5086.8  748.55  5087.4  747.75  5093.7  747.75  5094.3  748.55
  5281.1  750.04  5361.3  751.81  5391.4  751.92  5557.8  754.51    5719  755.99
#Mann= 10 ,-1 , 0
  3010.8      .1       0  3208.1     .05       0  3362.8      .1       0
  4327.1     .05       0  4829.7      .1       0    4845     .08       0
  4943.6      .1       0  5086.8     .07       0  5094.3      .1       0
  5557.8     .05       0
Bank Sta=5086.8,5094.3
XS Rating Curve= 0 ,0
Exp/Cntr=0.3,0.1

Type RM Length L Ch R = 1 ,38963   ,253,253,253
BEGIN DESCRIPTION:
Mapping XS c66186de
END DESCRIPTION:
XS GIS Cut Line= 3
      2022521.82     13642039.84      2021101.35     13642048.94
      2020375.67     13642212.13
#Sta/Elev= 30
  3509.2  754.36    3526  753.52    3556  753.39    4146  752.39    4286  752.54
    4316  752.22    4366  752.59    4516  751.67  4830.8   750.9    4876  750.45
    4886  750.77    4916  750.22  4925.4  748.47  4929.2  748.47  4934.2  747.99
  4934.7  747.19  4941.1  747.19  4941.7  747.99  4959.4  748.51  5018.2  748.78
  5067.8  748.39  5072.9  748.94    5100  748.74    5172  748.67  5256.3  749.17
    5348  750.07  5366.7  750.61  5391.3  750.52  5571.7  754.07  5673.5  755.13
#Mann= 8 ,-1 , 0
  3509.2     .05       0  4830.8     .08       0  4929.2      .1       0
  4934.2     .07       0  4941.7      .1       0  4959.4     .12       0
    5100      .1       0  5571.7     .05       0
Bank Sta=4934.2,4941.7
XS Rating Curve= 0 ,0
Exp/Cntr=0.3,0.1

Type RM Length L Ch R = 1 ,38710   ,158,158,158
BEGIN DESCRIPTION:
Mapping XS 88f1e4cd
END DESCRIPTION:
XS GIS Cut Line= 3
      2022547.81     13641905.29      2020976.35     13641851.02
      2020243.73     13641951.72
#Sta/Elev= 30
  3328.2  753.83    3351  753.87    3371   753.1  4063.7  751.76  4151.5     752
  4191.5  752.71  4221.5  752.42  4241.6  753.34  4261.6  752.18  4271.6  753.26
  4291.6  751.65  4321.6  752.56  4348.7  752.06  4670.6  751.04  4731.8  750.94
  4761.9  749.99    4769     749  4778.1  747.75  4778.7  746.95  4785.1  746.95
  4785.7  747.75  4841.9  748.53  4992.4  748.41  5039.1  749.39  5044.1  748.68
  5154.3  749.34  5204.8  750.59  5411.6   752.7  5467.2  753.61  5640.1  754.84
#Mann= 7 ,-1 , 0
  3328.2     .05       0  4670.6     .08       0    4769     .12       0
  4778.1     .07       0  4785.7     .12       0  4992.4      .1       0
  5411.6     .05       0
Bank Sta=4778.1,4785.7
XS Rating Curve= 0 ,0
Exp/Cntr=0.3,0.1

Type RM Length L Ch R = 1 ,38552   ,57,57,57
BEGIN DESCRIPTION:
Mapping XS 1bd00980
END DESCRIPTION:
XS GIS Cut Line= 6
      2022539.17     13641853.21      2021627.69     13641761.52
      2020958.99     13641771.16       2020882.6     13641726.02
      2020827.05     13641726.02      2020178.86     13641836.94
#Sta/Elev= 30
  3241.4  753.23  3265.7  752.65  3272.1   753.2    3336  752.37  3386.3  752.68
  3506.9  752.08  3959.2  752.16  4073.7  751.75  4284.5  752.18  4360.2  751.82
  4390.2  752.22  4420.2  751.74  4450.2  752.09  4576.2  750.79  4640.2  750.47
  4670.2  749.72  4674.6  749.02  4680.2  748.13  4690.2  747.98  4752.4  748.37
  4810.2  747.93  4832.8  748.88  4864.1  747.54  4864.7  746.74  4871.1  746.74
  4871.7  747.54  4974.2  748.09  5044.1  749.32  5334.2  752.06  5628.6  753.57
#Mann= 9 ,-1 , 0
  3241.4     .05       0  4284.5      .1       0  4576.2     .08       0
  4674.6     .16       0  4752.4     .12       0  4864.1     .07       0
  4871.7     .12       0  4974.2      .1       0  5334.2     .05       0
Bank Sta=4864.1,4871.7
XS Rating Curve= 0 ,0
Exp/Cntr=0.3,0.1

Type RM Length L Ch R = 1 ,38495   ,44,44,44
BEGIN DESCRIPTION:
Mapping XS 63794743
END DESCRIPTION:
XS GIS Cut Line= 6
       2022504.4     13641822.82      2021636.42     13641729.13
      2021042.33     13641726.02      2020941.63     13641677.41
      2020827.05       13641667.      2020163.83     13641802.42
#Sta/Elev= 30
  3263.7  752.34  4067.7  751.68  4277.4  752.14  4348.1  751.71  4388.1  752.23
  4562.8  750.59  4608.2  750.55  4648.2  749.93  4661.2  749.13  4668.2  748.01
  4674.4  747.88    4675  747.08  4681.4  747.08    4682  747.88  4698.2  748.35
  4762.3  748.08  4783.4   748.5    4818  751.51  4849.3  752.59  4929.6  752.03
  4949.7  750.82  4956.2   749.8  4968.8  748.91  4973.9  749.17  4980.2  748.39
  4993.8  748.04  5133.3  750.45  5163.9  750.24  5319.7  752.03  5634.6  753.76
#Mann= 9 ,-1 , 0
  3263.7     .05       0  4277.4      .1       0  4562.8     .08       0
  4661.2     .16       0  4674.4     .07       0    4682     .16       0
  4762.3     .12       0  4993.8      .1       0  5319.7     .05       0
Bank Sta=4674.4,4682
XS Rating Curve= 0 ,0
Exp/Cntr=0.3,0.1

Type RM Length L Ch R = 1 ,38451   ,66,66,66
BEGIN DESCRIPTION:
Mapping XS f10228fe
END DESCRIPTION:
XS GIS Cut Line= 6
      2022630.35     13641736.02      2021701.48     13641657.79
      2021000.66     13641673.94      2021000.66     13641618.38
       2020920.8     13641597.55      2020160.41     13641767.68
#Sta/Elev= 30
  3085.3  751.87  3983.8  751.47  4232.6     752    4294   751.6    4344  752.13
    4507   750.8  4584.1  750.06  4605.5  749.39  4614.1   747.8  4620.3   747.6
  4620.9   746.8  4627.3   746.8  4627.9   747.6  4644.1  748.14    4704  748.38
  4737.4  748.93  4773.2  748.41  4806.5  750.34  4811.6  749.59  4841.8  749.07
  4851.8  748.05  4872.9  748.52  4883.2  749.67  4902.4  748.32  4924.5  747.87
  5014.4  748.02  5084.3  749.64  5283.1  751.81  5313.5  751.81  5635.8  754.35
#Mann= 9 ,-1 , 0
  3085.3     .05       0  4232.6      .1       0    4507     .08       0
  4605.5     .16       0  4620.3     .07       0  4627.9     .16       0
    4704     .12       0  5014.4      .1       0  5313.5     .05       0
Bank Sta=4620.3,4627.9
XS Rating Curve= 0 ,0
Exp/Cntr=0.3,0.1

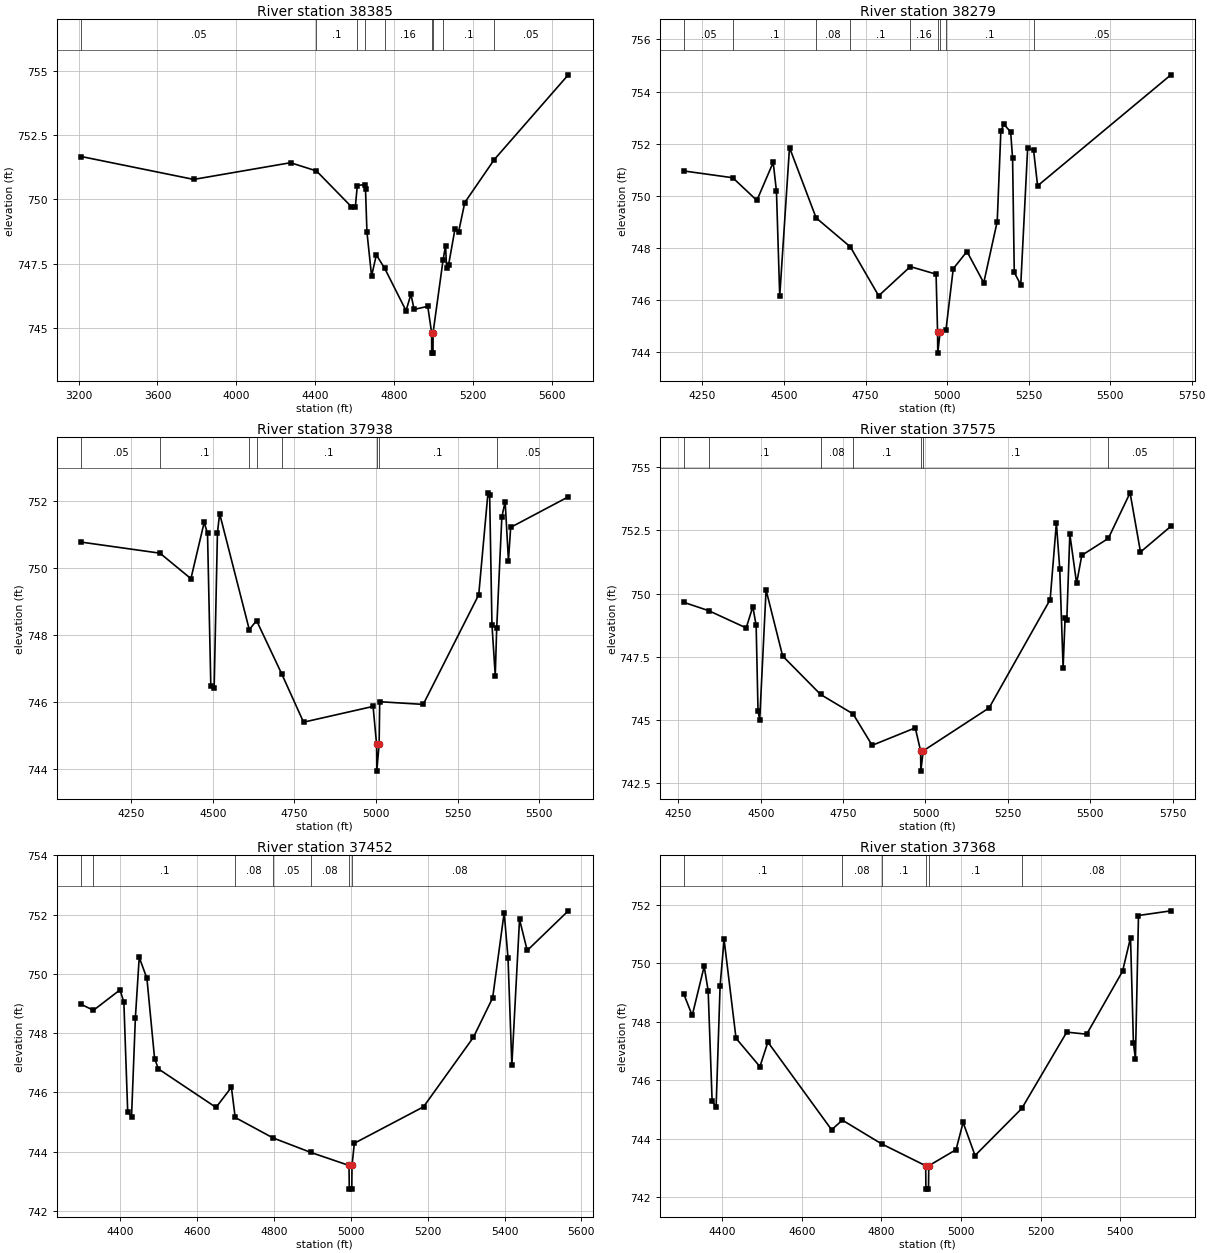
Type RM Length L Ch R = 1 ,38385   ,106,106,106
BEGIN DESCRIPTION:
Mapping XS f70f76d2
END DESCRIPTION:
XS GIS Cut Line= 5
      2022520.13     13641552.25      2021656.43     13641361.28
      2021031.91     13641507.27      2020524.96     13641625.33
      2020115.28     13641726.01
#Sta/Elev= 30
  3213.8  751.67  3783.8  750.78  4274.4  751.43  4405.7  751.11  4582.5  749.72
    4603  749.72  4612.8  750.54  4649.9  750.58  4654.4   750.4  4661.7  748.73
  4685.2  747.02  4709.3  747.84  4751.7  747.32  4859.8  745.67  4884.7  746.31
  4900.8  745.72  4969.9  745.84  4989.4  744.82    4990  744.02  4996.4  744.02
    4997  744.82  5047.8  747.66  5060.2   748.2  5065.3  747.34  5075.4  747.45
  5107.9  748.85  5126.7  748.75  5157.5  749.88  5306.8  751.55  5682.1  754.85
#Mann= 9 ,-1 , 0
  3213.8     .05       0  4405.7      .1       0  4612.8     .08       0
  4649.9     .05       0  4751.7     .16       0  4989.4     .07       0
    4997     .16       0  5047.8      .1       0  5306.8     .05       0
Bank Sta=4989.4,4997
XS Rating Curve= 0 ,0
Exp/Cntr=0.3,0.1

Type RM Length L Ch R = 1 ,38279   ,341,341,341
BEGIN DESCRIPTION:
Mapping XS eece863c
END DESCRIPTION:
XS GIS Cut Line= 4
      2021528.39     13641319.78       2021132.6     13641337.13
       2020695.1     13641482.97      2020078.53     13641638.84
#Sta/Elev= 30
  4193.2  750.95    4343  750.69  4416.8  749.82  4466.9  751.28  4476.9  750.17
  4486.9  746.15  4516.9  751.85  4598.5  749.15  4703.3  748.04  4790.3  746.16
  4887.3  747.28  4966.3  746.99  4970.9  744.76  4971.5  743.96  4978.6  744.76
  4996.6  744.85    5019   747.2    5061  747.86  5112.5  746.66  5153.8  749.01
    5165  752.49  5174.4  752.74    5195  752.45  5200.9  751.44  5206.1  747.06
    5226  746.58  5247.1  751.82  5265.3  751.75  5277.6  750.38  5686.5  754.64
#Mann= 9 ,-1 , 0
  4193.2     .05       0    4343      .1       0  4598.5     .08       0
  4703.3      .1       0  4887.3     .16       0  4970.9     .07       0
  4978.6     .16       0  4996.6      .1       0  5265.3     .05       0
Bank Sta=4970.9,4978.6
XS Rating Curve= 0 ,0
Exp/Cntr=0.3,0.1

Type RM Length L Ch R = 1 ,37938   ,363,363,363
BEGIN DESCRIPTION:
FORT EWELL CREEK 50.0
END DESCRIPTION:
XS GIS Cut Line= 3
      2021636.11     13641271.17        2020775.       13641125.
      2020163.81     13641215.61
#Sta/Elev= 30
  4097.4  750.77  4338.4  750.44  4433.2  749.68  4473.8  751.36    4484  751.03
  4494.1  746.49  4504.3  746.43  4514.4  751.05  4521.1  751.62  4611.9  748.16
  4634.2  748.43  4711.2  746.84  4778.1   745.4    4991  745.87  5001.7  744.74
  5002.3  743.94  5009.5  744.74  5011.3  746.01  5144.5  745.93  5314.5   749.2
  5342.8  752.24  5347.9  752.19    5355  748.31  5365.1  746.79  5369.5   748.2
  5385.3  751.52  5395.4  751.98  5405.5  750.22  5412.3  751.21  5588.7  752.12
#Mann= 8 ,-1 , 0
  4097.4     .05       0  4338.4      .1       0  4611.9     .05       0
  4634.2     .08       0  4711.2      .1       0  5001.7     .07       0
  5009.5      .1       0  5369.5     .05       0
Bank Sta=5001.7,5009.5
XS Rating Curve= 0 ,0
Exp/Cntr=0.3,0.1

Type RM Length L Ch R = 1 ,37575   ,123,123,123
BEGIN DESCRIPTION:
FORT EWELL CREEK 49.0
END DESCRIPTION:
XS GIS Cut Line= 3
      2021552.77      13640854.5        2020825.       13640775.
      2020094.42     13640923.94
#Sta/Elev= 30
  4267.1  749.65  4342.6  749.32    4456  748.64  4476.1  749.48  4486.2  748.74
  4491.9  745.35    4497  745.02  4516.3  750.14  4566.6  747.53  4681.8  746.01
  4780.4  745.24  4838.2     744    4969  744.69  4985.2  743.78  4985.9  742.98
    4993  743.78  5193.1  745.48  5378.3  749.76  5397.2  752.79  5407.4  750.97
  5417.6  747.07  5423.7  749.05  5428.8  748.97    5438  752.35  5458.5   750.4
  5474.3  751.51  5554.8  752.18  5620.8  753.98  5652.4  751.64  5744.8  752.66
#Mann= 7 ,-1 , 0
  4267.1     .05       0  4342.6      .1       0  4681.8     .08       0
  4780.4      .1       0  4985.2     .07       0    4993      .1       0
  5554.8     .05       0
Bank Sta=4985.2,4993
XS Rating Curve= 0 ,0
Exp/Cntr=0.3,0.1

Type RM Length L Ch R = 1 ,37452   ,84,84,84
BEGIN DESCRIPTION:
Mapping XS 53811aba
END DESCRIPTION:
XS GIS Cut Line= 4
      2021545.83     13640670.47      2020309.69     13640642.69
      2020316.63     13640642.69      2020292.28     13640639.21
#Sta/Elev= 30
  4297.9  748.97  4329.6  748.77  4398.8  749.46  4408.8  749.04  4418.8  745.34
  4428.8  745.18  4438.8  748.52  4448.8  750.56  4468.8  749.85  4488.8  747.14
  4498.8  746.79  4648.8  745.49  4688.8  746.17  4698.7  745.15    4797  744.46
  4895.4  743.97    4995  743.53  4995.7  742.73  5002.2  742.73  5002.8  743.53
  5008.9  744.28    5189  745.51    5319  747.86    5369  749.19    5399  752.07
    5409  750.54    5419  746.92    5439  751.84    5459  750.79  5565.9  752.13
#Mann= 7 ,-1 , 0
  4297.9     .05       0  4329.6      .1       0  4698.7     .08       0
    4797     .05       0  4895.4     .08       0    4995     .07       0
  5002.8     .08       0
Bank Sta=4995,5002.8
XS Rating Curve= 0 ,0
Exp/Cntr=0.3,0.1

Type RM Length L Ch R = 1 ,37368   ,246,246,246
BEGIN DESCRIPTION:
FORT EWELL CREEK 48.0
END DESCRIPTION:
XS GIS Cut Line= 3
      2021545.81     13640573.25      2020948.58      13640566.3
      2020323.57     13640594.08
#Sta/Elev= 30
    4304  748.94  4324.8  748.22  4354.8   749.9  4364.8  749.07  4374.8  745.28
  4384.8   745.1  4394.8  749.23  4404.8  750.82  4434.8  747.44  4494.8  746.47
  4514.8  747.31  4674.8  744.31  4701.8  744.64  4800.1  743.83    4911  743.08
  4911.6  742.28  4918.1  742.28  4918.8  743.08  4987.3  743.63    5005  744.56
    5035  743.43  5152.4  745.04  5265.2  747.65  5315.3  747.58  5405.3  749.73
  5425.4  750.88  5432.7  747.28  5437.7  746.73  5445.4  751.64  5526.9   751.8
#Mann= 6 ,-1 , 0
    4304      .1       0  4701.8     .08       0  4800.1      .1       0
    4911     .07       0  4918.8      .1       0  5152.4     .08       0
Bank Sta=4911,4918.8
XS Rating Curve= 0 ,0
Exp/Cntr=0.3,0.1