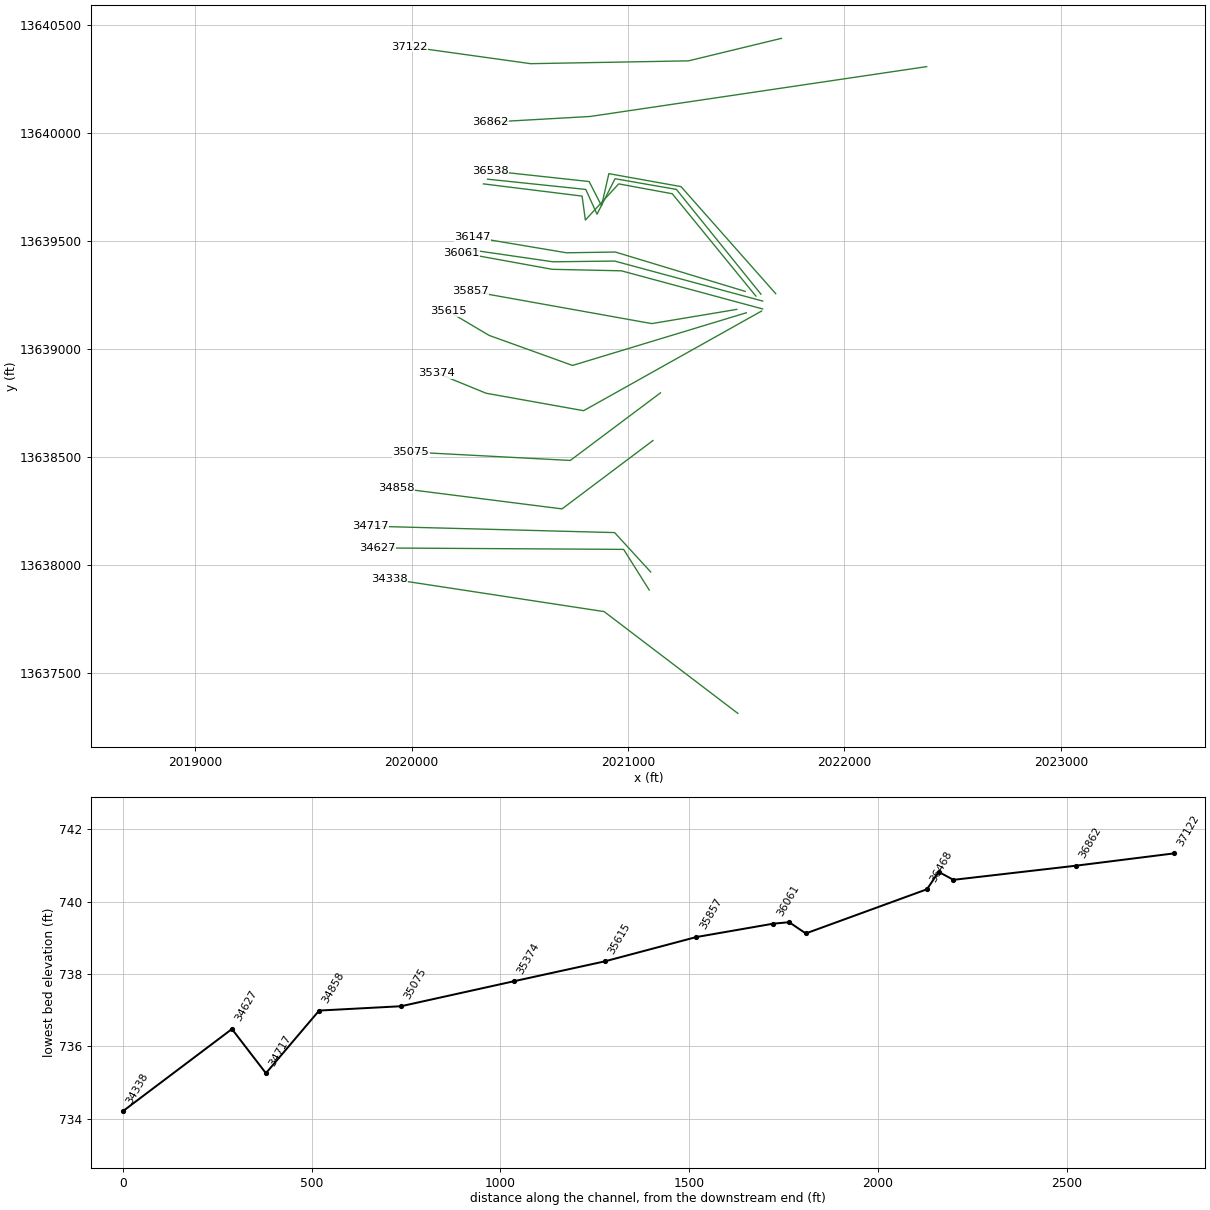
HEC-RAS study FORT EWELL CREEK.prj: FORT EWELL CREEK Base Level Engineering

--- FORT EWELL CREEK.g01 (geometry) --- (continued)

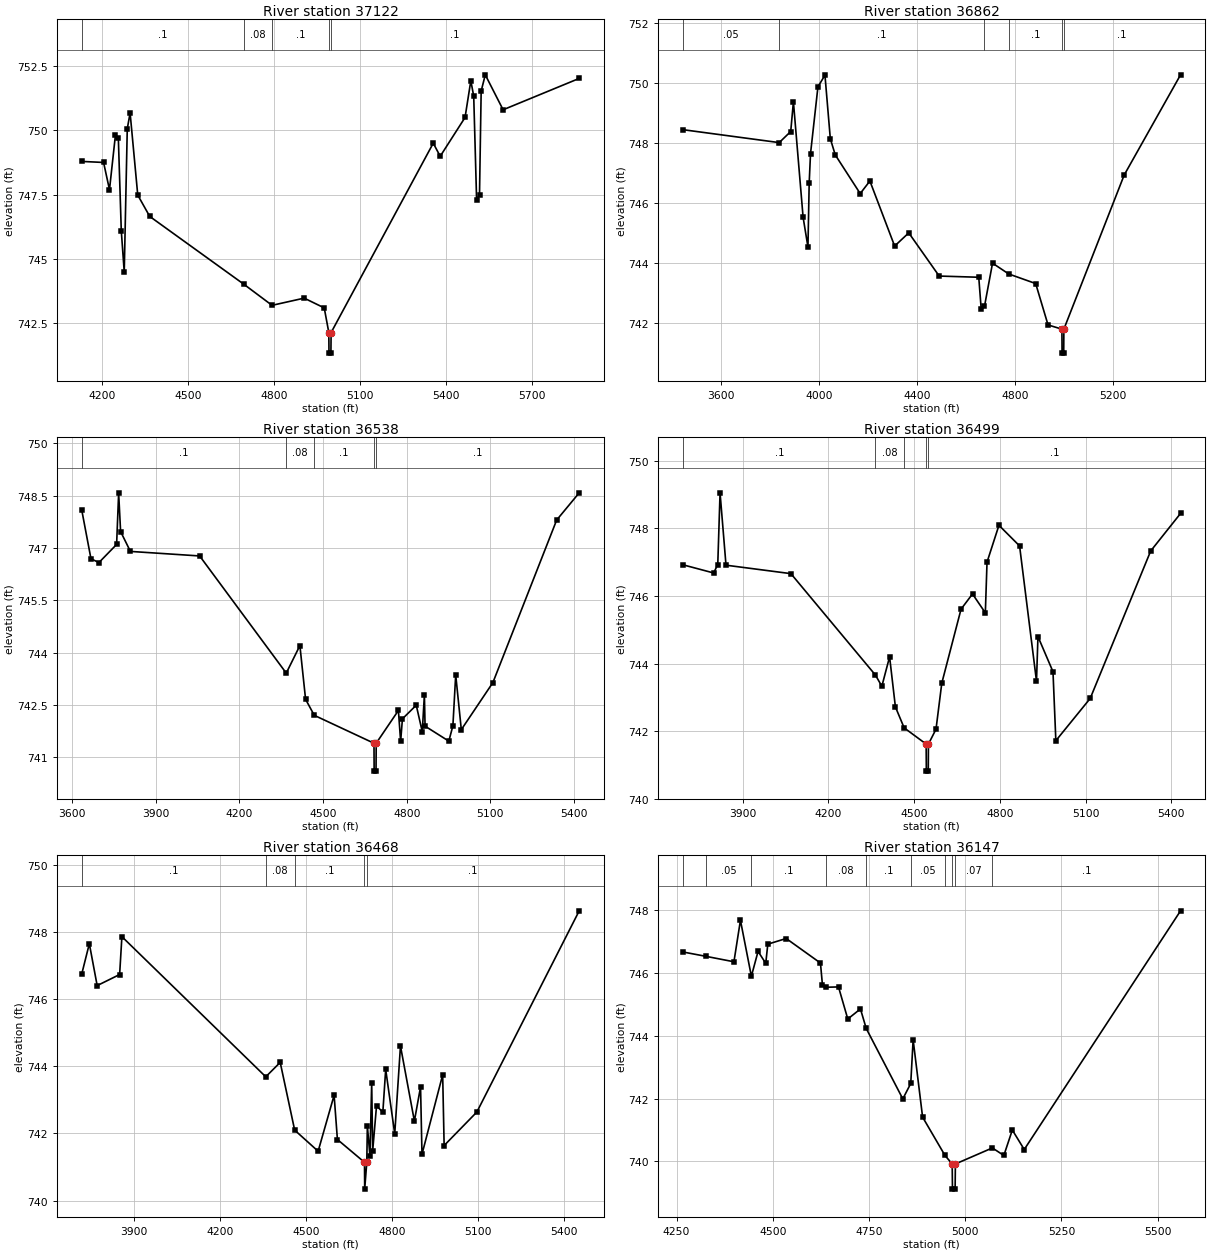
Type RM Length L Ch R = 1 ,37122   ,260,260,260
BEGIN DESCRIPTION:
Mapping XS 754dce83
END DESCRIPTION:
XS GIS Cut Line= 4
      2021708.98     13640436.26      2021279.31      13640332.1
      2020550.14     13640319.08      2019990.27      13640397.2
#Sta/Elev= 30
  4129.3  748.79  4205.4  748.75    4226  747.69  4246.6   749.8  4256.9   749.7
  4267.2  746.09  4277.5  744.49  4288.1  750.06    4298  750.68  4324.7  747.48
  4366.5  746.65  4695.2  744.01  4793.6  743.19  4905.8  743.47  4975.8  743.09
  4991.8  742.13  4992.4  741.33  4999.1  741.33  4999.8  742.13  5356.4   749.5
  5380.7  748.99  5467.4   750.5  5487.6  751.93  5497.7  751.33  5507.8  747.29
  5517.9  747.49  5523.7  751.53  5538.1  752.16  5600.3   750.8    5866  752.02
#Mann= 5 ,-1 , 0
  4129.3      .1       0  4695.2     .08       0  4793.6      .1       0
  4991.8     .07       0  4999.8      .1       0
Bank Sta=4991.8,4999.8
XS Rating Curve= 0 ,0
Exp/Cntr=0.3,0.1

Type RM Length L Ch R = 1 ,36862   ,324,324,324
BEGIN DESCRIPTION:
FORT EWELL CREEK 47.0
END DESCRIPTION:
XS GIS Cut Line= 3
      2022379.88     13640305.46        2020825.       13640075.
      2020365.21     13640048.94
#Sta/Elev= 30
  3444.1  748.44  3836.7  748.01  3883.7  748.38  3894.7  749.37  3934.3  745.52
  3954.1  744.53  3959.2  746.67  3964.6  747.64  3994.9  749.87  4023.6  750.26
  4045.5  748.14  4065.7   747.6  4167.6  746.31  4207.2  746.73  4308.3  744.56
    4366     745  4490.3  743.56    4652  743.52  4662.1  742.45  4675.4  742.55
  4708.3  743.99  4774.4  743.63  4884.6  743.31  4935.1  741.93  4991.8  741.79
  4992.4  740.99  4999.1  740.99  4999.8  741.79  5246.3  746.93  5476.5  750.27
#Mann= 6 ,-1 , 0
  3444.1     .05       0  3836.7      .1       0  4675.4     .08       0
  4774.4      .1       0  4991.8     .07       0  4999.8      .1       0
Bank Sta=4991.8,4999.8
XS Rating Curve= 0 ,0
Exp/Cntr=0.3,0.1

Type RM Length L Ch R = 1 ,36538   ,39,39,39
BEGIN DESCRIPTION:
Mapping XS d5235f57
END DESCRIPTION:
XS GIS Cut Line= 6
      2021682.35     13639255.94      2021244.83     13639750.75
       2020911.5     13639810.64      2020877.64      13639662.2
      2020820.35     13639774.18      2020364.64     13639823.66
#Sta/Elev= 30
  3634.7  748.08  3667.6  746.69  3696.1  746.58  3759.6   747.1  3766.9  748.57
  3773.9  747.47    3809   746.9  4057.4  746.77    4368  743.41  4416.9   744.2
  4437.3  742.66  4468.5   742.2  4682.6   741.4  4683.2   740.6  4689.9   740.6
  4690.6   741.4  4770.2  742.34  4778.2  741.45  4784.6   742.1  4834.2  742.49
  4855.8  741.73  4863.4  742.79  4865.8  741.89    4951  741.46  4965.6   741.9
  4975.7  743.36  4995.8  741.79  5109.1  743.14  5337.8   747.8  5418.6  748.58
#Mann= 5 ,-1 , 0
  3634.7      .1       0    4368     .08       0  4468.5      .1       0
  4682.6     .07       0  4690.6      .1       0
Bank Sta=4682.6,4690.6
XS Rating Curve= 0 ,0
Exp/Cntr=0.3,0.1

Type RM Length L Ch R = 1 ,36499   ,31,31,31
BEGIN DESCRIPTION:
FORT EWELL CREEK 46.0
END DESCRIPTION:
XS GIS Cut Line= 6
      2021614.25     13639253.37      2021223.62     13639737.75
      2020940.14      13639787.2      2020856.81     13639623.14
      2020804.72     13639737.73      2020351.31     13639785.06
#Sta/Elev= 30
  3691.7  746.92  3798.5  746.68  3812.9  746.93  3820.9  749.05  3841.7  746.91
  4068.8  746.66  4364.6  743.66    4387  743.33  4414.1   744.2  4434.4  742.72
    4465   742.1    4542  741.62  4542.7  740.82  4549.4  740.82    4550  741.62
  4576.5  742.06  4596.7  743.42  4664.1  745.61  4704.2  746.06  4749.1   745.5
    4755     747  4796.7  748.09  4868.9  747.48  4928.1  743.48  4933.2   744.8
  4985.8  743.76  4995.8  741.72    5116  742.97  5327.6  747.33  5432.1  748.44
#Mann= 5 ,-1 , 0
  3691.7      .1       0  4364.6     .08       0    4465      .1       0
    4542     .07       0    4550      .1       0
Bank Sta=4542,4550
XS Rating Curve= 0 ,0
Exp/Cntr=0.3,0.1

Type RM Length L Ch R = 1 ,36468   ,321,321,321
BEGIN DESCRIPTION:
Mapping XS 3b9d4ec9
END DESCRIPTION:
XS GIS Cut Line= 6
      2021590.77     13639244.64      2021204.46     13639717.76
      2020957.07     13639763.33      2020802.99     13639596.23
       2020787.8     13639706.91      2020332.03     13639763.34
#Sta/Elev= 30
  3718.4  746.76  3744.7  747.66    3772  746.41  3850.3  746.74  3858.2  747.87
  4359.7  743.69    4410  744.12  4460.4   742.1  4542.2  741.47  4597.9  743.14
  4609.4  741.82  4703.8  741.14  4704.5  740.34  4711.8  741.14  4713.8  742.23
  4722.8  741.33  4728.9  743.51  4732.3  741.48  4745.8  742.83  4767.7  742.63
  4777.7  743.91  4809.2  741.99  4829.2  744.61  4877.7  742.37  4899.2  743.39
  4904.2  741.38  4976.3  743.75  4981.4  741.64  5095.5  742.64  5452.2  748.64
#Mann= 5 ,-1 , 0
  3718.4      .1       0  4359.7     .08       0  4460.4      .1       0
  4703.8     .07       0  4711.8      .1       0
Bank Sta=4703.8,4711.8
XS Rating Curve= 0 ,0
Exp/Cntr=0.3,0.1

Type RM Length L Ch R = 1 ,36147   ,44,44,44
BEGIN DESCRIPTION:
Mapping XS 6f78869a
END DESCRIPTION:
XS GIS Cut Line= 4
      2021541.28     13639266.41      2020941.63     13639448.25
      2020715.94     13639444.77      2020281.95     13639517.68
#Sta/Elev= 30
  4267.2  746.66  4327.7  746.52  4399.2  746.35  4416.1  747.67  4444.5  745.89
  4461.9  746.68  4481.9   746.3  4487.2  746.91    4535  747.09    4624  746.31
  4629.2  745.61  4639.1  745.54  4670.9  745.55    4695  744.53  4727.9  744.85
  4742.9  744.23    4838  741.99  4858.6  742.48  4864.8  743.87  4889.4  741.41
  4947.6  740.19  4966.3  739.92    4967  739.12  4973.9  739.12  4974.6  739.92
  5070.7  740.43  5100.5  740.19  5122.5     741  5153.5  740.38  5559.6  747.97
#Mann= 10 ,-1 , 0
  4267.2      .1       0  4327.7     .05       0  4444.5      .1       0
  4639.1     .08       0  4742.9      .1       0  4858.6     .05       0
  4947.6     .07       0  4966.3     .07       0  4974.6     .07       0
  5070.7      .1       0
Bank Sta=4966.3,4974.6
XS Rating Curve= 0 ,0
Exp/Cntr=0.3,0.1

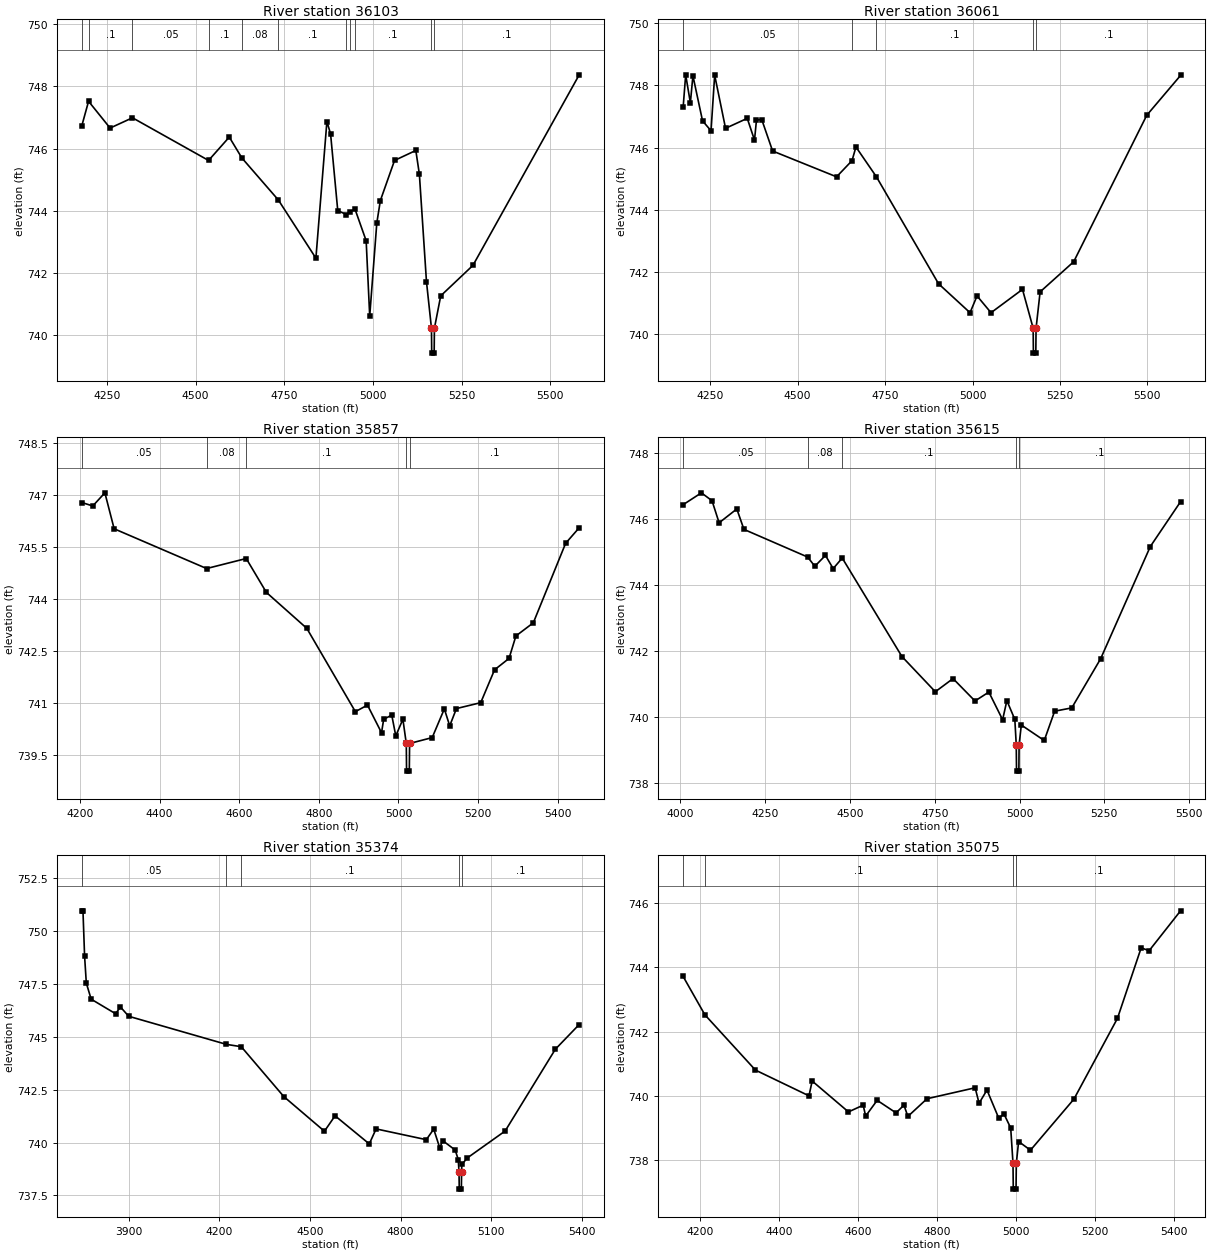
Type RM Length L Ch R = 1 ,36103   ,42,42,42
BEGIN DESCRIPTION:
Mapping XS 411db86c
END DESCRIPTION:
XS GIS Cut Line= 4
      2021622.07      13639221.6      2020938.16     13639406.58
      2020653.44     13639403.11      2020248.62     13639461.93
#Sta/Elev= 30
  4179.1  746.73  4198.2  747.52  4258.9  746.66    4322  746.99  4536.5  745.62
  4594.9  746.37  4630.4   745.7  4733.2  744.35  4839.1  742.48  4870.1  746.87
  4880.5  746.47  4900.7  744.01  4925.1  743.88  4936.6  743.97  4949.2  744.06
  4980.8  743.04  4990.8  740.62  5010.8  743.61  5020.8  744.33  5060.8  745.62
  5120.8  745.94  5130.8  745.18  5150.8  741.73  5164.9  740.23  5165.6  739.43
  5172.5  739.43  5173.2  740.23    5191  741.27  5281.9  742.25  5581.4  748.37
#Mann= 11 ,-1 , 0
  4179.1     .05       0  4198.2      .1       0    4322     .05       0
  4536.5      .1       0  4630.4     .08       0  4733.2      .1       0
  4925.1     .05       0  4936.6     .07       0  4949.2      .1       0
  5164.9     .07       0  5173.2      .1       0
Bank Sta=5164.9,5173.2
XS Rating Curve= 0 ,0
Exp/Cntr=0.3,0.1

Type RM Length L Ch R = 1 ,36061   ,204,204,204
BEGIN DESCRIPTION:
Mapping XS 11485d19
END DESCRIPTION:
XS GIS Cut Line= 4
      2021622.07     13639185.15      2020969.41     13639361.44
      2020649.96     13639368.38      2020229.92     13639444.76
#Sta/Elev= 30
  4172.4  747.29  4179.7  748.34  4193.1  747.44  4200.4  748.31  4227.9  746.86
  4252.2  746.54  4262.6  748.33  4293.7  746.62  4355.8  746.94  4376.5  746.24
  4382.2  746.89  4397.3   746.9  4428.3  745.89  4611.2  745.06  4655.4  745.58
  4666.6  746.02  4725.2  745.06  4902.9  741.62  4992.9  740.69  5012.9  741.23
  5052.9  740.69  5142.9  741.44  5173.4  740.19  5174.1  739.39    5181  739.39
  5181.7  740.19  5193.3  741.36  5289.4  742.33  5498.3  747.04  5594.9  748.32
#Mann= 5 ,-1 , 0
  4172.4     .05       0  4655.4     .08       0  4725.2      .1       0
  5173.4     .07       0  5181.7      .1       0
Bank Sta=5173.4,5181.7
XS Rating Curve= 0 ,0
Exp/Cntr=0.3,0.1

Type RM Length L Ch R = 1 ,35857   ,242,242,242
BEGIN DESCRIPTION:
Mapping XS 1d55aa96
END DESCRIPTION:
XS GIS Cut Line= 3
      2021502.25     13639183.06      2021109.87     13639117.38
      2020271.48     13639267.69
#Sta/Elev= 30
  4204.4  746.79    4232  746.69  4262.4  747.07  4285.7  746.03    4518  744.88
  4617.5  745.17  4668.1  744.19  4769.7  743.15  4891.7  740.74  4922.1  740.93
  4957.4  740.13  4962.8  740.52  4983.1  740.64  4993.2  740.04  5011.1  740.52
  5019.6  739.82  5020.3  739.02  5027.2  739.02  5027.9  739.82  5084.7  739.99
  5115.2  740.82  5128.7  740.33  5145.6  740.83  5206.6     741  5241.3  741.95
  5277.7  742.28    5295  742.93  5338.7  743.31  5419.9  745.61    5454  746.06
#Mann= 5 ,-1 , 0
  4204.4     .05       0    4518     .08       0  4617.5      .1       0
  5019.6     .07       0  5027.9      .1       0
Bank Sta=5019.6,5027.9
XS Rating Curve= 0 ,0
Exp/Cntr=0.3,0.1

Type RM Length L Ch R = 1 ,35615   ,241,241,241
BEGIN DESCRIPTION:
Mapping XS a2071335
END DESCRIPTION:
XS GIS Cut Line= 4
      2021546.57     13639167.45      2020743.71     13638923.94
       2020358.3     13639062.83       2020170.8     13639173.94
#Sta/Elev= 30
  4008.2  746.44  4062.1   746.8  4093.4  746.56  4114.3  745.89  4166.5  746.31
  4187.5  745.69  4375.4  744.85  4396.5  744.57  4427.8   744.9  4450.6   744.5
  4477.3  744.82  4653.3  741.83  4751.8  740.76    4804  741.16  4868.7  740.48
  4909.6  740.75  4950.2  739.91  4962.7  740.49  4986.2  739.92  4990.4  739.15
  4991.2  738.35  4998.1  738.35  4998.8  739.15  5005.3  739.75  5072.9  739.28
  5103.6  740.17  5154.1  740.27  5239.1  741.76  5385.7  745.17  5474.8  746.53
#Mann= 5 ,-1 , 0
  4008.2     .05       0  4375.4     .08       0  4477.3      .1       0
  4990.4     .07       0  4998.8      .1       0
Bank Sta=4990.4,4998.8
XS Rating Curve= 0 ,0
Exp/Cntr=0.3,0.1

Type RM Length L Ch R = 1 ,35374   ,299,299,299
BEGIN DESCRIPTION:
Mapping XS f28b9ce2
END DESCRIPTION:
XS GIS Cut Line= 4
      2021616.87     13639175.26      2020794.93     13638714.74
      2020344.41     13638795.47       2020115.2     13638889.23
#Sta/Elev= 30
  3744.3  750.97  3748.2  750.97  3753.6  748.82  3759.3  747.55  3775.3  746.79
  3856.3   746.1  3872.3  746.42  3899.7  745.98  4223.4  744.65  4272.5  744.54
  4413.4  742.18    4548  740.54  4583.2  741.27  4696.5  739.94  4719.1  740.65
  4885.4  740.14  4909.9  740.64  4930.2  739.74  4939.2   740.1    4981  739.65
  4991.2   739.2  4993.8   738.6  4994.5   737.8  5001.5   737.8  5002.2   738.6
  5003.1  738.97  5021.6  739.28  5146.5  740.55  5312.8  744.42  5391.8  745.59
#Mann= 5 ,-1 , 0
  3744.3     .05       0  4223.4     .08       0  4272.5      .1       0
  4993.8     .07       0  5002.2      .1       0
Bank Sta=4993.8,5002.2
XS Rating Curve= 0 ,0
Exp/Cntr=0.3,0.1

Type RM Length L Ch R = 1 ,35075   ,217,217,217
BEGIN DESCRIPTION:
Mapping XS e32e6c33
END DESCRIPTION:
XS GIS Cut Line= 3
      2021149.98     13638797.21       2020733.3      13638484.7
      2019995.48     13638523.76
#Sta/Elev= 30
  4156.2  743.72  4211.2  742.53  4339.3  740.81  4474.9  740.01    4483  740.47
  4574.9  739.51  4612.2  739.72  4618.4  739.38  4647.6  739.87  4695.4  739.48
  4715.4  739.72  4725.4  739.37  4773.9  739.92  4895.7  740.26  4905.7  739.78
  4925.7  740.19  4955.7  739.31  4968.6  739.45  4985.8  739.01  4991.6  737.91
  4992.3  737.11  4999.3  737.11    5000  737.91  5005.8  738.59  5035.8  738.32
    5146  739.91  5256.2  742.42  5316.2  744.61  5336.3  744.52  5415.9  745.76
#Mann= 4 ,-1 , 0
  4156.2     .08       0  4211.2      .1       0  4991.6     .07       0
    5000      .1       0
Bank Sta=4991.6,5000
XS Rating Curve= 0 ,0
Exp/Cntr=0.3,0.1

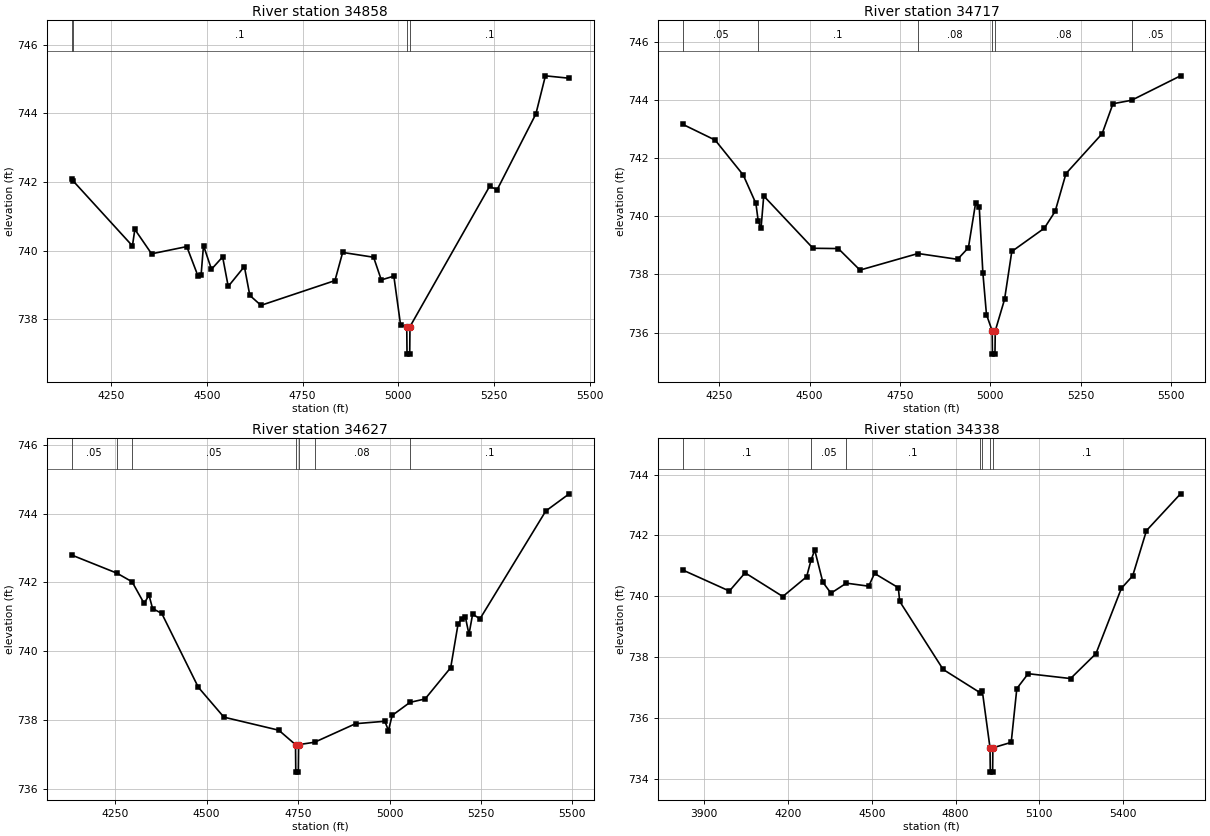
Type RM Length L Ch R = 1 ,34858   ,141,141,141
BEGIN DESCRIPTION:
Mapping XS 1e59af11
END DESCRIPTION:
XS GIS Cut Line= 3
      2021115.25     13638576.72       2020695.1     13638260.75
      2019928.83     13638357.83
#Sta/Elev= 30
  4147.4   742.1  4151.6  742.03  4306.2  740.14  4312.5  740.62  4356.2  739.91
    4448  740.12    4477  739.27  4485.3  739.29  4491.6  740.15  4512.4  739.46
  4541.5  739.82  4556.1  738.96  4598.2  739.54  4612.4   738.7  4641.5  738.41
  4834.5  739.13  4854.6  739.95  4935.3  739.81  4955.4  739.15  4988.1  739.26
  5005.8  737.83  5021.8  737.79  5022.5  736.99  5029.5  736.99  5030.2  737.79
  5237.7  741.87  5257.8  741.78  5358.6  743.98  5383.5  745.09  5445.5  745.02
#Mann= 4 ,-1 , 0
  4147.4     .08       0  4151.6      .1       0  5021.8     .07       0
  5030.2      .1       0
Bank Sta=5021.8,5030.2
XS Rating Curve= 0 ,0
Exp/Cntr=0.3,0.1

Type RM Length L Ch R = 1 ,34717   ,90,90,90
BEGIN DESCRIPTION:
Mapping XS bf0abe80
END DESCRIPTION:
XS GIS Cut Line= 3
      2021104.82     13637969.08       2020938.2     13638151.17
      2019808.11     13638180.83
#Sta/Elev= 30
  4149.5  743.16  4238.8  742.62  4316.5  741.42  4351.6  740.44    4358  739.83
  4365.8  739.59  4373.2   740.7  4509.6   738.9  4579.6  738.89  4639.6  738.15
  4800.3  738.72  4909.7  738.52  4939.7  738.92  4959.7  740.46  4969.7  740.32
  4979.7  738.06  4989.7  736.62  5005.5  736.06  5006.2  735.26  5013.2  735.26
    5014  736.06  5039.7  737.14  5059.8  738.79  5149.8  739.59  5179.8  740.17
  5209.8  741.47  5309.8  742.84  5339.8  743.87  5391.4  743.99  5526.8  744.83
#Mann= 6 ,-1 , 0
  4149.5     .05       0    4358      .1       0  4800.3     .08       0
  5005.5     .07       0    5014     .08       0  5391.4     .05       0
Bank Sta=5005.5,5014
XS Rating Curve= 0 ,0
Exp/Cntr=0.3,0.1

Type RM Length L Ch R = 1 ,34627   ,289,289,289
BEGIN DESCRIPTION:
Mapping XS 0cfa170e
END DESCRIPTION:
XS GIS Cut Line= 3
      2021097.89     13637885.73      2020979.83     13638073.51
      2019840.96     13638080.19
#Sta/Elev= 30
  4130.6   742.8  4254.9  742.27  4296.1  742.02    4329  741.39  4342.4  741.63
  4352.2  741.24  4377.2   741.1  4477.2  738.95  4547.2  738.08  4697.2   737.7
    4743  737.28  4743.7  736.48  4750.7  736.48  4751.5  737.28  4795.2  737.35
  4907.2  737.89  4987.2  737.96  4997.2  737.69  5007.2  738.13  5055.9  738.51
  5097.3  738.61  5167.3  739.52  5187.3  740.78  5197.3  740.95  5207.3     741
  5217.3  740.49  5227.3  741.08  5247.3  740.94  5427.3  744.08  5491.3  744.58
#Mann= 7 ,-1 , 0
  4130.6     .05       0  4254.9      .1       0  4296.1     .05       0
    4743     .07       0  4751.5     .05       0  4795.2     .08       0
  5055.9      .1       0
Bank Sta=4743,4751.5
XS Rating Curve= 0 ,0
Exp/Cntr=0.3,0.1

Type RM Length L Ch R = 1 ,34338   ,313,313,313
BEGIN DESCRIPTION:
Mapping XS 2e9d8d5e
END DESCRIPTION:
XS GIS Cut Line= 3
      2021507.47     13637315.36      2020889.55     13637785.92
      2019895.59     13637937.83
#Sta/Elev= 30
  3823.7  740.86  3990.2  740.17  4046.4  740.77  4181.5  739.99  4266.8  740.64
  4282.4  741.18  4295.8  741.52  4324.9  740.46    4354   740.1  4409.1  740.43
  4489.1  740.33    4510  740.75  4595.2  740.28  4600.1  739.83  4755.7  737.59
  4887.1  736.83    4896  736.88  4923.6  735.01  4924.6  734.21  4932.9  734.21
  4933.8  735.01  4999.5  735.19  5019.6  736.96  5060.2  737.45    5212  737.29
    5303  738.11  5394.1  740.26  5434.5  740.67  5483.9  742.16  5605.9  743.37
#Mann= 7 ,-1 , 0
  3823.7      .1       0  4282.4     .05       0  4409.1      .1       0
  4887.1     .05       0    4896      .1       0  4923.6     .07       0
  4933.8      .1       0
Bank Sta=4923.6,4933.8
XS Rating Curve= 0 ,0
Exp/Cntr=0.3,0.1