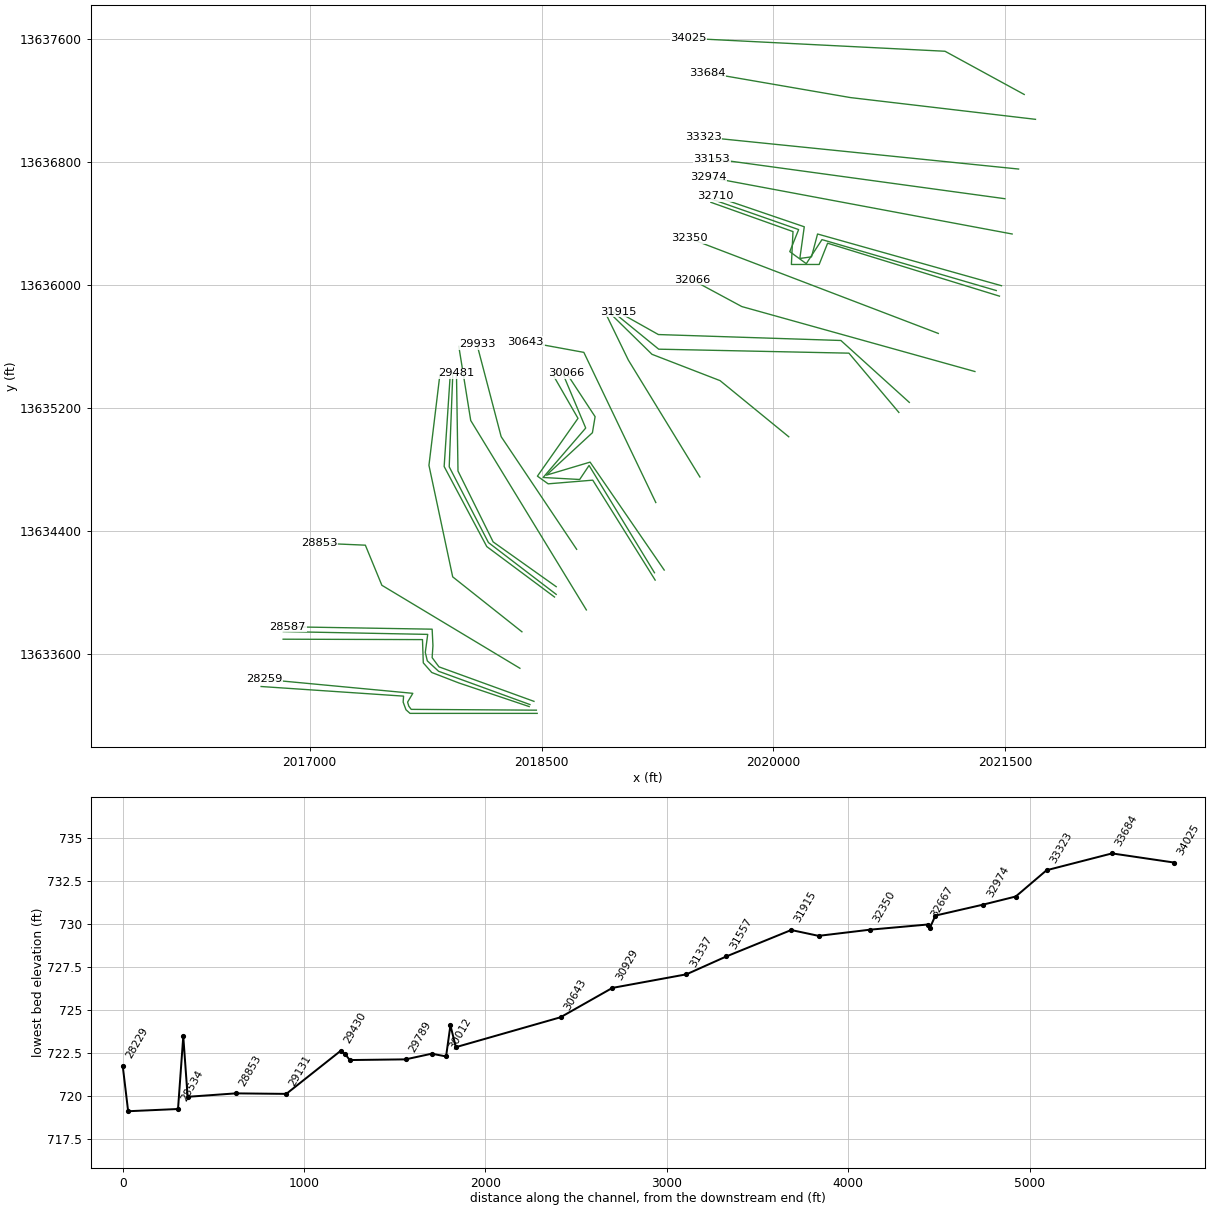
HEC-RAS study FORT EWELL CREEK.prj: FORT EWELL CREEK Base Level Engineering

--- FORT EWELL CREEK.g01 (geometry) --- (continued)

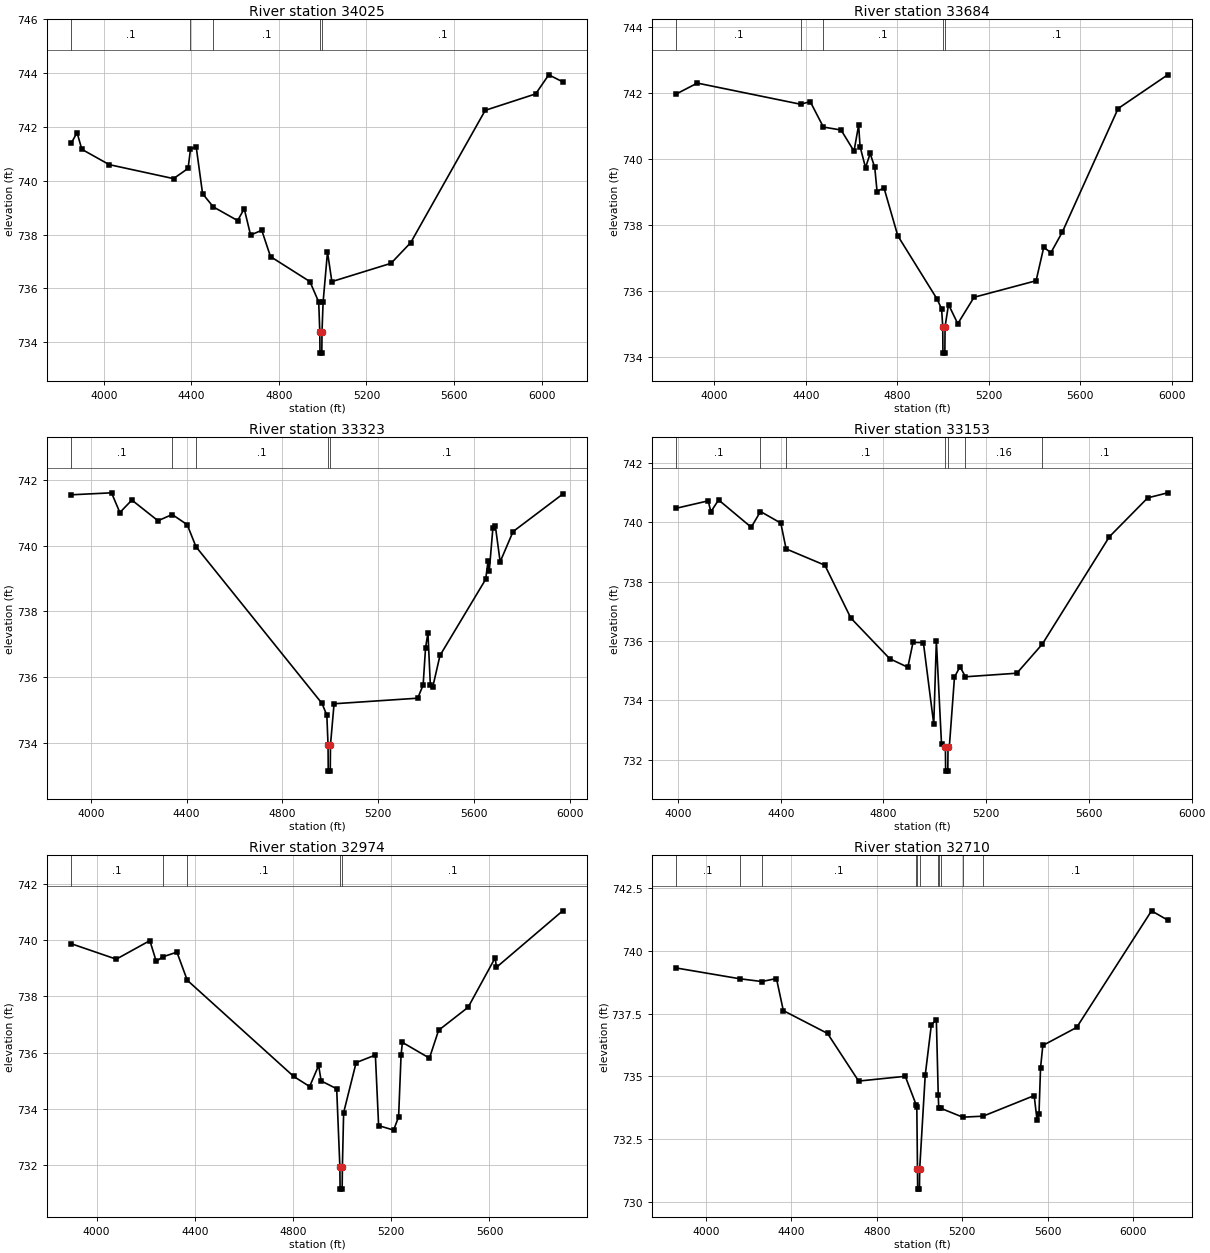
Type RM Length L Ch R = 1 ,34025   ,341,341,341
BEGIN DESCRIPTION:
FORT EWELL CREEK 45.0
END DESCRIPTION:
XS GIS Cut Line= 3
      2021623.37     13637237.23       2021110.9     13637517.91
      2019451.52     13637601.81
#Sta/Elev= 30
  3850.9   741.4  3877.5  741.79  3899.3  741.17  4024.5   740.6  4318.4  740.08
  4384.9  740.46  4395.8  741.17  4421.8  741.27  4451.1  739.52  4499.8  739.03
  4611.3  738.52  4641.4  738.96  4670.5  737.98  4721.5  738.16  4761.5  737.18
  4941.7  736.25  4981.8  735.49  4986.7  734.39  4987.7  733.59    4996  733.59
  4996.9  734.39  5001.8  735.48  5021.9  737.35  5041.9  736.25  5312.2  736.93
  5402.3   737.7  5742.8  742.62  5973.1  743.23  6033.1  743.94  6096.7  743.68
#Mann= 5 ,-1 , 0
  3850.9      .1       0  4395.8     .05       0  4499.8      .1       0
  4986.7     .07       0  4996.9      .1       0
Bank Sta=4986.7,4996.9
XS Rating Curve= 0 ,0
Exp/Cntr=0.3,0.1

Type RM Length L Ch R = 1 ,33684   ,361,361,361
BEGIN DESCRIPTION:
FORT EWELL CREEK 43.0
END DESCRIPTION:
XS GIS Cut Line= 3
      2021696.27     13637075.77      2020498.96     13637217.01
      2019571.31     13637377.85
#Sta/Elev= 30
  3834.3  741.96  3926.2  742.29  4377.6  741.65  4419.6  741.73    4477  740.96
  4554.4  740.87  4610.9  740.23  4631.1  741.02  4637.3  740.37  4661.3  739.73
  4681.4  740.16  4701.5  739.74  4711.6  739.01  4741.8  739.12  4802.2  737.67
  4973.4  735.76  4993.6  735.46  4998.5  734.92  4999.4  734.12  5007.8  734.12
  5008.7  734.92  5023.8  735.59  5064.2  735.01  5135.3  735.81  5406.4  736.31
  5439.8  737.32  5471.2  737.16  5520.8  737.78  5764.7  741.52  5981.4  742.54
#Mann= 5 ,-1 , 0
  3834.3      .1       0  4377.6     .05       0    4477      .1       0
  4998.5     .07       0  5008.7      .1       0
Bank Sta=4998.5,5008.7
XS Rating Curve= 0 ,0
Exp/Cntr=0.3,0.1

Type RM Length L Ch R = 1 ,33323   ,170,170,170
BEGIN DESCRIPTION:
Mapping XS 7050bb02
END DESCRIPTION:
XS GIS Cut Line= 2
      2021586.91     13636752.86      2019545.21     13636961.19
#Sta/Elev= 30
  3918.3  741.55  4086.6  741.61  4121.3  741.01  4171.5  741.39  4280.6  740.76
  4339.9  740.95  4402.7  740.64  4439.2  739.97  4965.6   735.2  4985.7  734.84
  4990.7  733.94  4991.6  733.14    5000  733.14  5000.9  733.94  5015.9  735.19
  5365.2  735.36  5387.8  735.76  5397.9  736.89  5407.9  737.35    5418  735.75
    5428   735.7  5458.2  736.66  5649.2  738.98  5658.7  739.53  5663.8  739.22
  5679.3  740.55  5689.4   740.6  5709.5  739.51  5763.3  740.43  5970.6  741.57
#Mann= 5 ,-1 , 0
  3918.3      .1       0  4339.9     .05       0  4439.2      .1       0
  4990.7     .07       0  5000.9      .1       0
Bank Sta=4990.7,5000.9
XS Rating Curve= 0 ,0
Exp/Cntr=0.3,0.1

Type RM Length L Ch R = 1 ,33153   ,179,179,179
BEGIN DESCRIPTION:
Mapping XS 0a292507
END DESCRIPTION:
XS GIS Cut Line= 2
      2021498.33     13636560.15      2019602.53     13636820.57
#Sta/Elev= 30
  3993.1  740.47  4117.6  740.72  4127.7  740.35    4158  740.75    4285  739.83
  4321.1  740.36  4400.2  739.97  4420.8   739.1  4571.8  738.55  4672.8  736.77
  4824.2   735.4  4894.8  735.11    4915  735.95  4955.4  735.94  4995.8  733.19
  5005.9     736    5026  732.51  5041.1  732.41    5042  731.61  5050.4  731.61
  5051.3  732.41  5056.3  732.42  5076.5  734.78    5098  735.13  5119.1  734.79
  5319.2  734.91  5418.4  735.89  5679.6  739.51  5828.8  740.82  5906.7  740.99
#Mann= 7 ,-1 , 0
  3993.1      .1       0  4321.1     .08       0  4420.8      .1       0
  5041.1     .07       0  5051.3      .1       0  5119.1     .16       0
  5418.4      .1       0
Bank Sta=5041.1,5051.3
XS Rating Curve= 0 ,0
Exp/Cntr=0.3,0.1

Type RM Length L Ch R = 1 ,32974   ,264,264,264
BEGIN DESCRIPTION:
Mapping XS b3bb7ea7
END DESCRIPTION:
XS GIS Cut Line= 2
      2021545.25     13636330.98      2019578.25     13636700.44
#Sta/Elev= 30
  3896.7  739.87  4080.1  739.32  4216.9  739.98  4242.9  739.24  4268.5   739.4
  4327.1  739.57  4369.2  738.57  4802.5  735.15  4867.6  734.79  4904.3  735.54
  4914.4  734.99  4977.7  734.71  4990.7  731.94  4991.6  731.14    5000  731.14
    5001  731.94    5006  733.86  5056.9  735.64  5135.3  735.91  5148.5   733.4
  5209.5  733.24  5229.9  733.71    5240  735.92  5245.4  736.36  5355.5   735.8
  5392.7  736.79  5513.1  737.61  5623.2  739.37  5628.3  739.03  5898.1  741.04
#Mann= 5 ,-1 , 0
  3896.7      .1       0  4268.5     .05       0  4369.2      .1       0
  4990.7     .07       0    5001      .1       0
Bank Sta=4990.7,5001
XS Rating Curve= 0 ,0
Exp/Cntr=0.3,0.1

Type RM Length L Ch R = 1 ,32710   ,30,30,30
BEGIN DESCRIPTION:
Mapping XS d83ff81a
END DESCRIPTION:
XS GIS Cut Line= 6
      2021476.19     13635995.05      2020286.12     13636330.98
      2020247.06     13636182.55      2020171.54     13636172.13
      2020200.18     13636377.86      2019622.07     13636575.77
#Sta/Elev= 30
  3861.8  739.32  4159.3  738.89  4262.4  738.78  4330.6   738.9  4362.8  737.62
  4569.6  736.71  4715.1  734.81  4933.3     735  4984.5  733.86  4987.4  733.79
  4990.5   731.3  4991.4   730.5  4999.8   730.5  5000.8   731.3  5026.8  735.05
  5055.4  737.05  5078.8  737.26  5087.7  734.26    5090  733.72    5101  733.72
  5202.3  733.37  5297.6  733.41  5536.6  734.23  5550.1  733.24    5559  733.48
  5566.4  735.34    5577  736.23  5735.5  736.95  6085.7   741.6  6161.4  741.23
#Mann= 11 ,-1 , 0
  3861.8      .1       0  4159.3     .08       0  4262.4      .1       0
  4984.5     .05       0  4990.5    .033       0  5000.8     .05       0
  5087.7     .07       0    5090      .1       0    5101     .07       0
  5202.3     .05       0  5297.6      .1       0
Bank Sta=4990.5,5000.8
XS Rating Curve= 0 ,0
Exp/Cntr=0.3,0.1

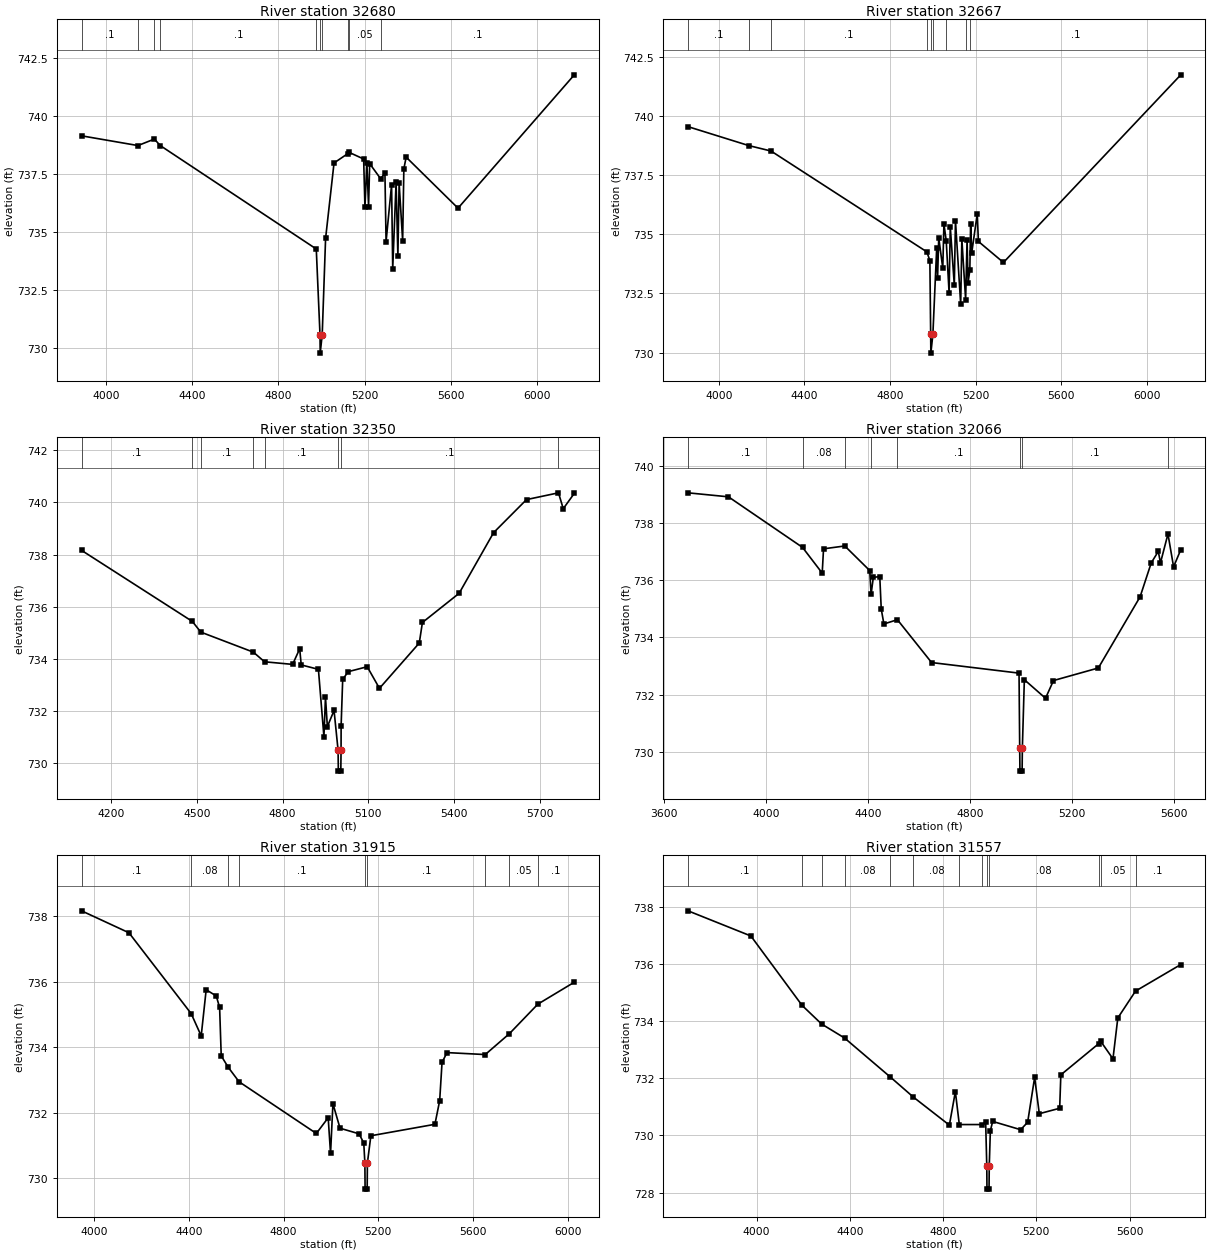
Type RM Length L Ch R = 1 ,32680   ,13,13,13
BEGIN DESCRIPTION:
Mapping XS dd1e1d7d
END DESCRIPTION:
XS GIS Cut Line= 6
      2021442.42     13635963.78      2020314.77     13636294.52
       2020213.2     13636138.27      2020106.43      13636216.4
      2020163.73     13636359.63      2019585.57     13636562.76
#Sta/Elev= 30
  3886.1  739.16    4148  738.74  4224.2  739.02  4251.5  738.74    4976  734.28
  4993.3  730.59  4994.3  729.79  5003.6  730.59  5019.3  734.74  5058.5  737.99
    5122  738.39  5127.7  738.45    5196  738.16    5202  736.08  5211.1  737.97
  5218.8  736.11    5224  737.96  5274.9  737.31  5294.8  737.55  5300.1   734.6
  5325.7  737.05    5331  733.43  5346.6  737.16    5355  733.96  5360.7  737.12
  5377.1  734.64  5382.7  737.74  5393.4  738.24  5634.2  736.04  6174.2  741.79
#Mann= 10 ,-1 , 0
  3886.1      .1       0    4148     .05       0  4224.2     .08       0
  4251.5      .1       0    4976     .05       0  4993.3    .033       0
  5003.6     .05       0    5122     .07       0  5127.7     .05       0
  5274.9      .1       0
Bank Sta=4993.3,5003.6
XS Rating Curve= 0 ,0
Exp/Cntr=0.3,0.1

Type RM Length L Ch R = 1 ,32667   ,317,317,317
BEGIN DESCRIPTION:
Mapping XS e4689445
END DESCRIPTION:
XS GIS Cut Line= 6
      2021463.19     13635927.34      2020351.23     13636271.09
      2020296.54     13636133.07      2020116.85     13636133.07
      2020127.27     13636346.61      2019596.04      13636536.7
#Sta/Elev= 30
  3856.6  739.55  4140.5  738.75  4244.5  738.52  4972.5  734.26  4986.7  733.89
  4990.4  730.78  4991.3  729.98  5000.8  730.78  5018.6  734.42  5022.7  733.16
  5028.1  734.86    5047  733.57  5052.3  735.44  5063.2  734.72  5076.6  732.51
    5082  735.33  5100.9  732.84  5106.3  735.58  5130.7  732.04  5136.1   734.8
  5153.8  732.24  5160.5  734.77  5165.2  732.96  5173.4  733.48  5177.1  735.42
  5182.3  734.22  5208.1  735.87  5213.4   734.7  5330.5  733.81  6159.1  741.74
#Mann= 9 ,-1 , 0
  3856.6      .1       0  4140.5     .05       0  4244.5      .1       0
  4972.5     .05       0  4990.4    .033       0  5000.8     .05       0
  5063.2     .07       0  5153.8     .05       0  5173.4      .1       0
Bank Sta=4990.4,5000.8
XS Rating Curve= 0 ,0
Exp/Cntr=0.3,0.1

Type RM Length L Ch R = 1 ,32350   ,284,284,284
BEGIN DESCRIPTION:
Mapping XS a2fa5a28
END DESCRIPTION:
XS GIS Cut Line= 2
      2021067.36     13635685.15      2019458.98     13636301.96
#Sta/Elev= 30
  4097.4  738.16  4484.7  735.43  4514.3  735.02    4698  734.25  4737.1  733.88
  4835.3  733.78    4860  734.38  4865.3  733.76  4925.4  733.59  4944.7     731
  4950.1  732.53  4956.7  731.39  4980.1  732.01  4994.2  730.48  4995.1  729.68
  5003.7  729.68  5004.6  730.48  5004.8  731.43  5010.3   733.2  5029.5   733.5
    5096  733.69  5138.8  732.86    5278   734.6    5289  735.39  5417.3  736.51
  5537.8  738.84  5652.9  740.11  5764.7  740.37  5781.3  739.76    5820  740.35
#Mann= 8 ,-1 , 0
  4097.4      .1       0  4484.7     .08       0  4514.3      .1       0
    4698     .08       0  4737.1      .1       0  4994.2     .07       0
  5004.6      .1       0  5764.7     .05       0
Bank Sta=4994.2,5004.6
XS Rating Curve= 0 ,0
Exp/Cntr=0.3,0.1

Type RM Length L Ch R = 1 ,32066   ,151,151,151
BEGIN DESCRIPTION:
Mapping XS a69cbb1c
END DESCRIPTION:
XS GIS Cut Line= 3
      2021304.33     13635437.76      2019796.15     13635859.62
      2019474.94     13636033.24
#Sta/Elev= 30
  3695.3  739.06  3853.8  738.92  4144.1  737.15  4221.2  736.25  4226.4   737.1
  4309.7   737.2  4407.4  736.34  4412.8  735.51  4421.5   736.1  4446.8  736.13
  4452.6  734.99    4463  734.47  4515.8  734.62  4649.9  733.12  4992.6  732.75
  4995.2  730.12  4996.1  729.32  5004.7  729.32  5005.6  730.12  5013.4  732.52
  5096.4  731.87  5127.6  732.49  5303.4  732.93    5467  735.42  5510.8  736.61
  5538.4  737.01  5546.9  736.61  5576.3  737.62  5598.3  736.47  5626.5  737.07
#Mann= 8 ,-1 , 0
  3695.3      .1       0  4144.1     .08       0  4309.7      .1       0
  4412.8     .08       0  4515.8      .1       0  4995.2     .07       0
  5005.6      .1       0  5576.3     .05       0
Bank Sta=4995.2,5005.6
XS Rating Curve= 0 ,0
Exp/Cntr=0.3,0.1

Type RM Length L Ch R = 1 ,31915   ,358,358,358
BEGIN DESCRIPTION:
Mapping XS 06165698
END DESCRIPTION:
XS GIS Cut Line= 4
      2020879.85     13635237.25      2020437.11     13635639.32
      2019256.16     13635677.91      2018995.71     13635824.89
#Sta/Elev= 30
    3948  738.16  4147.9  737.49  4410.5  735.02  4452.7  734.34  4473.7  735.75
  4516.2  735.56  4530.4  735.21  4537.2  733.73  4566.9  733.38  4612.4  732.94
  4938.4  731.36  4988.4  731.84  4998.4  730.75  5008.4  732.27  5038.4  731.52
  5118.5  731.35  5138.5  731.07  5143.2  730.46  5144.1  729.66  5152.9  729.66
  5153.8  730.46  5168.5  731.29  5438.6  731.64  5458.7  732.36  5468.7  733.53
  5489.6  733.83    5651  733.77  5753.2  734.41  5872.9  735.31  6026.7  735.98
#Mann= 9 ,-1 , 0
    3948      .1       0  4410.5     .08       0  4566.9     .05       0
  4612.4      .1       0  5143.2     .07       0  5153.8      .1       0
    5651     .08       0  5753.2     .05       0  5872.9      .1       0
Bank Sta=5143.2,5153.8
XS Rating Curve= 0 ,0
Exp/Cntr=0.3,0.1

Type RM Length L Ch R = 1 ,31557   ,220,220,220
BEGIN DESCRIPTION:
Mapping XS 1e92a35d
END DESCRIPTION:
XS GIS Cut Line= 4
      2020812.19      13635172.1      2020489.18     13635557.03
      2019258.27     13635582.87      2018964.25      13635823.8
#Sta/Elev= 30
  3706.1  737.86  3975.7  736.98  4195.4  734.55  4278.9   733.9  4377.4  733.41
  4574.4  732.04  4672.9  731.34  4827.2  730.36  4852.9  731.53  4869.9  730.38
  4968.4  730.38  4982.9  730.47  4987.7  728.92  4988.5  728.12  4997.4  728.12
  4998.3  728.92    5003  730.16    5013  730.49    5133   730.2    5163  730.46
    5193  732.03    5213  730.76  5300.4  730.95  5305.4  732.12  5467.7  733.21
  5475.9   733.3    5529  732.68  5549.8  734.11  5625.7  735.05  5819.9  735.98
#Mann= 13 ,-1 , 0
  3706.1      .1       0  4195.4     .08       0  4278.9     .05       0
  4377.4     .08       0  4574.4     .05       0  4672.9     .08       0
  4869.9     .05       0  4968.4     .08       0  4987.7     .07       0
  4998.3     .08       0  5467.7      .1       0  5475.9     .05       0
  5625.7      .1       0
Bank Sta=4987.7,4998.3
XS Rating Curve= 0 ,0
Exp/Cntr=0.3,0.1

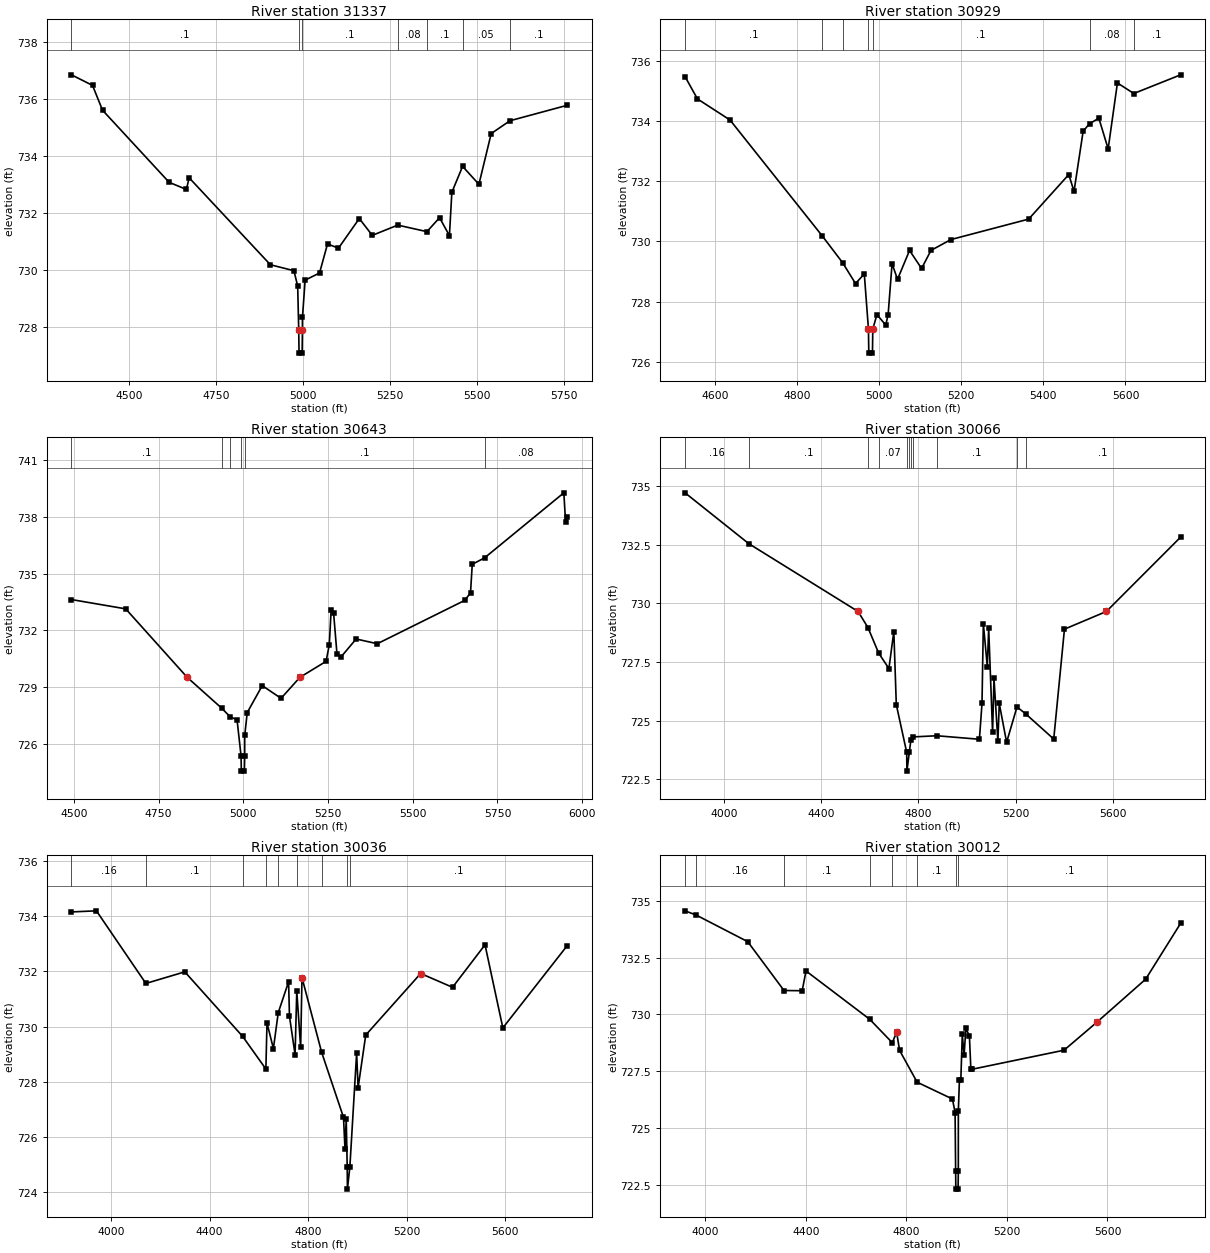
Type RM Length L Ch R = 1 ,31337   ,408,408,408
BEGIN DESCRIPTION:
Mapping XS ada66cb3
END DESCRIPTION:
XS GIS Cut Line= 4
      2020099.84     13635013.97      2019655.38     13635378.57
      2019214.94     13635549.48      2018945.79     13635814.03
#Sta/Elev= 30
  4335.3  736.84  4395.9  736.47  4424.6   735.6  4616.2  733.07  4665.8  732.82
  4673.6  733.23  4907.2  730.18  4974.9  729.97  4985.7  729.43  4988.7  727.88
  4989.6  727.08  4998.5  727.08  4999.3  727.88  4999.4  728.33  5007.1  729.64
  5048.5  729.89  5071.5  730.91  5102.9  730.76  5162.8   731.8  5200.2  731.21
  5273.4  731.57  5357.2  731.34  5393.6  731.83  5421.9   731.2  5428.9  732.72
  5459.8  733.63  5506.7     733    5542  734.78    5596  735.23    5760  735.77
#Mann= 7 ,-1 , 0
  4335.3      .1       0  4988.7     .07       0  4999.3      .1       0
  5273.4     .08       0  5357.2      .1       0  5459.8     .05       0
    5596      .1       0
Bank Sta=4988.7,4999.3
XS Rating Curve= 0 ,0
Exp/Cntr=0.3,0.1

Type RM Length L Ch R = 1 ,30929   ,286,286,286
BEGIN DESCRIPTION:
Mapping XS 149443fe
END DESCRIPTION:
XS GIS Cut Line= 3
       2019524.9     13634752.81       2019061.7      13635512.3
      2018922.97      13635798.9
#Sta/Elev= 30
  4526.5  735.47  4556.7  734.73  4636.1  734.03    4861  730.18  4910.7  729.29
    4942   728.6  4963.4  728.92  4973.5  727.09  4974.4  726.29  4983.3  726.29
  4984.1  727.09  4994.3  727.57  5015.6  727.22  5021.5  727.57  5031.1  729.26
  5044.4  728.74  5073.7   729.7    5103   729.1  5125.9   729.7  5174.4  730.06
  5364.1  730.74  5461.9  732.22  5474.6  731.66  5496.9  733.66  5512.6  733.91
  5535.2  734.09  5557.8  733.07  5580.4  735.26  5620.4  734.91  5734.5  735.53
#Mann= 7 ,-1 , 0
  4526.5      .1       0    4861     .12       0  4910.7      .1       0
  4973.5     .07       0  4984.1      .1       0  5512.6     .08       0
  5620.4      .1       0
Bank Sta=4973.5,4984.1
XS Rating Curve= 0 ,0
Exp/Cntr=0.3,0.1

Type RM Length L Ch R = 1 ,30643   ,577,577,577
BEGIN DESCRIPTION:
Mapping XS 31fa0e8b
END DESCRIPTION:
XS GIS Cut Line= 3
      2019239.56      13634586.8       2018773.9     13635562.17
      2018398.43     13635631.27
#Sta/Elev= 30
  4492.6  733.63  4652.7  733.14 4834.14 729.528  4936.7  727.89  4960.1  727.46
  4981.4  727.28  4993.2  725.38    4994  724.58    5003  724.58  5003.9  725.38
    5004  726.46  5011.4  727.67  5055.7  729.09  5111.2  728.42  5166.9729.5281
  5244.1  730.37  5253.6  731.25  5259.1   733.1  5266.3  732.92  5276.3  730.75
  5288.5  730.61  5332.8  731.55  5395.3   731.3  5653.7  733.59  5670.4  733.99
  5675.5  735.49  5711.9  735.83  5945.8  739.26  5950.9  737.72  5955.2  737.98
#Mann= 6 ,-1 , 0
  4492.6      .1       0  4936.7     .12       0  4960.1      .1       0
  4993.2     .07       0  5003.9      .1       0  5711.9     .08       0
Bank Sta=4834.14,5166.9
XS Rating Curve= 0 ,0
Exp/Cntr=0.3,0.1

Type RM Length L Ch R = 1 ,30066   ,30,30,30
BEGIN DESCRIPTION:
Mapping XS 81c5dc5d
END DESCRIPTION:
XS GIS Cut Line= 6
      2019293.91      13634148.3      2018814.23     13634849.35
      2018532.11     13634764.71      2018829.42     13635040.32
      2018846.78     13635144.48      2018662.29     13635426.64
#Sta/Elev= 30
  3840.1  734.72  4102.3  732.55 4551.87729.6553  4592.5  728.97  4636.5  727.88
  4678.8  727.22    4699   728.8  4709.2  725.68    4752  723.64  4752.8  722.84
  4762.7  723.64    4769  724.15  4776.3   724.3  4876.2  724.35  5051.1   724.2
  5061.8  725.73  5067.3  729.14  5083.6   727.3  5089.3  728.93  5105.3  724.49
  5111.1   726.8  5127.1  724.12  5132.8  725.73    5163  724.07  5205.7  725.58
  5240.9  725.29  5356.9  724.21    5401   728.9 5573.49729.6555    5879  732.83
#Mann= 11 ,-1 , 0
  3840.1     .16       0  4102.3      .1       0  4592.5     .05       0
  4636.5     .07       0    4752     .07       0  4762.7     .07       0
    4769     .05       0  4776.3     .07       0  4876.2      .1       0
  5205.7     .12       0  5240.9      .1       0
Bank Sta=4551.87,5573.49
XS Rating Curve= 0 ,0
Exp/Cntr=0.3,0.1

Type RM Length L Ch R = 1 ,30036   ,24,24,24
BEGIN DESCRIPTION:
Mapping XS 812b4bfa
END DESCRIPTION:
XS GIS Cut Line= 6
      2019231.02     13634130.87      2018807.72     13634827.64
      2018746.96      13634736.5      2018510.41     13634749.52
      2018786.02      13635070.7      2018640.61     13635417.94
#Sta/Elev= 30
  3839.8  734.15  3941.1  734.19  4141.7  731.56  4299.6  731.98  4534.3  729.64
  4628.4  728.46  4632.9  730.13  4658.9   729.2  4678.5   730.5  4720.5  731.62
  4724.1  730.37  4746.8  728.98  4753.7  731.28  4769.4  729.24  4774.9  731.77
  4854.4  729.07  4943.2  726.71  4949.2  725.58  4954.3  726.65  4958.3  724.91
  4959.1  724.11    4969  724.91  4996.5  729.04  5002.4  727.78  5033.4  729.69
  5256.2  731.92  5385.5  731.42  5517.2  732.96  5589.5  729.95  5849.8  732.92
#Mann= 9 ,-1 , 0
  3839.8     .16       0  4141.7      .1       0  4534.3     .05       0
  4628.4     .07       0  4678.5     .05       0  4753.7     .07       0
  4854.4      .1       0  4958.3     .07       0    4969      .1       0
Bank Sta=4774.9,5256.2
XS Rating Curve= 0 ,0
Exp/Cntr=0.3,0.1

Type RM Length L Ch R = 1 ,30012   ,79,79,79
BEGIN DESCRIPTION:
Mapping XS aa7da357
END DESCRIPTION:
XS GIS Cut Line= 6
      2019235.35     13634083.13      2018831.59     13634732.16
      2018542.96     13634708.29      2018473.52      13634758.2
       2018736.1     13635133.63      2018573.32     13635417.96
#Sta/Elev= 30
  3919.5  734.56  3964.4  734.37    4169   733.2  4313.1  731.05  4385.4  731.04
  4400.8  731.91  4654.4  729.78    4744  728.75  4761.2  729.21  4773.1  728.41
  4842.9  727.01  4983.4  726.27  4993.8  725.67    4996   723.1  4996.8   722.3
  5005.8   722.3  5006.7   723.1  5006.8  725.73  5011.1  727.12  5016.7  727.12
  5022.5  729.12  5029.6  728.19  5036.7  729.38  5050.8  729.05  5056.6  727.58
  5061.2  727.58  5427.3  728.42  5557.7  729.65  5752.1  731.55  5891.2  734.01
#Mann= 8 ,-1 , 0
  3919.5      .1       0  3964.4     .16       0  4313.1      .1       0
  4654.4     .05       0    4744     .07       0  4842.9      .1       0
    4996     .07       0  5006.7      .1       0
Bank Sta=4761.2,5557.7
XS Rating Curve= 0 ,0
Exp/Cntr=0.3,0.1

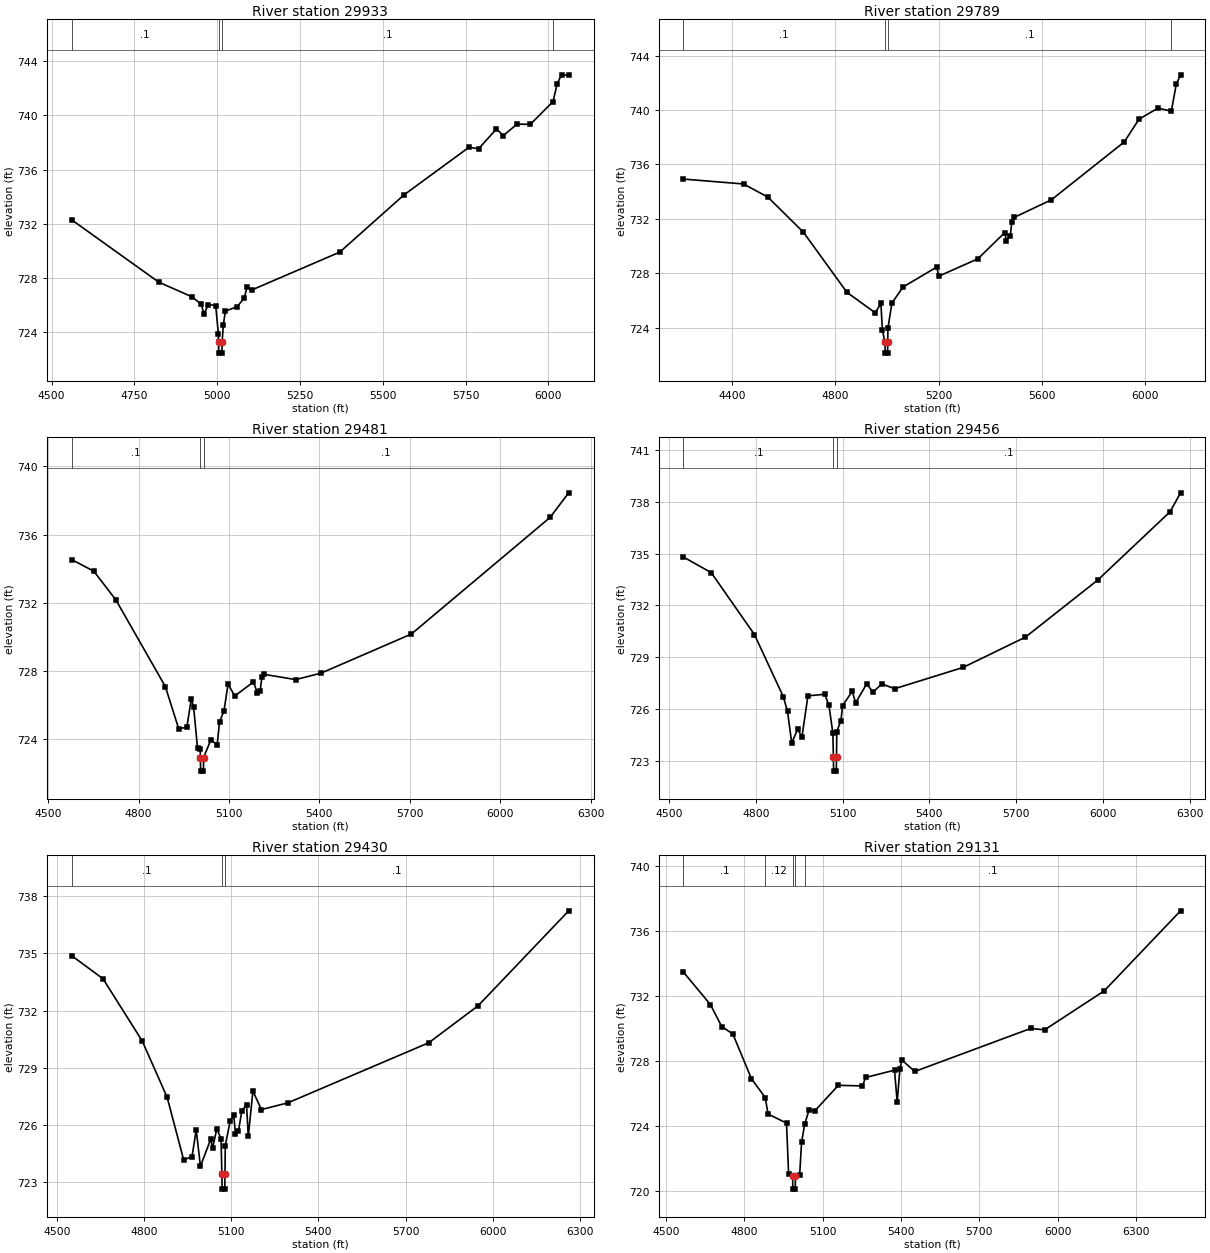
Type RM Length L Ch R = 1 ,29933   ,144,144,144
BEGIN DESCRIPTION:
Mapping XS 82dc421d
END DESCRIPTION:
XS GIS Cut Line= 3
       2018727.4     13634282.98      2018238.81     13635014.84
      2018081.84     13635615.92
#Sta/Elev= 30
  4560.2   732.3  4823.4   727.7  4923.3  726.62  4952.6  726.06  4959.4  725.34
  4973.6  726.04  4995.5  725.97  5003.6  723.88  5004.2  723.26    5005  722.46
  5014.2  722.46    5015  723.26  5018.6  724.54  5024.7  725.56  5060.7  725.89
  5081.7  726.53  5090.7  727.36  5103.7  727.11  5370.1  729.91  5564.4  734.14
  5760.7  737.65  5789.1  737.53  5843.4     739  5864.1  738.51  5905.3  739.35
  5945.8  739.34  6014.2  741.02  6026.7  742.34  6039.8  742.99  6061.4  742.97
#Mann= 4 ,-1 , 0
  4560.2      .1       0  5004.2     .07       0    5015      .1       0
  6014.2     .08       0
Bank Sta=5004.2,5015
XS Rating Curve= 0 ,0
Exp/Cntr=0.3,0.1

Type RM Length L Ch R = 1 ,29789   ,308,308,308
BEGIN DESCRIPTION:
Mapping XS cf87c01c
END DESCRIPTION:
XS GIS Cut Line= 3
      2018790.19     13633889.34      2018042.02     13635119.65
      2017964.88     13635601.48
#Sta/Elev= 30
  4210.5  734.92  4443.6  734.56  4538.5  733.59  4676.1  731.01  4844.6   726.6
  4954.5  725.09  4976.4  725.78  4982.2  723.83  4992.3  722.93  4993.1  722.13
  5002.3  722.13  5003.1  722.93  5003.5  723.95    5019   725.8  5061.7  726.98
  5193.4  728.46  5200.3  727.78  5352.4  729.06  5456.9  730.99  5462.7   730.4
  5478.2  730.76  5484.1  731.79  5492.8   732.1  5637.1  733.39  5920.2  737.65
  5977.2  739.32  6050.8  740.13  6102.8  739.91  6121.7  741.89  6138.4  742.58
#Mann= 4 ,-1 , 0
  4210.5      .1       0  4992.3     .07       0  5003.1      .1       0
  6102.8     .08       0
Bank Sta=4992.3,5003.1
XS Rating Curve= 0 ,0
Exp/Cntr=0.3,0.1

Type RM Length L Ch R = 1 ,29481   ,25,25,25
BEGIN DESCRIPTION:
Mapping XS 0f797096
END DESCRIPTION:
XS GIS Cut Line= 4
      2018595.02     13634040.33      2018187.06     13634331.12
      2017959.65     13634791.32      2017949.75     13635427.03
#Sta/Elev= 30
  4577.2  734.53  4651.3  733.84  4724.6  732.15  4888.6  727.06  4932.8  724.59
  4959.9  724.66  4974.6  726.33  4982.5  725.84  4995.5  723.43  5004.1  723.39
  5004.9  722.89  5005.7  722.09  5014.9  722.09  5015.7  722.89  5039.8  723.94
  5060.7  723.64  5068.4  724.99  5083.1  725.62  5096.7   727.2  5119.1  726.51
  5180.9  727.33  5194.1  726.69  5203.3   726.8  5208.9  727.61  5216.4  727.78
  5321.1  727.47  5405.3  727.85  5705.2  730.15  6165.3     737  6227.3  738.45
#Mann= 3 ,-1 , 0
  4577.2      .1       0  5004.9     .07       0  5015.7      .1       0
Bank Sta=5004.9,5015.7
XS Rating Curve= 0 ,0
Exp/Cntr=0.3,0.1

Type RM Length L Ch R = 1 ,29456   ,26,26,26
BEGIN DESCRIPTION:
Mapping XS af09409f
END DESCRIPTION:
XS GIS Cut Line= 4
      2018595.01     13633990.43      2018156.68     13634326.78
      2017902.83     13634818.85      2017926.27      13635431.1
#Sta/Elev= 30
  4549.4   734.8  4645.6   733.9  4795.1  730.32  4894.8  726.73  4909.4  725.88
  4923.9  724.06  4944.7  724.86  4959.2  724.39    4980  726.78  5038.1  726.87
  5052.6  726.23  5066.2  724.63    5068  723.23  5068.8  722.43    5078  722.43
  5078.8  723.23  5079.7  724.71  5094.2  725.35  5099.8  726.22  5133.2  727.04
  5144.9  726.38  5183.1  727.47  5205.3  726.99  5234.9  727.47  5279.9  727.19
  5516.2  728.42  5731.8  730.17    5982  733.47  6232.2  737.42  6268.3  738.51
#Mann= 3 ,-1 , 0
  4549.4      .1       0    5068     .07       0  5078.8      .1       0
Bank Sta=5068,5078.8
XS Rating Curve= 0 ,0
Exp/Cntr=0.3,0.1

Type RM Length L Ch R = 1 ,29430   ,299,299,299
BEGIN DESCRIPTION:
Mapping XS 2182f731
END DESCRIPTION:
XS GIS Cut Line= 4
      2018584.19     13633973.05      2018145.83     13634300.73
      2017870.05     13634820.77      2017908.09     13635395.78
#Sta/Elev= 30
  4549.8  734.89  4658.3  733.67  4793.7  730.39  4879.2  727.44  4935.8  724.17
  4964.6  724.31  4979.2  725.73  4993.8  723.82  5029.3  725.25  5035.7  724.78
  5050.1  725.79  5064.7  725.27  5067.6  723.42  5068.4  722.62  5077.6  722.62
  5078.4  723.42  5079.3  724.91  5096.5  726.22  5108.6   726.5  5114.2  725.52
  5124.6  725.65  5136.2  726.73  5152.5  727.06  5158.5  725.39  5174.5  727.77
  5203.8   726.8  5294.4  727.15  5780.2  730.31  5950.5  732.26    6262  737.24
#Mann= 3 ,-1 , 0
  4549.8      .1       0  5067.6     .07       0  5078.4      .1       0
Bank Sta=5067.6,5078.4
XS Rating Curve= 0 ,0
Exp/Cntr=0.3,0.1

Type RM Length L Ch R = 1 ,29131   ,278,278,278
BEGIN DESCRIPTION:
Mapping XS 92012729
END DESCRIPTION:
XS GIS Cut Line= 4
      2018373.26     13633747.34      2017925.34     13634104.12
      2017771.69     13634828.46      2017842.26     13635415.43
#Sta/Elev= 30
  4566.5  733.46    4670  731.46  4713.3  730.11    4756  729.65    4827  726.91
  4879.8  725.75    4891  724.73  4961.5  724.18  4969.5  721.04  4984.9  720.92
  4985.7  720.12    4995  720.12  4995.7  720.92  5011.7  720.96  5019.2  723.01
  5031.3  724.12    5048  724.99  5068.8  724.91  5160.1   726.5  5252.5  726.46
  5264.5  726.98  5375.2  727.43  5385.4  725.47  5395.6  727.48  5403.3  728.05
  5452.9  727.35  5896.3  729.99  5950.4  729.91  6178.3   732.3  6470.8  737.22
#Mann= 5 ,-1 , 0
  4566.5      .1       0  4879.8     .12       0  4984.9     .07       0
  4995.7     .12       0  5031.3      .1       0
Bank Sta=4984.9,4995.7
XS Rating Curve= 0 ,0
Exp/Cntr=0.3,0.1

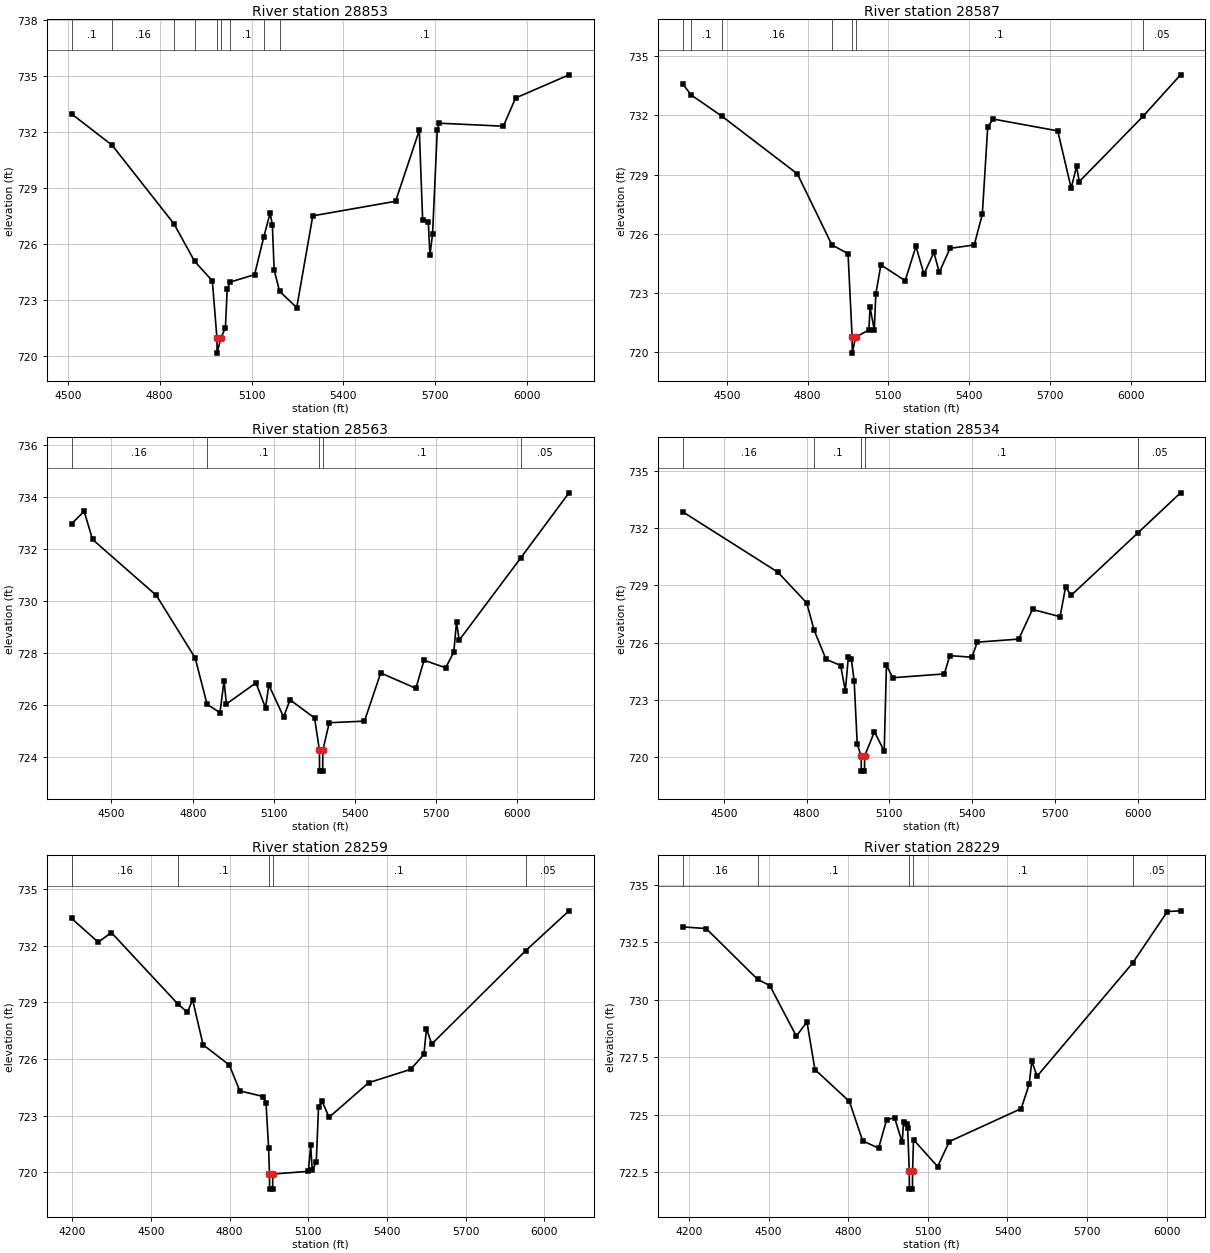
Type RM Length L Ch R = 1 ,28853   ,266,266,266
BEGIN DESCRIPTION:
Mapping XS f5ca29eb
END DESCRIPTION:
XS GIS Cut Line= 4
      2018360.21     13633510.38      2017467.01     13634049.43
      2017360.24     13634309.85      2017060.73     13634322.87
#Sta/Elev= 30
  4512.3  732.96  4644.9  731.28  4846.9  727.07    4914  725.07  4972.1  724.02
  4987.1  720.95  4987.6  720.15  4999.7  720.95  5014.8  721.51  5020.6  723.59
  5031.2  723.96  5109.9  724.35  5140.1  726.37  5160.8  727.65  5168.1  727.02
  5173.9   724.6  5191.7  723.46  5247.7  722.59  5300.1   727.5  5570.5  728.28
  5647.9  732.08  5658.8  727.29  5677.3  727.19  5682.7  725.39  5691.3  726.55
  5706.7  732.12  5712.9  732.46  5922.3   732.3  5962.4  733.81  6136.8  735.05
#Mann= 9 ,-1 , 0
  4512.3      .1       0  4644.9     .16       0  4846.9      .1       0
    4914     .05       0  4987.1    .035       0  4999.7     .05       0
  5031.2      .1       0  5140.1     .05       0  5191.7      .1       0
Bank Sta=4987.1,4999.7
XS Rating Curve= 0 ,0
Exp/Cntr=0.3,0.1

Type RM Length L Ch R = 1 ,28587   ,24,24,24
BEGIN DESCRIPTION:
Mapping XS a0e271c5
END DESCRIPTION:
XS GIS Cut Line= 6
      2018451.19     13633295.53      2017836.63     13633519.48
      2017792.35     13633579.38      2017797.56      13633657.5
      2017792.35     13633764.28      2016858.73     13633779.88
#Sta/Elev= 30
  4337.7  733.57  4366.9  733.04  4483.3  731.94  4762.5  729.03  4890.8  725.43
  4950.6  724.99  4965.8  720.75  4966.3  719.95  4978.4  720.75  5028.2  721.13
  5032.3  722.27  5048.1  721.13  5053.8  722.95  5072.6  724.42  5162.8  723.62
  5202.8  725.36  5232.8  723.95  5269.5  725.06  5289.5  724.04  5329.5  725.26
  5419.5  725.43  5449.5  726.99  5469.5   731.4  5489.5  731.81  5729.6  731.21
  5779.6  728.31  5799.6  729.41  5809.6  728.64    6046  731.94  6185.9  734.05
#Mann= 7 ,-1 , 0
  4337.7     .16       0  4366.9      .1       0  4483.3     .16       0
  4890.8      .1       0  4965.8     .07       0  4978.4      .1       0
    6046     .05       0
Bank Sta=4965.8,4978.4
XS Rating Curve= 0 ,0
Exp/Cntr=0.3,0.1

Type RM Length L Ch R = 1 ,28563   ,29,29,29
BEGIN DESCRIPTION:
Mapping XS f7473185
END DESCRIPTION:
XS GIS Cut Line= 6
      2018425.17     13633274.69      2017834.02     13633490.84
       2017761.1     13633558.55      2017748.08     13633613.23
      2017763.71     13633730.42      2016829.37     13633748.64
#Sta/Elev= 30
  4352.4  732.97  4399.1  733.45  4429.9  732.37  4665.7  730.22    4809  727.82
  4853.4  726.03  4900.9  725.72  4915.8  726.94  4924.6  726.05  5033.9  726.86
  5069.1   725.9  5081.4  726.78    5136  725.55  5159.6  726.21  5250.4  725.51
  5268.3  724.27  5268.8  723.47  5280.4  723.47  5280.9  724.27  5304.6  725.33
  5434.6  725.39  5494.6  727.24  5624.7  726.65  5654.7  727.73  5734.7  727.44
  5764.7  728.04  5774.7  729.19  5784.7   728.5  6012.1  731.66  6190.4  734.16
#Mann= 5 ,-1 , 0
  4352.4     .16       0  4853.4      .1       0  5268.3     .07       0
  5280.9      .1       0  6012.1     .05       0
Bank Sta=5268.3,5280.9
XS Rating Curve= 0 ,0
Exp/Cntr=0.3,0.1

Type RM Length L Ch R = 1 ,28534   ,275,275,275
BEGIN DESCRIPTION:
Mapping XS 86d522f0
END DESCRIPTION:
XS GIS Cut Line= 6
      2018420.01     13633261.66      2017964.23     13633415.32
      2017789.75     13633483.03      2017735.06     13633545.53
      2017729.85     13633696.57      2016828.14     13633699.17
#Sta/Elev= 30
  4351.8  732.86  4695.5   729.7  4800.3  728.08  4827.3  726.64  4870.3  725.12
  4923.3  724.79  4940.4  723.46  4951.3  725.25  4961.8  725.16  4972.4  723.97
  4983.5  720.65  4997.7  720.04  4998.2  719.24  5009.8  719.24  5010.3  720.04
    5046  721.31  5081.3  720.29  5089.4   724.8  5112.7  724.15  5299.2  724.35
  5319.2  725.31  5399.2  725.23  5419.2  726.02  5569.2  726.18  5619.2  727.74
  5719.2  727.36  5739.2  728.92  5759.2  728.48  6002.6  731.78  6156.1  733.87
#Mann= 5 ,-1 , 0
  4351.8     .16       0  4827.3      .1       0  4997.7     .07       0
  5010.3      .1       0  6002.6     .05       0
Bank Sta=4997.7,5010.3
XS Rating Curve= 0 ,0
Exp/Cntr=0.3,0.1

Type RM Length L Ch R = 1 ,28259   ,30,30,30
BEGIN DESCRIPTION:
Mapping XS acb71e50
END DESCRIPTION:
XS GIS Cut Line= 6
      2018466.83     13633238.23      2017656.94     13633243.44
      2017641.31     13633264.28       2017633.5     13633290.32
      2017667.35     13633347.61      2016703.84     13633438.75
#Sta/Elev= 30
    4197  733.44  4298.8  732.18  4348.8  732.69  4601.2  728.93  4638.8  728.47
  4658.8  729.13  4698.8  726.75  4798.8  725.68  4838.8  724.31  4928.8  724.01
  4938.8  723.66  4948.8  721.27  4951.9  719.91  4952.4  719.11    4964  719.11
  4964.5  719.91  5100.4  720.05  5109.2  721.43    5115  720.12  5130.4  720.53
  5139.1  723.45  5153.1  723.75  5179.3  722.91  5329.9  724.74  5490.7  725.45
  5540.9  726.24  5550.9   727.6    5571  726.79  5929.1  731.73  6094.5  733.84
#Mann= 5 ,-1 , 0
    4197     .16       0  4601.2      .1       0  4951.9     .07       0
  4964.5      .1       0  5929.1     .05       0
Bank Sta=4951.9,4964.5
XS Rating Curve= 0 ,0
Exp/Cntr=0.3,0.1

Type RM Length L Ch R = 1 ,28229   ,13,13,13
BEGIN DESCRIPTION:
Mapping XS 796b7778
END DESCRIPTION:
XS GIS Cut Line= 6
      2018472.03      13633217.4      2017649.13      13633217.4
      2017623.08     13633240.84      2017604.85     13633290.32
      2017607.46     13633329.38      2016685.61     13633391.88
#Sta/Elev= 30
  4177.3  733.16  4264.3  733.09  4458.3  730.88  4504.3  730.61  4604.3  728.41
  4644.3  729.03  4674.3  726.96  4804.3  725.57  4854.3  723.86  4914.3  723.54
  4944.3  724.77  4974.4  724.87  5003.2  723.79  5008.3  724.66  5020.7  724.57
  5023.8  724.43  5029.8  722.56  5030.3  721.76  5041.9  721.76  5042.4  722.56
  5045.9  723.91  5136.8  722.74    5181  723.83  5451.6  725.26  5481.7  726.31
  5491.7  727.32  5511.8  726.67  5871.8  731.59  6002.9  733.83  6052.4  733.86
#Mann= 5 ,-1 , 0
  4177.3     .16       0  4458.3      .1       0  5029.8     .07       0
  5042.4      .1       0  5871.8     .05       0
Bank Sta=5029.8,5042.4
XS Rating Curve= 0 ,0
Exp/Cntr=0.3,0.1