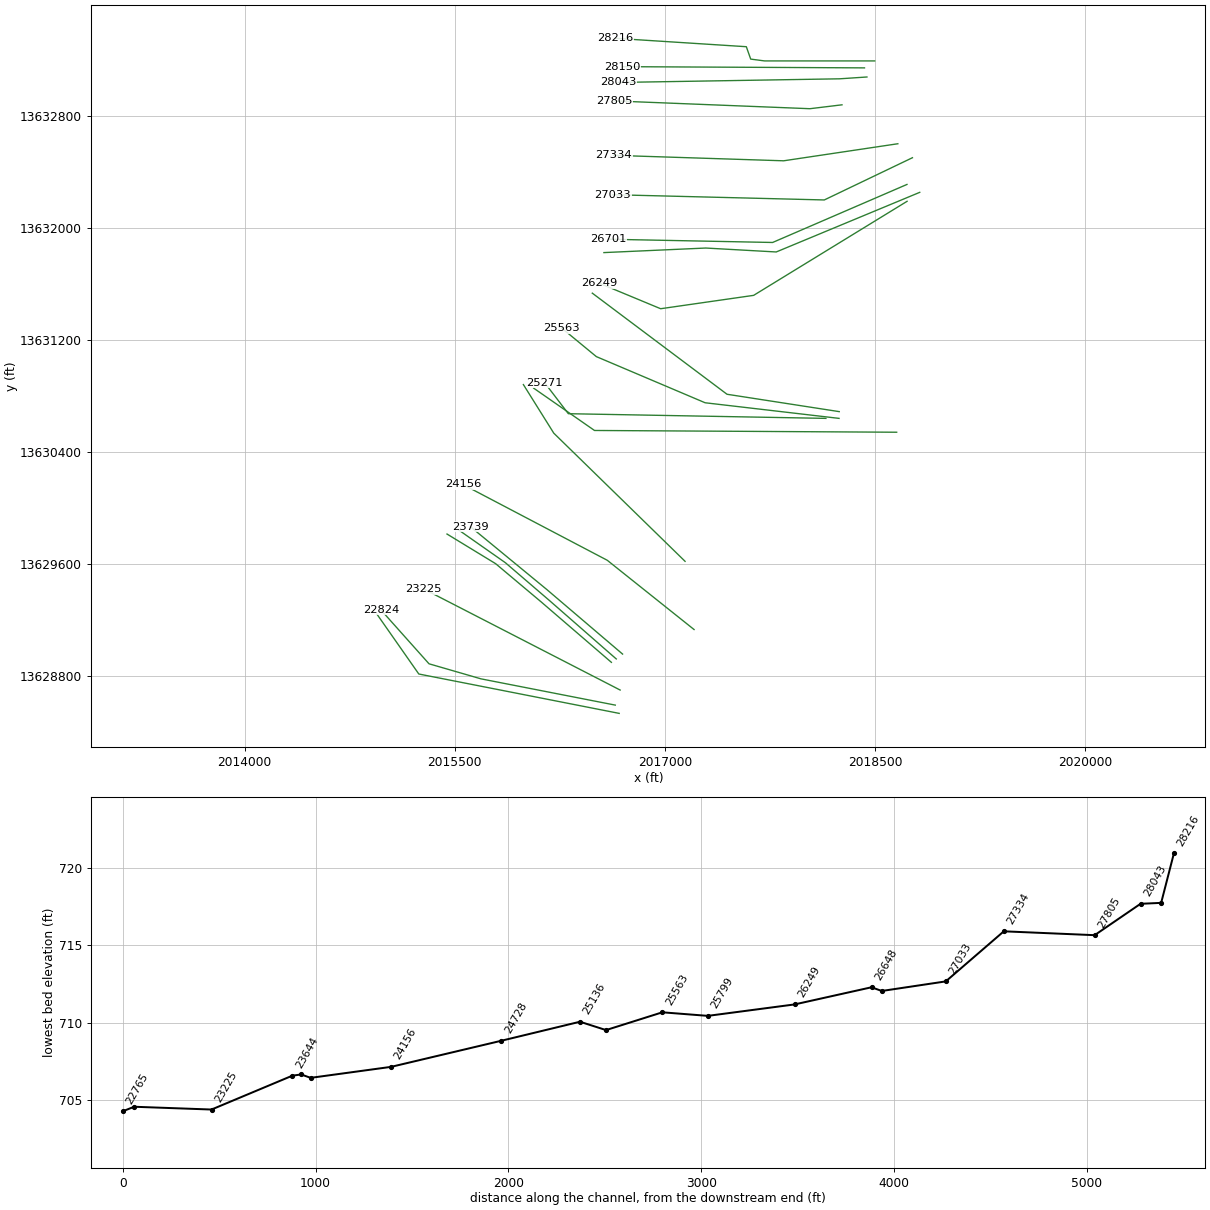
HEC-RAS study FORT EWELL CREEK.prj: FORT EWELL CREEK Base Level Engineering

--- FORT EWELL CREEK.g01 (geometry) --- (continued)

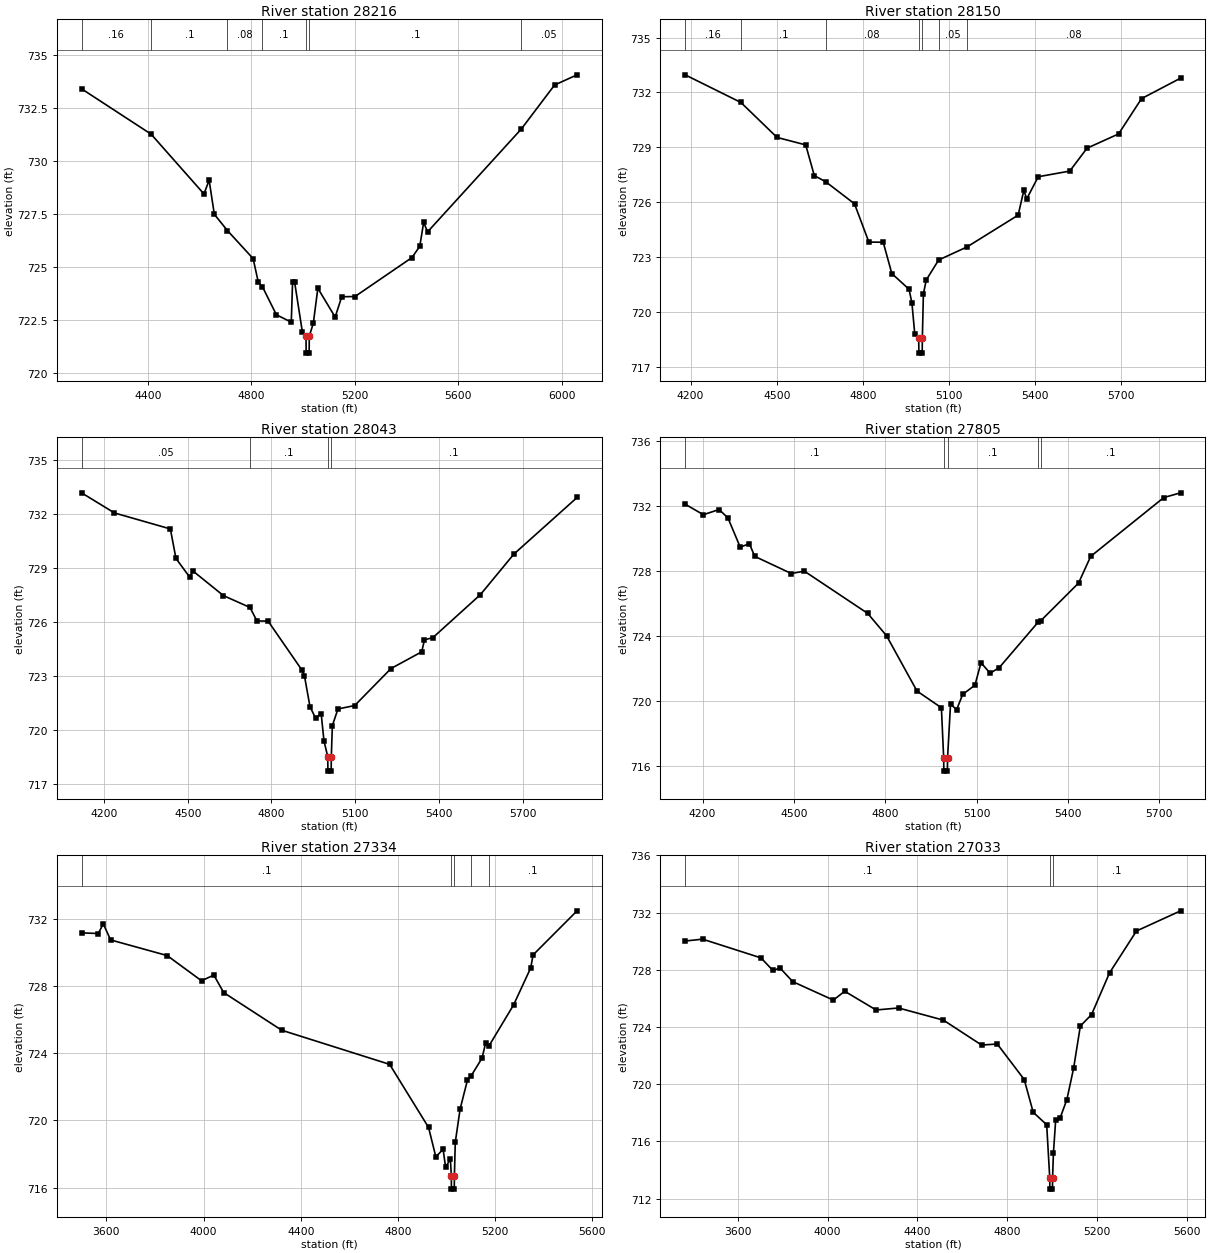
Type RM Length L Ch R = 1 ,28216   ,66,66,66
BEGIN DESCRIPTION:
Mapping XS 8c7be8ad
END DESCRIPTION:
XS GIS Cut Line= 5
      2018498.13     13633196.57      2017711.63     13633196.57
      2017612.67     13633209.59      2017581.42     13633298.13
      2016648.24     13633357.92
#Sta/Elev= 30
  4144.2  733.42    4413  731.28  4617.3  728.46  4637.3  729.11  4657.3   727.5
  4708.2  726.73  4807.3  725.41  4827.3   724.3  4843.4  724.08  4897.3  722.76
  4954.8  722.41  4959.8  724.29  4967.6  724.31  4997.9  721.93  5011.8  721.75
  5012.3  720.95  5023.9  720.95  5024.4  721.75    5040  722.36  5057.5  724.01
  5124.4  722.65  5149.8  723.61    5201  723.62  5421.4  725.46  5451.5  725.99
  5466.5  727.12  5481.6  726.67  5843.7  731.52  5972.6   733.6  6059.5  734.08
#Mann= 7 ,-1 , 0
  4144.2     .16       0    4413      .1       0  4708.2     .08       0
  4843.4      .1       0  5011.8     .07       0  5024.4      .1       0
  5843.7     .05       0
Bank Sta=5011.8,5024.4
XS Rating Curve= 0 ,0
Exp/Cntr=0.3,0.1

Type RM Length L Ch R = 1 ,28150   ,107,107,107
BEGIN DESCRIPTION:
Mapping XS a05de575
END DESCRIPTION:
XS GIS Cut Line= 2
      2018425.13     13633146.87      2016698.85     13633155.55
#Sta/Elev= 30
    4181  732.96  4375.3  731.45  4501.1  729.54  4601.1  729.13  4631.1  727.45
  4670.5  727.12  4771.1  725.91  4821.1  723.82  4871.1  723.81  4901.1   722.1
  4961.1  721.24  4971.1  720.49  4981.1  718.78  4994.8  718.55  4995.3  717.75
  5006.9  717.75  5007.4  718.55  5011.1  720.99  5021.1  721.75  5064.2  722.84
  5162.6  723.55  5341.1  725.29  5361.1  726.65  5371.1  726.18  5411.1  727.39
  5521.1   727.7  5581.1  728.95  5691.1  729.73  5771.1  731.66  5907.3  732.78
#Mann= 7 ,-1 , 0
    4181     .16       0  4375.3      .1       0  4670.5     .08       0
  4994.8     .07       0  5007.4     .08       0  5064.2     .05       0
  5162.6     .08       0
Bank Sta=4994.8,5007.4
XS Rating Curve= 0 ,0
Exp/Cntr=0.3,0.1

Type RM Length L Ch R = 1 ,28043   ,238,238,238
BEGIN DESCRIPTION:
FORT EWELL CREEK 36.0
END DESCRIPTION:
XS GIS Cut Line= 3
      2018442.53     13633081.77      2018247.22     13633068.75
      2016668.68     13633042.73
#Sta/Elev= 30
  4119.9  733.18  4237.7  732.06  4437.9  731.17  4457.9  729.53  4507.9  728.47
  4517.9  728.84  4627.9  727.46    4723   726.8  4747.9  726.05  4787.9  726.04
  4907.9  723.34  4917.9  723.01    4938  721.27    4958  720.64    4978  720.89
    4988  719.37  5001.6  718.49  5002.1  717.69  5013.8  717.69  5014.3  718.49
    5018  720.22    5038  721.15    5098  721.34    5228   723.4    5338  724.33
    5348     725    5378  725.12    5548  727.51  5668.1  729.77  5894.4  732.92
#Mann= 4 ,-1 , 0
  4119.9     .05       0    4723      .1       0  5001.6     .07       0
  5014.3      .1       0
Bank Sta=5001.6,5014.3
XS Rating Curve= 0 ,0
Exp/Cntr=0.3,0.1

Type RM Length L Ch R = 1 ,27805   ,471,471,471
BEGIN DESCRIPTION:
FORT EWELL CREEK 35.0
END DESCRIPTION:
XS GIS Cut Line= 3
      2018264.54     13632882.98      2018035.41      13632855.2
      2016639.82     13632910.75
#Sta/Elev= 30
  4142.8  732.13  4202.8  731.48  4254.4   731.8  4283.4  731.28  4323.7  729.48
  4353.9  729.69  4371.3  728.91  4491.7  727.85  4534.1     728  4742.5  725.39
  4804.4  724.01  4904.4   720.6  4984.5  719.57    4992  716.46  4992.5  715.66
  5004.2  715.66  5004.7  716.46  5014.5   719.8  5034.5  719.45  5054.6   720.4
  5094.6  720.96  5114.6  722.35  5144.6   721.7  5174.7  722.05  5302.2  724.85
  5311.6  724.95  5434.9  727.26  5474.9  728.91  5715.1  732.54  5770.3  732.83
#Mann= 5 ,-1 , 0
  4142.8      .1       0    4992     .07       0  5004.7      .1       0
  5302.2     .07       0  5311.6      .1       0
Bank Sta=4992,5004.7
XS Rating Curve= 0 ,0
Exp/Cntr=0.3,0.1

Type RM Length L Ch R = 1 ,27334   ,301,301,301
BEGIN DESCRIPTION:
FORT EWELL CREEK 34.0
END DESCRIPTION:
XS GIS Cut Line= 3
       2018663.2     13632604.85      2017847.69     13632483.03
      2016634.18     13632522.09
#Sta/Elev= 30
  3498.2  731.15  3567.2  731.11  3587.4  731.69  3617.7  730.73  3850.3   729.8
  3991.8   728.3  4042.4  728.64  4082.8   727.6  4321.6  725.36  4765.7  723.33
  4925.8  719.58  4955.8  717.83  4985.8  718.28  4995.8  717.22  5015.8  717.69
  5019.5  716.71    5020  715.91  5031.7  715.91  5032.2  716.71  5035.8   718.7
  5055.8  720.68  5085.8  722.39  5100.8  722.64  5145.9   723.7    5161  724.62
  5174.1  724.42  5275.9  726.87    5346  729.06    5356  729.84  5536.9  732.46
#Mann= 5 ,-1 , 0
  3498.2      .1       0  5019.5     .07       0  5032.2      .1       0
  5100.8     .07       0  5174.1      .1       0
Bank Sta=5019.5,5032.2
XS Rating Curve= 0 ,0
Exp/Cntr=0.3,0.1

Type RM Length L Ch R = 1 ,27033   ,332,332,332
BEGIN DESCRIPTION:
Mapping XS 30949f8f
END DESCRIPTION:
XS GIS Cut Line= 3
      2018767.38     13632505.02      2018138.21      13632203.3
      2016628.15     13632240.79
#Sta/Elev= 30
  3364.8  730.01  3442.7  730.14  3702.9  728.83  3755.6  727.96    3788  728.12
  3844.4  727.17  4025.6  725.88  4075.8   726.5  4215.8  725.19  4315.9  725.33
  4515.9  724.48    4686  722.74    4756  722.81    4876  720.33    4916  718.04
  4976.1  717.17  4989.7  713.47  4990.2  712.67  5001.9  712.67  5002.4  713.47
  5006.1  715.18  5016.1  717.48  5036.1  717.65  5066.1  718.93  5096.1  721.12
  5126.1  724.07  5176.1  724.87  5256.1  727.78  5376.2  730.71  5573.1  732.12
#Mann= 3 ,-1 , 0
  3364.8      .1       0  4989.7     .07       0  5002.4      .1       0
Bank Sta=4989.7,5002.4
XS Rating Curve= 0 ,0
Exp/Cntr=0.3,0.1

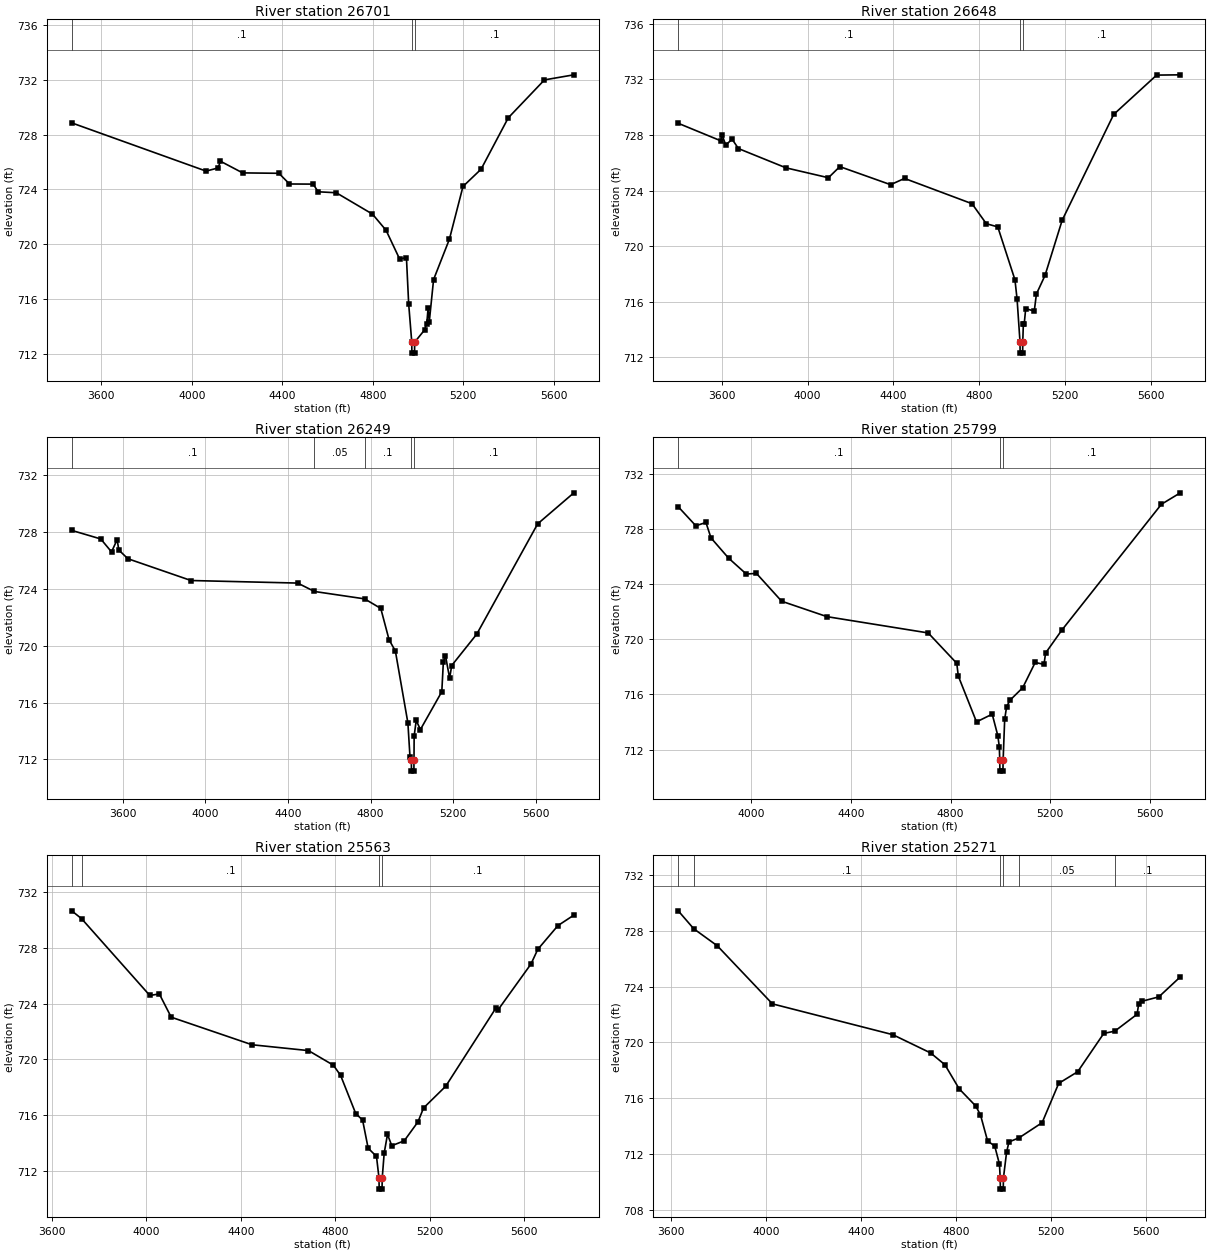
Type RM Length L Ch R = 1 ,26701   ,53,53,53
BEGIN DESCRIPTION:
Mapping XS 588b0abe
END DESCRIPTION:
XS GIS Cut Line= 3
      2018728.35     13632314.07      2017769.08     13631899.51
      2016595.12      13631922.7
#Sta/Elev= 30
  3469.2  728.86  4062.9  725.34  4115.6  725.57  4126.5  726.06  4224.5  725.21
  4384.7  725.18  4431.5   724.4  4536.1  724.39  4558.3  723.83  4638.3  723.76
  4798.3   722.2  4858.4  721.02  4918.4  718.92  4948.4  719.03  4958.4  715.63
    4972  712.85  4972.5  712.05  4984.3  712.05  4984.8  712.85  5028.4  713.74
  5038.4  714.21  5044.4  715.38  5049.4  714.34  5068.4  717.42  5138.4  720.37
  5198.4  724.22  5278.4  725.48  5398.5  729.23  5558.5     732  5688.4  732.37
#Mann= 3 ,-1 , 0
  3469.2      .1       0    4972     .07       0  4984.8      .1       0
Bank Sta=4972,4984.8
XS Rating Curve= 0 ,0
Exp/Cntr=0.3,0.1

Type RM Length L Ch R = 1 ,26648   ,399,399,399
BEGIN DESCRIPTION:
Mapping XS 187ce9d2
END DESCRIPTION:
XS GIS Cut Line= 4
      2018819.46     13632257.63      2017794.89      13631831.7
       2017291.7     13631859.76      2016564.68     13631827.21
#Sta/Elev= 30
    3397  728.84  3595.3  727.58  3600.7  728.03  3618.4  727.28  3648.4  727.69
  3677.7  727.02    3900  725.63  4097.3  724.92  4150.4  725.72  4387.3  724.42
  4452.3  724.87  4766.9  723.05  4833.6  721.61  4887.1  721.38  4967.2  717.57
  4977.2  716.16  4990.8  713.09  4991.3  712.29  5003.1  712.29  5003.6  713.09
  5006.4  714.41  5010.5  714.41  5017.3  715.49  5057.3  715.32  5067.3  716.55
  5107.3  717.88  5187.4  721.86  5427.7  729.48  5627.9  732.31  5738.3  732.33
#Mann= 3 ,-1 , 0
    3397      .1       0  4990.8     .07       0  5003.6      .1       0
Bank Sta=4990.8,5003.6
XS Rating Curve= 0 ,0
Exp/Cntr=0.3,0.1

Type RM Length L Ch R = 1 ,26249   ,450,450,450
BEGIN DESCRIPTION:
FORT EWELL CREEK 32.0
END DESCRIPTION:
XS GIS Cut Line= 4
      2018729.21     13632193.62      2017633.69     13631521.71
      2016969.63     13631426.23      2016531.27     13631608.51
#Sta/Elev= 30
  3353.3  728.09  3493.6  727.49  3545.8  726.58  3572.9  727.44  3581.1  726.71
  3625.1   726.1  3930.6  724.57  4446.9  724.39  4528.3   723.8  4771.4  723.28
  4849.3  722.61  4889.7   720.4    4920  719.62  4980.6  714.57  4990.7   712.2
  4997.4  711.98  4997.9  711.18  5009.7  711.18  5010.2  711.98  5010.9  713.65
    5021  714.74  5041.2   714.1  5144.8  716.76  5152.4  718.86  5162.5   719.3
  5182.7  717.71  5192.8   718.6  5314.3  720.81  5608.9  728.55  5784.1  730.73
#Mann= 5 ,-1 , 0
  3353.3      .1       0  4528.3     .05       0  4771.4      .1       0
  4997.4     .07       0  5010.2      .1       0
Bank Sta=4997.4,5010.2
XS Rating Curve= 0 ,0
Exp/Cntr=0.3,0.1

Type RM Length L Ch R = 1 ,25799   ,236,236,236
BEGIN DESCRIPTION:
Mapping XS 7d3602a5
END DESCRIPTION:
XS GIS Cut Line= 3
       2018244.8     13630691.01      2017443.58     13630815.11
      2016481.74     13631537.37
#Sta/Elev= 30
  3707.9  729.61  3778.5  728.23    3819  728.47  3839.3  727.35  3910.1  725.88
  3980.9  724.73  4021.4  724.78  4122.6  722.76  4304.7  721.64  4710.4  720.46
  4824.9  718.26  4831.2  717.33  4904.1  714.01  4967.1  714.57  4989.5  713.02
  4995.7   712.2  4997.3  711.24    4998  710.44  5010.1  710.44  5010.9  711.24
  5017.1  714.19  5024.9  715.12  5039.5   715.6  5089.5  716.49  5139.5  718.32
  5174.9  718.18  5181.1     719  5245.7  720.65  5645.6  729.79  5721.5  730.62
#Mann= 3 ,-1 , 0
  3707.9      .1       0  4997.3     .07       0  5010.9      .1       0
Bank Sta=4997.3,5010.9
XS Rating Curve= 0 ,0
Exp/Cntr=0.3,0.1

Type RM Length L Ch R = 1 ,25563   ,292,292,292
BEGIN DESCRIPTION:
Mapping XS b2e5421c
END DESCRIPTION:
XS GIS Cut Line= 4
      2018243.51     13630642.83      2017287.33     13630754.35
      2016510.42     13631084.21      2016263.06     13631288.18
#Sta/Elev= 30
  3683.4  730.66  3725.3  730.09  4014.1  724.58  4054.4  724.69  4104.7  723.02
  4447.1  721.04  4686.4  720.62  4791.9  719.57  4822.4  718.84  4886.5   716.1
  4915.6  715.63  4939.2  713.61  4974.5  713.02  4985.1  711.47  4985.9  710.67
    4998  710.67  4998.8  711.47  5007.1  713.26  5021.1   714.6  5039.3  713.79
    5092  714.14  5150.2   715.5  5173.9   716.5  5267.8  718.06  5479.5  723.65
  5490.1  723.56  5629.1  726.84  5657.8  727.89  5743.4   729.6  5810.7  730.35
#Mann= 4 ,-1 , 0
  3683.4     .05       0  3725.3      .1       0  4985.1     .07       0
  4998.8      .1       0
Bank Sta=4985.1,4998.8
XS Rating Curve= 0 ,0
Exp/Cntr=0.3,0.1

Type RM Length L Ch R = 1 ,25271   ,135,135,135
BEGIN DESCRIPTION:
Mapping XS fee57e7b
END DESCRIPTION:
XS GIS Cut Line= 3
      2018149.76     13630642.83      2016310.77     13630676.23
      2016141.53     13630897.54
#Sta/Elev= 30
  3628.8  729.41  3694.1  728.13  3793.6  726.91  4026.1  722.76  4533.7  720.56
  4693.7  719.25  4753.7  718.41  4813.8  716.69  4883.8  715.46  4903.8  714.82
  4933.8  712.96  4963.8   712.6  4983.8  711.31  4986.9  710.32  4987.7  709.52
  4999.8  709.52  5000.6  710.32  5013.8  712.15  5023.8  712.89  5066.8  713.19
  5163.8  714.27  5233.8  717.08  5313.8  717.91  5423.9  720.65  5470.3  720.81
  5564.5  722.02  5570.8  722.73  5585.4  722.95  5656.1  723.26  5746.7  724.69
#Mann= 6 ,-1 , 0
  3628.8     .05       0  3694.1      .1       0  4986.9     .07       0
  5000.6      .1       0  5066.8     .05       0  5470.3      .1       0
Bank Sta=4986.9,5000.6
XS Rating Curve= 0 ,0
Exp/Cntr=0.3,0.1

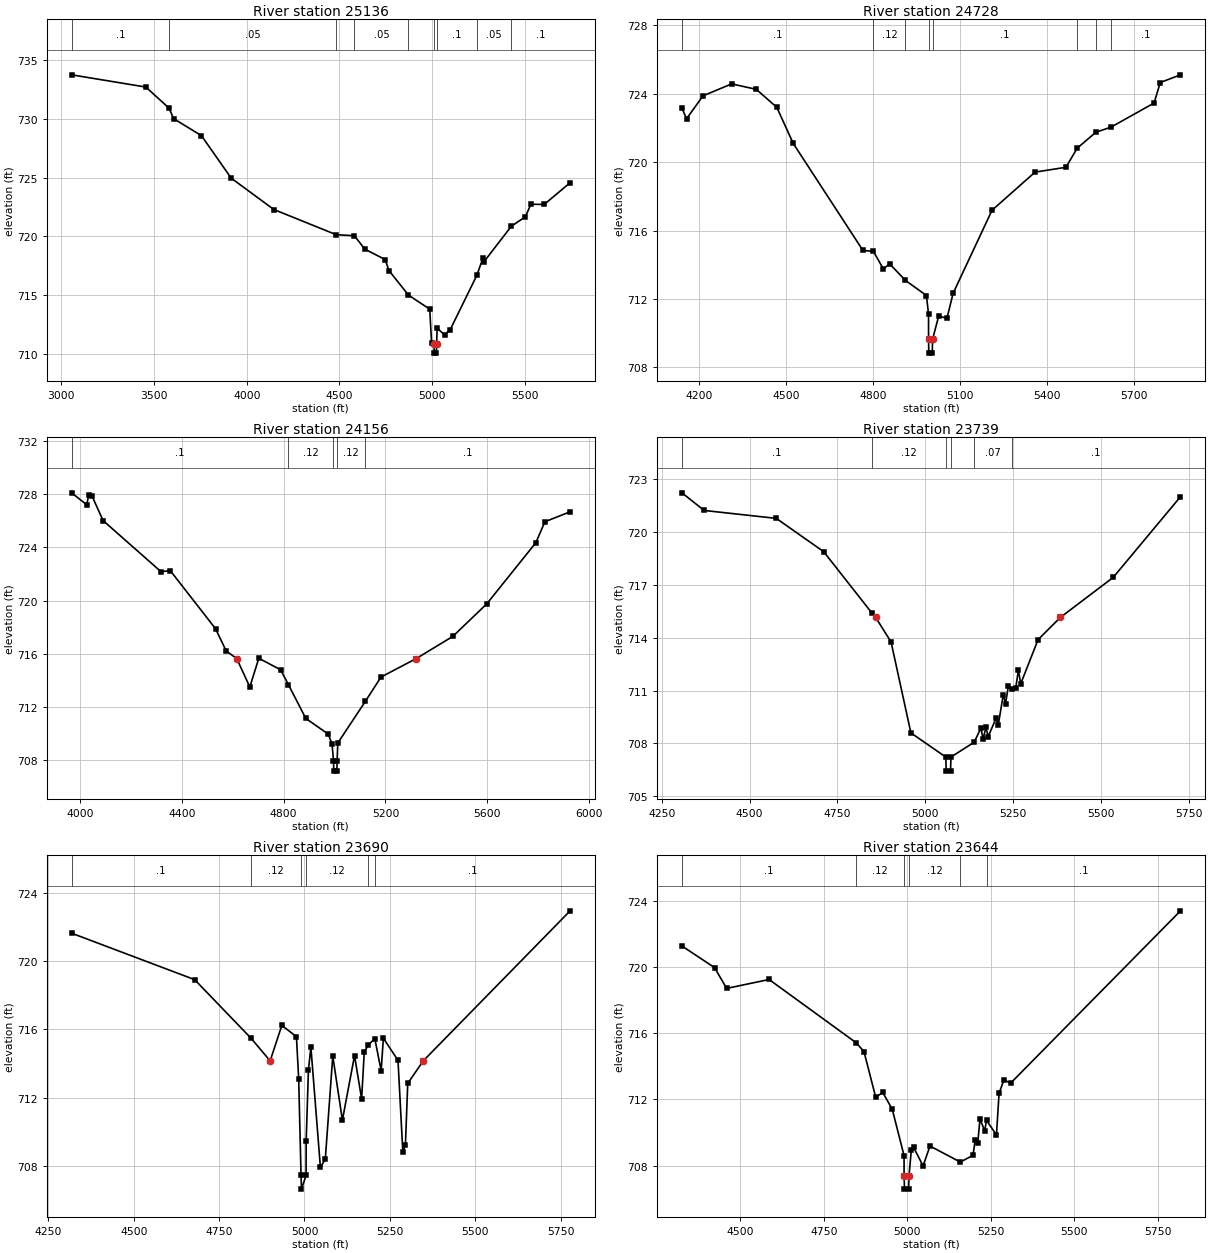
Type RM Length L Ch R = 1 ,25136   ,408,408,408
BEGIN DESCRIPTION:
Mapping XS 0e363da8
END DESCRIPTION:
XS GIS Cut Line= 3
      2018655.02     13630543.87       2016497.4     13630556.43
      2016063.34     13630858.54
#Sta/Elev= 30
  3056.4  733.74  3456.4   732.7  3581.2  730.91  3606.4  730.01  3756.4  728.56
  3916.4  724.95  4146.4  722.28  4481.9  720.14  4580.3  720.05  4636.4  718.91
  4746.4  718.02  4766.4  717.09  4871.7     715  4986.4   713.8  4996.4  710.91
  5009.6  710.86  5010.4  710.06  5022.5  710.06  5023.3  710.86  5026.4  712.17
  5066.5  711.62  5096.5  712.05  5240.9   716.7  5272.3  718.12  5278.4  717.83
  5426.3  720.86  5501.8  721.66  5531.5  722.73  5603.1  722.71  5742.9  724.56
#Mann= 9 ,-1 , 0
  3056.4      .1       0  3581.2     .05       0  4481.9     .08       0
  4580.3     .05       0  4871.7      .1       0  5009.6     .07       0
  5023.3      .1       0  5240.9     .05       0  5426.3      .1       0
Bank Sta=5009.6,5023.3
XS Rating Curve= 0 ,0
Exp/Cntr=0.3,0.1

Type RM Length L Ch R = 1 ,24728   ,572,572,572
BEGIN DESCRIPTION:
Mapping XS aac59125
END DESCRIPTION:
XS GIS Cut Line= 3
      2017144.09     13629621.55      2016206.61     13630537.34
      2015989.81     13630884.21
#Sta/Elev= 30
  4139.9  723.15  4155.8  722.54  4212.4  723.88  4311.4  724.58  4396.3  724.26
    4467  723.21  4523.6   721.1    4764  714.84  4800.4  714.78  4834.8  713.75
  4855.9  714.06  4910.3  713.09  4983.2   712.2  4990.4  711.11  4990.5  709.63
  4991.3  708.83  5003.4  708.83  5004.2  709.63  5025.6  711.01  5053.9  710.86
  5075.2  712.33  5209.5  717.19    5358  719.42  5464.2   719.7  5503.3  720.82
  5567.6  721.75  5619.8  722.05  5768.4  723.46  5789.7  724.66  5859.5  725.11
#Mann= 8 ,-1 , 0
  4139.9      .1       0  4800.4     .12       0  4910.3      .1       0
  4990.5     .07       0  5004.2      .1       0  5503.3     .05       0
  5567.6     .08       0  5619.8      .1       0
Bank Sta=4990.5,5004.2
XS Rating Curve= 0 ,0
Exp/Cntr=0.3,0.1

Type RM Length L Ch R = 1 ,24156   ,417,417,417
BEGIN DESCRIPTION:
FORT EWELL CREEK 28.0
END DESCRIPTION:
XS GIS Cut Line= 3
      2017208.31      13629134.3      2016588.55     13629629.06
      2015557.28     13630170.74
#Sta/Elev= 30
  3967.6  728.12  4027.1  727.22  4035.1  727.99  4048.6  727.85  4091.2  726.03
  4318.5  722.18  4355.4  722.25  4533.1  717.87  4574.7   716.2  4616.2715.6256
  4667.6  713.48  4702.8  715.65  4788.5  714.78  4819.1  713.66  4887.5  711.11
  4975.7  709.93  4990.5  709.18  4996.2  707.94  4997.2  707.14  5009.4  707.14
  5010.4  707.94  5013.1  709.26  5121.4   712.4  5182.6  714.23 5321.15715.6255
    5465   717.3  5598.1  719.75  5790.9  724.36  5826.4  725.94  5925.5  726.69
#Mann= 5 ,-1 , 0
  3967.6      .1       0  4819.1     .12       0  4996.2     .07       0
  5010.4     .12       0  5121.4      .1       0
Bank Sta=4616.2,5321.15
XS Rating Curve= 0 ,0
Exp/Cntr=0.3,0.1

Type RM Length L Ch R = 1 ,23739   ,49,49,49
BEGIN DESCRIPTION:
FORT EWELL CREEK 27.0
END DESCRIPTION:
XS GIS Cut Line= 3
      2016697.93     13628958.92      2016156.26     13629420.73
      2015610.08     13629870.12
#Sta/Elev= 30
  4307.3  722.22  4370.4  721.22  4575.8  720.77  4710.8  718.88    4848   715.4
 4858.67715.1518  4902.5  713.76    4959   708.6  5058.3  707.23  5059.5  706.43
  5071.8  706.43    5073  707.23  5139.2  708.07  5158.2  708.87  5164.6  708.25
  5172.5  708.92    5179  708.39  5201.2  709.42  5207.7  709.05    5222  710.77
  5228.5  710.26  5236.4  711.25  5245.8  711.07  5257.2  711.12    5265  712.16
  5271.5  711.38    5321  713.89 5384.54715.1517  5534.8  717.42  5726.4     722
#Mann= 6 ,-1 , 0
  4307.3      .1       0    4848     .12       0  5058.3     .07       0
    5073     .12       0  5139.2     .07       0  5245.8      .1       0
Bank Sta=4858.67,5384.54
XS Rating Curve= 0 ,0
Exp/Cntr=0.3,0.1

Type RM Length L Ch R = 1 ,23690   ,46,46,46
BEGIN DESCRIPTION:
Mapping XS 893b7cf9
END DESCRIPTION:
XS GIS Cut Line= 4
      2016652.78     13628924.21      2016180.56     13629337.39
      2015861.12      13629611.7      2015524.35     13629847.79
#Sta/Elev= 30
    4318  721.64  4678.3  718.92  4842.9   715.5  4899.4714.1618  4933.6  716.24
  4976.4  715.58    4983   713.1  4989.9  707.45  4991.1  706.65  5004.6  707.45
  5004.9  709.48  5011.5  713.61  5018.7  714.97  5046.6  707.92  5060.9  708.41
  5082.8  714.44    5111  710.69  5146.5  714.47  5167.3  711.93    5175  714.68
  5187.3  715.11  5205.9  715.46  5224.4  713.59    5231  715.49  5273.8  714.19
    5288   708.8  5295.5  709.24  5302.3  712.84 5347.68714.1616  5777.8  722.95
#Mann= 6 ,-1 , 0
    4318      .1       0  4842.9     .12       0  4989.9     .07       0
  5004.6     .12       0  5187.3     .07       0  5205.9      .1       0
Bank Sta=4899.4,5347.68
XS Rating Curve= 0 ,0
Exp/Cntr=0.3,0.1

Type RM Length L Ch R = 1 ,23644   ,419,419,419
BEGIN DESCRIPTION:
Mapping XS bb0da6b1
END DESCRIPTION:
XS GIS Cut Line= 4
      2016618.07     13628899.89      2016118.06     13629330.45
      2015791.67     13629604.76      2015444.47     13629816.55
#Sta/Elev= 30
    4325   721.3  4422.6  719.99  4458.8  718.73    4586  719.27  4847.2  715.43
  4870.1   714.9  4905.3  712.13  4926.2  712.43  4954.7  711.41  4990.1   708.6
  4990.2  707.37  4991.4  706.57  5003.7  706.57  5004.9  707.37  5011.8  708.92
  5018.4  709.11    5047  707.98  5067.8  709.18  5158.6  708.21  5196.5  708.62
  5203.1  709.53  5210.8  709.36  5217.4  710.81  5231.7  710.11    5237  710.74
  5266.8  709.85  5274.6  712.37  5288.9  713.18  5309.7     713  5817.9  723.43
#Mann= 6 ,-1 , 0
    4325      .1       0  4847.2     .12       0  4990.2     .07       0
  5004.9     .12       0  5158.6     .07       0    5237      .1       0
Bank Sta=4990.2,5004.9
XS Rating Curve= 0 ,0
Exp/Cntr=0.3,0.1

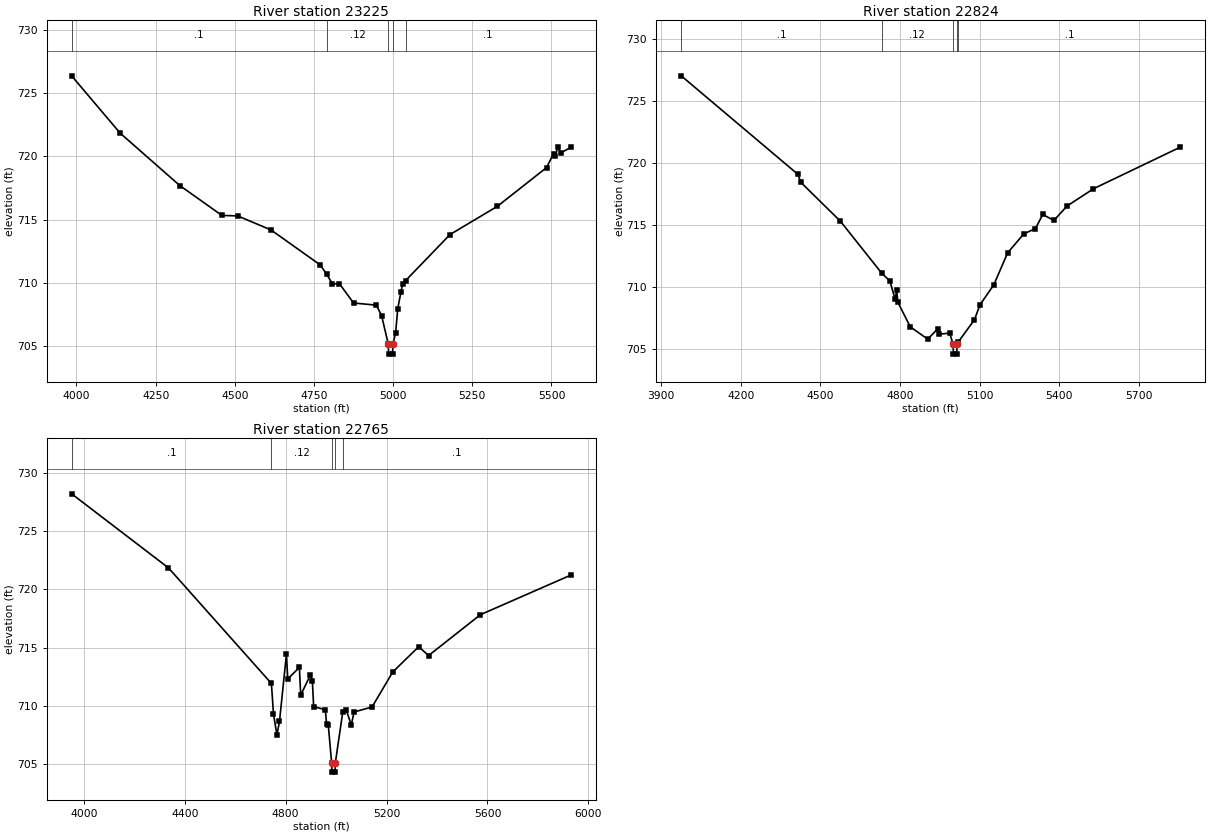
Type RM Length L Ch R = 1 ,23225   ,401,401,401
BEGIN DESCRIPTION:
Mapping XS 9431f8e7
END DESCRIPTION:
XS GIS Cut Line= 2
      2016680.54     13628701.99       2015278.9     13629423.63
#Sta/Elev= 30
  3984.7  726.37    4138  721.84  4326.3   717.7  4459.3  715.34  4509.3   715.3
  4614.5  714.19  4769.7  711.43  4789.8  710.71  4808.4  709.93  4830.6  709.94
    4875  708.42  4947.1  708.25  4963.6  707.42  4984.6  705.18  4985.8  704.38
  4998.1  704.38  4999.3  705.18    5008  706.08  5014.5  707.96  5024.5  709.27
  5030.2  709.95  5039.4  710.19  5179.7  713.83  5329.3  716.06  5484.5  719.12
  5506.7  720.23  5512.3  720.04  5520.6  720.78  5528.8  720.27  5561.2  720.72
#Mann= 5 ,-1 , 0
  3984.7      .1       0  4789.8     .12       0  4984.6     .07       0
  4999.3     .12       0  5039.4      .1       0
Bank Sta=4984.6,4999.3
XS Rating Curve= 0 ,0
Exp/Cntr=0.3,0.1

Type RM Length L Ch R = 1 ,22824   ,59,59,59
BEGIN DESCRIPTION:
Mapping XS 22eebadb
END DESCRIPTION:
XS GIS Cut Line= 4
      2016645.81     13628594.35      2015687.51     13628781.84
      2015315.98     13628889.48      2014972.24     13629274.88
#Sta/Elev= 30
    3976  727.06    4415   719.1  4426.2  718.45  4575.6   715.3  4730.2  711.12
  4761.4  710.48  4781.7  708.98  4786.8  709.72    4792  708.74  4838.3  706.77
  4904.1  705.77  4941.3  706.59  4946.4  706.17  4986.7  706.26  4999.7  705.36
  5000.9  704.56  5013.3  704.56  5014.5  705.36  5018.3  705.52    5080  707.34
  5100.8  708.55  5152.9  710.16    5205  712.75  5265.7  714.28  5309.7  714.71
  5337.2  715.85  5379.2  715.37  5428.6  716.53  5528.1  717.93  5855.7   721.3
#Mann= 5 ,-1 , 0
    3976      .1       0  4730.2     .12       0  4999.7     .07       0
  5014.5     .12       0  5018.3      .1       0
Bank Sta=4999.7,5014.5
XS Rating Curve= 0 ,0
Exp/Cntr=0.3,0.1

Type RM Length L Ch R = 1 ,22765   ,62,62,62
BEGIN DESCRIPTION:
Mapping XS 756b95ee
END DESCRIPTION:
XS GIS Cut Line= 3
      2016673.63     13628535.31      2015243.06     13628816.56
      2014944.44     13629243.67
#Sta/Elev= 30
  3951.5  728.24  4335.5  721.86  4743.5  711.91  4751.8  709.27  4765.4  707.47
  4775.6  708.64  4803.2  714.45  4808.2  712.29  4854.5  713.29  4859.6   710.9
  4897.9  712.63  4905.9  712.13    4911  709.91  4957.3  709.65  4962.4  708.39
  4969.2  708.29  4982.2  705.07  4983.4  704.27  4995.8  704.27    4997  705.07
  5026.2  709.42  5040.6   709.6  5060.1  708.33  5071.2  709.45  5142.5  709.88
  5224.5  712.89  5327.3  715.07  5366.7  714.31  5572.1  717.83  5930.6  721.24
#Mann= 5 ,-1 , 0
  3951.5      .1       0  4743.5     .12       0  4982.2     .07       0
    4997     .12       0  5026.2      .1       0
Bank Sta=4982.2,4997
XS Rating Curve= 0 ,0
Exp/Cntr=0.3,0.1