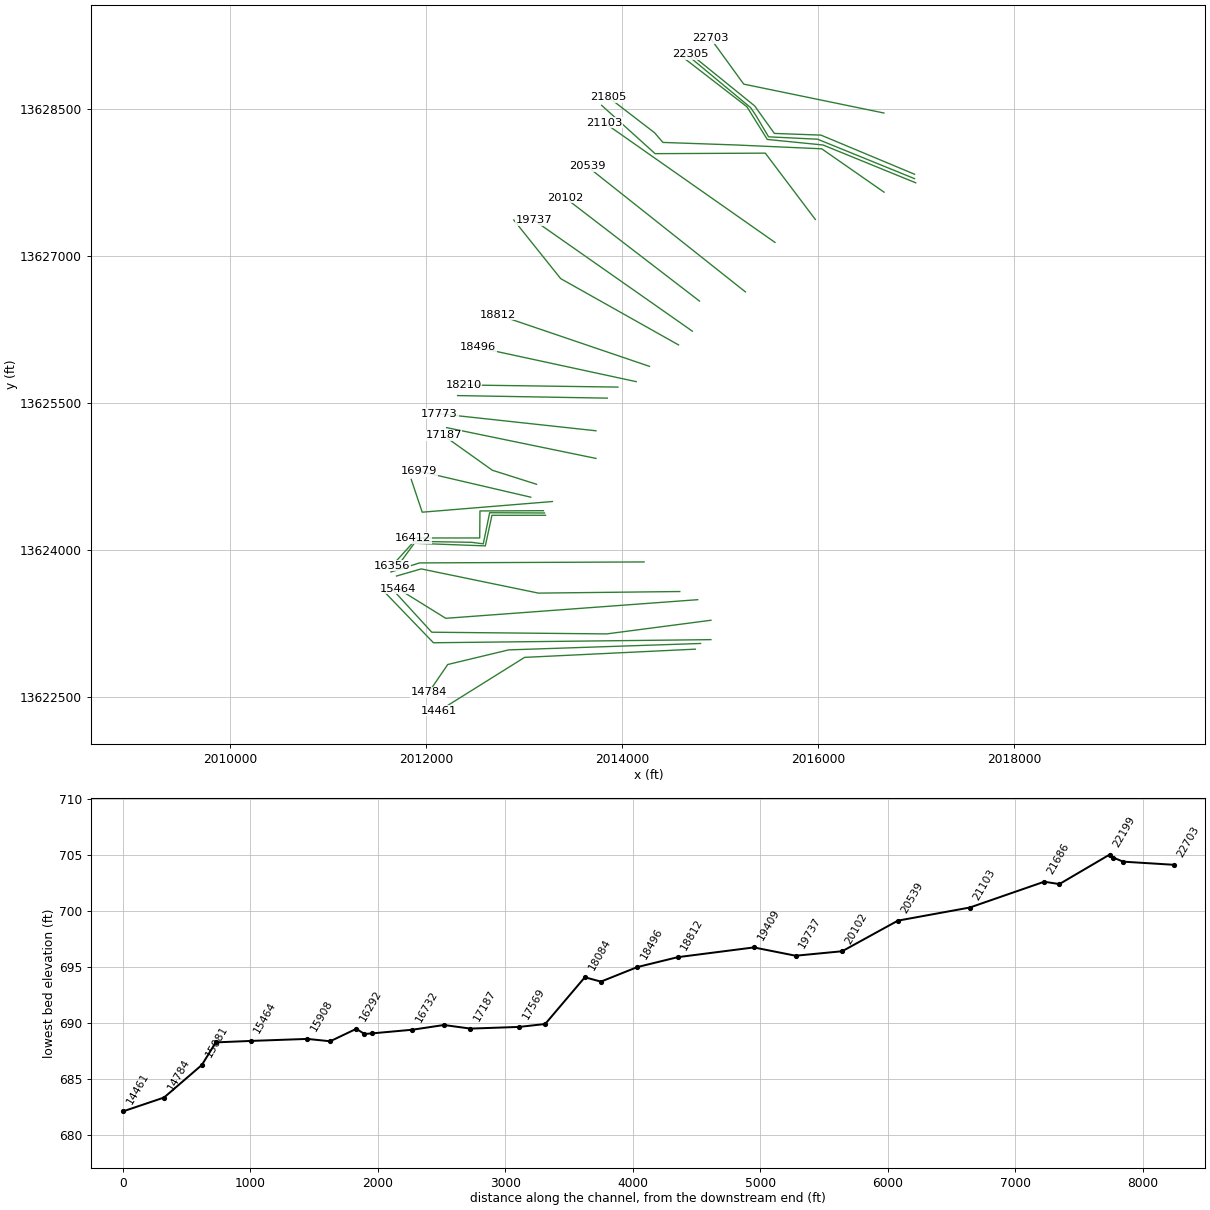
HEC-RAS study FORT EWELL CREEK.prj: FORT EWELL CREEK Base Level Engineering

--- FORT EWELL CREEK.g01 (geometry) --- (continued)

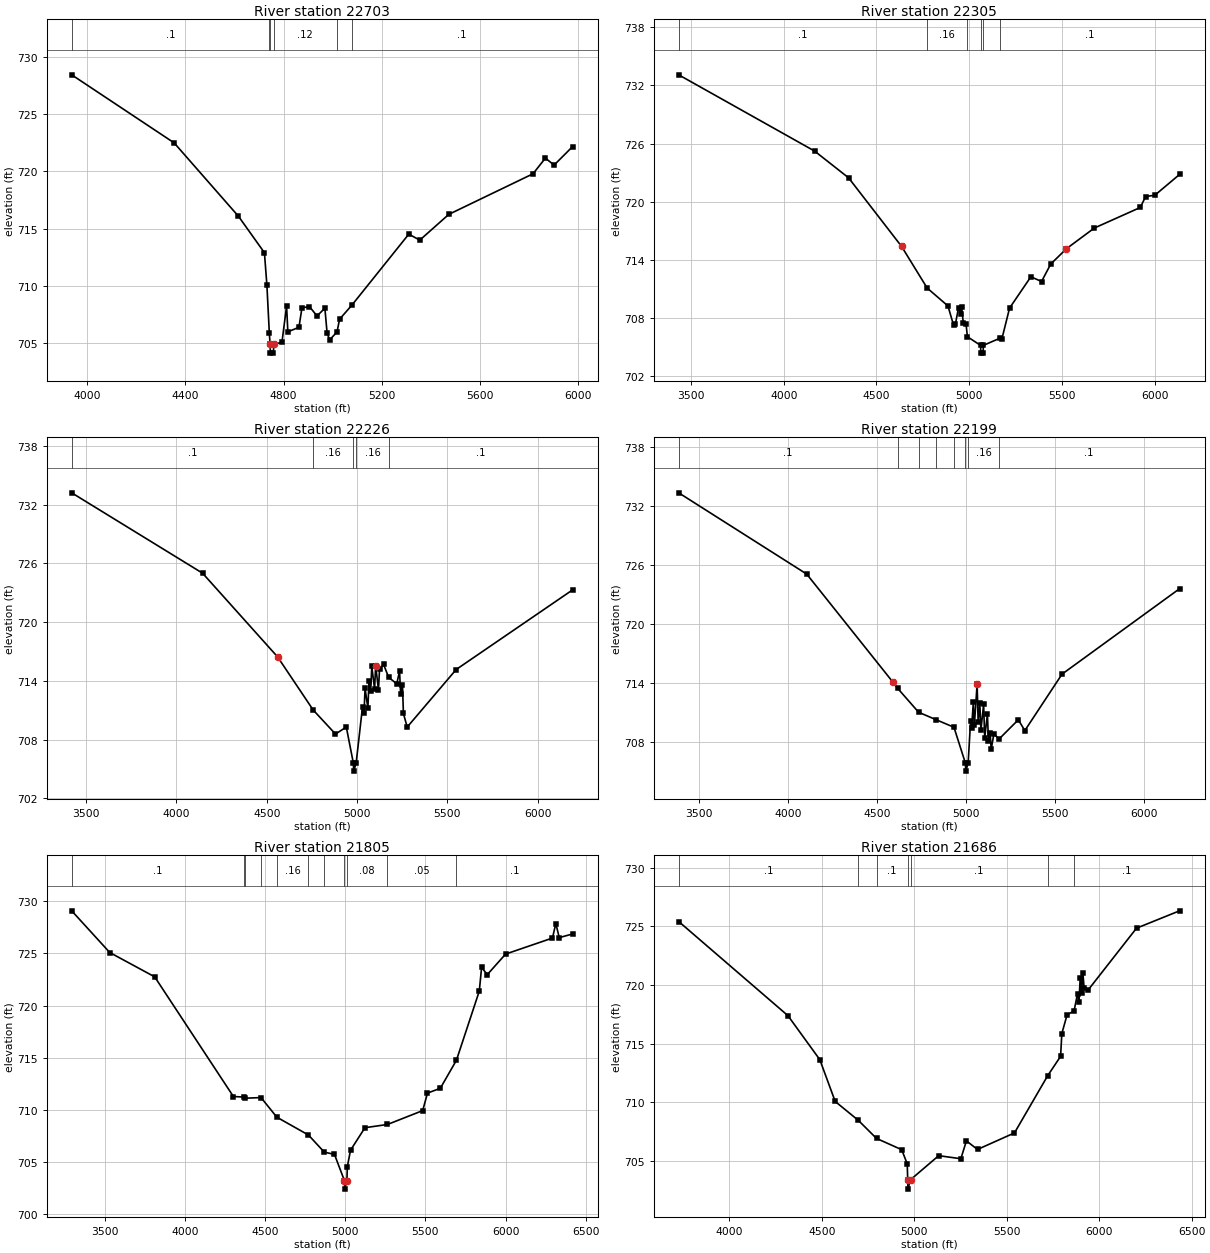
Type RM Length L Ch R = 1 ,22703   ,398,398,398
BEGIN DESCRIPTION:
Mapping XS 2e1d0d52
END DESCRIPTION:
XS GIS Cut Line= 3
      2016673.67     13628462.39      2015243.06     13628757.53
      2014902.77     13629226.31
#Sta/Elev= 30
  3937.1  728.45  4354.4   722.5  4616.5  716.08  4722.1   712.9  4732.2  710.06
  4742.1  705.87  4745.1  704.92  4746.4  704.12  4758.8  704.12    4760  704.92
  4793.4  705.05  4812.4  708.24  4817.5  705.98  4862.7  706.38  4875.1  708.09
  4905.7  708.18  4936.4  707.37  4968.4  708.05  4977.2  705.91  4987.4  705.27
  5017.8  705.97  5028.3  707.09  5078.2  708.31  5310.1  714.52    5355     714
  5473.1  716.25  5816.3   719.8  5866.5  721.17  5902.1  720.56  5977.1  722.17
#Mann= 6 ,-1 , 0
  3937.1      .1       0  4742.1     .12       0  4745.1     .07       0
    4760     .12       0  5017.8     .07       0  5078.2      .1       0
Bank Sta=4745.1,4760
XS Rating Curve= 0 ,0
Exp/Cntr=0.3,0.1

Type RM Length L Ch R = 1 ,22305   ,79,79,79
BEGIN DESCRIPTION:
Mapping XS a86cd17d
END DESCRIPTION:
XS GIS Cut Line= 5
      2016986.16     13627837.38      2016031.26      13628236.7
      2015555.56     13628254.06      2015354.17     13628535.31
      2014698.93     13629065.75
#Sta/Elev= 30
  3433.7  733.08  4166.4  725.22  4349.3  722.47  4635.1   715.4    4773  711.11
  4885.3  709.26  4915.3  707.29  4925.3  707.38  4942.5   709.1  4953.2  708.44
  4959.3  709.13  4967.9  707.49  4982.6  707.43  4990.1  706.09  5061.1   705.2
  5062.4   704.4  5074.8   704.4  5076.2   705.2  5167.1  705.95  5175.5  705.82
  5217.3  709.04  5332.3  712.27  5389.8  711.78  5439.4  713.58  5524.1  715.16
  5674.3  717.29  5922.2  719.41    5951  720.54  6000.5  720.67  6133.7  722.81
#Mann= 6 ,-1 , 0
  3433.7      .1       0    4773     .16       0  4990.1     .12       0
  5061.1     .07       0  5076.2     .12       0  5167.1      .1       0
Bank Sta=4635.1,5524.1
XS Rating Curve= 0 ,0
Exp/Cntr=0.3,0.1

Type RM Length L Ch R = 1 ,22226   ,27,27,27
BEGIN DESCRIPTION:
Mapping XS 83586a61
END DESCRIPTION:
XS GIS Cut Line= 6
      2016986.09     13627792.27      2015996.54     13628195.03
      2015496.54     13628219.34      2015364.59     13628441.56
      2015312.51     13628517.95      2014656.26     13629063.09
#Sta/Elev= 30
    3420   733.2  4144.6  724.99    4560  716.44  4756.8  711.02  4880.4  708.56
  4940.5  709.27  4979.7  705.57    4981  704.77  4994.8  705.57  5030.4  711.37
  5038.6  710.73  5044.4  713.23    5060  711.18  5065.8  713.95  5075.6  712.92
  5081.5  715.47  5097.1  713.15  5102.9  715.56  5118.5  713.07  5124.3  715.16
  5146.7  715.68  5174.9  714.35  5219.8  713.69  5235.4  714.99  5241.2  712.63
  5251.5  713.61  5256.6  710.66  5277.6  709.27  5548.8  715.15    6193  723.28
#Mann= 5 ,-1 , 0
    3420      .1       0  4756.8     .16       0  4979.7     .07       0
  4994.8     .16       0  5174.9      .1       0
Bank Sta=4560,5102.9
XS Rating Curve= 0 ,0
Exp/Cntr=0.3,0.1

Type RM Length L Ch R = 1 ,22199   ,394,394,394
BEGIN DESCRIPTION:
Mapping XS 112bfb5e
END DESCRIPTION:
XS GIS Cut Line= 5
      2016998.25     13627749.73      2016052.09     13628136.01
      2015483.52     13628192.43      2015275.18     13628526.63
      2014624.19     13629030.06
#Sta/Elev= 30
  3386.8  733.38  4105.2   725.1  4586.7  714.14  4615.5  713.46  4732.8  711.03
    4832  710.26  4931.2   709.5  4995.7  705.83  4997.1  705.03  5010.8  705.83
  5024.5  710.15  5030.4  709.44  5039.8  712.03  5045.7  709.71  5061.1  713.88
    5067  710.03  5076.4  711.95  5082.3  709.18  5097.7  711.83  5103.6  708.41
  5118.9  710.85  5124.8  708.11  5134.2  708.89  5140.1  707.25  5155.5  708.85
  5183.7  708.29  5292.3  710.26  5328.9  709.16  5537.6  714.91  6196.9  723.61
#Mann= 8 ,-1 , 0
  3386.8      .1       0  4615.5     .12       0  4732.8     .07       0
    4832     .12       0  4931.2     .16       0  4995.7     .07       0
  5010.8     .16       0  5183.7      .1       0
Bank Sta=4586.7,5061.1
XS Rating Curve= 0 ,0
Exp/Cntr=0.3,0.1

Type RM Length L Ch R = 1 ,21805   ,119,119,119
BEGIN DESCRIPTION:
FORT EWELL CREEK 24.0
END DESCRIPTION:
XS GIS Cut Line= 6
      2016674.89     13627654.26      2016039.07     13628096.94
      2015166.24     13628136.01      2014417.98     13628162.05
      2014332.91     13628261.01      2013859.44     13628625.21
#Sta/Elev= 30
  3292.9  729.09  3530.4  725.09  3810.6  722.76  4301.9  711.28  4368.3  711.23
  4375.6  711.12  4474.2  711.18  4572.8   709.3  4770.1  707.59  4868.8  705.95
  4932.6  705.73    4995   703.2  4996.4   702.4  5010.2   703.2  5012.6  704.54
  5032.6  706.13  5122.7  708.29  5263.1   708.6  5482.9  709.93  5512.9  711.61
    5593  712.07  5693.5  714.76  5836.1  721.39  5850.6  723.67  5885.9  722.97
  6000.1  724.94  6292.8  726.48  6313.6  727.87  6335.2  726.52  6417.9  726.87
#Mann= 11 ,-1 , 0
  3292.9      .1       0  4368.3     .12       0  4375.6     .07       0
  4474.2     .12       0  4572.8     .16       0  4770.1     .05       0
  4868.8     .08       0    4995     .07       0  5010.2     .08       0
  5263.1     .05       0  5693.5      .1       0
Bank Sta=4995,5010.2
XS Rating Curve= 0 ,0
Exp/Cntr=0.3,0.1

Type RM Length L Ch R = 1 ,21686   ,583,583,583
BEGIN DESCRIPTION:
FORT EWELL CREEK 23.0
END DESCRIPTION:
XS GIS Cut Line= 4
      2015973.55     13627375.57      2015463.12     13628052.67
      2014338.12     13628047.46      2013792.46     13628541.15
#Sta/Elev= 30
  3725.9  725.41  4316.6  717.39  4489.1  713.64  4572.2  710.08  4697.3  708.47
  4795.7  706.93    4932  705.97    4962  704.76  4964.4  703.41  4965.8  702.61
  4979.6  703.41    5132  705.46    5252   705.2    5282  706.72    5342  705.99
    5542   707.4  5722.2  712.29  5791.4  713.92  5798.1  715.86  5826.5  717.46
  5864.1  717.79  5883.3  719.27  5890.8  718.55  5897.5   720.6  5904.9  719.36
  5911.7  721.06  5918.8  719.72  5940.1  719.57    6202  724.84  6434.7  726.32
#Mann= 7 ,-1 , 0
  3725.9      .1       0  4697.3     .08       0  4795.7      .1       0
  4964.4     .07       0  4979.6      .1       0  5722.2     .05       0
  5864.1      .1       0
Bank Sta=4964.4,4979.6
XS Rating Curve= 0 ,0
Exp/Cntr=0.3,0.1

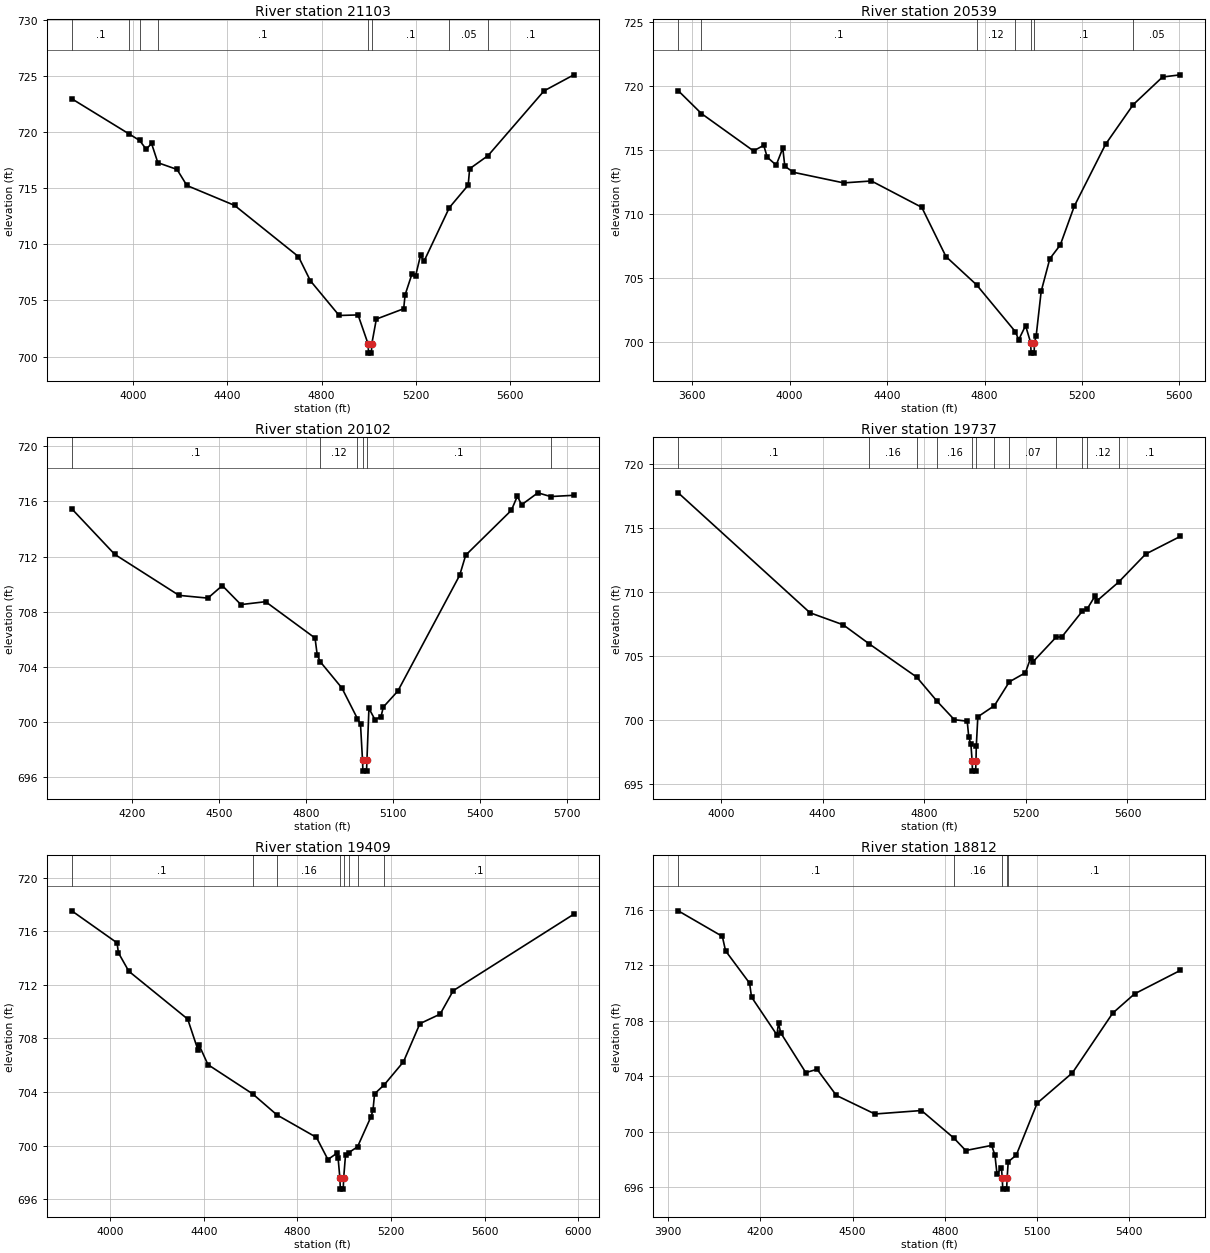
Type RM Length L Ch R = 1 ,21103   ,564,564,564
BEGIN DESCRIPTION:
Mapping XS 8d1fc85e
END DESCRIPTION:
XS GIS Cut Line= 2
      2015562.05     13627141.23      2013818.64     13628364.22
#Sta/Elev= 30
  3740.5  722.95  3982.7  719.83  4028.2  719.24  4056.2  718.46  4078.9  718.97
  4105.6  717.26  4186.9  716.66  4228.8  715.23    4431  713.46    4702   708.9
  4752.6  706.75  4874.6  703.66  4954.8  703.71  4997.7  701.11  4999.1  700.31
  5011.5  700.31  5012.9  701.11  5032.4  703.34  5148.3  704.26  5154.4   705.5
    5184  707.39  5198.8  707.19  5219.8     709  5234.6  708.49    5342  713.26
    5422  715.26  5428.1  716.72  5506.2  717.89  5743.6  723.65  5870.1  725.08
#Mann= 8 ,-1 , 0
  3740.5      .1       0  3982.7     .05       0  4028.2     .08       0
  4105.6      .1       0  4997.7     .07       0  5012.9      .1       0
    5342     .05       0  5506.2      .1       0
Bank Sta=4997.7,5012.9
XS Rating Curve= 0 ,0
Exp/Cntr=0.3,0.1

Type RM Length L Ch R = 1 ,20539   ,437,437,437
BEGIN DESCRIPTION:
Mapping XS 5bb2ed38
END DESCRIPTION:
XS GIS Cut Line= 2
      2015259.97     13626636.02      2013645.38     13627917.28
#Sta/Elev= 30
  3542.5  719.66  3637.8  717.87  3851.7  714.95  3893.5  715.39  3907.8  714.46
  3944.6  713.84  3971.8  715.17  3979.9  713.76  4015.1  713.28  4221.8  712.45
  4335.6   712.6  4542.3  710.54  4641.6  706.69  4767.3  704.48  4925.9  700.83
  4940.3  700.19  4968.4  701.29  4989.6  699.94    4991  699.14  5003.5  699.14
  5004.9  699.94  5011.7  700.45  5032.5  703.97    5068  706.52    5111   707.6
  5168.7  710.64  5296.9  715.47  5410.4  718.57  5530.8  720.73  5603.7   720.9
#Mann= 7 ,-1 , 0
  3542.5     .05       0  3637.8      .1       0  4767.3     .12       0
  4925.9      .1       0  4989.6     .07       0  5004.9      .1       0
  5410.4     .05       0
Bank Sta=4989.6,5004.9
XS Rating Curve= 0 ,0
Exp/Cntr=0.3,0.1

Type RM Length L Ch R = 1 ,20102   ,365,365,365
BEGIN DESCRIPTION:
Mapping XS 44bafe70
END DESCRIPTION:
XS GIS Cut Line= 2
      2014791.22     13626542.27      2013416.22     13627599.56
#Sta/Elev= 30
  3990.3  715.47  4138.7  712.16  4360.8  709.18  4460.5  708.98  4510.3  709.89
  4574.6  708.51  4659.8  708.72  4830.7  706.08  4838.3  704.84  4849.4  704.34
  4923.5  702.45    4977  700.23  4987.8   699.8  4994.7  697.21  4996.1  696.41
  5008.6  696.41    5010  697.21  5016.9  700.97  5037.7  700.15  5058.5  700.36
  5066.7  701.07  5116.5  702.22  5330.4  710.64  5351.2   712.1  5508.9  715.36
  5529.7  716.39  5544.2  715.76  5600.4  716.63  5644.8  716.36  5724.8  716.45
#Mann= 6 ,-1 , 0
  3990.3      .1       0  4849.4     .12       0    4977      .1       0
  4994.7     .07       0    5010      .1       0  5644.8     .05       0
Bank Sta=4994.7,5010
XS Rating Curve= 0 ,0
Exp/Cntr=0.3,0.1

Type RM Length L Ch R = 1 ,19737   ,328,328,328
BEGIN DESCRIPTION:
Mapping XS f2277a91
END DESCRIPTION:
XS GIS Cut Line= 2
      2014718.34     13626234.95      2013100.03     13627369.33
#Sta/Elev= 30
  3831.8  717.73  4350.4  708.37  4481.1  707.43  4582.2  705.96  4770.4  703.35
  4851.3  701.45  4918.7  700.02  4969.3  699.91  4975.4  698.66  4983.8  698.11
  4988.6  696.81    4990  696.01  5002.5  696.01  5003.9  696.81    5005  697.95
  5011.1  700.25  5076.3  701.12  5135.1  702.98  5198.5  703.69  5219.4  704.87
  5228.1  704.54  5319.4  706.47  5341.5  706.48  5422.6   708.5  5442.2  708.69
  5472.2  709.67  5478.3  709.27  5565.1  710.76  5671.8  712.95  5808.1  714.33
#Mann= 12 ,-1 , 0
  3831.8      .1       0  4582.2     .16       0  4770.4     .12       0
  4851.3     .16       0  4988.6     .07       0  5003.9     .16       0
  5076.3     .12       0  5135.1     .07       0  5319.4     .12       0
  5422.6      .1       0  5442.2     .12       0  5565.1      .1       0
Bank Sta=4988.6,5003.9
XS Rating Curve= 0 ,0
Exp/Cntr=0.3,0.1

Type RM Length L Ch R = 1 ,19409   ,597,597,597
BEGIN DESCRIPTION:
Mapping XS 8d9cb1a9
END DESCRIPTION:
XS GIS Cut Line= 3
      2014577.66     13626094.36      2013374.57     13626771.42
      2012895.57     13627370.18
#Sta/Elev= 30
  3834.7  717.52  4028.4  715.13  4034.1  714.39  4078.7  713.01  4330.5  709.44
  4373.8  707.17  4379.6  707.48  4417.2  706.04  4608.2  703.86  4712.1  702.29
  4881.2  700.61  4930.2  698.96  4967.8  699.42  4973.8  699.06  4981.5  697.55
  4983.2  696.75  4995.8  696.75  4997.4  697.55  5005.4  699.28  5019.8  699.48
  5056.9  699.91  5113.8  702.13  5122.9  702.63  5129.7  703.86  5171.8  704.55
  5253.2  706.25  5323.6   709.1  5410.1  709.81  5466.1  711.56    5982  717.27
#Mann= 8 ,-1 , 0
  3834.7      .1       0  4608.2     .07       0  4712.1     .16       0
  4981.5     .07       0  4997.4     .16       0  5019.8     .12       0
  5056.9     .07       0  5171.8      .1       0
Bank Sta=4981.5,4997.4
XS Rating Curve= 0 ,0
Exp/Cntr=0.3,0.1

Type RM Length L Ch R = 1 ,18812   ,316,316,316
BEGIN DESCRIPTION:
Mapping XS 51335cc1
END DESCRIPTION:
XS GIS Cut Line= 2
      2014280.83     13625875.59      2012733.93     13626401.64
#Sta/Elev= 30
  3932.8  715.92  4076.3  714.08  4086.8  713.04    4165  710.71  4171.3  709.71
  4253.8  706.99  4259.1  707.83  4266.4  707.13  4347.9  704.27  4384.6  704.51
  4447.3  702.63  4572.8  701.29  4724.4  701.54  4830.1  699.55  4868.4  698.66
  4952.9  699.03  4963.5  698.31  4970.1  696.98  4984.6   697.4  4987.2  696.68
  4988.9  695.88  5001.5  695.88  5003.1  696.68  5006.7  697.85  5032.9  698.33
  5100.9  702.07  5215.8  704.26  5346.6  708.55  5417.7  709.94  5566.7  711.63
#Mann= 5 ,-1 , 0
  3932.8      .1       0  4830.1     .16       0  4987.2     .07       0
  5003.1     .16       0  5006.7      .1       0
Bank Sta=4987.2,5003.1
XS Rating Curve= 0 ,0
Exp/Cntr=0.3,0.1

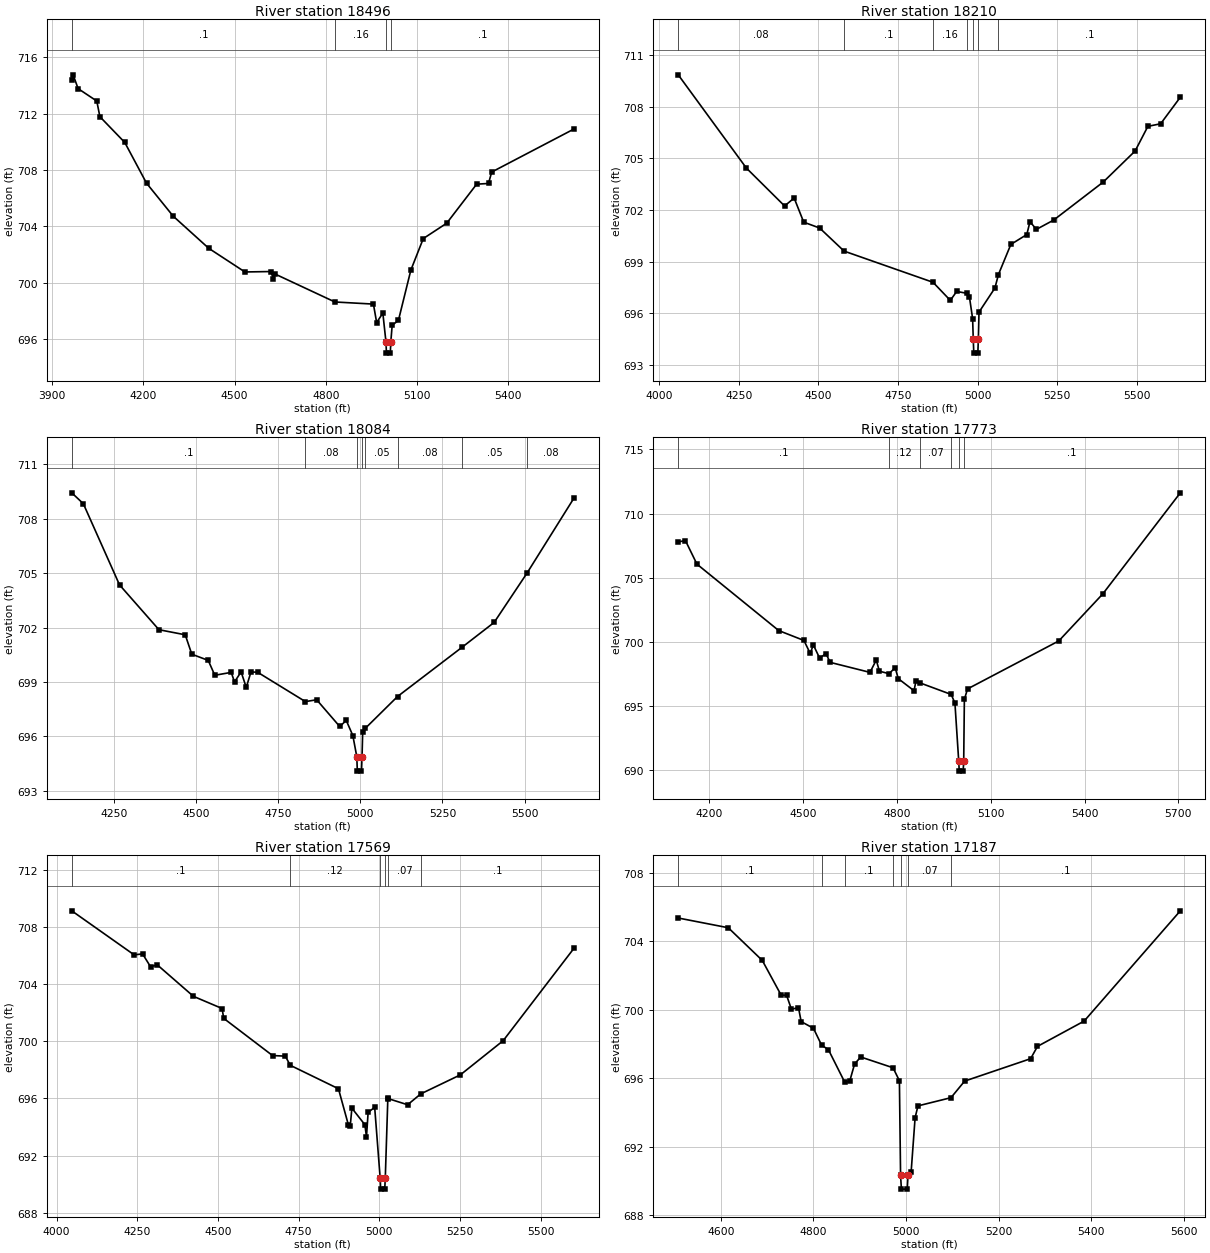
Type RM Length L Ch R = 1 ,18496   ,286,286,286
BEGIN DESCRIPTION:
Mapping XS 02190890
END DESCRIPTION:
XS GIS Cut Line= 2
      2014145.44     13625719.33      2012530.82      13626068.3
#Sta/Elev= 30
  3964.3   714.4  3968.7  714.75  3985.2  713.77  4046.6  712.89  4056.8  711.78
  4138.7  709.95  4210.3  707.06    4298  704.72  4414.9  702.44    4534  700.76
  4619.5  700.79  4627.4  700.27  4632.5  700.62    4830  698.63  4956.8  698.48
  4967.4  697.17  4987.8  697.84    4998   695.8  4999.7     695  5012.3     695
    5014   695.8  5018.5  696.98    5039  697.32  5079.9  700.89  5120.8  703.13
  5197.9  704.22  5296.4  706.99  5335.4  707.04  5345.9  707.85  5616.2   710.9
#Mann= 4 ,-1 , 0
  3964.3      .1       0    4830     .16       0    4998     .07       0
    5014      .1       0
Bank Sta=4998,5014
XS Rating Curve= 0 ,0
Exp/Cntr=0.3,0.1

Type RM Length L Ch R = 1 ,18210   ,126,126,126
BEGIN DESCRIPTION:
Mapping XS dd9fffb5
END DESCRIPTION:
XS GIS Cut Line= 2
      2013958.81     13625663.78      2012383.26     13625685.49
#Sta/Elev= 30
  4060.2  709.85    4274  704.44    4394  702.24    4424   702.7    4454   701.3
    4504  700.96  4580.7  699.62  4859.9  697.81  4914.1  696.76  4934.1  697.28
  4966.7  697.17  4974.1  696.96  4984.1   695.7  4986.1   694.5  4987.8   693.7
  5000.4   693.7  5002.1   694.5  5004.1  696.08  5054.1  697.48  5065.1  698.26
  5104.1  700.01  5154.1  700.58  5164.1  701.33  5184.1  700.88  5238.4  701.42
  5394.1  703.63  5494.1  705.43  5534.1  706.86  5574.2  707.01  5635.9  708.55
#Mann= 7 ,-1 , 0
  4060.2     .08       0  4580.7      .1       0  4859.9     .16       0
  4966.7     .12       0  4986.1     .07       0  5002.1     .12       0
  5065.1      .1       0
Bank Sta=4986.1,5002.1
XS Rating Curve= 0 ,0
Exp/Cntr=0.3,0.1

Type RM Length L Ch R = 1 ,18084   ,311,311,311
BEGIN DESCRIPTION:
Mapping XS 336cdd15
END DESCRIPTION:
XS GIS Cut Line= 2
      2013850.24     13625550.94      2012322.46     13625576.98
#Sta/Elev= 30
  4121.8  709.42    4157  708.82  4267.1  704.35  4387.1  701.88  4467.1   701.6
  4487.1  700.53  4537.1  700.19  4557.1  699.37  4607.1  699.53  4617.1     699
  4637.1  699.56  4652.8   698.7  4667.1  699.55  4687.1  699.54  4832.8  697.92
  4867.1  698.02  4937.2  696.55  4957.2  696.88  4977.2  696.05  4989.2  694.89
  4990.9  694.09  5003.5  694.09  5005.2  694.89  5007.2  696.27  5014.7  696.44
  5113.2   698.2  5310.1  700.92  5407.2  702.28    5507  704.99  5649.8  709.12
#Mann= 8 ,-1 , 0
  4121.8      .1       0  4832.8     .08       0  4989.2     .07       0
  5005.2     .08       0  5014.7     .05       0  5113.2     .08       0
  5310.1     .05       0    5507     .08       0
Bank Sta=4989.2,5005.2
XS Rating Curve= 0 ,0
Exp/Cntr=0.3,0.1

Type RM Length L Ch R = 1 ,17773   ,204,204,204
BEGIN DESCRIPTION:
Mapping XS 29cc722f
END DESCRIPTION:
XS GIS Cut Line= 2
      2013734.43      13625217.7      2012138.63     13625391.15
#Sta/Elev= 30
  4101.1  707.79    4124   707.9  4160.9  706.06  4422.4  700.88  4502.9  700.11
    4523   699.1  4533.1  699.76  4553.2  698.73  4573.3  699.09  4586.8   698.4
  4714.1  697.62  4734.2  698.58  4744.3  697.71    4775  697.52  4794.6  697.98
  4804.7  697.13  4854.9  696.19  4861.4  696.97  4872.9  696.81  4973.7   695.9
  4985.7  695.23  4997.8  690.72  4999.5  689.92  5012.1  689.92  5013.8  690.72
  5015.9  695.51    5026  696.33  5317.7  700.07  5458.5  703.74  5706.3  711.62
#Mann= 6 ,-1 , 0
  4101.1      .1       0    4775     .12       0  4872.9     .07       0
  4973.7      .1       0  4997.8     .07       0  5013.8      .1       0
Bank Sta=4997.8,5013.8
XS Rating Curve= 0 ,0
Exp/Cntr=0.3,0.1

Type RM Length L Ch R = 1 ,17569   ,382,382,382
BEGIN DESCRIPTION:
Mapping XS a89d0ecf
END DESCRIPTION:
XS GIS Cut Line= 2
      2013734.37     13624935.59      2012210.51     13625249.72
#Sta/Elev= 30
  4046.8  709.12  4240.2  706.04  4266.2  706.11  4291.2   705.2  4311.4  705.35
  4423.9  703.14  4512.6  702.29  4517.7   701.6    4669     699  4708.6  698.96
  4723.8  698.32  4873.2  696.68  4903.8  694.17  4909.8  694.09  4914.9  695.32
  4954.9  694.17  4960.1  693.33  4965.2  695.03  4985.5  695.38  5002.4  690.46
  5004.1  689.66  5016.7  689.66  5018.4  690.46  5026.3  696.02  5027.2  695.99
  5087.6  695.56  5128.3  696.32    5251  697.65  5383.7  700.04  5602.7  706.49
#Mann= 6 ,-1 , 0
  4046.8      .1       0  4723.8     .12       0  5002.4     .07       0
  5018.4     .12       0  5027.2     .07       0  5128.3      .1       0
Bank Sta=5002.4,5018.4
XS Rating Curve= 0 ,0
Exp/Cntr=0.3,0.1

Type RM Length L Ch R = 1 ,17187   ,208,208,208
BEGIN DESCRIPTION:
FORT EWELL CREEK 16.0
END DESCRIPTION:
XS GIS Cut Line= 3
      2013128.04      13624671.6      2012676.66     13624814.83
      2012179.31     13625169.46
#Sta/Elev= 30
  4508.1  705.37  4616.2   704.8  4689.6  702.89  4730.3  700.86  4742.1  700.85
  4752.6  700.03  4767.8  700.13  4773.6  699.31  4800.1  698.92  4817.8  697.93
  4832.4  697.67  4867.8  695.76  4878.5  695.83    4889  696.83  4902.2  697.24
    4972  696.61  4985.8  695.85  4988.3  690.31  4990.1  689.51  5002.7  689.51
  5004.4  690.31  5011.1  690.51  5019.7  693.69  5025.9  694.38  5097.2  694.86
  5126.7  695.83  5269.2  697.14    5284  697.86  5384.8  699.34  5592.5  705.79
#Mann= 7 ,-1 , 0
  4508.1      .1       0  4817.8     .16       0  4867.8      .1       0
    4972     .07       0  4988.3     .07       0  5004.4     .07       0
  5097.2      .1       0
Bank Sta=4988.3,5004.4
XS Rating Curve= 0 ,0
Exp/Cntr=0.3,0.1

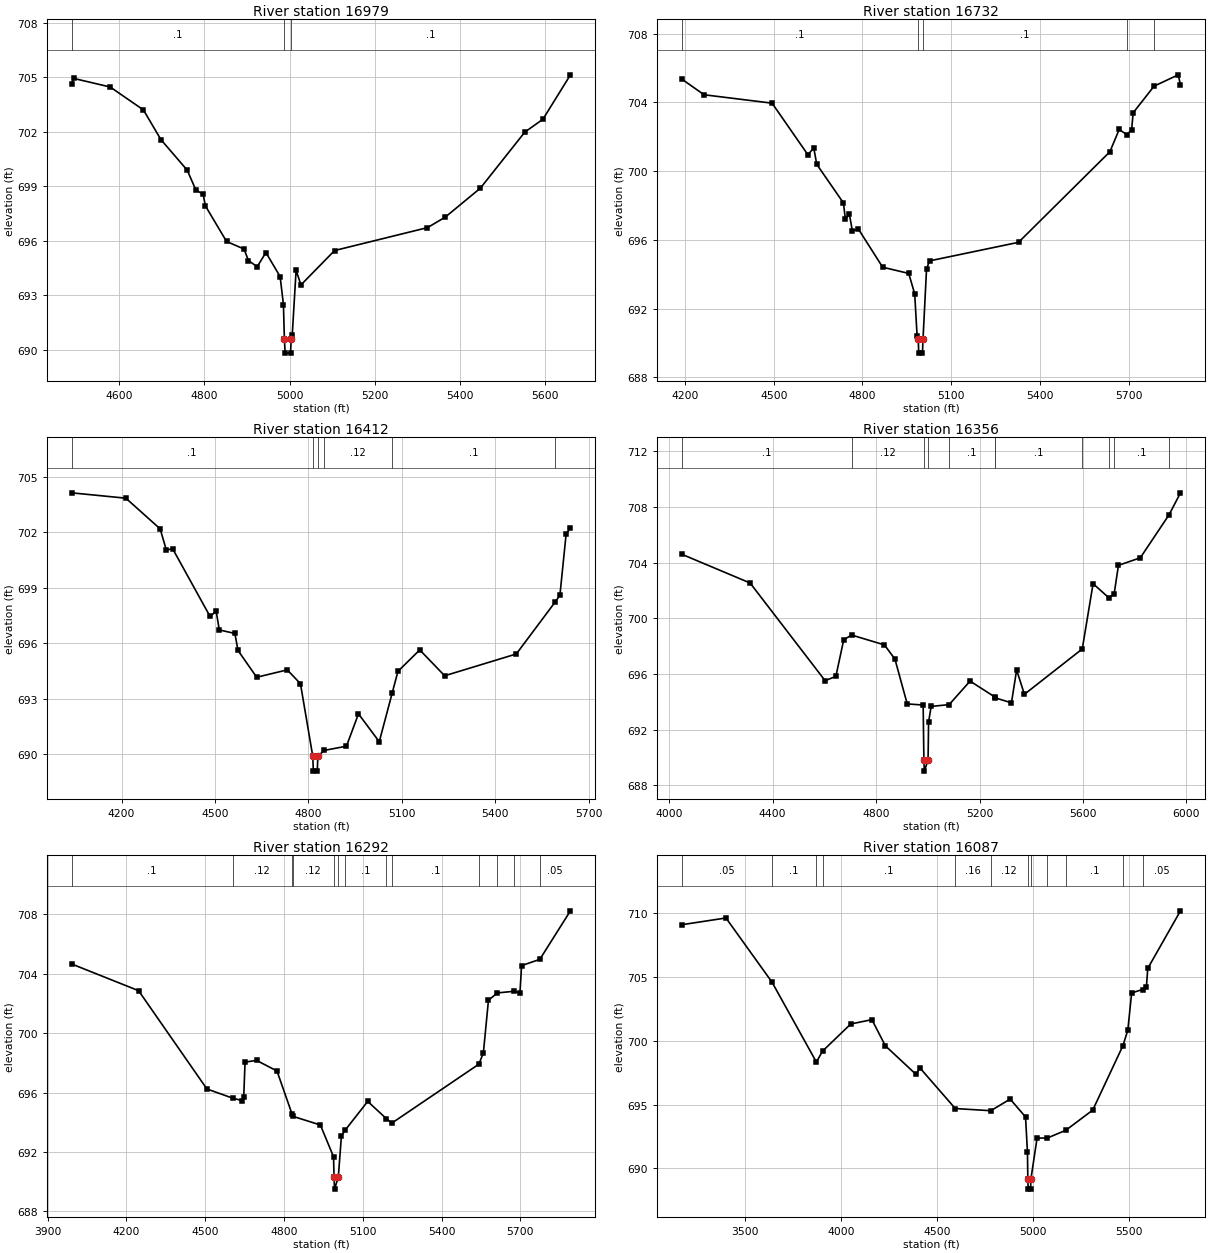
Type RM Length L Ch R = 1 ,16979   ,247,247,247
BEGIN DESCRIPTION:
Mapping XS 82040066
END DESCRIPTION:
XS GIS Cut Line= 2
      2013069.07     13624539.64      2011929.17      13624805.1
#Sta/Elev= 30
  4488.4  704.65  4493.8  704.93    4579  704.46  4656.9   703.2  4697.9  701.57
  4759.6  699.89  4780.1  698.79    4797  698.57  4802.2  697.93  4851.9  695.97
    4893  695.55  4903.3  694.92  4923.8  694.58  4944.3  695.36  4977.6  694.04
  4985.4   692.5  4987.6  690.63  4989.4  689.83    5002  689.83  5003.7  690.63
    5006   690.8  5015.1  694.38  5026.5  693.58  5105.4  695.47  5323.4  696.73
  5365.3  697.31  5447.5   698.9  5551.7  701.98  5594.3  702.69  5658.8  705.13
#Mann= 3 ,-1 , 0
  4488.4      .1       0  4987.6     .07       0  5003.7      .1       0
Bank Sta=4987.6,5003.7
XS Rating Curve= 0 ,0
Exp/Cntr=0.3,0.1

Type RM Length L Ch R = 1 ,16732   ,320,320,320
BEGIN DESCRIPTION:
Mapping XS c613aac7
END DESCRIPTION:
XS GIS Cut Line= 3
      2013290.41     13624495.38      2011961.41     13624386.33
      2011849.05     13624721.42
#Sta/Elev= 30
  4188.7  705.37  4264.4  704.45  4494.6  703.96  4615.5  700.96  4635.6  701.35
  4645.6   700.4  4735.9  698.15  4742.3  697.22    4756  697.49    4766  696.53
  4786.1  696.64  4868.6  694.41  4956.7  694.05  4976.8  692.86    4985   690.4
  4988.8  690.21  4990.5  689.41  5003.1  689.41  5004.9  690.21  5016.9  694.31
  5026.9  694.78  5327.9  695.86  5636.8  701.13  5668.4  702.43  5693.7  702.13
  5710.3   702.4  5715.6   703.4  5786.3  704.95  5868.1  705.61  5875.6  705.01
#Mann= 5 ,-1 , 0
  4188.7      .1       0  4988.8     .07       0  5004.9      .1       0
  5693.7     .05       0  5786.3     .08       0
Bank Sta=4988.8,5004.9
XS Rating Curve= 0 ,0
Exp/Cntr=0.3,0.1

Type RM Length L Ch R = 1 ,16412   ,56,56,56
BEGIN DESCRIPTION:
Mapping XS 959a1ddf
END DESCRIPTION:
XS GIS Cut Line= 5
       2013199.2     13624401.63      2012550.79     13624399.03
      2012548.19     13624122.99      2012464.85     13624122.99
      2011871.15     13624122.99
#Sta/Elev= 30
  4039.7  704.14  4213.9  703.85  4323.9  702.19  4343.9  701.04  4363.9  701.12
  4483.9  697.46  4503.9  697.72  4513.9  696.72  4563.9  696.53  4573.9  695.61
  4633.9  694.16  4732.1  694.56  4774.4  693.81    4814  689.88  4815.8  689.08
  4828.4  689.08  4830.2  689.88  4850.2   690.2  4922.1  690.43  4960.7  692.18
  5027.4  690.67  5069.3  693.33  5087.4  694.48  5157.4  695.64  5237.4  694.24
  5467.4  695.42  5592.1  698.23  5607.4   698.6  5627.4  701.92  5641.2  702.23
#Mann= 6 ,-1 , 0
  4039.7      .1       0    4814     .07       0  4830.2      .1       0
  4850.2     .12       0  5069.3      .1       0  5592.1     .08       0
Bank Sta=4814,4830.2
XS Rating Curve= 0 ,0
Exp/Cntr=0.3,0.1

Type RM Length L Ch R = 1 ,16356   ,64,64,64
BEGIN DESCRIPTION:
Mapping XS c8d3bfe7
END DESCRIPTION:
XS GIS Cut Line= 6
      2013209.68     13624378.19      2012649.75      13624380.8
      2012584.64     13624063.09      2012464.85     13624078.71
      2011878.85     13624088.56      2011652.22     13623838.77
#Sta/Elev= 30
  4048.3  704.62    4313  702.55    4603  695.53  4644.6  695.84    4675  698.47
  4705.5  698.81  4832.5   698.1    4873  697.08  4920.5  693.86  4982.1  693.78
  4984.9  689.83  4986.7  689.03  5001.1  689.83  5003.1  692.57  5013.1  693.68
  5082.6  693.81  5163.5   695.5  5258.3  694.37  5261.4  694.29  5323.5  693.94
  5343.5   696.3  5373.5  694.55  5597.3  697.81  5639.1   702.5  5699.3   701.5
  5720.2  701.73  5737.2  703.82  5821.7  704.36  5932.8  707.45    5977  709.03
#Mann= 11 ,-1 , 0
  4048.3      .1       0  4705.5     .12       0  4984.9     .07       0
  5001.1     .12       0  5082.6      .1       0  5258.3     .12       0
  5261.4      .1       0  5597.3     .08       0  5699.3     .05       0
  5720.2      .1       0  5932.8     .05       0
Bank Sta=4984.9,5001.1
XS Rating Curve= 0 ,0
Exp/Cntr=0.3,0.1

Type RM Length L Ch R = 1 ,16292   ,205,205,205
BEGIN DESCRIPTION:
Mapping XS 0e6317b3
END DESCRIPTION:
XS GIS Cut Line= 5
      2013220.04     13624354.76      2012673.19     13624354.76
      2012605.48     13624042.26      2011881.08     13624069.18
      2011699.41     13623820.96
#Sta/Elev= 30
  3991.6  704.66  4246.6  702.86  4506.6  696.24  4604.5  695.62  4640.5  695.46
  4646.8  695.67  4651.9  698.05    4696  698.16  4773.5  697.45  4831.2  694.53
  4833.3   694.4  4938.7  693.81  4988.8  691.67  4990.7  690.29  4992.5  689.49
  5006.9  690.29  5018.8  693.07  5032.9  693.46  5118.9   695.4  5190.4  694.23
  5210.9  693.94  5542.2  697.91  5559.2  698.67  5578.6  702.22  5612.8  702.71
  5676.6  702.82  5698.5  702.71  5704.7  704.55  5774.1  704.97  5890.7  708.24
#Mann= 13 ,-1 , 0
  3991.6      .1       0  4604.5     .12       0  4831.2      .1       0
  4833.3     .12       0  4990.7     .07       0  5006.9     .12       0
  5032.9      .1       0  5190.4     .12       0  5210.9      .1       0
  5542.2     .08       0  5612.8     .05       0  5676.6      .1       0
  5774.1     .05       0
Bank Sta=4990.7,5006.9
XS Rating Curve= 0 ,0
Exp/Cntr=0.3,0.1

Type RM Length L Ch R = 1 ,16087   ,179,179,179
BEGIN DESCRIPTION:
Mapping XS 02db2193
END DESCRIPTION:
XS GIS Cut Line= 3
      2014225.82     13623878.29       2011934.2     13623868.37
      2011642.56     13623775.87
#Sta/Elev= 30
  3170.8  709.08  3401.6  709.61  3641.6  704.58  3872.4  698.33  3904.8  699.19
  4051.6  701.31  4161.6  701.65  4231.6   699.6  4391.6  697.36  4411.6  697.87
  4595.8  694.69  4780.7  694.52  4881.6  695.43  4961.6  694.03  4971.6  691.26
  4973.5  689.18  4975.3  688.38  4987.9  688.38  4989.7  689.18  5021.6  692.38
  5074.9  692.38  5171.5  692.99  5311.6  694.57  5468.7  699.61  5494.2  700.83
  5514.1  703.74  5570.9  704.01    5591   704.2    5598  705.66  5768.4  710.17
#Mann= 12 ,-1 , 0
  3170.8     .05       0  3641.6      .1       0  3872.4     .16       0
  3904.8      .1       0  4595.8     .16       0  4780.7     .12       0
  4973.5     .07       0  4989.7     .12       0  5074.9     .12       0
  5171.5      .1       0  5468.7     .08       0  5570.9     .05       0
Bank Sta=4973.5,4989.7
XS Rating Curve= 0 ,0
Exp/Cntr=0.3,0.1

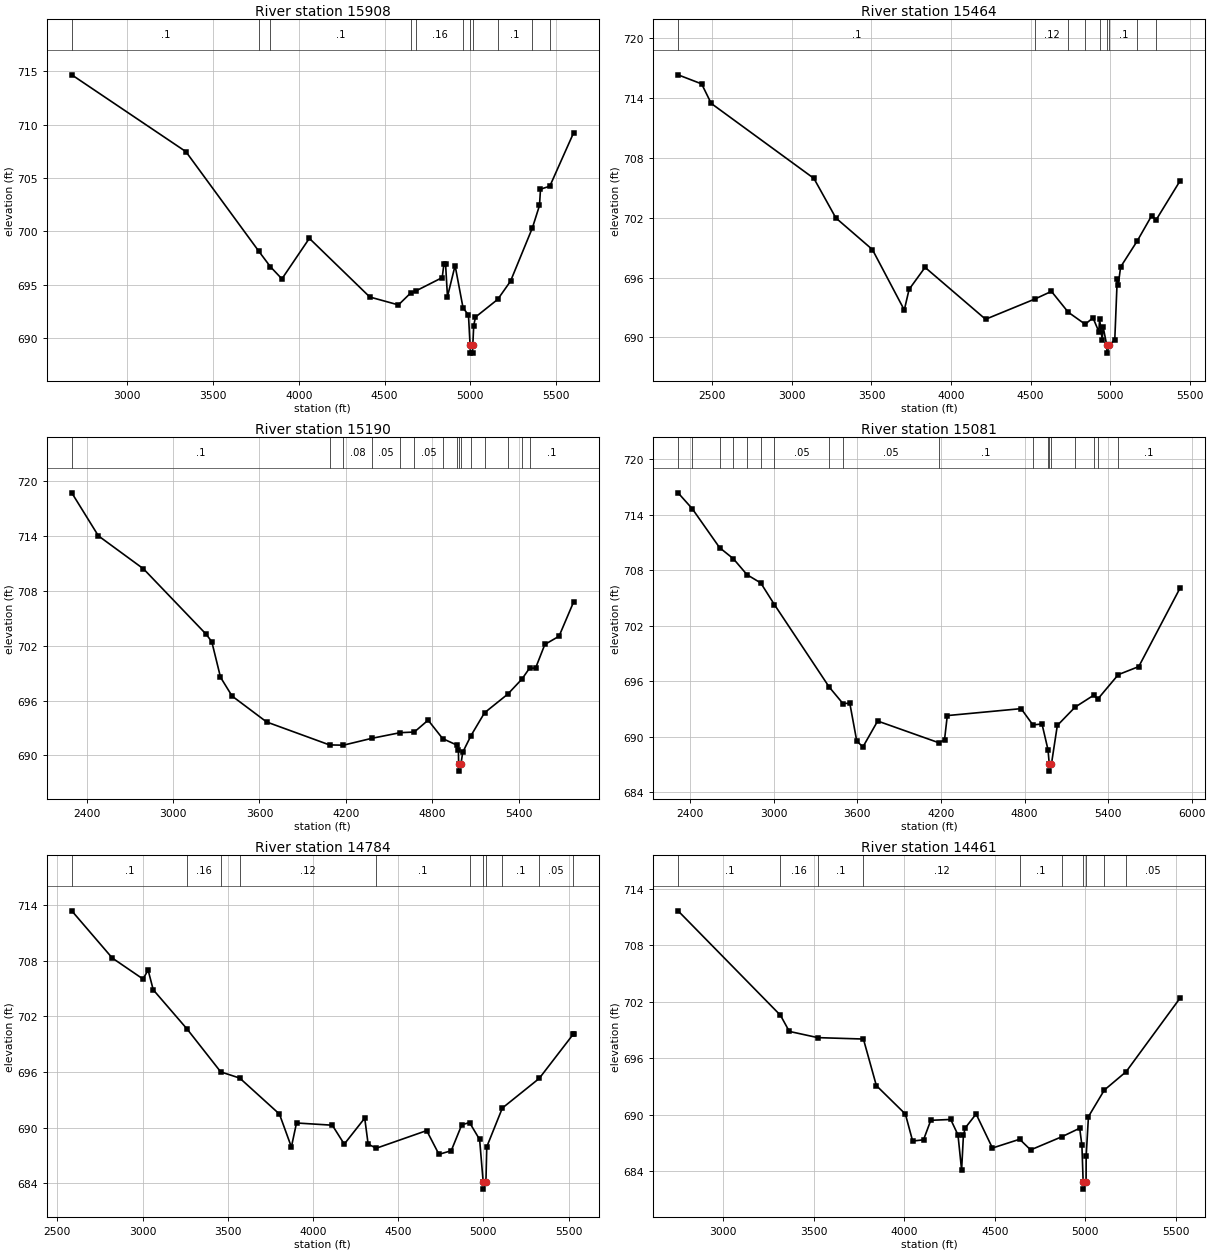
Type RM Length L Ch R = 1 ,15908   ,444,444,444
BEGIN DESCRIPTION:
Mapping XS a9298068
END DESCRIPTION:
XS GIS Cut Line= 4
      2014590.43     13623576.21      2013147.62       13623560.
      2011950.86      13623807.2      2011699.07     13623734.48
#Sta/Elev= 30
  2675.8  714.68  3341.3  707.48  3766.7  698.14  3834.1  696.69  3901.3  695.55
  4061.3  699.35  4413.9  693.85  4580.9  693.11  4654.2  694.26  4682.6  694.42
  4836.1  695.67  4846.4  696.99  4855.8   696.9  4866.8  693.89  4911.2   696.8
  4957.6  692.84  4989.3  692.15  4998.5  689.39  5000.3  688.59  5012.9  688.59
  5014.7  689.39  5019.9  691.18  5030.2  691.97  5159.8  693.63  5234.4  695.33
  5362.2  700.34  5403.4  702.43  5409.3  703.96  5463.7  704.24  5602.8  709.26
#Mann= 11 ,-1 , 0
  2675.8      .1       0  3766.7     .16       0  3834.1      .1       0
  4654.2     .12       0  4682.6     .16       0  4957.6     .12       0
  4998.5     .07       0  5014.7     .12       0  5159.8      .1       0
  5362.2     .08       0  5463.7     .05       0
Bank Sta=4998.5,5014.7
XS Rating Curve= 0 ,0
Exp/Cntr=0.3,0.1

Type RM Length L Ch R = 1 ,15464   ,274,274,274
BEGIN DESCRIPTION:
Mapping XS aec2a9bc
END DESCRIPTION:
XS GIS Cut Line= 3
      2014772.76     13623492.88      2012201.83     13623302.67
      2011712.57     13623606.35
#Sta/Elev= 30
  2284.6  716.35  2432.8  715.44  2492.9  713.48  3138.3  705.95  3276.2  701.98
  3505.7  698.81  3706.2  692.74  3736.3  694.81  3836.6  697.02  4216.9  691.81
    4528  693.85  4630.7  694.61  4736.2  692.52  4842.8  691.31  4891.8  691.95
  4928.5  690.57  4933.6  691.79  4949.7  689.76  4955.6  691.04  4978.2  689.21
    4980  688.41  4994.4  689.21  5028.8  689.76  5044.2  695.87  5050.1  695.21
  5065.4  697.06  5169.8  699.67  5260.3   702.2  5287.9  701.77  5438.4  705.69
#Mann= 9 ,-1 , 0
  2284.6      .1       0    4528     .12       0  4736.2     .16       0
  4842.8     .12       0  4933.6      .1       0  4978.2     .07       0
  4994.4      .1       0  5169.8     .08       0  5287.9     .05       0
Bank Sta=4978.2,4994.4
XS Rating Curve= 0 ,0
Exp/Cntr=0.3,0.1

Type RM Length L Ch R = 1 ,15190   ,109,109,109
BEGIN DESCRIPTION:
Mapping XS 4ad6fa09
END DESCRIPTION:
XS GIS Cut Line= 4
      2014908.13      13623282.8      2013843.32     13623143.38
       2012058.6     13623160.75      2011637.97     13623620.98
#Sta/Elev= 30
  2297.6  718.75  2482.3  714.04  2794.9  710.43  3228.6  703.29  3268.9  702.46
  3329.5  698.56  3409.8   696.5  3649.8  693.66  4085.8  691.15  4181.9  691.12
  4378.8  691.87  4575.6  692.49  4674.1  692.56  4769.9  693.86  4870.9  691.84
  4969.4  691.13  4979.9  690.59  4981.8  689.08  4983.6  688.28    4998  689.08
  5009.9  690.34  5067.8  692.18  5161.4  694.67  5322.5  696.71  5420.9  698.36
  5473.5  699.55  5515.5  699.56  5579.7  702.15  5678.3  703.05  5779.8  706.82
#Mann= 15 ,-1 , 0
  2297.6      .1       0  4085.8     .05       0  4181.9     .08       0
  4378.8     .05       0  4575.6     .08       0  4674.1     .05       0
  4870.9     .08       0  4969.4     .05       0  4981.8     .04       0
    4998     .05       0  5067.8     .08       0  5161.4      .1       0
  5322.5     .05       0  5420.9     .08       0  5473.5      .1       0
Bank Sta=4981.8,4998
XS Rating Curve= 0 ,0
Exp/Cntr=0.3,0.1

Type RM Length L Ch R = 1 ,15081   ,297,297,297
BEGIN DESCRIPTION:
Mapping XS 994e0aa0
END DESCRIPTION:
XS GIS Cut Line= 3
      2014908.14     13623084.89      2012075.96     13623053.11
      2011540.72     13623608.94
#Sta/Elev= 30
  2312.3  716.38  2414.3  714.66    2611  710.44  2709.4  709.25  2807.7  707.52
  2906.1  706.63  3004.5  704.28  3397.9  695.36  3496.3  693.58  3545.5  693.62
  3595.5  689.52  3639.8  688.89  3745.5  691.69  4184.9  689.34  4225.6  689.65
  4245.6  692.28  4775.6  693.03  4860.2  691.27  4925.6  691.37  4968.9  688.57
  4977.5  687.07  4979.3  686.27  4993.7  687.07  5035.6  691.21  5162.9  693.19
  5295.7  694.47  5326.9  694.08  5473.5  696.71  5620.4  697.58  5916.3  706.06
#Mann= 18 ,-1 , 0
  2312.3     .05       0  2414.3     .08       0    2611     .05       0
  2709.4     .08       0  2807.7     .05       0  2906.1     .08       0
  3004.5     .05       0  3397.9     .08       0  3496.3     .05       0
  4184.9      .1       0  4860.2     .12       0  4968.9      .1       0
  4977.5     .07       0  4993.7      .1       0  5162.9     .08       0
  5295.7      .1       0  5326.9     .05       0  5473.5      .1       0
Bank Sta=4977.5,4993.7
XS Rating Curve= 0 ,0
Exp/Cntr=0.3,0.1

Type RM Length L Ch R = 1 ,14784   ,323,323,323
BEGIN DESCRIPTION:
Mapping XS e7b8b76b
END DESCRIPTION:
XS GIS Cut Line= 4
      2014802.65     13623045.74      2012843.32     13622980.19
       2012221.8     13622830.88      2012027.36     13622546.18
#Sta/Elev= 30
    2585  713.36  2822.8  708.27  3002.9  706.01  3032.9  706.97  3062.9  704.85
  3262.3   700.6  3458.8     696  3570.4  695.33  3803.3  691.45  3873.4   687.9
  3903.4  690.49  4113.5  690.25  4183.5  688.21  4303.6  691.01  4323.6  688.21
  4371.7  687.77  4667.1  689.67  4739.1  687.11  4811.1   687.5  4872.8  690.29
  4918.4  690.54  4977.6  688.71  4998.4  684.16  5000.2  683.36  5014.6  684.16
  5019.6  687.92  5110.9   692.1  5327.1  695.29  5526.9  700.06  5529.4  700.08
#Mann= 11 ,-1 , 0
    2585      .1       0  3262.3     .16       0  3458.8      .1       0
  3570.4     .12       0  4371.7      .1       0  4918.4     .12       0
  4998.4     .07       0  5014.6     .12       0  5110.9      .1       0
  5327.1     .05       0  5526.9      .1       0
Bank Sta=4998.4,5014.6
XS Rating Curve= 0 ,0
Exp/Cntr=0.3,0.1

Type RM Length L Ch R = 1 ,14461   ,233,233,233
BEGIN DESCRIPTION:
Mapping XS 574eb815
END DESCRIPTION:
XS GIS Cut Line= 3
       2014748.4     13622987.66      2013006.52      13622903.8
      2012136.07     13622359.34
#Sta/Elev= 30
  2751.8  711.64  3317.1  700.56  3365.9  698.85  3523.1  698.19    3775  698.04
  3846.5   693.1  4006.7  690.08  4046.7  687.22  4106.8  687.35  4146.8  689.42
  4256.9  689.51    4297  687.87    4317  684.14    4327  687.82    4337  688.61
  4397.1  690.09  4487.2  686.48  4637.6  687.41    4698  686.28  4870.8  687.68
  4968.8  688.58  4981.1  686.77  4987.9  682.92  4989.7  682.12  5004.1  682.92
  5004.7  685.67  5017.2  689.81  5104.9  692.63  5225.4  694.58  5522.4  702.37
#Mann= 10 ,-1 , 0
  2751.8      .1       0  3317.1     .16       0  3523.1      .1       0
    3775     .12       0  4637.6      .1       0  4870.8     .12       0
  4987.9     .07       0  5004.1     .12       0  5104.9      .1       0
  5225.4     .05       0
Bank Sta=4987.9,5004.1
XS Rating Curve= 0 ,0
Exp/Cntr=0.3,0.1