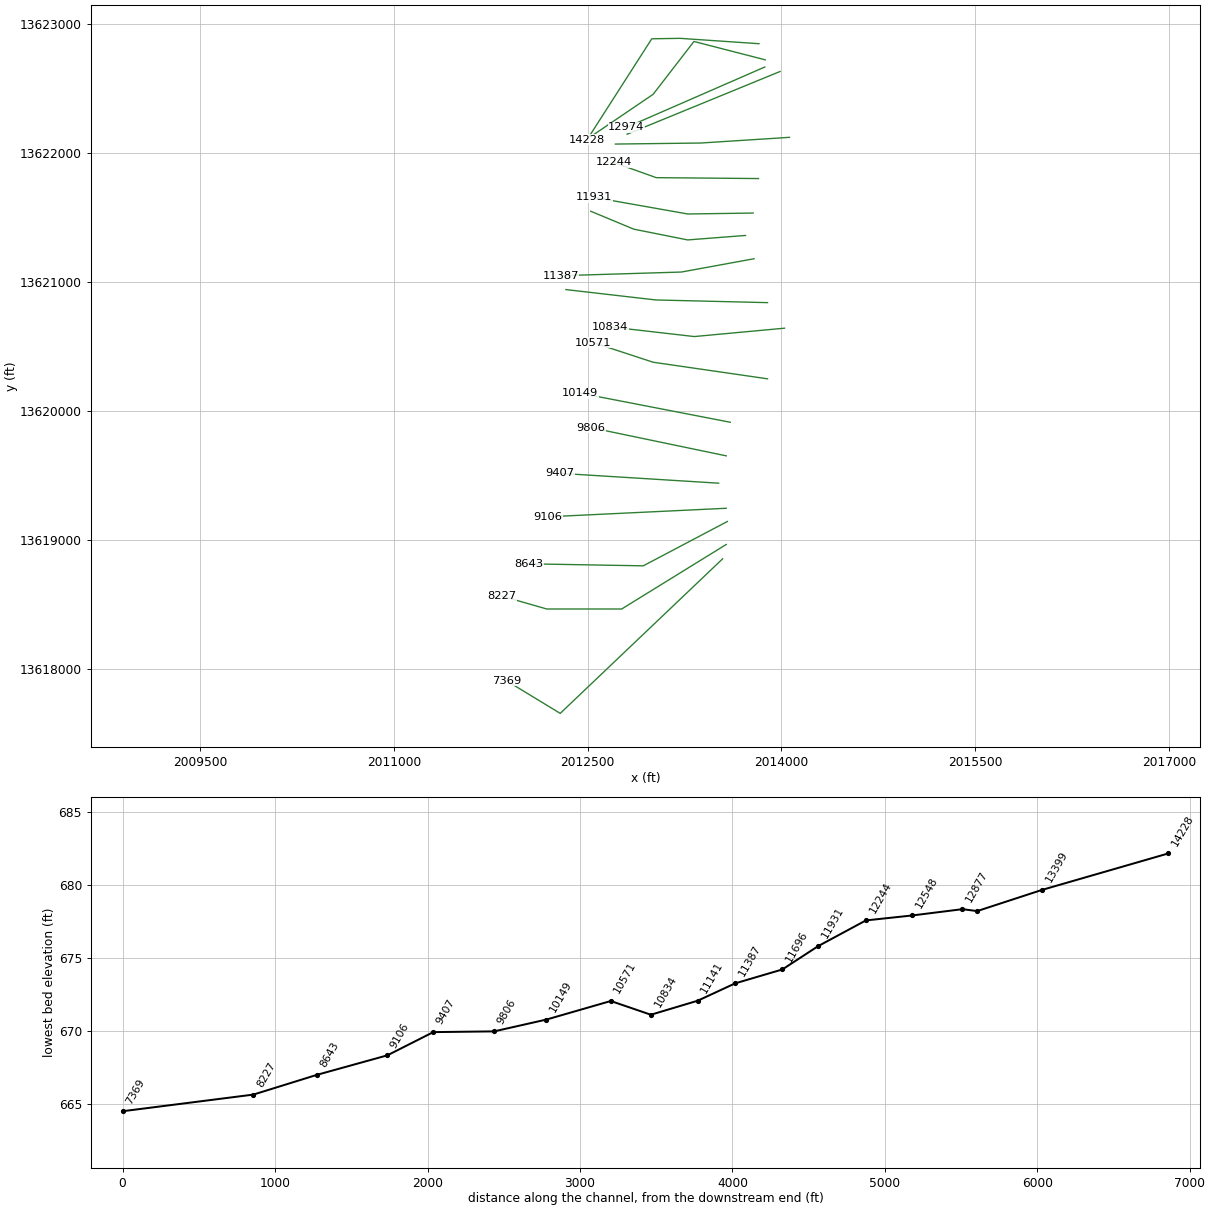
HEC-RAS study FORT EWELL CREEK.prj: FORT EWELL CREEK Base Level Engineering

--- FORT EWELL CREEK.g01 (geometry) --- (continued)

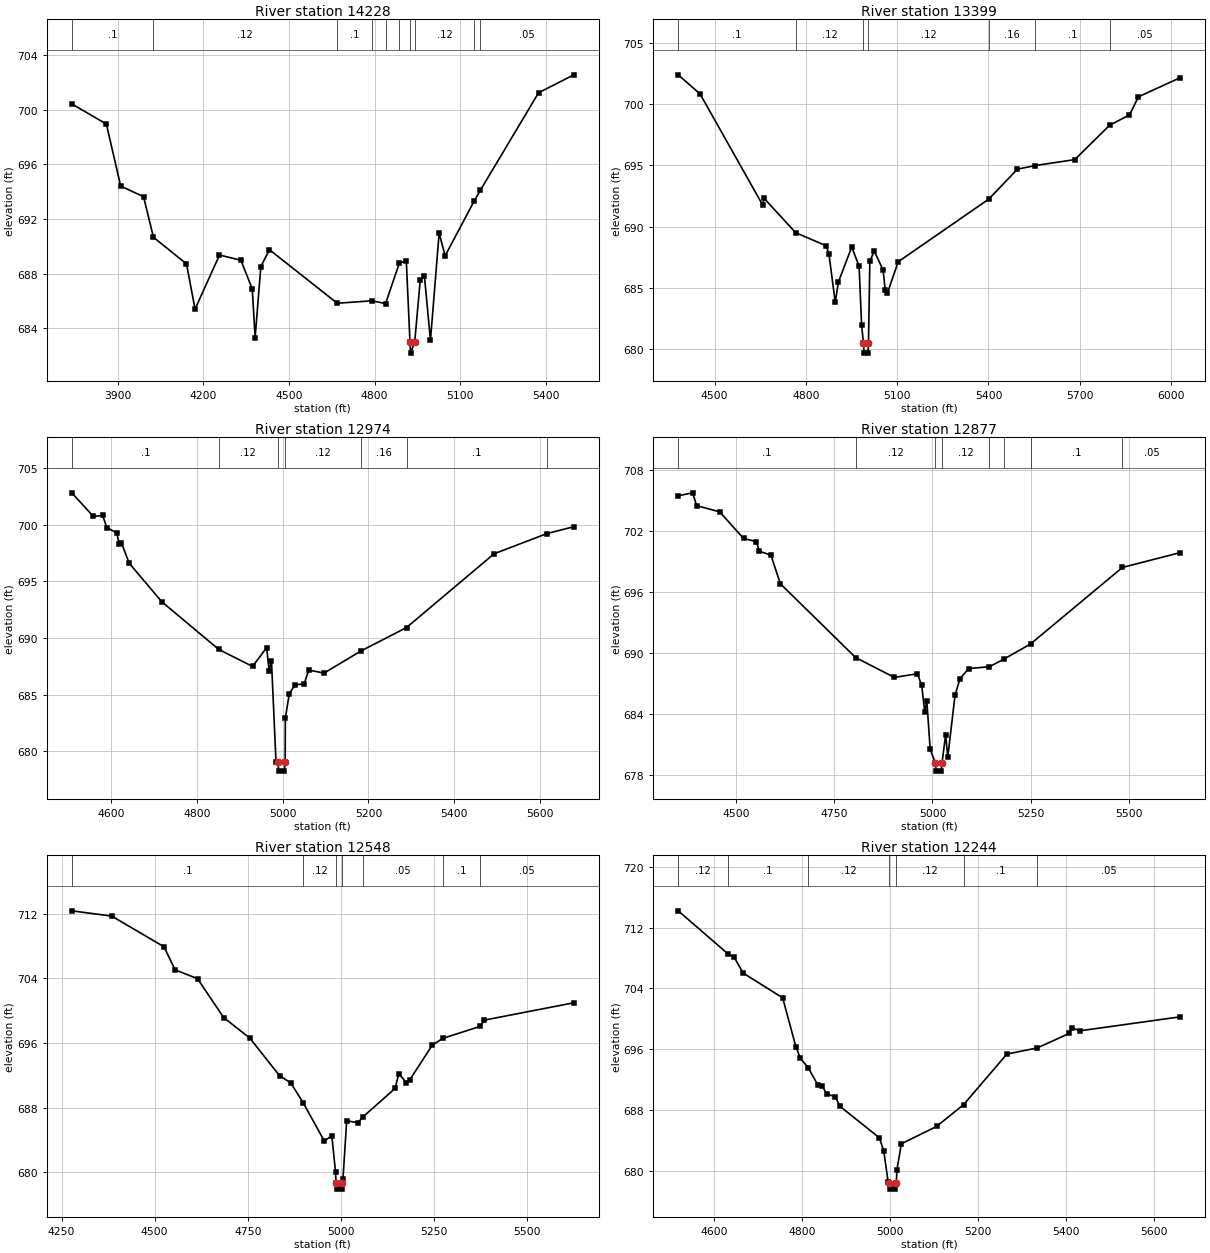
Type RM Length L Ch R = 1 ,14228   ,829,829,829
BEGIN DESCRIPTION:
Mapping XS 408c73a5
END DESCRIPTION:
XS GIS Cut Line= 4
      2013825.93     13622844.78      2013214.85     13622886.44
       2012996.1     13622882.97      2012496.11     13622101.74
#Sta/Elev= 30
  3738.9  700.43  3860.1  698.96  3910.2  694.42  3990.4  693.64    4025  690.67
  4140.8  688.72  4170.8  685.41  4256.4  689.37  4331.2  688.99  4371.2  686.89
  4381.2  683.33  4401.3  688.53  4431.3  689.76    4669  685.84  4790.2  686.02
  4838.2  685.82  4886.6  688.79  4910.8  688.93  4923.7  682.99  4925.6  682.19
  4940.2  682.99  4959.6  687.54  4974.2  687.83  4995.4  683.13  5025.8  690.97
  5046.9  689.32  5148.3  693.31  5170.2  694.11  5374.2  701.25  5497.7  702.56
#Mann= 10 ,-1 , 0
  3738.9      .1       0    4025     .12       0    4669      .1       0
  4790.2     .12       0  4838.2      .1       0  4886.6     .12       0
  4923.7     .07       0  4940.2     .12       0  5148.3      .1       0
  5170.2     .05       0
Bank Sta=4923.7,4940.2
XS Rating Curve= 0 ,0
Exp/Cntr=0.3,0.1

Type RM Length L Ch R = 1 ,13399   ,425,425,425
BEGIN DESCRIPTION:
Mapping XS bd063001
END DESCRIPTION:
XS GIS Cut Line= 4
      2013874.53     13622719.78      2013322.49     13622862.13
      2013006.52     13622452.41      2012541.27     13622136.46
#Sta/Elev= 30
  4380.5  702.37  4452.3  700.81  4657.7  691.77  4662.9   692.3  4766.2  689.51
  4866.3  688.44  4875.7  687.78  4896.4  683.83  4906.9  685.49  4950.6  688.34
  4974.8  686.77    4983  681.99  4989.2  680.49  4991.1  679.69  5003.8  679.69
  5005.7  680.49  5010.1  687.16  5024.6  688.02  5053.6  686.46  5060.6  684.87
  5068.1   684.6  5103.4  687.14  5400.4  692.23  5495.1  694.68  5554.4  694.98
  5683.6  695.46  5798.5  698.27  5863.3   699.1  5892.9  700.58  6030.4  702.14
#Mann= 7 ,-1 , 0
  4380.5      .1       0  4766.2     .12       0  4989.2     .07       0
  5005.7     .12       0  5400.4     .16       0  5554.4      .1       0
  5798.5     .05       0
Bank Sta=4989.2,5005.7
XS Rating Curve= 0 ,0
Exp/Cntr=0.3,0.1

Type RM Length L Ch R = 1 ,12974   ,97,97,97
BEGIN DESCRIPTION:
Mapping XS 905a941b
END DESCRIPTION:
XS GIS Cut Line= 2
       2013871.1     13622664.22      2012799.05     13622195.84
#Sta/Elev= 30
  4508.6   702.8  4558.9  700.72  4580.7   700.8  4590.1  699.73  4613.5  699.26
    4619  698.24  4624.4  698.37  4642.4  696.59    4718   693.2  4851.1  688.98
  4929.9  687.48  4962.7  689.14  4968.4  687.09  4973.9  687.99  4984.5  679.04
  4988.8  679.04  4990.9  678.24  5003.7  678.24  5005.8  679.04  5006.3  682.92
  5015.2  685.03  5028.2  685.85    5050  685.94  5060.9  687.16  5096.4  686.89
  5182.7  688.85  5288.6  690.91  5492.6  697.42  5615.5   699.2  5678.5  699.81
#Mann= 7 ,-1 , 0
  4508.6      .1       0  4851.1     .12       0  4988.8     .07       0
  5005.8     .12       0  5182.7     .16       0  5288.6      .1       0
  5615.5     .05       0
Bank Sta=4988.8,5005.8
XS Rating Curve= 0 ,0
Exp/Cntr=0.3,0.1

Type RM Length L Ch R = 1 ,12877   ,329,329,329
BEGIN DESCRIPTION:
Mapping XS 6a83cfd4
END DESCRIPTION:
XS GIS Cut Line= 2
      2013989.15     13622629.49      2012805.15     13622143.39
#Sta/Elev= 30
  4351.9  705.46  4388.8  705.75  4398.7  704.49  4457.5  703.88  4518.5  701.26
    4551  700.95  4558.8     700  4588.2  699.62  4612.1  696.81  4804.2  689.54
  4902.9  687.59  4961.7  687.95  4972.5  686.81  4980.2  684.23  4985.6  685.25
  4994.2  680.52  5007.3  679.17  5009.4  678.37  5022.2  678.37  5024.3  679.17
  5033.6  681.95    5039  679.74  5057.5  685.83  5069.8  687.44  5092.3  688.46
    5145  688.64  5181.7  689.38    5250  690.88  5484.3  698.41  5631.8  699.87
#Mann= 8 ,-1 , 0
  4351.9      .1       0  4804.2     .12       0  5007.3     .07       0
  5024.3     .12       0    5145     .16       0  5181.7     .12       0
    5250      .1       0  5484.3     .05       0
Bank Sta=5007.3,5024.3
XS Rating Curve= 0 ,0
Exp/Cntr=0.3,0.1

Type RM Length L Ch R = 1 ,12548   ,304,304,304
BEGIN DESCRIPTION:
FORT EWELL CREEK 15.0
END DESCRIPTION:
XS GIS Cut Line= 3
      2014062.08     13622119.08        2013375.       13622075.
      2012714.84       13622067.
#Sta/Elev= 30
  4277.3  712.35  4384.6   711.7  4524.9  707.91    4555  705.05  4615.1  703.96
  4685.2  699.16  4755.4  696.62  4835.5  691.97  4865.6  691.07  4899.2   688.6
  4955.8  683.88  4975.8  684.55  4985.8  680.08  4987.3  678.74  4989.4  677.94
  5002.2  677.94  5004.3  678.74  5005.8  679.17  5015.8  686.39  5045.8  686.15
  5059.9  686.89  5145.8  690.39  5155.8  692.23  5175.8  691.11  5185.8  691.49
  5245.8  695.75  5274.1  696.58  5374.5  698.07  5385.8  698.84    5626  700.98
#Mann= 7 ,-1 , 0
  4277.3      .1       0  4899.2     .12       0  4987.3     .07       0
  5004.3     .12       0  5059.9     .05       0  5274.1      .1       0
  5374.5     .05       0
Bank Sta=4987.3,5004.3
XS Rating Curve= 0 ,0
Exp/Cntr=0.3,0.1

Type RM Length L Ch R = 1 ,12244   ,313,313,313
BEGIN DESCRIPTION:
Mapping XS f9a3c485
END DESCRIPTION:
XS GIS Cut Line= 3
      2013822.48     13621799.63      2013030.82     13621806.58
        2012701.     13621924.62
#Sta/Elev= 30
  4518.3   714.2  4631.6  708.53  4645.8  708.07  4665.8  706.02  4755.8  702.76
  4785.8  696.34  4795.8  694.85  4814.1  693.54  4835.8   691.3  4845.8  691.18
  4855.8  690.12  4875.8  689.74  4885.8  688.51  4975.8  684.35  4985.8  682.61
  4995.8  678.51  4997.3   678.4  4999.4   677.6  5012.2   677.6  5014.3   678.4
  5015.8  680.17  5025.8  683.56  5105.8  685.84  5167.4  688.71  5265.8  695.36
    5335  696.17  5407.8  698.08  5413.1   698.8    5433  698.43  5660.3  700.26
#Mann= 7 ,-1 , 0
  4518.3     .12       0  4631.6      .1       0  4814.1     .12       0
  4997.3     .07       0  5014.3     .12       0  5167.4      .1       0
    5335     .05       0
Bank Sta=4997.3,5014.3
XS Rating Curve= 0 ,0
Exp/Cntr=0.3,0.1

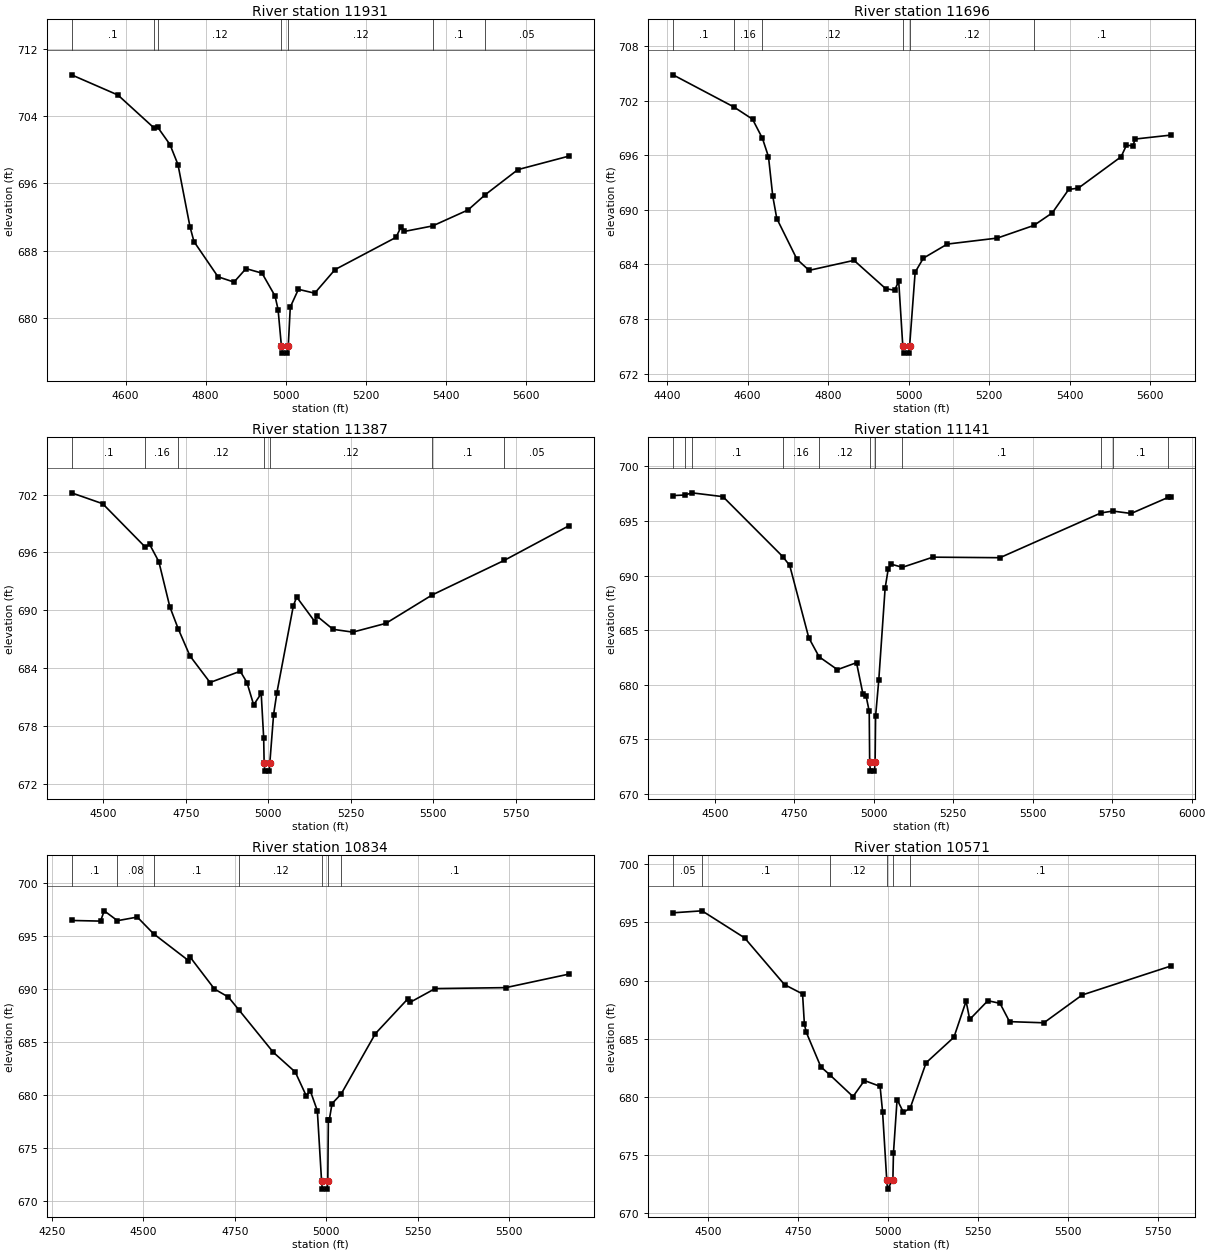
Type RM Length L Ch R = 1 ,11931   ,235,235,235
BEGIN DESCRIPTION:
FORT EWELL CREEK 14.0
END DESCRIPTION:
XS GIS Cut Line= 3
      2013780.84     13621532.27        2013275.       13621525.
       2012549.1     13621653.64
#Sta/Elev= 30
    4465   708.9  4580.9   706.5  4670.6  702.61  4680.3  702.67  4710.9  700.62
  4730.9  698.24  4760.9  690.86  4770.9  689.09  4830.9  684.91  4870.9  684.28
  4900.9  685.88  4940.9  685.34  4973.4  682.63    4981  681.02  4989.4  676.64
  4991.5  675.84  5004.3  675.84  5006.4  676.64  5011.5  681.31  5031.8  683.42
  5072.5  682.96  5123.2  685.76  5275.6  689.59  5288.4  690.86  5295.9  690.29
  5367.1  690.95  5455.7  692.85  5498.4  694.65  5580.2  697.64  5708.1  699.25
#Mann= 7 ,-1 , 0
    4465      .1       0  4670.6     .16       0  4680.3     .12       0
  4989.4     .07       0  5006.4     .12       0  5367.1      .1       0
  5498.4     .05       0
Bank Sta=4989.4,5006.4
XS Rating Curve= 0 ,0
Exp/Cntr=0.3,0.1

Type RM Length L Ch R = 1 ,11696   ,309,309,309
BEGIN DESCRIPTION:
Mapping XS 3a6a4aaf
END DESCRIPTION:
XS GIS Cut Line= 4
      2013721.82     13621358.66      2013273.88     13621323.94
      2012857.21     13621407.27      2012523.89     13621546.16
#Sta/Elev= 30
    4415  704.84  4565.5  701.32  4612.4  699.96    4637  697.85    4652  695.83
  4662.6   691.5  4672.6  689.04  4722.7  684.56  4752.8  683.34  4864.3  684.44
  4942.9  681.33  4965.1  681.15  4975.3  682.15  4985.4  675.04  4987.5  674.24
  5000.3  674.24  5002.4  675.04  5016.1  683.14  5036.5  684.68  5095.9  686.23
  5220.1  686.89  5310.8  688.28  5356.6  689.66  5397.4  692.24  5421.2  692.38
  5527.4  695.83  5540.8   697.1  5556.7  697.03  5562.4  697.78  5650.3  698.21
#Mann= 6 ,-1 , 0
    4415      .1       0  4565.5     .16       0    4637     .12       0
  4985.4     .07       0  5002.4     .12       0  5310.8      .1       0
Bank Sta=4985.4,5002.4
XS Rating Curve= 0 ,0
Exp/Cntr=0.3,0.1

Type RM Length L Ch R = 1 ,11387   ,246,246,246
BEGIN DESCRIPTION:
FORT EWELL CREEK 13.0
END DESCRIPTION:
XS GIS Cut Line= 3
      2013787.72      13621178.1        2013225.       13621075.
      2012290.12     13621046.69
#Sta/Elev= 30
  4403.7  702.18    4498  701.05  4627.3  696.54  4640.3  696.83  4668.2  695.03
  4701.3  690.37  4726.8  688.07  4762.3  685.26  4823.3  682.49  4914.8  683.66
  4935.1  682.49  4955.5  680.17  4978.3  681.35  4985.8  676.73  4987.2  674.09
  4989.4  673.29  5002.2  673.29  5004.3  674.09  5015.8  679.15  5025.8  681.43
  5075.8  690.47  5085.8  691.36  5140.9   688.8  5145.9  689.42  5195.9  688.01
  5255.9  687.72    5356  688.63  5496.3  691.58  5714.2  695.16  5911.1  698.77
#Mann= 7 ,-1 , 0
  4403.7      .1       0  4627.3     .16       0  4726.8     .12       0
  4987.2     .07       0  5004.3     .12       0  5496.3      .1       0
  5714.2     .05       0
Bank Sta=4987.2,5004.3
XS Rating Curve= 0 ,0
Exp/Cntr=0.3,0.1

Type RM Length L Ch R = 1 ,11141   ,307,307,307
BEGIN DESCRIPTION:
Mapping XS 95aeffa3
END DESCRIPTION:
XS GIS Cut Line= 3
      2013891.92     13620837.83      2013027.35     13620858.66
       2012331.8     13620939.05
#Sta/Elev= 30
  4368.7  697.33  4406.8  697.38  4427.8  697.58  4525.7  697.23  4713.5  691.75
  4735.7  690.93  4795.7  684.31  4828.1  682.57  4885.8  681.39  4945.8  682.03
  4965.8   679.2  4975.8  678.99  4985.8  677.58  4987.2   672.9  4989.4   672.1
  5002.2   672.1  5004.3   672.9  5005.8  677.13  5015.8  680.42  5035.8  688.85
  5045.8  690.65  5055.8  691.04    5090  690.76  5185.9  691.69  5396.9  691.64
  5714.8  695.74  5751.9  695.91  5809.7  695.69  5925.8  697.16  5933.7  697.24
#Mann= 11 ,-1 , 0
  4368.7      .1       0  4406.8     .05       0  4427.8      .1       0
  4713.5     .16       0  4828.1     .12       0  4987.2     .07       0
  5004.3     .12       0    5090      .1       0  5714.8     .05       0
  5751.9      .1       0  5925.8     .05       0
Bank Sta=4987.2,5004.3
XS Rating Curve= 0 ,0
Exp/Cntr=0.3,0.1

Type RM Length L Ch R = 1 ,10834   ,263,263,263
BEGIN DESCRIPTION:
FORT EWELL CREEK 12.0
END DESCRIPTION:
XS GIS Cut Line= 3
      2014023.92     13620639.92        2013325.       13620575.
      2012671.33     13620650.14
#Sta/Elev= 30
  4303.9   696.5  4383.2  696.44  4393.2  697.41  4429.4  696.48  4483.6  696.82
  4527.9  695.25  4623.3  692.72  4628.3  693.03  4694.5  690.03  4732.6  689.27
  4762.2  688.02  4855.2  684.06  4915.4  682.19  4945.6  679.93  4956.2  680.44
  4975.7  678.54  4987.2  671.94  4989.4  671.14  5002.2  671.14  5004.3  671.94
  5005.8  677.67  5008.3  677.67  5015.9  679.21  5040.8  680.12  5134.4  685.82
  5223.5  689.12  5228.5  688.76  5297.7  690.07  5490.7  690.16  5663.8  691.44
#Mann= 7 ,-1 , 0
  4303.9      .1       0  4429.4     .08       0  4527.9      .1       0
  4762.2     .12       0  4987.2     .07       0  5004.3     .12       0
  5040.8      .1       0
Bank Sta=4987.2,5004.3
XS Rating Curve= 0 ,0
Exp/Cntr=0.3,0.1

Type RM Length L Ch R = 1 ,10571   ,422,422,422
BEGIN DESCRIPTION:
Mapping XS 9dd72909
END DESCRIPTION:
XS GIS Cut Line= 3
      2013891.94     13620247.55      2013006.52     13620376.02
      2012541.25      13620528.8
#Sta/Elev= 30
  4401.6  695.82  4482.3  695.99  4600.6  693.67  4711.8  689.65    4762  688.85
  4767.1  686.24  4772.4  685.55  4812.8  682.59  4837.5  681.91  4902.4  680.03
  4934.1  681.41  4977.7  680.91  4984.6  678.74  4996.2  672.88  4998.4  672.08
  5013.3  672.88  5014.9  675.17    5025  679.78  5042.8  678.67  5061.7  679.06
  5105.8  682.94  5183.2  685.13    5217  688.23  5227.1  686.66  5277.6  688.27
  5311.4  688.04  5337.9  686.47  5433.4  686.37    5540  688.76    5786  691.24
#Mann= 6 ,-1 , 0
  4401.6     .05       0  4482.3      .1       0  4837.5     .12       0
  4996.2     .07       0  5013.3     .12       0  5061.7      .1       0
Bank Sta=4996.2,5013.3
XS Rating Curve= 0 ,0
Exp/Cntr=0.3,0.1

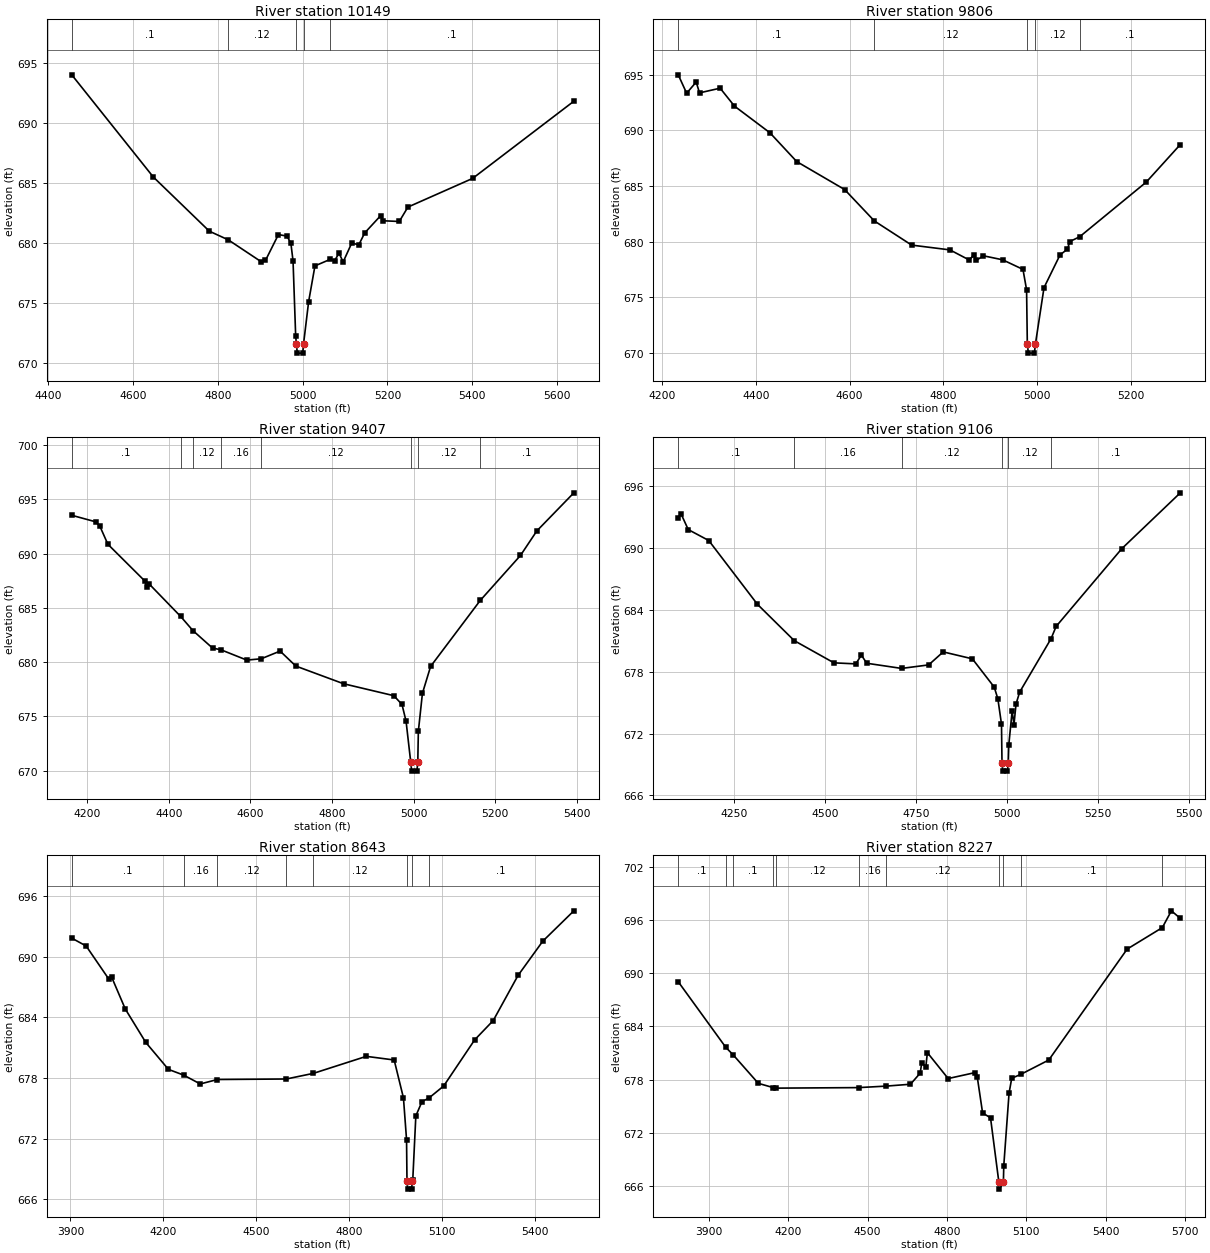
Type RM Length L Ch R = 1 ,10149   ,343,343,343
BEGIN DESCRIPTION:
Mapping XS 7df398d2
END DESCRIPTION:
XS GIS Cut Line= 2
      2013603.74     13619910.75      2012440.53     13620136.44
#Sta/Elev= 30
  4455.1     694  4647.4  685.49  4779.8  680.97  4824.4  680.25    4902  678.43
  4912.2  678.53  4942.8  680.69  4963.1  680.56  4972.2  679.96  4977.3   678.5
  4983.5  672.25  4985.1  671.61  4987.3  670.81  5000.1  670.81  5002.2  671.61
  5014.1   675.1    5029  678.08  5064.8  678.62  5075.2   678.5  5085.8  679.14
  5095.6  678.41  5115.9  679.99  5132.4  679.83  5146.5  680.83  5184.2  682.27
  5189.3  681.84    5228  681.78  5248.4  682.98  5401.2  685.37    5640   691.8
#Mann= 5 ,-1 , 0
  4455.1      .1       0  4824.4     .12       0  4985.1     .07       0
  5002.2     .12       0  5064.8      .1       0
Bank Sta=4985.1,5002.2
XS Rating Curve= 0 ,0
Exp/Cntr=0.3,0.1

Type RM Length L Ch R = 1 ,9806    ,399,399,399
BEGIN DESCRIPTION:
Mapping XS 9cb7cc8a
END DESCRIPTION:
XS GIS Cut Line= 2
      2013572.51     13619650.32      2012523.89     13619869.08
#Sta/Elev= 30
  4234.3  694.99  4252.2  693.34  4272.6  694.34  4279.7  693.37  4323.7  693.79
  4354.3  692.18  4429.8  689.79  4487.1   687.2  4589.3  684.69  4652.7  681.87
  4732.3   679.7    4814  679.27  4854.9  678.37  4864.7  678.78  4869.8  678.32
  4885.5  678.74  4926.4  678.38  4969.8  677.52  4977.5  675.69  4979.1   670.8
  4981.3     670  4994.1     670  4996.3   670.8  5014.7  675.88    5049  678.83
  5064.7  679.33  5069.8  680.02  5090.8  680.45  5232.9  685.36  5305.5  688.73
#Mann= 5 ,-1 , 0
  4234.3      .1       0  4652.7     .12       0  4979.1     .07       0
  4996.3     .12       0  5090.8      .1       0
Bank Sta=4979.1,4996.3
XS Rating Curve= 0 ,0
Exp/Cntr=0.3,0.1

Type RM Length L Ch R = 1 ,9407    ,301,301,301
BEGIN DESCRIPTION:
Mapping XS 6e1d4e09
END DESCRIPTION:
XS GIS Cut Line= 2
      2013513.47     13619438.52      2012284.34     13619514.91
#Sta/Elev= 30
  4161.7  693.52  4220.3  692.92  4230.3  692.54  4250.3  690.85  4340.5  687.48
  4346.1  686.87  4351.1  687.21  4428.8   684.2  4458.8   682.9  4506.9  681.29
  4527.6  681.13    4591  680.18  4626.3   680.3  4672.7  681.01  4711.2  679.63
  4828.4     678  4951.7   676.9  4971.7  676.09  4981.7  674.54  4993.2  670.75
  4995.4  669.95  5008.2  669.95  5010.4  670.75  5011.8  673.62  5021.8  677.12
  5041.9   679.6  5163.7  685.68  5262.3  689.82  5302.4  692.08  5393.2  695.59
#Mann= 8 ,-1 , 0
  4161.7      .1       0  4428.8     .16       0  4458.8     .12       0
  4527.6     .16       0  4626.3     .12       0  4993.2     .07       0
  5010.4     .12       0  5163.7      .1       0
Bank Sta=4993.2,5010.4
XS Rating Curve= 0 ,0
Exp/Cntr=0.3,0.1

Type RM Length L Ch R = 1 ,9106    ,463,463,463
BEGIN DESCRIPTION:
Mapping XS 59b401ea
END DESCRIPTION:
XS GIS Cut Line= 2
      2013572.47     13619244.08      2012194.04     13619178.11
#Sta/Elev= 30
  4097.3   692.9  4104.8   693.3  4124.8  691.76  4181.2   690.7    4315  684.52
  4416.2     681  4525.3  678.85  4585.3  678.75  4600.7   679.6  4615.4  678.81
  4711.2  678.31  4785.6  678.65  4825.6  679.91  4905.7  679.24  4965.8   676.5
  4975.8  675.37  4985.8  672.91  4987.2  669.16  4989.4  668.36  5002.2  668.36
  5004.4  669.16  5005.8  670.89  5015.1  674.19  5020.1  672.87  5025.8  674.87
  5035.8  676.02    5122  681.19    5136  682.38  5316.2   689.9  5477.3  695.32
#Mann= 6 ,-1 , 0
  4097.3      .1       0  4416.2     .16       0  4711.2     .12       0
  4987.2     .07       0  5004.4     .12       0    5122      .1       0
Bank Sta=4987.2,5004.4
XS Rating Curve= 0 ,0
Exp/Cntr=0.3,0.1

Type RM Length L Ch R = 1 ,8643    ,416,416,416
BEGIN DESCRIPTION:
Mapping XS f7ffdb45
END DESCRIPTION:
XS GIS Cut Line= 3
      2013581.17     13619141.65      2012930.13      13618797.9
      2012044.68     13618813.52
#Sta/Elev= 30
  3904.4  691.84  3950.9  691.06  4024.5  687.77  4033.3  687.98  4077.3  684.83
  4143.4  681.53  4216.7  678.86  4265.4   678.3  4319.5  677.42  4374.8  677.86
  4597.4  677.91  4685.2  678.47  4855.8  680.15  4945.8  679.79  4975.8  676.04
  4985.8  671.91  4987.2  667.82  4989.4  667.02  5002.2  667.02  5004.4  667.82
  5005.8  667.88  5015.8  674.26  5035.8  675.68  5056.9     676  5105.8  677.22
  5205.8  681.78  5265.8  683.69  5345.9  688.15  5425.9  691.54  5526.2  694.54
#Mann= 8 ,-1 , 0
  3904.4      .1       0  4265.4     .16       0  4374.8     .12       0
  4597.4     .16       0  4685.2     .12       0  4987.2     .07       0
  5004.4     .12       0  5056.9      .1       0
Bank Sta=4987.2,5004.4
XS Rating Curve= 0 ,0
Exp/Cntr=0.3,0.1

Type RM Length L Ch R = 1 ,8227    ,858,858,858
BEGIN DESCRIPTION:
Mapping XS 0a9fb0e0
END DESCRIPTION:
XS GIS Cut Line= 4
       2013572.2     13618963.36       2012763.2     13618463.38
      2012183.34     13618463.38      2011832.61     13618564.08
#Sta/Elev= 30
  3785.3  689.04  3964.8  681.65  3992.7   680.8  4087.7  677.59  4142.8  677.12
  4155.9  677.05  4466.7  677.11  4571.4  677.28  4662.2  677.49  4698.9  678.74
  4704.8  679.91  4720.2  679.44    4726  681.05  4804.5  678.13  4904.5  678.79
  4914.5  678.29  4934.5  674.26  4964.5   673.7  4995.9  666.47  4998.1  665.67
  5013.1  666.47  5014.5  668.31  5034.5   676.5  5044.5  678.16  5079.9  678.62
  5184.5  680.22  5480.4  692.72  5613.2  695.14  5647.4  697.03  5681.1  696.18
#Mann= 11 ,-1 , 0
  3785.3      .1       0  3964.8     .12       0  3992.7      .1       0
  4142.8     .16       0  4155.9     .12       0  4466.7     .16       0
  4571.4     .12       0  4995.9     .07       0  5013.1     .12       0
  5079.9      .1       0  5613.2     .05       0
Bank Sta=4995.9,5013.1
XS Rating Curve= 0 ,0
Exp/Cntr=0.3,0.1

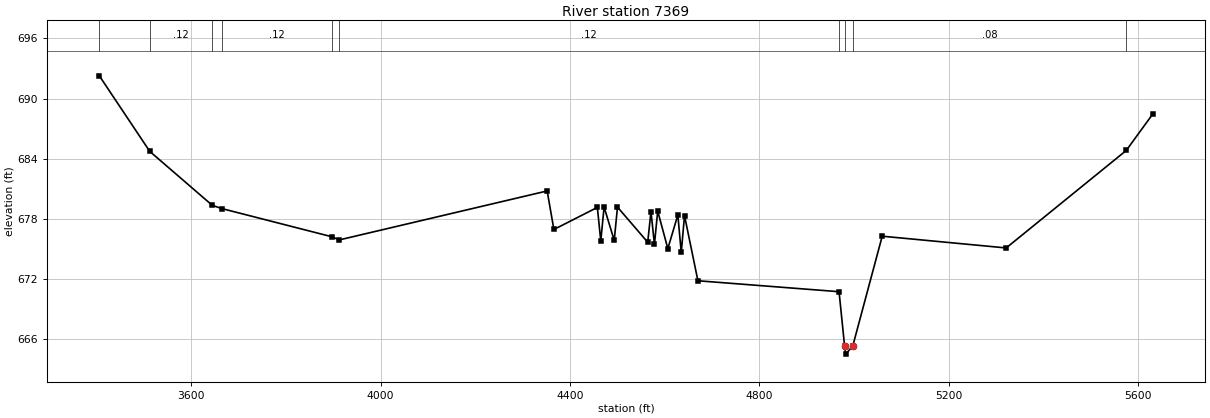
Type RM Length L Ch R = 1 ,7369    ,126,126,126
BEGIN DESCRIPTION:
Mapping XS c1f8c317
END DESCRIPTION:
XS GIS Cut Line= 3
      2013544.48     13618852.29      2012287.51     13617654.35
      2011870.84     13617907.83
#Sta/Elev= 30
  3406.3  692.26  3512.8  684.73  3644.9  679.35    3666  679.02  3896.8  676.23
  3912.9  675.91  4351.8  680.79    4366  676.95  4457.8  679.15    4465   675.8
    4472  679.19  4493.4  675.86  4500.3  679.18  4564.1  675.68    4571  678.74
  4578.3  675.46  4585.2  678.79  4606.6  675.04  4627.7   678.4  4634.9  674.66
  4641.8  678.33  4670.1  671.84  4968.1  670.75  4979.8  665.33    4982  664.53
    4997  665.33  5059.2  676.28    5321  675.11  5574.4  684.82  5630.4  688.45
#Mann= 10 ,-1 , 0
  3406.3      .1       0  3512.8     .12       0  3644.9      .1       0
    3666     .12       0  3896.8     .16       0  3912.9     .12       0
  4968.1     .08       0  4979.8     .07       0    4997     .08       0
  5574.4     .08       0
Bank Sta=4979.8,4997
XS Rating Curve= 0 ,0
Exp/Cntr=0.3,0.1