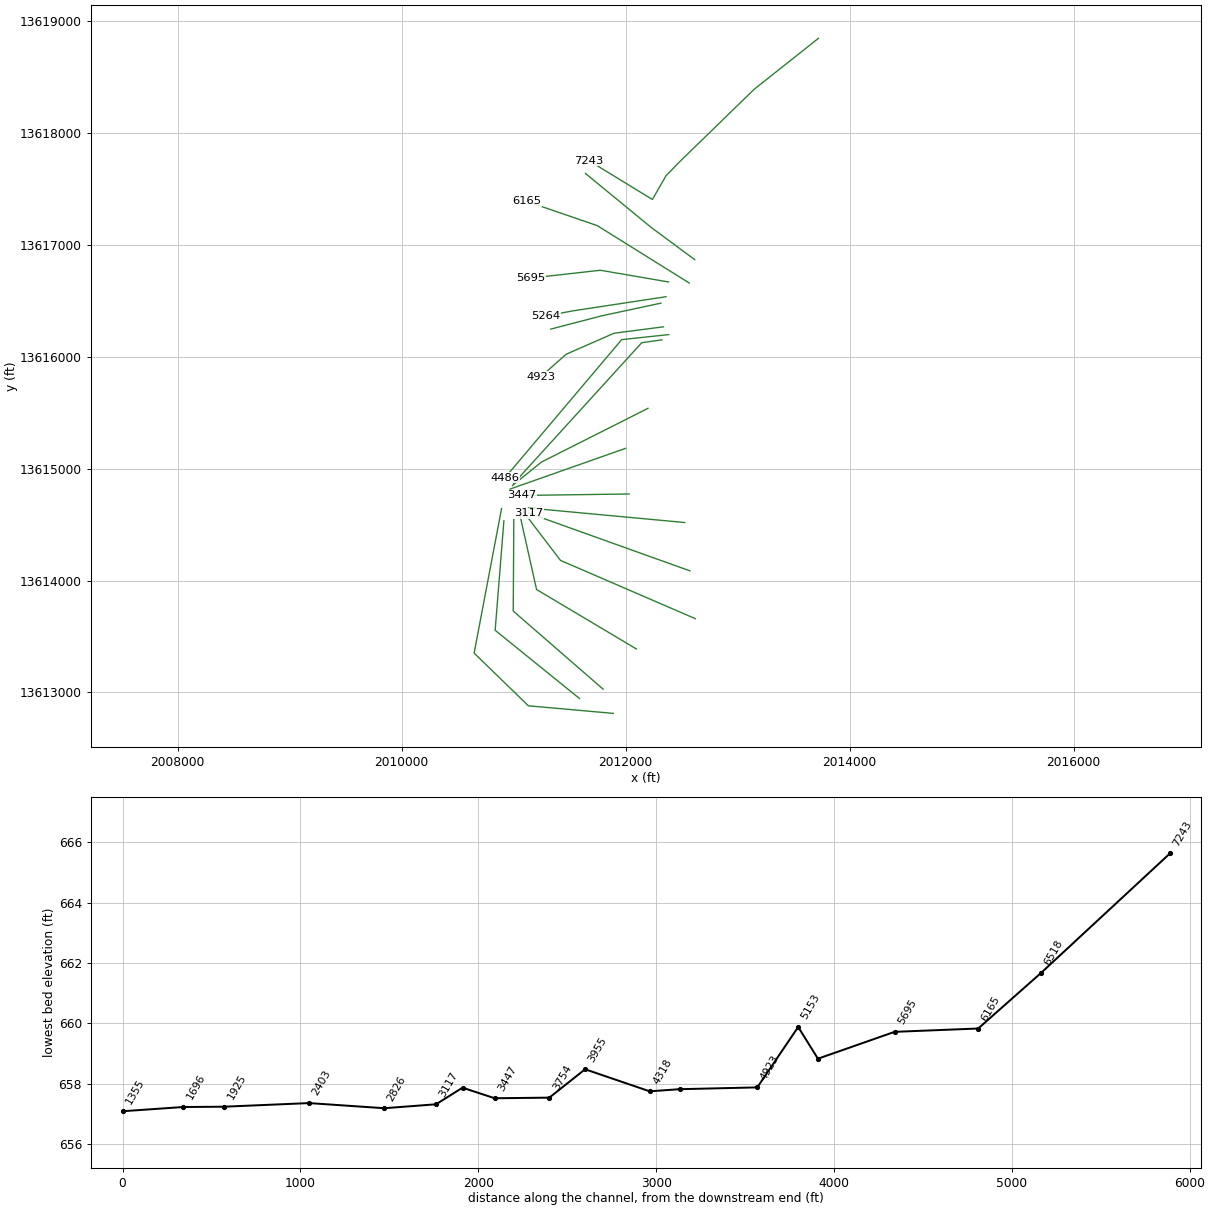
HEC-RAS study FORT EWELL CREEK.prj: FORT EWELL CREEK Base Level Engineering

--- FORT EWELL CREEK.g01 (geometry) --- (continued)

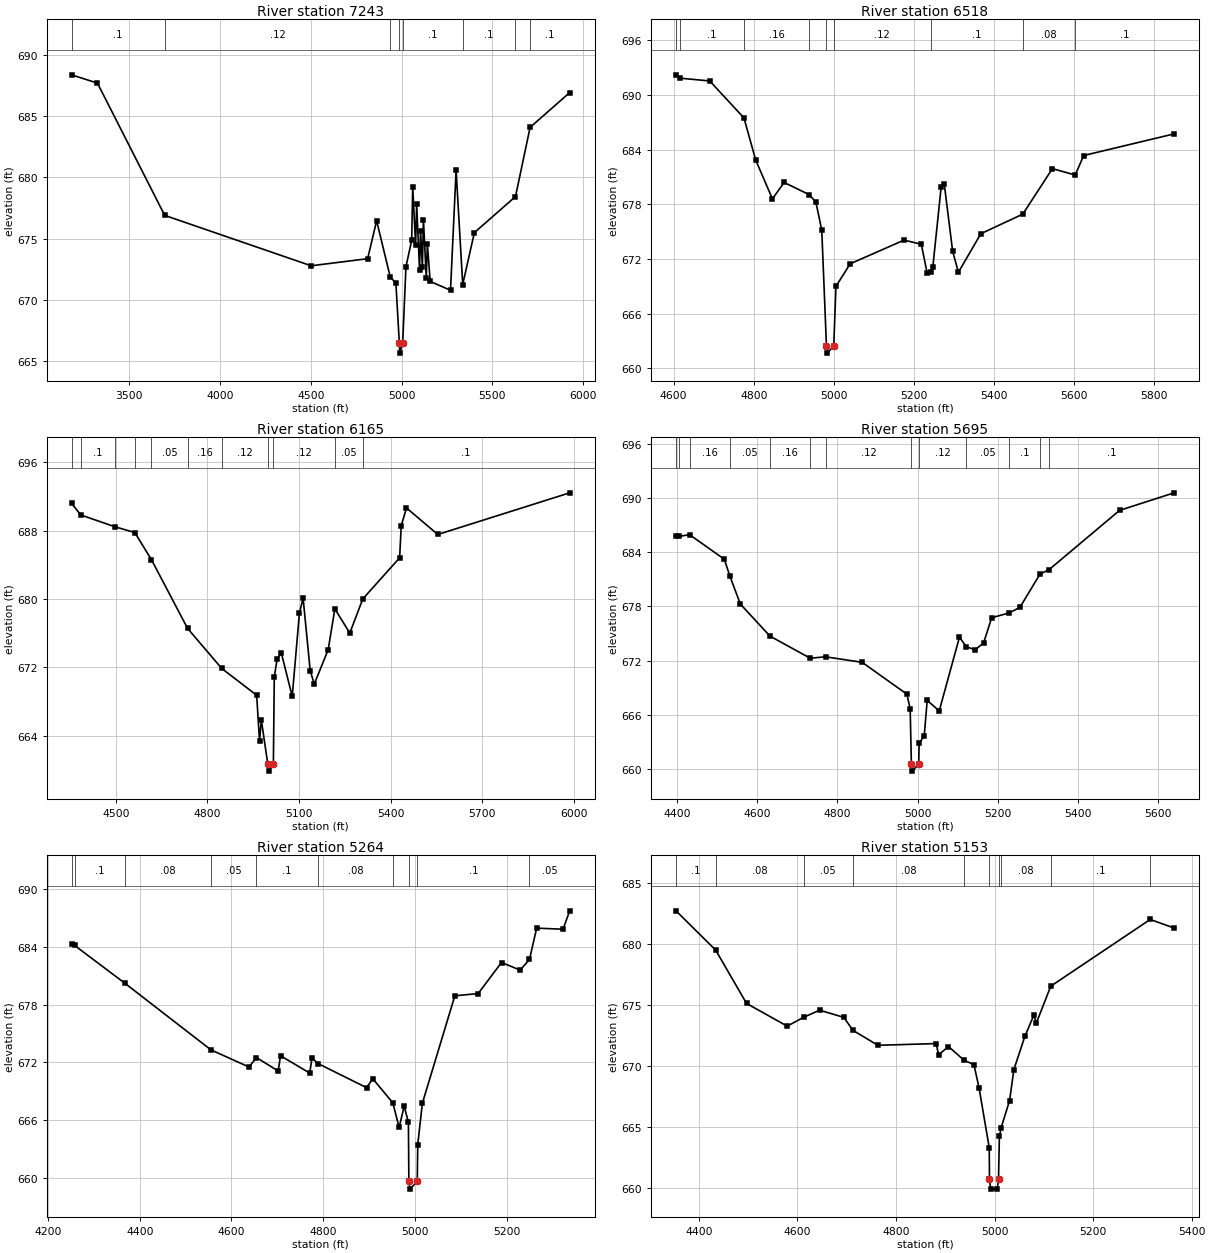
Type RM Length L Ch R = 1 ,7243    ,725,725,725
BEGIN DESCRIPTION:
Mapping XS fcbd288e
END DESCRIPTION:
XS GIS Cut Line= 6
      2013721.54     13618848.79      2013148.62     13618393.93
       2012488.9     13617751.57      2012360.42     13617619.63
       2012238.9     13617407.82       2011672.9     13617755.06
#Sta/Elev= 30
  3181.4  688.38    3324   687.7  3694.6  676.89  4501.7  672.77  4812.8  673.35
  4862.3  676.45  4936.9  671.88  4968.5  671.33  4987.5  666.43    4990  665.63
  5005.7  666.43  5023.9  672.69  5055.5  674.86  5061.2  679.24  5077.1  674.43
  5082.8  677.86  5098.6  672.46  5104.4  675.63  5114.4  672.64  5120.2  676.55
    5136  671.75  5141.8  674.55  5157.6  671.49  5269.4  670.77  5300.2  680.58
  5336.7  671.24  5400.8  675.48  5627.5  678.43  5707.8  684.08  5926.1  686.93
#Mann= 8 ,-1 , 0
  3181.4      .1       0  3694.6     .12       0  4936.9      .1       0
  4987.5     .07       0  5005.7      .1       0  5336.7      .1       0
  5627.5     .08       0  5707.8      .1       0
Bank Sta=4987.5,5005.7
XS Rating Curve= 0 ,0
Exp/Cntr=0.3,0.1

Type RM Length L Ch R = 1 ,6518    ,353,353,353
BEGIN DESCRIPTION:
FORT EWELL CREEK 4.0
END DESCRIPTION:
XS GIS Cut Line= 3
      2012617.33     13616869.65      2012228.48     13617157.82
      2011641.97     13617640.22
#Sta/Elev= 30
  4605.8   692.2  4616.7  691.83    4690  691.53  4775.5  687.47  4804.8  682.85
  4846.5  678.59  4875.7  680.39  4938.2  679.06    4955  678.24  4969.7  675.16
  4981.4  662.47  4983.9  661.67  4999.6  662.47  5005.1  668.99  5040.6  671.47
  5175.2  674.07  5218.2  673.61  5232.6  670.49  5242.3  670.62  5246.9   671.1
  5267.7  679.88  5275.6  680.17  5296.4  672.85  5310.8  670.54  5366.8  674.77
  5471.6  676.92  5545.4  681.91  5602.3  681.21  5623.6  683.35  5849.2  685.72
#Mann= 9 ,-1 , 0
  4605.8     .15       0  4616.7      .1       0  4775.5     .16       0
  4938.2     .12       0  4981.4     .07       0  4999.6     .12       0
  5242.3      .1       0  5471.6     .08       0  5602.3      .1       0
Bank Sta=4981.4,4999.6
XS Rating Curve= 0 ,0
Exp/Cntr=0.3,0.1

Type RM Length L Ch R = 1 ,6165    ,470,470,470
BEGIN DESCRIPTION:
Mapping XS 045636e3
END DESCRIPTION:
XS GIS Cut Line= 3
      2012567.81     13616661.15      2011746.66      13617174.2
      2011119.55     13617389.83
#Sta/Elev= 30
    4355   691.2    4385  689.84  4498.2  688.44  4562.1  687.78  4616.6   684.6
  4734.9  676.55  4846.7  671.86  4961.2  668.72  4970.6  663.36  4976.5  665.82
  4997.7  660.63  5000.2  659.83  5015.9  660.63  5018.9  670.84  5028.4  673.01
  5042.2  673.65  5077.6  668.58  5101.2  678.32  5113.3   680.1  5136.5  671.61
  5149.9  670.03  5195.5  674.07  5217.3  678.84  5266.2     676  5308.8     680
  5429.4  684.82  5434.7  688.58  5451.9  690.66  5554.4  687.55  5986.4  692.43
#Mann= 11 ,-1 , 0
    4355     .15       0    4385      .1       0  4498.2     .08       0
  4562.1     .16       0  4616.6     .05       0  4734.9     .16       0
  4846.7     .12       0  4997.7     .07       0  5015.9     .12       0
  5217.3     .05       0  5308.8      .1       0
Bank Sta=4997.7,5015.9
XS Rating Curve= 0 ,0
Exp/Cntr=0.3,0.1

Type RM Length L Ch R = 1 ,5695    ,431,431,431
BEGIN DESCRIPTION:
FORT EWELL CREEK 3.0
END DESCRIPTION:
XS GIS Cut Line= 3
      2012383.34     13616670.32        2011775.       13616775.
       2011152.4     13616705.04
#Sta/Elev= 30
  4396.8  685.82  4405.4  685.79  4430.8  685.97  4517.4  683.25  4531.2   681.4
  4557.5  678.27  4631.5  674.71  4731.9  672.26  4770.6  672.41  4861.7   671.8
  4973.5  668.26  4981.6   666.6  4984.6  660.52  4987.1  659.72  5002.9  660.52
  5003.9  662.81  5016.6  663.62  5024.1  667.58  5054.1   666.4  5104.6  674.59
  5121.6  673.54  5144.1  673.19    5165  673.97  5185.1  676.75  5228.5  677.28
  5255.6   677.9  5305.8   681.6  5328.7   682.1  5504.4  688.67  5640.6  690.62
#Mann= 13 ,-1 , 0
  4396.8      .1       0  4405.4     .08       0  4430.8     .16       0
  4531.2     .05       0  4631.5     .16       0  4731.9      .1       0
  4770.6     .12       0  4984.6     .07       0  5002.9     .12       0
  5121.6     .05       0  5228.5      .1       0  5305.8     .05       0
  5328.7      .1       0
Bank Sta=4984.6,5002.9
XS Rating Curve= 0 ,0
Exp/Cntr=0.3,0.1

Type RM Length L Ch R = 1 ,5264    ,111,111,111
BEGIN DESCRIPTION:
Mapping XS 8e7603c8
END DESCRIPTION:
XS GIS Cut Line= 3
      2012360.79     13616538.38      2011527.44     13616411.64
      2011288.97     13616366.71
#Sta/Elev= 30
  4251.5  684.31  4258.2  684.15    4367  680.25  4555.3   673.3  4638.2  671.52
  4654.4   672.5  4701.8  671.11  4706.9  672.69  4770.5  670.89  4775.5  672.46
  4788.5  671.88  4894.6  669.37  4907.8  670.31  4951.6   667.8  4965.4  665.24
  4976.5  667.46  4985.6  665.76  4986.6  659.63  4989.1  658.83  5004.9  659.63
  5005.9  663.42    5016  667.75  5086.8  678.92  5137.6  679.15  5188.5  682.38
  5229.2  681.59  5249.5   682.7  5265.1  685.95  5322.6  685.84  5337.1  687.75
#Mann= 10 ,-1 , 0
  4251.5     .15       0  4258.2      .1       0    4367     .08       0
  4555.3     .05       0  4654.4      .1       0  4788.5     .08       0
  4951.6      .1       0  4986.6     .07       0  5004.9      .1       0
  5249.5     .05       0
Bank Sta=4986.6,5004.9
XS Rating Curve= 0 ,0
Exp/Cntr=0.3,0.1

Type RM Length L Ch R = 1 ,5153    ,230,230,230
BEGIN DESCRIPTION:
FORT EWELL CREEK 2.0
END DESCRIPTION:
XS GIS Cut Line= 3
      2012315.62     13616481.09      2011782.65      13616366.5
      2011331.97     13616248.62
#Sta/Elev= 30
  4353.4  682.71  4433.9  679.49  4496.7  675.11  4579.1  673.25  4612.3  673.97
  4644.8  674.56  4694.2  673.97  4712.3  672.91  4763.2  671.68  4881.4  671.82
  4886.5   670.9  4906.5  671.58  4938.4  670.44  4958.1   670.1  4968.7  668.15
  4989.2  663.28  4989.7  660.68  4992.2  659.88  5005.5  659.88    5008  660.68
  5009.8   664.2  5013.2   664.9  5030.5  667.15  5039.2  669.69  5061.5  672.41
  5079.7  674.15  5084.8   673.5  5114.1  676.53  5315.9     682  5364.4   681.3
#Mann= 10 ,-1 , 0
  4353.4      .1       0  4433.9     .08       0  4612.3     .05       0
  4712.3     .08       0  4938.4      .1       0  4989.7     .07       0
    5008      .1       0  5013.2     .08       0  5114.1      .1       0
  5315.9     .05       0
Bank Sta=4989.7,5008
XS Rating Curve= 0 ,0
Exp/Cntr=0.3,0.1

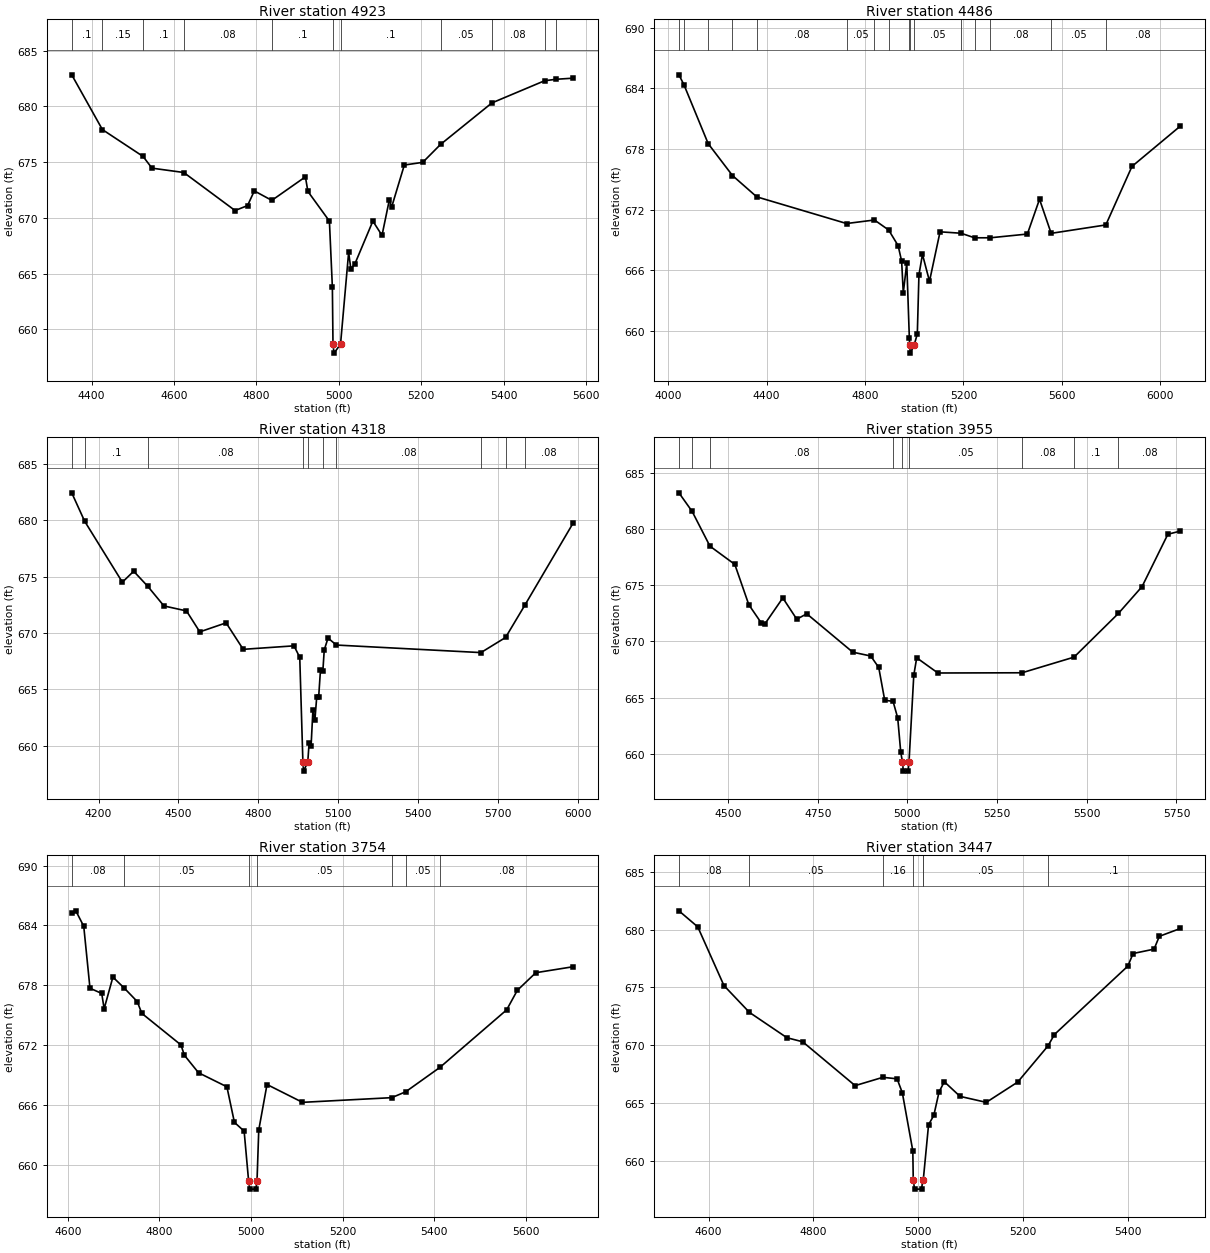
Type RM Length L Ch R = 1 ,4923    ,437,437,437
BEGIN DESCRIPTION:
Mapping XS c0bd9966
END DESCRIPTION:
XS GIS Cut Line= 4
      2012338.22     13616269.28      2011897.23     13616211.99
      2011470.15     13616024.49      2011240.94     13615821.33
#Sta/Elev= 30
  4351.7  682.84  4426.1  677.93  4524.9  675.52  4546.5  674.47  4623.7  674.08
  4748.2  670.67  4778.5  671.11    4795  672.43  4837.5  671.58    4919  673.69
  4925.1  672.38  4977.3  669.72  4984.5  663.79    4986  658.68  4988.5  657.88
  5004.3  658.68    5024  666.92  5029.4  665.43  5039.1  665.88  5082.8  669.72
    5105  668.44  5122.9  671.64  5128.3  670.97  5159.2  674.75  5203.9  674.99
  5247.2   676.6  5371.8  680.32  5499.8  682.31  5527.4  682.44  5569.1  682.54
#Mann= 11 ,-1 , 0
  4351.7      .1       0  4426.1     .15       0  4524.9      .1       0
  4623.7     .08       0  4837.5      .1       0    4986     .07       0
  5004.3      .1       0  5247.2     .05       0  5371.8     .08       0
  5499.8      .1       0  5527.4     .15       0
Bank Sta=4986,5004.3
XS Rating Curve= 0 ,0
Exp/Cntr=0.3,0.1

Type RM Length L Ch R = 1 ,4486    ,168,168,168
BEGIN DESCRIPTION:
Mapping XS 1411dfea
END DESCRIPTION:
XS GIS Cut Line= 3
      2012385.06     13616199.83      2011964.94      13616154.7
      2010923.12     13614919.93
#Sta/Elev= 30
  4043.8  685.35  4064.2  684.37  4162.8  678.54  4261.4  675.39  4360.1  673.28
  4725.2  670.64  4838.5  670.99  4896.3     670  4934.8  668.45  4949.1  666.91
  4955.7  663.77  4969.9  666.72  4980.4  659.31  4981.6  658.62  4984.1  657.82
  4999.9  658.62  5012.8  659.72  5019.4  665.57  5033.7  667.59  5062.3  664.93
  5105.2  669.82  5190.5  669.68  5245.3  669.23  5309.7  669.23  5460.1   669.6
  5509.5  673.04  5556.8  669.67    5779   670.5  5885.3  676.29  6081.9  680.28
#Mann= 16 ,-1 , 0
  4043.8     .08       0  4064.2      .1       0  4162.8     .15       0
  4261.4      .1       0  4360.1     .08       0  4725.2     .05       0
  4838.5     .08       0  4896.3      .1       0  4980.4     .05       0
  4981.6     .04       0  4999.9     .05       0  5190.5     .08       0
  5245.3     .05       0  5309.7     .08       0  5556.8     .05       0
    5779     .08       0
Bank Sta=4981.6,4999.9
XS Rating Curve= 0 ,0
Exp/Cntr=0.3,0.1

Type RM Length L Ch R = 1 ,4318    ,363,363,363
BEGIN DESCRIPTION:
Mapping XS 99a2b195
END DESCRIPTION:
XS GIS Cut Line= 3
      2012324.27     13616152.96      2012143.76     13616126.92
      2011001.15      13614869.9
#Sta/Elev= 30
  4099.6  682.45    4148  679.93  4289.5  674.52    4332  675.49  4385.3  674.14
  4445.5  672.41    4530  671.97    4580  670.11  4678.7  670.91  4742.9  668.56
  4933.4  668.87    4955  667.85  4966.8  658.55  4969.3  657.75  4985.1  658.55
  4990.2  660.29  4997.6  660.02  5004.4  663.18  5011.8  662.29  5018.6  664.31
    5026  664.34  5032.8  666.75  5041.8  666.68  5046.9  668.51  5061.1  669.56
  5092.4  668.94  5634.7  668.27    5727  669.61  5799.5  672.48  5980.7  679.77
#Mann= 10 ,-1 , 0
  4099.6     .08       0    4148      .1       0  4385.3     .08       0
  4966.8     .07       0  4985.1     .08       0  5041.8      .1       0
  5092.4     .08       0  5634.7     .05       0    5727      .1       0
  5799.5     .08       0
Bank Sta=4966.8,4985.1
XS Rating Curve= 0 ,0
Exp/Cntr=0.3,0.1

Type RM Length L Ch R = 1 ,3955    ,201,201,201
BEGIN DESCRIPTION:
Mapping XS 536b9bc6
END DESCRIPTION:
XS GIS Cut Line= 3
      2012199.34     13615540.13      2011248.13     13615059.48
      2010990.24     13614850.31
#Sta/Elev= 30
    4363  683.21  4399.8  681.56  4449.5  678.47  4518.8  676.85  4557.8  673.27
  4591.9  671.68  4602.4  671.55  4652.6  673.87  4691.5  671.98  4719.4  672.46
  4847.6  669.05  4897.7  668.71    4920  667.69  4936.7  664.78  4959.9  664.68
  4972.9  663.21  4981.3  660.19  4986.1  659.28  4988.6  658.48  5001.9  658.48
  5004.4  659.28  5017.7     667  5025.9  668.55  5084.9   667.2  5319.5  667.22
  5464.5  668.61    5588  672.49  5654.1  674.88    5726  679.53  5760.8  679.81
#Mann= 9 ,-1 , 0
    4363     .08       0  4399.8      .1       0  4449.5     .08       0
  4959.9     .05       0  4986.1     .04       0  5004.4     .05       0
  5319.5     .08       0  5464.5      .1       0    5588     .08       0
Bank Sta=4986.1,5004.4
XS Rating Curve= 0 ,0
Exp/Cntr=0.3,0.1

Type RM Length L Ch R = 1 ,3754    ,307,307,307
BEGIN DESCRIPTION:
Mapping XS 89313baa
END DESCRIPTION:
XS GIS Cut Line= 2
       2011999.7     13615182.49      2010968.16     13614818.41
#Sta/Elev= 30
  4608.8  685.24  4617.7  685.47    4635  683.92  4648.6   677.7  4674.2  677.18
  4679.5  675.64  4698.6  678.82  4723.1  677.73  4751.6  676.37  4761.7  675.18
  4847.1  672.01  4854.5  670.98  4885.4  669.22  4947.3  667.81  4963.7  664.24
  4984.9  663.36  4994.7  658.34  4997.2  657.54  5010.5  657.54    5013  658.34
  5016.8  663.47  5034.8  668.04  5112.2  666.25  5306.9  666.72  5337.4  667.31
  5412.1  669.76  5557.6  675.53  5580.9  677.49  5621.2  679.26  5702.7  679.86
#Mann= 7 ,-1 , 0
  4608.8     .08       0  4723.1     .05       0  4994.7     .04       0
    5013     .05       0  5306.9     .08       0  5337.4     .05       0
  5412.1     .08       0
Bank Sta=4994.7,5013
XS Rating Curve= 0 ,0
Exp/Cntr=0.3,0.1

Type RM Length L Ch R = 1 ,3447    ,181,181,181
BEGIN DESCRIPTION:
Mapping XS c46afc8e
END DESCRIPTION:
XS GIS Cut Line= 2
      2012030.94     13614774.49      2011074.93     13614761.36
#Sta/Elev= 30
  4543.5  681.64  4579.4  680.25  4629.4  675.16  4677.9  672.84  4749.5  670.64
  4779.5  670.29  4879.5  666.49  4932.4  667.21  4959.5  667.08  4969.5  665.87
  4989.5  660.83  4990.3  658.32  4992.8  657.52  5006.1  657.52  5008.6  658.32
  5009.5  658.35  5019.5   663.1  5029.5  663.91  5039.5  665.94  5049.5  666.83
  5079.5  665.56  5129.5  665.04  5189.5   666.8  5247.2  669.93  5259.5  670.92
  5399.5  676.85  5409.5  677.94  5449.5  678.32  5459.5  679.43  5499.6  680.11
#Mann= 7 ,-1 , 0
  4543.5     .08       0  4677.9     .05       0  4932.4     .16       0
  4990.3     .07       0  5008.6     .16       0  5009.5     .05       0
  5247.2      .1       0
Bank Sta=4990.3,5008.6
XS Rating Curve= 0 ,0
Exp/Cntr=0.3,0.1

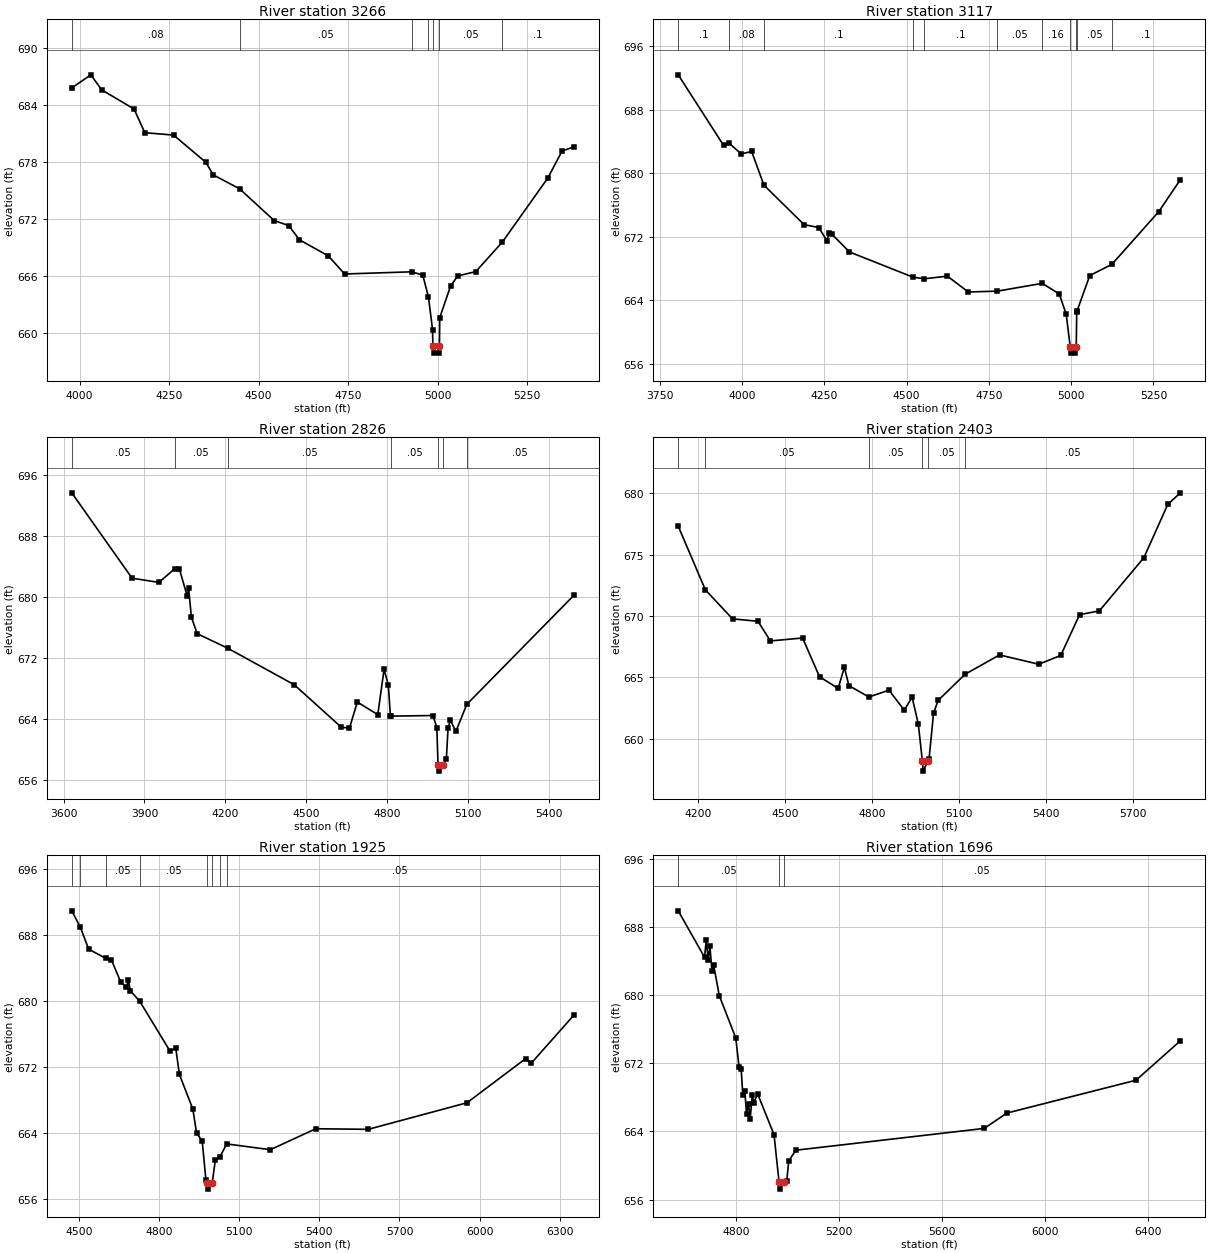
Type RM Length L Ch R = 1 ,3266    ,149,149,149
BEGIN DESCRIPTION:
Mapping XS 9a2f7882
END DESCRIPTION:
XS GIS Cut Line= 2
      2012528.08     13614519.17      2011132.24     13614649.38
#Sta/Elev= 30
  3978.3  685.82  4031.6   687.2  4061.7  685.62  4152.1   683.6  4182.3   681.1
  4262.6  680.85    4353  677.97  4373.1  676.66  4446.8  675.19  4543.8  671.83
    4584  671.32  4614.1  669.81  4694.5  668.12  4740.3  666.21  4927.7  666.44
  4958.4  666.09  4974.2  663.79  4985.7  660.33  4986.6  658.67  4989.1  657.87
  5002.4  657.87  5004.9  658.67  5005.8  661.61    5036  664.94    5056  666.01
  5106.3  666.46  5180.1  669.55  5307.1   676.3  5347.3  679.16  5380.2  679.61
#Mann= 7 ,-1 , 0
  3978.3     .08       0  4446.8     .05       0  4927.7     .16       0
  4974.2     .05       0  4986.6     .04       0  5004.9     .05       0
  5180.1      .1       0
Bank Sta=4986.6,5004.9
XS Rating Curve= 0 ,0
Exp/Cntr=0.3,0.1

Type RM Length L Ch R = 1 ,3117    ,291,291,291
BEGIN DESCRIPTION:
Mapping XS af490740
END DESCRIPTION:
XS GIS Cut Line= 2
      2012574.87      13614086.9      2011138.67     13614602.06
#Sta/Elev= 30
  3805.8  692.42  3943.8  683.51  3960.6  683.79  3997.5  682.44  4028.8  682.76
  4066.3   678.5  4188.1  673.53  4232.8  673.16  4258.2  671.47  4263.5  672.44
  4273.1  672.31  4326.2  670.08  4519.2   666.9  4554.1   666.7  4623.7  667.03
  4687.4  665.03  4775.9  665.14    4912  666.12  4963.7  664.78  4984.9  662.22
    4997  658.12  4999.5  657.32  5012.8  657.32  5015.3  658.12  5016.8  662.47
  5017.7  662.63  5056.5  667.11  5123.5  668.51  5266.4  675.18  5331.6  679.19
#Mann= 11 ,-1 , 0
  3805.8      .1       0  3960.6     .08       0  4066.3      .1       0
  4519.2     .05       0  4554.1      .1       0  4775.9     .05       0
    4912     .16       0    4997     .07       0  5015.3     .16       0
  5017.7     .05       0  5123.5      .1       0
Bank Sta=4997,5015.3
XS Rating Curve= 0 ,0
Exp/Cntr=0.3,0.1

Type RM Length L Ch R = 1 ,2826    ,423,423,423
BEGIN DESCRIPTION:
Mapping XS 89b3a152
END DESCRIPTION:
XS GIS Cut Line= 3
      2012621.82     13613659.79      2011418.66     13614180.64
      2011085.31     13614618.15
#Sta/Elev= 30
  3630.6  693.67  3854.1  682.48  3953.5  681.93  4011.8   683.7  4029.4  683.71
  4058.3  680.15  4063.8  681.19  4073.9  677.39  4095.7   675.2  4208.4  673.31
  4455.3  668.51  4629.6  662.95    4660  662.82    4689  666.25  4764.9  664.59
  4788.3  670.55    4804  668.47  4811.8  664.36  4815.7   664.4  4969.2  664.48
  4983.8   662.9  4988.3  657.99  4990.8  657.19  5006.6  657.99  5019.1  658.76
  5025.4  662.81  5033.7  663.87  5054.5   662.4  5094.8  665.94  5491.7  680.23
#Mann= 7 ,-1 , 0
  3630.6     .05       0  4011.8     .05       0  4208.4     .05       0
  4815.7     .05       0  4988.3     .03       0  5006.6     .05       0
  5094.8     .05       0
Bank Sta=4988.3,5006.6
XS Rating Curve= 0 ,0
Exp/Cntr=0.3,0.1

Type RM Length L Ch R = 1 ,2403    ,478,478,478
BEGIN DESCRIPTION:
Mapping XS dbe32f2a
END DESCRIPTION:
XS GIS Cut Line= 3
      2012095.74     13613388.97      2011205.12     13613920.22
      2011054.07     13614597.35
#Sta/Elev= 30
  4132.6  677.32  4226.2  672.13  4319.8  669.77  4407.5  669.57  4450.3  667.97
  4561.3  668.21  4619.7  665.05  4683.9   664.1  4705.3  665.82  4720.9  664.33
  4789.9   663.4    4859  663.96  4911.6  662.33  4938.8  663.38  4960.2   661.2
  4974.3  658.16  4976.8  657.36  4992.6  658.16  4997.2  658.34  5012.8  662.08
  5028.4  663.12  5121.1  665.25  5240.1  666.83  5375.6  666.07  5451.2  666.79
  5516.2  670.11  5584.4  670.42    5738  674.76    5820  679.09  5863.4  680.04
#Mann= 6 ,-1 , 0
  4132.6     .05       0  4226.2     .05       0  4789.9     .05       0
  4974.3     .03       0  4992.6     .05       0  5121.1     .05       0
Bank Sta=4974.3,4992.6
XS Rating Curve= 0 ,0
Exp/Cntr=0.3,0.1

Type RM Length L Ch R = 1 ,1925    ,229,229,229
BEGIN DESCRIPTION:
Mapping XS 5b87ccae
END DESCRIPTION:
XS GIS Cut Line= 3
      2011798.89     13613029.57      2010996.78     13613727.51
      2011001.99     13614545.25
#Sta/Elev= 30
  4472.3  690.98  4504.7  688.97  4535.5  686.34  4598.9  685.23    4621  685.03
  4656.1  682.31    4677  681.72  4684.6   682.6  4691.2  681.31  4726.8  680.02
  4840.3  673.98  4861.9  674.35  4875.4  671.16  4925.8  666.95    4940  664.02
  4960.9  663.09  4975.1   658.3  4980.2  658.04  4982.7  657.24  4998.6  658.04
  5010.2  660.78  5027.6  661.15  5052.4  662.72  5216.3  662.02  5386.2  664.56
    5583  664.49    5953  667.71  6173.1  673.07  6193.1  672.48  6353.3  678.33
#Mann= 8 ,-1 , 0
  4472.3     .05       0  4504.7     .05       0  4598.9     .05       0
  4726.8     .05       0  4980.2     .03       0  4998.6     .05       0
  5027.6     .05       0  5052.4     .05       0
Bank Sta=4980.2,4998.6
XS Rating Curve= 0 ,0
Exp/Cntr=0.3,0.1

Type RM Length L Ch R = 1 ,1696    ,341,341,341
BEGIN DESCRIPTION:
Mapping XS 9f095d57
END DESCRIPTION:
XS GIS Cut Line= 3
      2011588.94     13612945.05      2010835.33     13613555.64
      2010913.45     13614534.81
#Sta/Elev= 30
  4575.1  689.91  4677.5  684.45  4683.9  686.46  4691.9  684.13  4698.3  685.76
  4706.2  682.86  4712.7  683.56  4734.6  679.96  4798.9  674.97  4811.8  671.54
  4819.8  671.35  4826.2  668.24  4834.1  668.74  4840.6  666.08  4848.5  667.26
  4854.9  665.47  4862.9  668.25  4869.3  667.39  4883.7  668.43  4947.6  663.62
  4967.2  658.03  4969.7  657.23  4985.6  658.03  4997.2  658.24  5004.9  660.56
  5032.4   661.8  5765.1  664.36  5852.8  666.16  6355.1  670.02  6527.3  674.64
#Mann= 3 ,-1 , 0
  4575.1     .05       0  4967.2     .03       0  4985.6     .05       0
Bank Sta=4967.2,4985.6
XS Rating Curve= 0 ,0
Exp/Cntr=0.3,0.1

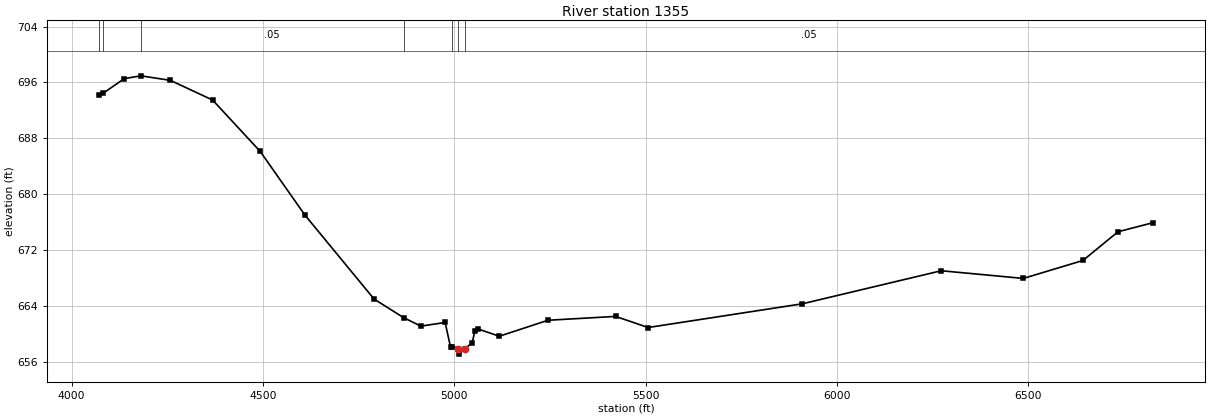
Type RM Length L Ch R = 1 ,1355    ,0,0,0
BEGIN DESCRIPTION:
FORT EWELL CREEK 1.0
END DESCRIPTION:
XS GIS Cut Line= 4
      2011889.85     13612812.68        2011132.     13612880.39
      2010647.63     13613351.75      2010892.62      13614644.2
#Sta/Elev= 30
  4072.7  694.17  4082.3  694.43  4137.8  696.54  4181.4  696.94  4258.3  696.29
  4368.7  693.47  4493.1  686.11  4609.7  677.01  4790.4  664.98  4867.5  662.32
  4912.6   661.1  4976.1  661.62  4990.3   658.1  4995.2  658.12  5009.4  657.89
  5011.9  657.09  5027.8  657.89  5046.9  658.69  5053.9  660.45    5061  660.72
  5117.6  659.65  5244.9  661.94  5421.6  662.49  5506.5   660.9  5909.7   664.3
  6272.4  669.03  6486.7  667.93  6642.5   670.5  6734.1  674.61  6824.9   675.9
#Mann= 7 ,-1 , 0
  4072.7     .05       0  4082.3     .05       0  4181.4     .05       0
  4867.5     .12       0  4995.2     .05       0  5009.4     .03       0
  5027.8     .05       0
Bank Sta=5009.4,5027.8
XS Rating Curve= 0 ,0
Exp/Cntr=0.3,0.1
LCMann Table=0

Chan Stop Cuts=-1
Use User Specified Reach Order=0
Composite Channel Slope=5