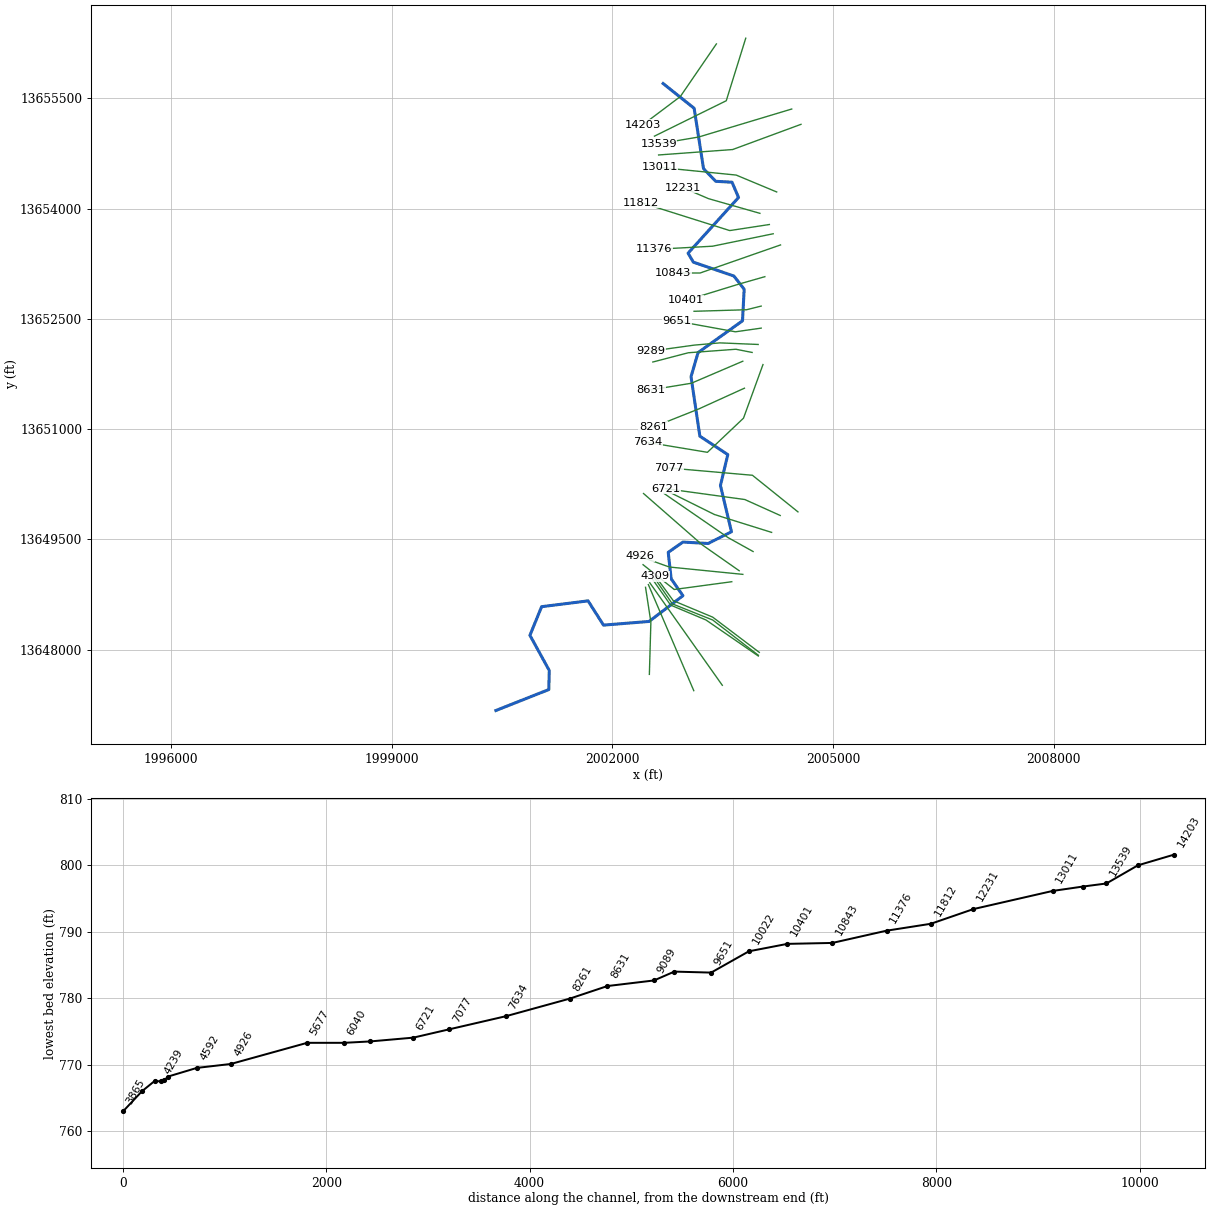
--- GOOSE CREEK.prj (project) ---

Proj Title=GOOSE CREEK Base Level Engineering
Current Plan=p01
Default Exp/Contr=0.3,0.1
English Units
Geom File=g01
Flow File=f01
Plan File=p01
Y Axis Title=Elevation
X Axis Title(PF)=Main Channel Distance
X Axis Title(XS)=Station
BEGIN DESCRIPTION:
GOOSE CREEK
END DESCRIPTION:
DSS Export Rating Curves= 0
DSS Export Rating Curve Sorted= 0
DSS Export Volume Flow Curves= 0
DXF OffsetX= 0
DXF OffsetY= 0
DXF ScaleX= 1
DXF ScaleY= 10

--- GOOSE CREEK.p01 (plan) ---

Plan Title=Multiple Run
Short Identifier=Multiple
Geom File=g01
Flow File=f01
Subcritical Flow
K Sum by GR= 0
Std Step Tol= 0.01
Critical Tol= 0.01
Num of Std Step Trials= 20
Max Error Tol= 0.3
Flow Tol Ratio= 0.001
Split Flow NTrial= 30
Split Flow Tol= 0.02
Split Flow Ratio= 0.02
Log Output Level= 0
Friction Slope Method= 1
Unsteady Friction Slope Method= 2
Unsteady Bridges Friction Slope Method= 1
Parabolic Critical Depth
Global Vel Dist=  1 , 1 , 1
Global Log Level= 0
CheckData=True
Encroach Param= -1, 0, 0, 0
BEGIN DESCRIPTION:
Multiple Run
END DESCRIPTION:

--- GOOSE CREEK.f01 (steady flow) ---

Flow Title=Multiple
Program Version=5.05
Number of Profiles= 7
Profile Names=10-year,25-year,50-year,1pct_min,100-year,1pct_plu,500-year
River Rch & RM=GOOSE CREEK,Reach-1         ,14203
     575     810    1006     620    1236    2467    1872
River Rch & RM=GOOSE CREEK,Reach-1         ,13539
    1094    1590    2017    1265    2524    5037    3970
River Rch & RM=GOOSE CREEK,Reach-1         ,7077
    1423    2091    2672    1687    3365    6714    5360
River Rch & RM=GOOSE CREEK,Reach-1         ,4309
    1585    2340    3001    1899    3789    7561    6069
River Rch & RM=GOOSE CREEK,Reach-1         ,2757
    1585    2340    3001    1899    3789    7561    6069
Boundary for River Rch & Prof#=GOOSE CREEK,Reach-1         , 1
Up Type= 0
Dn Type= 3
Dn Slope=0.005
Boundary for River Rch & Prof#=GOOSE CREEK,Reach-1         , 2
Up Type= 0
Dn Type= 3
Dn Slope=0.005
Boundary for River Rch & Prof#=GOOSE CREEK,Reach-1         , 3
Up Type= 0
Dn Type= 3
Dn Slope=0.005
Boundary for River Rch & Prof#=GOOSE CREEK,Reach-1         , 4
Up Type= 0
Dn Type= 3
Dn Slope=0.005
Boundary for River Rch & Prof#=GOOSE CREEK,Reach-1         , 5
Up Type= 0
Dn Type= 3
Dn Slope=0.005
Boundary for River Rch & Prof#=GOOSE CREEK,Reach-1         , 6
Up Type= 0
Dn Type= 3
Dn Slope=0.005
Boundary for River Rch & Prof#=GOOSE CREEK,Reach-1         , 7
Up Type= 0
Dn Type= 3
Dn Slope=0.005
DSS Import GetInterval= 0
DSS Import GetPeak= 0
DSS Import FillOption= 0

--- GOOSE CREEK.g01 (geometry) ---

Geom Title=Existing Conditions

River Reach=GOOSE CREEK,Reach-1
Reach XY= 30
      2002691.51     13655702.23      2003113.04     13655366.12
      2003240.80     13654544.54      2003406.55     13654372.58
      2003628.08     13654360.08      2003716.97     13654152.44
      2003030.80     13653394.54      2003102.39     13653272.58
      2003653.77     13653083.69      2003793.36     13652904.53
      2003770.80     13652474.54      2003166.27     13652042.03
      2003070.80     13651714.54      2003190.80     13650904.54
      2003570.80     13650654.54      2003470.80     13650234.54
      2003620.80     13649604.54      2003302.78     13649445.05
      2002960.80     13649464.54      2002760.80     13649324.54
      2002800.80     13648964.54      2002960.80     13648734.54
      2002500.80     13648384.54      2001880.80     13648334.54
      2001670.80     13648664.54      2001039.32     13648585.46
      2000880.47     13648196.13      2001143.49     13647716.97
      2001136.98     13647457.85      2000417.33     13647172.84

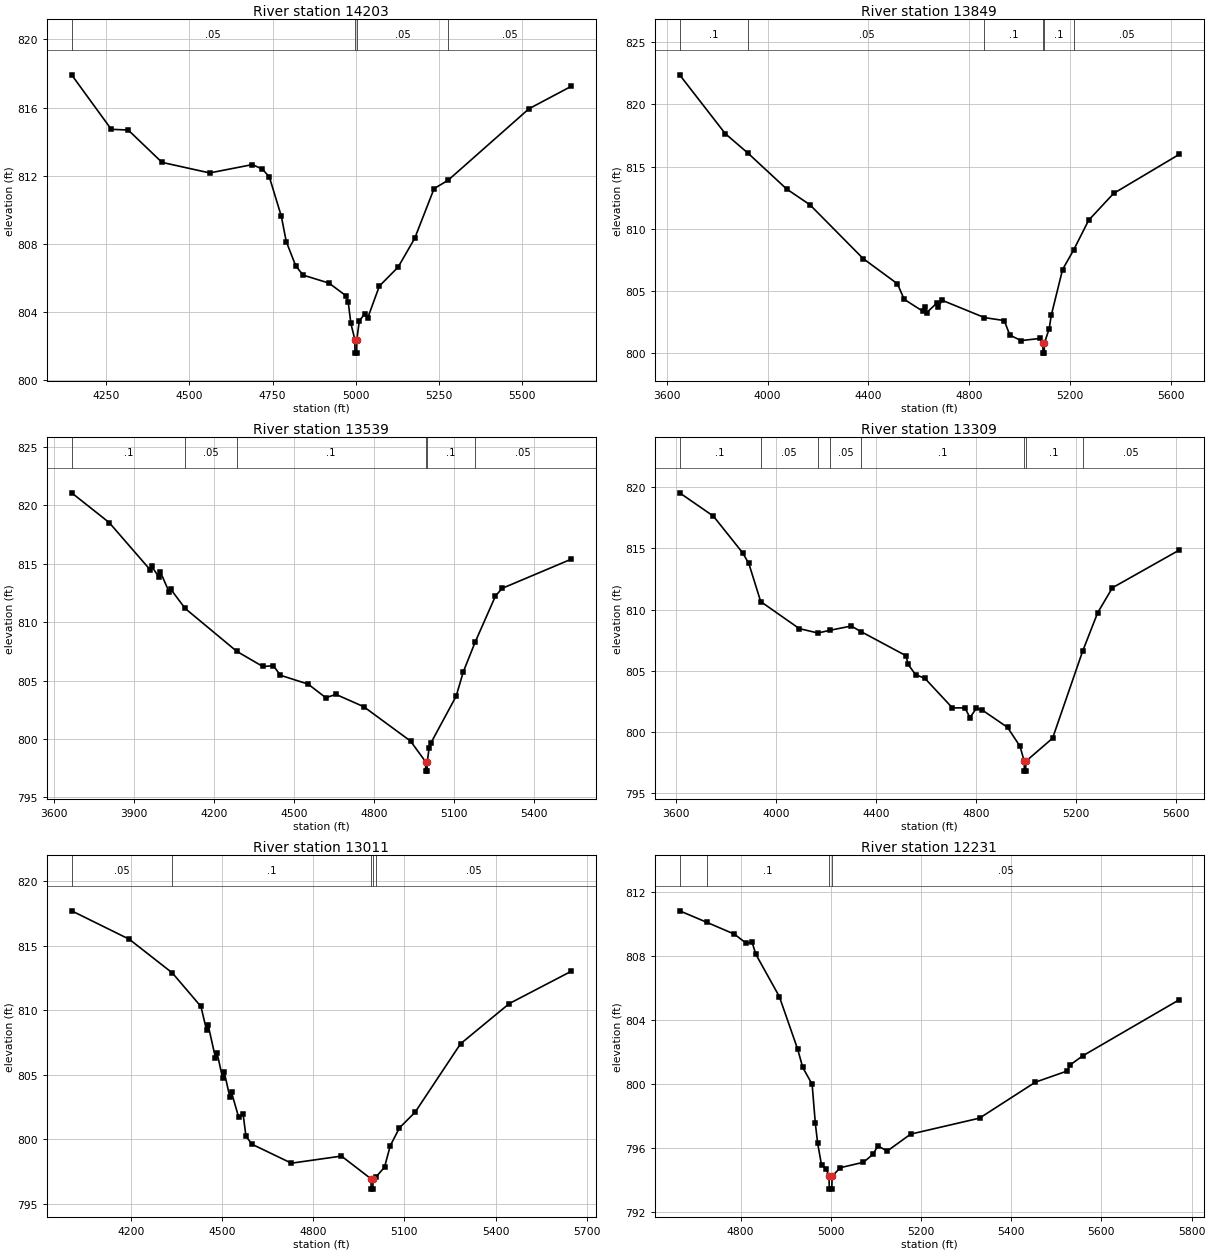
Type RM Length L Ch R = 1,14203,354,354,354
BEGIN DESCRIPTION:
GOOSE CREEK 28.0
END DESCRIPTION:
XS GIS Cut Line= 3
      2003415.43     13656241.23      2002925.00     13655525.00
      2002418.55     13655144.17
#Sta/Elev= 30
  4146.0  817.92  4265.2  814.72  4316.0  814.68  4417.6  812.78  4561.1  812.16
  4689.7  812.65  4719.6  812.38  4740.5  811.92  4776.4  809.62  4791.3  808.13
  4820.1  806.69  4842.1  806.16  4919.9  805.69  4970.7  804.95  4977.7  804.56
  4985.6  803.32  4997.5  802.38  4998.0  801.58  5003.0  801.58  5003.5  802.38
  5011.0  803.48  5027.6  803.89  5035.9  803.63  5071.3  805.52  5127.6  806.63
  5177.5  808.32  5235.8  811.24  5277.9  811.73  5521.2  815.93  5647.7  817.24
#Mann=4,-1,0
  4146.0    0.05       0  4997.5   0.035       0  5003.5    0.05       0
  5277.9    0.05       0
Bank Sta=4997.5,5003.5
Exp/Cntr=0.3,0.1

Type RM Length L Ch R = 1,13849,310,310,310
BEGIN DESCRIPTION:
GOOSE CREEK 27.0
END DESCRIPTION:
XS GIS Cut Line= 3
      2003814.72     13656319.36      2003549.96     13655468.64
      2002573.40     13654986.87
#Sta/Elev= 30
  3651.4  822.38  3832.2  817.65  3923.7  816.05  4075.6  813.19  4168.0  811.92
  4378.9  807.59  4514.8  805.56  4541.6  804.31  4614.8  803.36  4625.0  803.68
  4630.6  803.23  4669.9  803.99  4675.5  803.66  4692.4  804.23  4859.9  802.84
  4938.2  802.60  4960.5  801.43  5005.1  800.99  5079.7  801.16  5091.3  800.78
  5091.8  799.98  5096.8  799.98  5097.3  800.78  5116.6  801.96  5124.6  803.02
  5169.5  806.71  5214.1  808.31  5272.7  810.67  5371.5  812.83  5631.3  815.97
#Mann=6,-1,0
  3651.4     0.1       0  3923.7    0.05       0  4859.9     0.1       0
  5091.3    0.07       0  5097.3     0.1       0  5214.1    0.05       0
Bank Sta=5091.3,5097.3
Exp/Cntr=0.3,0.1

Type RM Length L Ch R = 1,13539,230,230,230
BEGIN DESCRIPTION:
GOOSE CREEK 26.0
END DESCRIPTION:
XS GIS Cut Line= 3
      2004439.71     13655355.79      2003175.00     13654975.00
      2002629.95     13654882.72
#Sta/Elev= 30
  3664.8  821.05  3805.5  818.51  3959.6  814.46  3964.9  814.76  3992.7  813.84
  3997.9  814.27  4030.9  812.55  4036.1  812.82  4090.7  811.16  4284.5  807.49
  4381.8  806.20  4421.7  806.26  4447.9  805.45  4552.1  804.69  4618.1  803.53
  4656.4  803.81  4760.6  802.76  4936.1  799.82  4992.6  798.05  4993.1  797.25
  4998.4  797.25  4998.9  798.05  5005.9  799.24  5013.3  799.69  5107.3  803.66
  5134.0  805.74  5178.3  808.27  5254.8  812.23  5279.7  812.88  5538.4  815.37
#Mann=6,-1,0
  3664.8     0.1       0  4090.7    0.05       0  4284.5     0.1       0
  4992.6    0.07       0  4998.9     0.1       0  5178.3    0.05       0
Bank Sta=4992.6,4998.9
Exp/Cntr=0.3,0.1

Type RM Length L Ch R = 1,13309,298,298,298
BEGIN DESCRIPTION:
Mapping XS 5aa0589c
END DESCRIPTION:
XS GIS Cut Line= 3
      2004565.57     13655147.45      2003636.77     13654804.58
      2002629.94     13654730.80
#Sta/Elev= 30
  3612.9  819.54  3748.3  817.63  3864.7  814.65  3889.8  813.77  3937.5  810.65
  4092.1  808.44  4166.6  808.08  4213.9  808.30  4299.8  808.65  4339.6  808.19
  4519.6  806.22  4527.2  805.53  4557.7  804.67  4594.2  804.39  4705.0  801.96
  4755.1  801.96  4775.2  801.17  4801.3  801.93  4825.3  801.77  4925.6  800.37
  4975.7  798.82  4992.6  797.59  4993.1  796.79  4998.4  796.79  4998.9  797.59
  5106.1  799.48  5226.2  806.58  5286.6  809.74  5345.7  811.78  5612.5  814.85
#Mann=8,-1,0
  3612.9     0.1       0  3937.5    0.05       0  4166.6     0.1       0
  4213.9    0.05       0  4339.6     0.1       0  4992.6    0.07       0
  4998.9     0.1       0  5226.2    0.05       0
Bank Sta=4992.6,4998.9
Exp/Cntr=0.3,0.1

Type RM Length L Ch R = 1,13011,780,780,780
BEGIN DESCRIPTION:
Mapping XS 161aa6cc
END DESCRIPTION:
XS GIS Cut Line= 3
      2004235.72     13654227.32      2003684.51     13654457.35
      2002642.89     13654561.52
#Sta/Elev= 30
  4004.6  817.69  4194.2  815.49  4336.0  812.88  4430.2  810.28  4448.6  808.45
  4454.0  808.84  4477.8  806.32  4483.3  806.68  4501.7  804.72  4507.1  805.18
  4525.5  803.25  4530.9  803.62  4554.7  801.68  4568.8  801.98  4578.5  800.22
  4598.9  799.60  4728.0  798.14  4892.8  798.69  4990.0  796.93  4990.5  796.13
  4996.2  796.13  4996.7  796.93  5007.5  797.10  5034.5  797.83  5053.6  799.50
  5083.8  800.88  5135.0  802.08  5284.8  807.39  5445.6  810.51  5648.7  813.00
#Mann=5,-1,0
  4004.6    0.05       0  4336.0     0.1       0  4990.0    0.07       0
  4996.7     0.1       0  5007.5    0.05       0
Bank Sta=4990,4996.7
Exp/Cntr=0.3,0.1

Type RM Length L Ch R = 1,12231,419,419,419
BEGIN DESCRIPTION:
GOOSE CREEK 25.0
END DESCRIPTION:
XS GIS Cut Line= 3
      2004007.46     13653936.81      2003307.47     13654136.81
      2002958.74     13654286.26
#Sta/Elev= 30
  4664.8  810.81  4725.2  810.09  4786.3  809.35  4813.0  808.77  4825.3  808.86
  4833.8  808.09  4885.8  805.45  4926.7  802.14  4937.8  801.01  4958.6  799.96
  4965.7  797.51  4970.9  796.26  4979.4  794.91  4989.8  794.67  4996.1  794.20
  4996.6  793.40  5002.3  793.40  5002.8  794.20  5021.0  794.74  5072.3  795.08
  5093.8  795.58  5104.2  796.11  5125.0  795.78  5177.0  796.84  5329.7  797.84
  5453.5  800.09  5524.2  800.79  5529.7  801.15  5558.7  801.74  5772.2  805.24
#Mann=4,-1,0
  4664.8    0.05       0  4725.2     0.1       0  4996.1   0.035       0
  5002.8    0.05       0
Bank Sta=4996.1,5002.8
Exp/Cntr=0.3,0.1

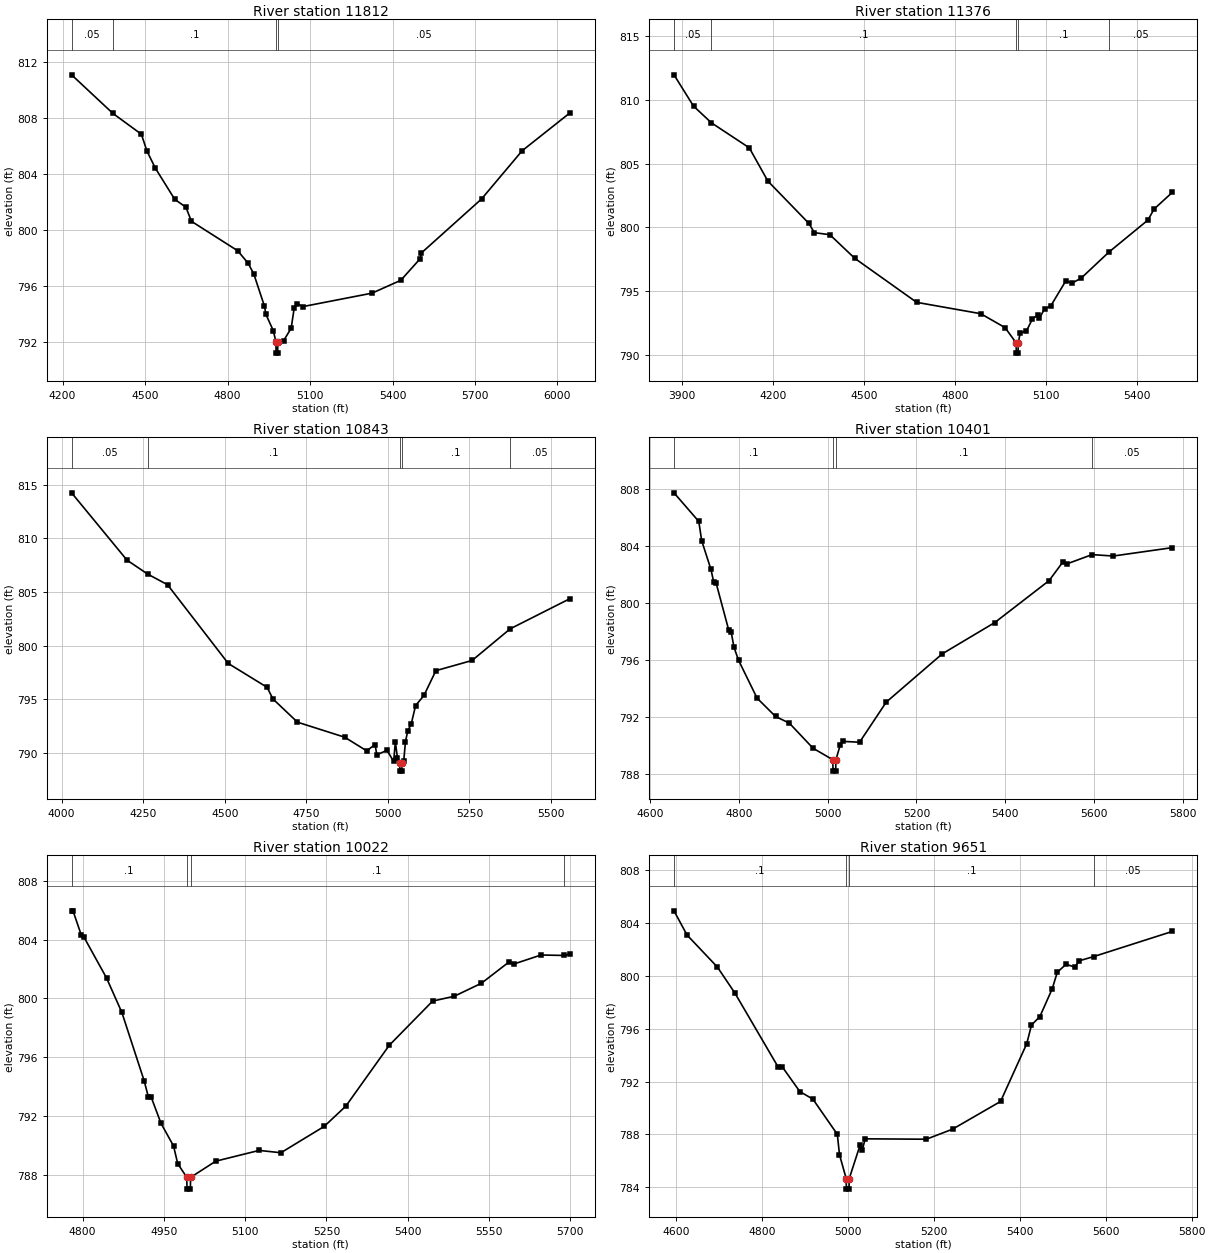
Type RM Length L Ch R = 1,11812,436,436,436
BEGIN DESCRIPTION:
GOOSE CREEK 24.0
END DESCRIPTION:
XS GIS Cut Line= 3
      2004135.88     13653784.61      2003597.70     13653702.15
      2002388.39     13654083.58
#Sta/Elev= 30
  4232.9  811.10  4383.1  808.34  4486.7  806.85  4506.9  805.65  4537.3  804.43
  4608.1  802.19  4648.6  801.63  4668.8  800.62  4837.3  798.51  4874.9  797.62
  4895.5  796.86  4934.3  794.55  4939.6  793.96  4966.7  792.79  4976.1  791.99
  4976.6  791.19  4982.3  791.19  4982.8  791.99  5004.3  792.09  5031.4  792.97
  5042.3  794.39  5052.8  794.74  5074.2  794.52  5325.4  795.48  5430.1  796.40
  5500.0  797.93  5505.3  798.36  5723.9  802.22  5871.6  805.67  6045.4  808.38
#Mann=4,-1,0
  4232.9    0.05       0  4383.1     0.1       0  4976.1   0.035       0
  4982.8    0.05       0
Bank Sta=4976.1,4982.8
Exp/Cntr=0.3,0.1

Type RM Length L Ch R = 1,11376,533,533,533
BEGIN DESCRIPTION:
Mapping XS 695e6f5f
END DESCRIPTION:
XS GIS Cut Line= 3
      2004187.97     13653658.74      2003363.33     13653489.47
      2002564.74     13653446.07
#Sta/Elev= 30
  3874.5  811.96  3938.8  809.51  3997.7  808.20  4122.5  806.24  4183.8  803.63
  4318.7  800.32  4336.9  799.59  4388.0  799.43  4469.9  797.58  4673.8  794.13
  4884.9  793.24  4965.0  792.15  5001.6  790.95  5002.1  790.15  5008.0  790.15
  5008.5  790.95  5015.1  791.76  5035.1  791.87  5055.2  792.83  5072.7  793.14
  5077.7  792.87  5095.2  793.62  5115.3  793.84  5165.3  795.82  5185.4  795.64
  5215.4  796.02  5307.2  798.07  5435.7  800.58  5455.8  801.44  5516.1  802.75
#Mann=5,-1,0
  3874.5    0.05       0  3997.7     0.1       0  5001.6    0.07       0
  5008.5     0.1       0  5307.2    0.05       0
Bank Sta=5001.6,5008.5
Exp/Cntr=0.3,0.1

Type RM Length L Ch R = 1,10843,442,442,442
BEGIN DESCRIPTION:
GOOSE CREEK 23.0
END DESCRIPTION:
XS GIS Cut Line= 3
      2004287.82     13653506.84      2003194.06     13653124.89
      2002824.99     13653125.00
#Sta/Elev= 30
  4030.4  814.24  4200.2  807.97  4263.5  806.67  4324.4  805.68  4510.7  798.34
  4629.6  796.12  4647.7  795.03  4722.8  792.87  4867.5  791.47  4934.9  790.20
  4960.7  790.79  4965.9  789.83  4997.3  790.25  5017.5  789.21  5022.8  791.02
  5029.1  789.57  5036.2  789.11  5036.7  788.31  5042.6  788.31  5043.1  789.11
  5048.5  789.25  5053.8  791.07  5060.8  792.05  5071.4  792.71  5084.9  794.42
  5110.6  795.37  5147.0  797.67  5258.0  798.62  5374.9  801.57  5558.0  804.38
#Mann=5,-1,0
  4030.4    0.05       0  4263.5     0.1       0  5036.2    0.07       0
  5043.1     0.1       0  5374.9    0.05       0
Bank Sta=5036.2,5043.1
Exp/Cntr=0.3,0.1

Type RM Length L Ch R = 1,10401,379,379,379
BEGIN DESCRIPTION:
GOOSE CREEK 22.0
END DESCRIPTION:
XS GIS Cut Line= 3
      2004074.96     13653074.99      2003725.00     13652975.00
      2002999.41     13652751.83
#Sta/Elev= 30
  4653.6  807.72  4709.5  805.71  4716.0  804.36  4736.8  802.35  4743.3  801.43
  4748.5  801.39  4777.1  798.06  4782.3  797.97  4788.8  796.87  4799.2  795.95
  4840.8  793.30  4882.4  792.01  4913.6  791.54  4966.9  789.78  5011.5  788.97
  5012.0  788.17  5018.0  788.17  5018.5  788.97  5028.0  789.98  5033.9  790.26
  5071.8  790.20  5132.0  793.02  5258.2  796.41  5376.6  798.61  5498.8  801.55
  5530.2  802.87  5540.1  802.74  5595.8  803.38  5643.5  803.28  5776.7  803.87
#Mann=4,-1,0
  4653.6     0.1       0  5011.5    0.07       0  5018.5     0.1       0
  5595.8    0.05       0
Bank Sta=5011.5,5018.5
Exp/Cntr=0.3,0.1

Type RM Length L Ch R = 1,10022,371,371,371
BEGIN DESCRIPTION:
GOOSE CREEK 21.0
END DESCRIPTION:
XS GIS Cut Line= 3
      2004025.04     13652675.01      2003825.00     13652625.00
      2003111.60     13652604.06
#Sta/Elev= 30
  4779.6  805.95  4782.2  805.95  4797.7  804.28  4802.8  804.14  4844.1  801.39
  4872.4  799.05  4913.6  794.40  4921.4  793.30  4926.5  793.30  4944.6  791.52
  4967.8  789.98  4975.5  788.78  4992.2  787.85  4992.7  787.05  4998.8  787.05
  4999.3  787.85  5045.8  788.95  5125.9  789.68  5165.9  789.52  5245.9  791.31
  5285.9  792.69  5366.0  796.82  5446.0  799.82  5486.0  800.15  5536.0  801.03
  5586.1  802.45  5596.1  802.34  5646.1  802.95  5687.6  802.92  5699.5  803.00
#Mann=4,-1,0
  4779.6     0.1       0  4992.2    0.07       0  4999.3     0.1       0
  5687.6    0.05       0
Bank Sta=4992.2,4999.3
Exp/Cntr=0.3,0.1

Type RM Length L Ch R = 1,9651,362,362,362
BEGIN DESCRIPTION:
GOOSE CREEK 20.0
END DESCRIPTION:
XS GIS Cut Line= 3
      2004024.95     13652374.99      2003675.00     13652325.00
      2002881.56     13652469.51
#Sta/Elev= 30
  4595.1  804.93  4625.4  803.10  4696.1  800.67  4736.5  798.72  4837.5  793.10
  4847.6  793.09  4888.0  791.24  4918.3  790.67  4975.3  788.00  4980.3  786.46
  4995.9  784.65  4996.4  783.85  5002.5  783.85  5003.0  784.65  5028.6  787.22
  5033.7  786.85  5040.1  787.66  5182.4  787.63  5243.4  788.39  5355.2  790.49
  5416.2  794.87  5427.2  796.28  5446.7  796.92  5475.4  799.02  5487.3  800.28
  5507.7  800.88  5528.0  800.67  5538.9  801.15  5572.5  801.47  5755.1  803.37
#Mann=4,-1,0
  4595.1     0.1       0  4995.9    0.07       0  5003.0     0.1       0
  5572.5    0.05       0
Bank Sta=4995.9,5003
Exp/Cntr=0.3,0.1

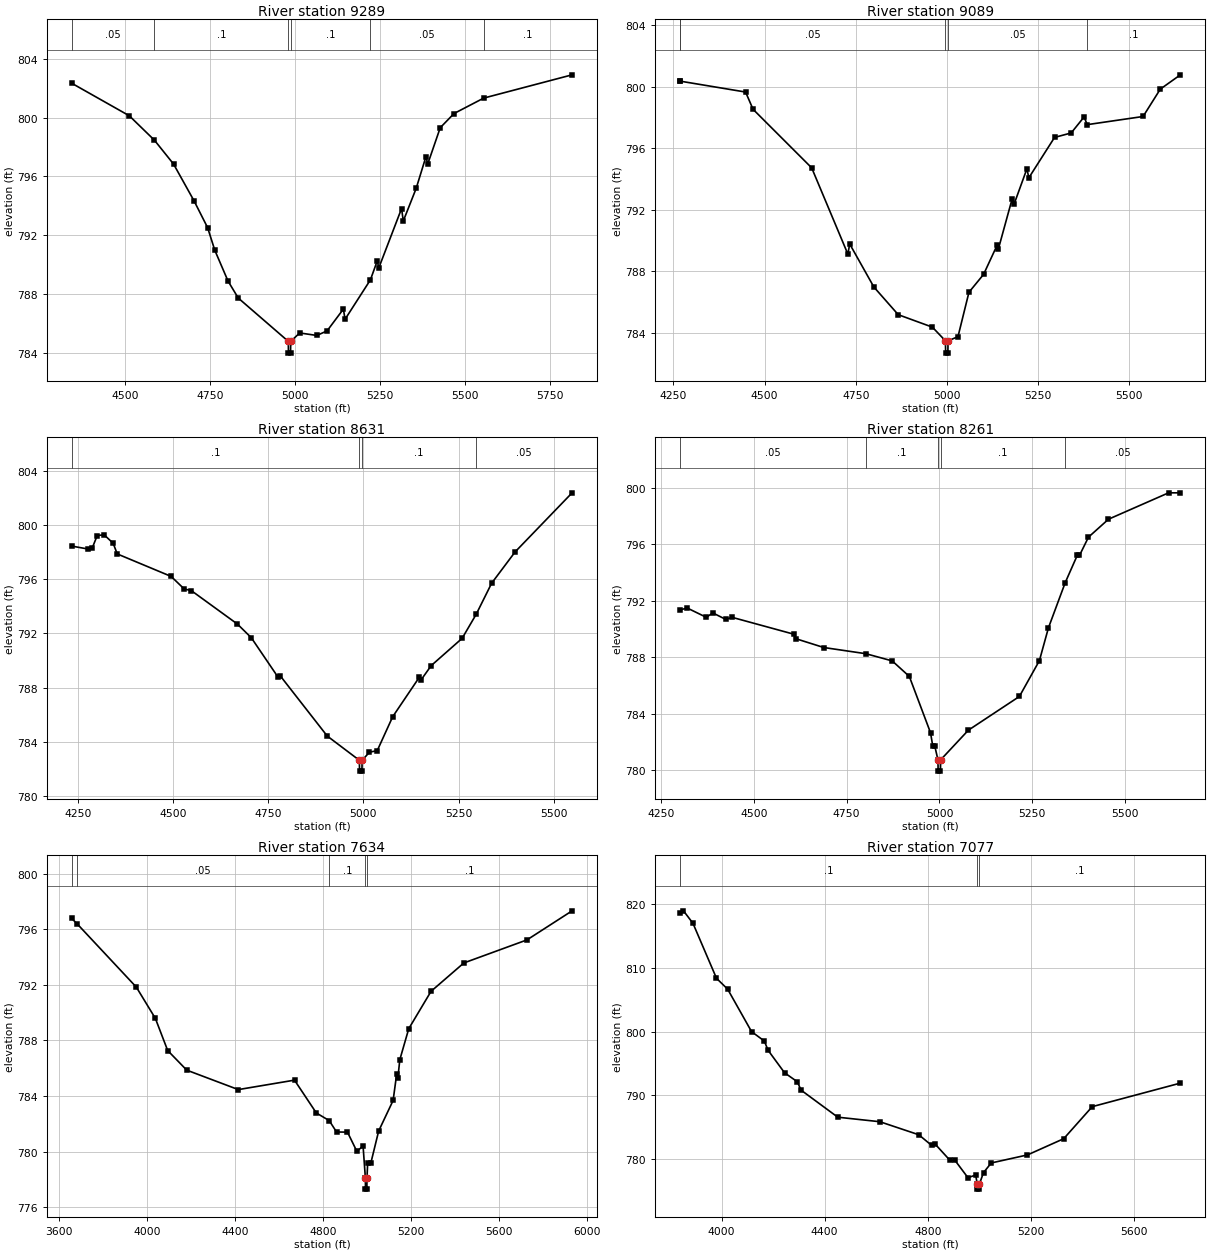
Type RM Length L Ch R = 1,9289,200,200,200
BEGIN DESCRIPTION:
Mapping XS ed78951c
END DESCRIPTION:
XS GIS Cut Line= 4
      2003984.01     13652152.66      2003463.15     13652174.37
      2003115.93     13652143.99      2002521.28     13652061.52
#Sta/Elev= 30
  4343.9  802.33  4513.1  800.12  4587.0  798.46  4643.2  796.84  4703.2  794.35
  4743.3  792.52  4764.3  790.99  4803.3  788.89  4833.3  787.74  4980.3  784.80
  4980.8  784.00  4986.9  784.00  4987.4  784.80  5013.9  785.37  5064.1  785.20
  5094.2  785.51  5142.1  786.99  5147.1  786.30  5221.6  788.98  5241.4  790.25
  5246.4  789.80  5313.1  793.82  5318.1  792.97  5356.0  795.19  5384.8  797.35
  5389.9  796.84  5426.7  799.31  5467.1  800.27  5554.4  801.32  5814.1  802.90
#Mann=6,-1,0
  4343.9    0.05       0  4587.0     0.1       0  4980.3    0.07       0
  4987.4     0.1       0  5221.6    0.05       0  5554.4     0.1       0
Bank Sta=4980.3,4987.4
Exp/Cntr=0.3,0.1

Type RM Length L Ch R = 1,9089,458,458,458
BEGIN DESCRIPTION:
GOOSE CREEK 19.0
END DESCRIPTION:
XS GIS Cut Line= 4
      2003901.54     13652044.16      2003680.17     13652087.56
      2003033.47     13652039.82      2002551.69     13651913.95
#Sta/Elev= 30
  4267.9  800.36  4268.1  800.36  4447.8  799.65  4468.2  798.53  4629.0  794.72
  4728.2  789.11  4733.2  789.77  4799.5  786.97  4866.3  785.17  4959.9  784.36
  4995.7  783.47  4996.3  782.67  5002.4  782.67  5002.9  783.47  5030.1  783.74
  5060.2  786.63  5100.3  787.79  5137.4  789.69  5140.7  789.43  5178.7  792.71
  5183.8  792.35  5219.1  794.66  5224.3  794.07  5294.9  796.70  5340.5  796.99
  5375.8  798.03  5384.5  797.53  5537.6  798.06  5584.8  799.84  5639.9  800.77
#Mann=5,-1,0
  4267.9     0.1       0  4268.1    0.05       0  4995.7    0.04       0
  5002.9    0.05       0  5384.5     0.1       0
Bank Sta=4995.7,5002.9
Exp/Cntr=0.3,0.1

Type RM Length L Ch R = 1,8631,370,370,370
BEGIN DESCRIPTION:
GOOSE CREEK 18.0
END DESCRIPTION:
XS GIS Cut Line= 3
      2003774.97     13651924.99      2003075.00     13651625.00
      2002530.01     13651536.35
#Sta/Elev= 30
  4234.2  798.44  4277.7  798.22  4288.6  798.33  4301.3  799.22  4319.4  799.27
  4343.0  798.65  4353.8  797.86  4495.3  796.20  4529.7  795.27  4547.9  795.16
  4669.4  792.68  4705.6  791.68  4776.3  788.75  4781.8  788.86  4905.1  784.42
  4989.4  782.63  4989.9  781.83  4996.1  781.83  4996.7  782.63  5016.0  783.23
  5036.3  783.34  5076.8  785.84  5147.1  788.77  5152.1  788.59  5178.1  789.62
  5259.2  791.63  5296.2  793.41  5336.7  795.70  5398.3  798.01  5547.9  802.37
#Mann=4,-1,0
  4234.2     0.1       0  4989.4    0.07       0  4996.7     0.1       0
  5296.2    0.05       0
Bank Sta=4989.4,4996.7
Exp/Cntr=0.3,0.1

Type RM Length L Ch R = 1,8261,627,627,627
BEGIN DESCRIPTION:
GOOSE CREEK 17.0
END DESCRIPTION:
XS GIS Cut Line= 3
      2003797.37     13651558.05      2003175.00     13651275.00
      2002557.84     13651029.25
#Sta/Elev= 30
  4301.0  791.36  4320.3  791.50  4371.9  790.84  4389.5  791.15  4424.4  790.69
  4441.1  790.84  4608.0  789.64  4613.5  789.32  4688.2  788.70  4801.8  788.26
  4872.7  787.75  4918.8  786.65  4975.9  782.66  4982.0  781.71  4987.4  781.71
  4995.9  780.74  4996.4  779.94  5002.6  779.94  5003.2  780.74  5077.8  782.84
  5215.3  785.23  5269.2  787.77  5293.5  790.09  5338.8  793.30  5371.7  795.26
  5377.1  795.22  5401.4  796.52  5455.3  797.79  5617.2  799.66  5649.0  799.66
#Mann=5,-1,0
  4301.0    0.05       0  4801.8     0.1       0  4995.9    0.07       0
  5003.2     0.1       0  5338.8    0.05       0
Bank Sta=4995.9,5003.2
Exp/Cntr=0.3,0.1

Type RM Length L Ch R = 1,7634,557,557,557
BEGIN DESCRIPTION:
GOOSE CREEK 16.0
END DESCRIPTION:
XS GIS Cut Line= 4
      2004049.10     13651879.25      2003784.33     13651150.06
      2003293.88     13650685.65      2002482.86     13650820.10
#Sta/Elev= 30
  3659.0  796.77  3683.4  796.39  3952.7  791.83  4039.2  789.58  4095.1  787.27
  4181.6  785.86  4415.9  784.46  4671.2  785.14  4770.3  782.78  4828.9  782.23
  4862.2  781.41  4911.9  781.40  4954.4  780.02  4982.7  780.40  4993.2  778.10
  4993.7  777.30  4999.9  777.30  5000.5  778.10  5003.7  779.21  5017.9  779.17
  5053.5  781.48  5119.2  783.68  5135.6  785.60  5140.7  785.28  5149.6  786.61
  5190.2  788.84  5291.5  791.53  5440.5  793.57  5727.4  795.23  5932.3  797.32
#Mann=5,-1,0
  3659.0     0.1       0  3683.4    0.05       0  4828.9     0.1       0
  4993.2    0.07       0  5000.5     0.1       0
Bank Sta=4993.2,5000.5
Exp/Cntr=0.3,0.1

Type RM Length L Ch R = 1,7077,356,356,356
BEGIN DESCRIPTION:
GOOSE CREEK 15.0
END DESCRIPTION:
XS GIS Cut Line= 3
      2004524.99     13649875.01      2003905.86     13650373.15
      2002764.36     13650472.98
#Sta/Elev= 30
  3838.9  818.60  3852.5  818.93  3889.3  816.97  3980.5  808.36  4023.7  806.66
  4116.4  800.01  4166.0  798.53  4180.4  797.09  4244.4  793.56  4294.0  792.15
  4308.4  790.84  4450.8  786.60  4614.0  785.89  4764.9  783.85  4815.1  782.17
  4828.5  782.38  4885.4  779.86  4905.4  779.83  4955.6  777.12  4985.7  777.54
  4991.4  776.13  4992.2  775.33  4999.3  775.33  5000.1  776.13  5015.9  777.92
  5046.0  779.43  5186.5  780.69  5327.0  783.23  5437.5  788.25  5779.4  791.94
#Mann=3,-1,0
  3838.9     0.1       0  4991.4    0.07       0  5000.1     0.1       0
Bank Sta=4991.4,5000.1
Exp/Cntr=0.3,0.1

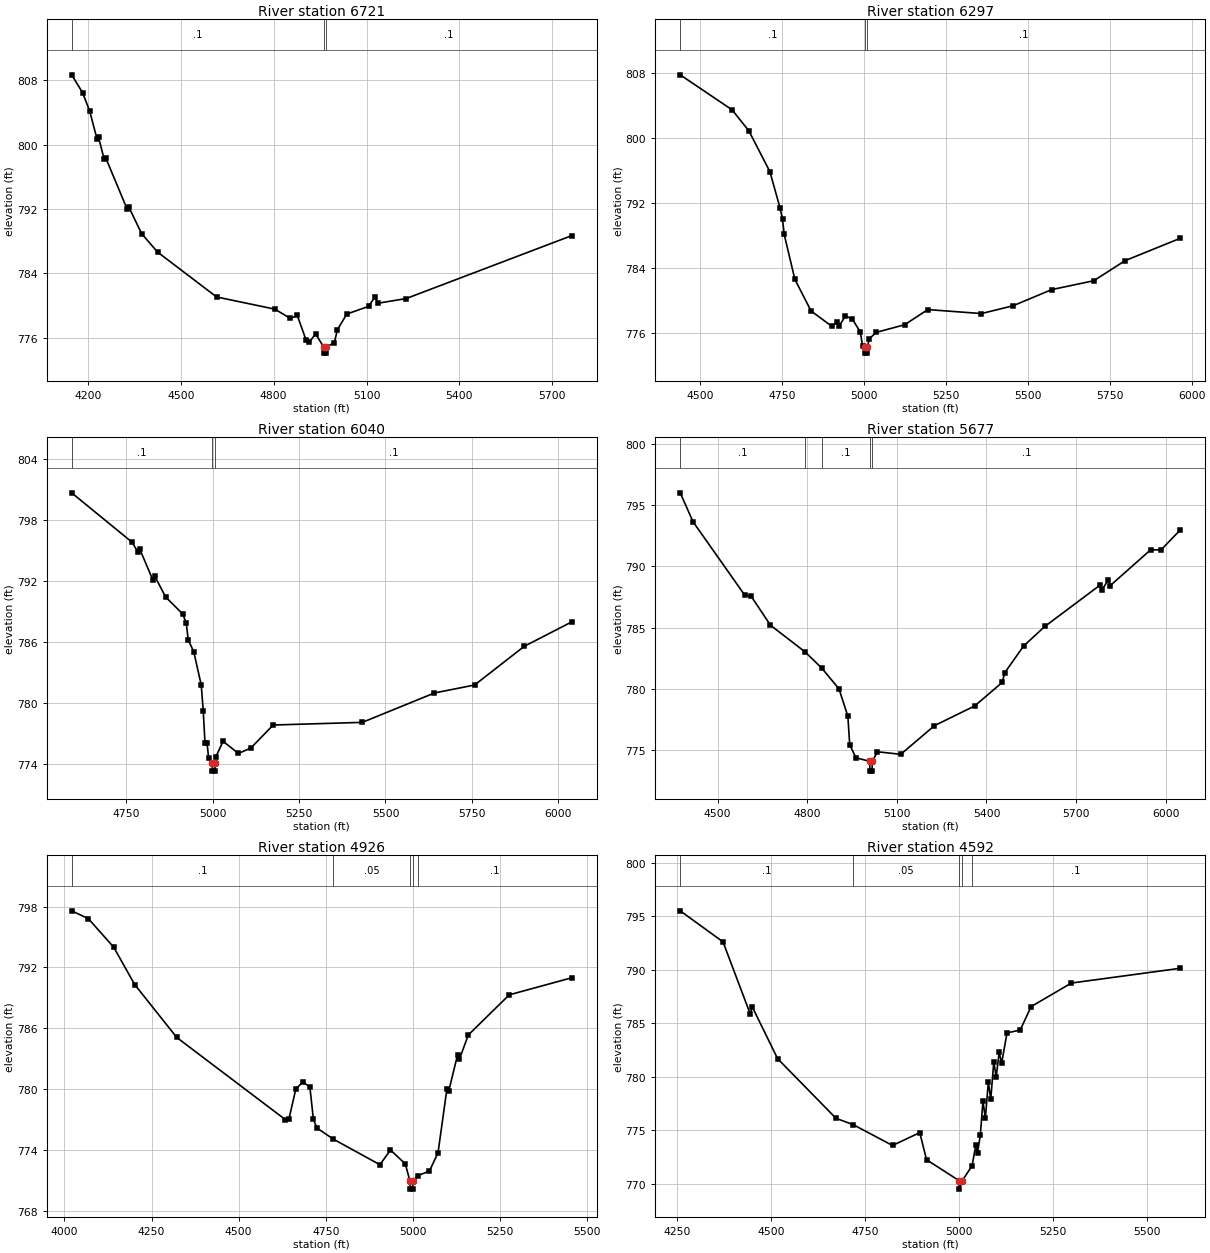
Type RM Length L Ch R = 1,6721,424,424,424
BEGIN DESCRIPTION:
GOOSE CREEK 14.0
END DESCRIPTION:
XS GIS Cut Line= 3
      2004283.47     13649826.27      2003801.70     13650043.29
      2002725.27     13650190.87
#Sta/Elev= 30
  4147.7  808.70  4182.8  806.49  4205.9  804.20  4229.1  800.77  4234.5  800.94
  4252.2  798.25  4257.7  798.37  4327.1  791.97  4332.6  792.23  4373.4  788.95
  4425.2  786.64  4615.8  781.06  4804.1  779.54  4854.4  778.38  4876.2  778.77
  4904.9  775.68  4915.0  775.40  4935.2  776.48  4961.1  774.87  4961.9  774.07
  4969.1  774.07  4969.9  774.87  4995.8  775.34  5005.9  776.98  5036.1  778.93
  5106.8  779.89  5127.0  781.06  5137.1  780.28  5227.9  780.86  5762.6  788.69
#Mann=3,-1,0
  4147.7     0.1       0  4961.1    0.07       0  4969.9     0.1       0
Bank Sta=4961.1,4969.9
Exp/Cntr=0.3,0.1

Type RM Length L Ch R = 1,6297,257,257,257
BEGIN DESCRIPTION:
Mapping XS cb603e80
END DESCRIPTION:
XS GIS Cut Line= 3
      2004166.30     13649596.23      2003389.37     13649839.30
      2002751.37     13650156.13
#Sta/Elev= 30
  4438.9  807.82  4597.4  803.50  4648.5  800.91  4712.7  795.88  4744.1  791.34
  4751.2  790.01  4756.4  788.14  4788.9  782.60  4838.4  778.70  4901.3  776.82
  4918.7  777.35  4923.9  776.83  4943.2  778.08  4964.2  777.71  4988.9  776.09
  4995.6  774.35  5001.7  774.30  5002.5  773.50  5009.7  773.50  5010.5  774.30
  5016.1  775.27  5037.5  776.06  5124.0  777.00  5194.7  778.87  5358.3  778.38
  5455.1  779.34  5572.7  781.33  5701.5  782.43  5796.8  784.90  5965.3  787.66
#Mann=3,-1,0
  4438.9     0.1       0  5001.7    0.07       0  5010.5     0.1       0
Bank Sta=5001.7,5010.5
Exp/Cntr=0.3,0.1

Type RM Length L Ch R = 1,6040,363,363,363
BEGIN DESCRIPTION:
GOOSE CREEK 13.0
END DESCRIPTION:
XS GIS Cut Line= 3
      2003914.57     13649335.81      2003575.00     13649525.00
      2002703.63     13650125.74
#Sta/Elev= 30
  4591.8  800.63  4766.8  795.77  4782.8  794.85  4788.5  795.13  4826.2  792.11
  4831.9  792.46  4863.9  790.39  4913.1  788.73  4923.3  787.85  4929.1  786.19
  4945.1  785.02  4966.8  781.75  4972.5  779.24  4977.7  776.04  4983.6  776.04
  4988.0  774.62  4998.4  774.09  4999.2  773.29  5006.4  773.29  5007.2  774.09
  5008.9  774.68  5029.9  776.22  5074.5  775.03  5110.4  775.56  5174.9  777.82
  5432.9  778.08  5641.8  780.97  5757.9  781.75  5901.5  785.55  6038.9  787.95
#Mann=3,-1,0
  4591.8     0.1       0  4998.4    0.07       0  5007.2     0.1       0
Bank Sta=4998.4,5007.2
Exp/Cntr=0.3,0.1

Type RM Length L Ch R = 1,5677,751,751,751
BEGIN DESCRIPTION:
GOOSE CREEK 12.0
END DESCRIPTION:
XS GIS Cut Line= 3
      2003725.00     13649075.00      2003225.00     13649425.00
      2002425.03     13650124.97
#Sta/Elev= 30
  4375.1  795.99  4418.3  793.62  4590.9  787.65  4611.8  787.58  4677.2  785.19
  4792.7  783.02  4848.2  781.71  4906.5  780.00  4936.2  777.76  4942.3  775.45
  4963.2  774.38  5009.0  774.09  5009.8  773.29  5017.1  773.29  5017.9  774.09
  5035.3  774.87  5113.1  774.66  5226.0  777.00  5360.8  778.61  5452.9  780.53
  5460.5  781.29  5524.1  783.49  5595.2  785.09  5779.4  788.45  5786.0  788.05
  5807.8  788.90  5814.5  788.43  5949.3  791.34  5984.4  791.34  6048.4  792.96
#Mann=5,-1,0
  4375.1     0.1       0  4792.7    0.05       0  4848.2     0.1       0
  5009.0    0.07       0  5017.9     0.1       0
Bank Sta=5009,5017.9
Exp/Cntr=0.3,0.1

Type RM Length L Ch R = 1,4926,334,334,334
BEGIN DESCRIPTION:
GOOSE CREEK 11.0
END DESCRIPTION:
XS GIS Cut Line= 3
      2003775.04     13649025.00      2002775.00     13649125.00
      2002370.73     13649270.25
#Sta/Elev= 30
  4020.9  797.58  4068.7  796.81  4141.5  793.99  4201.8  790.30  4322.4  785.08
  4634.0  776.97  4644.0  777.01  4664.1  780.00  4684.2  780.68  4704.3  780.20
  4714.4  777.00  4724.4  776.15  4770.9  775.06  4905.3  772.52  4935.5  773.97
  4978.2  772.60  4991.3  770.91  4992.1  770.11  4999.4  770.11  5000.3  770.91
  5014.4  771.45  5047.2  771.89  5072.0  773.70  5097.4  779.99  5102.7  779.79
  5128.2  783.39  5133.5  782.95  5158.9  785.33  5276.5  789.29  5455.5  790.97
#Mann=5,-1,0
  4020.9     0.1       0  4770.9    0.05       0  4991.3   0.035       0
  5000.3    0.05       0  5014.4     0.1       0
Bank Sta=4991.3,5000.3
Exp/Cntr=0.3,0.1

Type RM Length L Ch R = 1,4592,283,283,283
BEGIN DESCRIPTION:
GOOSE CREEK 10.0
END DESCRIPTION:
XS GIS Cut Line= 3
      2003624.96     13648925.00      2002842.49     13648819.33
      2002418.55     13649156.75
#Sta/Elev= 30
  4258.0  795.53  4372.0  792.63  4444.7  785.87  4449.8  786.56  4517.4  781.71
  4672.8  776.14  4719.0  775.54  4823.3  773.60  4895.9  774.80  4913.9  772.27
  5000.2  770.32  5001.0  769.52  5009.2  770.32  5035.2  771.71  5045.1  773.63
  5049.7  772.90  5057.1  774.58  5064.1  777.73  5070.5  776.16  5078.5  779.53
  5084.9  777.92  5093.0  781.42  5099.3  780.01  5107.4  782.32  5113.8  781.28
  5128.2  784.12  5163.4  784.39  5192.3  786.58  5299.6  788.78  5589.4  790.16
#Mann=5,-1,0
  4258.0     0.1       0  4719.0    0.05       0  5000.2   0.035       0
  5009.2    0.05       0  5035.2     0.1       0
Bank Sta=5000.2,5009.2
Exp/Cntr=0.3,0.1

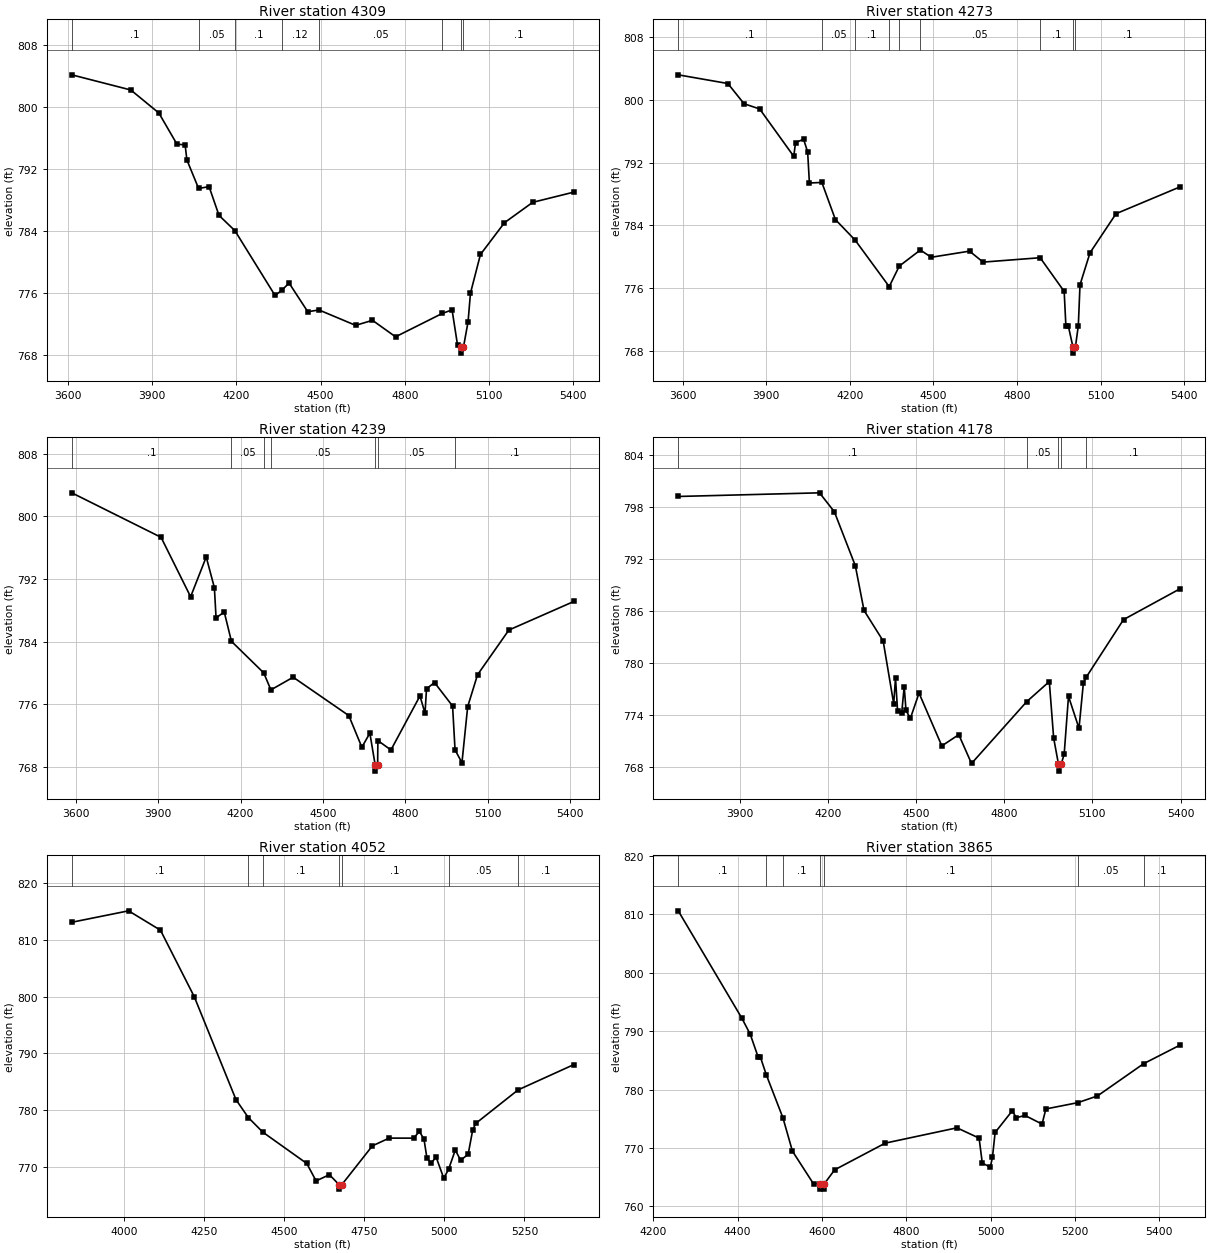
Type RM Length L Ch R = 1,4309,36,36,36
BEGIN DESCRIPTION:
Mapping XS 2475a9c7
END DESCRIPTION:
XS GIS Cut Line= 4
      2003998.73     13647963.79      2003365.86     13648442.78
      2002829.47     13648666.90      2002585.74     13649001.39
#Sta/Elev= 30
  3613.3  804.19  3823.7  802.23  3923.5  799.26  3988.0  795.23  4017.2  795.13
  4023.4  793.20  4065.2  789.50  4102.5  789.74  4137.9  786.02  4194.5  784.05
  4337.6  775.67  4361.4  776.33  4387.5  777.28  4454.2  773.57  4494.0  773.80
  4624.7  771.81  4684.7  772.46  4767.0  770.33  4933.3  773.35  4968.3  773.81
  4988.0  769.21  5000.0  769.02  5000.8  768.22  5009.0  769.02  5025.3  772.27
  5033.8  775.96  5069.4  780.97  5155.1  785.08  5255.6  787.71  5402.2  789.03
#Mann=8,-1,0
  3613.3     0.1       0  4065.2    0.05       0  4194.5     0.1       0
  4361.4    0.12       0  4494.0    0.05       0  4933.3     0.1       0
  5000.0    0.07       0  5009.0     0.1       0
Bank Sta=5000,5009
Exp/Cntr=0.3,0.1

Type RM Length L Ch R = 1,4273,34,34,34
BEGIN DESCRIPTION:
GOOSE CREEK 9.0
END DESCRIPTION:
XS GIS Cut Line= 4
      2003985.70     13647924.74      2003365.93     13648403.88
      2002816.89     13648623.50      2002575.01     13648974.99
#Sta/Elev= 30
  3584.2  803.21  3762.3  802.10  3820.3  799.52  3876.4  798.85  3998.7  792.80
  4005.0  794.55  4034.0  794.99  4048.5  793.36  4054.8  789.40  4099.5  789.47
  4148.1  784.73  4218.8  782.11  4341.2  776.17  4377.2  778.79  4452.7  780.84
  4492.1  779.92  4629.4  780.70  4677.9  779.30  4882.7  779.86  4968.9  775.56
  4975.0  771.19  4983.8  771.14  5000.3  768.48  5001.1  767.68  5009.3  768.48
  5019.7  771.20  5025.7  776.40  5061.6  780.49  5155.0  785.48  5385.6  788.92
#Mann=9,-1,0
  3584.2     0.1       0  4099.5    0.05       0  4218.8     0.1       0
  4341.2    0.05       0  4377.2    0.12       0  4452.7    0.05       0
  4882.7     0.1       0  5000.3    0.07       0  5009.3     0.1       0
Bank Sta=5000.3,5009.3
Exp/Cntr=0.3,0.1

Type RM Length L Ch R = 1,4239,61,61,61
BEGIN DESCRIPTION:
Mapping XS 00010bf0
END DESCRIPTION:
XS GIS Cut Line= 4
      2003985.71     13647914.31      2003273.60     13648404.65
      2002793.02     13648607.01      2002540.39     13648969.02
#Sta/Elev= 30
  3585.4  803.01  3910.4  797.33  4018.0  789.74  4074.8  794.82  4104.5  790.90
  4110.6  787.05  4140.4  787.79  4166.6  784.05  4284.2  780.02  4310.2  777.85
  4391.3  779.47  4593.8  774.57  4641.3  770.53  4670.4  772.33  4689.7  768.28
  4690.5  767.48  4698.7  768.28  4699.6  771.38  4747.1  770.18  4852.8  777.08
  4871.2  774.86  4876.6  777.99  4905.7  778.79  4971.5  775.79  4980.5  770.19
  5005.6  768.55  5026.5  775.71  5062.3  779.78  5176.3  785.49  5412.9  789.14
#Mann=7,-1,0
  3585.4     0.1       0  4166.6    0.05       0  4284.2     0.1       0
  4310.2    0.05       0  4689.7    0.07       0  4698.7    0.05       0
  4980.5     0.1       0
Bank Sta=4689.7,4698.7
Exp/Cntr=0.3,0.1

Type RM Length L Ch R = 1,4178,126,126,126
BEGIN DESCRIPTION:
Mapping XS 97f9b67a
END DESCRIPTION:
XS GIS Cut Line= 2
      2003496.13     13647515.88      2002510.20     13648910.22
#Sta/Elev= 30
  3691.4  799.22  4171.9  799.64  4222.4  797.46  4293.7  791.24  4323.3  786.09
  4388.4  782.57  4424.3  775.33  4430.4  778.32  4437.4  774.53  4451.3  774.22
  4460.0  777.32  4466.1  774.57  4480.9  773.64  4510.4  776.56  4587.9  770.48
  4645.6  771.77  4688.9  768.45  4876.5  775.57  4953.5  777.89  4968.3  771.39
  4984.7  768.37  4985.6  767.57  4993.7  768.37  5004.0  769.50  5018.8  776.19
  5054.5  772.50  5069.3  777.70  5079.8  778.43  5205.9  785.03  5399.1  788.60
#Mann=5,-1,0
  3691.4     0.1       0  4876.5    0.05       0  4984.7    0.04       0
  4993.7    0.05       0  5079.8     0.1       0
Bank Sta=4984.7,4993.7
Exp/Cntr=0.3,0.1

Type RM Length L Ch R = 1,4052,187,187,187
BEGIN DESCRIPTION:
Mapping XS eebe1ad3
END DESCRIPTION:
XS GIS Cut Line= 2
      2003108.12     13647442.94      2002490.93     13648885.66
#Sta/Elev= 30
  3835.3  813.13  4012.8  815.15  4112.5  811.73  4218.2  799.98  4348.7  781.79
  4387.1  778.65  4432.4  776.07  4569.8  770.54  4598.9  767.46  4640.5  768.56
  4670.5  766.81  4671.4  766.01  4679.5  766.81  4774.8  773.65  4827.4  775.02
  4903.6  775.01  4921.8  776.19  4936.1  774.85  4945.4  771.46  4957.8  770.64
  4974.4  771.61  4998.0  767.92  5013.0  769.52  5034.0  772.91  5050.6  771.11
  5074.2  772.16  5088.4  776.47  5097.8  777.61  5230.2  783.53  5404.5  788.00
#Mann=7,-1,0
  3835.3     0.1       0  4387.1    0.16       0  4432.4     0.1       0
  4670.5    0.07       0  4679.5     0.1       0  5013.0    0.05       0
  5230.2     0.1       0
Bank Sta=4670.5,4679.5
Exp/Cntr=0.3,0.1

Type RM Length L Ch R = 1,3865,325,325,325
BEGIN DESCRIPTION:
GOOSE CREEK 8.0
END DESCRIPTION:
XS GIS Cut Line= 3
      2002504.39     13647664.29      2002525.00     13648375.00
      2002452.31     13648849.16
#Sta/Elev= 30
  4259.4  810.59  4410.2  792.23  4430.2  789.46  4449.1  785.53  4454.1  785.60
  4468.6  782.46  4507.7  775.17  4530.2  769.47  4580.2  763.87  4595.7  763.77
  4596.6  762.97  4603.9  762.97  4604.7  763.77  4630.3  766.27  4750.3  770.84
  4920.4  773.46  4972.9  771.70  4980.5  767.42  4999.5  766.73  5004.6  768.43
  5010.9  772.66  5051.3  776.35  5061.5  775.19  5081.7  775.58  5122.2  774.10
  5131.3  776.69  5207.3  777.77  5253.7  778.92  5363.0  784.43  5450.1  787.64
#Mann=7,-1,0
  4259.4     0.1       0  4468.6    0.16       0  4507.7     0.1       0
  4595.7    0.07       0  4604.7     0.1       0  5207.3    0.05       0
  5363.0     0.1       0
Bank Sta=4595.7,4604.7
Exp/Cntr=0.3,0.1