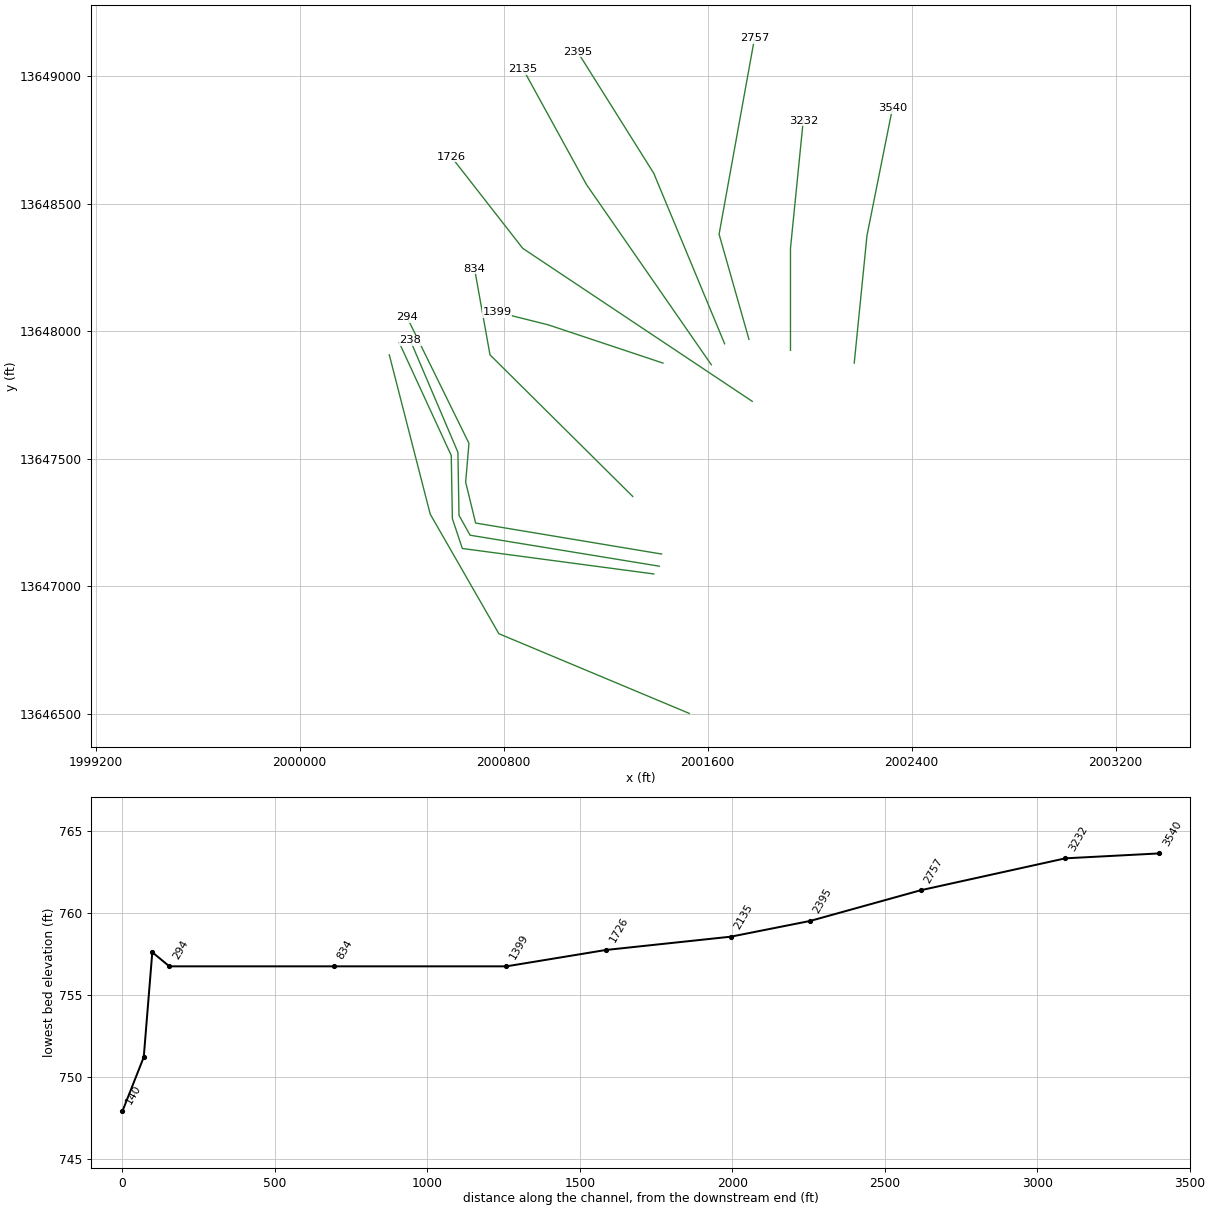
HEC-RAS study GOOSE CREEK.prj: GOOSE CREEK Base Level Engineering

--- GOOSE CREEK.g01 (geometry) --- (continued)

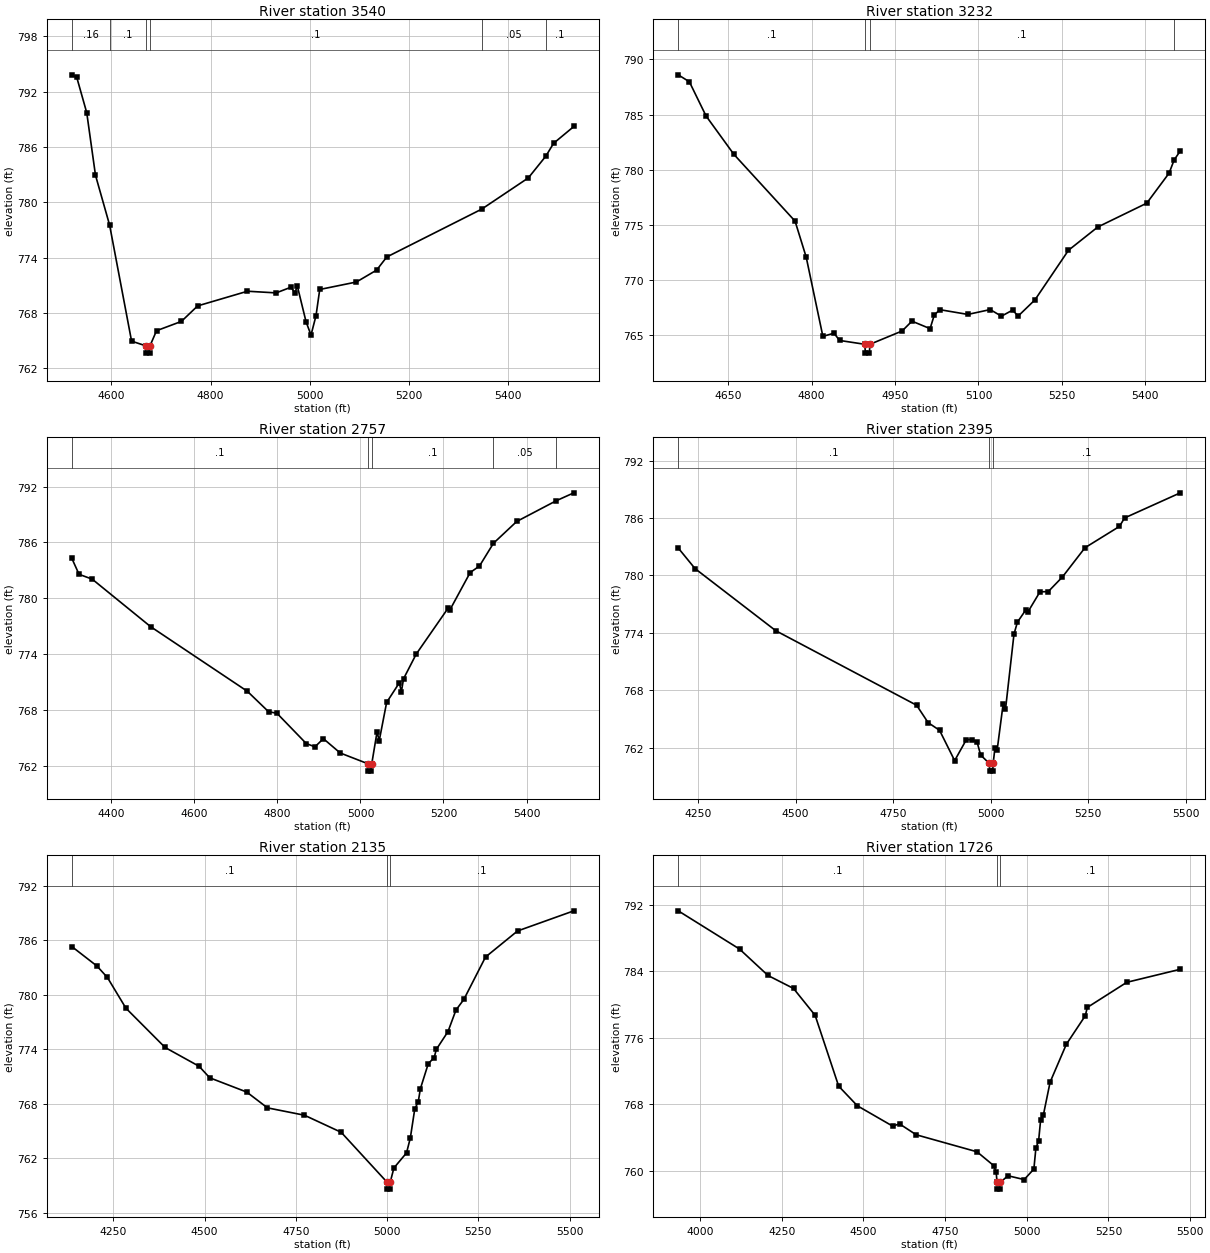
Type RM Length L Ch R = 1,3540,308,308,308
BEGIN DESCRIPTION:
GOOSE CREEK 7.0
END DESCRIPTION:
XS GIS Cut Line= 3
      2002175.00     13647874.96      2002225.00     13648375.00
      2002324.99     13648874.97
#Sta/Elev= 30
  4520.0  793.83  4530.1  793.55  4550.2  789.72  4567.8  782.95  4596.3  777.54
  4640.6  764.96  4668.8  764.46  4669.7  763.66  4677.0  763.66  4677.8  764.46
  4690.9  766.09  4741.1  767.10  4773.8  768.78  4874.3  770.37  4932.1  770.19
  4962.2  770.81  4969.8  770.18  4974.8  770.94  4992.4  767.06  5002.4  765.62
  5012.5  767.72  5020.0  770.56  5093.9  771.37  5134.7  772.66  5155.1  774.08
  5346.6  779.27  5440.7  782.66  5476.0  785.02  5491.6  786.41  5532.4  788.23
#Mann=6,-1,0
  4520.0    0.16       0  4596.3     0.1       0  4668.8    0.07       0
  4677.8     0.1       0  5346.6    0.05       0  5476.0     0.1       0
Bank Sta=4668.8,4677.8
Exp/Cntr=0.3,0.1

Type RM Length L Ch R = 1,3232,475,475,475
BEGIN DESCRIPTION:
GOOSE CREEK 6.0
END DESCRIPTION:
XS GIS Cut Line= 3
      2001925.00     13647925.03      2001925.00     13648325.00
      2001975.00     13648825.04
#Sta/Elev= 30
  4560.3  788.60  4580.3  787.97  4610.3  784.87  4660.3  781.39  4770.3  775.33
  4790.3  772.07  4820.3  764.88  4840.3  765.17  4850.3  764.51  4895.8  764.16
  4896.6  763.36  4903.9  763.36  4904.8  764.16  4962.8  765.37  4980.4  766.26
  5013.0  765.58  5020.6  766.82  5030.6  767.30  5080.9  766.87  5121.1  767.31
  5141.2  766.71  5161.3  767.26  5171.3  766.72  5201.5  768.19  5261.8  772.69
  5314.5  774.80  5402.5  776.96  5442.7  779.69  5451.7  780.88  5462.8  781.70
#Mann=4,-1,0
  4560.3     0.1       0  4895.8    0.07       0  4904.8     0.1       0
  5451.7    0.05       0
Bank Sta=4895.8,4904.8
Exp/Cntr=0.3,0.1

Type RM Length L Ch R = 1,2757,362,362,362
BEGIN DESCRIPTION:
Mapping XS f9dd6a5f
END DESCRIPTION:
XS GIS Cut Line= 3
      2001762.19     13647968.16      2001645.01     13648380.44
      2001783.90     13649148.68
#Sta/Elev= 30
  4304.7  784.30  4322.2  782.57  4353.9  782.05  4494.7  776.94  4727.7  769.99
  4778.6  767.80  4798.9  767.63  4869.4  764.38  4890.4  764.02  4910.7  764.90
  4951.3  763.36  5017.6  762.21  5018.6  761.41  5026.4  761.41  5027.3  762.21
  5040.1  765.66  5045.1  764.65  5063.1  768.80  5093.6  770.90  5098.6  769.95
  5103.8  771.34  5134.3  773.99  5210.8  778.91  5215.8  778.77  5264.3  782.76
  5286.7  783.46  5320.4  785.91  5376.4  788.25  5471.2  790.47  5514.0  791.33
#Mann=5,-1,0
  4304.7     0.1       0  5017.6    0.07       0  5027.3     0.1       0
  5320.4    0.05       0  5471.2     0.1       0
Bank Sta=5017.6,5027.3
Exp/Cntr=0.3,0.1

Type RM Length L Ch R = 1,2395,260,260,260
BEGIN DESCRIPTION:
GOOSE CREEK 5.0
END DESCRIPTION:
XS GIS Cut Line= 3
      2001666.71     13647950.76      2001388.94     13648619.16
      2001089.73     13649096.16
#Sta/Elev= 30
  4199.0  782.87  4242.0  780.72  4449.1  774.22  4810.0  766.43  4839.5  764.61
  4868.8  763.81  4907.5  760.64  4937.6  762.84  4952.9  762.83  4965.1  762.56
  4974.2  761.22  4996.4  760.34  4997.3  759.54  5005.2  759.54  5006.2  760.34
  5010.7  761.95  5016.6  761.80  5031.9  766.60  5037.8  765.99  5059.6  773.87
  5068.4  775.12  5089.6  776.38  5095.5  776.20  5126.2  778.29  5147.4  778.31
  5183.9  779.85  5241.6  782.90  5330.0  785.13  5342.9  786.01  5485.9  788.64
#Mann=3,-1,0
  4199.0     0.1       0  4996.4    0.07       0  5006.2     0.1       0
Bank Sta=4996.4,5006.2
Exp/Cntr=0.3,0.1

Type RM Length L Ch R = 1,2135,409,409,409
BEGIN DESCRIPTION:
GOOSE CREEK 4.0
END DESCRIPTION:
XS GIS Cut Line= 3
      2001614.61     13647868.32      2001125.00     13648575.00
      2000876.79     13649027.13
#Sta/Elev= 30
  4136.3  785.30  4205.3  783.15  4233.9  781.89  4284.6  778.51  4392.0  774.18
  4485.1  772.11  4514.3  770.84  4615.7  769.27  4672.4  767.53  4773.7  766.72
  4874.4  764.84  4999.2  759.38  5000.1  758.58  5008.0  758.58  5009.0  759.38
  5018.8  760.91  5053.4  762.57  5063.8  764.21  5075.9  767.39  5085.6  768.21
  5091.3  769.63  5113.1  772.41  5129.2  773.06  5134.9  773.96  5167.0  775.93
  5188.8  778.30  5210.6  779.48  5269.8  784.14  5357.5  787.01  5511.8  789.23
#Mann=3,-1,0
  4136.3     0.1       0  4999.2    0.07       0  5009.0     0.1       0
Bank Sta=4999.2,5009
Exp/Cntr=0.3,0.1

Type RM Length L Ch R = 1,1726,327,327,327
BEGIN DESCRIPTION:
GOOSE CREEK 3.0
END DESCRIPTION:
XS GIS Cut Line= 3
      2001774.96     13647725.02      2000875.00     13648325.00
      2000594.68     13648684.25
#Sta/Elev= 30
  3932.8  791.25  4120.5  786.65  4207.7  783.47  4285.8  781.91  4351.9  778.68
  4424.0  770.16  4481.1  767.80  4589.3  765.35  4610.3  765.62  4661.4  764.31
  4847.7  762.26  4898.7  760.60  4906.3  759.82  4908.9  758.57  4909.8  757.77
  4917.7  757.77  4918.7  758.57  4942.3  759.38  4991.9  758.92  5021.7  760.18
  5028.0  762.75  5036.1  763.52  5042.5  766.13  5050.6  766.65  5071.4  770.64
  5121.2  775.20  5179.0  778.62  5185.4  779.63  5306.2  782.65  5470.1  784.22
#Mann=3,-1,0
  3932.8     0.1       0  4908.9    0.07       0  4918.7     0.1       0
Bank Sta=4908.9,4918.7
Exp/Cntr=0.3,0.1

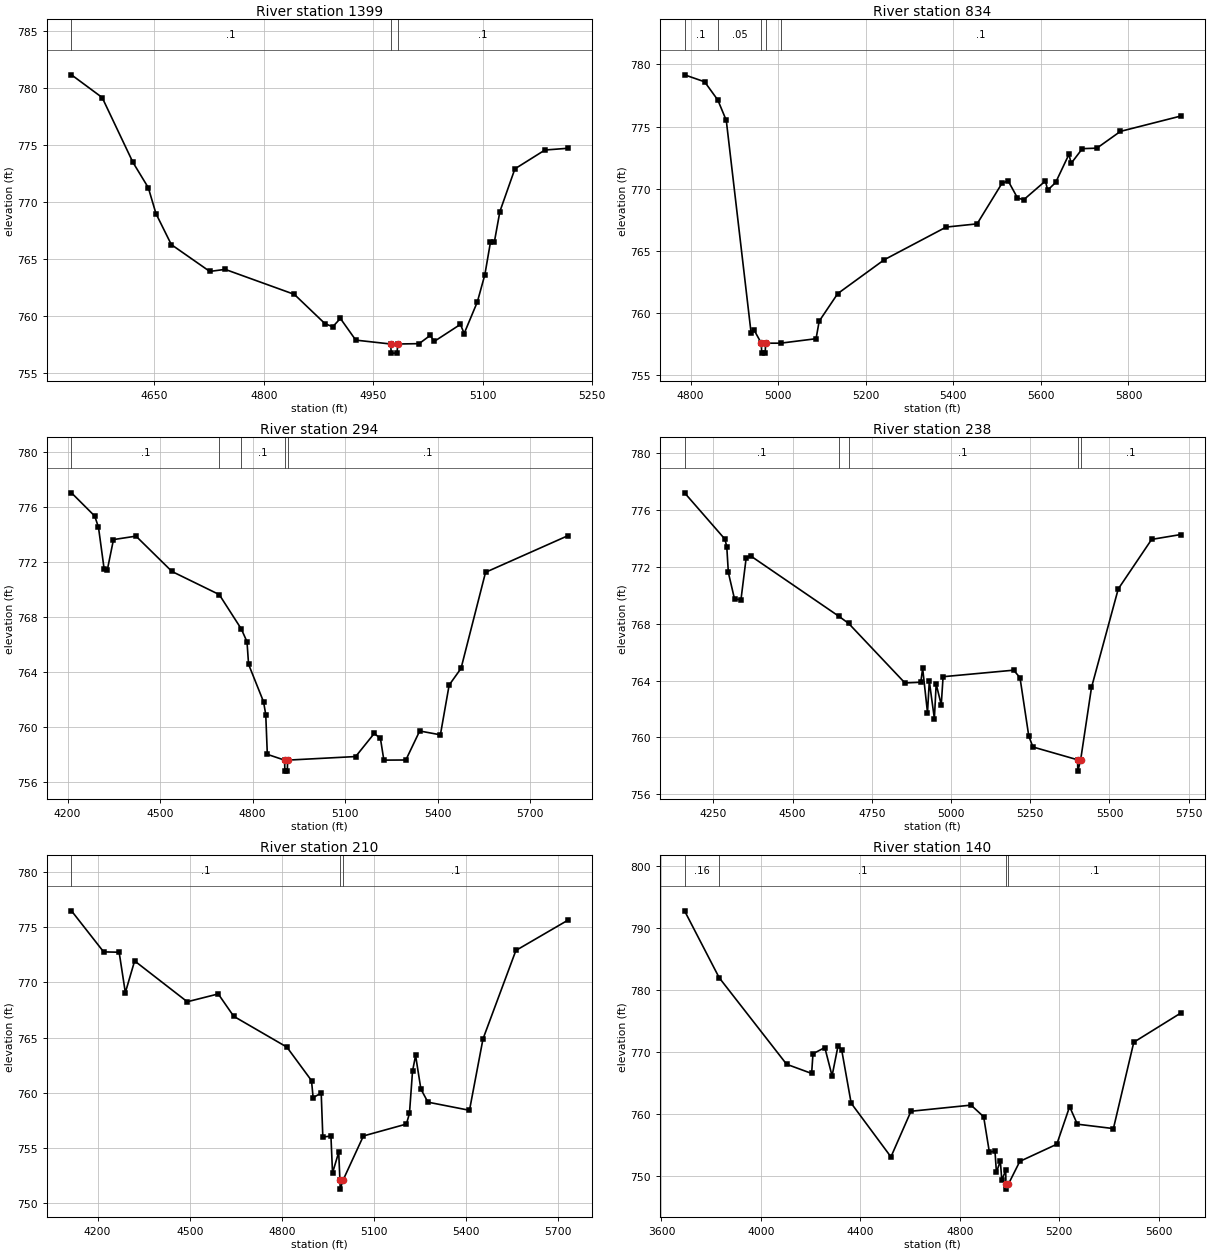
Type RM Length L Ch R = 1,1399,565,565,565
BEGIN DESCRIPTION:
GOOSE CREEK 2.0
END DESCRIPTION:
XS GIS Cut Line= 3
      2001424.97     13647875.01      2000975.00     13648025.00
      2000774.96     13648075.01
#Sta/Elev= 30
  4536.1  781.16  4578.2  779.17  4620.4  773.49  4641.5  771.27  4652.0  769.00
  4673.1  766.28  4725.8  763.93  4746.9  764.11  4841.8  761.92  4883.9  759.35
  4894.5  759.08  4905.0  759.81  4926.1  757.91  4973.9  757.57  4974.8  756.77
  4982.7  756.77  4983.7  757.57  5013.0  757.60  5028.4  758.33  5033.6  757.79
  5069.7  759.29  5074.8  758.49  5092.9  761.26  5103.2  763.65  5110.9  766.50
  5116.1  766.47  5123.8  769.18  5144.4  772.92  5185.6  774.57  5216.6  774.72
#Mann=3,-1,0
  4536.1     0.1       0  4973.9    0.07       0  4983.7     0.1       0
Bank Sta=4973.9,4983.7
Exp/Cntr=0.3,0.1

Type RM Length L Ch R = 1,834,540,540,540
BEGIN DESCRIPTION:
Mapping XS 2ca070a1
END DESCRIPTION:
XS GIS Cut Line= 3
      2001306.50     13647351.77      2000746.57     13647907.35
      2000685.82     13648245.85
#Sta/Elev= 30
  4786.4  779.16  4832.2  778.60  4862.4  777.13  4881.7  775.49  4938.3  758.41
  4945.3  758.62  4961.6  757.57  4962.6  756.77  4970.5  756.77  4971.5  757.57
  5005.5  757.57  5086.7  757.93  5093.8  759.34  5136.2  761.56  5242.3  764.28
  5383.7  766.91  5454.4  767.17  5511.0  770.42  5525.1  770.64  5546.4  769.27
  5560.5  769.10  5610.4  770.62  5615.5  769.88  5633.8  770.50  5664.1  772.76
  5669.2  772.04  5694.7  773.22  5727.9  773.26  5781.7  774.61  5919.1  775.84
#Mann=5,-1,0
  4786.4     0.1       0  4862.4    0.05       0  4961.6   0.033       0
  4971.5    0.05       0  5005.5     0.1       0
Bank Sta=4961.6,4971.5
Exp/Cntr=0.3,0.1

Type RM Length L Ch R = 1,294,56,56,56
BEGIN DESCRIPTION:
Mapping XS 80cceea8
END DESCRIPTION:
XS GIS Cut Line= 5
      2001419.34     13647126.10      2000690.15     13647247.63
      2000651.09     13647408.22      2000664.11     13647560.13
      2000421.04     13648054.96
#Sta/Elev= 30
  4212.7  777.01  4288.1  775.32  4300.3  774.50  4318.5  771.49  4328.6  771.37
  4348.9  773.61  4421.9  773.86  4538.5  771.29  4691.8  769.61  4763.3  767.11
  4781.8  766.18  4786.9  764.54  4835.5  761.81  4842.6  760.88  4847.7  757.99
  4903.6  757.57  4904.6  756.77  4912.5  756.77  4913.5  757.57  5134.1  757.83
  5194.3  759.51  5214.4  759.15  5225.5  757.57  5296.8  757.58  5341.7  759.69
  5408.8  759.41  5437.2  763.03  5475.7  764.24  5555.2  771.23  5821.0  773.88
#Mann=5,-1,0
  4212.7     0.1       0  4691.8    0.05       0  4763.3     0.1       0
  4903.6    0.07       0  4913.5     0.1       0
Bank Sta=4903.6,4913.5
Exp/Cntr=0.3,0.1

Type RM Length L Ch R = 1,238,28,28,28
BEGIN DESCRIPTION:
Mapping XS 6e9f4682
END DESCRIPTION:
XS GIS Cut Line= 5
      2001410.64     13647078.36      2000668.45     13647199.89
      2000625.05     13647278.01      2000620.71     13647525.41
      2000434.09     13647963.75
#Sta/Elev= 30
  4159.2  777.23  4286.5  773.97  4292.4  773.44  4297.4  771.62  4316.9  769.75
  4337.2  769.70  4353.7  772.66  4367.6  772.79  4646.5  768.53  4677.1  768.03
  4854.6  763.84  4904.6  763.89  4910.5  764.87  4925.8  761.75  4931.5  763.96
  4947.5  761.33  4953.2  763.76  4969.2  762.30  4975.0  764.28  5197.7  764.74
  5217.7  764.21  5245.4  760.10  5258.5  759.33  5399.2  758.43  5400.2  757.63
  5409.1  758.43  5443.3  763.52  5527.7  770.46  5633.1  773.95  5724.5  774.29
#Mann=5,-1,0
  4159.2     0.1       0  4646.5    0.05       0  4677.1     0.1       0
  5399.2    0.07       0  5409.1     0.1       0
Bank Sta=5399.2,5409.1
Exp/Cntr=0.3,0.1

Type RM Length L Ch R = 1,210,70,70,70
BEGIN DESCRIPTION:
Mapping XS 7379eb41
END DESCRIPTION:
XS GIS Cut Line= 5
      2001388.93     13647047.98      2000638.07     13647147.80
      2000599.00     13647264.99      2000594.66     13647512.39
      2000390.66     13647955.12
#Sta/Elev= 30
  4114.9  776.51  4219.7  772.78  4270.2  772.75  4290.4  769.08  4320.6  771.96
  4492.1  768.25  4593.0  768.96  4643.4  766.93  4816.6  764.13  4896.8  761.09
  4902.1  759.54  4928.4  759.96  4933.7  755.96  4960.1  756.05  4965.3  752.70
  4985.4  754.58  4989.4  752.03  4990.4  751.23  4999.3  752.03  5065.9  756.06
  5205.9  757.14  5215.9  758.11  5225.9  761.95  5235.9  763.37  5253.1  760.32
  5276.0  759.13  5411.4  758.39  5455.4  764.87  5562.6  772.91  5730.8  775.64
#Mann=3,-1,0
  4114.9     0.1       0  4989.4    0.07       0  4999.3     0.1       0
Bank Sta=4989.4,4999.3
Exp/Cntr=0.3,0.1

Type RM Length L Ch R = 1,140,0,0,0
BEGIN DESCRIPTION:
GOOSE CREEK 1.0
END DESCRIPTION:
XS GIS Cut Line= 4
      2001527.81     13646501.11      2000781.30     13646813.60
      2000512.20     13647282.35      2000351.61     13647907.37
#Sta/Elev= 30
  3692.9  792.75  3832.3  781.97  4103.4  768.04  4204.0  766.56  4209.4  769.73
  4257.0  770.73  4286.2  766.17  4310.0  770.96  4324.7  770.39  4363.0  761.77
  4523.0  753.12  4603.5  760.47  4845.1  761.46  4895.8  759.59  4918.9  753.87
  4941.4  754.06  4947.2  750.65  4963.0  752.46  4968.8  749.38  4984.6  750.96
  4985.4  748.73  4986.4  747.93  4995.3  748.73  5041.3  752.40  5190.0  755.16
  5241.6  761.21  5272.6  758.39  5417.7  757.68  5499.7  771.59  5688.0  776.27
#Mann=4,-1,0
  3692.9    0.16       0  3832.3     0.1       0  4985.4    0.07       0
  4995.3     0.1       0
Bank Sta=4985.4,4995.3
Exp/Cntr=0.3,0.1

Chan Stop Cuts=-1