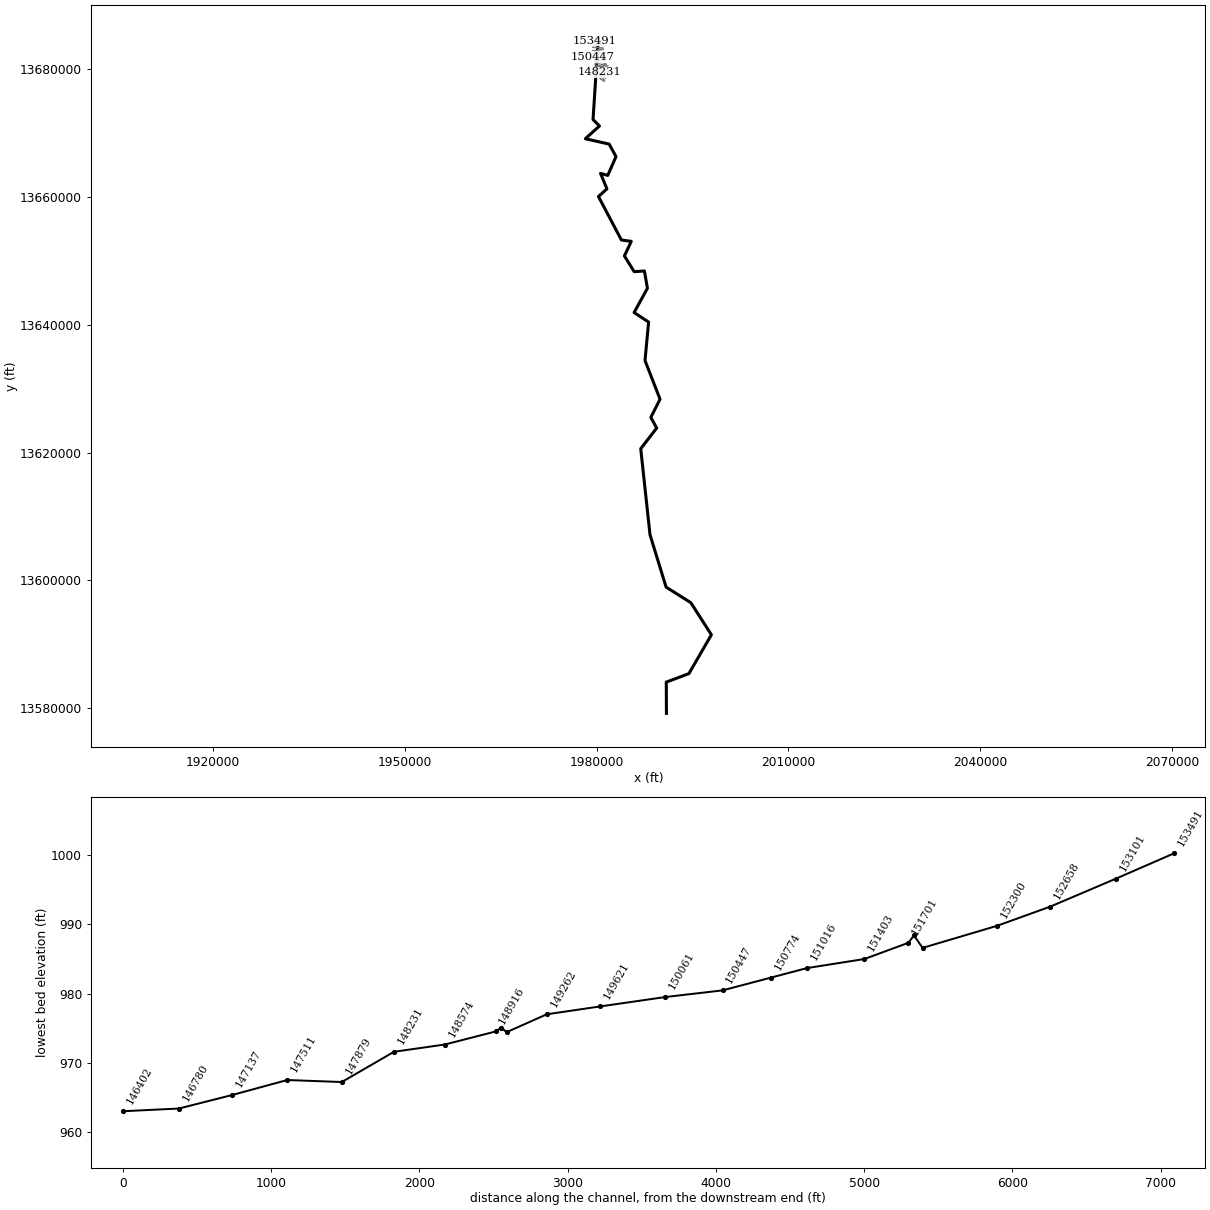
--- SF PEREZ CREEK.prj (project) ---

Proj Title=SF PEREZ CREEK Base Level Engineering
Current Plan=p02
Default Exp/Contr=0.3,0.1
English Units
Geom File=g01
Flow File=f01
Plan File=p02
Y Axis Title=Elevation
X Axis Title(PF)=Main Channel Distance
X Axis Title(XS)=Station
BEGIN DESCRIPTION:
SF PEREZ CREEK
END DESCRIPTION:
DSS Export Rating Curves= 0
DSS Export Rating Curve Sorted= 0
DSS Export Volume Flow Curves= 0
DXF OffsetX= 0
DXF OffsetY= 0
DXF ScaleX= 1
DXF ScaleY= 10

--- SF PEREZ CREEK.p02 (plan) ---

Plan Title=Multiple Run
Program Version=5.05
Short Identifier=Multiple Run
Geom File=g01
Flow File=f01
Subcritical Flow
K Sum by GR= 0
Std Step Tol= 0.01
Critical Tol= 0.01
Num of Std Step Trials= 20
Max Error Tol= 0.3
Flow Tol Ratio= 0.001
Split Flow NTrial= 30
Split Flow Tol= 0.02
Split Flow Ratio= 0.02
Log Output Level= 0
Friction Slope Method= 1
Unsteady Friction Slope Method= 2
Unsteady Bridges Friction Slope Method= 1
Parabolic Critical Depth
Global Vel Dist= 1 , 1 , 1
Global Log Level= 0
CheckData=True
Encroach Param=-1 ,0,0, 0
BEGIN DESCRIPTION:
Multiple Run
END DESCRIPTION:
Computation Interval=1MIN
Output Interval=1HOUR
Instantaneous Interval=1HOUR
Mapping Interval=1HOUR
Computation Time Step Use Courant=        0
Computation Time Step Use Time Series=    0
Computation Time Step Count To Double=0
Computation Time Step Max Doubling=0
Computation Time Step Max Halving=0
Computation Time Step Residence Courant=0
Run HTab= 0
Run UNet= 0
Run Sediment= 0
Run PostProcess= 0
Run WQNet= 0
Run RASMapper= 0
UNET Theta= 1
UNET Theta Warmup= 1
UNET ZTol= 0.02
UNET ZSATol= 0.02
UNET MxIter= 20
UNET Max Iter WO Improvement= 0
UNET MaxInSteps= 0
UNET DtIC= 0
UNET DtMin= 0
UNET MaxCRTS= 20
UNET WFStab= 2
UNET SFStab= 1
UNET WFX= 1
UNET SFX= 1
UNET 1D Methodology=Finite Difference
UNET DSS MLevel= 4
UNET Pardiso=0
UNET DZMax Abort= 100
UNET Use Existing IB Tables=-1
UNET Froude Reduction=False
UNET Froude Limit= 0.8
UNET Froude Power= 4
UNET D1 Cores= 0
UNET D2 Coriolis=0
UNET D2 Cores= 0
UNET D2 Theta= 1
UNET D2 Theta Warmup= 1
UNET D2 Z Tol= 0.01
UNET D2 Volume Tol= 0.01
UNET D2 Max Iterations= 20
UNET D2 Equation= 0
UNET D2 RampUpFraction=0.1
UNET D2 TimeSlices= 1
UNET D2 BCVolumeCheck=0
UNET D1D2 MaxIter= 0
UNET D1D2 ZTol=0.01
UNET D1D2 QTol=0.1
UNET D1D2 MinQTol=1
Write IC File= 0
Write IC File at Fixed DateTime=0
Write IC File at Sim End=0
Echo Input=False
Echo Parameters=False
Echo Output=False
Write Detailed= 0
HDF Write Warmup=0
HDF Write Time Slices=0
HDF Flush=0
HDF Face Node Velocities=0
HDF Compression= 1
HDF Chunk Size= 1
HDF Spatial Parts= 1
HDF Use Max Rows=0
HDF Fixed Rows= 1
Calibration Method= 0
Calibration Iterations= 20
Calibration Max Change=0.05
Calibration Tolerance=0.2
Calibration Maximum=1.5
Calibration Minimum=0.5
Calibration Optimization Method= 1
WQ AD Non Conservative
WQ ULTIMATE=-1
WQ Max Comp Step=1HOUR
WQ Output Interval=15MIN
WQ Output Selected Increments= 0
WQ Output face flow=0
WQ Output face velocity=0
WQ Output face area=0
WQ Output face dispersion=0
WQ Output cell volume=0
WQ Output cell surface area=0
WQ Output cell continuity=0
WQ Output cumulative cell continuity=0
WQ Output face conc=0
WQ Output face dconc_dx=0
WQ Output face courant=0
WQ Output face peclet=0
WQ Output face adv mass=0
WQ Output face disp mass=0
WQ Output cell mass=0
WQ Output cell source sink temp=0
WQ Output nsm pathways=0
WQ Output nsm derived pathways=0
WQ Output MaxMinRange=-1
WQ Daily Max Min Mean=-1
WQ Daily Range=0
WQ Daily Time=0
WQ Create Restart=0
WQ Fixed Restart=0
WQ System Summary=0
WQ Write To DSS=0
WQ Use Fixed Temperature=0
Sorting and Armoring Iterations= 10
XS Update Threshold= 0.02
Bed Roughness Predictor= 0
Hydraulics Update Threshold= 0.02
Energy Slope Method= 1
Volume Change Method= 1
Sediment Retention Method= 0
XS Weighting Method= 0
Number of US Weighted Cross Sections= 1
Number of DS Weighted Cross Sections= 1
Upstream XS Weight=0
Main XS Weight=1
Downstream XS Weight=0
Number of DS XS's Weighted with US Boundary= 1
Upstream Boundary Weight= 1
Weight of XSs Associated with US Boundary= 0
Number of US XS's Weighted with DS Boundary= 1
Downstream Boundary Weight= 0.5
Weight of XSs Associated with DS Boundary= 0.5
Percentile Method= 0
Sediment Output Level= 3
Mass or Volume Output= 0
Output Increment Type= 1
Profile and TS Output Increment= 1
XS Output Flag= 0
XS Output Increment= 10
Write Gradation File= 0
Read Gradation Hotstart= 0
Write HDF5 File= 1
Write Binary Output= 1
Write DSS Sediment File= 0
SV Curve= 0
Specific Gage Flag= 0

--- SF PEREZ CREEK.f01 (steady flow) ---

Flow Title=Multiple
Program Version=5.05
Number of Profiles= 7
Profile Names=10-year,25-year,50-year,1pct_min,100-year,1pct_plu,500-year
River Rch & RM=SF PEREZ CREEK,Reach-1         ,153491
     415     560     675     403     804    1604    1143
River Rch & RM=SF PEREZ CREEK,Reach-1         ,152658
     799    1121    1389     851    1697    3387    2543
River Rch & RM=SF PEREZ CREEK,Reach-1         ,143592
     934    1325    1653    1019    2032    4055    3084
River Rch & RM=SF PEREZ CREEK,Reach-1         ,137858
    1797    2621    3331    2086    4163    8306    6529
River Rch & RM=SF PEREZ CREEK,Reach-1         ,131850
    1931    2824    3596    2256    4500    8980    7081
River Rch & RM=SF PEREZ CREEK,Reach-1         ,126274
    2136    3135    4001    2514    5016   10009    7922
River Rch & RM=SF PEREZ CREEK,Reach-1         ,119980
    2233    3280    4189    2634    5255   10484    8306
River Rch & RM=SF PEREZ CREEK,Reach-1         ,114515
    2680    3968    5094    3219    6422   12814   10254
River Rch & RM=SF PEREZ CREEK,Reach-1         ,112367
    2861    4244    5456    3451    6886   13739   11017
River Rch & RM=SF PEREZ CREEK,Reach-1         ,110956
    2861    4244    5456    3451    6886   13739   11017
River Rch & RM=SF PEREZ CREEK,Reach-1         ,107625
    2995    4446    5719    3619    7220   14406   11562
River Rch & RM=SF PEREZ CREEK,Reach-1         ,107133
    3266    4866    6276    3981    7943   15848   12780
River Rch & RM=SF PEREZ CREEK,Reach-1         ,103727
    3266    4866    6276    3981    7943   15848   12780
River Rch & RM=SF PEREZ CREEK,Reach-1         ,102762
    3345    4986    6431    4080    8141   16243   13101
River Rch & RM=SF PEREZ CREEK,Reach-1         ,97230
    3527    5268    6804    4322    8624   17207   13916
River Rch & RM=SF PEREZ CREEK,Reach-1         ,96568
    3527    5268    6804    4322    8624   17207   13916
River Rch & RM=SF PEREZ CREEK,Reach-1         ,94777
    3633    5432    7023    4465    8908   17774   14396
River Rch & RM=SF PEREZ CREEK,Reach-1         ,93630
    3725    5572    7204    4580    9139   18235   14771
River Rch & RM=SF PEREZ CREEK,Reach-1         ,90209
    3974    5954    7707    4905    9787   19527   15849
River Rch & RM=SF PEREZ CREEK,Reach-1         ,83408
    4056    6080    7872    5012    9999   19952   16202
River Rch & RM=SF PEREZ CREEK,Reach-1         ,80820
    4293    6448    8361    5330   10635   21219   17277
River Rch & RM=SF PEREZ CREEK,Reach-1         ,78804
    4410    6630    8602    5487   10947   21842   17803
River Rch & RM=SF PEREZ CREEK,Reach-1         ,76313
    4533    6822    8857    5652   11278   22502   18363
River Rch & RM=SF PEREZ CREEK,Reach-1         ,74219
    4533    6822    8857    5652   11278   22502   18363
River Rch & RM=SF PEREZ CREEK,Reach-1         ,73125
    4548    6840    8877    5662   11298   22542   18377
River Rch & RM=SF PEREZ CREEK,Reach-1         ,71194
    4730    7114    9233    5889   11749   23443   19108
River Rch & RM=SF PEREZ CREEK,Reach-1         ,69865
    4730    7114    9233    5889   11749   23443   19108
River Rch & RM=SF PEREZ CREEK,Reach-1         ,68420
    4943    7456    9696    6197   12364   24669   20188
River Rch & RM=SF PEREZ CREEK,Reach-1         ,62102
    4943    7456    9696    6197   12364   24669   20188
River Rch & RM=SF PEREZ CREEK,Reach-1         ,60252
    5171    7804   10153    6490   12950   25839   21155
River Rch & RM=SF PEREZ CREEK,Reach-1         ,58693
    5268    7963   10372    6638   13245   26426   21687
River Rch & RM=SF PEREZ CREEK,Reach-1         ,57031
    5400    8163   10632    6803   13575   27085   22221
River Rch & RM=SF PEREZ CREEK,Reach-1         ,54363
    5571    8425   10975    7024   14016   27965   22951
River Rch & RM=SF PEREZ CREEK,Reach-1         ,49868
    5793    8768   11428    7318   14601   29132   23929
River Rch & RM=SF PEREZ CREEK,Reach-1         ,48544
    5793    8768   11428    7318   14601   29132   23929
River Rch & RM=SF PEREZ CREEK,Reach-1         ,41065
    5999    9083   11842    7584   15132   30191   24806
River Rch & RM=SF PEREZ CREEK,Reach-1         ,33212
    6339    9615   12553    8049   16059   32042   26390
River Rch & RM=SF PEREZ CREEK,Reach-1         ,29439
    6355    9629   12561    8048   16057   32038   26343
River Rch & RM=SF PEREZ CREEK,Reach-1         ,25780
    6515    9875   12884    8256   16473   32867   27032
River Rch & RM=SF PEREZ CREEK,Reach-1         ,25277
    7257   11035   14432    9267   18490   36893   30471
River Rch & RM=SF PEREZ CREEK,Reach-1         ,23716
    7257   11035   14432    9267   18490   36893   30471
River Rch & RM=SF PEREZ CREEK,Reach-1         ,18945
    7257   11035   14432    9267   18490   36893   30471
River Rch & RM=SF PEREZ CREEK,Reach-1         ,17451
    7207   10943   14298    9172   18301   36516   30100
River Rch & RM=SF PEREZ CREEK,Reach-1         ,15001
    7445   11321   14804    9505   18966   37841   31246
River Rch & RM=SF PEREZ CREEK,Reach-1         ,8501
    7373   11196   14627    9382   18720   37351   30781
River Rch & RM=SF PEREZ CREEK,Reach-1         ,6184
    7475   11358   14845    9526   19006   37922   31276
River Rch & RM=SF PEREZ CREEK,Reach-1         ,2132
    7475   11358   14845    9526   19006   37922   31276
Boundary for River Rch & Prof#=SF PEREZ CREEK,Reach-1         , 1
Up Type= 0
Dn Type= 3
Dn Slope=0.00125
Boundary for River Rch & Prof#=SF PEREZ CREEK,Reach-1         , 2
Up Type= 0
Dn Type= 3
Dn Slope=0.00125
Boundary for River Rch & Prof#=SF PEREZ CREEK,Reach-1         , 3
Up Type= 0
Dn Type= 3
Dn Slope=0.00125
Boundary for River Rch & Prof#=SF PEREZ CREEK,Reach-1         , 4
Up Type= 0
Dn Type= 3
Dn Slope=0.00125
Boundary for River Rch & Prof#=SF PEREZ CREEK,Reach-1         , 5
Up Type= 0
Dn Type= 3
Dn Slope=0.00125
Boundary for River Rch & Prof#=SF PEREZ CREEK,Reach-1         , 6
Up Type= 0
Dn Type= 3
Dn Slope=0.00125
Boundary for River Rch & Prof#=SF PEREZ CREEK,Reach-1         , 7
Up Type= 0
Dn Type= 3
Dn Slope=0.00125
DSS Import GetInterval= 0
DSS Import GetPeak= 0
DSS Import FillOption= 0

--- SF PEREZ CREEK.g01 (geometry) ---

Geom Title=Existing Conditions
Program Version=5.05

River Reach=SF PEREZ CREEK  ,Reach-1
Reach XY= 30
       1980270.8     13684874.54      1979451.66     13672161.61
      1980457.75     13671146.36      1978245.29       13669152.
       1981970.8     13668314.54      1983047.04     13666358.43
       1981750.8     13663404.54      1980621.07     13663735.58
      1981624.21     13661305.43       1980300.8     13660100.03
      1983888.35     13653293.65       1985430.8     13653084.54
       1984360.8     13650804.54      1985887.16     13648332.66
      1987483.69     13648443.46       1987960.8     13645734.54
       1985870.8     13641934.54      1988142.95     13640446.82
       1987580.8     13634414.54       1989930.8     13628364.54
       1988490.8     13625514.54      1989408.32      13623848.4
       1986910.8     13620614.54       1988360.8     13607144.54
       1990880.8     13598934.54       1994740.8     13596504.54
       1997960.8     13591474.54       1994450.8     13585394.54
        1990907.     13584061.11       1990930.8     13579164.54

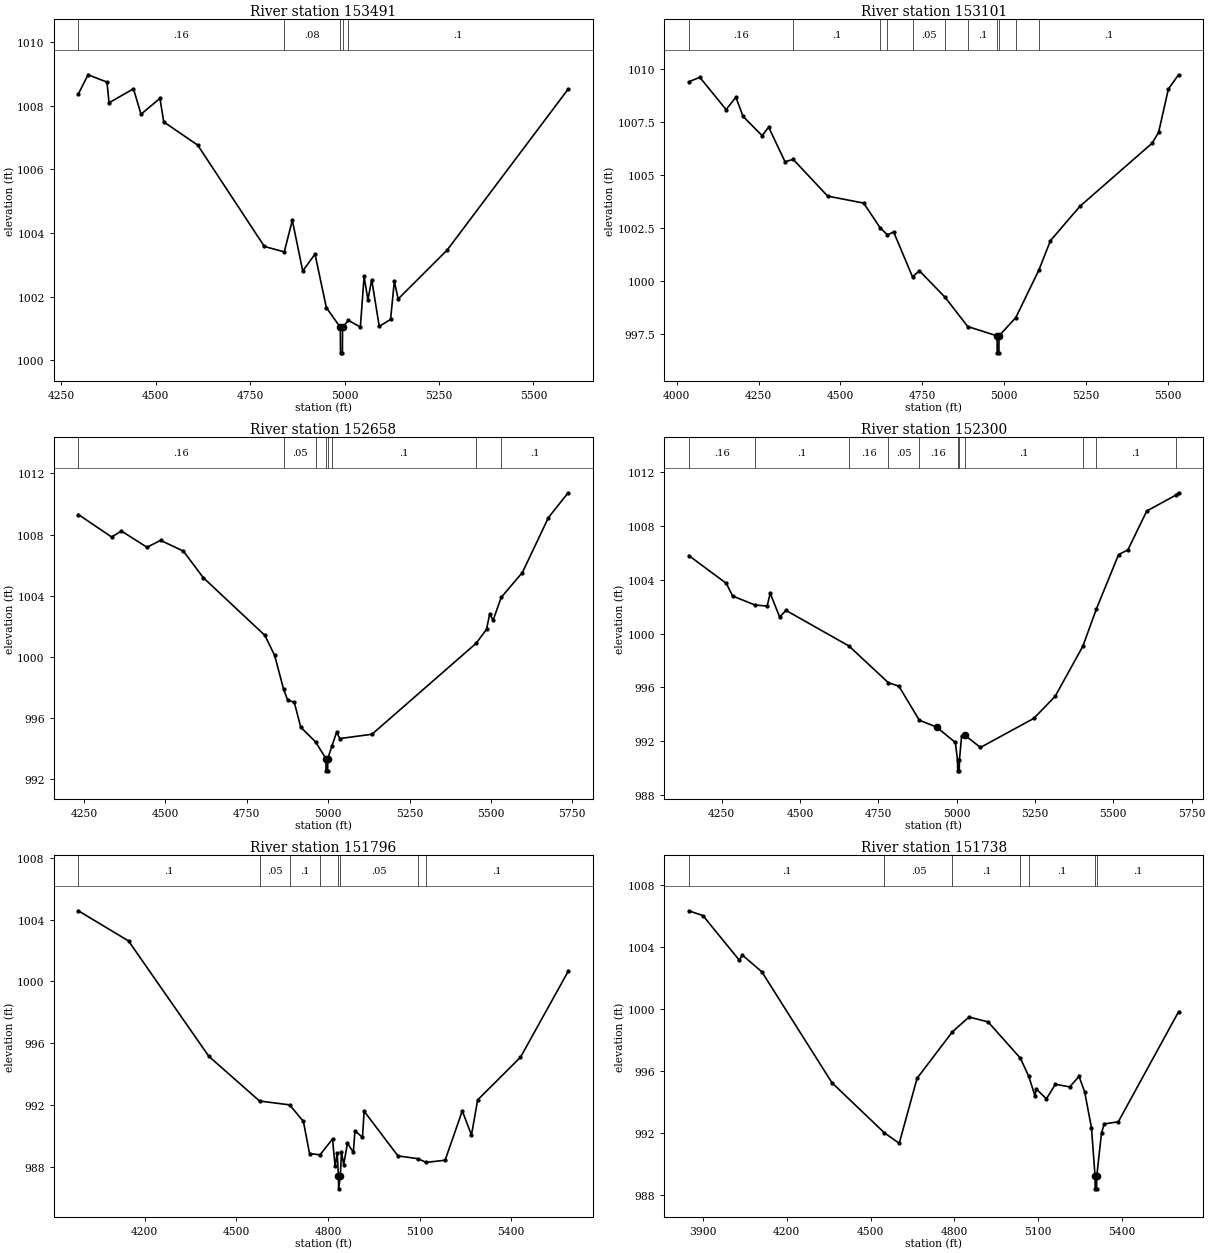
Type RM Length L Ch R = 1 ,153491  ,390,390,390
BEGIN DESCRIPTION:
SF PEREZ CREEK 215.0
END DESCRIPTION:
XS GIS Cut Line= 3
      1980920.71     13684503.96        1980325.       13684475.
      1979625.01       13684475.
#Sta/Elev= 30
  4295.4 1008.37  4321.1 1008.97  4371.2 1008.74  4376.6 1008.09  4441.3 1008.53
  4461.3 1007.73  4511.4 1008.23  4521.4 1007.49  4611.5 1006.76  4787.8 1003.58
  4840.4 1003.41  4861.8  1004.4  4889.3 1002.81  4921.8 1003.34  4951.8 1001.66
  4988.8 1001.04  4989.3 1000.24  4994.3 1000.24  4994.8 1001.04  5010.1 1001.26
  5041.8 1001.05  5051.8 1002.64  5061.8  1001.9  5071.8 1002.54  5091.8 1001.07
  5121.8 1001.29  5131.8 1002.49  5141.8 1001.93  5271.8 1003.47  5591.8 1008.52
#Mann= 5 ,-1 , 0
  4295.4     .16       0  4840.4     .08       0  4988.8     .07       0
  4994.8     .08       0  5010.1      .1       0
Bank Sta=4988.8,4994.8
XS Rating Curve= 0 ,0
Exp/Cntr=0.3,0.1

Type RM Length L Ch R = 1 ,153101  ,443,443,443
BEGIN DESCRIPTION:
Mapping XS 92119f0b
END DESCRIPTION:
XS GIS Cut Line= 2
      1980998.86     13684102.92      1979504.08     13684168.02
#Sta/Elev= 30
  4036.9 1009.38  4070.8 1009.59  4150.9 1008.07  4180.9 1008.65  4202.8 1007.75
    4261 1006.84    4281 1007.24    4331 1005.61    4356 1005.72  4461.2 1003.99
  4571.3 1003.66  4621.8 1002.49    4644 1002.16  4662.8  1002.3  4720.5 1000.18
  4741.4 1000.47  4819.2  999.23  4889.3  997.84  4978.7   997.4  4979.2   996.6
  4984.2   996.6  4984.7   997.4  5035.9  998.26  5106.7 1000.51  5141.8 1001.89
  5231.9 1003.51  5452.1 1006.48  5472.1 1006.99  5502.1 1009.04  5533.1 1009.71
#Mann= 11 ,-1 , 0
  4036.9     .16       0    4356      .1       0  4621.8     .08       0
    4644     .16       0  4720.5     .05       0  4819.2     .16       0
  4889.3      .1       0  4978.7     .07       0  4984.7      .1       0
  5035.9     .16       0  5106.7      .1       0
Bank Sta=4978.7,4984.7
XS Rating Curve= 0 ,0
Exp/Cntr=0.3,0.1

Type RM Length L Ch R = 1 ,152658  ,358,358,358
BEGIN DESCRIPTION:
SF PEREZ CREEK 214.0
END DESCRIPTION:
XS GIS Cut Line= 3
      1980957.11     13683793.02        1980250.       13683750.
      1979454.55     13683790.42
#Sta/Elev= 30
  4232.3 1009.31  4334.6 1007.84  4364.7 1008.23  4443.3 1007.17  4484.9 1007.62
    4555 1006.92  4615.8 1005.19  4805.5 1001.41  4835.5  1000.1  4862.8   997.9
  4875.6  997.17  4895.6  997.05  4915.7  995.41  4961.3  994.45  4992.8  993.36
  4993.3  992.56  4998.3  992.56  4998.8  993.36    5011  994.16  5025.8  995.08
  5035.8  994.67  5134.4  994.95  5454.9  1000.9  5486.4 1001.81  5496.4 1002.83
  5506.5 1002.39  5531.5 1003.89  5596.6 1005.52  5676.7 1009.11  5737.2 1010.73
#Mann= 8 ,-1 , 0
  4232.3     .16       0  4862.8     .05       0  4961.3     .16       0
  4992.8     .07       0  4998.8     .16       0    5011      .1       0
  5454.9     .16       0  5531.5      .1       0
Bank Sta=4992.8,4998.8
XS Rating Curve= 0 ,0
Exp/Cntr=0.3,0.1

Type RM Length L Ch R = 1 ,152300  ,504,504,504
BEGIN DESCRIPTION:
Mapping XS 18cbcf39
END DESCRIPTION:
XS GIS Cut Line= 2
      1980974.77     13683379.83      1979413.53     13683460.06
#Sta/Elev= 30
  4144.9 1005.81  4264.8 1003.74  4284.9  1002.8  4356.1 1002.13    4395 1002.05
    4405    1003  4435.1 1001.23  4455.1 1001.73  4656.2  999.08  4781.9  996.35
  4815.6  996.09  4880.7  993.56  4935.7  993.05  4995.8   991.9  5002.8  990.59
  5003.3  989.79  5008.3  989.79  5008.8  990.59  5015.8  992.35  5025.7  992.45
  5075.9  991.53  5246.1  993.69  5314.3  995.33  5402.7  999.06  5445.9 1001.83
  5516.8 1005.88  5546.5 1006.23  5606.6 1009.12  5699.1  1010.3  5708.2 1010.48
#Mann= 11 ,-1 , 0
  4144.9     .16       0  4356.1      .1       0  4656.2     .16       0
  4781.9     .05       0  4880.7     .16       0  5002.8     .07       0
  5008.8     .16       0  5025.7      .1       0  5402.7     .16       0
  5445.9      .1       0  5699.1     .16       0
Bank Sta=4935.7,5025.7
XS Rating Curve= 0 ,0
Exp/Cntr=0.3,0.1

Type RM Length L Ch R = 1 ,151796  ,58,58,58
BEGIN DESCRIPTION:
Mapping XS caf8cbf1
END DESCRIPTION:
XS GIS Cut Line= 6
      1980938.77     13683174.97      1980225.22     13683115.94
      1980221.74     13682999.62      1980190.49     13682970.11
       1980114.1     13682940.59      1979469.16     13682977.02
#Sta/Elev= 30
  3982.5 1004.57  4146.8 1002.62  4409.7  995.16  4575.7  992.27  4674.2  992.02
  4719.4  990.95  4739.5  988.87  4773.8  988.79  4814.7  989.81  4823.1  988.05
    4830  988.89  4834.2  987.39  4834.7  986.59  4840.2  987.39  4844.1  988.98
  4851.3  988.16  4863.7  989.54  4882.9  988.95  4888.2  990.34  4912.8  989.92
  4918.2  991.61  5028.9  988.72  5094.2  988.54  5121.3   988.3  5183.4  988.44
  5239.6  991.63  5269.7  990.07  5289.9  992.34  5430.2   995.1  5586.2 1000.65
#Mann= 8 ,-1 , 0
  3982.5      .1       0  4575.7     .05       0  4674.2      .1       0
  4773.8     .05       0  4834.2    .033       0  4840.2     .05       0
  5094.2     .16       0  5121.3      .1       0
Bank Sta=4834.2,4840.2
XS Rating Curve= 0 ,0
Exp/Cntr=0.3,0.1

Type RM Length L Ch R = 1 ,151738  ,37,37,37
BEGIN DESCRIPTION:
SF PEREZ CREEK 213.0
END DESCRIPTION:
XS GIS Cut Line= 6
      1981045.71     13683156.74      1980266.41      13683100.1
      1980268.58     13682982.91      1980249.04     13682922.15
       1980055.9       13682882.      1979470.16     13682941.46
#Sta/Elev= 30
    3850 1006.35  3900.8 1006.04  4031.2 1003.15  4041.2  1003.5  4111.4 1002.41
  4362.1  995.25  4549.3  992.02  4602.7  991.34  4666.6  995.54    4793  998.54
  4852.3  999.49  4920.2  999.18  5035.7  996.84  5065.5  995.68  5087.9  994.42
    5093  994.84  5128.9  994.21  5161.2  995.15  5212.4  994.98  5245.6  995.66
  5265.8  994.66  5290.2  992.33    5303   989.2  5303.5   988.4  5308.5   988.4
    5309   989.2    5326  992.02    5336  992.59  5386.1  992.73  5601.5  999.83
#Mann= 7 ,-1 , 0
    3850      .1       0  4549.3     .05       0    4793      .1       0
  5035.7     .05       0  5065.5      .1       0    5303     .07       0
    5309      .1       0
Bank Sta=5303,5309
XS Rating Curve= 0 ,0
Exp/Cntr=0.3,0.1

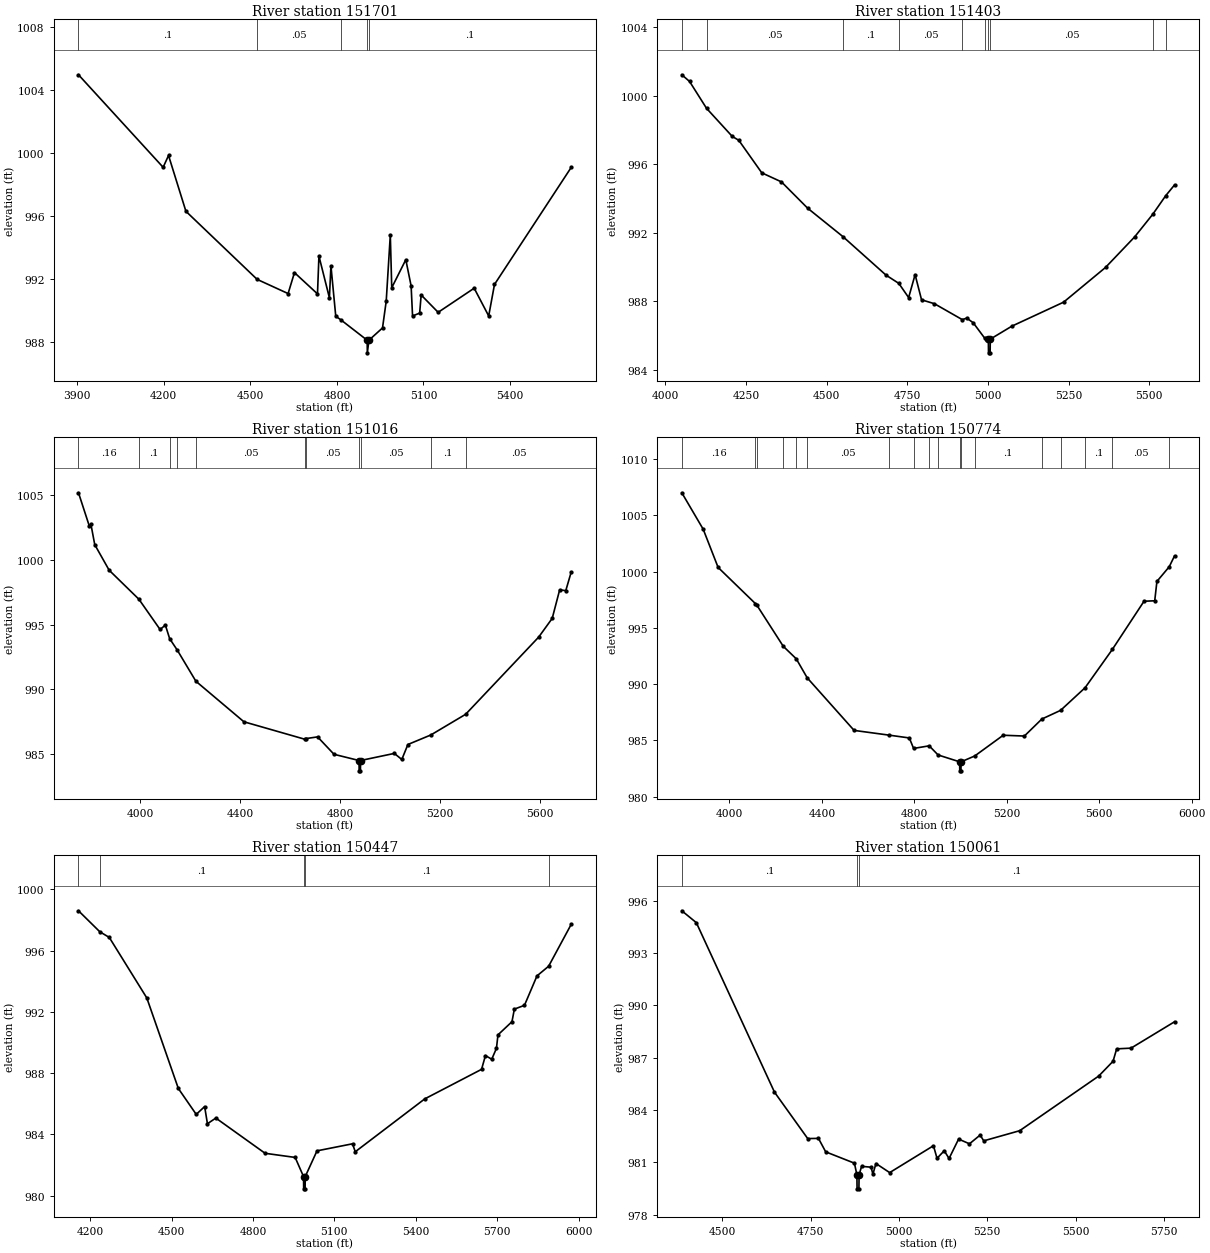
Type RM Length L Ch R = 1 ,151701  ,298,298,298
BEGIN DESCRIPTION:
Mapping XS 88b90165
END DESCRIPTION:
XS GIS Cut Line= 6
      1980966.07     13683132.43      1980295.53     13683080.35
      1980256.47     13682845.98      1979993.88      13682837.3
      1979872.35     13682876.36      1979470.84     13682919.77
#Sta/Elev= 30
  3904.7 1004.97    4198   999.1  4216.7  999.85  4276.9  996.31  4523.7  991.99
    4631  991.09    4653  992.42  4732.8  991.07  4737.8  993.47  4774.1  990.82
  4779.4  992.85  4796.1  989.65  4812.6  989.44    4905  988.13  4905.5  987.33
    4911  988.13  4958.1  988.91  4970.9   990.6  4985.1   994.8  4990.1  991.46
  5038.8  993.24  5057.2  991.58  5062.2  989.67  5086.8  989.85    5092     991
  5150.9   989.9  5275.7  991.43    5326  989.67  5346.1  991.67  5611.8  999.09
#Mann= 5 ,-1 , 0
  3904.7      .1       0  4523.7     .05       0  4812.6      .1       0
    4905     .07       0    4911      .1       0
Bank Sta=4905,4911
XS Rating Curve= 0 ,0
Exp/Cntr=0.3,0.1

Type RM Length L Ch R = 1 ,151403  ,387,387,387
BEGIN DESCRIPTION:
SF PEREZ CREEK 212.0
END DESCRIPTION:
XS GIS Cut Line= 3
      1981028.65     13682659.79      1980483.46     13682559.08
      1979511.23     13682541.72
#Sta/Elev= 30
  4051.1 1001.23  4075.1 1000.84  4127.7  999.27  4207.3  997.63  4227.7   997.4
  4298.9   995.5  4359.9  994.97  4441.2  993.43  4550.5  991.77    4684  989.52
  4723.5  989.04    4754  988.21    4774  989.55    4794  988.08    4834  987.85
  4920.3  986.92    4934  987.01    4954  986.74    4990  985.83    5001  985.78
  5001.5  984.98  5006.5  984.98    5007  985.78    5074  986.54  5234.1  987.94
  5364.1  989.97  5454.1  991.75  5510.6  993.08  5550.5  994.16  5577.9  994.79
#Mann= 10 ,-1 , 0
  4051.1      .1       0  4127.7     .05       0  4550.5      .1       0
  4723.5     .05       0  4920.3      .1       0    4990     .05       0
    5001    .035       0    5007     .05       0  5510.6     .08       0
  5550.5      .1       0
Bank Sta=5001,5007
XS Rating Curve= 0 ,0
Exp/Cntr=0.3,0.1

Type RM Length L Ch R = 1 ,151016  ,242,242,242
BEGIN DESCRIPTION:
SF PEREZ CREEK 211.0
END DESCRIPTION:
XS GIS Cut Line= 3
      1981173.58     13682285.65      1980647.53     13681954.92
      1979389.88     13682447.91
#Sta/Elev= 30
  3752.5 1005.21  3796.4  1002.6  3802.3 1002.77  3817.6 1001.19  3875.3  999.21
  3994.5  996.96  4079.1  994.62  4100.3  994.96  4117.4  993.91    4148  993.02
  4222.5  990.61  4414.7  987.47  4659.9  986.11  4663.5  986.17  4709.6   986.3
  4775.4  984.95  4875.5  984.47    4876  983.67  4881.1  983.67  4881.6  984.47
  5016.8  985.02  5046.7  984.55  5071.1  985.71  5163.1  986.45  5302.2  988.05
  5594.6  994.03  5648.8  995.48  5678.6  997.69  5703.1  997.63  5724.7  999.06
#Mann= 11 ,-1 , 0
  3752.5     .16       0  3994.5      .1       0  4117.4     .05       0
    4148      .1       0  4222.5     .05       0  4659.9     .08       0
  4663.5     .05       0  4875.5     .04       0  4881.6     .05       0
  5163.1      .1       0  5302.2     .05       0
Bank Sta=4875.5,4881.6
XS Rating Curve= 0 ,0
Exp/Cntr=0.3,0.1

Type RM Length L Ch R = 1 ,150774  ,327,327,327
BEGIN DESCRIPTION:
SF PEREZ CREEK 210.0
END DESCRIPTION:
XS GIS Cut Line= 3
      1981224.98     13682274.98      1980650.13     13681840.33
      1979324.63      13682324.7
#Sta/Elev= 30
  3793.9 1006.99  3886.5 1003.75    3951 1000.36  4112.3  997.15  4118.6  997.01
  4232.8  993.36    4289  992.25  4336.4  990.56  4539.4  985.89  4690.8  985.47
  4778.3  985.22  4796.8  984.29  4864.3  984.52  4902.8  983.71  4996.1   983.1
  4996.6   982.3  5001.7   982.3  5002.2   983.1  5061.4  983.62  5184.6  985.46
  5276.2  985.39  5351.8   986.9  5432.9  987.67  5538.9  989.68  5656.8  993.08
  5793.9  997.36  5840.2   997.4  5849.7  999.12  5902.9 1000.42  5925.8 1001.38
#Mann= 18 ,-1 , 0
  3793.9     .16       0  4112.3      .1       0  4118.6     .16       0
  4232.8      .1       0    4289     .16       0  4336.4     .05       0
  4690.8     .08       0  4796.8      .1       0  4864.3     .08       0
  4902.8     .05       0  4996.1     .04       0  5002.2     .05       0
  5061.4      .1       0  5351.8     .05       0  5432.9     .08       0
  5538.9      .1       0  5656.8     .05       0  5902.9      .1       0
Bank Sta=4996.1,5002.2
XS Rating Curve= 0 ,0
Exp/Cntr=0.3,0.1

Type RM Length L Ch R = 1 ,150447  ,386,386,386
BEGIN DESCRIPTION:
Mapping XS 775b3b60
END DESCRIPTION:
XS GIS Cut Line= 4
      1981164.84     13681646.77      1980665.75     13681776.97
      1979966.97      13681694.5      1979424.44      13681941.9
#Sta/Elev= 30
    4157   998.6  4235.6  997.23  4270.5  996.86  4408.8  992.91    4525     987
  4590.9  985.31  4621.9  985.82  4632.2   984.7  4663.2  985.07  4844.7  982.77
  4955.5   982.5  4986.4  981.25  4986.9  980.45  4992.1  980.45  4992.6  981.25
    5036  982.93  5166.9  983.39    5177  982.87    5433  986.32  5642.4  988.25
  5656.8  989.15  5679.9  988.91  5697.3  989.62  5702.9   990.5  5754.5  991.36
  5763.3  992.18  5800.6  992.43  5846.7  994.35  5889.6  994.98  5972.7  997.71
#Mann= 5 ,-1 , 0
    4157     .05       0  4235.6      .1       0  4986.4     .07       0
  4992.6      .1       0  5889.6     .05       0
Bank Sta=4986.4,4992.6
XS Rating Curve= 0 ,0
Exp/Cntr=0.3,0.1

Type RM Length L Ch R = 1 ,150061  ,440,440,440
BEGIN DESCRIPTION:
Mapping XS f5c4aeb4
END DESCRIPTION:
XS GIS Cut Line= 2
      1981095.45     13681568.63      1979723.95     13681312.56
#Sta/Elev= 30
  4384.9  995.42    4426  994.74  4647.3  985.03  4741.4  982.37  4771.9  982.38
  4792.3  981.61  4873.7  980.96  4880.7  980.29  4881.2  979.49  4886.4  979.49
  4886.9  980.29    4894  980.78  4920.9  980.73    4926  980.33  4934.7  980.94
  4973.5  980.42  5097.5  981.96  5107.6  981.24    5128  981.67  5141.7  981.23
  5168.7  982.34  5199.5  982.07  5229.7  982.57  5239.9  982.24  5341.6  982.82
  5565.4  985.95  5606.1   986.8  5616.3  987.51    5657  987.55  5780.1  989.06
#Mann= 3 ,-1 , 0
  4384.9      .1       0  4880.7     .07       0  4886.9      .1       0
Bank Sta=4880.7,4886.9
XS Rating Curve= 0 ,0
Exp/Cntr=0.3,0.1

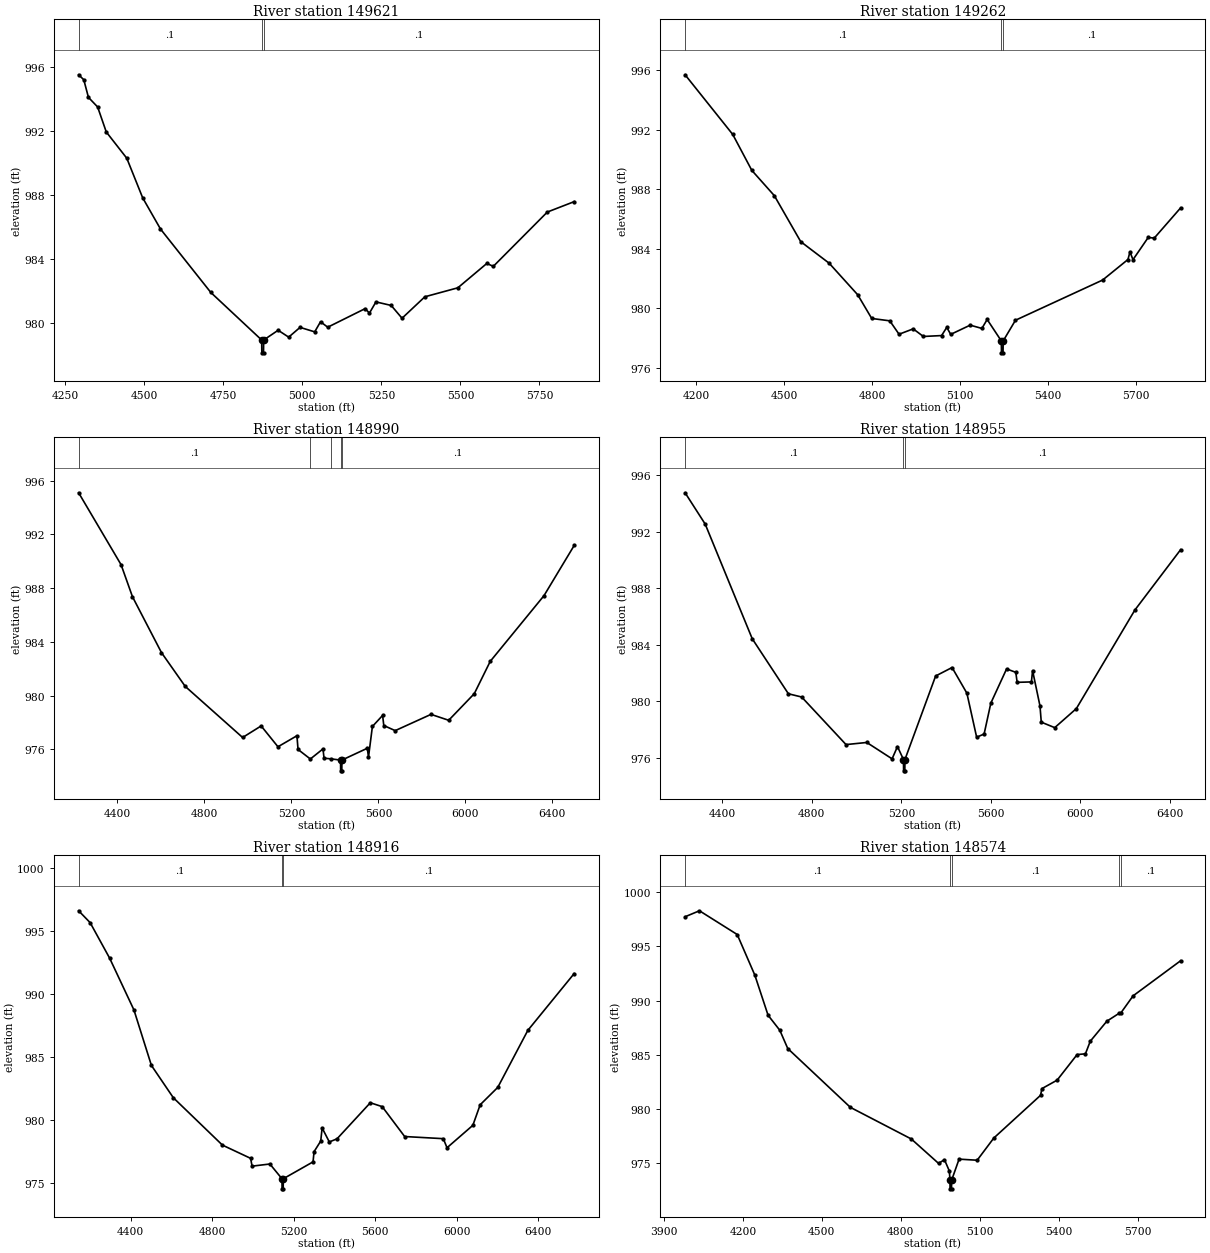
Type RM Length L Ch R = 1 ,149621  ,359,359,359
BEGIN DESCRIPTION:
SF PEREZ CREEK 207.0
END DESCRIPTION:
XS GIS Cut Line= 3
      1981173.53     13681399.33       1980756.9     13681095.54
      1979736.98     13680839.48
#Sta/Elev= 30
  4292.5  995.49  4308.8  995.18  4323.5  994.08  4352.6  993.48  4379.9  991.92
  4444.8  990.28    4495  987.81  4551.4  985.86  4710.5   981.9  4871.4  978.93
  4871.9  978.13  4877.2  978.13  4877.7  978.93  4923.5  979.54  4956.8  979.11
  4992.8  979.72  5039.1  979.44  5057.5  980.07  5080.3  979.73  5198.6  980.89
  5212.2  980.61  5232.8  981.31  5280.9  981.09  5315.3  980.29  5387.5  981.63
  5491.8  982.19  5583.4  983.71    5604  983.53  5774.8  986.92  5859.7  987.57
#Mann= 3 ,-1 , 0
  4292.5      .1       0  4871.4     .07       0  4877.7      .1       0
Bank Sta=4871.4,4877.7
XS Rating Curve= 0 ,0
Exp/Cntr=0.3,0.1

Type RM Length L Ch R = 1 ,149262  ,272,272,272
BEGIN DESCRIPTION:
SF PEREZ CREEK 206.0
END DESCRIPTION:
XS GIS Cut Line= 3
      1981425.34     13680974.03      1981108.46     13680843.81
      1979808.21     13680492.74
#Sta/Elev= 30
  4162.4  995.68  4324.9  991.67  4389.8  989.26  4466.6  987.56  4556.6  984.47
  4653.6  983.02  4750.9   980.9  4798.6  979.31  4860.2  979.15  4891.8  978.25
    4940  978.61  4974.7   978.1  5036.8  978.16  5054.5  978.71  5067.9  978.24
  5134.3  978.86  5174.2  978.64  5192.2  979.24  5240.5   977.8    5241     977
  5246.3     977  5246.8   977.8  5288.7  979.19  5585.8  981.89  5672.2  983.27
    5679  983.78  5689.4  983.26  5741.2  984.75  5761.9  984.71  5851.8  986.74
#Mann= 3 ,-1 , 0
  4162.4      .1       0  5240.5     .07       0  5246.8      .1       0
Bank Sta=5240.5,5246.8
XS Rating Curve= 0 ,0
Exp/Cntr=0.3,0.1

Type RM Length L Ch R = 1 ,148990  ,35,35,35
BEGIN DESCRIPTION:
Mapping XS 12214baf
END DESCRIPTION:
XS GIS Cut Line= 6
      1981454.22     13680800.06      1980659.92      13680453.7
      1980592.21     13680237.55      1980472.42     13680271.41
      1980537.53     13680503.18      1979761.47     13680284.42
#Sta/Elev= 30
  4221.7  995.09  4416.9  989.74  4469.2  987.36  4602.7   983.2  4711.8  980.69
  4975.7  976.89  5060.9  977.75  5138.2   976.2  5225.4  977.02  5230.5     976
  5287.1  975.29  5345.1  976.04  5350.1  975.35  5382.4   975.3  5425.9  975.21
  5426.4  974.41  5431.7  974.41  5432.2  975.21    5549  976.09  5554.4  975.43
  5572.4  977.71  5619.3  978.53  5624.8  977.78  5677.2   977.4  5841.9  978.61
  5923.2  978.17  6040.9  980.15  6114.1  982.55  6361.4  987.44  6500.1  991.17
#Mann= 5 ,-1 , 0
  4221.7      .1       0  5287.1     .05       0  5382.4      .1       0
  5425.9     .07       0  5432.2      .1       0
Bank Sta=5425.9,5432.2
XS Rating Curve= 0 ,0
Exp/Cntr=0.3,0.1

Type RM Length L Ch R = 1 ,148955  ,39,39,39
BEGIN DESCRIPTION:
Mapping XS 128b4859
END DESCRIPTION:
XS GIS Cut Line= 6
      1981443.75     13680753.17      1980805.75     13680497.97
      1980589.61     13680169.84      1980454.19     13680198.49
      1980472.42     13680448.49      1979809.21     13680248.23
#Sta/Elev= 30
  4234.2  994.77    4324  992.55    4534  984.43  4695.5  980.53  4754.8   980.3
  4952.9  976.93  5045.6  977.08  5158.6  975.92  5182.7  976.79  5209.5  975.87
    5210  975.07  5215.5  975.07    5216  975.87  5353.1  981.79  5426.5  982.39
  5492.7  980.57  5536.3  977.45  5569.6  977.68  5599.7  979.87    5670  982.29
  5711.1  982.05  5717.1  981.34  5780.9  981.37  5786.1  982.17  5819.1  979.67
  5824.9  978.52    5885  978.13  5981.6  979.48  6242.8  986.46  6447.3  990.74
#Mann= 3 ,-1 , 0
  4234.2      .1       0  5209.5     .07       0    5216      .1       0
Bank Sta=5209.5,5216
XS Rating Curve= 0 ,0
Exp/Cntr=0.3,0.1

Type RM Length L Ch R = 1 ,148916  ,342,342,342
BEGIN DESCRIPTION:
Mapping XS c2459095
END DESCRIPTION:
XS GIS Cut Line= 6
      1981537.55     13680727.15      1980719.82     13680406.82
      1980628.67     13680068.28      1980412.53      13680081.3
       1980394.3     13680412.03      1979788.78     13680191.13
#Sta/Elev= 30
  4144.3  996.57  4200.7  995.63  4296.5  992.81  4415.8   988.7  4501.5   984.3
  4608.9  981.74  4849.9  977.98  4988.3  976.93  4995.5  976.31  5082.9  976.48
  5142.2  975.31  5142.7  974.51  5148.2  974.51  5148.7  975.31  5294.7  976.65
  5299.7  977.46  5332.4   978.3  5339.3  979.34  5374.6  978.23  5412.5  978.48
  5575.8  981.34  5634.2  981.03  5744.3  978.66  5933.9  978.49  5952.2  977.77
    6079  979.55  6114.9  981.18  6201.3  982.56  6348.7  987.08  6576.2  991.59
#Mann= 3 ,-1 , 0
  4144.3      .1       0  5142.2     .07       0  5148.7      .1       0
Bank Sta=5142.2,5148.7
XS Rating Curve= 0 ,0
Exp/Cntr=0.3,0.1

Type RM Length L Ch R = 1 ,148574  ,343,343,343
BEGIN DESCRIPTION:
SF PEREZ CREEK 204.0
END DESCRIPTION:
XS GIS Cut Line= 3
      1981763.83     13680570.36        1980875.       13680125.
      1980032.06      13679841.2
#Sta/Elev= 30
  3980.3  997.74  4034.9  998.29  4178.4   996.1  4245.4  992.35  4295.7  988.65
  4340.4  987.26  4370.5  985.58  4608.5  980.15  4840.2  977.23  4943.7  974.98
  4966.1  975.32  4984.9  974.27    4987  973.43  4987.5  972.63    4993  972.63
  4993.5  973.43  5021.7  975.37  5090.5  975.27  5153.8  977.32  5331.4  981.26
  5336.7  981.88  5394.4  982.66  5470.4  985.02    5502  985.09  5520.4  986.25
  5583.4   988.1  5629.5  988.82  5636.9  988.87  5683.2  990.44  5863.9  993.68
#Mann= 5 ,-1 , 0
  3980.3      .1       0    4987     .07       0  4993.5      .1       0
  5629.5     .16       0  5636.9      .1       0
Bank Sta=4987,4993.5
XS Rating Curve= 0 ,0
Exp/Cntr=0.3,0.1

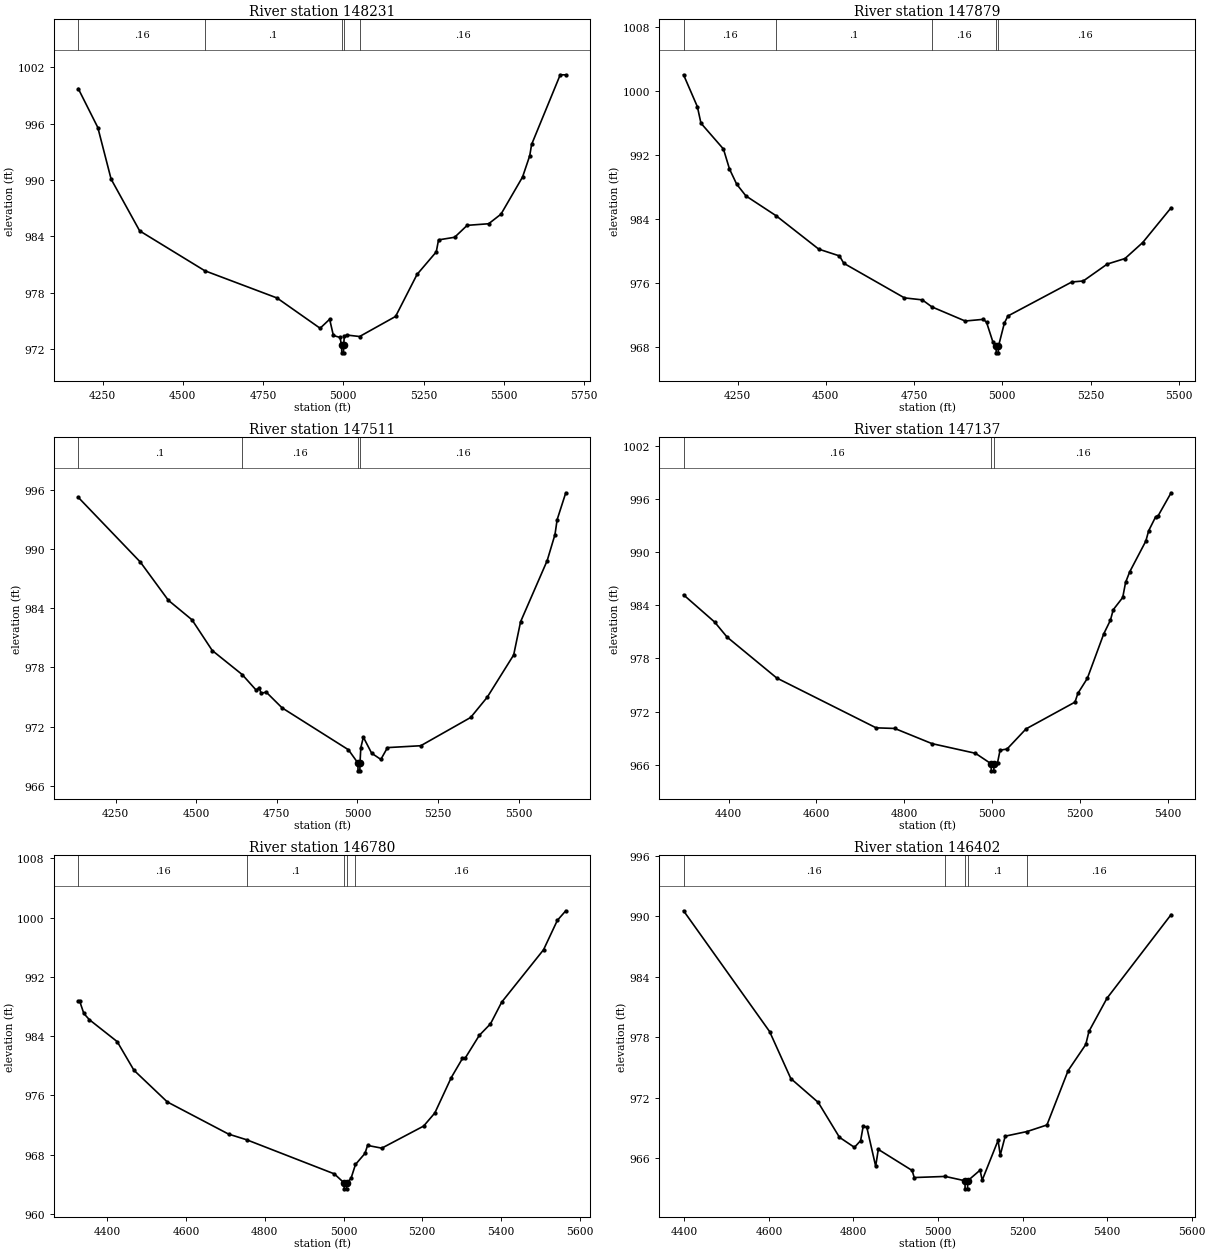
Type RM Length L Ch R = 1 ,148231  ,352,352,352
BEGIN DESCRIPTION:
SF PEREZ CREEK 203.0
END DESCRIPTION:
XS GIS Cut Line= 3
      1981894.07      13680088.6        1981075.       13679875.
      1980474.77      13679572.1
#Sta/Elev= 30
  4174.3  999.75  4235.3   995.6  4276.7   990.1  4365.7  984.58  4568.6  980.33
  4793.4  977.43  4927.8   974.2  4957.5  975.16  4969.1  973.43  4989.8  973.22
  4994.7  972.38  4995.2  971.58  5000.7  971.58  5001.2  972.38  5003.1  973.34
  5010.4  973.48  5050.8  973.32  5162.9  975.46  5229.8  979.94  5289.6  982.34
  5296.7  983.62  5346.9   983.9  5385.9  985.17  5452.8  985.34  5491.2  986.36
  5558.4  990.32  5580.8  992.59  5586.6  993.79  5675.8 1001.22  5693.1 1001.21
#Mann= 5 ,-1 , 0
  4174.3     .16       0  4568.6      .1       0  4994.7     .07       0
  5001.2      .1       0  5050.8     .16       0
Bank Sta=4994.7,5001.2
XS Rating Curve= 0 ,0
Exp/Cntr=0.3,0.1

Type RM Length L Ch R = 1 ,147879  ,368,368,368
BEGIN DESCRIPTION:
SF PEREZ CREEK 202.0
END DESCRIPTION:
XS GIS Cut Line= 3
      1982093.66     13679706.65        1981225.       13679575.
      1980724.97       13679525.
#Sta/Elev= 30
  4097.1 1002.07  4136.2  998.07  4146.4     996  4210.1  992.76  4227.2  990.26
  4247.5  988.36  4273.8  986.88  4359.2   984.4  4480.1  980.21  4538.8  979.36
  4550.9  978.44  4722.8   974.1  4773.4  973.85  4800.6  972.97  4894.8   971.2
  4946.4  971.41  4955.4  971.04  4973.1  968.61  4982.4  968.01  4982.9  967.21
  4988.5  967.21    4989  968.01  5005.8  970.93  5015.9  971.83  5196.8  976.09
  5229.4  976.22  5297.3  978.34  5347.5  979.03  5397.8  981.04  5478.2   985.4
#Mann= 5 ,-1 , 0
  4097.1     .16       0  4359.2      .1       0  4800.6     .16       0
  4982.4     .07       0    4989     .16       0
Bank Sta=4982.4,4989
XS Rating Curve= 0 ,0
Exp/Cntr=0.3,0.1

Type RM Length L Ch R = 1 ,147511  ,374,374,374
BEGIN DESCRIPTION:
SF PEREZ CREEK 201.0
END DESCRIPTION:
XS GIS Cut Line= 3
      1982071.96     13679012.22        1981225.       13679275.
      1980619.05     13679428.61
#Sta/Elev= 30
  4134.2  995.28  4326.9   988.7  4413.7  984.82    4487  982.84  4549.8  979.72
  4642.6  977.28  4685.9   975.7  4695.8  975.96    4701  975.38  4717.3  975.49
  4766.2   973.9  4972.1  969.64  5001.4   968.3  5001.9   967.5  5007.5   967.5
    5008   968.3  5010.5  969.86  5018.4  970.92  5044.1  969.29  5072.6  968.66
  5093.2  969.86  5196.4  970.05  5351.1  972.92  5402.6  974.98  5484.5  979.27
  5505.9  982.64  5588.4  988.85  5612.6   991.5  5619.3  993.01  5646.1  995.74
#Mann= 4 ,-1 , 0
  4134.2      .1       0  4642.6     .16       0  5001.4     .07       0
    5008     .16       0
Bank Sta=5001.4,5008
XS Rating Curve= 0 ,0
Exp/Cntr=0.3,0.1

Type RM Length L Ch R = 1 ,147137  ,357,357,357
BEGIN DESCRIPTION:
SF PEREZ CREEK 200.0
END DESCRIPTION:
XS GIS Cut Line= 3
      1981425.03     13678624.97        1980925.       13679125.
      1980574.97     13679325.02
#Sta/Elev= 30
  4297.4  985.17  4368.2   982.1  4396.4  980.41  4509.6  975.79  4735.9  970.17
  4778.3   970.1  4863.1  968.39  4962.1   967.3  4997.7  966.12  4998.2  965.32
  5003.9  965.32  5004.4  966.12  5012.5  966.26  5018.2  967.65  5034.1  967.78
  5077.3  970.05  5188.8  973.07  5195.3  974.05  5216.9  975.75  5254.3  980.77
  5269.5  982.31  5275.9  983.49  5297.5  984.87    5304  986.57  5313.4  987.76
  5350.1  991.23  5356.6   992.4  5372.4  993.96  5378.2  994.09  5407.7  996.68
#Mann= 3 ,-1 , 0
  4297.4     .16       0  4997.7     .07       0  5004.4     .16       0
Bank Sta=4997.7,5004.4
XS Rating Curve= 0 ,0
Exp/Cntr=0.3,0.1

Type RM Length L Ch R = 1 ,146780  ,378,378,378
BEGIN DESCRIPTION:
SF PEREZ CREEK 199.0
END DESCRIPTION:
XS GIS Cut Line= 3
      1981275.03     13678324.97        1980775.       13678825.
      1980424.97     13679225.04
#Sta/Elev= 30
  4325.9  988.72  4329.5  988.72  4340.1  987.05  4354.2  986.21  4424.9  983.25
  4467.4  979.39  4552.2  975.11  4707.8  970.77    4754     970  4976.5   965.4
  5001.4  964.18  5001.9  963.38  5007.6  963.38  5008.1  964.18  5018.9  964.78
  5030.3  966.67  5054.4  968.16    5061  969.24  5097.1  968.87  5203.4  971.85
  5231.9  973.62  5273.6  978.39  5302.1  980.98  5309.7  981.08  5344.8  984.09
  5373.3  985.65  5401.8  988.58  5508.1  995.65  5543.2  999.62  5564.6 1000.91
#Mann= 5 ,-1 , 0
  4325.9     .16       0    4754      .1       0  5001.4     .07       0
  5008.1      .1       0  5030.3     .16       0
Bank Sta=5001.4,5008.1
XS Rating Curve= 0 ,0
Exp/Cntr=0.3,0.1

Type RM Length L Ch R = 1 ,146402  ,32,32,32
BEGIN DESCRIPTION:
Mapping XS 7cfe996c
END DESCRIPTION:
XS GIS Cut Line= 6
      1981174.66     13678140.07      1980789.24     13678422.63
       1980642.1     13678460.39      1980614.76     13678499.45
      1980631.68     13678572.37      1980334.83     13678839.27
#Sta/Elev= 30
  4398.2  990.55  4601.7  978.58  4651.9  973.92  4716.7  971.56  4766.9   968.1
  4802.4   967.1    4817  967.77  4823.2  969.22  4831.7  969.08  4852.6  965.23
  4858.8   966.9  4938.8  964.81  4943.8  964.11  5017.2  964.22  5063.7  963.79
  5064.2  962.99  5069.9  962.99  5070.4  963.79  5099.5  964.84  5104.6  963.85
  5142.1  967.79  5147.3  966.34    5159  968.21  5210.7  968.67  5257.7  969.32
  5307.8  974.71  5349.6   977.3  5357.1   978.6  5399.7  981.88  5551.4  990.17
#Mann= 5 ,-1 , 0
  4398.2     .16       0  5017.2      .1       0  5063.7     .07       0
  5070.4      .1       0  5210.7     .16       0
Bank Sta=5063.7,5070.4
XS Rating Curve= 0 ,0
Exp/Cntr=0.3,0.1