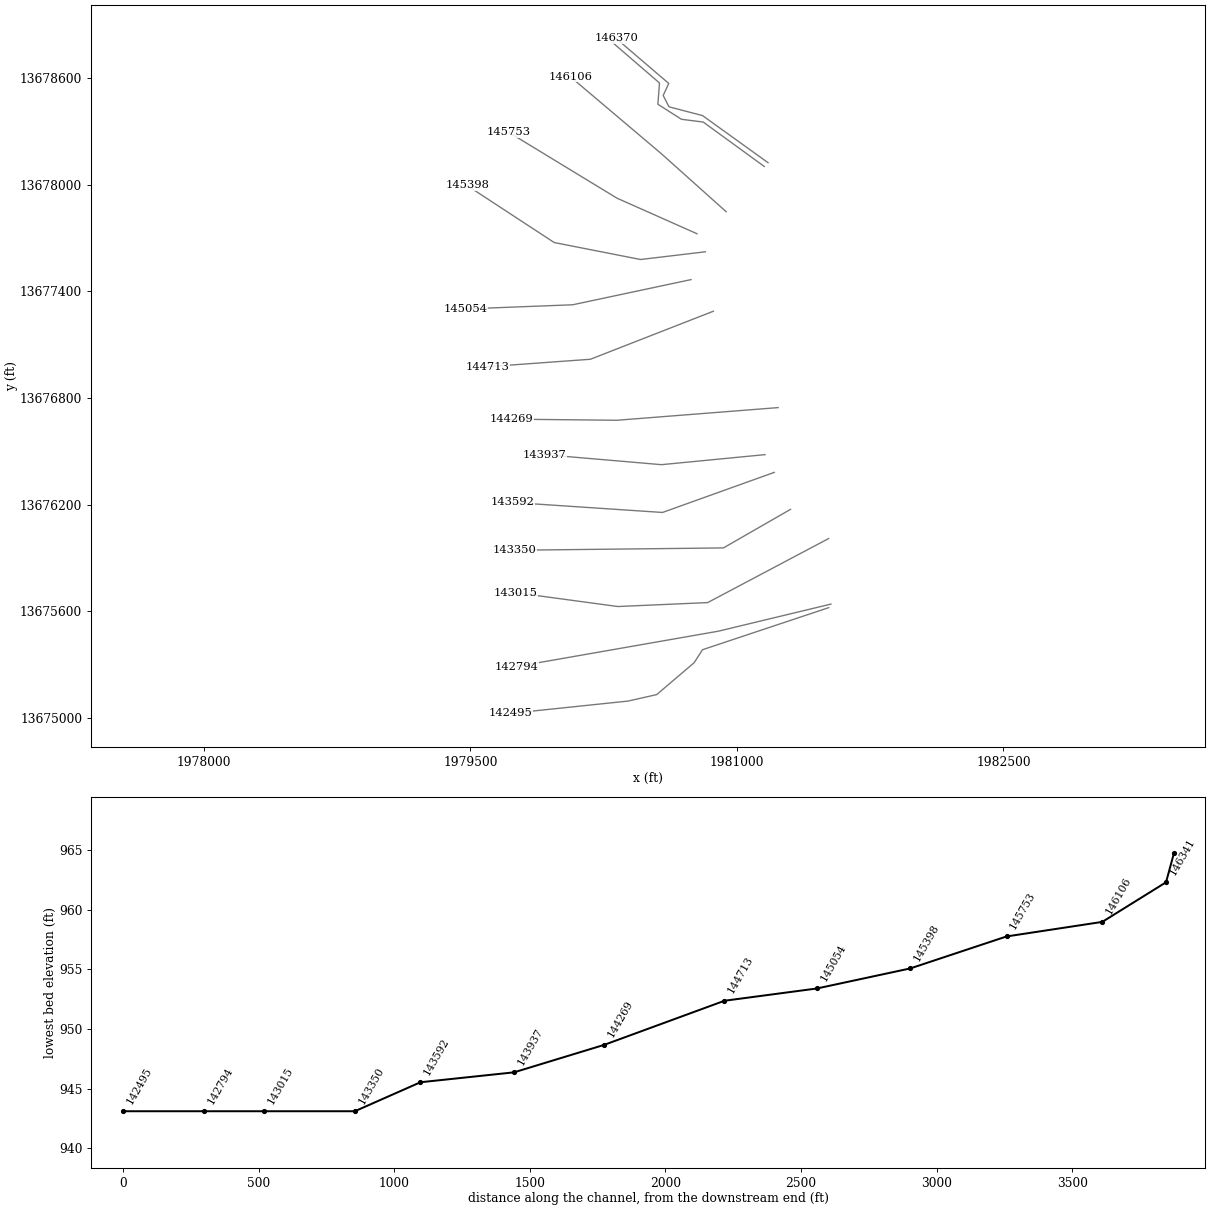
HEC-RAS study SF PEREZ CREEK.prj: SF PEREZ CREEK Base Level Engineering

--- SF PEREZ CREEK.g01 (geometry) --- (continued)

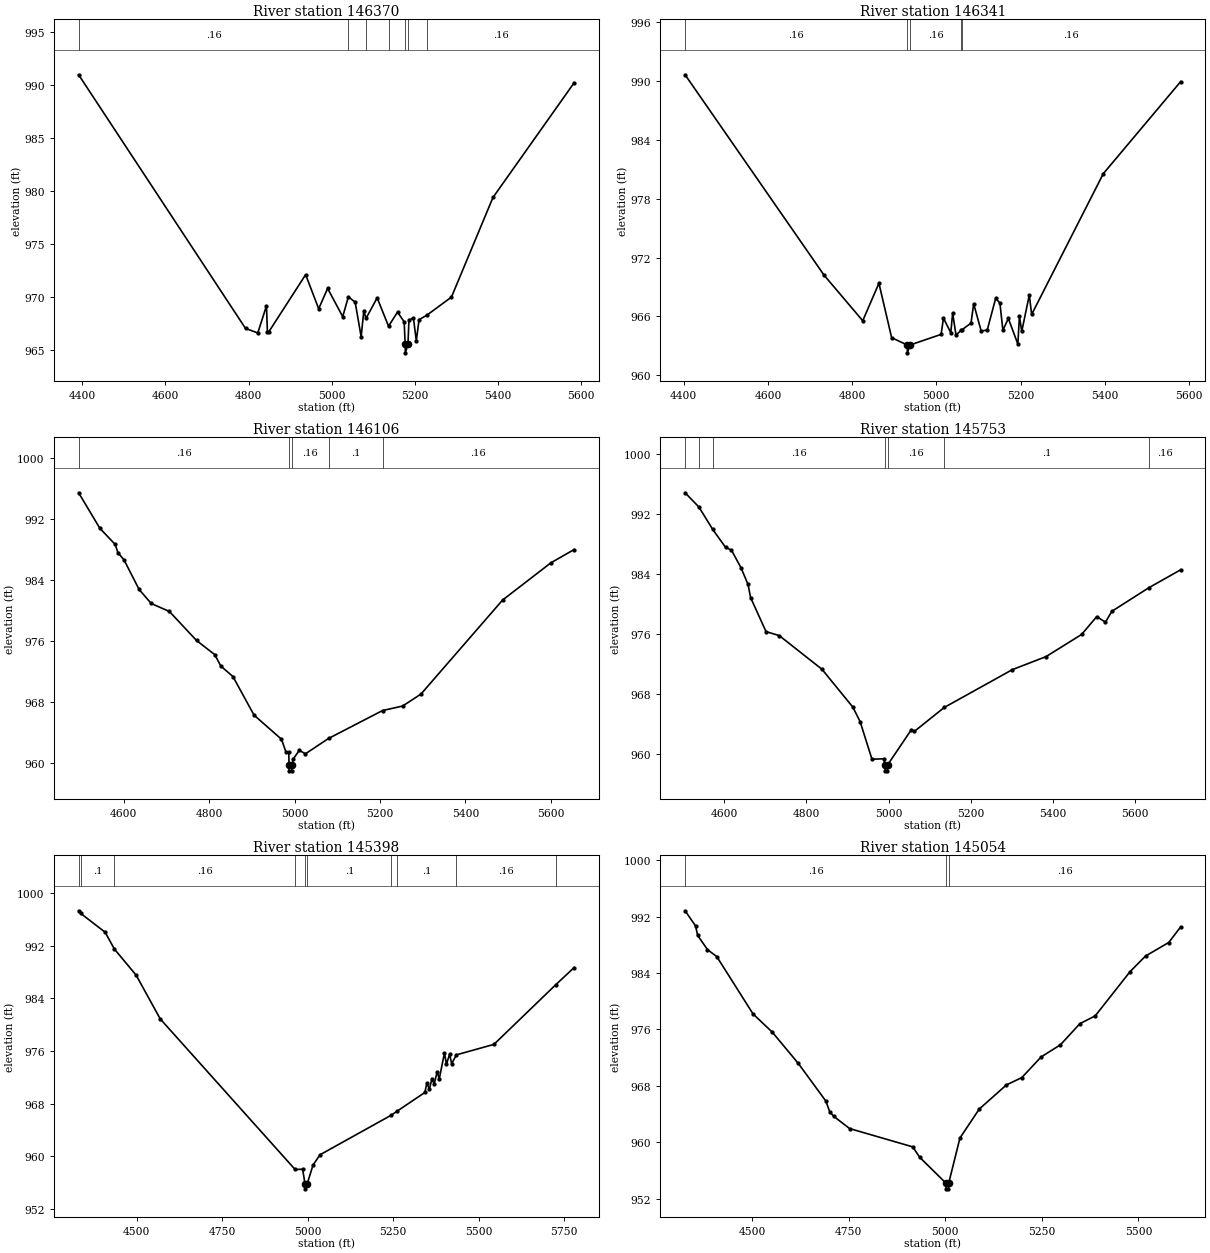
Type RM Length L Ch R = 1 ,146370  ,29,29,29
BEGIN DESCRIPTION:
SF PEREZ CREEK 198.0
END DESCRIPTION:
XS GIS Cut Line= 6
        1981175.       13678125.      1980806.16     13678390.07
      1980617.36     13678439.55      1980584.81     13678503.36
      1980616.06     13678571.06      1980319.29     13678824.93
#Sta/Elev= 30
  4391.2     991  4792.6  967.02  4822.1  966.59    4843  969.15  4845.3  966.69
  4848.5  966.69  4937.2   972.1  4968.6  968.88  4990.1   970.8  5026.4  968.13
    5040  970.01  5056.4  969.49  5070.7  966.23  5077.2  968.71  5082.4  967.96
  5109.2  969.91  5136.6  967.23  5158.2  968.56  5174.2  967.64  5176.6  965.51
  5177.1  964.71  5183.3  965.51  5185.7  967.81  5196.5     968  5203.4  965.85
    5210  967.85  5228.5  968.26  5287.9  969.98  5387.8   979.4  5583.1  990.25
#Mann= 7 ,-1 , 0
  4391.2     .16       0    5040      .1       0  5082.4     .16       0
  5136.6      .1       0  5176.6     .07       0  5183.3      .1       0
  5228.5     .16       0
Bank Sta=5176.6,5183.3
XS Rating Curve= 0 ,0
Exp/Cntr=0.3,0.1

Type RM Length L Ch R = 1 ,146341  ,235,235,235
BEGIN DESCRIPTION:
Mapping XS 954ec163
END DESCRIPTION:
XS GIS Cut Line= 6
      1981153.79     13678103.64      1980810.07     13678353.62
      1980687.67     13678369.24      1980554.86     13678453.88
      1980563.97     13678573.67      1980301.11     13678800.09
#Sta/Elev= 30
  4403.2  990.63  4733.2  970.21  4825.1  965.56  4863.6  969.38  4893.8  963.83
  4930.8  963.09  4931.3  962.29  4937.5  963.09  5011.2  964.17  5016.9  965.82
  5034.3  964.34  5038.7  966.36  5046.6   964.1  5059.6  964.62  5060.3  964.62
  5082.3  965.32  5088.6  967.29  5106.4  964.52  5120.8  964.61  5140.9  967.85
  5150.9  967.37    5158   964.6    5171  965.79  5193.6  963.18  5197.3  966.04
  5202.8  964.47  5220.8  968.19  5226.3   966.2  5396.5  980.55  5580.2  989.93
#Mann= 5 ,-1 , 0
  4403.2     .16       0  4930.8     .07       0  4937.5     .16       0
  5059.6      .1       0  5060.3     .16       0
Bank Sta=4930.8,4937.5
XS Rating Curve= 0 ,0
Exp/Cntr=0.3,0.1

Type RM Length L Ch R = 1 ,146106  ,353,353,353
BEGIN DESCRIPTION:
SF PEREZ CREEK 197.0
END DESCRIPTION:
XS GIS Cut Line= 3
      1980939.18     13677849.03        1980575.       13678175.
      1980062.44     13678608.58
#Sta/Elev= 30
  4494.4  995.49  4543.9  990.84  4579.8  988.71  4586.5  987.61  4600.7  986.67
  4635.9   982.8  4664.3  980.95  4706.9   979.9  4770.4  976.09  4813.1  974.23
  4827.3  972.73  4855.7  971.35    4905  966.29  4969.3  963.12  4979.8  961.43
  4986.4  961.43  4986.9  959.77  4987.4  958.97  4993.2  958.97  4993.7  959.77
  4996.9  960.54  5011.1  961.66  5025.4  961.21  5079.4  963.22  5205.9  966.89
  5252.9  967.48  5295.8  969.05  5486.9   981.4    5600  986.29  5654.5  988.04
#Mann= 5 ,-1 , 0
  4494.4     .16       0  4986.9     .07       0  4993.7     .16       0
  5079.4      .1       0  5205.9     .16       0
Bank Sta=4986.9,4993.7
XS Rating Curve= 0 ,0
Exp/Cntr=0.3,0.1

Type RM Length L Ch R = 1 ,145753  ,355,355,355
BEGIN DESCRIPTION:
SF PEREZ CREEK 196.0
END DESCRIPTION:
XS GIS Cut Line= 3
      1980775.03     13677724.99        1980325.       13677925.
      1979715.21     13678296.08
#Sta/Elev= 30
  4504.8  994.86  4538.4  992.96    4572  989.97  4603.3  987.58  4617.7   987.2
  4640.9  984.85    4658  982.63  4664.2  980.88  4701.8  976.33    4734   975.8
  4837.9  971.31  4913.2  966.25  4930.9  964.31  4959.7   959.3  4988.4  959.36
  4991.1  958.55  4991.6  957.75  4997.4  957.75  4997.9  958.55  5055.8  963.26
  5063.1  963.02  5135.7  966.21  5301.6  971.26  5383.6     973    5470  975.95
  5506.8  978.33  5528.1  977.59  5543.6  979.04  5634.1   982.2  5711.1  984.58
#Mann= 7 ,-1 , 0
  4504.8     .16       0  4538.4      .1       0    4572     .16       0
  4991.1     .07       0  4997.9     .16       0  5135.7      .1       0
  5634.1     .16       0
Bank Sta=4991.1,4997.9
XS Rating Curve= 0 ,0
Exp/Cntr=0.3,0.1

Type RM Length L Ch R = 1 ,145398  ,344,344,344
BEGIN DESCRIPTION:
SF PEREZ CREEK 195.0
END DESCRIPTION:
XS GIS Cut Line= 4
      1980821.96     13677623.31      1980457.42     13677579.92
      1979971.31      13677675.4      1979480.83      13677996.6
#Sta/Elev= 30
  4330.6  997.32  4336.4  996.93  4408.1  994.06  4435.2   991.5  4498.7  987.54
  4569.2  980.89  4963.5  958.01  4985.5  958.05  4992.3  955.87  4992.8  955.07
  4999.1  955.87  5016.1  958.71  5036.5  960.25  5245.2  966.28  5260.8  966.84
  5342.8  969.71  5348.8  971.13    5356  970.23  5363.9  971.83  5369.9  970.97
    5379  972.85    5385  971.77  5400.1   975.7  5406.1  974.01  5415.2  975.54
  5421.2  974.09  5435.2  975.43  5544.8  977.02  5725.7  986.09  5779.4   988.7
#Mann= 10 ,-1 , 0
  4330.6     .16       0  4336.4      .1       0  4435.2     .16       0
  4963.5      .1       0  4992.3     .07       0  4999.1      .1       0
  5245.2     .16       0  5260.8      .1       0  5435.2     .16       0
  5725.7      .1       0
Bank Sta=4992.3,4999.1
XS Rating Curve= 0 ,0
Exp/Cntr=0.3,0.1

Type RM Length L Ch R = 1 ,145054  ,341,341,341
BEGIN DESCRIPTION:
SF PEREZ CREEK 194.0
END DESCRIPTION:
XS GIS Cut Line= 3
      1980741.52     13677466.76        1980075.       13677325.
      1979474.18     13677301.82
#Sta/Elev= 30
  4326.7  992.83  4353.8  990.68  4359.1  989.35  4384.5  987.33  4408.7  986.33
  4502.7  978.19  4552.3  975.62  4619.6  971.19  4690.9  965.85  4701.4  964.28
  4711.6  963.67  4752.5  961.94  4916.1  959.34  4933.7  957.88  5002.1  954.19
  5002.6  953.39  5008.5  953.39    5009  954.19  5038.2  960.61  5088.2  964.71
  5158.2  968.12  5198.3  969.17  5248.3   972.1  5298.3  973.82  5348.4  976.81
  5388.4  977.93  5478.5   984.2  5518.5  986.41  5578.6  988.33  5609.4  990.54
#Mann= 3 ,-1 , 0
  4326.7     .16       0  5002.1     .07       0    5009     .16       0
Bank Sta=5002.1,5009
XS Rating Curve= 0 ,0
Exp/Cntr=0.3,0.1

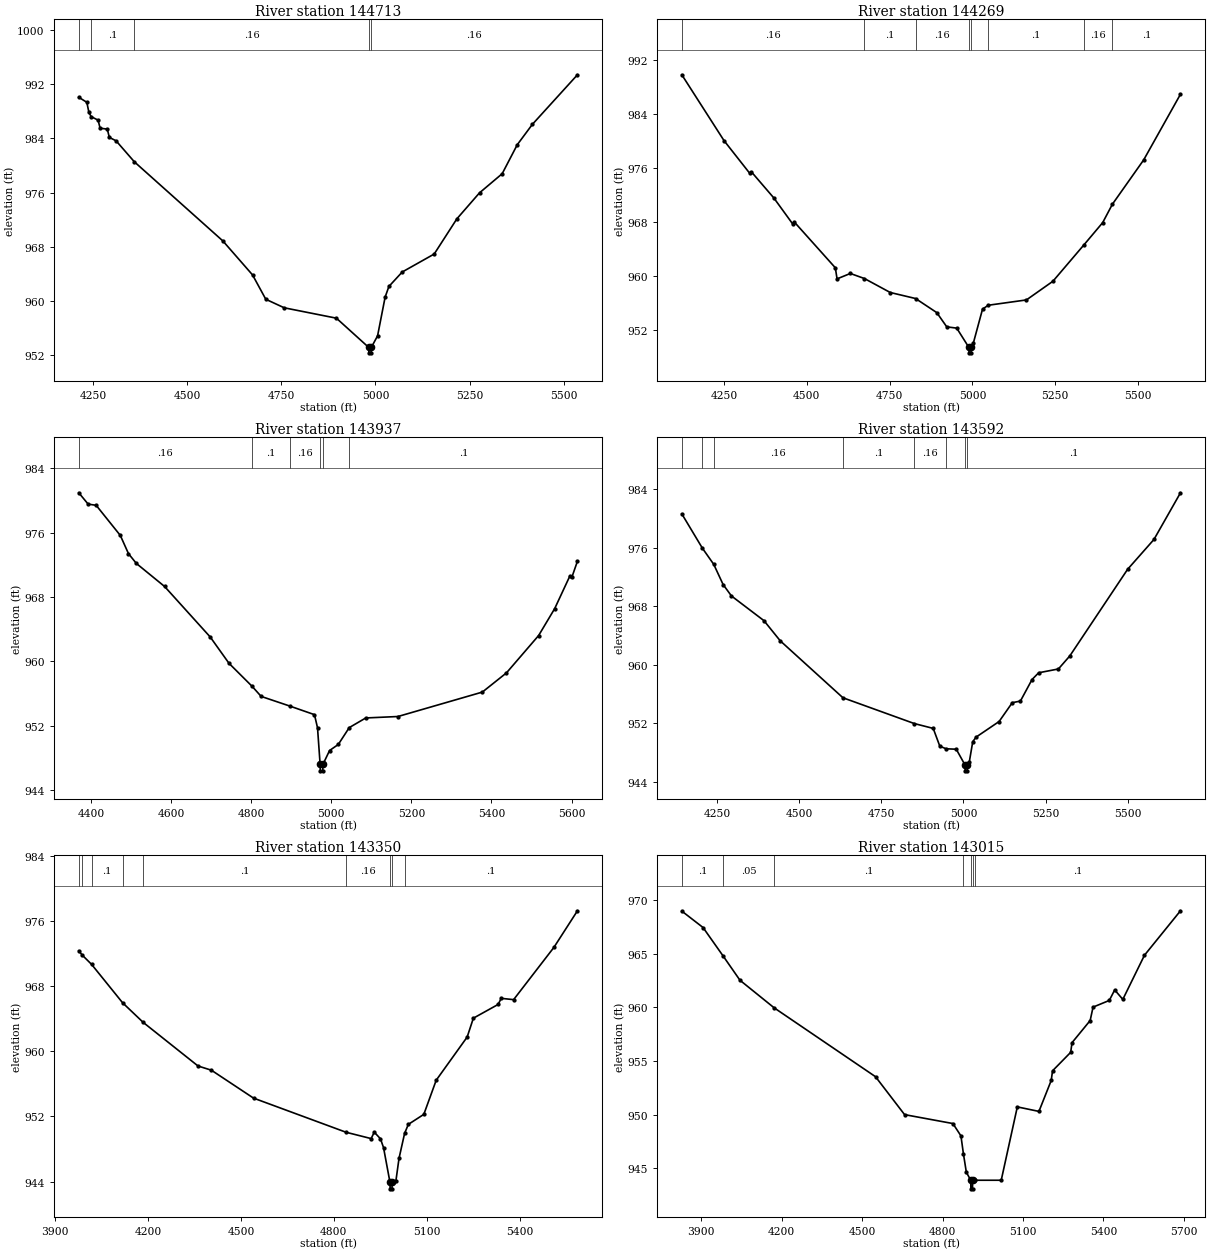
Type RM Length L Ch R = 1 ,144713  ,444,444,444
BEGIN DESCRIPTION:
SF PEREZ CREEK 193.0
END DESCRIPTION:
XS GIS Cut Line= 3
      1980867.35      13677288.8        1980175.      13677018.4
      1979595.61      13676976.3
#Sta/Elev= 30
  4212.4  990.04  4233.8   989.3  4239.2  987.82  4245.3  987.19  4263.7  986.67
    4269  985.48  4288.1  985.35  4293.5  984.13  4311.5  983.62  4359.9  980.53
    4595  968.86  4673.8  963.85    4709  960.26    4758     959  4896.5  957.47
  4982.3  953.16  4982.8  952.36  4988.7  952.36  4989.2  953.16  5005.8  954.86
  5025.9  960.58  5035.9  962.15  5071.3  964.28  5156.2  966.93  5216.4  972.12
  5276.5  975.95  5336.7  978.77  5376.8  983.05  5416.9  986.05  5536.6  993.36
#Mann= 5 ,-1 , 0
  4212.4     .16       0  4245.3      .1       0  4359.9     .16       0
  4982.3     .07       0  4989.2     .16       0
Bank Sta=4982.3,4989.2
XS Rating Curve= 0 ,0
Exp/Cntr=0.3,0.1

Type RM Length L Ch R = 1 ,144269  ,332,332,332
BEGIN DESCRIPTION:
SF PEREZ CREEK 192.0
END DESCRIPTION:
XS GIS Cut Line= 3
      1981231.97     13676746.27        1980325.       13676675.
      1979730.19     13676681.16
#Sta/Elev= 30
  4123.1  989.86  4250.5   980.1  4328.2  975.25  4333.2  975.47  4400.9   971.6
  4457.3  967.78  4462.3  968.06  4586.3  961.26  4591.5  959.62  4631.6  960.42
  4674.1  959.67    4752   957.6  4828.3  956.71  4892.4  954.62  4922.5  952.51
  4952.6  952.32  4989.3  949.46  4989.8  948.66  4995.7  948.66  4996.2  949.46
  5002.8  950.12  5030.4  955.13  5047.5  955.71  5162.9   956.5  5242.9  959.27
  5336.6  964.67  5392.9  967.95  5422.4  970.69  5516.7  977.25  5627.7  986.98
#Mann= 8 ,-1 , 0
  4123.1     .16       0  4674.1      .1       0  4828.3     .16       0
  4989.3     .07       0  4996.2     .16       0  5047.5      .1       0
  5336.6     .16       0  5422.4      .1       0
Bank Sta=4989.3,4996.2
XS Rating Curve= 0 ,0
Exp/Cntr=0.3,0.1

Type RM Length L Ch R = 1 ,143937  ,345,345,345
BEGIN DESCRIPTION:
SF PEREZ CREEK 191.0
END DESCRIPTION:
XS GIS Cut Line= 3
       1981158.2     13676481.51        1980575.       13676425.
      1979918.45     13676481.37
#Sta/Elev= 30
  4369.7  980.96    4393  979.55  4413.1   979.4  4473.4  975.65  4493.8  973.38
  4513.6  972.16  4583.9   969.3  4697.9  963.01  4744.7  959.74  4802.3  956.88
    4825  955.62  4896.5  954.42  4958.1  953.35  4965.7  951.71  4972.2  947.16
  4972.7  946.36  4978.7  946.36  4979.2  947.16  4995.8  948.89  5017.5  949.64
  5044.9  951.74  5086.1  952.94  5166.4  953.12  5377.2  956.16  5437.4  958.55
  5517.7   963.2  5557.8  966.55  5595.8  970.62  5600.8  970.47  5614.6  972.45
#Mann= 6 ,-1 , 0
  4369.7     .16       0  4802.3      .1       0  4896.5     .16       0
  4972.2     .07       0  4979.2     .16       0  5044.9      .1       0
Bank Sta=4972.2,4979.2
XS Rating Curve= 0 ,0
Exp/Cntr=0.3,0.1

Type RM Length L Ch R = 1 ,143592  ,242,242,242
BEGIN DESCRIPTION:
SF PEREZ CREEK 190.0
END DESCRIPTION:
XS GIS Cut Line= 3
      1981210.21     13676381.67       1980580.9     13676155.99
      1979734.53     13676212.41
#Sta/Elev= 30
  4143.5  980.59  4206.2   975.9  4240.7   973.7  4269.1  970.95  4294.5  969.39
  4393.4  966.02  4442.9  963.27  4633.6   955.5  4850.8  951.98  4908.2  951.32
  4928.2   948.9  4947.3  948.54  4978.3  948.48  5004.9  946.33  5005.4  945.53
  5011.4  945.53  5011.9  946.33    5018  946.76  5028.4   949.5  5038.5  950.13
  5108.6  952.26  5148.7  954.83  5173.4  955.05  5208.8  957.99  5228.9  958.91
    5289  959.43  5323.7  961.21  5499.5  973.03  5579.6   977.1  5660.3  983.47
#Mann= 8 ,-1 , 0
  4143.5     .16       0  4206.2      .1       0  4240.7     .16       0
  4633.6      .1       0  4850.8     .16       0  4947.3      .1       0
  5004.9     .07       0  5011.9      .1       0
Bank Sta=5004.9,5011.9
XS Rating Curve= 0 ,0
Exp/Cntr=0.3,0.1

Type RM Length L Ch R = 1 ,143350  ,335,335,335
BEGIN DESCRIPTION:
SF PEREZ CREEK 189.0
END DESCRIPTION:
XS GIS Cut Line= 3
      1981301.39     13676173.35      1980923.78     13675956.34
      1979748.78     13675943.33
#Sta/Elev= 30
  3976.2  972.37  3988.1  971.82  4017.7   970.7  4117.8  965.98  4184.3  963.57
  4361.3  958.21  4404.5  957.69  4540.5  954.26  4839.4  950.06  4920.5  949.28
  4930.5  950.07  4950.5  949.26  4960.5  948.17  4981.3   943.9  4981.8   943.1
  4987.8   943.1  4988.3   943.9  5000.5   944.1  5010.5  946.85  5028.5  949.92
  5040.6  951.03  5090.6  952.26  5130.6  956.46  5230.6  961.77  5250.6  964.09
  5330.6  965.78  5340.6  966.53  5380.6  966.37  5510.6  972.79  5586.8   977.3
#Mann= 9 ,-1 , 0
  3976.2      .1       0  3988.1     .16       0  4017.7      .1       0
  4117.8     .05       0  4184.3      .1       0  4839.4     .16       0
  4981.3     .07       0  4988.3     .16       0  5028.5      .1       0
Bank Sta=4981.3,4988.3
XS Rating Curve= 0 ,0
Exp/Cntr=0.3,0.1

Type RM Length L Ch R = 1 ,143015  ,221,221,221
BEGIN DESCRIPTION:
SF PEREZ CREEK 188.0
END DESCRIPTION:
XS GIS Cut Line= 4
      1981516.06     13676009.13      1980835.06     13675648.63
      1980329.17     13675626.47      1979751.93      13675704.6
#Sta/Elev= 30
  3827.7  968.96  3906.9  967.43  3982.3  964.76  4044.6  962.52  4172.2  959.95
    4550  953.54  4658.3  950.01  4838.5  949.18  4868.5  948.03  4877.7  946.37
  4888.6  944.65    4905   943.9  4905.6   943.1  4911.6   943.1  4912.1   943.9
  4921.2   943.9  5018.7   943.9  5078.7  950.73  5159.3  950.31  5205.1  953.19
  5210.1  954.09  5277.7  955.81  5282.7  956.71  5350.3  958.77  5361.1  960.02
  5421.6  960.64  5441.8  961.62  5472.1  960.74  5552.8  964.85  5687.1  968.99
#Mann= 7 ,-1 , 0
  3827.7      .1       0  3982.3     .05       0  4172.2      .1       0
  4877.7     .16       0    4905     .07       0  4912.1     .16       0
  4921.2      .1       0
Bank Sta=4905,4912.1
XS Rating Curve= 0 ,0
Exp/Cntr=0.3,0.1

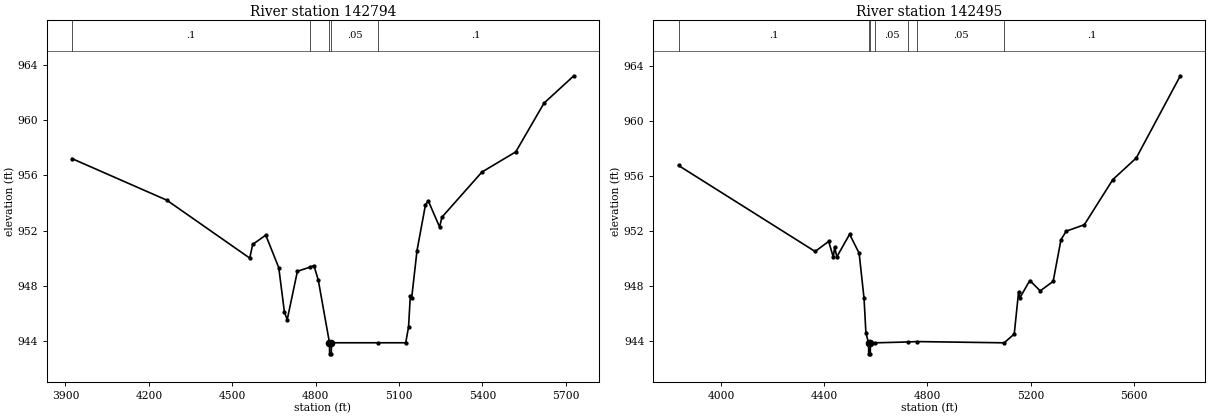
Type RM Length L Ch R = 1 ,142794  ,299,299,299
BEGIN DESCRIPTION:
SF PEREZ CREEK 187.0
END DESCRIPTION:
XS GIS Cut Line= 3
      1981529.07     13675640.21      1980894.56     13675487.44
      1979759.15     13675288.81
#Sta/Elev= 30
  3923.8  957.21  4264.4  954.21    4563  950.02  4573.6  951.01  4620.7  951.68
  4667.4  949.33  4687.7  946.13  4697.8  945.57  4734.5  949.07  4778.9  949.36
    4794  949.48  4809.5  948.44  4849.9   943.9  4850.4   943.1  4856.5   943.1
  4857.1   943.9  5023.6   943.9  5124.2   943.9  5134.4  945.05  5140.7  947.29
  5145.7  947.16  5164.8  950.56  5195.1  953.86  5205.4  954.16    5246  952.27
  5254.5  952.98  5398.3  956.24  5520.1   957.7  5621.6  961.22  5729.1   963.2
#Mann= 5 ,-1 , 0
  3923.8      .1       0  4778.9     .05       0  4849.9    .033       0
  4857.1     .05       0  5023.6      .1       0
Bank Sta=4849.9,4857.1
XS Rating Curve= 0 ,0
Exp/Cntr=0.3,0.1

Type RM Length L Ch R = 1 ,142495  ,63,63,63
BEGIN DESCRIPTION:
SF PEREZ CREEK 186.0
END DESCRIPTION:
XS GIS Cut Line= 6
      1981516.94     13675620.25      1980806.02     13675383.27
      1980759.14     13675310.36      1980548.21     13675130.67
      1980386.75     13675094.21      1979725.01       13675025.
#Sta/Elev= 30
  3835.9  956.77    4365  950.53  4417.7  951.26  4435.5  950.12  4440.8  950.84
  4449.3  950.14  4498.8  951.78  4535.7   950.4  4554.7  947.12    4562   944.6
  4572.2   943.9  4572.8   943.1  4578.9   943.1  4579.4   943.9  4598.2   943.9
  4723.1  943.96  4760.8  943.99  5097.7   943.9  5136.7  944.54  5153.6  947.61
  5158.6  947.17    5197  948.42  5237.3  947.67  5287.5  948.36  5317.7  951.38
  5337.8     952  5408.2  952.47  5518.8  955.75  5609.3  957.31  5780.2  963.28
#Mann= 7 ,-1 , 0
  3835.9      .1       0  4572.2    .035       0  4579.4      .1       0
  4598.2     .05       0  4723.1     .16       0  4760.8     .05       0
  5097.7      .1       0
Bank Sta=4572.2,4579.4
XS Rating Curve= 0 ,0
Exp/Cntr=0.3,0.1