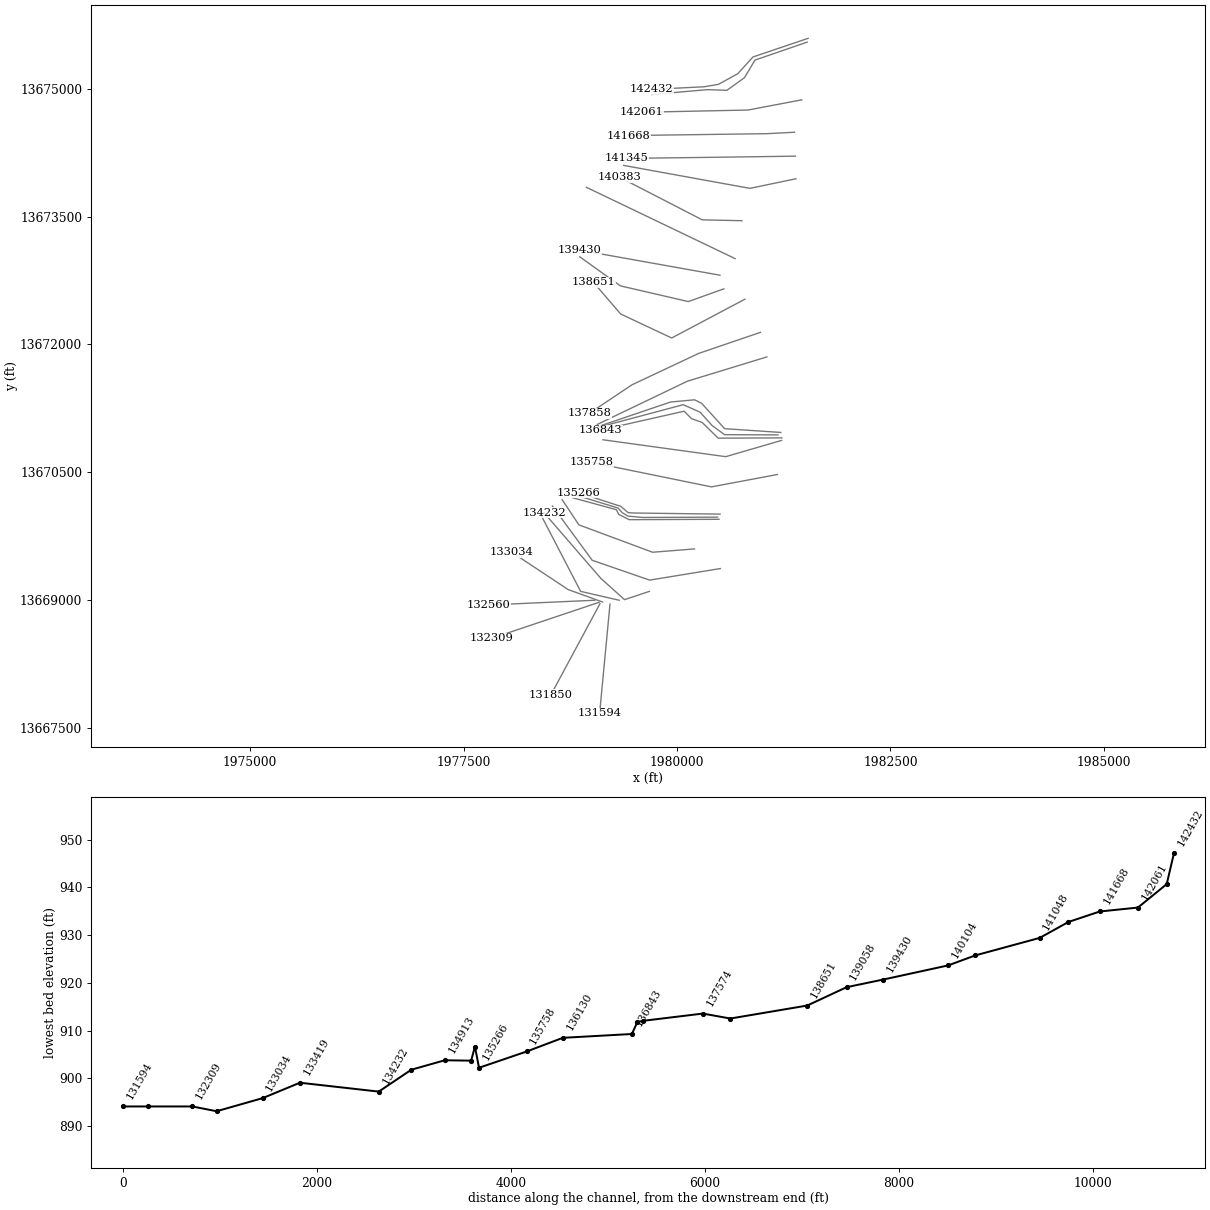
HEC-RAS study SF PEREZ CREEK.prj: SF PEREZ CREEK Base Level Engineering

--- SF PEREZ CREEK.g01 (geometry) --- (continued)

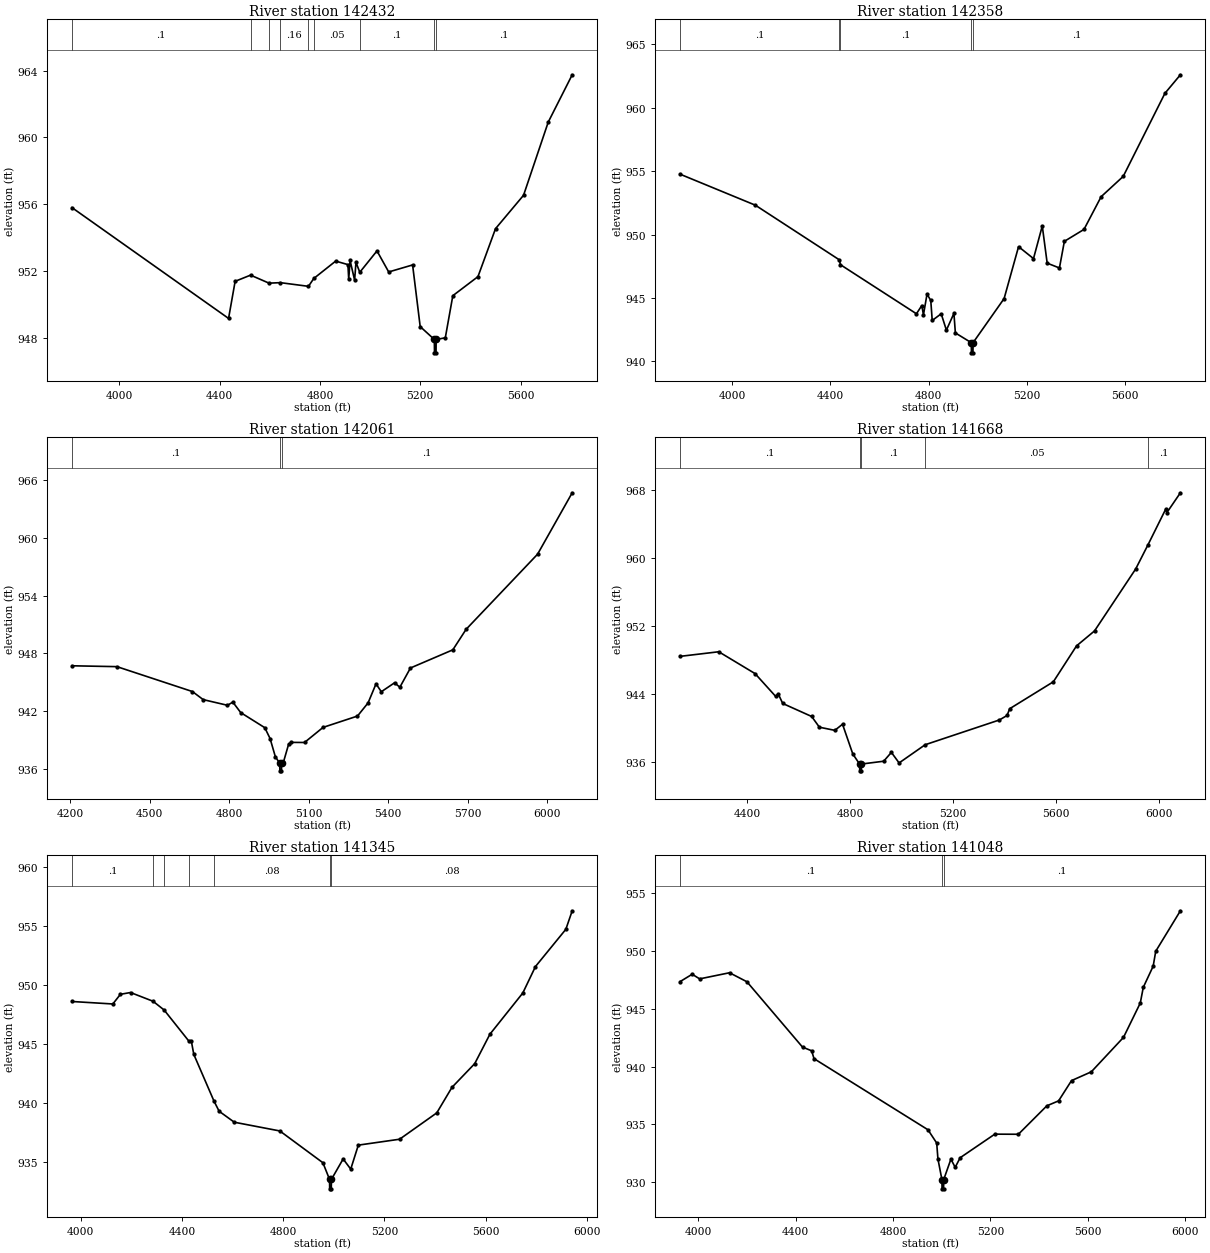
Type RM Length L Ch R = 1 ,142432  ,74,74,74
BEGIN DESCRIPTION:
Mapping XS 276f0d5c
END DESCRIPTION:
XS GIS Cut Line= 6
      1981535.14     13675588.99      1980889.35     13675370.25
      1980712.27     13675174.94      1980485.71     13675049.94
      1980319.04     13675021.29      1979699.63     13674990.06
#Sta/Elev= 30
  3811.4   955.8  4435.7  949.17  4461.9  951.39  4523.4  951.76  4597.1  951.28
  4642.3  951.31  4754.3  951.09  4775.5  951.56  4862.8   952.6  4911.6  952.39
  4914.8  951.51  4920.2  952.64  4938.3  951.46  4943.7  952.53  4958.9  951.93
  5027.5  953.21  5074.2  951.95  5169.5  952.37  5199.8  948.68  5256.2  947.91
  5256.8  947.11  5262.9  947.11  5263.4  947.91  5299.9  948.01  5329.9  950.53
  5430.1  951.67  5500.1  954.54  5611.9  956.54  5710.4  960.92  5805.9  963.75
#Mann= 9 ,-1 , 0
  3811.4      .1       0  4523.4     .05       0  4597.1      .1       0
  4642.3     .16       0  4754.3      .1       0  4775.5     .05       0
  4958.9      .1       0  5256.2     .07       0  5263.4      .1       0
Bank Sta=5256.2,5263.4
XS Rating Curve= 0 ,0
Exp/Cntr=0.3,0.1

Type RM Length L Ch R = 1 ,142358  ,297,297,297
BEGIN DESCRIPTION:
Mapping XS 3340fe94
END DESCRIPTION:
XS GIS Cut Line= 6
      1981524.73     13675544.72      1980912.79     13675333.79
      1980790.39     13675128.07      1980584.66     13674979.63
       1980355.5     13674987.44      1979701.87     13674930.15
#Sta/Elev= 30
  3787.3  954.76  4093.8  952.32  4436.4  948.01  4440.7  947.63  4750.7  943.76
  4772.7  944.41  4779.3  943.67  4793.9  945.31  4809.2  944.81  4815.1  943.23
  4851.7  943.76  4872.9  942.47  4903.6  943.79  4909.5  942.25  4974.5  941.48
    4975  940.68  4981.2  940.68  4981.7  941.48  5108.3  944.96  5167.2  949.05
  5228.1  948.11  5263.9  950.68  5283.9  947.75  5333.9  947.37    5354  949.47
    5434  950.41    5504  952.99    5594  954.59  5764.1  961.14  5827.2   962.6
#Mann= 5 ,-1 , 0
  3787.3      .1       0  4436.4     .05       0  4440.7      .1       0
  4974.5     .07       0  4981.7      .1       0
Bank Sta=4974.5,4981.7
XS Rating Curve= 0 ,0
Exp/Cntr=0.3,0.1

Type RM Length L Ch R = 1 ,142061  ,393,393,393
BEGIN DESCRIPTION:
Mapping XS 7ffb0de1
END DESCRIPTION:
XS GIS Cut Line= 3
       1981461.8     13674868.08      1980831.63     13674748.29
      1979584.26     13674722.25
#Sta/Elev= 30
  4206.2   946.7    4376  946.61    4661  944.02  4701.7  943.18  4793.3  942.59
  4813.7  942.92  4843.4  941.83  4934.3  940.26  4954.3  939.13  4974.3  937.23
  4990.7  936.57  4991.2  935.77  4997.4  935.77  4997.9  936.57  5004.3  936.63
  5024.3  938.54  5034.3  938.73  5084.3  938.72  5154.4  940.29  5284.4  941.47
  5324.4  942.84  5354.4  944.82  5374.4     944  5424.4  944.93  5444.4  944.47
  5484.4  946.47  5644.5  948.36  5694.5  950.49  5964.5  958.31  6095.3   964.7
#Mann= 3 ,-1 , 0
  4206.2      .1       0  4990.7     .07       0  4997.9      .1       0
Bank Sta=4990.7,4997.9
XS Rating Curve= 0 ,0
Exp/Cntr=0.3,0.1

Type RM Length L Ch R = 1 ,141668  ,323,323,323
BEGIN DESCRIPTION:
SF PEREZ CREEK 185.0
END DESCRIPTION:
XS GIS Cut Line= 3
      1981375.91     13674487.88       1981045.6     13674470.95
      1979430.99     13674449.25
#Sta/Elev= 30
  4138.8  948.41  4288.8  948.95  4430.1  946.38  4510.2   943.7  4520.2  943.99
  4537.6  942.87  4650.2  941.34  4680.2  940.08  4740.2  939.71  4770.2  940.43
  4810.2  936.93  4836.5  935.75  4837.1  934.95  4843.3  934.95  4843.8  935.75
  4930.2  936.08  4960.2  937.12  4990.2  935.88  5091.7  938.02  5380.2  940.93
  5410.2  941.46  5420.2  942.25  5590.2  945.42  5680.3  949.64  5750.3   951.4
  5910.3  958.68    5958  961.51  6026.7  965.69  6031.7  965.31  6084.3  967.64
#Mann= 5 ,-1 , 0
  4138.8      .1       0  4836.5     .07       0  4843.8      .1       0
  5091.7     .05       0    5958      .1       0
Bank Sta=4836.5,4843.8
XS Rating Curve= 0 ,0
Exp/Cntr=0.3,0.1

Type RM Length L Ch R = 1 ,141345  ,297,297,297
BEGIN DESCRIPTION:
SF PEREZ CREEK 184.0
END DESCRIPTION:
XS GIS Cut Line= 3
      1981386.36     13674207.49      1980451.42     13674194.47
      1979409.83     13674181.45
#Sta/Elev= 30
  3965.2  948.62  4126.6  948.41  4156.6  949.23  4196.6  949.38  4285.5  948.64
  4329.3   947.9  4427.7  945.25  4436.6  945.29  4446.6  944.14  4526.1   940.2
  4546.6  939.33  4606.6   938.4  4786.6  937.66  4956.7  934.97    4983  933.56
  4983.5  932.76  4989.8  932.76  4990.4  933.56  5036.7  935.29  5066.7  934.43
  5096.7  936.46  5259.8  936.96  5406.7  939.19  5466.7  941.35  5556.7  943.36
  5616.7  945.85  5746.7  949.34  5796.7  951.58  5916.7  954.73  5941.9   956.3
#Mann= 7 ,-1 , 0
  3965.2      .1       0  4285.5     .08       0  4329.3     .15       0
  4427.7      .1       0  4526.1     .08       0    4983     .07       0
  4990.4     .08       0
Bank Sta=4983,4990.4
XS Rating Curve= 0 ,0
Exp/Cntr=0.3,0.1

Type RM Length L Ch R = 1 ,141048  ,665,665,665
BEGIN DESCRIPTION:
SF PEREZ CREEK 183.0
END DESCRIPTION:
XS GIS Cut Line= 3
      1981393.28     13673942.74      1980855.06     13673829.89
      1979375.05     13674098.98
#Sta/Elev= 30
  3926.4  947.35  3975.7  947.98  4006.4  947.58    4129  948.11  4200.5  947.33
  4428.7  941.68  4466.2  941.36    4476  940.68  4943.9  934.53  4979.8  933.38
  4984.9     932  5001.2  930.22  5001.8  929.42  5008.1  929.42  5008.6  930.22
  5038.2  931.99  5055.7  931.28  5076.1  932.11  5218.4  934.15  5315.2  934.14
  5432.1   936.6  5480.4  937.03  5533.4  938.78  5614.7  939.54  5746.9  942.52
  5815.8  945.49  5828.2  946.85  5868.8  948.68  5879.3  949.97  5980.6  953.47
#Mann= 3 ,-1 , 0
  3926.4      .1       0  5001.2     .07       0  5008.6      .1       0
Bank Sta=5001.2,5008.6
XS Rating Curve= 0 ,0
Exp/Cntr=0.3,0.1

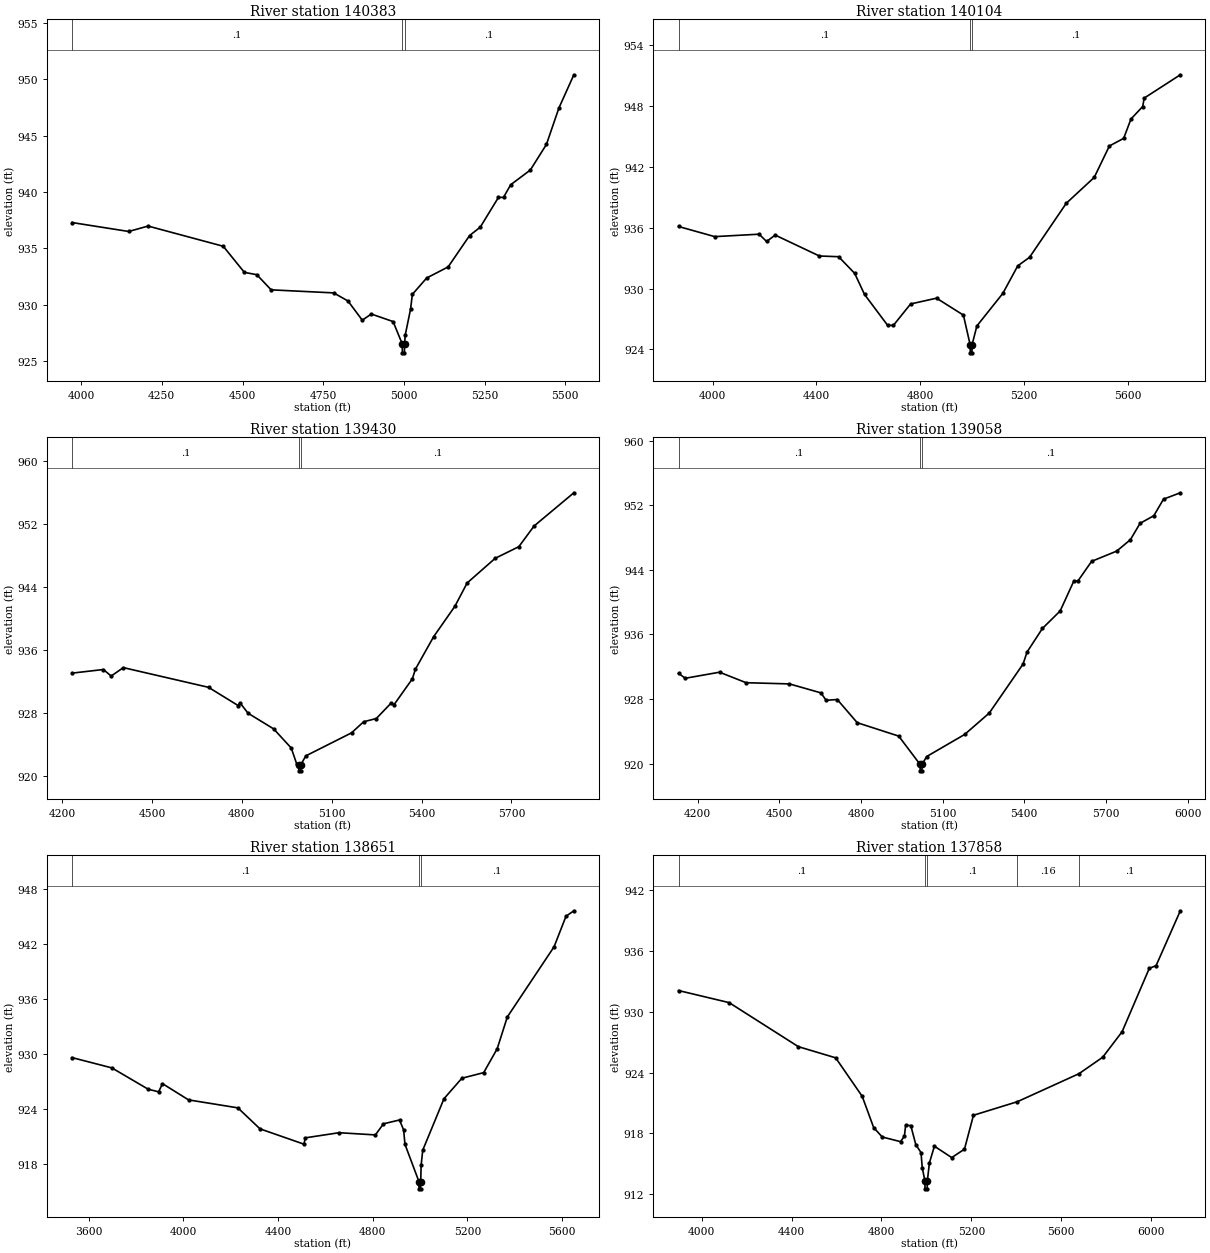
Type RM Length L Ch R = 1 ,140383  ,279,279,279
BEGIN DESCRIPTION:
Mapping XS cf102be5
END DESCRIPTION:
XS GIS Cut Line= 3
      1980760.47     13673450.55      1980295.17     13673460.97
      1979327.39     13673960.46
#Sta/Elev= 30
    3972  937.29  4147.5   936.5  4207.5  936.98  4440.3  935.19  4505.7  932.88
  4544.4  932.67  4588.7  931.33  4782.5  931.06  4826.8  930.34  4871.1  928.64
    4899  929.19  4966.5  928.52  4994.7  926.55  4995.3  925.75  5001.6  925.75
  5002.1  926.55  5004.1  927.32  5020.6  929.62  5026.2  930.93  5070.5  932.38
    5137  933.36  5203.5  936.14  5236.5  936.88  5292.9  939.52  5308.6  939.52
  5330.8  940.64  5391.6  941.94  5441.5  944.21  5480.2  947.44  5526.5  950.38
#Mann= 3 ,-1 , 0
    3972      .1       0  4994.7     .07       0  5002.1      .1       0
Bank Sta=4994.7,5002.1
XS Rating Curve= 0 ,0
Exp/Cntr=0.3,0.1

Type RM Length L Ch R = 1 ,140104  ,674,674,674
BEGIN DESCRIPTION:
Mapping XS 89d484e5
END DESCRIPTION:
XS GIS Cut Line= 2
      1980680.57     13673006.11      1978938.79      13673842.3
#Sta/Elev= 30
  3868.8  936.12  4008.1  935.12  4179.1  935.36  4207.8  934.64    4241  935.27
  4411.1  933.21  4485.1  933.14    4547   931.5  4584.9  929.42  4673.7  926.38
  4695.8  926.36  4762.4  928.48  4862.2  929.05  4965.7  927.38  4991.6  924.46
  4992.2  923.66  4998.5  923.66  4999.1  924.46  5017.5  926.31  5117.4  929.52
    5175  932.24  5220.3  933.08  5361.8  938.41  5469.4  940.96  5527.8  944.06
  5582.7  944.81  5610.9  946.72  5656.1  947.95  5661.7  948.78  5800.9  951.08
#Mann= 3 ,-1 , 0
  3868.8      .1       0  4991.6     .07       0  4999.1      .1       0
Bank Sta=4991.6,4999.1
XS Rating Curve= 0 ,0
Exp/Cntr=0.3,0.1

Type RM Length L Ch R = 1 ,139430  ,372,372,372
BEGIN DESCRIPTION:
Mapping XS 2ef0813e
END DESCRIPTION:
XS GIS Cut Line= 2
       1980503.5     13672811.66      1978854.19      13673106.8
#Sta/Elev= 30
  4233.1  933.08  4337.7  933.54  4363.6  932.71  4404.3  933.78  4688.7  931.28
  4788.3  928.95  4793.4  929.33  4820.8  927.99    4906  926.01  4964.9  923.58
  4983.3  921.54  4989.7  921.48  4990.3  920.68  4996.7  920.68  4997.3  921.48
  5013.6  922.58  5166.2   925.5  5206.8  926.91    5249  927.32  5297.7  929.25
  5308.4  929.09  5369.4  932.36  5379.5  933.58  5440.5  937.71  5511.6  941.58
  5552.2  944.52  5645.8  947.65  5724.9  949.13  5775.7  951.75  5908.6  955.97
#Mann= 3 ,-1 , 0
  4233.1      .1       0  4989.7     .07       0  4997.3      .1       0
Bank Sta=4989.7,4997.3
XS Rating Curve= 0 ,0
Exp/Cntr=0.3,0.1

Type RM Length L Ch R = 1 ,139058  ,407,407,407
BEGIN DESCRIPTION:
Mapping XS 165ad4ae
END DESCRIPTION:
XS GIS Cut Line= 4
      1980548.66     13672651.95      1980131.97     13672502.63
      1979336.83     13672686.66      1978861.11     13673026.96
#Sta/Elev= 30
  4129.7  931.17  4154.8  930.57  4280.3  931.32  4377.9  930.02  4537.3  929.87
  4652.9  928.76  4671.9  927.84  4712.9  927.94  4786.2  925.07  4938.7  923.41
  5017.1  919.91  5017.7  919.11  5024.1  919.11  5024.7  919.91  5041.4  920.88
  5180.8  923.61  5271.3  926.26  5395.6  932.33  5410.3  933.82  5466.8  936.74
  5531.9   938.9  5582.3  942.62  5597.1  942.61  5647.4  945.04  5739.6  946.31
  5789.9  947.72  5825.6  949.75    5876  950.69  5911.6  952.74  5973.4  953.53
#Mann= 3 ,-1 , 0
  4129.7      .1       0  5017.1     .07       0  5024.7      .1       0
Bank Sta=5017.1,5024.7
XS Rating Curve= 0 ,0
Exp/Cntr=0.3,0.1

Type RM Length L Ch R = 1 ,138651  ,793,793,793
BEGIN DESCRIPTION:
SF PEREZ CREEK 180.0
END DESCRIPTION:
XS GIS Cut Line= 4
      1980795.19     13672530.42      1979937.53     13672075.55
      1979340.31      13672356.8      1979020.88      13672728.3
#Sta/Elev= 30
  3529.1  929.57  3697.1  928.45    3851  926.12    3895  925.84  3911.3  926.73
  4021.3  924.96  4229.9  924.09  4323.5   921.8  4509.3  920.13  4514.8  920.82
  4657.5  921.38  4811.1  921.14  4845.4  922.35  4913.3  922.77  4930.6  921.67
  4936.1  920.12  4995.1  916.06  4995.7  915.26  5002.1  915.26  5002.7  916.06
  5004.5  917.82  5011.2  919.47  5101.1  925.09  5176.7  927.32  5268.8  927.93
  5325.9  930.53  5368.7     934  5566.5  941.66  5616.7  944.98    5650  945.58
#Mann= 3 ,-1 , 0
  3529.1      .1       0  4995.1     .07       0  5002.7      .1       0
Bank Sta=4995.1,5002.7
XS Rating Curve= 0 ,0
Exp/Cntr=0.3,0.1

Type RM Length L Ch R = 1 ,137858  ,284,284,284
BEGIN DESCRIPTION:
SF PEREZ CREEK 179.0
END DESCRIPTION:
XS GIS Cut Line= 4
      1980976.39     13672141.51      1980254.19     13671894.99
      1979472.94     13671526.94      1978969.77     13671190.33
#Sta/Elev= 30
  3897.4  932.08  4122.4  930.89  4430.4  926.55  4596.3  925.45  4714.3  921.66
  4765.4  918.58  4803.3  917.65  4884.8  917.19  4902.1  917.72  4907.6   918.8
  4930.4  918.78  4953.2  916.87    4976  916.12  4981.5  914.62  4993.2  913.34
  4993.9  912.54  5003.5  912.54  5004.3  913.34  5013.3  915.09  5035.5  916.74
  5112.7  915.62  5169.3  916.45  5209.3  919.79    5405  921.13    5679  923.89
  5784.3  925.51  5870.5  928.02  5991.5  934.27  6021.6  934.53  6129.5  939.94
#Mann= 5 ,-1 , 0
  3897.4      .1       0  4993.2     .07       0  5004.3      .1       0
    5405     .16       0    5679      .1       0
Bank Sta=4993.2,5004.3
XS Rating Curve= 0 ,0
Exp/Cntr=0.3,0.1

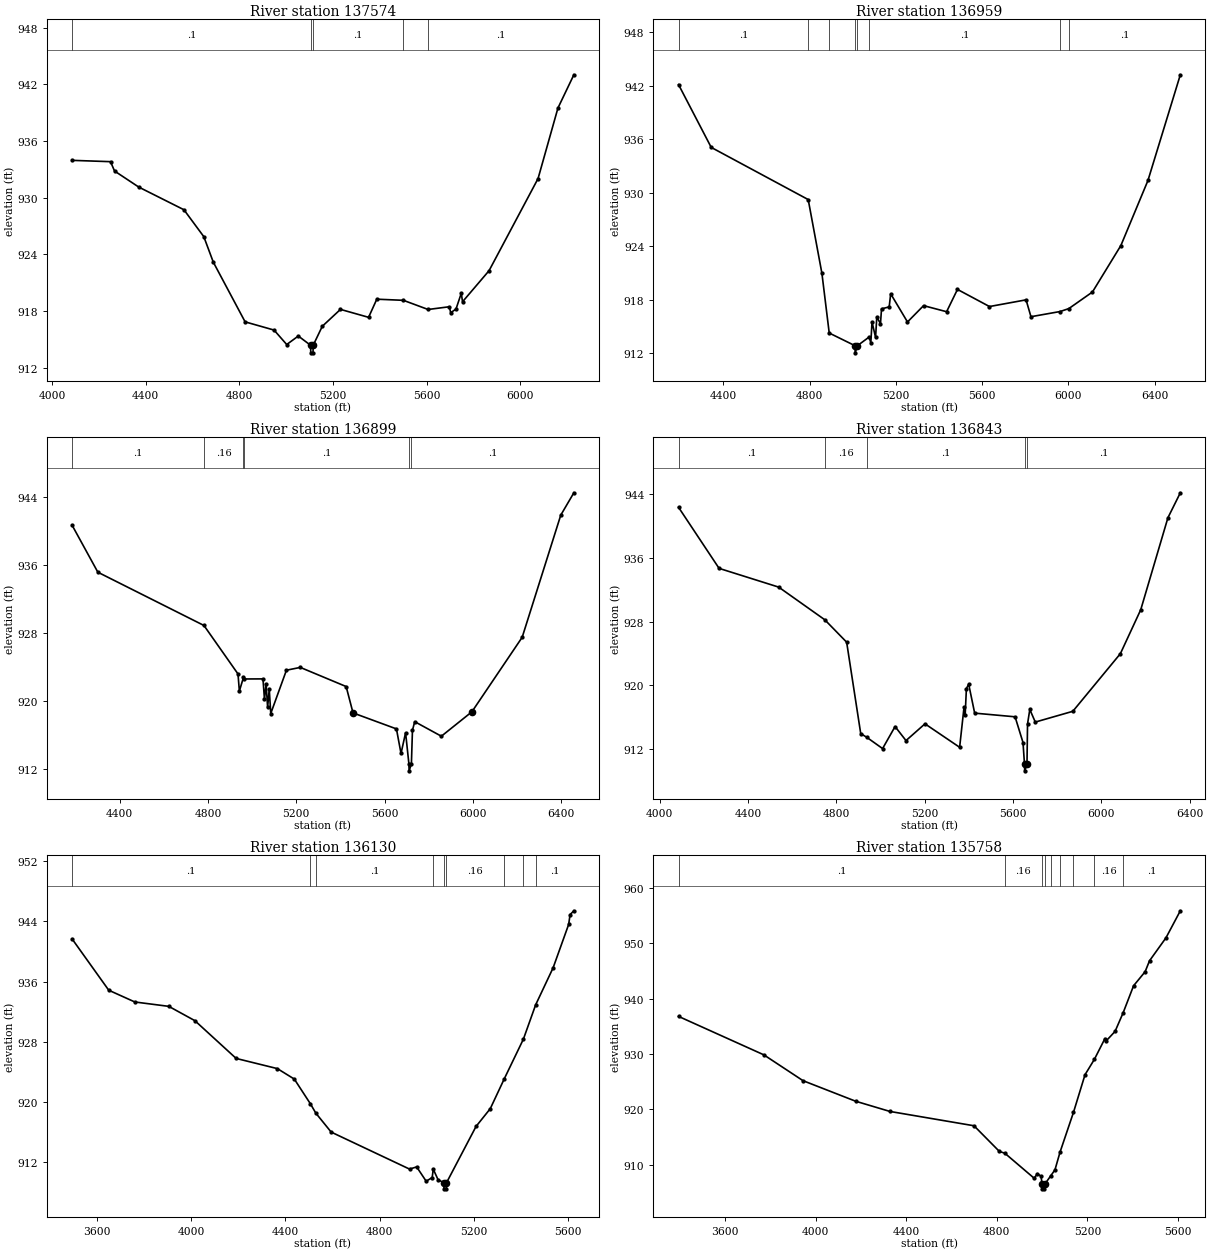
Type RM Length L Ch R = 1 ,137574  ,615,615,615
BEGIN DESCRIPTION:
SF PEREZ CREEK 178.0
END DESCRIPTION:
XS GIS Cut Line= 3
      1981052.06     13671853.55      1980121.53     13671568.84
      1979065.97     13671061.89
#Sta/Elev= 30
  4085.4  933.96  4249.7  933.82  4266.9  932.83  4370.4  931.13  4563.4  928.73
  4648.3  925.88  4688.9  923.18  4824.8  916.86  4948.5  915.99  5002.6  914.46
  5052.1  915.36  5104.6  914.38  5105.3  913.58    5115  913.58  5115.7  914.38
  5154.5  916.39  5232.2  918.18  5352.4  917.34  5387.5  919.26  5501.2  919.14
  5606.7  918.17  5697.6  918.46  5703.1  917.83  5725.8  918.21  5748.4  919.88
  5753.9  918.99  5867.2  922.28  6076.5  932.03  6161.5   939.5  6229.5  943.02
#Mann= 5 ,-1 , 0
  4085.4      .1       0  5104.6     .07       0  5115.7      .1       0
  5501.2     .16       0  5606.7      .1       0
Bank Sta=5104.6,5115.7
XS Rating Curve= 0 ,0
Exp/Cntr=0.3,0.1

Type RM Length L Ch R = 1 ,136959  ,60,60,60
BEGIN DESCRIPTION:
Mapping XS 5aded5de
END DESCRIPTION:
XS GIS Cut Line= 6
      1981216.12     13670968.14      1980557.29     13671012.41
      1980289.06     13671309.29      1980205.73     13671350.95
      1979924.48     13671324.91      1979089.24      13671041.3
#Sta/Elev= 30
  4192.4  942.13  4343.9  935.09  4793.6  929.24  4857.1  920.97    4891  914.28
  5010.5  912.86  5011.3  912.06  5021.7  912.86  5075.9  913.83  5083.8  913.19
  5089.4  915.52  5105.9  913.79  5111.5  916.07  5128.6  915.33  5133.5  916.99
    5169  917.21  5175.9  918.68  5253.8  915.52  5328.4  917.35  5435.2  916.67
  5485.5  919.17  5633.9  917.25  5803.6     918  5826.2  916.11  5961.2  916.69
  6001.8  917.02  6111.3  918.88  6243.1  924.09  6368.6  931.38  6518.7  943.23
#Mann= 8 ,-1 , 0
  4192.4      .1       0  4793.6     .16       0    4891     .05       0
  5010.5    .033       0  5021.7     .05       0  5075.9      .1       0
  5961.2     .16       0  6001.8      .1       0
Bank Sta=5010.5,5021.7
XS Rating Curve= 0 ,0
Exp/Cntr=0.3,0.1

Type RM Length L Ch R = 1 ,136899  ,56,56,56
BEGIN DESCRIPTION:
Mapping XS 1654ac3f
END DESCRIPTION:
XS GIS Cut Line= 6
      1981182.33      13670939.5      1980557.29      13670942.1
      1980411.46     13671048.87      1980270.83     13671205.12
      1980072.92     13671293.66      1979068.86     13671025.74
#Sta/Elev= 30
    4185   940.7  4301.8  935.17  4782.1  928.91  4936.3  923.21  4942.5   921.2
  4961.1   922.8  4964.4  922.62  5049.4  922.63  5056.2  920.21  5063.6  922.05
  5070.4  919.28  5077.8  921.44  5084.6  918.56  5155.6  923.65  5218.4  923.98
    5426  921.73  5457.1  918.63  5653.7  916.75  5674.4  913.86  5695.1   916.3
  5710.2  912.62    5711  911.82  5721.4  912.62  5726.2  916.59  5736.5   917.6
  5857.1  915.89  5995.3  918.76    6223  927.52  6397.7  941.88    6457  944.51
#Mann= 6 ,-1 , 0
    4185      .1       0  4782.1     .16       0  4961.1     .05       0
  4964.4      .1       0  5710.2     .07       0  5721.4      .1       0
Bank Sta=5457.1,5995.3
XS Rating Curve= 0 ,0
Exp/Cntr=0.3,0.1

Type RM Length L Ch R = 1 ,136843  ,713,713,713
BEGIN DESCRIPTION:
SF PEREZ CREEK 177.0
END DESCRIPTION:
XS GIS Cut Line= 6
      1981228.57     13670904.64      1980482.07     13670901.17
      1980294.57      13671085.2      1980169.57     13671130.34
      1980082.77     13671217.14      1979100.17     13670994.93
#Sta/Elev= 30
  4085.5  942.32  4269.1  934.67  4539.1  932.32  4747.7  928.23  4846.8  925.42
  4910.5  913.97  4937.4  913.51  5009.5  912.09  5066.1  914.85  5115.5  913.09
  5201.5  915.19  5358.4  912.25  5378.3  917.26  5383.4  916.26  5389.1  919.61
  5399.4  920.16  5426.5  916.53  5609.5  916.07  5645.4  912.85  5652.2   910.1
  5652.9   909.3  5663.4   910.1  5665.9  915.17  5676.2  916.99    5701  915.41
    5871  916.76  6086.3  923.98  6178.6  929.49  6301.6  941.01  6357.8  944.14
#Mann= 5 ,-1 , 0
  4085.5      .1       0  4747.7     .16       0  4937.4      .1       0
  5652.2     .07       0  5663.4      .1       0
Bank Sta=5652.2,5663.4
XS Rating Curve= 0 ,0
Exp/Cntr=0.3,0.1

Type RM Length L Ch R = 1 ,136130  ,372,372,372
BEGIN DESCRIPTION:
SF PEREZ CREEK 176.0
END DESCRIPTION:
XS GIS Cut Line= 3
      1981225.01       13670875.      1980570.62     13670684.16
      1979133.14     13670882.07
#Sta/Elev= 30
    3493  941.66  3648.9  934.85  3759.8  933.29  3904.1  932.71    4015  930.81
  4190.4   925.8  4365.6  924.45  4437.6  923.06  4505.8  919.79  4529.1  918.54
  4594.2  916.03  4927.3  911.12  4957.6  911.41    4998  909.51  5023.6     910
  5028.1  911.11  5048.4  909.72  5073.1   909.3  5073.8   908.5  5083.6   908.5
  5084.3   909.3    5210  916.78  5270.5  919.14  5330.3  923.12  5411.2  928.36
  5463.3  932.91  5537.6  937.83  5603.6  943.58  5609.6  944.88  5625.7  945.39
#Mann= 9 ,-1 , 0
    3493      .1       0  4505.8     .16       0  4529.1      .1       0
  5028.1     .16       0  5073.1     .07       0  5084.3     .16       0
  5330.3      .1       0  5411.2     .16       0  5463.3      .1       0
Bank Sta=5073.1,5084.3
XS Rating Curve= 0 ,0
Exp/Cntr=0.3,0.1

Type RM Length L Ch R = 1 ,135758  ,492,492,492
BEGIN DESCRIPTION:
SF PEREZ CREEK 175.0
END DESCRIPTION:
XS GIS Cut Line= 3
      1981174.98       13670475.      1980403.95     13670329.99
      1979002.88     13670616.45
#Sta/Elev= 30
  3395.4  936.81  3771.9  929.86  3944.8  925.19  4176.8  921.48  4328.3  919.63
  4699.4  917.04  4811.7  912.39  4835.1  912.09  4964.8  907.56  4979.4  908.39
  4995.4  907.89    5000  906.44  5000.7  905.64  5010.5  905.64  5011.2  906.44
  5037.3  907.95  5056.7  909.07    5079  912.26  5138.4  919.46  5189.4  926.27
  5230.6  929.04  5277.2   932.8  5282.3  932.36    5322   934.1  5357.8  937.48
  5403.7  942.35  5454.7  944.89    5474  946.86  5546.6  951.01    5610   955.9
#Mann= 9 ,-1 , 0
  3395.4      .1       0  4835.1     .16       0    5000     .07       0
  5011.2     .16       0  5037.3      .1       0    5079     .16       0
  5138.4      .1       0  5230.6     .16       0  5357.8      .1       0
Bank Sta=5000,5011.2
XS Rating Curve= 0 ,0
Exp/Cntr=0.3,0.1

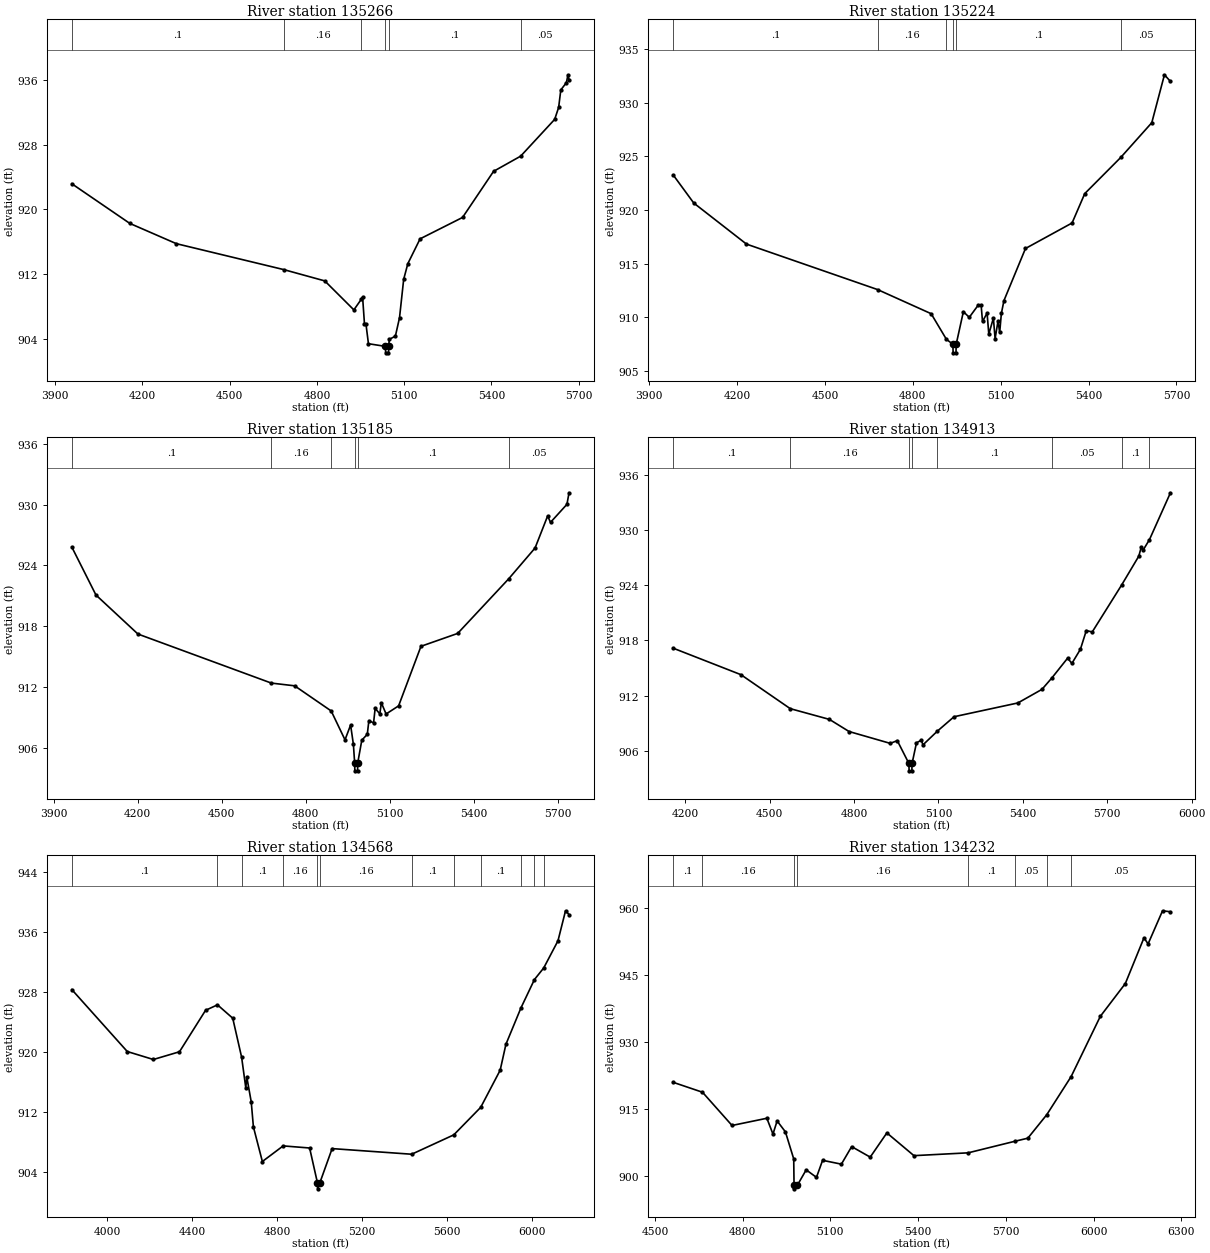
Type RM Length L Ch R = 1 ,135266  ,42,42,42
BEGIN DESCRIPTION:
Mapping XS 3265d8ac
END DESCRIPTION:
XS GIS Cut Line= 5
      1980504.25     13670010.55      1979497.26     13670023.57
      1979427.82     13670027.91      1979341.01     13670101.69
       1978848.1     13670261.67
#Sta/Elev= 30
  3957.8  923.17  4157.1  918.26  4317.1  915.75  4686.1  912.54  4827.1  911.14
  4927.1  907.55  4952.9  908.88  4957.1  909.14  4963.5  905.84  4968.5  905.84
  4977.2  903.36  5035.6  903.03  5036.3  902.23  5046.1  902.23  5046.8  903.03
  5048.9   903.9  5069.8   904.3    5084  906.58  5098.3  911.34  5112.6  913.28
  5154.7  916.35  5300.7     919  5407.2  924.71  5500.3  926.59  5617.3  931.15
  5630.9  932.63  5638.3  934.79  5657.6   935.7  5662.9  936.67  5666.6  936.04
#Mann= 6 ,-1 , 0
  3957.8      .1       0  4686.1     .16       0  4952.9      .1       0
  5035.6     .07       0  5046.8      .1       0  5500.3     .05       0
Bank Sta=5035.6,5046.8
XS Rating Curve= 0 ,0
Exp/Cntr=0.3,0.1

Type RM Length L Ch R = 1 ,135224  ,39,39,39
BEGIN DESCRIPTION:
SF PEREZ CREEK 174.0
END DESCRIPTION:
XS GIS Cut Line= 6
      1980474.96       13669975.      1979599.26     13669971.48
      1979427.82     13669986.67      1979360.55     13670025.74
      1979308.46     13670082.16       1978835.4     13670227.55
#Sta/Elev= 30
  3982.1  923.26  4052.1  920.65  4232.1  916.82  4679.6  912.58  4862.5  910.33
  4914.6  907.94  4936.8  907.48  4937.5  906.68  4947.3  906.68    4948  907.48
  4972.5  910.52  4992.6  909.99  5022.7  911.11  5033.2  911.11  5037.8  909.61
  5053.5  910.38  5059.3  908.42    5075  909.92  5080.8     908  5090.8  909.65
  5096.5  908.58  5102.2  910.35    5111  911.55  5184.5  916.41  5343.6  918.79
  5386.9  921.53  5509.7   924.9  5615.7  928.14  5658.9  932.61  5679.4  931.99
#Mann= 6 ,-1 , 0
  3982.1      .1       0  4679.6     .16       0  4914.6      .1       0
  4936.8     .07       0    4948      .1       0  5509.7     .05       0
Bank Sta=4936.8,4948
XS Rating Curve= 0 ,0
Exp/Cntr=0.3,0.1

Type RM Length L Ch R = 1 ,135185  ,272,272,272
BEGIN DESCRIPTION:
Mapping XS b8fdcf3b
END DESCRIPTION:
XS GIS Cut Line= 5
      1980491.19     13669949.78      1979440.84     13669945.44
      1979319.31     13670006.21      1979288.93     13670062.63
       1978781.1     13670201.52
#Sta/Elev= 30
  3964.3   925.8  4050.5  921.07  4200.5  917.22  4677.2  912.38  4760.5  912.11
  4891.1  909.63  4940.5  906.78  4960.5  908.24  4970.5  906.33  4974.9  904.52
  4975.6  903.72  4985.4  903.72  4986.1  904.52  5000.5  906.74  5020.2  907.33
  5025.8  908.68  5042.6  908.45  5048.2  909.88  5064.9  909.35  5070.5  910.43
  5087.3  909.33    5132  910.13    5212  916.01  5343.1  917.28  5525.8  922.68
  5619.7  925.71  5664.6  928.87  5674.9  928.24  5733.6  930.02  5741.1  931.16
#Mann= 6 ,-1 , 0
  3964.3      .1       0  4677.2     .16       0  4891.1      .1       0
  4974.9     .07       0  4986.1      .1       0  5525.8     .05       0
Bank Sta=4974.9,4986.1
XS Rating Curve= 0 ,0
Exp/Cntr=0.3,0.1

Type RM Length L Ch R = 1 ,134913  ,345,345,345
BEGIN DESCRIPTION:
Mapping XS 9baddf4c
END DESCRIPTION:
XS GIS Cut Line= 4
      1980204.71     13669602.56      1979714.28      13669563.5
      1978850.56     13669884.68      1978655.25     13670179.82
#Sta/Elev= 30
  4157.2  917.15  4397.7  914.27  4573.1  910.57  4712.4   909.4  4782.2  908.08
  4928.6  906.79  4953.6  907.09  4994.9   904.6  4995.6   903.8  5005.4   903.8
  5006.1   904.6  5021.8  906.85  5039.3  907.14  5044.7  906.62    5096  908.12
  5155.4  909.69  5382.2  911.19  5467.9  912.67  5503.8  913.94  5558.9  916.06
  5574.4   915.5  5604.5  917.03  5625.5  919.07  5646.6  918.92  5750.9  924.02
  5812.1  927.17  5821.1  928.18  5827.1  927.81    5850  928.97  5924.6  934.07
#Mann= 8 ,-1 , 0
  4157.2      .1       0  4573.1     .16       0  4994.9     .07       0
  5006.1     .16       0    5096      .1       0  5503.8     .05       0
  5750.9      .1       0    5850     .05       0
Bank Sta=4994.9,5006.1
XS Rating Curve= 0 ,0
Exp/Cntr=0.3,0.1

Type RM Length L Ch R = 1 ,134568  ,336,336,336
BEGIN DESCRIPTION:
SF PEREZ CREEK 173.0
END DESCRIPTION:
XS GIS Cut Line= 4
      1980506.63     13669372.23      1979679.04     13669236.71
      1979006.67     13669469.46      1978541.38     13670104.89
#Sta/Elev= 30
  3835.2  928.36  4095.9  920.11  4218.6  919.05  4341.3  920.08  4463.9   925.6
    4520  926.33  4591.7  924.55  4633.5  919.35    4653  915.29  4658.1  916.66
  4678.6  913.42  4688.9  910.07    4731  905.46  4828.8  907.54  4953.2  907.26
    4990  902.62  4990.7  901.82  5001.2  902.62    5059  907.18    5433  906.43
    5631  909.01  5757.7  912.68  5849.1  917.62  5876.2  921.08  5946.8  925.92
  6010.2   929.7  6053.8  931.24  6120.9  934.86  6156.4  938.86  6172.9  938.36
#Mann= 12 ,-1 , 0
  3835.2      .1       0    4520     .16       0  4633.5      .1       0
  4828.8     .16       0    4990     .07       0  5001.2     .16       0
    5433      .1       0    5631     .05       0  5757.7      .1       0
  5946.8     .08       0  6010.2      .1       0  6053.8     .05       0
Bank Sta=4990,5001.2
XS Rating Curve= 0 ,0
Exp/Cntr=0.3,0.1

Type RM Length L Ch R = 1 ,134232  ,813,813,813
BEGIN DESCRIPTION:
SF PEREZ CREEK 172.0
END DESCRIPTION:
XS GIS Cut Line= 4
      1979676.78     13669104.87      1979385.14     13669007.65
      1979107.36     13669257.65      1978440.67     13670028.51
#Sta/Elev= 30
  4562.7  921.02  4662.7  918.81  4763.7  911.39  4882.8     913  4903.7  909.47
  4917.9   912.4  4946.3  909.96  4974.7  903.92  4975.8  898.04  4976.5  897.24
  4987.1  898.04  5017.3  901.48  5052.5   899.8  5073.4  903.61  5137.7  902.75
  5172.8  906.67  5236.3  904.32  5293.2  909.73  5385.8  904.65  5571.2  905.28
  5730.3  907.85  5775.3  908.55    5840  913.79  5923.4  922.31  6023.2  935.76
  6108.7  943.08  6172.4  953.28  6186.6  951.94    6236  959.33    6263  959.11
#Mann= 8 ,-1 , 0
  4562.7      .1       0  4662.7     .16       0  4975.8     .07       0
  4987.1     .16       0  5571.2      .1       0  5730.3     .05       0
    5840      .1       0  5923.4     .05       0
Bank Sta=4975.8,4987.1
XS Rating Curve= 0 ,0
Exp/Cntr=0.3,0.1

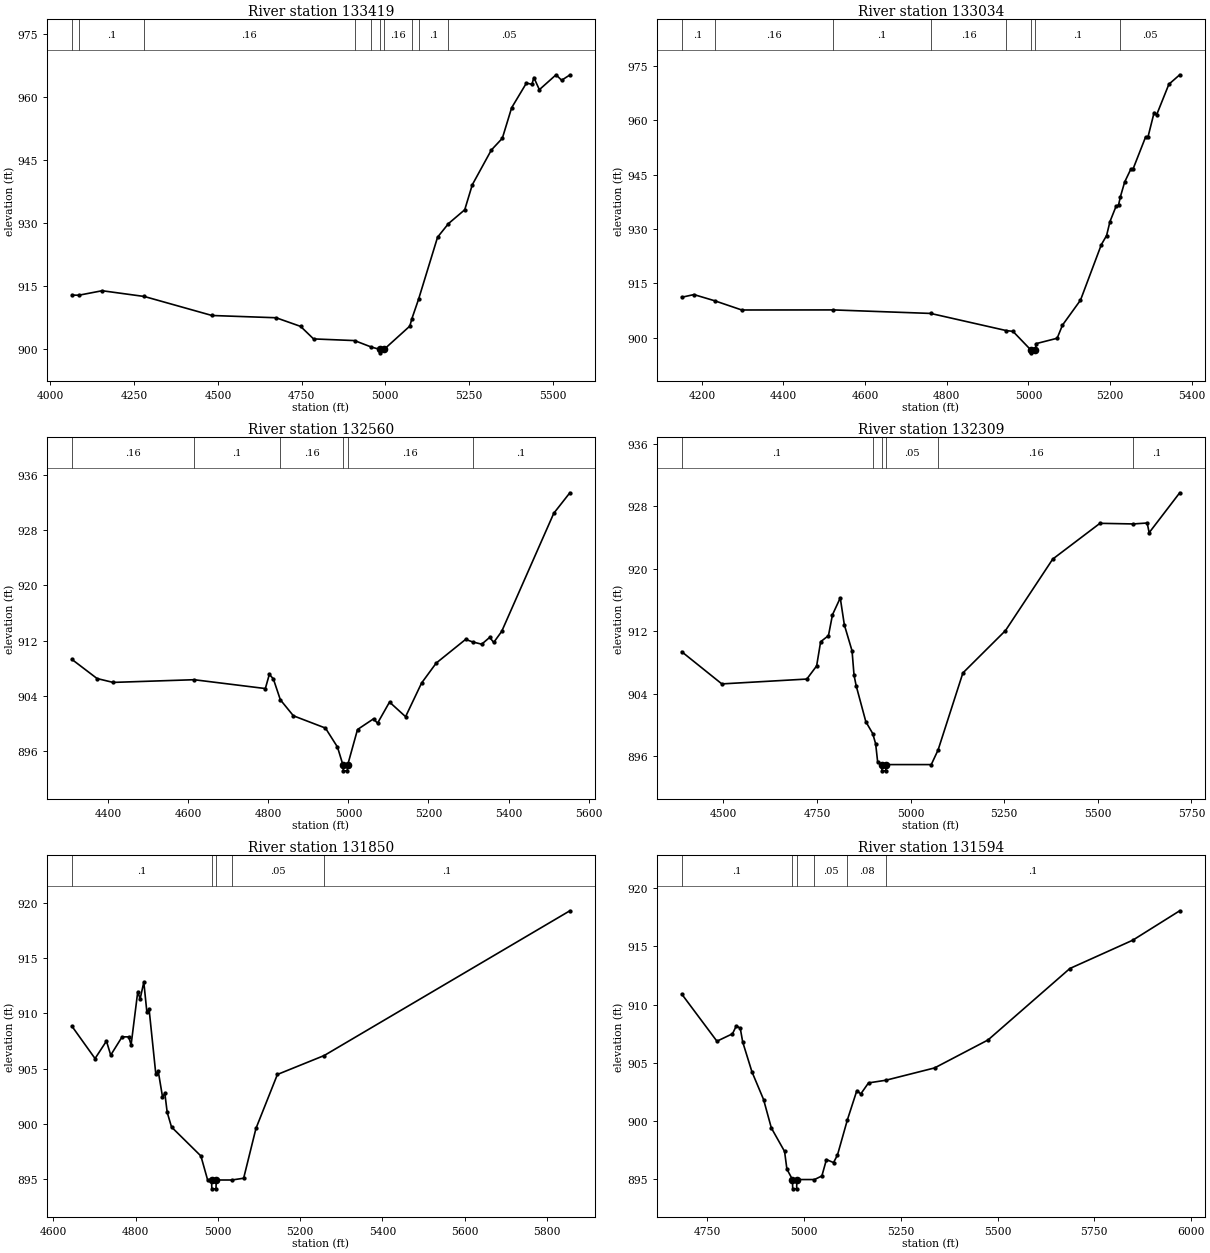
Type RM Length L Ch R = 1 ,133419  ,385,385,385
BEGIN DESCRIPTION:
Mapping XS 629aacbb
END DESCRIPTION:
XS GIS Cut Line= 3
      1979322.65      13669000.7      1978871.25     13669104.87
      1978399.51     13670013.67
#Sta/Elev= 30
  4063.9  912.86  4084.6  912.83  4154.3   913.9  4280.2  912.53  4482.3     908
  4673.8  907.46    4747   905.4  4785.6  902.42  4908.1  902.02  4958.5  900.47
  4984.6   899.9  4985.3   899.1  4995.9   899.9  5073.1  905.47  5079.4  907.26
  5099.2  911.86    5156  926.66  5188.6   929.9  5237.1  933.19  5259.7  939.15
  5316.5  947.42  5349.4  950.23  5377.2   957.5  5421.4  963.39  5437.9  963.08
  5443.5  964.71    5460  961.81  5509.9  965.36  5526.4  964.05  5551.1  965.32
#Mann= 10 ,-1 , 0
  4063.9     .16       0  4084.6      .1       0  4280.2     .16       0
  4908.1      .1       0  4958.5     .16       0  4984.6     .07       0
  4995.9     .16       0  5079.4     .08       0  5099.2      .1       0
  5188.6     .05       0
Bank Sta=4984.6,4995.9
XS Rating Curve= 0 ,0
Exp/Cntr=0.3,0.1

Type RM Length L Ch R = 1 ,133034  ,474,474,474
BEGIN DESCRIPTION:
Mapping XS 6bcce092
END DESCRIPTION:
XS GIS Cut Line= 3
      1979128.19     13668979.88      1978725.42     13669125.71
      1978065.67     13669563.23
#Sta/Elev= 30
  4150.7   911.2  4180.6  911.94  4231.2  910.24  4297.8  907.69  4522.5  907.71
  4760.5  906.74  4945.8  902.01  4962.2  901.79  5005.9  896.67  5006.6  895.87
  5017.2  896.67  5019.3  898.42  5070.4  899.89  5083.5  903.52  5127.6   910.4
  5178.7  925.72  5191.5  928.21  5199.8  932.07  5214.8  936.31  5220.8  936.65
  5225.5  938.98  5235.9  943.01  5250.9  946.54  5256.3  946.56    5287  955.38
    5293  955.43    5308  962.16    5314  961.49  5344.1  969.95  5370.7  972.57
#Mann= 8 ,-1 , 0
  4150.7      .1       0  4231.2     .16       0  4522.5      .1       0
  4760.5     .16       0  4945.8      .1       0  5005.9     .07       0
  5017.2      .1       0  5225.5     .05       0
Bank Sta=5005.9,5017.2
XS Rating Curve= 0 ,0
Exp/Cntr=0.3,0.1

Type RM Length L Ch R = 1 ,132560  ,251,251,251
BEGIN DESCRIPTION:
Mapping XS 70221408
END DESCRIPTION:
XS GIS Cut Line= 2
      1979037.94     13669000.71      1977794.88     13668945.15
#Sta/Elev= 30
    4309  909.29    4372  906.51    4412  905.95  4614.3  906.34  4792.4  905.06
  4802.4  907.12  4812.4  906.46  4829.9  903.43  4862.5  901.11  4942.6  899.33
  4972.6  896.58  4986.6  893.93  4987.3  893.13  4997.2  893.13  4997.9  893.93
  5022.7  899.12  5062.7  900.67  5072.7  900.03  5102.7   903.1  5142.8  900.98
  5182.8  905.86  5219.3  908.75  5292.9  912.19  5310.1  911.82    5333  911.49
    5353  912.48    5363  911.74    5383  913.35  5513.1  930.47  5553.3  933.44
#Mann= 6 ,-1 , 0
    4309     .16       0  4614.3      .1       0  4829.9     .16       0
  4986.6     .07       0  4997.9     .16       0  5310.1      .1       0
Bank Sta=4986.6,4997.9
XS Rating Curve= 0 ,0
Exp/Cntr=0.3,0.1

Type RM Length L Ch R = 1 ,132309  ,459,459,459
BEGIN DESCRIPTION:
Mapping XS 6ce2179f
END DESCRIPTION:
XS GIS Cut Line= 2
      1979086.56     13668976.41      1977826.14      13668552.8
#Sta/Elev= 30
  4388.9  909.38    4496  905.26  4722.9  905.88  4749.1  907.56  4759.8  910.66
  4780.7  911.44  4791.4  914.11  4812.2  916.27  4823.1  912.82  4843.7  909.49
    4849  906.37  4854.7  905.02  4880.5  900.42  4898.9   898.9  4906.7  897.59
    4912  895.29  4922.9  894.93  4923.6  894.13  4933.6  894.13  4934.2  894.93
  5055.2  894.93  5073.4   896.8  5139.6  906.66  5253.4  912.09  5379.5  921.24
  5505.6  925.82  5594.5  925.74  5631.7  925.86    5637  924.62  5718.6  929.73
#Mann= 6 ,-1 , 0
  4388.9      .1       0  4898.9     .05       0  4922.9     .07       0
  4934.2     .05       0  5073.4     .16       0  5594.5      .1       0
Bank Sta=4922.9,4934.2
XS Rating Curve= 0 ,0
Exp/Cntr=0.3,0.1

Type RM Length L Ch R = 1 ,131850  ,256,256,256
BEGIN DESCRIPTION:
Mapping XS 889953de
END DESCRIPTION:
XS GIS Cut Line= 2
      1979096.93       13668959.      1978524.05      13667893.1
#Sta/Elev= 30
  4645.4  908.84  4701.7  905.91  4729.4  907.49  4739.8  906.22  4767.4  907.87
  4783.6  907.87  4789.3  907.14  4805.5  911.96  4811.2  911.29  4820.2  912.82
  4827.5  910.16  4833.1  910.35  4849.4  904.49  4855.1   904.8  4865.6  902.46
  4871.3  902.76    4877  901.05  4887.5  899.72  4958.9   897.1  4975.2  894.94
  4984.8  894.93  4985.5  894.13  4995.6  894.13  4996.2  894.93  5034.4  894.93
  5062.8  895.09  5092.7  899.59  5144.8  904.47  5258.4  906.18  5855.5  919.27
#Mann= 5 ,-1 , 0
  4645.4      .1       0  4984.8     .07       0  4996.2      .1       0
  5034.4     .05       0  5258.4      .1       0
Bank Sta=4984.8,4996.2
XS Rating Curve= 0 ,0
Exp/Cntr=0.3,0.1

Type RM Length L Ch R = 1 ,131594  ,318,318,318
BEGIN DESCRIPTION:
Mapping XS 488befd9
END DESCRIPTION:
XS GIS Cut Line= 2
        1979215.     13668955.59      1979093.48     13667674.34
#Sta/Elev= 30
  4683.9   910.9  4774.9  906.84  4815.1  907.48  4825.1  908.17  4835.2  907.95
  4841.5  906.77  4865.3  904.21  4895.4  901.82  4915.5  899.37  4949.7  897.35
  4955.7  895.83  4970.1  894.93  4970.7  894.13  4980.8  894.13  4981.5  894.93
    5027  894.93  5046.1  895.24  5057.9  896.65  5076.2  896.39  5086.3  897.03
  5112.2  900.09  5136.5  902.59  5146.6   902.3  5166.6  903.25  5211.5  903.48
  5337.4  904.54  5475.6  906.95    5687   913.1  5849.7  915.54  5970.9  918.07
#Mann= 6 ,-1 , 0
  4683.9      .1       0  4970.1     .07       0  4981.5      .1       0
    5027     .05       0  5112.2     .08       0  5211.5      .1       0
Bank Sta=4970.1,4981.5
XS Rating Curve= 0 ,0
Exp/Cntr=0.3,0.1