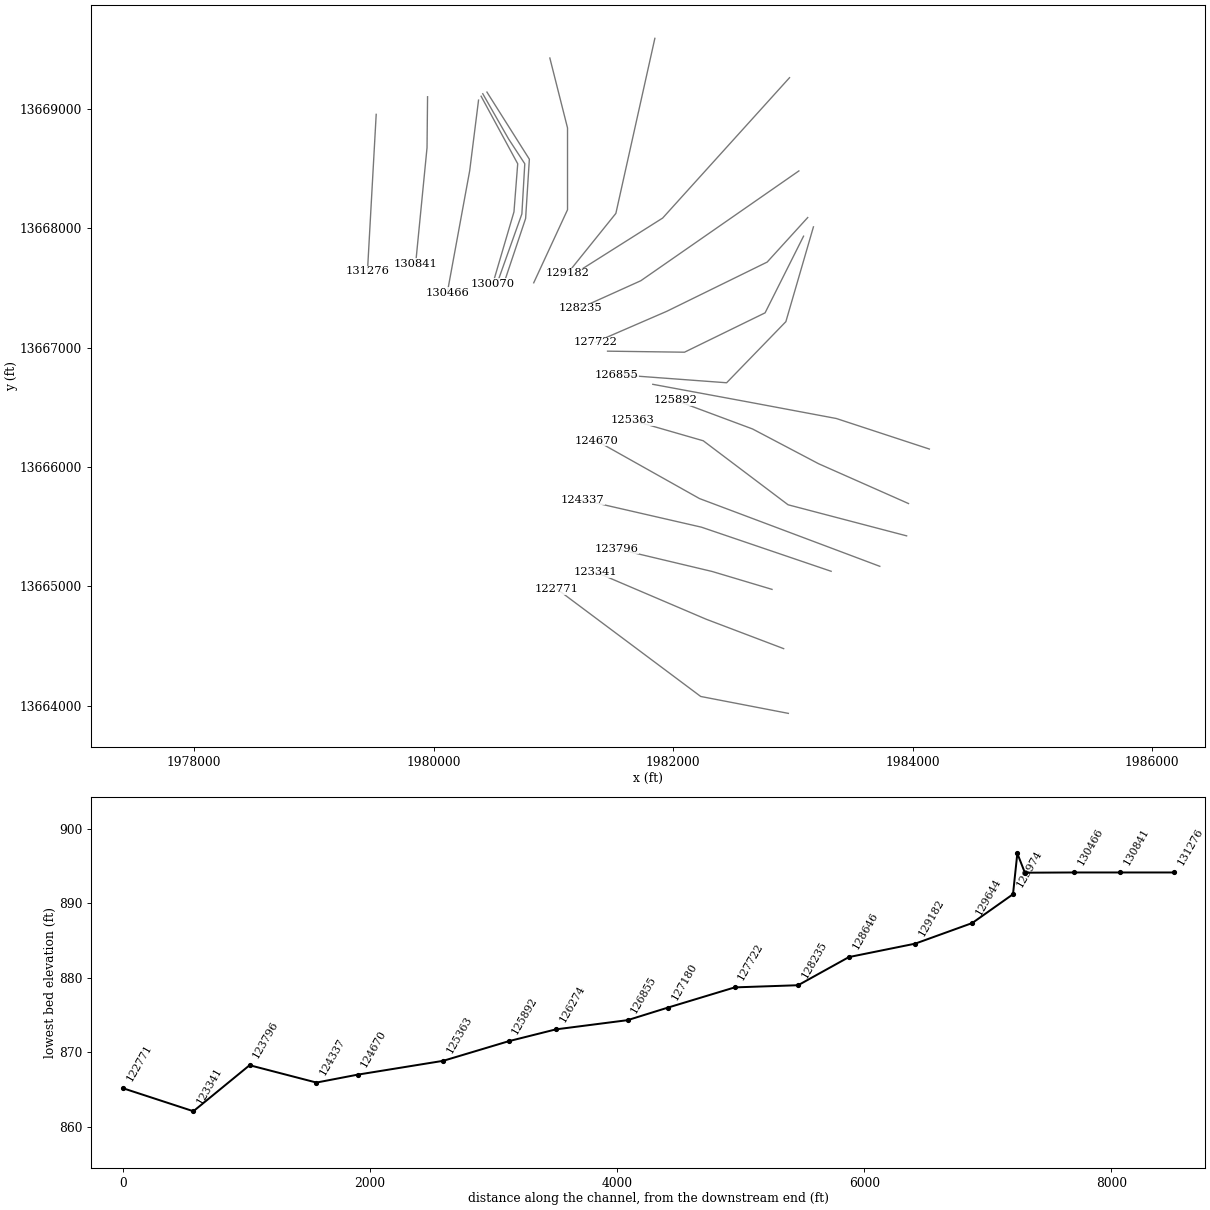
HEC-RAS study SF PEREZ CREEK.prj: SF PEREZ CREEK Base Level Engineering

--- SF PEREZ CREEK.g01 (geometry) --- (continued)

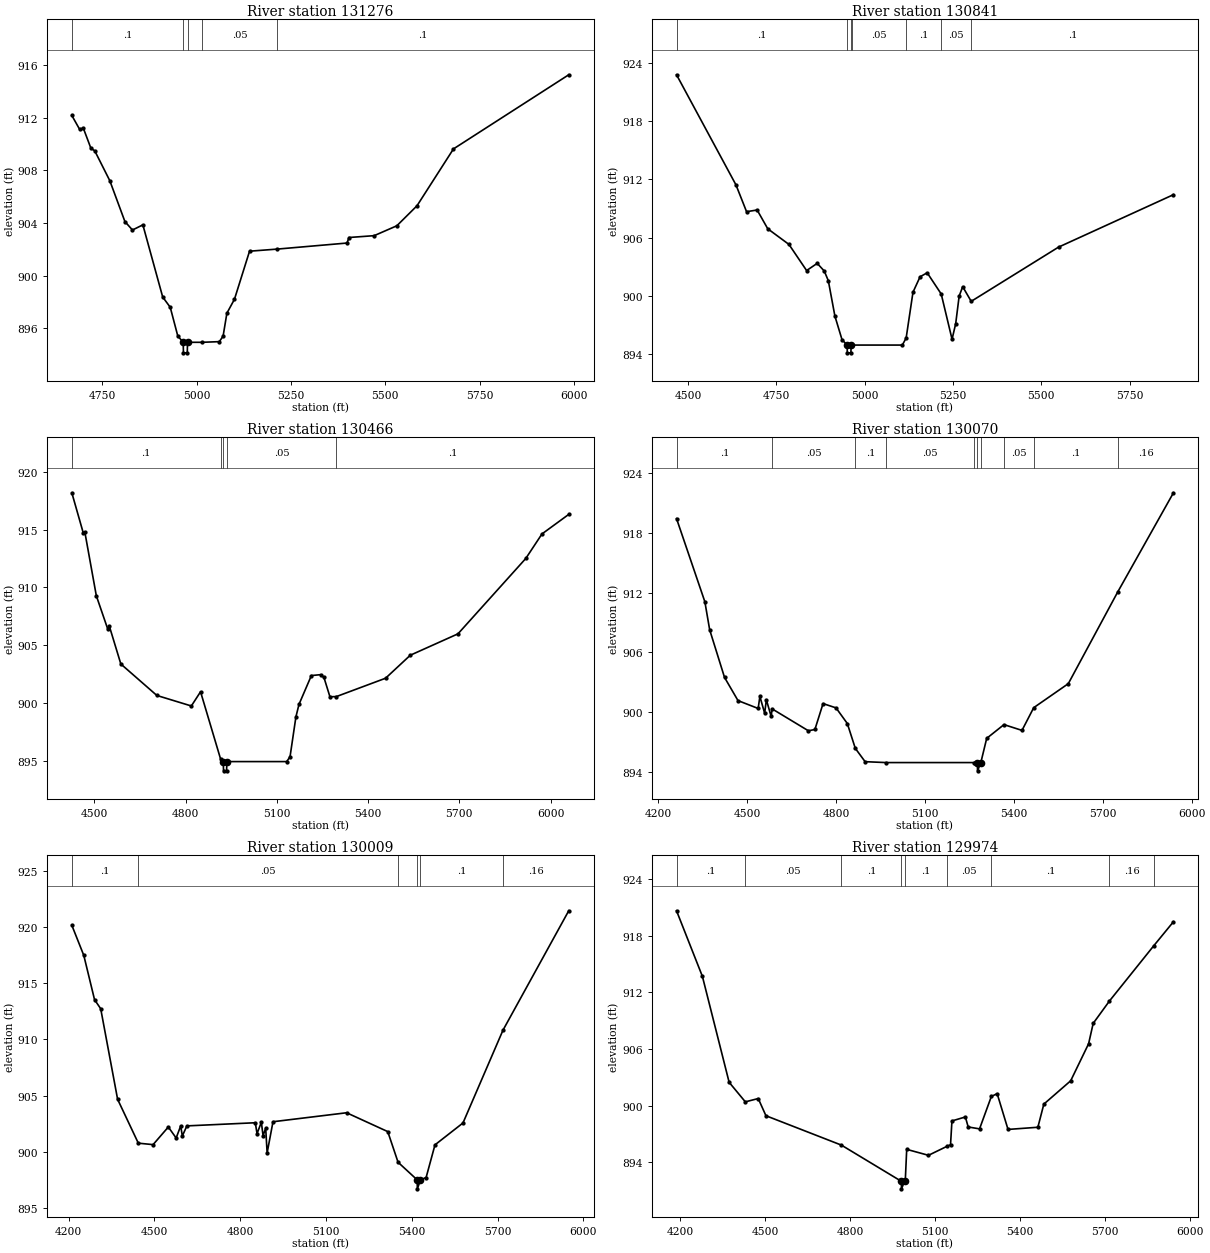
Type RM Length L Ch R = 1 ,131276  ,435,435,435
BEGIN DESCRIPTION:
Mapping XS fa59f674
END DESCRIPTION:
XS GIS Cut Line= 2
      1979520.56      13668955.6      1979447.65     13667639.82
#Sta/Elev= 30
  4668.8  912.16  4689.4  911.11  4699.4  911.19  4719.5  909.66  4729.5  909.48
  4769.6   907.2  4809.6   904.1  4829.6  903.46  4857.2  903.85  4909.8  898.37
  4929.8  897.59  4949.8  895.41  4964.2  894.93  4964.8  894.13    4975  894.13
  4975.6  894.93  5013.7  894.93    5060  894.98    5070   895.4    5080  897.14
  5100.1   898.2  5140.1  901.85  5213.5  902.01  5398.7  902.47  5403.7  902.89
  5470.6  903.03  5530.7  903.78  5584.2   905.3  5680.9  909.62  5986.6  915.25
#Mann= 5 ,-1 , 0
  4668.8      .1       0  4964.2     .07       0  4975.6      .1       0
  5013.7     .05       0  5213.5      .1       0
Bank Sta=4964.2,4975.6
XS Rating Curve= 0 ,0
Exp/Cntr=0.3,0.1

Type RM Length L Ch R = 1 ,130841  ,375,375,375
BEGIN DESCRIPTION:
SF PEREZ CREEK 171.0
END DESCRIPTION:
XS GIS Cut Line= 3
      1979949.38     13669103.16      1979944.97     13668676.91
      1979849.55     13667701.23
#Sta/Elev= 30
  4467.7  922.75  4635.9  911.42  4665.9  908.66  4695.9  908.83  4725.9   906.9
  4785.9  905.29  4835.9   902.6  4865.9  903.34  4885.9  902.55  4897.4  901.55
    4916  897.91  4936.1  895.49  4950.5  894.93  4951.1  894.13  4961.3  894.13
  4961.9  894.93  4963.7  894.93  5106.9  894.93  5117.7  895.66    5137  900.37
  5157.1  901.96  5177.2  902.37  5216.9  900.19  5247.6  895.53  5257.9  897.13
  5267.7  899.97  5277.7  900.94  5301.8  899.43    5549  905.01  5874.3  910.41
#Mann= 7 ,-1 , 0
  4467.7      .1       0  4950.5    .033       0  4961.9      .1       0
  4963.7     .05       0  5117.7      .1       0  5216.9     .05       0
  5301.8      .1       0
Bank Sta=4950.5,4961.9
XS Rating Curve= 0 ,0
Exp/Cntr=0.3,0.1

Type RM Length L Ch R = 1 ,130466  ,396,396,396
BEGIN DESCRIPTION:
SF PEREZ CREEK 170.0
END DESCRIPTION:
XS GIS Cut Line= 3
        1980375.     13669074.98      1980300.94     13668482.48
      1980114.31     13667462.53
#Sta/Elev= 30
  4425.8  918.18  4463.6  914.69  4468.6  914.78  4506.4  909.27  4544.2  906.37
  4549.2  906.64    4587  903.37  4705.4  900.65  4818.8  899.74  4849.1  900.97
    4915  895.15  4923.9  894.93  4924.6  894.13  4934.8  894.13  4935.4  894.93
  5132.2  894.93  5143.3  895.34  5162.7   898.8  5172.8  899.88  5213.5  902.37
    5244  902.45  5254.8  902.21  5274.5  900.54  5295.4  900.55  5457.5  902.14
  5538.8  904.13  5695.6  905.98  5918.6   912.5  5971.8  914.62  6059.8  916.31
#Mann= 5 ,-1 , 0
  4425.8      .1       0    4915     .05       0  4923.9    .033       0
  4935.4     .05       0  5295.4      .1       0
Bank Sta=4923.9,4935.4
XS Rating Curve= 0 ,0
Exp/Cntr=0.3,0.1

Type RM Length L Ch R = 1 ,130070  ,61,61,61
BEGIN DESCRIPTION:
Mapping XS 2bbbf15d
END DESCRIPTION:
XS GIS Cut Line= 4
      1980396.42     13669107.49      1980701.98     13668541.51
      1980670.73     13668138.73      1980493.64     13667534.53
#Sta/Elev= 30
  4261.8  919.42  4357.4  911.07  4373.6  908.26  4423.7  903.48  4469.2  901.15
  4537.3  900.36    4543  901.57  4559.2  899.88  4564.9  901.24  4581.1  899.56
  4584.3  900.32  4706.8  898.12  4728.7  898.25  4756.2  900.85    4800  900.42
  4838.1  898.85    4865  896.36  4898.1  895.02    4968  894.93  5265.1  894.93
  5276.9   894.9  5277.5   894.1  5288.4   894.9  5308.4  897.36  5366.7  898.74
  5427.5  898.16  5467.1  900.44  5583.8  902.85  5750.3  912.04  5938.6  922.01
#Mann= 10 ,-1 , 0
  4261.8      .1       0  4584.3     .05       0    4865      .1       0
    4968     .05       0  5265.1     .08       0  5276.9    .033       0
  5288.4     .08       0  5366.7     .05       0  5467.1      .1       0
  5750.3     .16       0
Bank Sta=5276.9,5288.4
XS Rating Curve= 0 ,0
Exp/Cntr=0.3,0.1

Type RM Length L Ch R = 1 ,130009  ,35,35,35
BEGIN DESCRIPTION:
SF PEREZ CREEK 169.0
END DESCRIPTION:
XS GIS Cut Line= 5
      1980410.33     13669128.29      1980625.59     13668749.84
      1980761.01     13668541.51       1980736.7     13668121.37
      1980525.01     13667525.04
#Sta/Elev= 30
  4211.2  920.18  4253.1  917.49  4290.6  913.55  4312.2  912.74  4371.3  904.67
  4443.7  900.76  4495.3  900.63  4548.6   902.2    4576  901.22  4591.9   902.3
  4597.6   901.4  4613.5   902.3  4852.8  902.58  4858.8  901.61  4873.9  902.62
  4879.9  901.43  4889.1  902.09  4894.1  899.89  4914.6  902.67    5172  903.47
  5315.9  901.79  5351.9  899.06  5418.8  897.49  5419.4  896.69  5430.3  897.49
    5450   897.7    5481  900.61  5578.9  902.56  5718.8  910.83  5948.7  921.47
#Mann= 6 ,-1 , 0
  4211.2      .1       0  4443.7     .05       0  5351.9      .1       0
  5418.8     .04       0  5430.3      .1       0  5718.8     .16       0
Bank Sta=5418.8,5430.3
XS Rating Curve= 0 ,0
Exp/Cntr=0.3,0.1

Type RM Length L Ch R = 1 ,129974  ,330,330,330
BEGIN DESCRIPTION:
Mapping XS 9d33236e
END DESCRIPTION:
XS GIS Cut Line= 4
      1980445.01     13669142.24       1980799.2      13668579.7
      1980767.95     13668083.17      1980580.45     13667520.66
#Sta/Elev= 30
  4186.1  920.65  4277.4  913.71  4371.9  902.49  4429.1  900.42  4474.7  900.77
  4501.9  898.95  4768.4  895.84  4980.1  892.01  4980.7  891.21  4991.6  892.01
  4994.1  892.07  4999.1  895.39    5076  894.76    5142  895.72  5153.9  895.88
  5158.9   898.4  5206.3  898.82  5216.3  897.76  5256.4  897.56  5298.1  900.99
  5318.6  901.29    5357   897.5  5462.4  897.73  5483.5  900.18  5578.3  902.65
  5641.6  906.57  5657.8  908.73  5715.3   911.1  5871.6  916.94  5941.3  919.49
#Mann= 9 ,-1 , 0
  4186.1      .1       0  4429.1     .05       0  4768.4      .1       0
  4980.1     .07       0  4991.6      .1       0    5142     .05       0
  5298.1      .1       0  5715.3     .16       0  5871.6      .1       0
Bank Sta=4980.1,4991.6
XS Rating Curve= 0 ,0
Exp/Cntr=0.3,0.1

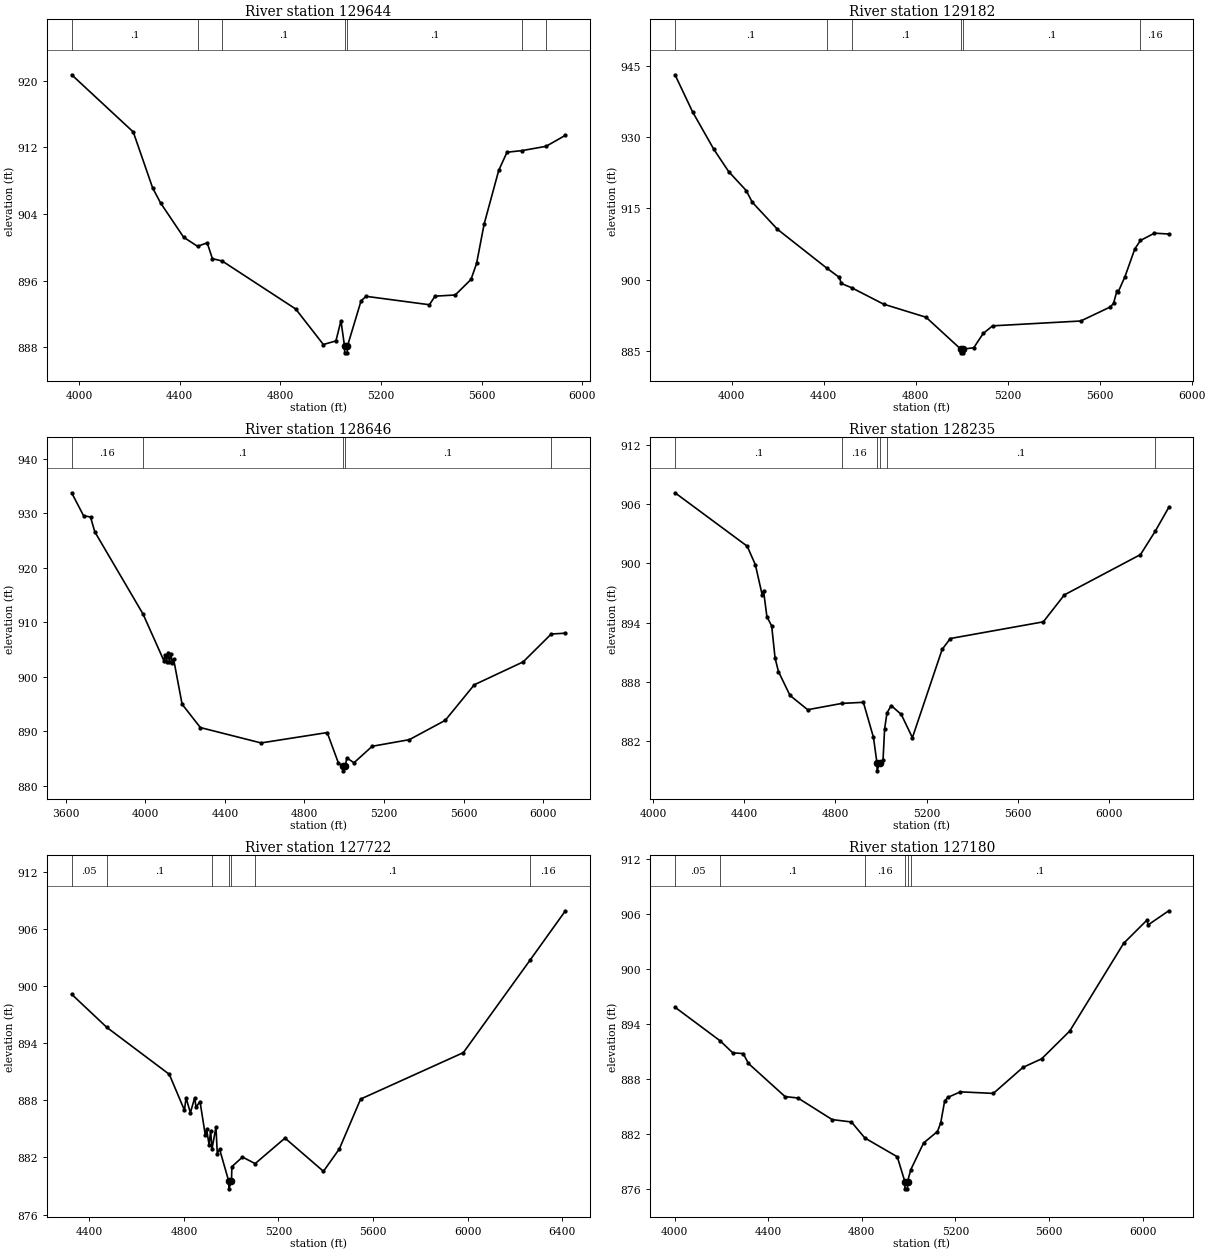
Type RM Length L Ch R = 1 ,129644  ,462,462,462
BEGIN DESCRIPTION:
SF PEREZ CREEK 168.0
END DESCRIPTION:
XS GIS Cut Line= 4
      1980970.21     13669427.78      1981117.78     13668841.85
      1981117.78     13668156.09      1980835.65     13667544.08
#Sta/Elev= 30
  3969.9   920.7  4214.9  913.84  4291.9  907.13  4323.4  905.33  4415.2  901.21
  4470.5  900.12    4509  900.54  4529.6  898.64  4568.4  898.36    4861   892.6
    4971  888.34    5021  888.77    5041  891.19  5055.2  888.14  5055.8  887.34
  5066.1  887.34  5066.7  888.14    5121  893.58    5141  894.12  5392.8  893.11
  5415.2  894.14  5495.6  894.28  5558.4  896.15  5580.4  898.06  5610.4  902.78
  5668.5  909.23  5701.5  911.41  5760.8   911.6    5857  912.12  5933.8  913.44
#Mann= 7 ,-1 , 0
  3969.9      .1       0  4470.5     .05       0  4568.4      .1       0
  5055.2     .07       0  5066.7      .1       0  5760.8     .16       0
    5857      .1       0
Bank Sta=5055.2,5066.7
XS Rating Curve= 0 ,0
Exp/Cntr=0.3,0.1

Type RM Length L Ch R = 1 ,129182  ,536,536,536
BEGIN DESCRIPTION:
SF PEREZ CREEK 167.0
END DESCRIPTION:
XS GIS Cut Line= 3
      1981846.94      13669592.7      1981521.43     13668125.71
      1981118.89     13667623.62
#Sta/Elev= 30
  3754.3  943.17  3830.6  935.36  3922.9  927.47  3987.5  922.77  4063.8  918.77
    4090  916.31  4199.7   910.6  4413.5  902.44    4469  900.45  4476.4  899.21
  4522.4  898.28    4661  894.83  4845.5  892.07  4995.9  885.37  4996.5  884.57
  5006.8  884.57  5007.4  885.37  5052.8  885.64  5093.8  888.65  5134.8  890.26
  5517.8  891.28  5645.9  894.23  5660.3  894.97  5674.7  897.55  5681.1  897.45
  5709.9   900.6  5753.1   906.5  5777.6  908.25  5837.9  909.79  5900.5  909.61
#Mann= 6 ,-1 , 0
  3754.3      .1       0  4413.5     .05       0  4522.4      .1       0
  4995.9     .07       0  5007.4      .1       0  5777.6     .16       0
Bank Sta=4995.9,5007.4
XS Rating Curve= 0 ,0
Exp/Cntr=0.3,0.1

Type RM Length L Ch R = 1 ,128646  ,411,411,411
BEGIN DESCRIPTION:
Mapping XS 7ffccda4
END DESCRIPTION:
XS GIS Cut Line= 3
       1982971.1     13669262.89      1981912.05     13668086.65
      1981152.52     13667604.88
#Sta/Elev= 30
  3629.7  933.79  3689.3  929.59  3724.4  929.34  3746.1  926.62  3988.6  911.53
  4092.9  903.01  4099.6  904.04  4107.1  902.78  4113.8  904.48  4121.3  902.71
    4128  904.27  4135.5   902.6  4142.2  903.27  4184.8     895  4276.7  890.71
  4581.7  887.89  4914.3  889.79  4971.1  884.16  4993.6  883.57  4994.2  882.77
  5005.2  883.57  5012.9  885.16  5048.8  884.25  5140.7  887.28  5327.4  888.49
  5507.9  892.04  5653.7  898.56  5899.4  902.76  6040.5  907.87  6111.9  908.03
#Mann= 5 ,-1 , 0
  3629.7     .16       0  3988.6      .1       0  4993.6     .07       0
  5005.2      .1       0  6040.5     .16       0
Bank Sta=4993.6,5005.2
XS Rating Curve= 0 ,0
Exp/Cntr=0.3,0.1

Type RM Length L Ch R = 1 ,128235  ,513,513,513
BEGIN DESCRIPTION:
Mapping XS 4ce48c01
END DESCRIPTION:
XS GIS Cut Line= 3
       1983049.2     13668481.61      1981729.76     13667561.47
      1981221.93     13667331.43
#Sta/Elev= 30
  4096.2  907.15  4412.9  901.74  4448.7  899.86  4478.4  896.83  4484.5  897.24
  4499.3  894.61  4520.3  893.66  4535.1  890.42  4549.9  889.05  4600.5  886.63
  4678.2  885.18  4828.4  885.82  4922.5  885.93  4966.9  882.37  4982.1  879.79
  4982.8  878.99  4993.7  879.79  5008.8  880.09  5015.7  883.25  5026.1  884.85
  5044.6   885.6  5088.8   884.7  5137.6  882.35    5268  891.28  5303.7  892.39
  5711.9  894.08  5804.3  896.81  6138.2  900.89  6202.2  903.23  6262.3  905.67
#Mann= 6 ,-1 , 0
  4096.2      .1       0  4828.4     .16       0  4982.1     .07       0
  4993.7     .16       0  5026.1      .1       0  6202.2     .16       0
Bank Sta=4982.1,4993.7
XS Rating Curve= 0 ,0
Exp/Cntr=0.3,0.1

Type RM Length L Ch R = 1 ,127722  ,542,542,542
BEGIN DESCRIPTION:
Mapping XS a397bb08
END DESCRIPTION:
XS GIS Cut Line= 4
      1983123.01       13668091.      1982784.45     13667717.72
      1981946.77      13667305.4      1981348.94     13667045.47
#Sta/Elev= 30
  4324.8  899.14  4473.6  895.66  4737.9  890.73  4802.1  886.96  4808.9  888.26
  4827.2  886.69  4845.5  888.27  4851.1  887.28    4868  887.87  4890.5  884.31
    4896  884.96  4906.2  883.33  4912.9  884.82  4918.6  882.89  4935.4  885.19
    4941  882.41  4950.7  882.87  4989.5   879.5  4990.1   878.7  5001.1   879.5
  5002.8  881.03  5047.7  882.04  5101.3  881.35  5227.5  884.03  5390.3  880.54
  5457.7   882.9  5547.6  888.13  5982.4  893.01  6264.8  902.73  6414.3  907.91
#Mann= 7 ,-1 , 0
  4324.8     .05       0  4473.6      .1       0  4918.6     .16       0
  4989.5     .07       0  5001.1     .16       0  5101.3      .1       0
  6264.8     .16       0
Bank Sta=4989.5,5001.1
XS Rating Curve= 0 ,0
Exp/Cntr=0.3,0.1

Type RM Length L Ch R = 1 ,127180  ,325,325,325
BEGIN DESCRIPTION:
Mapping XS 38d61f96
END DESCRIPTION:
XS GIS Cut Line= 4
      1983088.28     13667934.76      1982767.09     13667292.37
      1982094.34     13666962.51      1981451.97     13666971.19
#Sta/Elev= 30
  4002.2  895.81  4195.1  892.14  4248.9  890.83  4293.6  890.75    4316  889.67
  4472.5  886.05  4527.4   885.9  4673.8  883.54  4756.1  883.28  4813.5  881.53
    4952  879.48  4984.2  876.78  4984.8  875.98  4995.3  875.98  4995.9  876.78
    5010  878.09  5064.5  880.99  5123.7  882.24  5137.5  883.17  5154.5  885.58
  5168.2  885.97  5221.9  886.57  5362.5   886.4    5489  889.24    5569  890.18
    5689  893.21  5919.1  902.78  6018.9  905.32  6023.9   904.8  6112.1  906.34
#Mann= 6 ,-1 , 0
  4002.2     .05       0  4195.1      .1       0  4813.5     .16       0
  4984.2     .07       0  4995.9     .16       0    5010      .1       0
Bank Sta=4984.2,4995.9
XS Rating Curve= 0 ,0
Exp/Cntr=0.3,0.1

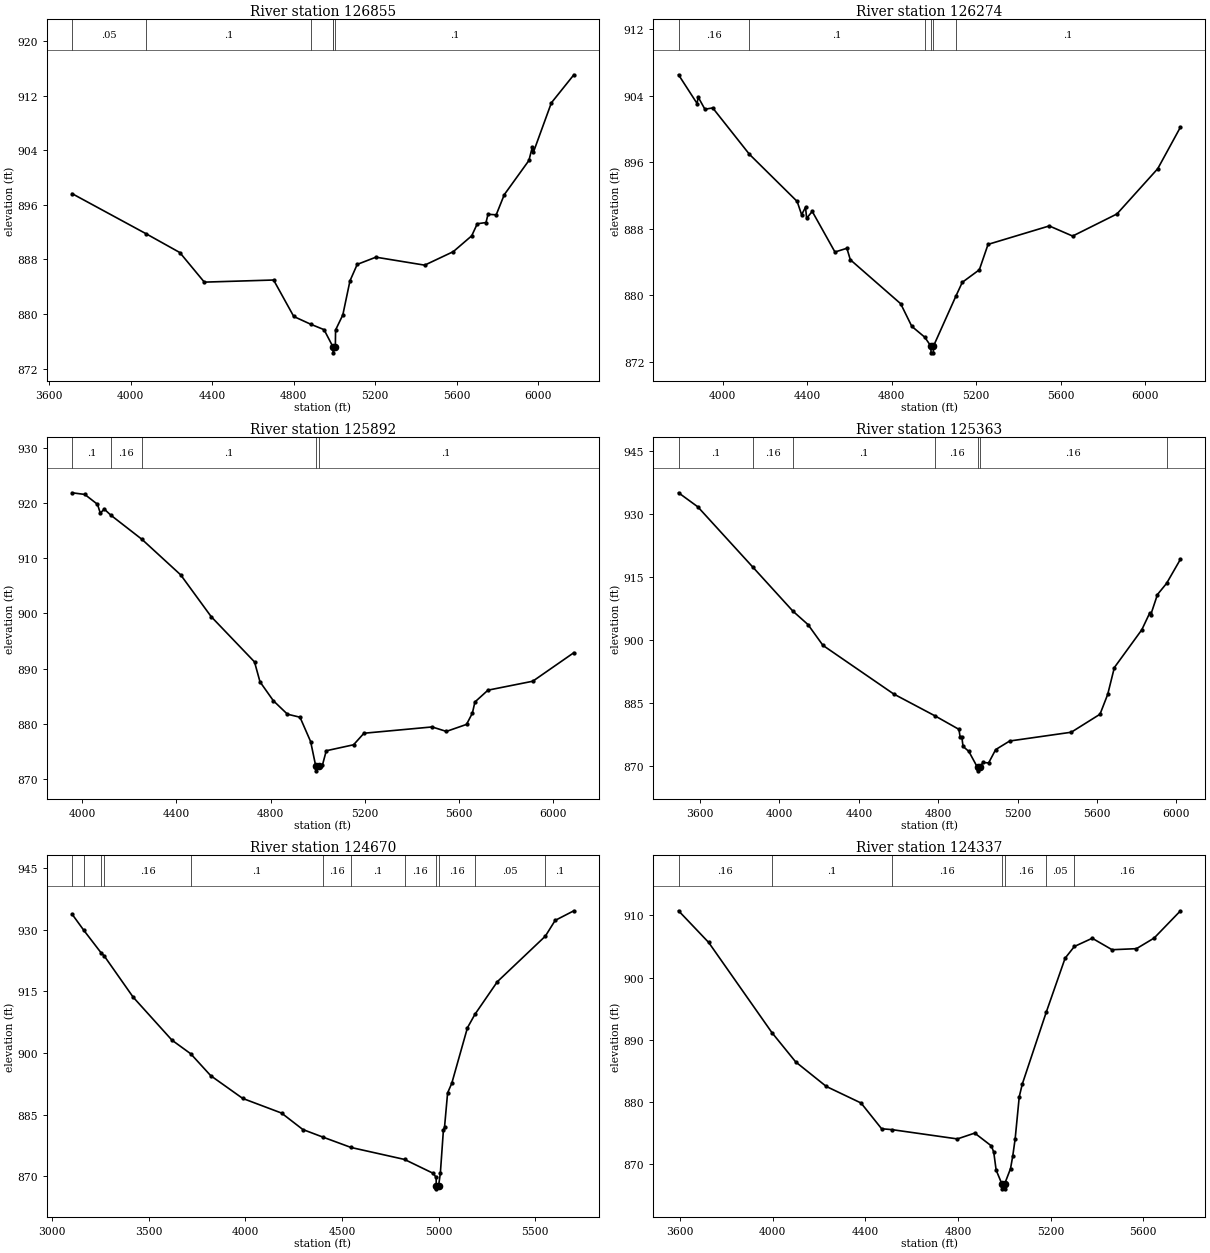
Type RM Length L Ch R = 1 ,126855  ,581,581,581
BEGIN DESCRIPTION:
SF PEREZ CREEK 163.0
END DESCRIPTION:
XS GIS Cut Line= 4
      1983170.73     13668012.84       1982940.7     13667218.59
       1982445.9     13666706.44      1981524.97       13666775.
#Sta/Elev= 30
  3712.7  897.65  4076.9  891.75  4241.4  889.01  4361.7  884.67  4701.7  884.98
  4800.7  879.63  4883.5   878.5  4949.2   877.7  4992.5  875.21    4993   875.1
  4993.6   874.3  5004.7   875.1  5005.8  877.65  5041.3  879.85  5076.5  884.86
    5112  887.27  5203.8  888.33  5443.1  887.16  5583.5  889.14  5673.8  891.46
  5701.3  893.23    5744  893.41    5754  894.62  5794.1  894.54  5833.8   897.5
  5954.6  902.51  5971.4  904.48  5976.4   903.7  6064.9  910.97  6175.2  915.08
#Mann= 6 ,-1 , 0
  3712.7     .05       0  4076.9      .1       0  4883.5     .16       0
  4992.5      .1       0    4993     .07       0  5004.7      .1       0
Bank Sta=4993,5004.7
XS Rating Curve= 0 ,0
Exp/Cntr=0.3,0.1

Type RM Length L Ch R = 1 ,126274  ,382,382,382
BEGIN DESCRIPTION:
SF PEREZ CREEK 162.0
END DESCRIPTION:
XS GIS Cut Line= 4
      1984138.59     13666150.89       1983361.7     13666406.96
      1982623.86     13666545.85      1981829.75     13666693.38
#Sta/Elev= 30
  3790.8  906.54  3878.7  903.08  3883.9  903.85  3915.7  902.39  3952.7  902.55
  4126.4  896.97  4352.6  891.29  4373.7  889.69  4392.2  890.59  4397.5  889.26
    4424  890.09  4531.6   885.2  4588.1  885.65  4604.4  884.27    4843  878.97
  4895.5  876.25  4956.7  874.95  4986.1  873.86  4986.6  873.06  4997.6  873.06
  4998.1  873.86  5103.7  879.85  5134.6  881.55  5215.4  883.06  5256.7  886.12
  5546.6  888.34  5657.3  887.12    5867  889.78  6060.3  895.23  6167.3  900.21
#Mann= 6 ,-1 , 0
  3790.8     .16       0  4126.4      .1       0  4956.7     .16       0
  4986.1     .07       0  4998.1     .16       0  5103.7      .1       0
Bank Sta=4986.1,4998.1
XS Rating Curve= 0 ,0
Exp/Cntr=0.3,0.1

Type RM Length L Ch R = 1 ,125892  ,529,529,529
BEGIN DESCRIPTION:
SF PEREZ CREEK 161.0
END DESCRIPTION:
XS GIS Cut Line= 4
      1983964.38     13665694.27      1983214.35     13666027.62
      1982662.27     13666319.28      1982021.66     13666558.86
#Sta/Elev= 30
    3958  921.83    4012  921.53  4065.9  919.74  4077.7  918.15  4094.7  918.87
    4122  917.79  4254.7  913.39  4418.9  906.96  4548.2   899.4  4732.1   891.2
  4755.4  887.59    4812  884.17  4871.8  881.73  4925.1  881.18  4970.3  876.76
  4992.2  872.27  4992.7  871.47  5004.3  872.27  5020.3  872.51  5036.6  875.11
  5152.4  876.19  5196.5  878.28  5485.6  879.42  5546.2  878.61  5631.7  879.88
  5656.5  881.92  5667.3  883.94  5722.6  886.08  5912.7   887.7  6087.1  892.87
#Mann= 5 ,-1 , 0
    3958      .1       0    4122     .16       0  4254.7      .1       0
  4992.2     .07       0  5004.3      .1       0
Bank Sta=4992.2,5004.3
XS Rating Curve= 0 ,0
Exp/Cntr=0.3,0.1

Type RM Length L Ch R = 1 ,125363  ,693,693,693
BEGIN DESCRIPTION:
SF PEREZ CREEK 160.0
END DESCRIPTION:
XS GIS Cut Line= 4
       1983948.7     13665423.46      1982959.14     13665683.87
      1982250.81     13666220.33      1981658.53     13666391.78
#Sta/Elev= 30
  3491.5  935.11  3588.4  931.77  3865.9  917.39    4068  906.89  4143.8   903.7
  4219.2  898.74  4575.5  887.16  4785.8  881.89  4904.2  878.73  4910.5  876.87
  4918.8  876.95    4925  874.67  4954.1  873.48    4998  869.64  4998.5  868.84
  5010.1  869.64  5024.9  870.83    5054  870.73  5089.4   873.9  5160.1  875.95
  5470.3  878.04  5615.1  882.33  5653.9  887.05  5687.5  893.46  5825.8  902.46
  5865.9  906.48  5871.1  906.07  5904.7  910.86  5950.3   913.5  6019.9  919.22
#Mann= 7 ,-1 , 0
  3491.5      .1       0  3865.9     .16       0    4068      .1       0
  4785.8     .16       0    4998     .07       0  5010.1     .16       0
  5950.3     .16       0
Bank Sta=4998,5010.1
XS Rating Curve= 0 ,0
Exp/Cntr=0.3,0.1

Type RM Length L Ch R = 1 ,124670  ,333,333,333
BEGIN DESCRIPTION:
Mapping XS 89b5f514
END DESCRIPTION:
XS GIS Cut Line= 3
      1983724.81     13665168.23      1982219.56     13665735.95
      1981360.47     13666220.16
#Sta/Elev= 30
  3104.4  933.79    3165  929.87  3253.3  924.46  3270.8  923.62  3420.3   913.6
    3621  903.14  3718.2  899.82  3821.7  894.49  3986.9  888.97  4187.6  885.41
  4297.7  881.41    4400  879.59  4547.2  877.04  4823.6  874.13  4971.2  870.77
  4987.1  869.77  4987.8  867.78  4988.3  866.98  4999.9  867.78  5008.8  870.72
  5024.7  881.27  5030.5  881.97  5046.4  890.31  5068.1  892.67    5149  906.16
  5187.8  909.43  5303.8  917.37  5551.9  928.44  5602.6  932.27  5699.3  934.61
#Mann= 12 ,-1 , 0
  3104.4      .1       0    3165     .16       0  3253.3      .1       0
  3270.8     .16       0  3718.2      .1       0    4400     .16       0
  4547.2      .1       0  4823.6     .16       0  4987.8     .07       0
  4999.9     .16       0  5187.8     .05       0  5551.9      .1       0
Bank Sta=4987.8,4999.9
XS Rating Curve= 0 ,0
Exp/Cntr=0.3,0.1

Type RM Length L Ch R = 1 ,124337  ,541,541,541
BEGIN DESCRIPTION:
SF PEREZ CREEK 159.0
END DESCRIPTION:
XS GIS Cut Line= 3
      1983318.56     13665126.56      1982235.18     13665496.37
      1981240.39     13665725.53
#Sta/Elev= 30
  3594.2  910.76  3724.1  905.66  3997.1  891.12    4100  886.38    4232  882.43
  4381.9  879.76  4470.6  875.61  4514.7  875.47  4797.6  873.97  4872.5  874.91
  4944.4  872.84  4954.6  871.83  4964.9  868.94  4989.6  866.72  4990.1  865.92
  5001.2  865.92  5001.7  866.72    5027  869.18  5036.7  871.23    5047  873.99
  5064.7  880.79  5077.8  882.82  5181.2  894.41  5262.5  903.11  5302.5     905
  5379.6  906.33  5465.2  904.48  5570.4  904.65  5646.7  906.36  5759.8  910.73
#Mann= 7 ,-1 , 0
  3594.2     .16       0  3997.1      .1       0  4514.7     .16       0
  4989.6     .07       0  5001.7     .16       0  5181.2     .05       0
  5302.5     .16       0
Bank Sta=4989.6,5001.7
XS Rating Curve= 0 ,0
Exp/Cntr=0.3,0.1

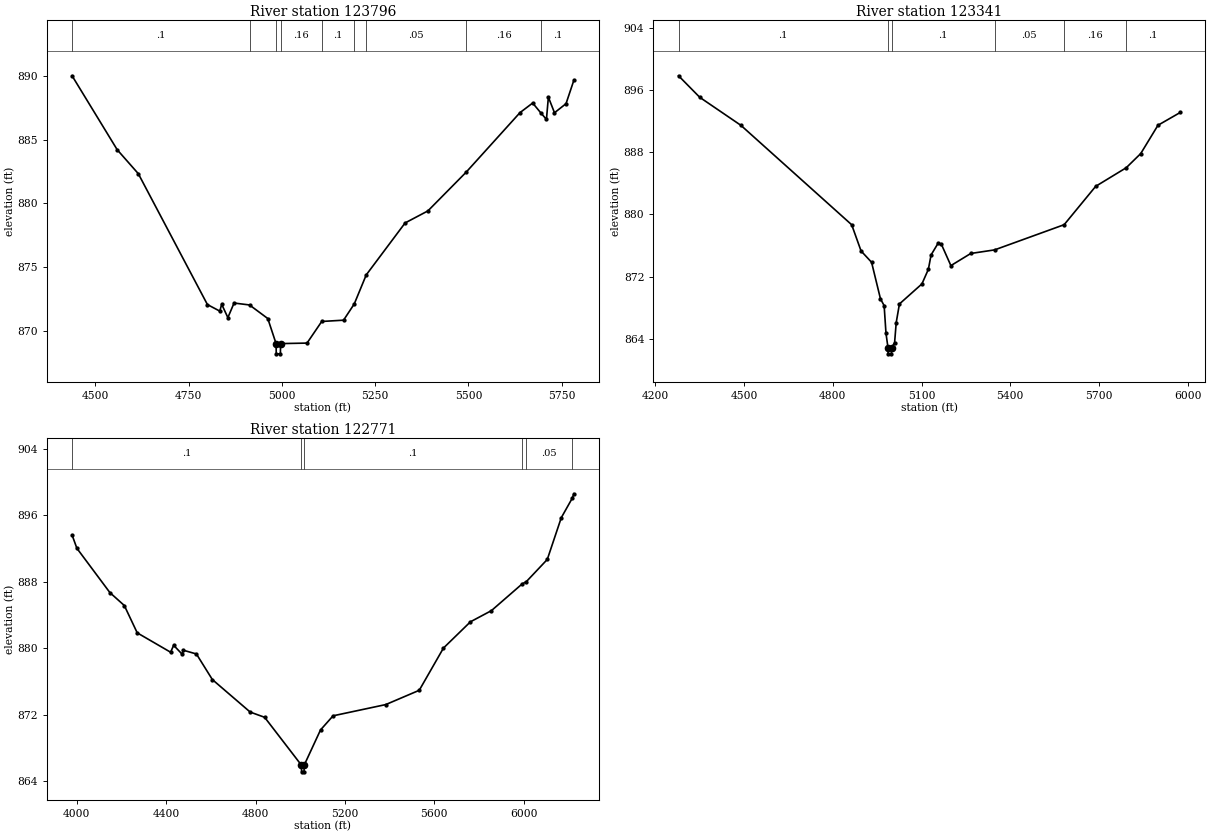
Type RM Length L Ch R = 1 ,123796  ,455,455,455
BEGIN DESCRIPTION:
SF PEREZ CREEK 158.0
END DESCRIPTION:
XS GIS Cut Line= 3
      1982825.02       13664975.        1982325.       13665125.
      1981524.53      13665316.1
#Sta/Elev= 30
  4437.5  889.98  4558.5   884.2    4615  882.33  4800.3   872.1  4833.4  871.59
  4838.6  872.12  4855.1  871.08  4871.7  872.22  4913.1  872.07  4962.1  871.01
  4984.3  869.05  4984.8  868.25  4995.9  868.25  4996.4  869.05  5067.3  869.09
  5106.7  870.78  5165.2  870.88  5193.9  872.15    5226  874.42  5330.2  878.48
  5391.3  879.42  5493.6  882.44  5638.1   887.1  5672.1  887.85  5694.8  887.05
    5709  886.57  5714.2  888.31  5730.6  887.09  5761.5   887.8  5782.5  889.63
#Mann= 9 ,-1 , 0
  4437.5      .1       0  4913.1     .16       0  4984.3     .07       0
  4996.4     .16       0  5106.7      .1       0  5193.9     .16       0
    5226     .05       0  5493.6     .16       0  5694.8      .1       0
Bank Sta=4984.3,4996.4
XS Rating Curve= 0 ,0
Exp/Cntr=0.3,0.1

Type RM Length L Ch R = 1 ,123341  ,570,570,570
BEGIN DESCRIPTION:
SF PEREZ CREEK 157.0
END DESCRIPTION:
XS GIS Cut Line= 3
      1982922.08     13664478.44        1982275.       13664725.
      1981351.88     13665120.38
#Sta/Elev= 30
  4278.2  897.81    4350  895.04  4489.1  891.44  4863.7  878.66  4895.4  875.29
  4930.9  873.84    4961  869.14  4973.4  868.27  4979.7  864.69  4986.4  862.87
  4986.9  862.07    4998  862.07  4998.5  862.87  5008.8  863.51  5014.2  866.08
  5025.1  868.48  5101.2  871.06    5123  872.94  5132.1  874.78  5155.6  876.27
  5166.5  876.19  5199.1  873.41  5266.3  874.97  5346.8  875.43  5582.1  878.67
  5688.7   883.6    5792  885.99    5841  887.81  5899.3  891.45  5974.9   893.1
#Mann= 6 ,-1 , 0
  4278.2      .1       0  4986.4     .07       0  4998.5      .1       0
  5346.8     .05       0  5582.1     .16       0    5792      .1       0
Bank Sta=4986.4,4998.5
XS Rating Curve= 0 ,0
Exp/Cntr=0.3,0.1

Type RM Length L Ch R = 1 ,122771  ,450,450,450
BEGIN DESCRIPTION:
SF PEREZ CREEK 156.0
END DESCRIPTION:
XS GIS Cut Line= 3
      1982961.19     13663935.89      1982229.74     13664077.56
      1981029.86     13664977.48
#Sta/Elev= 30
  3979.3  893.65  4000.9  892.05  4148.6  886.72    4213  885.17  4270.8  881.88
  4420.1  879.55  4433.8  880.38  4471.8  879.31  4476.9  879.79  4535.6  879.34
  4606.9  876.26  4776.2  872.35  4840.8  871.72  5005.5  865.96    5006  865.16
  5017.2  865.16  5017.7  865.96  5090.8   870.2    5147   871.9  5382.5  873.25
  5532.5  874.97  5640.8  880.05  5761.6  883.21  5855.3  884.55  5992.2  887.75
  6011.9  888.05  6105.3  890.71  6167.9  895.73  6217.1  898.08  6224.2  898.61
#Mann= 6 ,-1 , 0
  3979.3      .1       0  5005.5     .07       0  5017.7      .1       0
  5992.2     .16       0  6011.9     .05       0  6217.1      .1       0
Bank Sta=5005.5,5017.7
XS Rating Curve= 0 ,0
Exp/Cntr=0.3,0.1