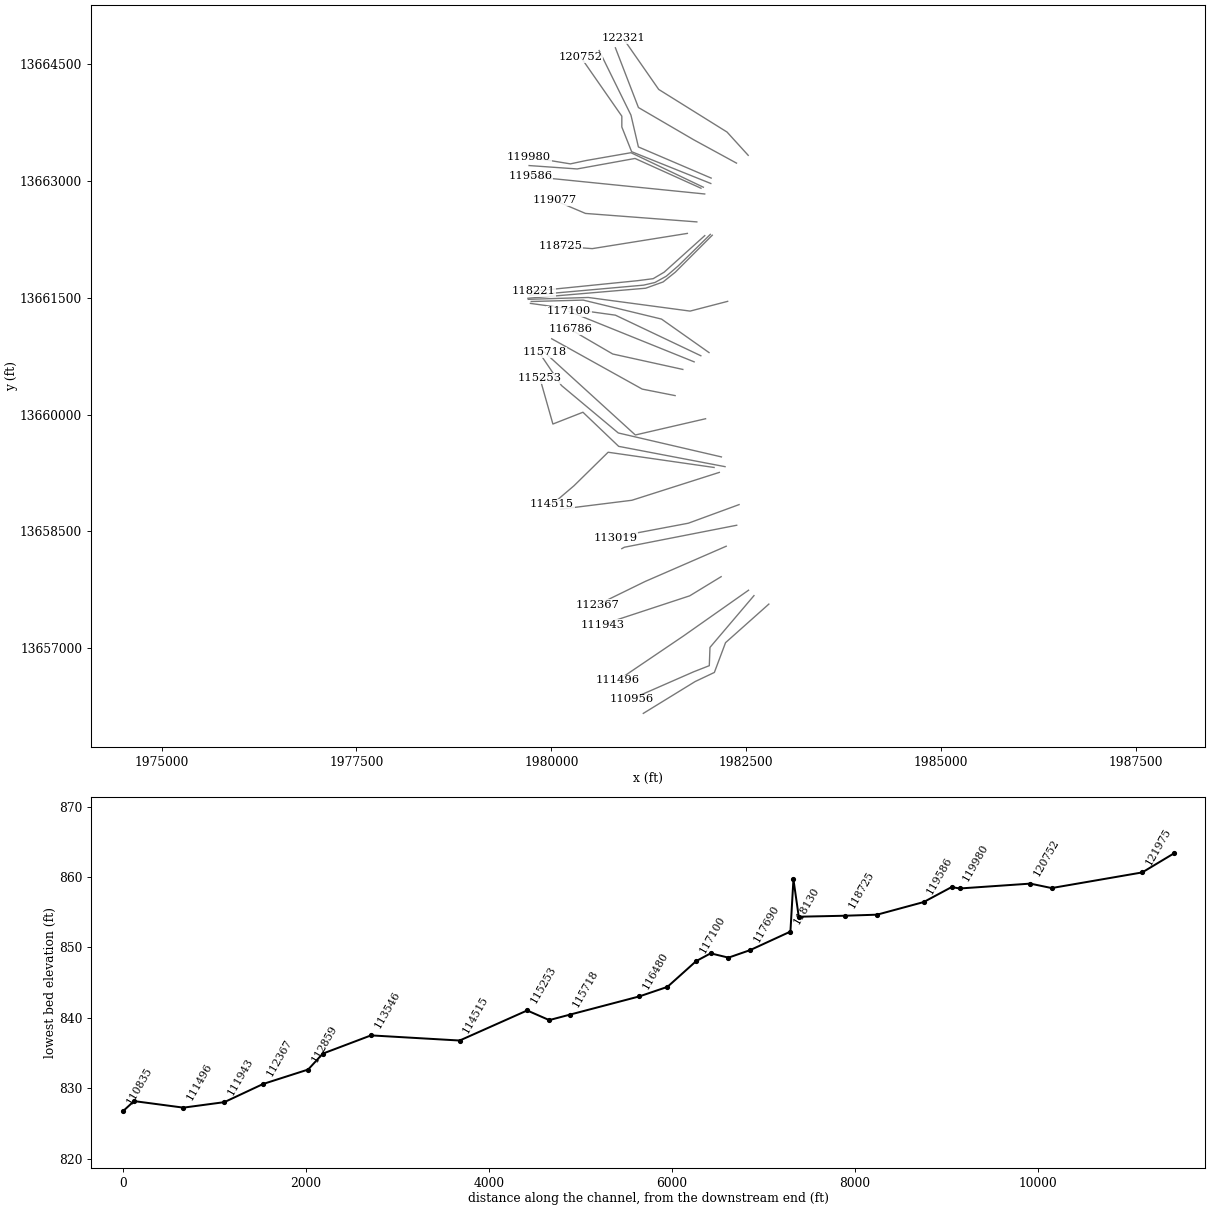
HEC-RAS study SF PEREZ CREEK.prj: SF PEREZ CREEK Base Level Engineering

--- SF PEREZ CREEK.g01 (geometry) --- (continued)

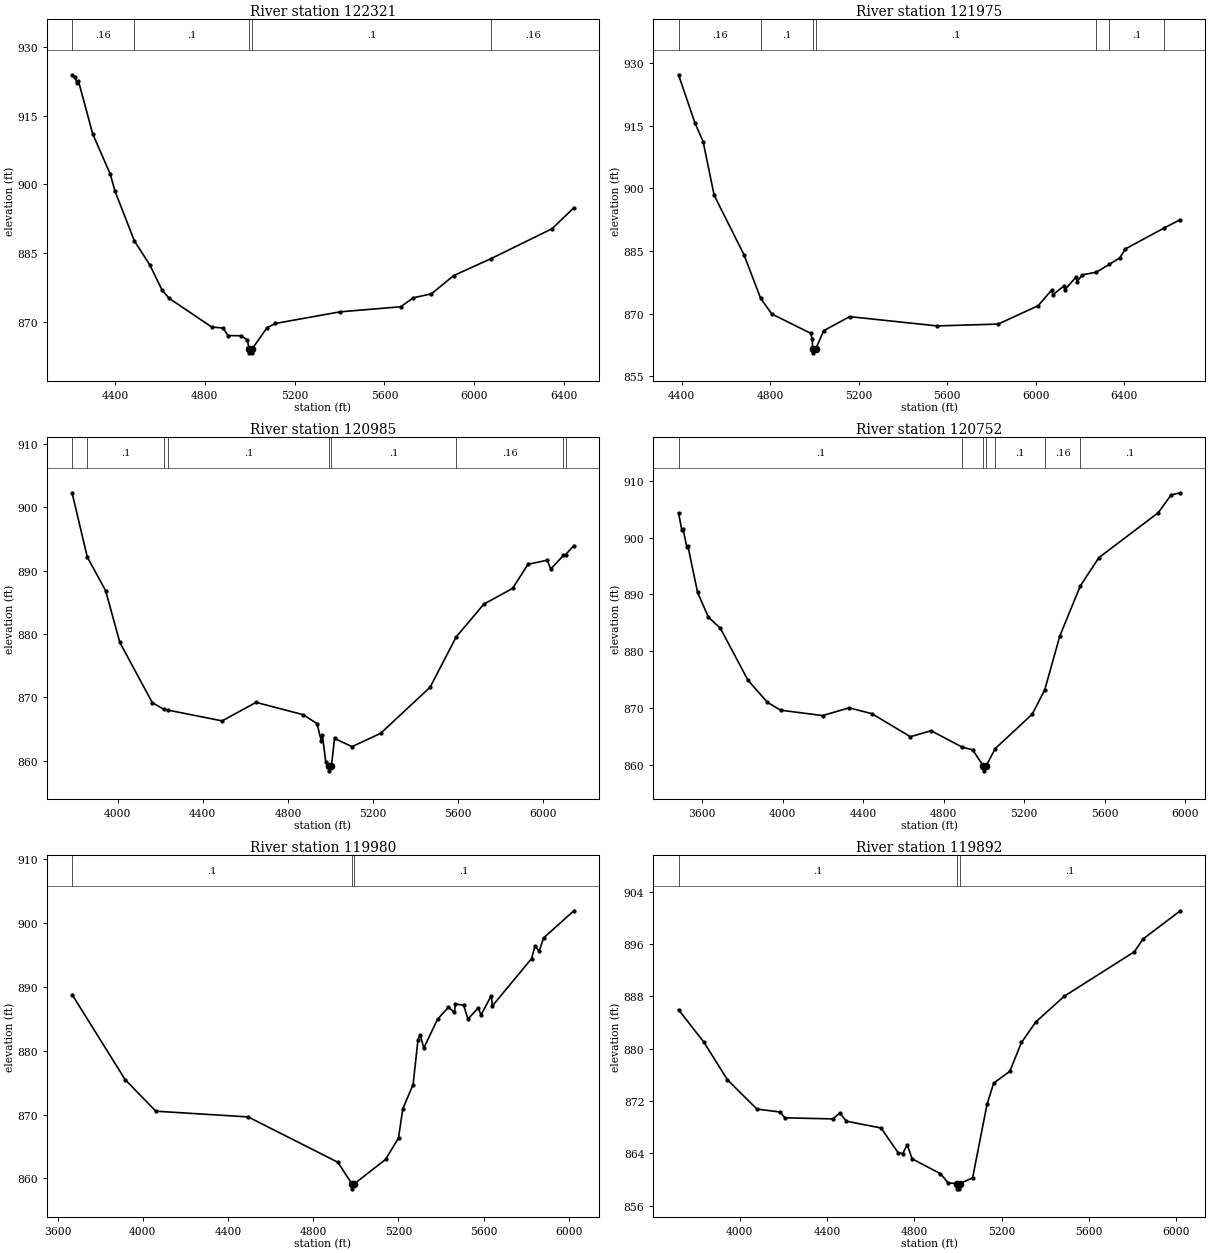
Type RM Length L Ch R = 1 ,122321  ,346,346,346
BEGIN DESCRIPTION:
SF PEREZ CREEK 155.0
END DESCRIPTION:
XS GIS Cut Line= 4
      1982524.99     13663325.02       1982253.7     13663623.39
      1981376.97     13664170.27      1980921.26     13664825.62
#Sta/Elev= 30
  4209.1  923.88  4222.9  923.36  4230.4  922.01  4237.1  922.59  4301.3  910.95
    4379  902.28    4400  898.59  4486.4  887.73  4556.1  882.41  4610.1  876.98
    4642  875.19  4830.8  868.97  4881.9  868.73  4903.9   867.1  4961.7  867.06
  4988.9  866.18  4998.1  864.14  4998.6  863.34  5009.9  863.34  5010.4  864.14
  5077.4  868.81  5113.9  869.73    5403  872.27  5672.6  873.37  5729.3  875.33
  5809.6  876.19  5908.2  880.15  6075.4  883.86  6346.4  890.35  6443.9  894.92
#Mann= 5 ,-1 , 0
  4209.1     .16       0  4486.4      .1       0  4998.1     .07       0
  5010.4      .1       0  6075.4     .16       0
Bank Sta=4998.1,5010.4
XS Rating Curve= 0 ,0
Exp/Cntr=0.3,0.1

Type RM Length L Ch R = 1 ,121975  ,990,990,990
BEGIN DESCRIPTION:
SF PEREZ CREEK 154.0
END DESCRIPTION:
XS GIS Cut Line= 4
      1982374.99     13663225.01        1981825.       13663525.
      1981117.04     13663937.98      1980821.41     13664704.13
#Sta/Elev= 30
  4385.5  927.15  4459.1  915.71    4497  911.08  4546.4  898.33  4681.6  884.06
  4756.1  873.73  4806.9  869.93  4982.1  865.33  4989.2  864.01  4992.1  861.44
  4992.6  860.64  5004.4  861.44  5041.3  865.93  5158.8   869.3    5554  867.08
  5829.9  867.52  6010.6  871.92  6071.5  875.66  6076.8  874.52    6126   876.6
  6131.4  875.74  6180.6  878.72    6186   877.7  6210.6   879.3  6273.2  879.93
  6331.7  881.79  6379.7  883.37  6404.3  885.49  6576.8  890.42  6652.8  892.51
#Mann= 7 ,-1 , 0
  4385.5     .16       0  4756.1      .1       0  4992.1     .07       0
  5004.4      .1       0  6273.2     .16       0  6331.7      .1       0
  6576.8     .16       0
Bank Sta=4992.1,5004.4
XS Rating Curve= 0 ,0
Exp/Cntr=0.3,0.1

Type RM Length L Ch R = 1 ,120985  ,233,233,233
BEGIN DESCRIPTION:
Mapping XS 3ea7f9d6
END DESCRIPTION:
XS GIS Cut Line= 4
      1982049.68     13663033.13      1981116.55     13663432.42
      1981021.06     13663840.41      1980613.09     13664669.37
#Sta/Elev= 30
  3785.8  902.29  3857.3  892.15  3943.2  886.87  4010.3  878.68  4162.6  869.19
  4217.4  868.11  4236.5     868    4491   866.3  4650.2  869.22  4871.8  867.28
  4936.9  865.87  4956.8  863.12  4961.9  864.14    4978  859.77  4992.4  859.22
  4992.9  858.42  5004.7  859.22  5019.1  863.53  5101.3  862.23  5236.1  864.35
  5467.9   871.6  5590.7  879.55  5720.7  884.72  5855.5   887.2  5928.4  891.01
  6018.3  891.65  6035.2  890.26  6094.6  892.41  6105.5  892.55  6143.7  893.96
#Mann= 9 ,-1 , 0
  3785.8     .16       0  3857.3      .1       0  4217.4     .16       0
  4236.5      .1       0  4992.4     .07       0  5004.7      .1       0
  5590.7     .16       0  6094.6      .1       0  6105.5     .16       0
Bank Sta=4992.4,5004.7
XS Rating Curve= 0 ,0
Exp/Cntr=0.3,0.1

Type RM Length L Ch R = 1 ,120752  ,772,772,772
BEGIN DESCRIPTION:
Mapping XS 68cb8f23
END DESCRIPTION:
XS GIS Cut Line= 5
      1982045.33     13662963.69      1981029.74     13663371.66
      1980903.88      13663688.5      1980903.88     13663827.39
      1980378.73     13664582.56
#Sta/Elev= 30
  3481.6  904.32  3498.3  901.23  3503.7  901.54  3522.5  898.39  3527.9  898.53
  3576.3  890.36  3630.1  886.01  3689.2  884.09  3826.8  874.95  3923.1  871.08
  3988.5   869.7  4197.3  868.75  4329.1   870.1    4442  869.09  4634.2  865.04
  4736.8  866.09  4891.1  863.22  4943.5  862.74  4997.3  859.85  4997.8  859.05
  5009.6  859.85  5055.5  862.95  5239.8     869  5301.8  873.27  5376.9  882.73
  5478.3  891.48  5570.6  896.46  5865.7  904.34    5930  907.47  5975.7  907.85
#Mann= 7 ,-1 , 0
  3481.6      .1       0  4891.1     .16       0  4997.3     .07       0
  5009.6     .16       0  5055.5      .1       0  5301.8     .16       0
  5478.3      .1       0
Bank Sta=4997.3,5009.6
XS Rating Curve= 0 ,0
Exp/Cntr=0.3,0.1

Type RM Length L Ch R = 1 ,119980  ,88,88,88
BEGIN DESCRIPTION:
Mapping XS 1a66261c
END DESCRIPTION:
XS GIS Cut Line= 5
      1981949.85     13662915.94      1981021.06     13663358.64
      1980448.15     13663258.81      1980244.15     13663215.41
      1979714.62     13663302.22
#Sta/Elev= 30
    3668  888.81  3917.1  875.48  4061.1  870.53  4494.8  869.63  4916.2  862.52
  4981.1  859.16  4981.6  858.36  4993.5  859.16  5139.5  862.97  5200.4  866.32
  5220.7  870.93    5269   874.7  5291.9  881.76  5302.1  882.51  5319.1  880.44
  5383.9  884.95    5435  886.83  5462.8  886.01  5467.9  887.34  5506.4  887.12
  5526.7  884.96  5574.7  886.74  5587.5   885.6    5636  888.64  5641.1  887.03
    5825  894.44  5840.8  896.38  5861.1  895.62  5881.3  897.68  6023.6  901.94
#Mann= 3 ,-1 , 0
    3668      .1       0  4981.1     .07       0  4993.5      .1       0
Bank Sta=4981.1,4993.5
XS Rating Curve= 0 ,0
Exp/Cntr=0.3,0.1

Type RM Length L Ch R = 1 ,119892  ,306,306,306
BEGIN DESCRIPTION:
Mapping XS 791879ae
END DESCRIPTION:
XS GIS Cut Line= 4
      1981919.52      13662902.9      1981073.15     13663284.85
      1980330.96      13663150.3      1979714.64     13663193.71
#Sta/Elev= 30
  3718.9  885.94  3836.2  880.93  3943.3  875.22  4078.5  870.75  4184.6   870.3
  4206.6  869.41    4426  869.25  4458.9  870.14  4488.1   868.9  4647.5  867.86
  4726.3  864.05  4747.2  863.96  4767.5   865.3  4789.9  863.15    4920  860.87
  4955.3  859.47  4995.1  859.36  4995.6  858.56    5007  858.56  5007.5  859.36
  5067.2  860.23  5133.4  871.49  5163.9  874.72  5237.7  876.52  5291.1  880.93
    5357  884.07  5487.9  888.01  5808.7  894.79  5848.8  896.75  6019.6  901.06
#Mann= 3 ,-1 , 0
  3718.9      .1       0  4995.1     .07       0  5007.5      .1       0
Bank Sta=4995.1,5007.5
XS Rating Curve= 0 ,0
Exp/Cntr=0.3,0.1

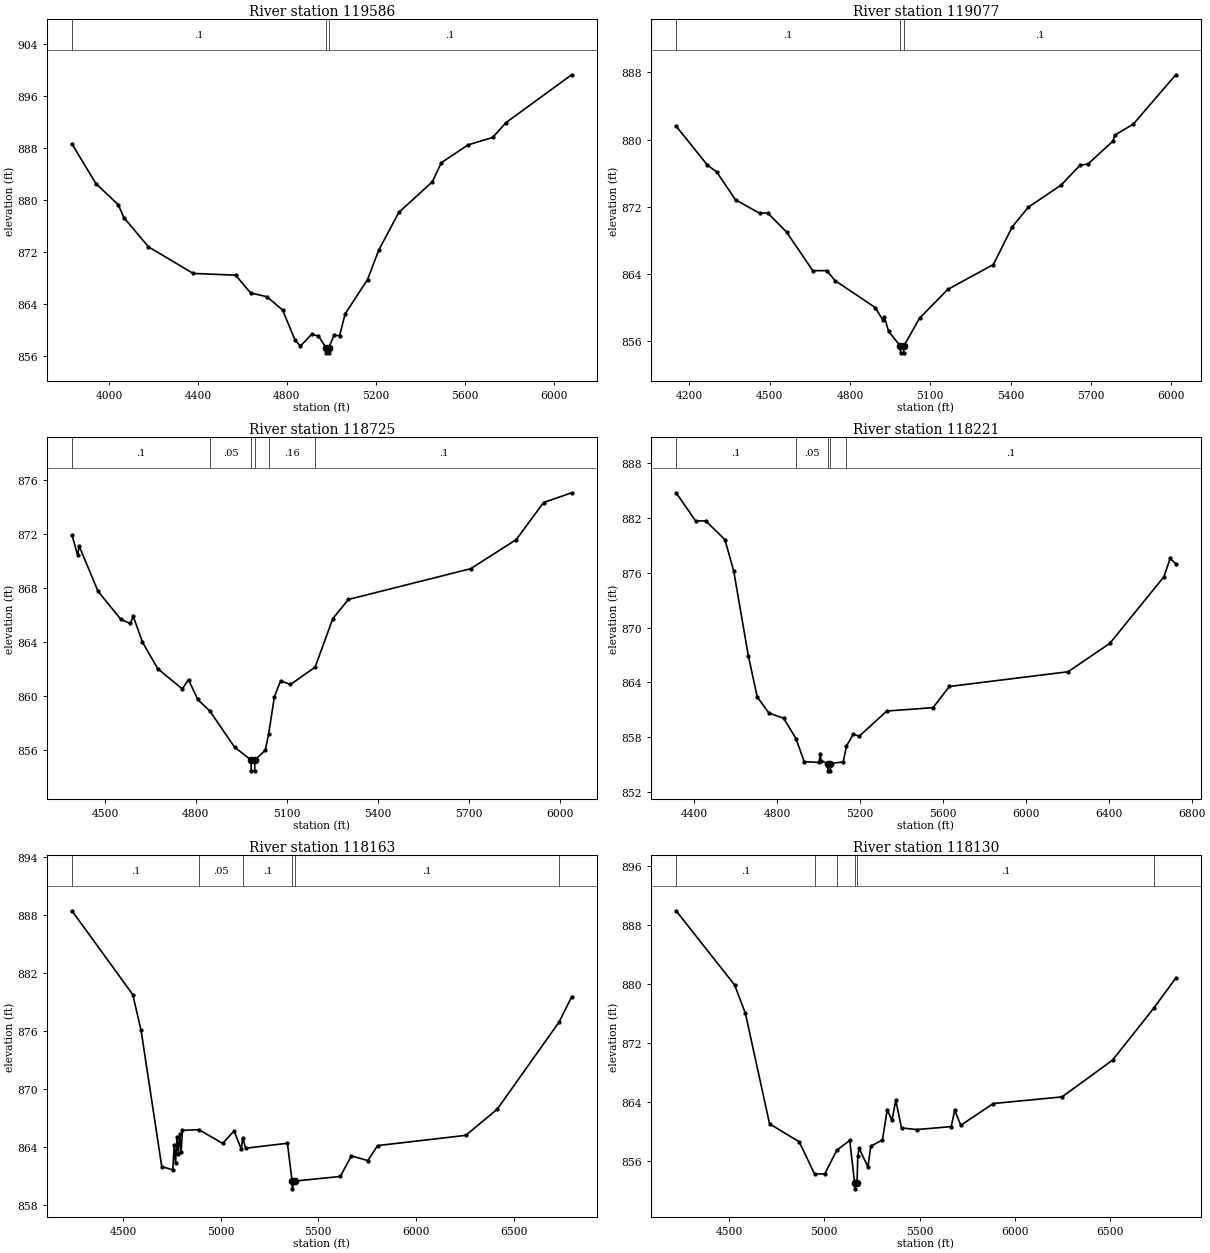
Type RM Length L Ch R = 1 ,119586  ,509,509,509
BEGIN DESCRIPTION:
Mapping XS 700dec39
END DESCRIPTION:
XS GIS Cut Line= 2
      1981967.21     13662829.13      1979731.98     13663054.82
#Sta/Elev= 30
  3833.9   888.6  3941.9  882.48  4041.9  879.25  4067.3  877.26  4177.9  872.75
  4378.9  868.66  4569.8  868.39  4637.1  865.66  4710.5  865.07  4780.9  863.03
  4837.1  858.37  4861.3  857.48  4911.6  859.28  4942.2  859.02  4975.7  857.23
  4976.2  856.43  4987.7  856.43  4988.2  857.23  5012.1  859.11  5037.2  859.09
  5062.3  862.44  5162.8  867.71  5213.1  872.24  5303.5  878.06  5454.3  882.77
  5494.5  885.71  5615.1  888.45  5725.7   889.6    5786   891.9  6080.5  899.25
#Mann= 3 ,-1 , 0
  3833.9      .1       0  4975.7     .07       0  4988.2      .1       0
Bank Sta=4975.7,4988.2
XS Rating Curve= 0 ,0
Exp/Cntr=0.3,0.1

Type RM Length L Ch R = 1 ,119077  ,352,352,352
BEGIN DESCRIPTION:
Mapping XS db013413
END DESCRIPTION:
XS GIS Cut Line= 3
      1981866.12     13662471.14      1980438.16     13662579.64
      1980039.39     13662748.69
#Sta/Elev= 30
  4151.2   881.6  4267.9  876.97  4302.8  876.15    4373  872.83  4463.2  871.23
  4493.3  871.27  4563.5     869  4661.5  864.41  4713.9  864.41    4744  863.24
  4894.5  860.03  4923.8   858.5  4928.8  858.91  4944.6  857.18  4988.5  855.44
    4989  854.64  5000.5  854.64    5001  855.44    5060  858.76  5165.2  862.18
  5335.7  865.14  5405.9  869.62  5466.1  871.96  5588.2  874.58  5659.2  876.95
  5688.3  877.08  5782.2  879.82  5788.4  880.52  5858.2  881.84  6016.4   887.7
#Mann= 3 ,-1 , 0
  4151.2      .1       0  4988.5     .07       0    5001      .1       0
Bank Sta=4988.5,5001
XS Rating Curve= 0 ,0
Exp/Cntr=0.3,0.1

Type RM Length L Ch R = 1 ,118725  ,504,504,504
BEGIN DESCRIPTION:
Mapping XS c9e0f073
END DESCRIPTION:
XS GIS Cut Line= 3
      1981744.63     13662323.57      1980524.97     13662128.25
      1980112.69     13662158.63
#Sta/Elev= 30
  4391.3  871.92    4410  870.43  4415.1  871.09  4477.1  867.76    4553  865.67
  4583.4  865.38  4593.5   865.9  4623.9     864  4674.5  862.03  4755.5  860.54
  4775.8  861.23  4806.2  859.76  4846.6   858.9  4927.7  856.24  4982.2  855.29
  4982.7  854.49  4994.2  854.49  4994.7  855.29    5029  856.01    5040  857.19
  5059.3  859.97  5079.6  861.14  5112.3  860.87  5193.6  862.15  5251.8  865.73
  5303.4  867.15  5706.7  869.42  5857.1  871.57  5947.3  874.31  6039.9  875.03
#Mann= 6 ,-1 , 0
  4391.3      .1       0  4846.6     .05       0  4982.2    .033       0
  4994.7     .05       0    5040     .16       0  5193.6      .1       0
Bank Sta=4982.2,4994.7
XS Rating Curve= 0 ,0
Exp/Cntr=0.3,0.1

Type RM Length L Ch R = 1 ,118221  ,58,58,58
BEGIN DESCRIPTION:
Mapping XS b1d9f90e
END DESCRIPTION:
XS GIS Cut Line= 5
      1981967.71     13662294.95      1981446.85     13661826.17
      1981306.22     13661742.84       1981103.1      13661716.8
      1979768.07     13661582.14
#Sta/Elev= 30
  4312.6  884.71  4406.7  881.64    4456  881.63    4548   879.6  4590.6  876.16
  4661.6  866.85  4704.2  862.42  4760.2  860.66  4831.2   860.1    4891  857.87
  4930.6  855.35  5001.6  855.27  5008.4  856.17  5011.2  855.44  5044.4  855.15
  5044.9  854.35  5056.4  854.35  5056.9  855.15  5118.9  855.32  5134.5  857.05
  5167.6  858.36  5196.1  858.13  5329.3  860.88  5552.3  861.25    5631  863.56
  6203.8  865.17  6404.9  868.26  6666.2  875.54  6696.3  877.54  6723.4  876.97
#Mann= 5 ,-1 , 0
  4312.6      .1       0    4891     .05       0  5044.4    .033       0
  5056.9     .05       0  5134.5      .1       0
Bank Sta=5044.4,5056.9
XS Rating Curve= 0 ,0
Exp/Cntr=0.3,0.1

Type RM Length L Ch R = 1 ,118163  ,33,33,33
BEGIN DESCRIPTION:
SF PEREZ CREEK 150.0
END DESCRIPTION:
XS GIS Cut Line= 6
       1982039.3      13662310.9      1981627.83     13661907.25
      1981474.19     13661774.43      1981328.36     13661693.71
      1981182.52     13661659.85       1979725.3     13661529.93
#Sta/Elev= 30
  4238.8   888.4  4550.1  879.74  4592.6  876.06  4698.6  861.96  4755.1  861.62
  4762.3  864.16  4769.3  862.32  4776.4  864.99  4783.4  863.31  4790.6  865.31
  4797.6  863.42  4804.7   865.7  4889.4  865.78  5010.2  864.35  5068.8  865.64
  5106.6  863.74  5112.7  864.95  5128.3  863.86  5342.2  864.37  5366.1  860.46
  5366.6  859.66  5378.6  860.46  5613.3  860.94  5669.7  863.07  5753.9  862.58
  5804.1  864.13  6255.9  865.19  6416.5  867.89  6733.1  876.89  6797.7   879.5
#Mann= 6 ,-1 , 0
  4238.8      .1       0  4889.4     .05       0  5112.7      .1       0
  5366.1    .033       0  5378.6      .1       0  6733.1     .16       0
Bank Sta=5366.1,5378.6
XS Rating Curve= 0 ,0
Exp/Cntr=0.3,0.1

Type RM Length L Ch R = 1 ,118130  ,440,440,440
BEGIN DESCRIPTION:
Mapping XS d3491088
END DESCRIPTION:
XS GIS Cut Line= 5
      1982064.01     13662300.11      1981590.07     13661826.17
      1981433.82     13661701.17      1981209.87     13661620.44
      1979700.16     13661491.66
#Sta/Elev= 30
  4221.8  889.95  4528.8   879.9  4585.3  876.08  4712.6  861.05  4868.2  858.62
    4949  854.25  5002.7  854.28  5065.2  857.46  5133.4  858.81  5159.1  853.04
  5159.6  852.24  5171.6  853.04  5175.9  856.66  5182.7  857.72  5229.1  855.23
    5244  858.02  5305.4  858.88  5330.1  862.97  5355.2  861.53  5375.2  864.26
  5405.4   860.5  5485.6  860.28  5666.3  860.68  5684.9   862.9  5716.5  860.86
  5887.1  863.81  6248.4  864.71  6513.2  869.69  6729.4  876.73  6845.4  880.82
#Mann= 6 ,-1 , 0
  4221.8      .1       0    4949     .05       0  5065.2      .1       0
  5159.1    .033       0  5171.6      .1       0  6729.4     .16       0
Bank Sta=5159.1,5171.6
XS Rating Curve= 0 ,0
Exp/Cntr=0.3,0.1

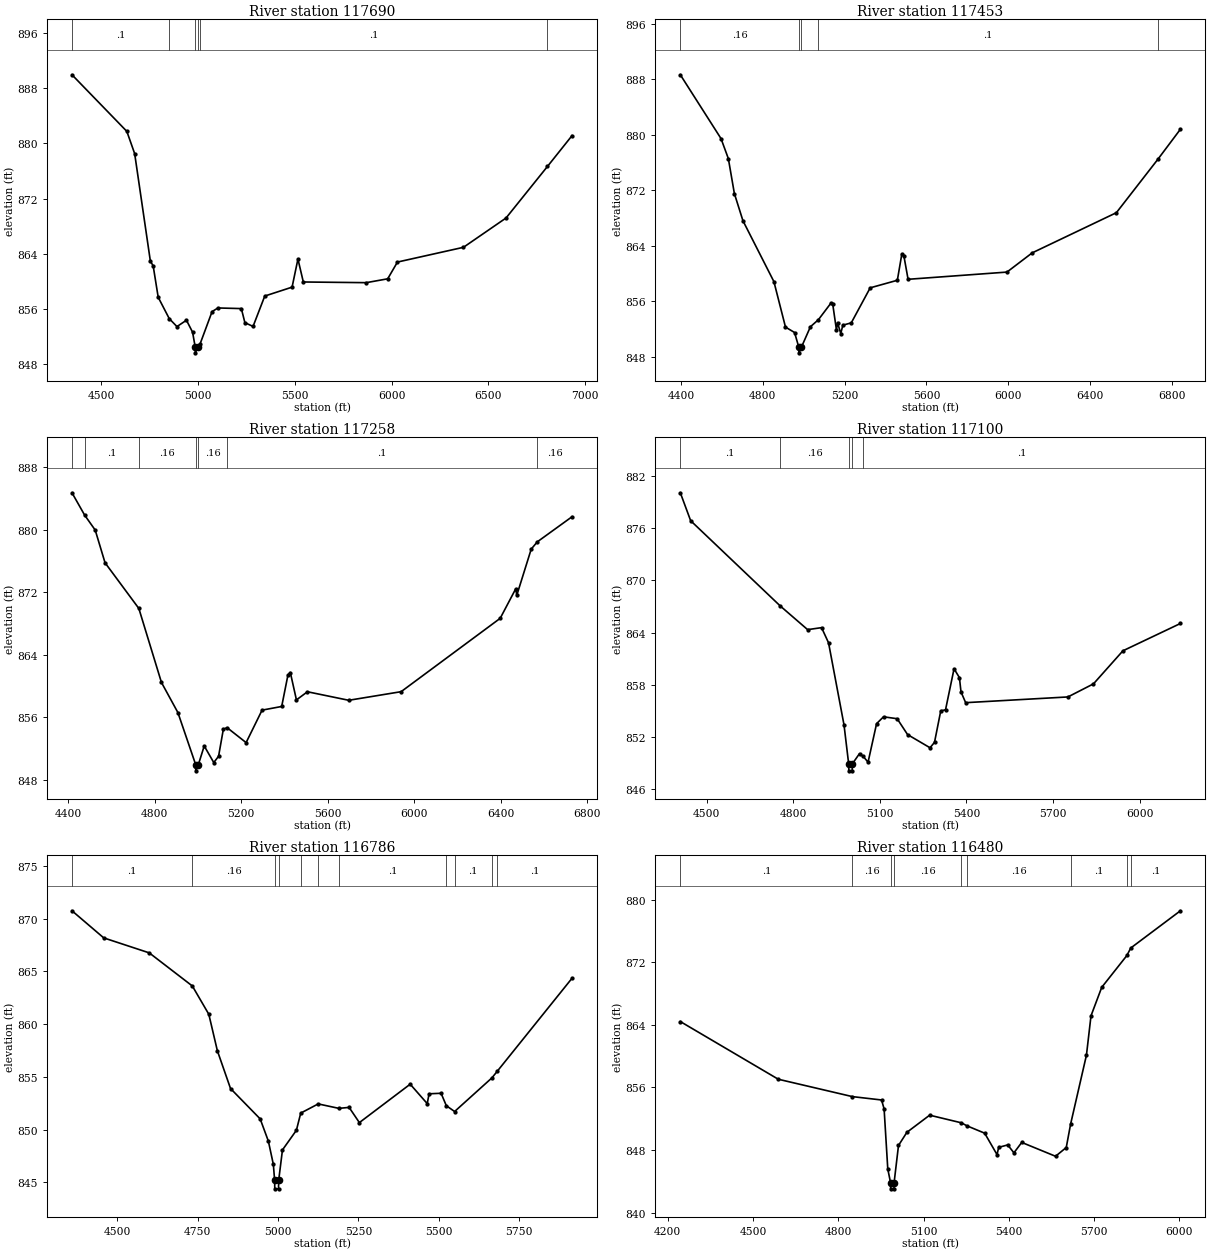
Type RM Length L Ch R = 1 ,117690  ,237,237,237
BEGIN DESCRIPTION:
Mapping XS fe8fa89a
END DESCRIPTION:
XS GIS Cut Line= 4
      1982261.39     13661452.01      1981779.65     13661327.02
      1980473.94     13661501.74      1979703.66     13661477.77
#Sta/Elev= 30
  4347.8  889.95  4631.4  881.74  4671.9  878.51  4753.1  862.91  4767.6  862.23
  4793.6  857.67  4850.8  854.57  4890.5  853.42  4939.7  854.34  4971.3  852.61
  4985.2  850.41  4985.7  849.61  4997.7  850.41  5010.9  850.96  5072.1  855.59
  5102.4  856.12  5223.5  856.03  5241.8  853.99    5284  853.44  5344.6  857.85
  5485.8  859.14  5516.1  863.22  5543.9  859.89  5869.2  859.79  5980.2  860.35
  6030.6  862.78  6371.9  864.92    6592  869.17  6806.2  876.65  6933.5  881.13
#Mann= 6 ,-1 , 0
  4347.8      .1       0  4850.8     .16       0  4985.2     .07       0
  4997.7     .16       0  5010.9      .1       0  6806.2     .16       0
Bank Sta=4985.2,4997.7
XS Rating Curve= 0 ,0
Exp/Cntr=0.3,0.1

Type RM Length L Ch R = 1 ,117453  ,195,195,195
BEGIN DESCRIPTION:
SF PEREZ CREEK 149.0
END DESCRIPTION:
XS GIS Cut Line= 4
      1982022.34     13660794.94      1981412.99     13661224.61
      1980408.64     13661468.02      1979741.91       13661450.
#Sta/Elev= 30
  4396.4  888.62  4595.5  879.42  4631.3  876.54  4660.8   871.5  4702.7  867.58
  4854.2   858.8  4910.8  852.25  4955.2  851.47    4976  849.34  4976.5  848.54
  4988.5  849.34  5032.7   852.3  5071.6  853.31  5133.7  855.73    5142  855.53
  5160.1  851.83  5165.3   852.9  5181.1  851.32  5191.4  852.53  5232.5  852.86
  5325.1  857.91  5457.9     859  5479.5  862.73  5489.8  862.53  5510.4  859.14
    5994  860.18  6117.4  862.95  6529.2  868.74  6731.4  876.41  6842.4  880.77
#Mann= 5 ,-1 , 0
  4396.4     .16       0    4976     .07       0  4988.5     .16       0
  5071.6      .1       0  6731.4     .16       0
Bank Sta=4976,4988.5
XS Rating Curve= 0 ,0
Exp/Cntr=0.3,0.1

Type RM Length L Ch R = 1 ,117258  ,158,158,158
BEGIN DESCRIPTION:
Mapping XS 7f761599
END DESCRIPTION:
XS GIS Cut Line= 3
      1981917.66      13660754.1      1980821.31     13661274.93
      1979731.36     13661425.69
#Sta/Elev= 30
  4416.6   884.7    4475  881.85  4524.1  879.93  4569.6  875.75    4726  869.91
  4830.6  860.45  4906.7   856.6  4988.9  849.95  4989.4  849.15  5001.5  849.95
  5028.5  852.33  5072.7  850.21  5094.9  851.01    5117  854.47  5134.4  854.67
  5222.4  852.76  5296.2  856.91    5387  857.38  5415.9   861.4    5427  861.72
  5455.2  858.22  5506.2  859.26  5697.3  858.17  5939.6  859.27  6398.1  868.65
  6469.9  872.42  6474.9   871.6  6541.7   877.5  6569.9  878.43  6730.7  881.64
#Mann= 7 ,-1 , 0
  4416.6     .16       0    4475      .1       0    4726     .16       0
  4988.9     .07       0  5001.5     .16       0  5134.4      .1       0
  6569.9     .16       0
Bank Sta=4988.9,5001.5
XS Rating Curve= 0 ,0
Exp/Cntr=0.3,0.1

Type RM Length L Ch R = 1 ,117100  ,314,314,314
BEGIN DESCRIPTION:
Mapping XS 37700726
END DESCRIPTION:
XS GIS Cut Line= 2
      1981831.73     13660675.98      1980224.94     13661324.42
#Sta/Elev= 30
  4408.8  880.11  4444.6  876.89    4755  867.06  4849.9  864.33  4898.2  864.56
  4922.4  862.81    4976  853.34  4992.1  848.85  4992.6  848.05  5004.2  848.05
  5004.7  848.85  5029.7  850.04  5042.5  849.71  5059.3  849.05  5088.8  853.49
  5112.9  854.28  5160.1  854.06  5196.2  852.23    5274  850.71  5289.5  851.34
  5311.1  854.96  5327.7  855.09  5357.2  859.82  5375.8   858.8  5381.3  857.15
  5397.4  855.91  5751.7  856.57  5840.3  858.08  5942.3  861.89  6141.5  865.04
#Mann= 5 ,-1 , 0
  4408.8      .1       0    4755     .16       0  4992.1     .07       0
  5004.7     .16       0  5042.5      .1       0
Bank Sta=4992.1,5004.7
XS Rating Curve= 0 ,0
Exp/Cntr=0.3,0.1

Type RM Length L Ch R = 1 ,116786  ,306,306,306
BEGIN DESCRIPTION:
SF PEREZ CREEK 148.0
END DESCRIPTION:
XS GIS Cut Line= 3
      1981686.43     13660578.78      1980787.12     13660776.69
      1980239.26      13661095.7
#Sta/Elev= 30
  4359.4  870.75  4458.1  868.18  4599.6  866.76  4733.6  863.62  4784.8  860.94
  4811.4  857.48  4852.3   853.9  4944.5  851.02    4970  848.91  4985.5   846.7
  4989.4  845.19  4989.9  844.39  5001.5  844.39    5002  845.19  5013.8  848.08
  5057.1  849.94  5070.6  851.57  5124.9  852.44  5189.1  852.02    5221  852.11
  5252.9  850.67  5410.9  854.31  5463.9  852.47  5469.6   853.4  5506.9  853.45
  5523.3  852.27    5549  851.72    5665  854.91  5682.2  855.56  5914.2  864.36
#Mann= 11 ,-1 , 0
  4359.4      .1       0  4733.6     .16       0  4989.4     .07       0
    5002     .16       0  5070.6      .1       0  5124.9     .16       0
  5189.1      .1       0  5523.3     .16       0    5549      .1       0
    5665     .16       0  5682.2      .1       0
Bank Sta=4989.4,5002
XS Rating Curve= 0 ,0
Exp/Cntr=0.3,0.1

Type RM Length L Ch R = 1 ,116480  ,762,762,762
BEGIN DESCRIPTION:
Mapping XS 37e6236b
END DESCRIPTION:
XS GIS Cut Line= 3
      1981587.49     13660243.12       1981165.6     13660326.46
      1980004.12      13660972.3
#Sta/Elev= 30
  4244.3  864.41  4588.9  857.04  4849.7  854.82  4952.2  854.39  4961.1  853.25
    4974  845.58  4983.7  843.84  4984.2  843.04  4995.8  843.04  4996.3  843.84
  5011.7  848.58  5041.2  850.26  5121.3  852.45  5233.3  851.47  5251.8   851.1
  5314.8  850.15  5358.3  847.41    5364  848.34  5395.9  848.65  5417.7  847.64
  5445.2  848.97  5564.1   847.2  5601.8  848.32  5616.9  851.28  5672.8  860.12
  5688.8  865.14  5726.5  868.78  5815.1  872.85  5828.5   873.8  6003.3  878.56
#Mann= 9 ,-1 , 0
  4244.3      .1       0  4849.7     .16       0  4983.7     .07       0
  4996.3     .16       0  5233.3      .1       0  5251.8     .16       0
  5616.9      .1       0  5815.1     .16       0  5828.5      .1       0
Bank Sta=4983.7,4996.3
XS Rating Curve= 0 ,0
Exp/Cntr=0.3,0.1

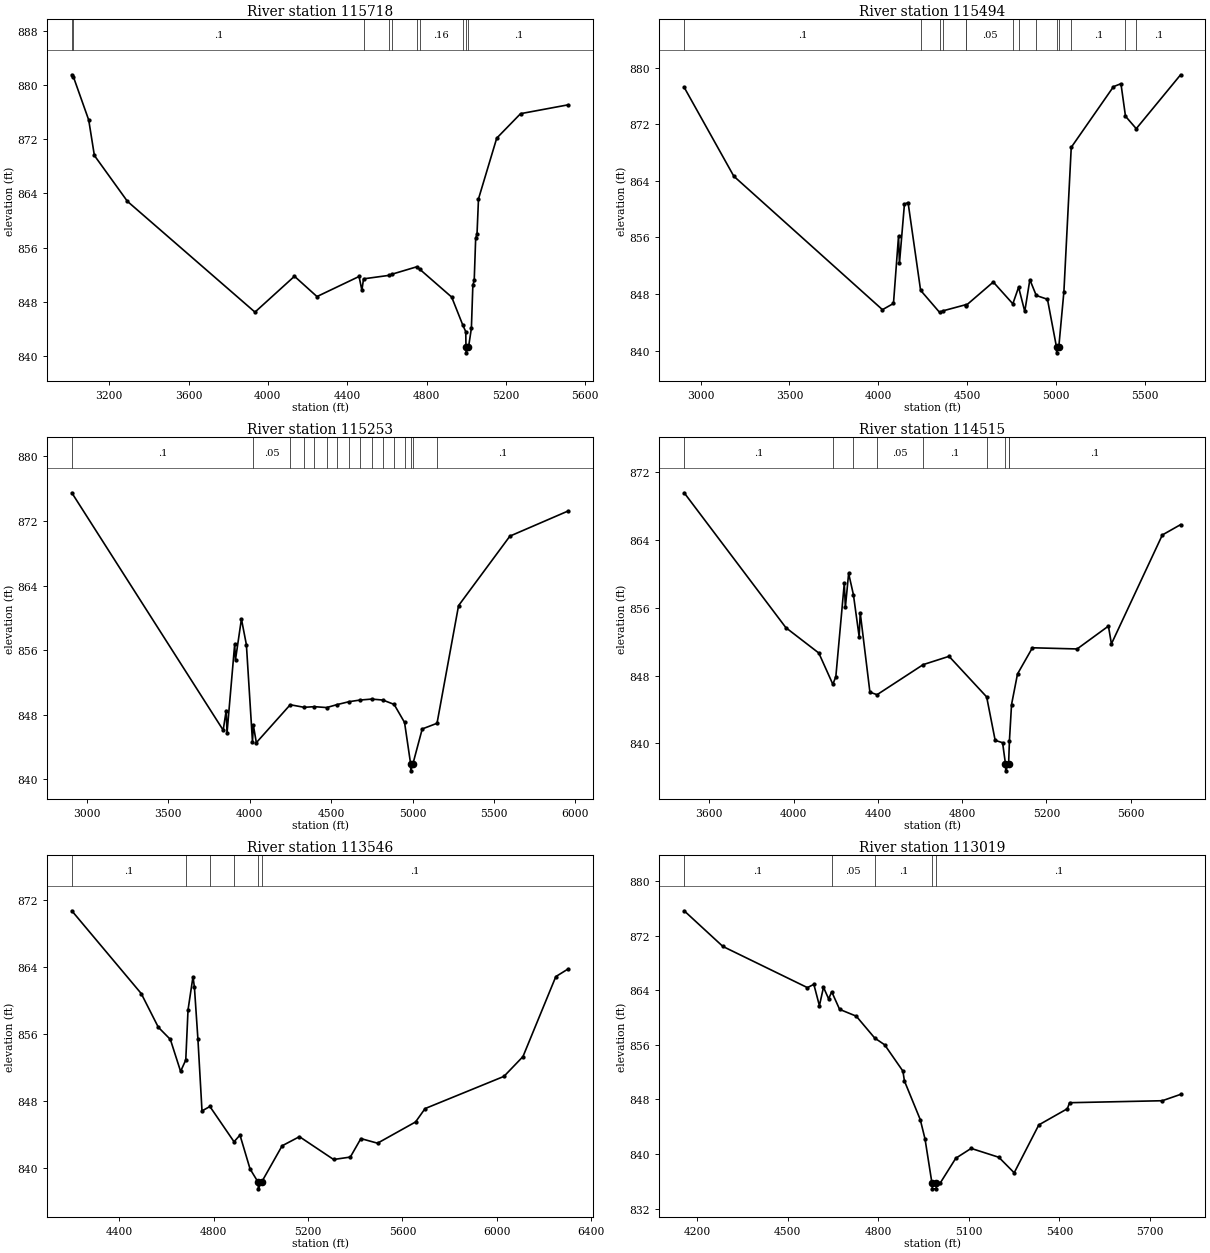
Type RM Length L Ch R = 1 ,115718  ,224,224,224
BEGIN DESCRIPTION:
SF PEREZ CREEK 147.0
END DESCRIPTION:
XS GIS Cut Line= 3
      1981978.13     13659946.26      1981077.05     13659737.92
      1979910.63      13660800.2
#Sta/Elev= 30
  3011.7  881.55    3020  881.23    3097  874.86  3125.5  869.62    3292  862.84
    3935  846.46  4134.1  851.76  4247.6  848.76  4459.8  851.73  4473.9  849.69
  4482.4  851.38  4612.3   851.9  4623.8  852.05  4749.3  853.15  4765.2  852.81
  4926.7  848.68    4983  844.52  4997.6  843.57  4998.7  841.24  4999.2  840.44
  5011.4  841.24    5026  844.08  5033.4  850.46  5040.2  851.14  5047.6   857.4
  5054.3  857.96  5061.8   863.2  5153.7  872.18  5273.9   875.8  5514.2  877.11
#Mann= 10 ,-1 , 0
  3011.7     .16       0    3020      .1       0  4482.4     .16       0
  4612.3      .1       0  4623.8     .16       0  4749.3     .08       0
  4765.2     .16       0    4983      .1       0  4998.7     .07       0
  5011.4      .1       0
Bank Sta=4998.7,5011.4
XS Rating Curve= 0 ,0
Exp/Cntr=0.3,0.1

Type RM Length L Ch R = 1 ,115494  ,241,241,241
BEGIN DESCRIPTION:
Mapping XS c2ed81c2
END DESCRIPTION:
XS GIS Cut Line= 4
       1982181.2     13659456.67       1980858.3     13659763.96
      1980129.14     13660373.33      1979859.15     13660773.12
#Sta/Elev= 30
  2907.8  877.21    3187  864.64  4022.6  845.77  4084.5  846.65    4113   856.2
  4118.1  852.32  4146.1  860.68  4166.6  860.92    4237  848.51  4343.8  845.39
  4360.3  845.59  4491.8  846.48  4492.2  846.36  4645.6  849.68  4755.5   846.6
  4787.9  848.95  4822.6  845.52  4851.2  850.01  4887.2  847.78  4950.2  847.24
  5001.1  840.47  5001.6  839.67  5013.8  840.47  5042.6  848.32  5083.9  868.72
  5321.3   877.3  5363.3  877.72  5388.8  873.12  5449.3  871.36  5698.6  878.98
#Mann= 14 ,-1 , 0
  2907.8      .1       0    4237     .05       0  4343.8      .1       0
  4360.3     .05       0  4491.8      .1       0  4492.2     .05       0
  4755.5     .08       0  4787.9      .1       0  4887.2     .16       0
  5001.1     .07       0  5013.8     .16       0  5083.9      .1       0
  5388.8     .05       0  5449.3      .1       0
Bank Sta=5001.1,5013.8
XS Rating Curve= 0 ,0
Exp/Cntr=0.3,0.1

Type RM Length L Ch R = 1 ,115253  ,738,738,738
BEGIN DESCRIPTION:
SF PEREZ CREEK 146.0
END DESCRIPTION:
XS GIS Cut Line= 6
      1982228.09     13659331.67      1981509.67     13659468.77
      1980863.51     13659592.08      1980405.18     13660029.58
      1980019.76     13659878.54      1979853.09     13660467.11
#Sta/Elev= 30
  2907.7  875.49  3837.3  846.08  3855.8  848.51  3860.9  845.73  3907.9  856.72
    3913  854.83  3949.3  859.85  3979.8  856.67  4017.2  844.66  4022.8  846.66
  4040.9  844.53    4249  849.23  4334.6  848.91  4397.1  848.99  4472.7  848.88
  4537.4  849.25  4610.8  849.61  4677.7  849.81  4748.9  849.93  4817.9  849.81
    4887  849.27  4951.1  847.03  4988.8  841.84  4989.3  841.04  5001.5  841.84
  5059.6  846.23  5150.4  846.93  5282.7  861.51    5598  870.12  5956.2  873.24
#Mann= 16 ,-1 , 0
  2907.7      .1       0  4022.8     .05       0    4249      .1       0
  4334.6     .08       0  4397.1      .1       0  4472.7     .08       0
  4537.4      .1       0  4610.8     .08       0  4677.7      .1       0
  4748.9     .05       0  4817.9      .1       0    4887     .08       0
  4951.1     .05       0  4988.8     .04       0  5001.5     .05       0
  5150.4      .1       0
Bank Sta=4988.8,5001.5
XS Rating Curve= 0 ,0
Exp/Cntr=0.3,0.1

Type RM Length L Ch R = 1 ,114515  ,969,969,969
BEGIN DESCRIPTION:
SF PEREZ CREEK 145.0
END DESCRIPTION:
XS GIS Cut Line= 4
      1982087.43     13659321.26       1980728.1     13659516.56
       1980290.6     13659086.88      1980009.71      13658847.6
#Sta/Elev= 30
  3481.1   869.6  3963.9  853.67    4120  850.68  4186.6  846.99  4200.8  847.89
    4241  858.93    4246  856.07  4261.5  860.08  4284.2  857.57  4311.5   852.6
  4316.5  855.44  4362.5  846.06  4396.4  845.76  4615.2  849.31  4737.9  850.29
  4916.4   845.5  4956.8  840.37    4992  840.09  5005.8  837.57    5007  836.77
  5020.5  837.57  5024.5  840.35  5034.5   844.6  5062.8  848.21  5133.5   851.3
  5345.6  851.16  5494.2  853.86  5508.4  851.76    5750  864.62  5836.6  865.84
#Mann= 9 ,-1 , 0
  3481.1      .1       0  4186.6     .08       0  4284.2      .1       0
  4396.4     .05       0  4615.2      .1       0  4916.4     .16       0
  5005.8     .07       0  5020.5     .16       0  5024.5      .1       0
Bank Sta=5005.8,5020.5
XS Rating Curve= 0 ,0
Exp/Cntr=0.3,0.1

Type RM Length L Ch R = 1 ,113546  ,527,527,527
BEGIN DESCRIPTION:
SF PEREZ CREEK 144.0
END DESCRIPTION:
XS GIS Cut Line= 3
      1982154.41     13659258.11      1981032.92     13658900.48
      1980112.76      13658785.9
#Sta/Elev= 30
  4198.5  870.76  4492.8  860.86  4565.2  856.83  4616.3  855.37  4659.7  851.55
  4681.6  852.91  4691.2  858.91  4712.2  862.87  4718.2  861.64  4733.2  855.37
  4750.4  846.82  4783.9  847.35  4886.2  843.13  4911.4  843.93  4954.1  839.88
  4988.2   838.3  4989.4   837.5    5003   838.3  5090.1  842.65  5163.5  843.74
  5308.3  841.01  5379.1   841.3  5423.9  843.51  5494.5  842.96  5655.7   845.5
    5696   847.1  6030.3  850.95    6111  853.32  6250.3  862.89  6302.9  863.81
#Mann= 6 ,-1 , 0
  4198.5      .1       0  4681.6     .05       0  4783.9     .08       0
  4886.2      .1       0  4988.2     .07       0    5003      .1       0
Bank Sta=4988.2,5003
XS Rating Curve= 0 ,0
Exp/Cntr=0.3,0.1

Type RM Length L Ch R = 1 ,113019  ,160,160,160
BEGIN DESCRIPTION:
SF PEREZ CREEK 143.0
END DESCRIPTION:
XS GIS Cut Line= 4
      1982407.93     13658844.93      1981756.88     13658606.21
      1981094.97     13658481.27      1980825.88     13658420.51
#Sta/Elev= 30
  4157.9  875.62    4286   870.4  4565.8  864.37  4587.1  864.85  4605.5  861.72
    4619  864.42    4636  862.73  4646.3  863.76  4672.3  861.19  4727.5  860.19
  4788.5  856.99  4821.4     856  4881.8  852.15  4886.9   850.7  4939.3  845.04
    4955  842.22  4978.1  835.71  4979.3  834.91  4991.7  834.91    4993  835.71
  5005.9   835.8  5056.8  839.39  5107.7  840.83  5199.3  839.53  5250.1  837.26
  5331.6  844.27  5426.1  846.64  5433.3  847.52  5740.2  847.81  5800.8  848.74
#Mann= 5 ,-1 , 0
  4157.9      .1       0  4646.3     .05       0  4788.5      .1       0
  4978.1     .07       0    4993      .1       0
Bank Sta=4978.1,4993
XS Rating Curve= 0 ,0
Exp/Cntr=0.3,0.1

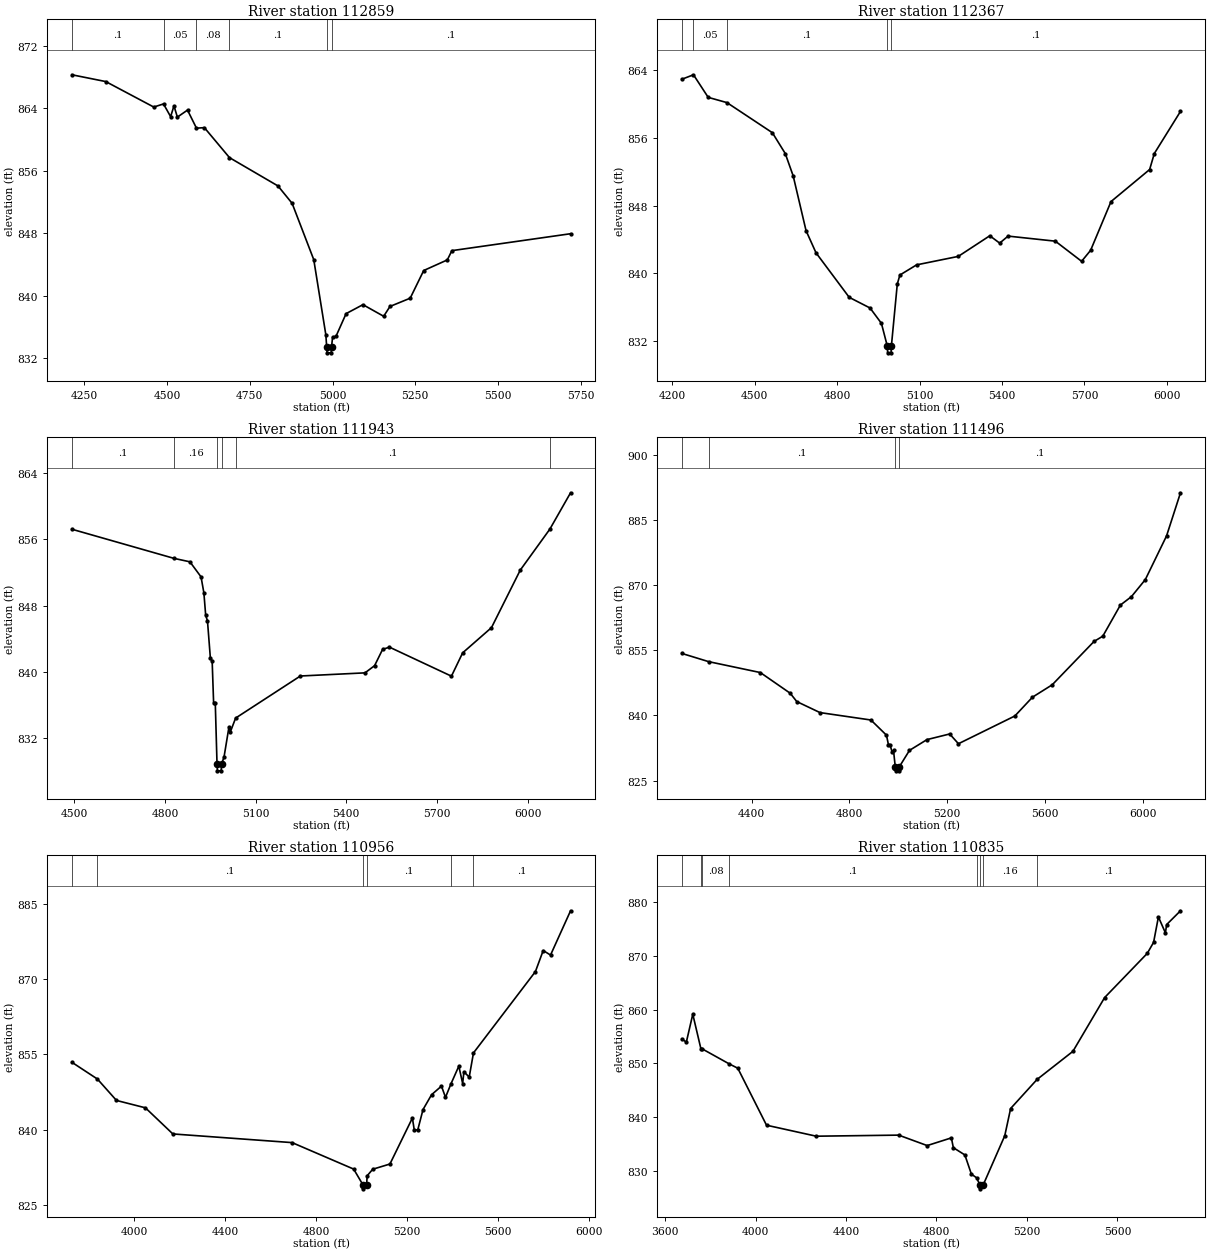
Type RM Length L Ch R = 1 ,112859  ,492,492,492
BEGIN DESCRIPTION:
Mapping XS d548cade
END DESCRIPTION:
XS GIS Cut Line= 3
      1982377.56     13658580.18      1980936.57     13658298.05
      1980903.64     13658280.02
#Sta/Elev= 30
    4213  868.32  4315.2  867.45  4460.2  864.18  4489.6  864.58  4511.1  862.95
  4521.2  864.33  4531.5  862.89  4562.1  863.79  4589.2  861.47    4613  861.54
  4688.9  857.69  4835.3  854.06    4878  851.83  4943.4   844.6  4979.9  834.95
  4982.3  833.45  4983.6  832.65    4996  832.65  4997.2  833.45  5000.2  834.66
  5010.4  834.76    5041  837.68  5091.9  838.83  5154.5  837.34  5173.5   838.6
  5234.6  839.66  5275.4  843.21  5346.7  844.57  5360.5  845.76  5718.9  847.93
#Mann= 6 ,-1 , 0
    4213      .1       0  4489.6     .05       0  4589.2     .08       0
  4688.9      .1       0  4982.3     .07       0  4997.2      .1       0
Bank Sta=4982.3,4997.2
XS Rating Curve= 0 ,0
Exp/Cntr=0.3,0.1

Type RM Length L Ch R = 1 ,112367  ,424,424,424
BEGIN DESCRIPTION:
Mapping XS ce298d64
END DESCRIPTION:
XS GIS Cut Line= 3
        1982243.     13658311.08      1981201.87     13657858.42
       1980591.2     13657559.68
#Sta/Elev= 30
  4234.3  862.94  4276.7  863.47  4330.3   860.8  4398.5  860.18  4563.9  856.62
  4610.8  854.16  4639.7  851.51  4686.5  845.04  4722.8  842.42  4843.6  837.16
  4919.4   835.9  4960.8  834.09  4982.2   831.4  4983.5   830.6  4995.9   830.6
  4997.1   831.4  5018.6  838.74  5028.1   839.8  5088.9     841  5240.5     842
  5355.3  844.44  5391.3  843.57  5421.8   844.4  5593.9   843.8  5689.5  841.42
  5722.3  842.72  5796.5  848.48  5937.1  852.27  5954.1  854.16  6049.4  859.14
#Mann= 5 ,-1 , 0
  4234.3      .1       0  4276.7     .05       0  4398.5      .1       0
  4982.2     .07       0  4997.1      .1       0
Bank Sta=4982.2,4997.1
XS Rating Curve= 0 ,0
Exp/Cntr=0.3,0.1

Type RM Length L Ch R = 1 ,111943  ,447,447,447
BEGIN DESCRIPTION:
SF PEREZ CREEK 142.0
END DESCRIPTION:
XS GIS Cut Line= 3
      1982177.91     13657920.46        1981775.       13657675.
      1980655.71     13657306.78
#Sta/Elev= 30
  4492.2  857.24  4829.7  853.72  4882.7   853.3  4919.5  851.48  4928.9  849.55
  4934.9  846.82  4940.8  846.16  4950.4  841.64  4956.3  841.31  4961.1  836.25
  4966.6  836.25  4972.4  828.82  4973.7  828.02  4986.1  828.02  4987.3  828.82
  4995.6  829.69  5011.7  833.28  5016.9  832.77  5033.9   834.4  5248.2  839.49
    5462  839.87  5493.8  840.74  5520.3  842.71    5543  842.98  5748.1  839.47
  5785.2  842.29  5880.6  845.34  5975.9   852.3  6073.9  857.26  6142.3  861.65
#Mann= 6 ,-1 , 0
  4492.2      .1       0  4829.7     .16       0  4972.4     .07       0
  4987.3     .16       0  5033.9      .1       0  6073.9     .16       0
Bank Sta=4972.4,4987.3
XS Rating Curve= 0 ,0
Exp/Cntr=0.3,0.1

Type RM Length L Ch R = 1 ,111496  ,540,540,540
BEGIN DESCRIPTION:
SF PEREZ CREEK 141.0
END DESCRIPTION:
XS GIS Cut Line= 3
      1982529.43     13657746.82      1981696.11      13657160.9
      1980851.35     13656589.06
#Sta/Elev= 30
  4114.6  854.31    4224  852.42  4435.6   849.9  4557.5  845.14  4584.6  843.21
  4679.5  840.67  4887.7  838.96  4951.3  835.46  4959.2  833.31  4965.3  833.31
    4974  831.68  4980.1  831.94  4987.5  828.04  4988.7  827.24  5001.1  827.24
  5002.4  828.04  5045.4  831.96  5116.9  834.44  5209.7  835.74  5245.6  833.49
  5476.3  839.89  5548.2  844.22    5629  847.08  5799.9  857.07  5835.8  858.29
  5907.7  865.46  5952.6  867.39  6009.6  871.33  6096.4   881.4  6153.4  891.35
#Mann= 4 ,-1 , 0
  4114.6     .05       0    4224      .1       0  4987.5     .07       0
  5002.4      .1       0
Bank Sta=4987.5,5002.4
XS Rating Curve= 0 ,0
Exp/Cntr=0.3,0.1

Type RM Length L Ch R = 1 ,110956  ,121,121,121
BEGIN DESCRIPTION:
Mapping XS b073bf4b
END DESCRIPTION:
XS GIS Cut Line= 5
      1982598.91     13657677.41      1982034.66     13657013.33
      1982025.98     13656778.96      1981826.32     13656700.83
       1981024.2     13656349.63
#Sta/Elev= 30
  3724.4  853.41  3836.7  850.07  3920.7   845.8  4048.1  844.33  4168.9  839.12
  4694.2  837.39  4965.2  832.11    5006  828.97  5007.7  828.17    5022  828.97
  5024.8  830.79  5049.2  832.08  5124.9  833.12  5223.8  842.29  5231.8     840
  5247.2  839.88  5270.6  843.98  5308.2  846.94  5351.9  848.66  5369.6  846.42
  5393.5  849.09  5428.3  852.64  5445.2  849.18  5450.7  851.53    5474  850.45
  5492.8  855.28  5765.6   871.5  5799.9   875.7  5832.2   874.8  5920.4  883.63
#Mann= 6 ,-1 , 0
  3724.4     .05       0  3836.7      .1       0    5006     .07       0
    5022      .1       0  5393.5     .16       0  5492.8      .1       0
Bank Sta=5006,5022
XS Rating Curve= 0 ,0
Exp/Cntr=0.3,0.1

Type RM Length L Ch R = 1 ,110835  ,309,309,309
BEGIN DESCRIPTION:
SF PEREZ CREEK 140.0
END DESCRIPTION:
XS GIS Cut Line= 5
      1982789.88      13657568.9      1982234.31     13657074.09
      1982091.08     13656692.15      1981843.68     13656574.96
      1981179.81     13656167.09
#Sta/Elev= 30
  3674.1  854.55  3694.1  853.96  3722.5  859.14  3758.2  852.77  3761.8  852.76
  3884.5   849.9  3921.5  849.12  4048.6  838.54  4268.5   836.5  4632.9   836.7
  4758.9  834.76  4865.9  836.19  4874.6  834.37  4925.6  833.02  4954.4  829.46
  4977.1  828.79  4991.4  827.53  4993.1  826.73  5007.4  827.53  5101.9  836.58
  5127.9  841.64  5244.9  847.04  5403.3  852.25  5543.5  862.23    5732  870.43
    5760  872.48  5781.3   877.2  5812.1  874.25    5818  875.79  5878.9  878.34
#Mann= 8 ,-1 , 0
  3674.1      .1       0  3758.2     .05       0  3761.8     .08       0
  3884.5      .1       0  4977.1     .16       0  4991.4     .07       0
  5007.4     .16       0  5244.9      .1       0
Bank Sta=4991.4,5007.4
XS Rating Curve= 0 ,0
Exp/Cntr=0.3,0.1