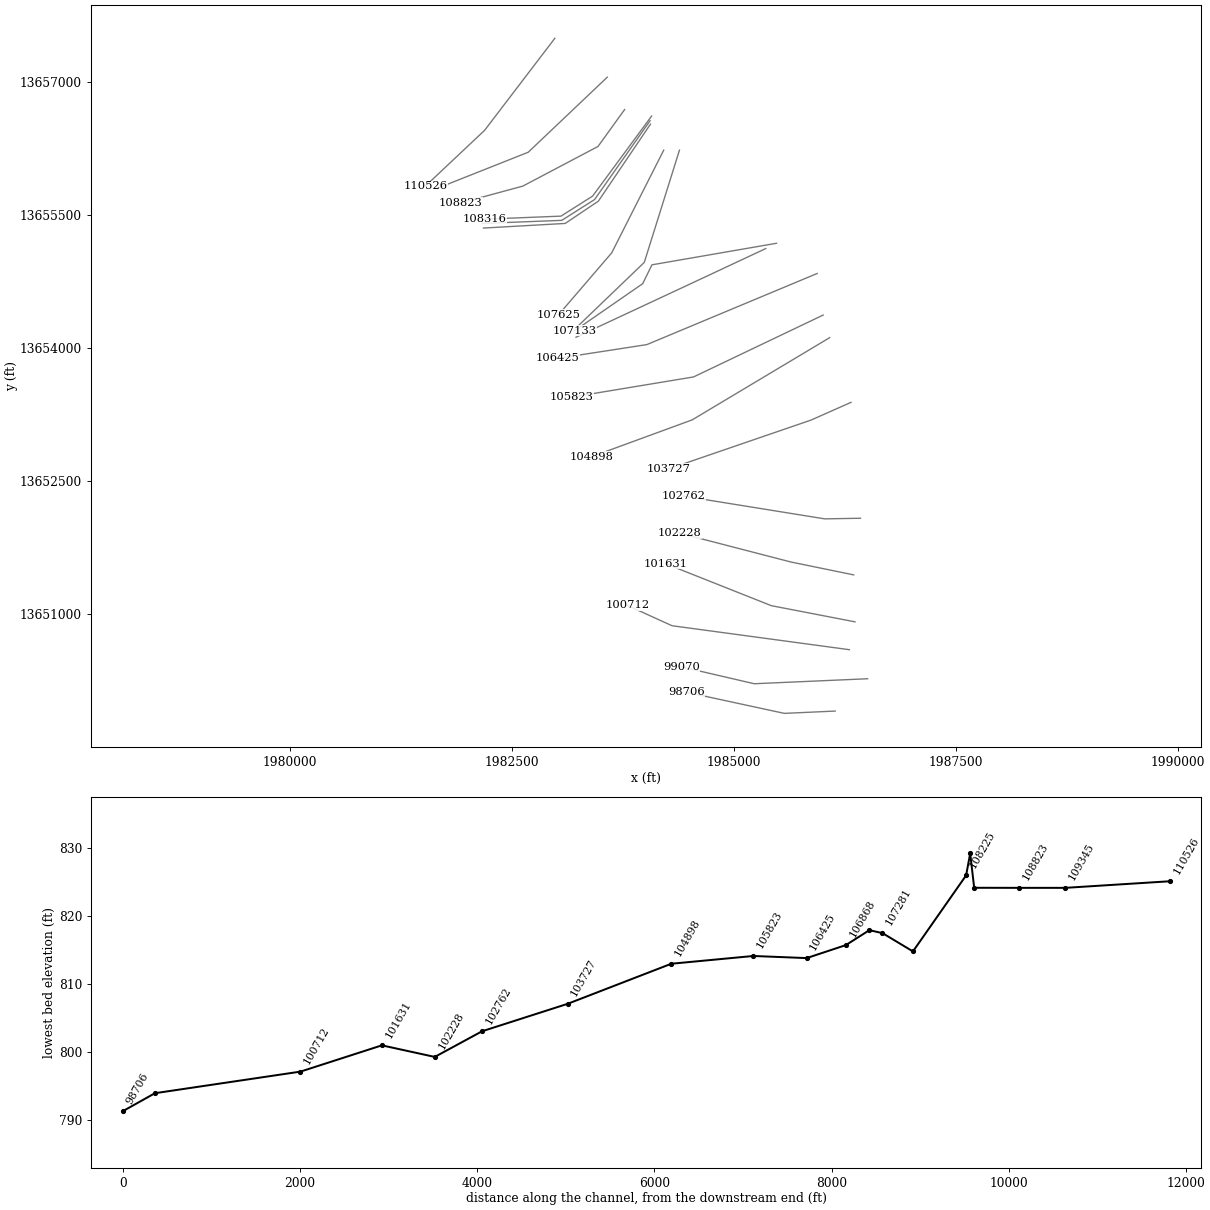
HEC-RAS study SF PEREZ CREEK.prj: SF PEREZ CREEK Base Level Engineering

--- SF PEREZ CREEK.g01 (geometry) --- (continued)

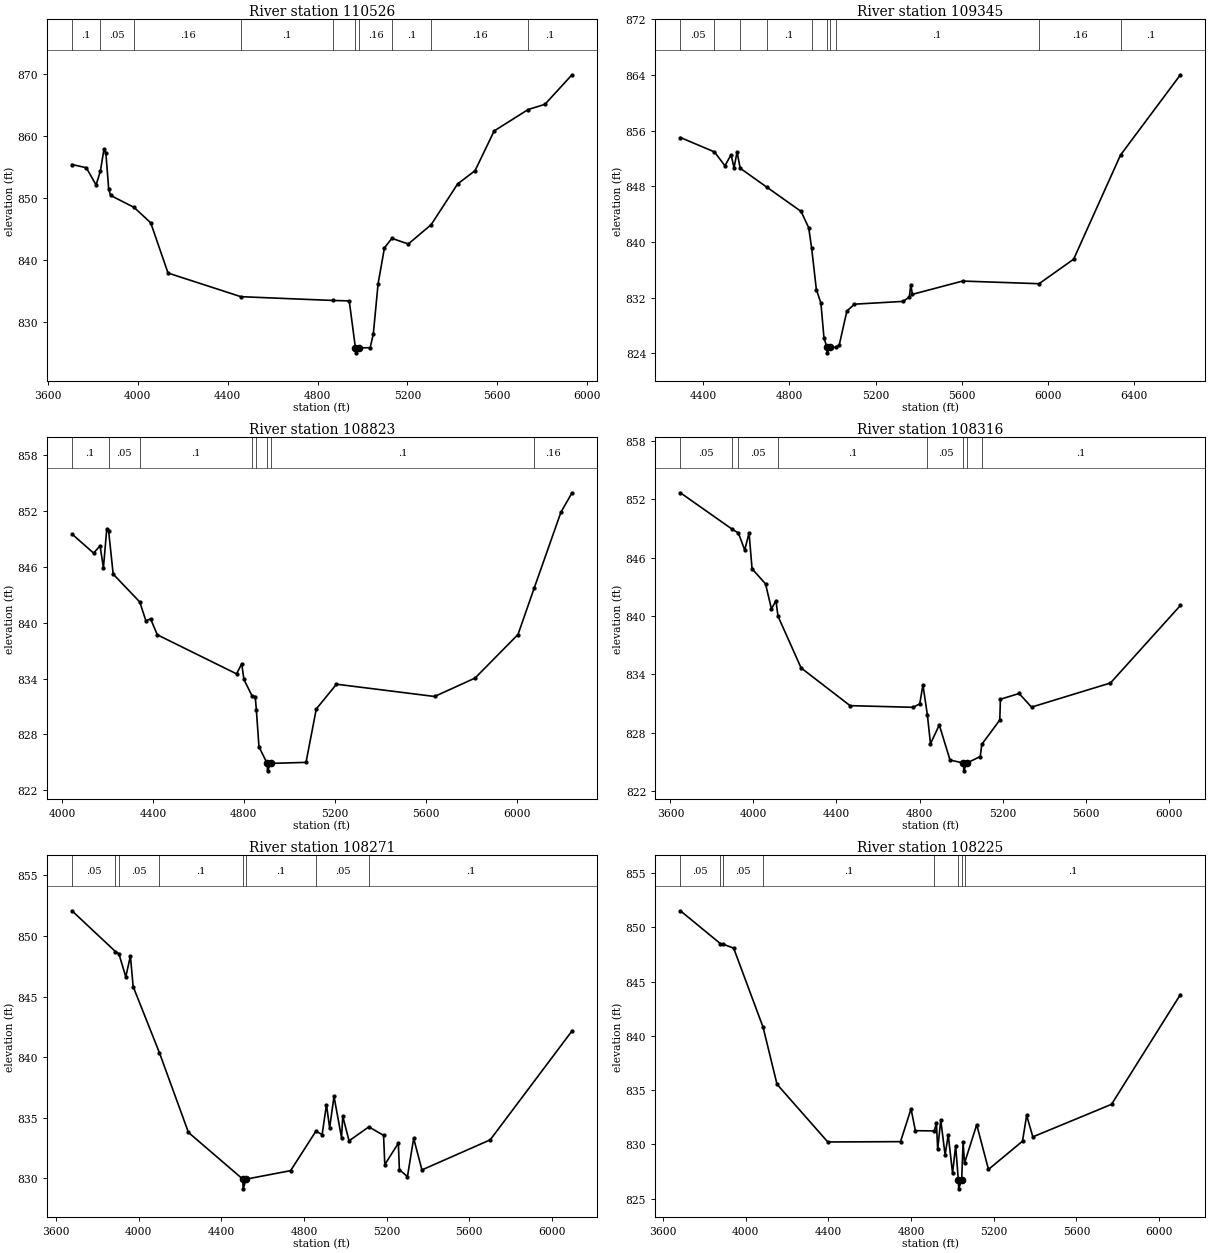
Type RM Length L Ch R = 1 ,110526  ,1181,1181,1181
BEGIN DESCRIPTION:
SF PEREZ CREEK 139.0
END DESCRIPTION:
XS GIS Cut Line= 3
      1982985.17     13657495.09      1982195.25     13656457.78
        1981525.       13655825.
#Sta/Elev= 30
  3707.1   855.4  3770.8  854.88  3814.4   852.1  3833.5  854.34  3849.7  857.92
    3858  857.21  3870.6  851.44  3878.8  850.42  3983.6  848.49  4057.6     846
  4134.6  837.91  4458.8   834.1  4868.7  833.49  4941.2  833.42  4968.7  825.85
  4970.4  825.05  4984.7  825.85  5034.4  825.88  5048.5  828.14  5069.6  836.18
  5097.9  841.98    5131   843.5  5203.9  842.59  5305.8   845.7  5423.6  852.27
  5501.2  854.41  5586.2  860.81  5737.6  864.26  5812.3   865.1  5932.7  869.86
#Mann= 10 ,-1 , 0
  3707.1      .1       0  3833.5     .05       0  3983.6     .16       0
  4458.8      .1       0  4868.7     .16       0  4968.7     .07       0
  4984.7     .16       0    5131      .1       0  5305.8     .16       0
  5737.6      .1       0
Bank Sta=4968.7,4984.7
XS Rating Curve= 0 ,0
Exp/Cntr=0.3,0.1

Type RM Length L Ch R = 1 ,109345  ,522,522,522
BEGIN DESCRIPTION:
SF PEREZ CREEK 138.0
END DESCRIPTION:
XS GIS Cut Line= 3
      1983575.44     13657056.72       1982685.7     13656210.38
      1981670.06     13655806.73
#Sta/Elev= 30
  4293.7  855.01  4451.7  852.94  4500.5  850.95  4528.8  852.53  4542.7  850.67
  4556.8  852.93  4571.1   850.6  4694.8  847.88    4854  844.39  4889.3  842.05
  4902.8  839.15  4924.8  833.16  4945.9  831.24    4960  826.28  4973.4  824.88
  4975.1  824.08  4989.5  824.88  5013.7  824.88  5030.8  825.17  5066.4  830.08
  5101.6  831.07  5328.1  831.47  5356.4  832.11  5363.3  833.87  5370.5  832.48
  5603.5  834.39  5958.7  834.01    6119  837.53  6336.6  852.49  6614.6  864.02
#Mann= 10 ,-1 , 0
  4293.7     .05       0  4451.7      .1       0  4571.1     .05       0
  4694.8      .1       0  4902.8     .05       0  4973.4    .033       0
  4989.5     .05       0  5013.7      .1       0  5958.7     .16       0
  6336.6      .1       0
Bank Sta=4973.4,4989.5
XS Rating Curve= 0 ,0
Exp/Cntr=0.3,0.1

Type RM Length L Ch R = 1 ,108823  ,507,507,507
BEGIN DESCRIPTION:
Mapping XS e239f139
END DESCRIPTION:
XS GIS Cut Line= 4
      1983770.78     13656692.16      1983471.29     13656275.48
      1982624.93     13655828.43      1981921.82     13655637.46
#Sta/Elev= 30
  4044.2  849.53  4139.2  847.48  4167.7  848.26  4182.5  845.89  4197.2  850.09
  4205.2  849.89  4225.4  845.22  4342.2  842.23  4369.1  840.21  4389.9  840.41
  4419.4   838.7    4768   834.5  4790.6  835.59  4800.4   833.9  4836.5  832.11
  4850.1  832.06  4855.1  830.59  4866.5  826.67  4902.4  824.88  4904.2  824.08
  4918.6  824.88  5073.4  824.99  5118.6  830.73  5207.4  833.39  5638.8  832.07
  5816.9  834.05  6005.6  838.73    6077  843.73  6194.2  851.86  6243.1  853.96
#Mann= 8 ,-1 , 0
  4044.2      .1       0  4205.2     .05       0  4342.2      .1       0
  4836.5     .16       0  4855.1      .1       0  4902.4     .07       0
  4918.6      .1       0    6077     .16       0
Bank Sta=4902.4,4918.6
XS Rating Curve= 0 ,0
Exp/Cntr=0.3,0.1

Type RM Length L Ch R = 1 ,108316  ,45,45,45
BEGIN DESCRIPTION:
SF PEREZ CREEK 137.0
END DESCRIPTION:
XS GIS Cut Line= 4
      1984074.59     13656618.37      1983410.52     13655715.59
      1983054.62     13655489.89      1982188.26     13655455.24
#Sta/Elev= 30
  3647.9  852.67  3895.1  848.96  3927.2  848.54  3957.8  846.79  3978.7  848.53
  3993.3  844.85  4058.1  843.31  4086.6  840.73  4108.3  841.58  4118.1  839.99
  4229.4  834.67  4465.5  830.79  4768.6  830.62  4801.2  830.97  4816.5  832.93
  4837.8  829.86  4852.9  826.87  4895.3  828.81    4947   825.2  5011.7  824.89
  5013.5  824.09  5027.9  824.89  5092.7  825.56  5100.3  826.82  5186.8  829.31
  5189.9  831.45  5279.7  832.04  5339.8  830.64  5720.1  833.12  6057.1  841.09
#Mann= 8 ,-1 , 0
  3647.9     .05       0  3895.1      .1       0  3927.2     .05       0
  4118.1      .1       0  4837.8     .05       0  5011.7    .033       0
  5027.9     .05       0  5100.3      .1       0
Bank Sta=5011.7,5027.9
XS Rating Curve= 0 ,0
Exp/Cntr=0.3,0.1

Type RM Length L Ch R = 1 ,108271  ,46,46,46
BEGIN DESCRIPTION:
Mapping XS 8d73d241
END DESCRIPTION:
XS GIS Cut Line= 4
       1984057.2     13656566.24      1983432.23     13655676.53
       1983063.3     13655442.15      1982169.64     13655407.44
#Sta/Elev= 30
  3677.8  852.07  3887.9  848.71  3904.7  848.53    3938  846.62  3960.4  848.34
  3973.7  845.82  4100.6  840.37  4241.2  833.79  4504.1  829.94  4505.9  829.14
  4520.3  829.94  4735.3  830.64    4858   833.9  4887.7  833.61  4908.8  836.07
  4924.1  834.17  4945.3  836.76  4981.7  833.35  4987.6  835.12  5018.1   833.1
  5113.8  834.25    5185  833.55  5190.9  831.14  5256.5   832.9  5261.5  830.72
  5300.5  830.15  5330.6   833.3  5370.6   830.7  5700.8  833.18  6096.5  842.16
#Mann= 8 ,-1 , 0
  3677.8     .05       0  3887.9      .1       0  3904.7     .05       0
  4100.6      .1       0  4504.1    .033       0  4520.3      .1       0
    4858     .05       0  5113.8      .1       0
Bank Sta=4504.1,4520.3
XS Rating Curve= 0 ,0
Exp/Cntr=0.3,0.1

Type RM Length L Ch R = 1 ,108225  ,600,600,600
BEGIN DESCRIPTION:
Mapping XS e920289d
END DESCRIPTION:
XS GIS Cut Line= 4
      1984061.58     13656527.24      1983475.63     13655659.16
      1983102.36     13655407.43      1982182.19     13655355.34
#Sta/Elev= 30
  3684.1  851.54  3877.1  848.52  3890.7  848.46  3941.7   848.1  4084.3   840.8
  4151.5  835.55  4397.2  830.23  4749.1  830.26    4800  833.28    4821  831.27
  4912.4  831.25  4922.9  831.99  4928.9  829.57  4943.9  832.24  4964.9  829.02
  4979.9  830.89  5000.9  827.36  5015.9  829.89  5028.8  826.71  5030.6  825.91
    5045  826.71  5051.8  830.19  5058.9  828.29  5117.8  831.82  5174.7   827.7
  5339.3   830.3  5359.3  832.68  5389.3   830.7    5770   833.7  6103.3  843.82
#Mann= 8 ,-1 , 0
  3684.1     .05       0  3877.1      .1       0  3890.7     .05       0
  4084.3      .1       0  4912.4     .05       0  5028.8    .033       0
    5045     .05       0  5058.9      .1       0
Bank Sta=5028.8,5045
XS Rating Curve= 0 ,0
Exp/Cntr=0.3,0.1

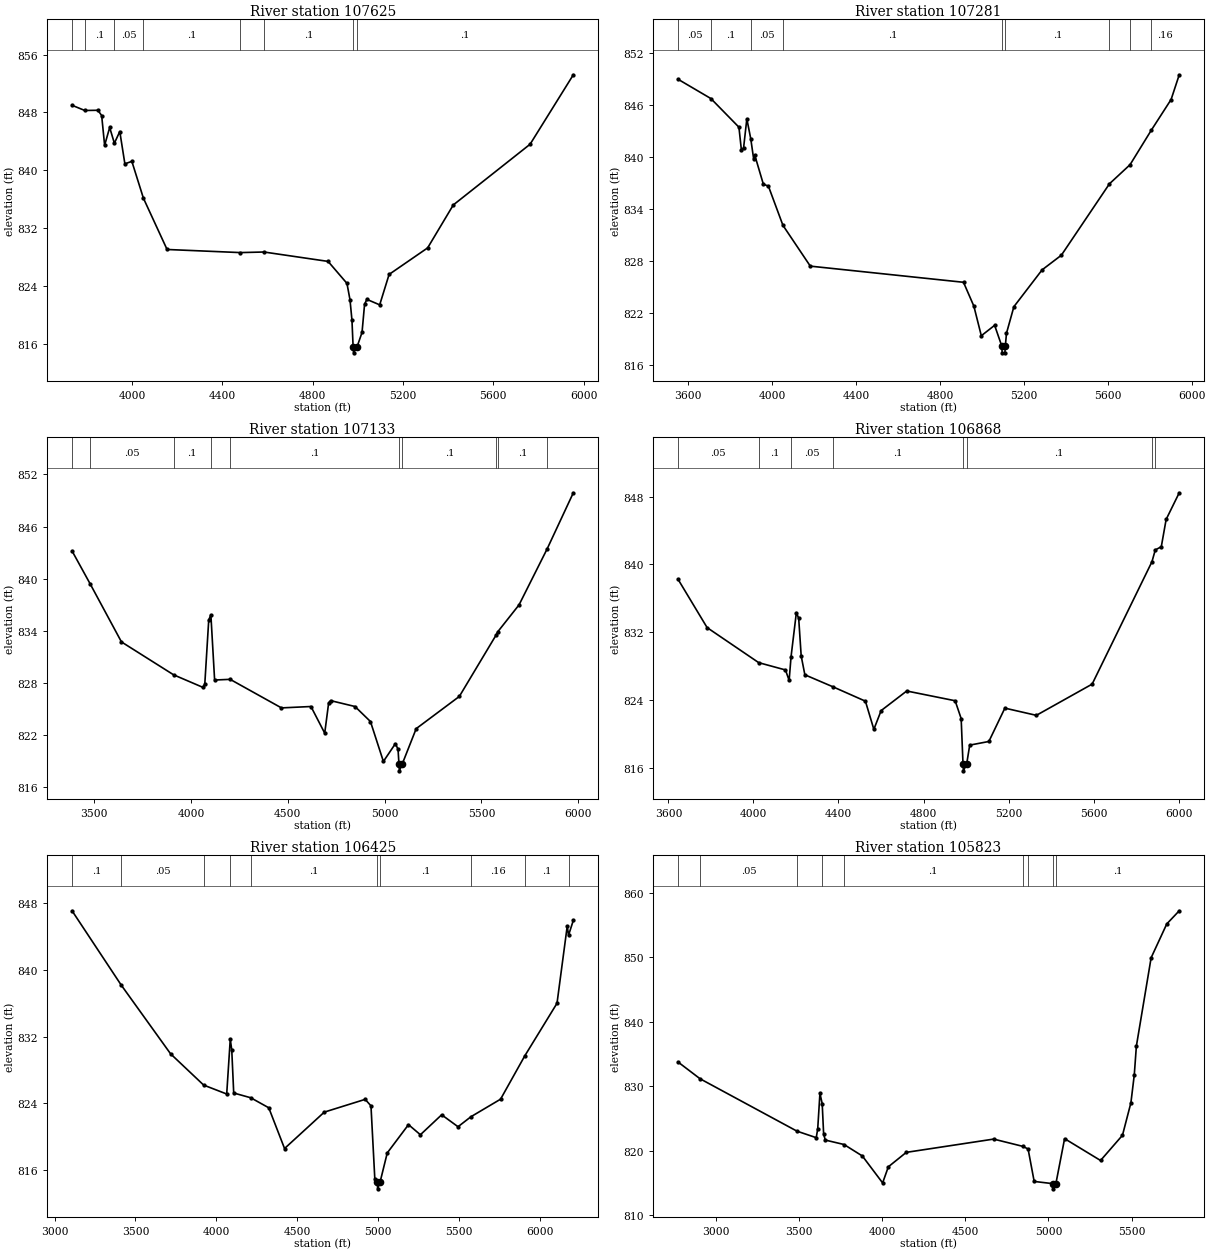
Type RM Length L Ch R = 1 ,107625  ,344,344,344
BEGIN DESCRIPTION:
SF PEREZ CREEK 136.0
END DESCRIPTION:
XS GIS Cut Line= 3
      1984210.86     13656233.79        1983625.       13655075.
      1983025.02     13654375.02
#Sta/Elev= 30
  3734.2  848.99  3790.7  848.27  3848.7   848.3  3865.4  847.57  3878.5  843.45
  3900.9  845.92  3921.7  843.74  3945.7  845.36  3968.2  840.89  3999.1  841.23
  4050.4  836.13  4155.1  829.04  4479.6  828.61  4584.3  828.69  4868.3  827.39
  4951.9  824.35  4965.4  822.08  4974.1  819.25  4979.2  815.54  4981.4  814.74
  4996.4  815.54  5018.7  817.57  5029.9  821.44  5039.8  822.14  5096.9  821.38
  5138.6  825.59  5309.3  829.26  5422.9   835.2  5763.1   843.6  5954.6  853.21
#Mann= 8 ,-1 , 0
  3734.2     .05       0  3790.7      .1       0  3921.7     .05       0
  4050.4      .1       0  4479.6     .05       0  4584.3      .1       0
  4979.2     .07       0  4996.4      .1       0
Bank Sta=4979.2,4996.4
XS Rating Curve= 0 ,0
Exp/Cntr=0.3,0.1

Type RM Length L Ch R = 1 ,107281  ,148,148,148
BEGIN DESCRIPTION:
SF PEREZ CREEK 135.0
END DESCRIPTION:
XS GIS Cut Line= 3
      1984387.97     13656233.85      1983992.12     13654968.19
      1983224.99      13654230.2
#Sta/Elev= 30
  3550.4  848.96  3707.5  846.73  3841.2  843.43    3853  840.78  3863.5  841.07
  3878.9  844.39  3897.6   842.1  3911.4  839.78  3916.6  840.22  3957.8  836.85
  3981.6  836.65  4051.1  832.12  4181.6  827.42  4912.2  825.56  4961.6  822.81
  4997.1   819.4  5060.6   820.6  5094.5  818.23  5096.7  817.43  5109.5  817.43
  5111.7  818.23  5117.2  819.69  5152.5  822.75    5287  826.99  5378.9  828.68
  5608.3  836.91  5706.5  839.11  5807.7  843.08  5902.2  846.62    5941  849.47
#Mann= 9 ,-1 , 0
  3550.4     .05       0  3707.5      .1       0  3897.6     .05       0
  4051.1      .1       0  5094.5     .07       0  5111.7      .1       0
  5608.3     .16       0  5706.5      .1       0  5807.7     .16       0
Bank Sta=5094.5,5111.7
XS Rating Curve= 0 ,0
Exp/Cntr=0.3,0.1

Type RM Length L Ch R = 1 ,107133  ,265,265,265
BEGIN DESCRIPTION:
Mapping XS 6175be17
END DESCRIPTION:
XS GIS Cut Line= 4
      1985480.21     13655183.77      1984078.34     13654940.72
      1983974.17     13654728.05      1983211.32     13654199.26
#Sta/Elev= 30
  3386.4  843.19  3480.8  839.36  3641.5  832.71  3910.8  828.92  4061.5  827.48
  4071.7  827.85    4092  835.23  4103.1  835.84  4122.4  828.32  4202.5   828.4
  4467.5  825.11  4619.7  825.27  4690.8   822.2  4711.1  825.69  4721.2  825.95
  4847.1  825.27  4926.9  823.54  4993.7  818.94  5055.6  820.99  5069.3  820.35
    5074  818.66  5076.2  817.86  5091.2  818.66    5163  822.72  5385.7  826.43
  5577.1  833.56  5583.8  833.87    5694  836.98  5838.9  843.42  5974.2  849.89
#Mann= 10 ,-1 , 0
  3386.4      .1       0  3480.8     .05       0  3910.8      .1       0
  4103.1     .08       0  4202.5      .1       0    5074     .07       0
  5091.2      .1       0  5577.1     .16       0  5583.8      .1       0
  5838.9     .16       0
Bank Sta=5074,5091.2
XS Rating Curve= 0 ,0
Exp/Cntr=0.3,0.1

Type RM Length L Ch R = 1 ,106868  ,443,443,443
BEGIN DESCRIPTION:
SF PEREZ CREEK 134.0
END DESCRIPTION:
XS GIS Cut Line= 3
      1985359.24     13655124.15      1984426.94     13654686.65
      1983223.79     13654124.14
#Sta/Elev= 30
  3644.8  838.26    3782  832.55  4024.7  828.42  4150.5  827.56  4167.8  826.33
  4176.9  829.14  4201.8  834.32  4212.8  833.64  4224.5  829.21  4241.8  826.99
  4373.3  825.58  4526.6  823.88  4566.3  820.56  4600.6  822.77  4720.9  825.08
  4948.7  823.93    4977  821.83  4985.7  816.47  4987.9  815.67  5002.9  816.47
  5017.2   818.7  5107.3  819.13  5182.6  823.06  5330.7  822.21  5593.1  825.89
  5874.4  840.31  5890.2  841.71  5918.4  842.08  5941.2   845.3  6002.8  848.44
#Mann= 8 ,-1 , 0
  3644.8     .05       0  4024.7      .1       0  4176.9     .05       0
  4373.3      .1       0  4985.7     .07       0  5002.9      .1       0
  5874.4     .16       0  5890.2      .1       0
Bank Sta=4985.7,5002.9
XS Rating Curve= 0 ,0
Exp/Cntr=0.3,0.1

Type RM Length L Ch R = 1 ,106425  ,602,602,602
BEGIN DESCRIPTION:
SF PEREZ CREEK 133.0
END DESCRIPTION:
XS GIS Cut Line= 3
      1985937.33     13654842.89      1984020.69     13654040.82
       1983010.3     13653884.57
#Sta/Elev= 30
  3107.8  847.07  3411.5  838.18  3717.4  829.93  3921.7  826.19  4064.3  825.12
  4086.3  831.69  4095.5  830.41  4107.6  825.24    4213  824.67  4324.4  823.47
    4422  818.59  4667.7  822.95  4920.7  824.48  4956.5   823.7  4980.3  814.93
  4995.5  814.56  4997.7  813.76  5012.7  814.56  5057.1  818.06  5188.5  821.45
  5262.1  820.24  5393.6  822.63  5494.8   821.2  5574.9   822.4  5757.9   824.5
  5907.4  829.68    6107  835.99  6170.1  845.22  6178.4  844.15  6207.9  845.92
#Mann= 10 ,-1 , 0
  3107.8      .1       0  3411.5     .05       0  3921.7      .1       0
  4086.3     .05       0    4213      .1       0  4995.5     .07       0
  5012.7      .1       0  5574.9     .16       0  5907.4      .1       0
  6178.4     .16       0
Bank Sta=4995.5,5012.7
XS Rating Curve= 0 ,0
Exp/Cntr=0.3,0.1

Type RM Length L Ch R = 1 ,105823  ,925,925,925
BEGIN DESCRIPTION:
SF PEREZ CREEK 132.0
END DESCRIPTION:
XS GIS Cut Line= 3
      1986005.04     13654374.14      1984546.74     13653676.24
      1983168.31     13653447.36
#Sta/Elev= 30
  2772.5  833.76  2905.5  831.15  3488.2  823.02    3604  822.01  3612.8  823.37
  3626.2  828.89  3639.8  827.29  3648.4   822.6  3658.1  821.64  3770.9  820.95
  3881.2  819.17  4003.1  814.99  4037.5  817.49  4145.3  819.73  4670.6  821.79
  4844.8  820.67  4877.7  820.26  4914.3  815.22  5027.6  814.87  5029.8  814.07
  5044.8  814.87  5097.2  821.86  5313.4  818.47  5445.2  822.38  5495.9  827.42
  5516.2  831.75  5528.8  836.22  5617.5  849.93  5711.6  855.18  5786.5  857.22
#Mann= 9 ,-1 , 0
  2772.5      .1       0  2905.5     .05       0  3488.2      .1       0
  3639.8     .05       0  3770.9      .1       0  4844.8     .05       0
  4877.7      .1       0  5027.6     .07       0  5044.8      .1       0
Bank Sta=5027.6,5044.8
XS Rating Curve= 0 ,0
Exp/Cntr=0.3,0.1

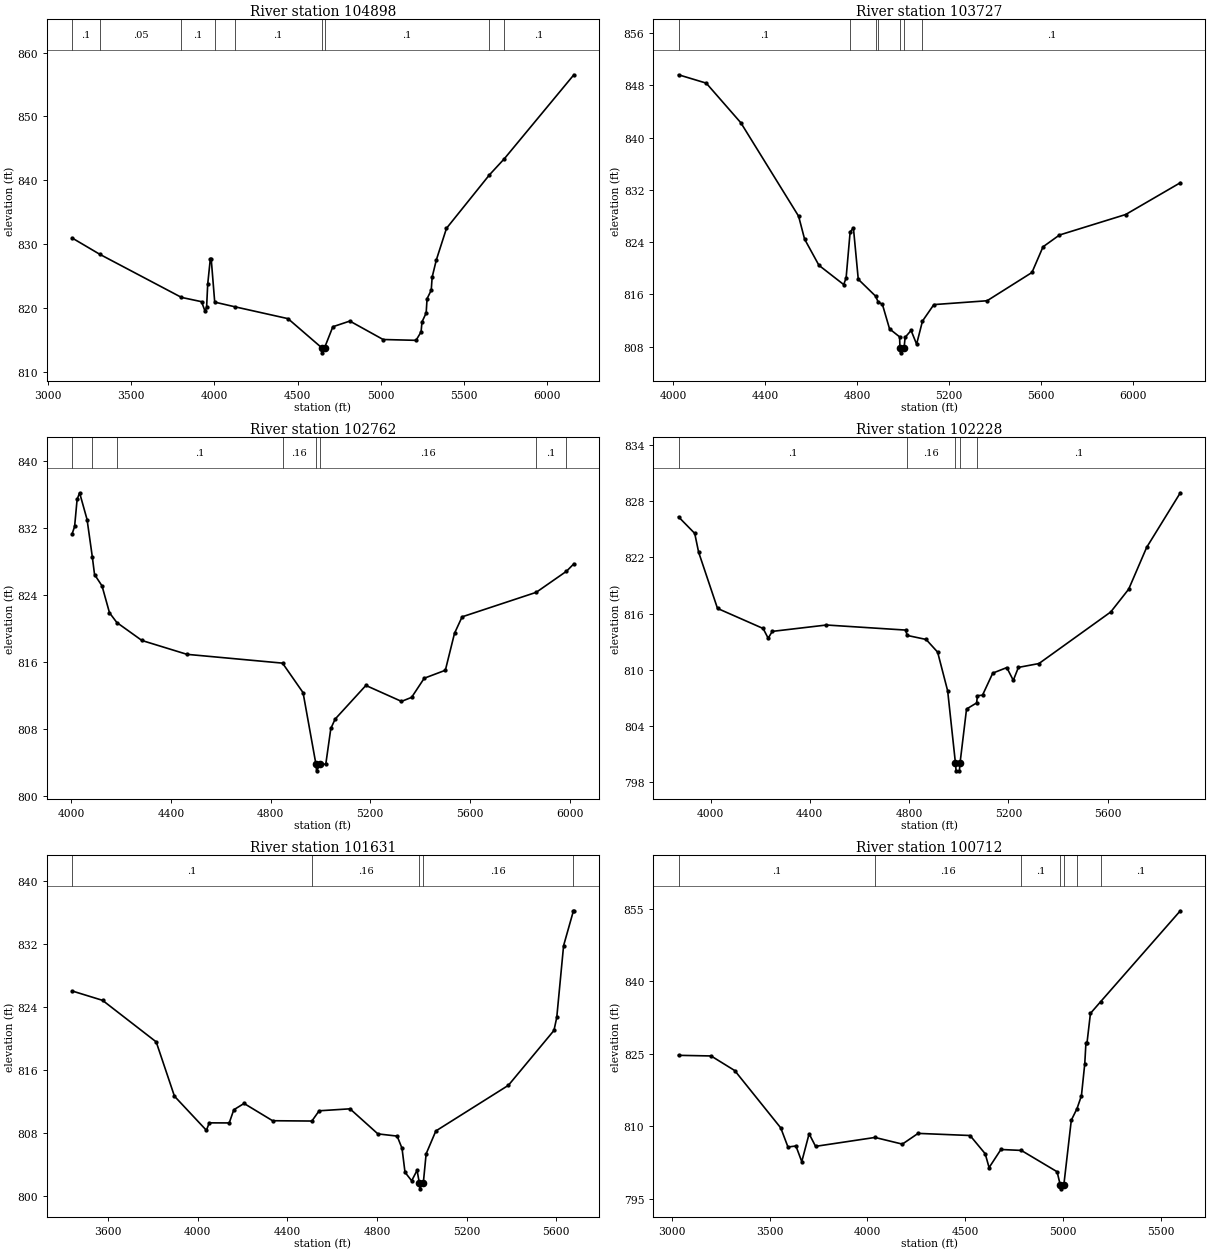
Type RM Length L Ch R = 1 ,104898  ,1171,1171,1171
BEGIN DESCRIPTION:
SF PEREZ CREEK 131.0
END DESCRIPTION:
XS GIS Cut Line= 3
      1986077.99     13654118.94      1984531.11     13653191.86
      1983395.67     13652775.18
#Sta/Elev= 30
  3146.3  830.94  3313.9  828.36  3803.2  821.62  3923.7  820.95  3945.1  819.43
  3954.2  820.12  3960.7  823.69  3976.2   827.6    3982  827.57  4002.8  820.88
  4123.7  820.15  4442.8  818.29  4645.1  813.73  4647.3  812.93  4662.4  813.73
    4712  817.02  4814.1  817.91    5014  815.02  5211.5  814.89  5241.9  816.21
  5247.3  817.77  5272.4  819.18  5277.8  821.42  5302.9  822.75  5308.3  824.79
  5333.4  827.49  5394.4  832.45  5652.6  840.84  5741.8  843.36  6159.2  856.52
#Mann= 9 ,-1 , 0
  3146.3      .1       0  3313.9     .05       0  3803.2      .1       0
  4002.8     .05       0  4123.7      .1       0  4645.1     .07       0
  4662.4      .1       0  5652.6     .16       0  5741.8      .1       0
Bank Sta=4645.1,4662.4
XS Rating Curve= 0 ,0
Exp/Cntr=0.3,0.1

Type RM Length L Ch R = 1 ,103727  ,965,965,965
BEGIN DESCRIPTION:
SF PEREZ CREEK 130.0
END DESCRIPTION:
XS GIS Cut Line= 3
      1986318.75     13653389.58      1985868.75     13653189.58
      1984270.02     13652640.02
#Sta/Elev= 30
  4023.3  849.64  4143.8  848.36  4294.3  842.29  4545.7  827.97  4571.6  824.47
  4634.1  820.45  4741.8   817.5  4752.3  818.51  4769.8  825.55  4784.1  826.18
  4805.2  818.31  4880.5  815.73  4892.3  814.79    4910  814.49  4941.3  810.71
    4985  809.49  4986.5  807.84    4989  807.04  5004.7  807.84    5009  809.41
    5035  810.47    5059  808.37  5084.6  811.91    5134  814.43  5365.7  815.02
  5560.8  819.35  5608.9  823.28  5680.5  825.09  5968.4  828.23  6206.3   833.1
#Mann= 7 ,-1 , 0
  4023.3      .1       0  4769.8     .05       0  4880.5      .1       0
  4892.3     .16       0  4986.5     .07       0  5004.7     .16       0
  5084.6      .1       0
Bank Sta=4986.5,5004.7
XS Rating Curve= 0 ,0
Exp/Cntr=0.3,0.1

Type RM Length L Ch R = 1 ,102762  ,534,534,534
BEGIN DESCRIPTION:
SF PEREZ CREEK 129.0
END DESCRIPTION:
XS GIS Cut Line= 3
      1986425.22     13652082.49      1986022.43     13652075.54
       1984432.2     13652332.48
#Sta/Elev= 30
  4003.6  831.24  4013.8  832.14  4023.8  835.36  4033.8  836.16  4063.8  832.97
  4084.9  828.51  4093.8  826.41  4123.8  825.06  4153.8  821.85  4183.3  820.69
  4283.9  818.55  4464.6   816.9  4848.2  815.85  4930.6  812.33  4982.2  803.81
  4984.7  803.01  5000.5  803.81  5021.8  803.81    5042  808.06  5059.3  809.18
  5182.7  813.19  5325.6  811.29  5366.2  811.77  5416.8  814.05  5501.6     815
  5538.4  819.41  5568.8  821.37  5866.1  824.29  5987.5   826.8  6017.3  827.69
#Mann= 8 ,-1 , 0
  4003.6     .05       0  4084.9     .08       0  4183.3      .1       0
  4848.2     .16       0  4982.2     .07       0  5000.5     .16       0
  5866.1      .1       0  5987.5     .16       0
Bank Sta=4982.2,5000.5
XS Rating Curve= 0 ,0
Exp/Cntr=0.3,0.1

Type RM Length L Ch R = 1 ,102228  ,597,597,597
BEGIN DESCRIPTION:
SF PEREZ CREEK 128.0
END DESCRIPTION:
XS GIS Cut Line= 3
      1986348.81      13651443.6      1985640.49     13651589.43
      1984383.56     13651915.82
#Sta/Elev= 30
  3871.2  826.32  3936.4  824.56  3952.1  822.56  4028.2  816.56    4212  814.42
  4232.4  813.38  4248.9  814.11  4467.3  814.79    4786  814.25  4792.5  813.68
  4868.7  813.25  4915.1   811.9  4955.6  807.76    4987  800.04  4989.5  799.24
  5002.8  799.24  5005.3  800.04  5031.6  805.83  5072.1  806.48  5075.7  807.25
    5096  807.31  5137.3  809.66  5193.8  810.25    5220  808.89  5240.6  810.27
  5323.3  810.68  5612.6  816.18  5684.9  818.61  5757.2  823.06    5893  828.89
#Mann= 5 ,-1 , 0
  3871.2      .1       0  4792.5     .16       0    4987     .07       0
  5005.3     .16       0  5075.7      .1       0
Bank Sta=4987,5005.3
XS Rating Curve= 0 ,0
Exp/Cntr=0.3,0.1

Type RM Length L Ch R = 1 ,101631  ,919,919,919
BEGIN DESCRIPTION:
SF PEREZ CREEK 127.0
END DESCRIPTION:
XS GIS Cut Line= 3
      1986363.54     13650914.18      1985421.74     13651096.46
      1984232.47     13651569.57
#Sta/Elev= 30
  3439.3  826.04  3575.3  824.85  3814.7  819.58  3896.2  812.69  4038.8  808.36
  4051.4  809.31  4140.6   809.3    4161  810.97  4206.8  811.77  4334.1  809.58
  4509.4  809.54  4541.9  810.84  4679.5  811.09    4804  807.91  4889.9  807.63
  4911.7  806.08    4925  803.04  4954.7  801.96  4978.9  803.29  4988.6  801.74
  4991.1  800.94  5006.9  801.74  5019.3  805.38  5062.6  808.28  5386.3  814.07
  5589.7  821.03  5602.2  822.68  5632.7  831.79  5676.7  836.21  5678.5  836.21
#Mann= 5 ,-1 , 0
  3439.3      .1       0  4509.4     .16       0  4988.6     .07       0
  5006.9     .16       0  5676.7      .1       0
Bank Sta=4988.6,5006.9
XS Rating Curve= 0 ,0
Exp/Cntr=0.3,0.1

Type RM Length L Ch R = 1 ,100712  ,1642,1642,1642
BEGIN DESCRIPTION:
SF PEREZ CREEK 126.0
END DESCRIPTION:
XS GIS Cut Line= 3
      1986300.01       13650600.      1984304.45     13650870.25
      1983799.98     13651100.01
#Sta/Elev= 30
    3033  824.67  3199.5  824.54  3320.6  821.52  3556.2  809.67  3593.1  805.72
  3633.8  805.94  3663.7   802.7  3701.3  808.46  3734.3  805.86  4038.4   807.7
  4178.4  806.32  4259.1  808.54  4524.9   808.1  4602.5  804.33  4622.4  801.47
  4682.9  805.21  4787.3  805.02  4970.5  800.61  4986.6  797.88  4989.1  797.08
  5004.9  797.88  5043.1  811.26  5072.2  813.64    5095  816.33  5112.1  822.96
  5118.1  827.28  5123.6  827.28  5141.1  833.34  5193.6  835.77  5601.1  854.54
#Mann= 7 ,-1 , 0
    3033      .1       0  4038.4     .16       0  4787.3      .1       0
  4986.6     .07       0  5004.9      .1       0  5072.2     .16       0
  5193.6      .1       0
Bank Sta=4986.6,5004.9
XS Rating Curve= 0 ,0
Exp/Cntr=0.3,0.1

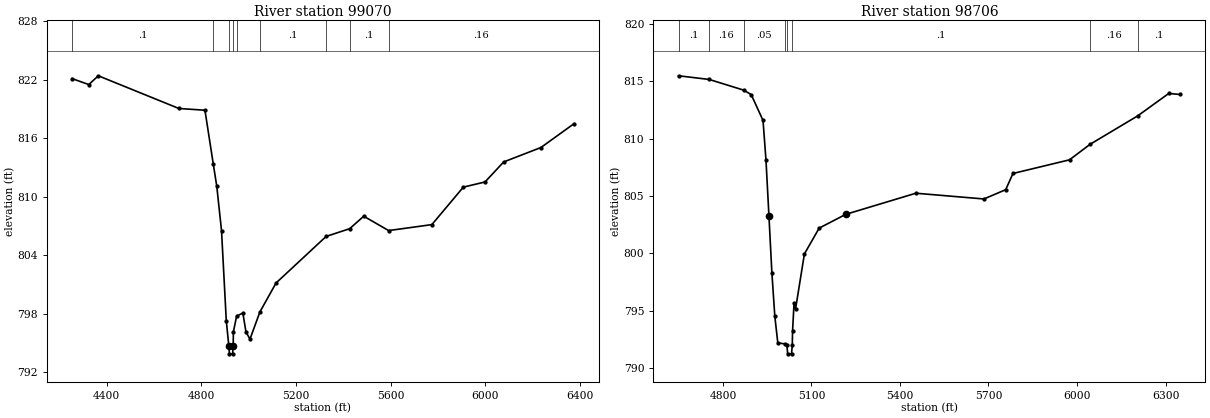
Type RM Length L Ch R = 1 ,99070   ,364,364,364
BEGIN DESCRIPTION:
SF PEREZ CREEK 125.0
END DESCRIPTION:
XS GIS Cut Line= 3
      1986505.62     13650272.37      1985229.58     13650215.94
      1984409.59     13650406.84
#Sta/Elev= 30
  4254.1  822.11  4324.8   821.5  4364.8   822.4  4705.2  819.05  4815.3  818.87
  4850.7  813.32  4865.3  811.07  4885.3  806.53  4905.4   797.3  4916.2  794.71
  4918.7  793.91    4932  793.91  4934.5  794.71  4935.4  796.17  4949.1  797.78
  4975.4  798.09  4988.6  796.15  5005.5  795.42  5047.5  798.21  5115.6  801.17
  5327.1  805.94  5426.4  806.73  5485.9  808.01    5591  806.54  5773.6  807.15
  5906.5  810.99  5998.1  811.52  6076.8  813.57  6234.3  815.05  6373.3  817.48
#Mann= 9 ,-1 , 0
  4254.1      .1       0  4850.7     .16       0  4916.2    .035       0
  4934.5     .16       0  4949.1     .05       0  5047.5      .1       0
  5327.1     .16       0  5426.4      .1       0    5591     .16       0
Bank Sta=4916.2,4934.5
XS Rating Curve= 0 ,0
Exp/Cntr=0.3,0.1

Type RM Length L Ch R = 1 ,98706   ,369,369,369
BEGIN DESCRIPTION:
SF PEREZ CREEK 124.0
END DESCRIPTION:
XS GIS Cut Line= 3
      1986141.01     13649907.78      1985568.12     13649881.74
      1984466.73     13650120.23
#Sta/Elev= 30
  4649.7  815.48  4753.6  815.16  4870.4  814.23    4896  813.84    4936  811.59
    4946  808.15    4956   803.3    4966  798.33    4976  794.52  4986.1  792.21
  5009.6  792.13  5016.9  792.06  5019.4  791.26  5032.7  791.26  5035.2  792.06
  5036.1  793.23  5041.2  795.72  5046.2  795.16  5076.2  799.96  5126.2  802.21
  5216.3  803.41  5453.9  805.25  5684.6  804.75  5758.4  805.56    5783  806.97
  5974.7  808.16  6044.2  809.51  6205.2  811.98  6310.9  813.94  6350.1  813.85
#Mann= 8 ,-1 , 0
  4649.7      .1       0  4753.6     .16       0  4870.4     .05       0
  5009.6      .1       0  5016.9    .035       0  5035.2      .1       0
  6044.2     .16       0  6205.2      .1       0
Bank Sta=4956,5216.3
XS Rating Curve= 0 ,0
Exp/Cntr=0.3,0.1