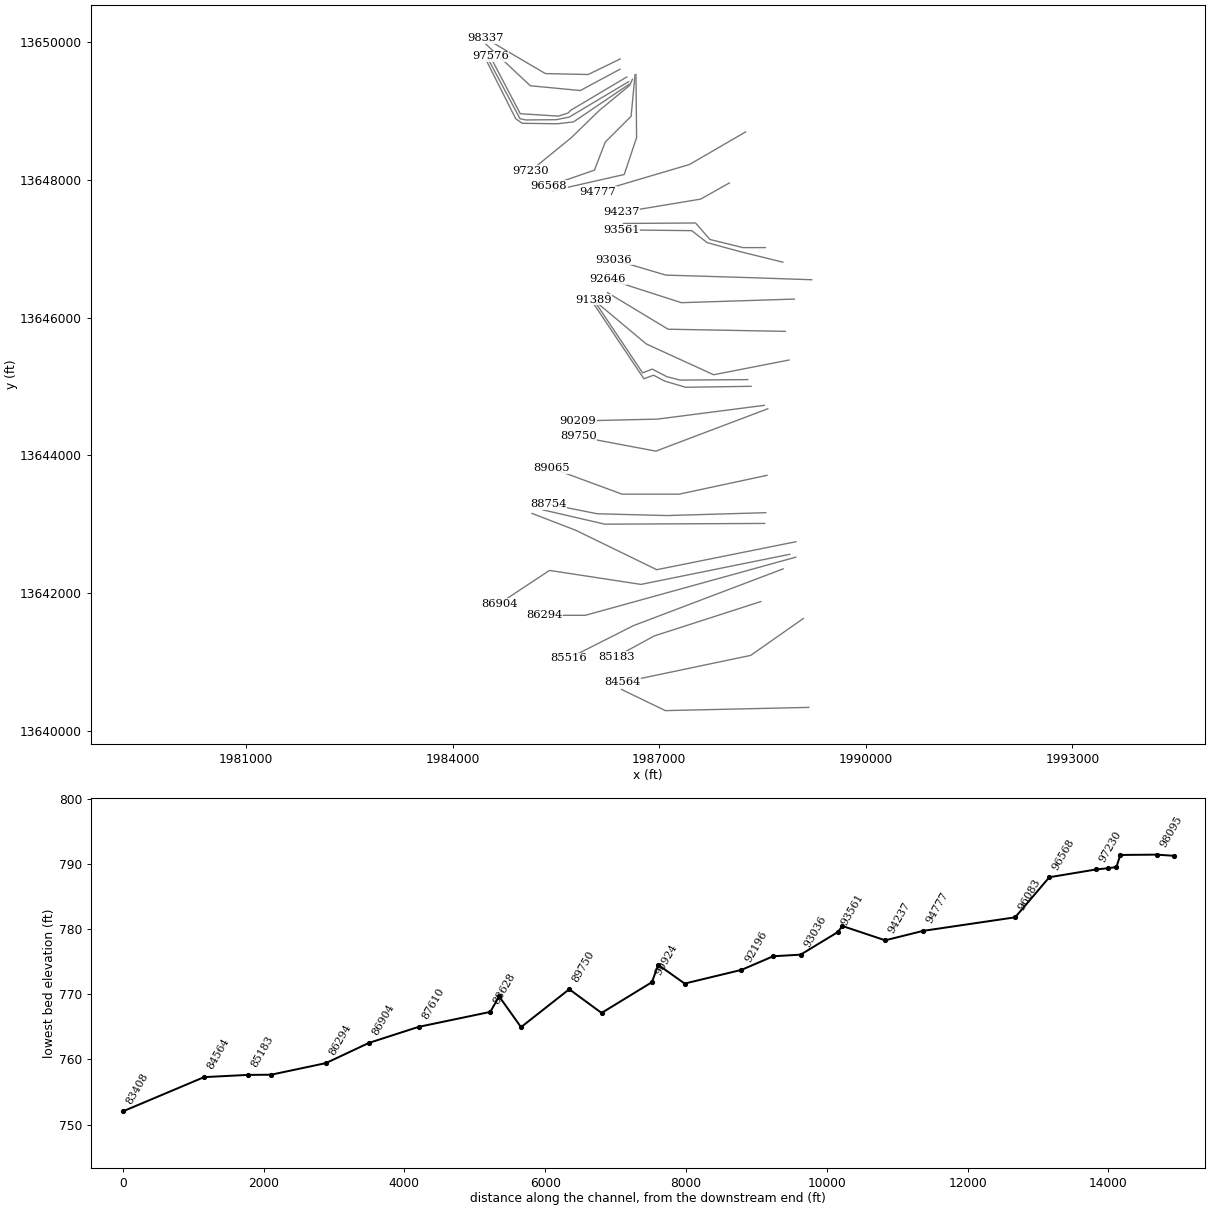
HEC-RAS study SF PEREZ CREEK.prj: SF PEREZ CREEK Base Level Engineering

--- SF PEREZ CREEK.g01 (geometry) --- (continued)

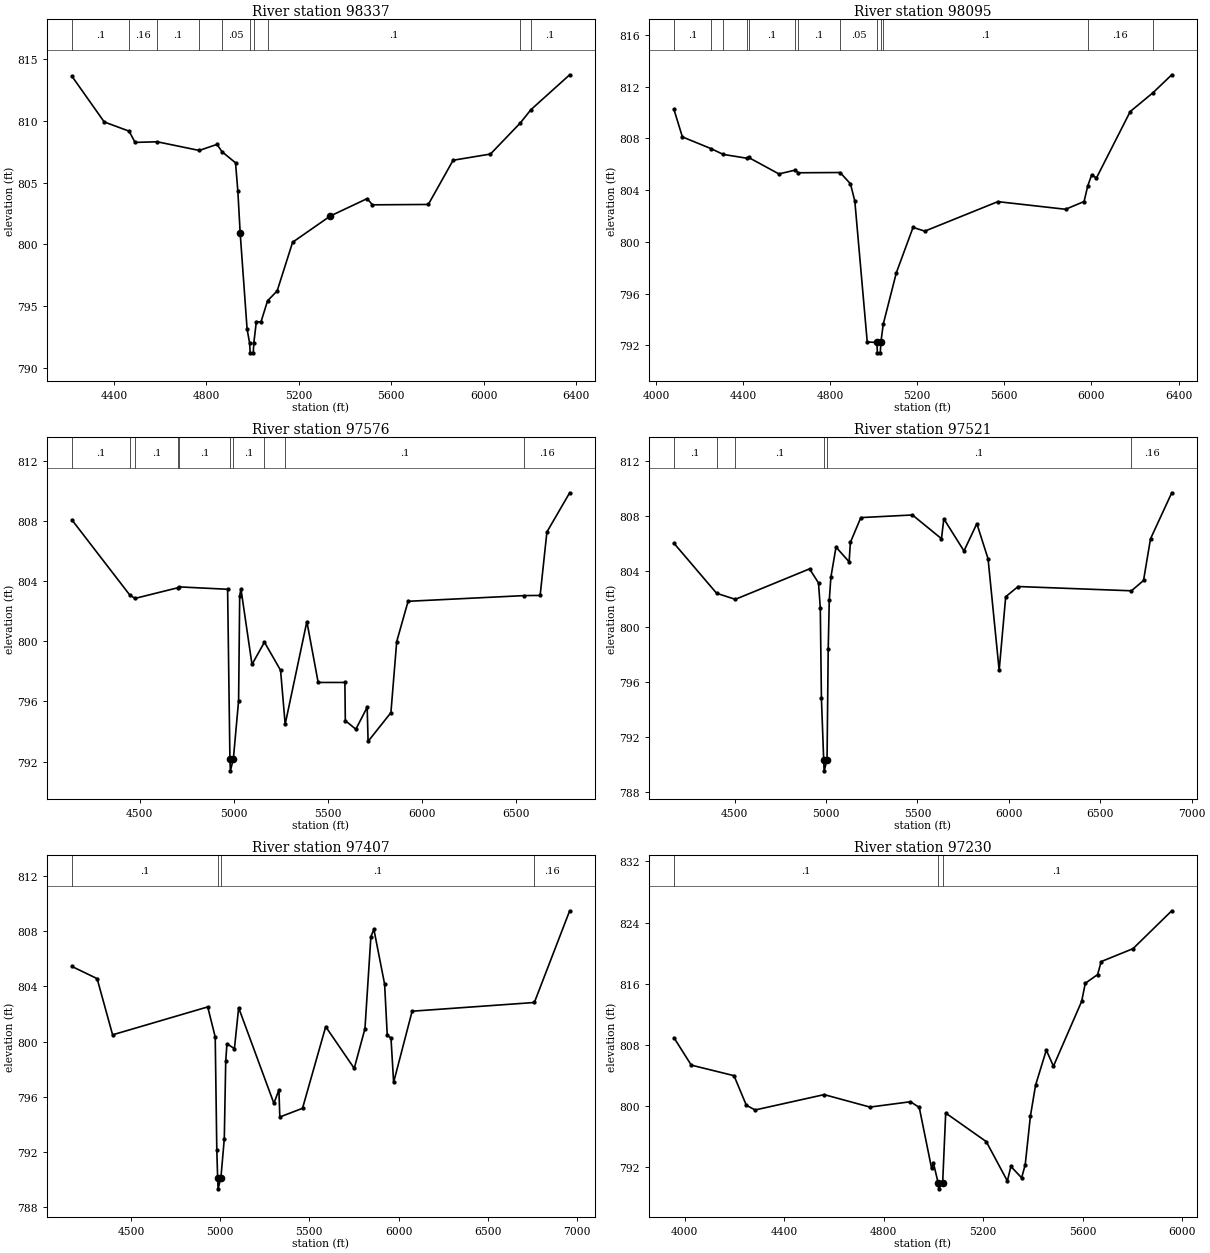
Type RM Length L Ch R = 1 ,98337   ,242,242,242
BEGIN DESCRIPTION:
Mapping XS f46e0bfb
END DESCRIPTION:
XS GIS Cut Line= 4
      1986430.96     13649755.87      1985965.69     13649530.18
      1985344.16     13649544.07      1984469.54     13650057.73
#Sta/Elev= 30
  4218.2  813.59  4358.2  809.89  4465.6  809.15  4491.6  808.24  4587.3  808.29
    4769  807.59    4846  808.08  4867.5  807.49  4926.1  806.59  4936.1  804.31
  4946.1  800.94  4976.1  793.16  4986.9  792.05  4989.4  791.25  5002.7  791.25
  5005.2  792.05  5016.1  793.77  5036.1  793.74  5064.5  795.45  5106.1  796.25
    5173  800.18  5336.2   802.3  5495.2   803.7  5518.4   803.2  5759.9  803.23
  5867.2   806.8  6028.7   807.3  6158.3  809.82  6203.6  810.88  6371.3   813.7
#Mann= 10 ,-1 , 0
  4218.2      .1       0  4465.6     .16       0  4587.3      .1       0
    4769     .16       0  4867.5     .05       0  4986.9    .035       0
  5005.2     .05       0  5064.5      .1       0  6158.3     .16       0
  6203.6      .1       0
Bank Sta=4946.1,5336.2
XS Rating Curve= 0 ,0
Exp/Cntr=0.3,0.1

Type RM Length L Ch R = 1 ,98095   ,519,519,519
BEGIN DESCRIPTION:
Mapping XS 841fee95
END DESCRIPTION:
XS GIS Cut Line= 4
      1986427.53     13649606.59      1985851.11     13649297.54
      1985125.41     13649366.98      1984465.66     13649985.07
#Sta/Elev= 30
  4081.9  810.23  4120.7  808.11    4253   807.2    4308  806.76  4417.8  806.46
  4425.3  806.52  4564.2  805.25  4637.4  805.54  4652.7  805.34  4845.3  805.36
  4892.8  804.49  4912.9  803.15  4969.9  792.27  5014.2  792.23  5016.7  791.43
    5030  791.43  5032.5  792.23  5043.6  793.65  5103.7  797.62  5180.4  801.12
  5234.3  800.83    5570  803.11  5881.2  802.52  5966.2  803.12  5982.9  804.32
  6001.4  805.19  6022.8  804.93  6178.2  810.07  6283.2  811.53    6369  812.91
#Mann= 13 ,-1 , 0
  4081.9      .1       0    4253     .16       0    4308      .1       0
  4417.8     .16       0  4425.3      .1       0  4637.4     .16       0
  4652.7      .1       0  4845.3     .05       0  5014.2    .035       0
  5032.5     .05       0  5043.6      .1       0  5982.9     .16       0
  6283.2      .1       0
Bank Sta=5014.2,5032.5
XS Rating Curve= 0 ,0
Exp/Cntr=0.3,0.1

Type RM Length L Ch R = 1 ,97576   ,55,55,55
BEGIN DESCRIPTION:
Mapping XS d428966c
END DESCRIPTION:
XS GIS Cut Line= 6
       1986528.2     13649495.46      1985715.69     13649012.82
      1985674.02     13648971.15      1985531.66     13648926.01
      1984979.58     13648960.73      1984542.06      13649794.1
#Sta/Elev= 30
  4140.2  808.08  4446.9   803.1  4475.3  802.85  4703.5  803.56  4708.9  803.62
  4968.6  803.46  4980.9  792.18  4983.4  791.38  4999.2  792.18  5027.1  796.05
  5032.9  803.01  5039.5  803.49  5098.3  798.46  5164.5  799.94  5250.3  798.07
  5274.8  794.48  5390.2  801.31  5450.3  797.26  5592.5  797.26  5594.7  794.72
  5650.8  794.15  5710.9  795.61  5715.9  793.34  5837.2  795.25  5868.1  799.98
  5928.6  802.66  6547.4  803.04    6631  803.05    6667  807.27  6788.1  809.88
#Mann= 10 ,-1 , 0
  4140.2      .1       0  4446.9     .16       0  4475.3      .1       0
  4703.5     .16       0  4708.9      .1       0  4980.9     .07       0
  4999.2      .1       0  5164.5     .05       0  5274.8      .1       0
  6547.4     .16       0
Bank Sta=4980.9,4999.2
XS Rating Curve= 0 ,0
Exp/Cntr=0.3,0.1

Type RM Length L Ch R = 1 ,97521   ,114,114,114
BEGIN DESCRIPTION:
Mapping XS 41a20227
END DESCRIPTION:
XS GIS Cut Line= 6
      1986552.49     13649426.01      1985691.38     13648912.12
      1985500.41     13648873.93      1985059.44     13648870.46
      1984976.11     13648887.82      1984507.34     13649766.32
#Sta/Elev= 30
  4168.1  806.04  4401.4  802.41  4503.8  801.97  4909.8  804.18  4958.8  803.16
  4968.6  801.35  4974.8  794.78  4987.2  790.33  4989.7  789.53  5005.5  790.33
  5011.9  798.34  5017.7   801.9  5026.6  803.58  5054.6  805.76  5126.4  804.69
  5133.1   806.1  5190.4   807.9  5472.6  808.09  5631.4  806.37  5644.4  807.81
  5754.6  805.48    5825  807.46  5886.3  804.91    5947  796.82  5982.8  802.16
  6050.8   802.9  6670.9  802.59  6736.7  803.34  6774.9  806.36  6891.1   809.7
#Mann= 6 ,-1 , 0
  4168.1      .1       0  4401.4     .16       0  4503.8      .1       0
  4987.2     .07       0  5005.5      .1       0  6670.9     .16       0
Bank Sta=4987.2,5005.5
XS Rating Curve= 0 ,0
Exp/Cntr=0.3,0.1

Type RM Length L Ch R = 1 ,97407   ,177,177,177
BEGIN DESCRIPTION:
Mapping XS 6c214d74
END DESCRIPTION:
XS GIS Cut Line= 6
      1986559.44     13649387.81      1985753.88     13648842.68
      1985521.25      13648814.9      1985007.36     13648821.85
      1984913.61     13648887.82      1984483.53     13649741.03
#Sta/Elev= 30
  4168.5  805.45    4310  804.57  4396.9   800.5  4930.2  802.52  4972.2  800.34
  4981.1  792.17  4985.8  790.15  4988.3  789.35  5004.1  790.15  5023.1  792.97
  5031.2  798.61    5038  799.85    5080   799.5  5103.6  802.46  5301.2  795.54
  5329.4  796.51  5334.4  794.55  5461.7  795.18  5591.7  801.09  5751.7  798.07
  5811.8  800.95  5845.1  807.61  5861.8  808.14    5922  804.17  5936.8  800.46
  5957.7  800.28  5972.5  797.06  6076.3  802.21  6761.6  802.84  6959.6  809.48
#Mann= 4 ,-1 , 0
  4168.5      .1       0  4985.8     .07       0  5004.1      .1       0
  6761.6     .16       0
Bank Sta=4985.8,5004.1
XS Rating Curve= 0 ,0
Exp/Cntr=0.3,0.1

Type RM Length L Ch R = 1 ,97230   ,662,662,662
BEGIN DESCRIPTION:
Mapping XS 4bb0a417
END DESCRIPTION:
XS GIS Cut Line= 5
       1986609.2      13649461.8       1986569.3     13649372.63
       1986124.8     13649006.03      1985723.76     13648615.41
      1985129.98     13648131.01
#Sta/Elev= 30
  3957.6  808.93  4027.2  805.34  4198.9  803.96  4248.4  800.09  4283.6  799.47
  4561.1  801.48  4745.1  799.85  4907.9  800.55  4943.2   799.8  4992.8  791.82
  4999.8  792.57  5018.9  789.95  5021.4  789.15  5037.2  789.95  5049.4  799.07
  5212.4  795.33  5297.1  790.18  5311.4  792.08  5354.5  790.59  5368.9  792.31
  5389.7  798.66  5410.5  802.72  5453.6   807.3  5482.3   805.2  5595.8   813.7
  5610.1  816.05  5659.7  817.19    5674  818.89  5801.9  820.58  5957.6  825.54
#Mann= 3 ,-1 , 0
  3957.6      .1       0  5018.9     .07       0  5037.2      .1       0
Bank Sta=5018.9,5037.2
XS Rating Curve= 0 ,0
Exp/Cntr=0.3,0.1

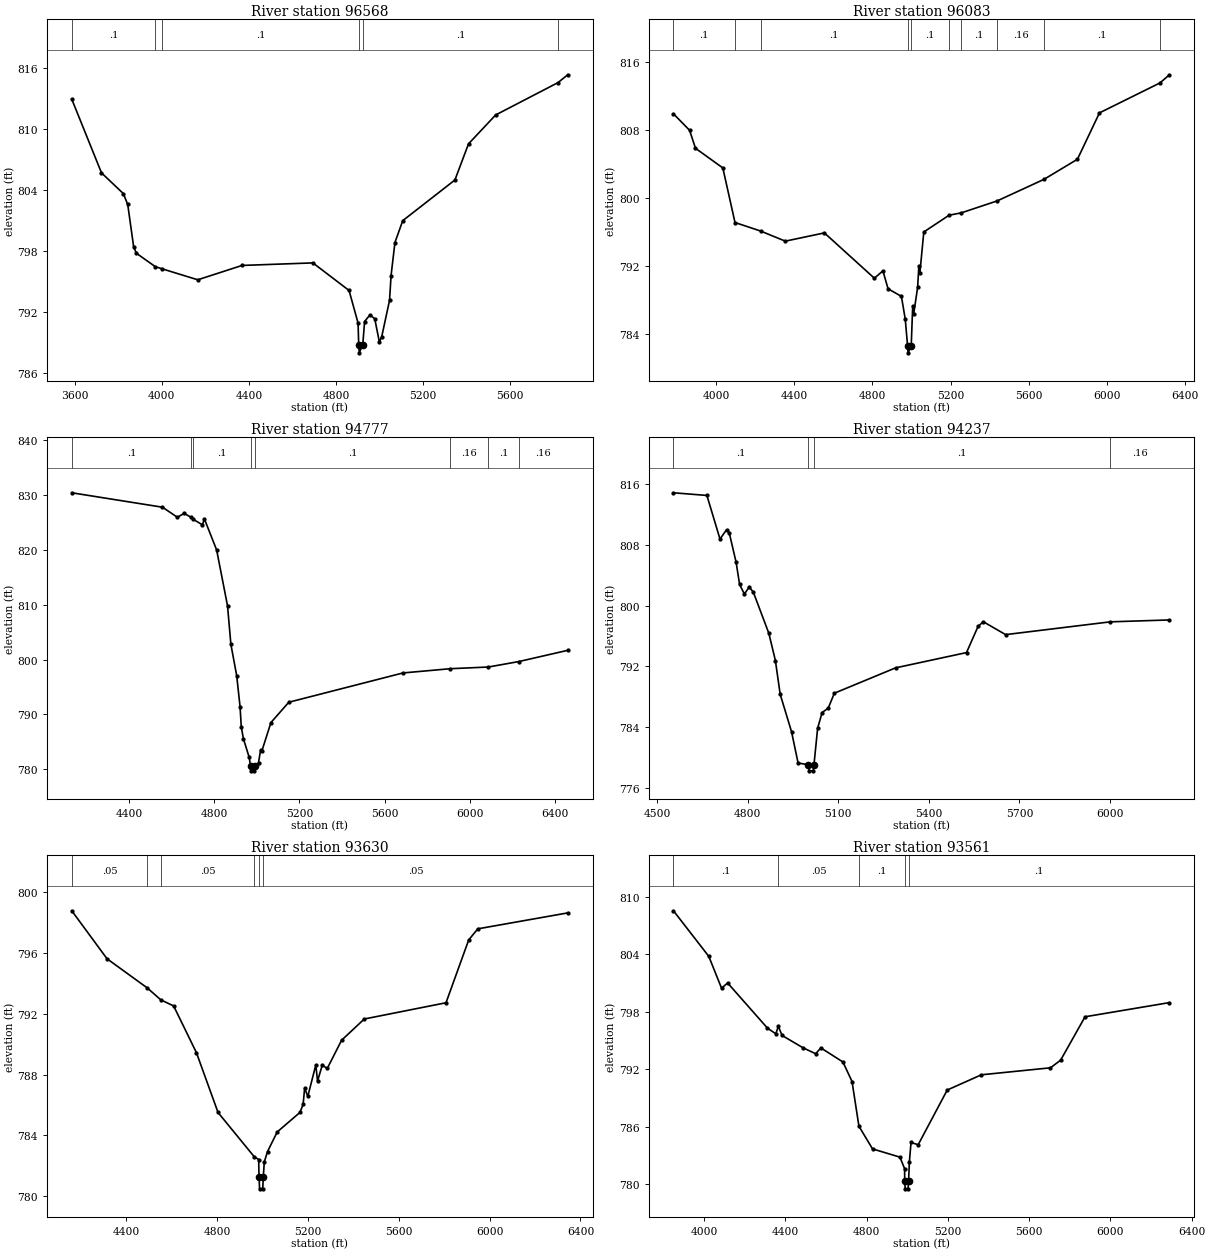
Type RM Length L Ch R = 1 ,96568   ,485,485,485
BEGIN DESCRIPTION:
Mapping XS 974de309
END DESCRIPTION:
XS GIS Cut Line= 5
      1986646.94     13649530.79      1986589.65       13648924.
      1986213.35      13648547.7       1986057.1     13648141.45
      1985395.59     13647912.27
#Sta/Elev= 30
  3587.1  812.89  3723.5  805.65  3823.9  803.61    3844  802.54  3871.4  798.35
  3884.2  797.74  3970.7  796.43  4001.4  796.22  4165.5  795.14  4368.9  796.55
  4694.1   796.8  4860.2  794.09  4901.5  790.89  4904.5  788.76    4907  787.96
  4923.1  788.76  4931.5  791.04  4956.1  791.69  4978.1  791.31  4999.5  789.01
  5010.2  789.55  5046.1  793.13  5053.1  795.56  5070.8   798.8  5106.6  800.95
  5346.2  804.95  5408.6   808.5  5533.2  811.34  5819.6  814.52  5864.1  815.29
#Mann= 6 ,-1 , 0
  3587.1      .1       0  3970.7     .16       0  4001.4      .1       0
  4904.5     .07       0  4923.1      .1       0  5819.6     .16       0
Bank Sta=4904.5,4923.1
XS Rating Curve= 0 ,0
Exp/Cntr=0.3,0.1

Type RM Length L Ch R = 1 ,96083   ,1306,1306,1306
BEGIN DESCRIPTION:
Mapping XS 94c1426a
END DESCRIPTION:
XS GIS Cut Line= 4
       1986660.3     13649527.67      1986669.34     13648614.37
      1986489.65     13648077.91      1985455.78     13647843.53
#Sta/Elev= 30
    3781  809.91  3863.7  807.97  3893.7  805.86  4033.7  803.55  4096.1  797.13
    4227  796.13  4353.7  794.94  4553.7  795.91  4809.7  790.58  4853.4  791.45
  4879.7  789.34  4948.1  788.45  4967.9  785.74  4979.7  782.61  4982.2  781.81
  4998.3  782.61  5005.9   787.3  5011.2  786.42  5031.2  789.53  5037.5  792.05
  5042.8  791.25  5062.8  796.02  5192.3  797.99  5255.1  798.27  5438.2  799.67
  5678.4  802.21  5849.3  804.57  5962.1  810.02  6271.8  813.54  6320.2   814.5
#Mann= 10 ,-1 , 0
    3781      .1       0  4096.1     .16       0    4227      .1       0
  4979.7     .07       0  4998.3      .1       0  5192.3     .16       0
  5255.1      .1       0  5438.2     .16       0  5678.4      .1       0
  6271.8     .16       0
Bank Sta=4979.7,4998.3
XS Rating Curve= 0 ,0
Exp/Cntr=0.3,0.1

Type RM Length L Ch R = 1 ,94777   ,540,540,540
BEGIN DESCRIPTION:
SF PEREZ CREEK 123.0
END DESCRIPTION:
XS GIS Cut Line= 3
       1988253.2     13648696.56      1987438.78     13648223.76
      1986109.35     13647830.46
#Sta/Elev= 30
  4131.4   830.4  4557.1  827.77  4627.4  825.93  4658.9  826.66  4692.1   825.9
  4702.6  825.54    4745  824.55  4753.7  825.66  4811.5  819.97  4862.5  809.81
  4878.3  802.78  4905.6  797.07  4921.3  791.45  4927.2   787.7  4937.1  785.58
  4964.4  782.17  4970.8  780.53  4973.3  779.73    4987  779.73  4989.5  780.53
  5008.1  781.23  5017.4  783.44  5023.1  783.27  5066.2  788.52  5150.1  792.23
  5686.4  797.57  5907.9  798.34  6087.1  798.65  6229.4  799.64  6459.5  801.69
#Mann= 8 ,-1 , 0
  4131.4      .1       0  4692.1     .16       0  4702.6      .1       0
  4970.8     .07       0  4989.5      .1       0  5907.9     .16       0
  6087.1      .1       0  6229.4     .16       0
Bank Sta=4970.8,4989.5
XS Rating Curve= 0 ,0
Exp/Cntr=0.3,0.1

Type RM Length L Ch R = 1 ,94237   ,607,607,607
BEGIN DESCRIPTION:
SF PEREZ CREEK 122.0
END DESCRIPTION:
XS GIS Cut Line= 3
      1988016.03     13647954.66      1987599.37     13647720.28
      1986449.57     13647529.37
#Sta/Elev= 30
  4553.5  814.82  4664.3  814.47  4707.7  808.74  4729.4  809.96  4738.3  809.57
  4761.2  805.67  4772.7  802.77  4788.6  801.51  4804.6  802.45  4818.6  801.72
  4869.6  796.35  4891.3  792.77  4907.2  788.34  4944.8  783.42  4966.5  779.31
  5000.5  779.08    5003  778.28  5016.7  778.28  5019.2  779.08  5031.2  783.86
  5046.1  785.94  5066.4  786.52  5086.7  788.48  5289.4  791.81  5524.7  793.82
  5563.1  797.27  5580.5  797.87  5654.3  796.18    6001  797.86  6197.1  798.11
#Mann= 4 ,-1 , 0
  4553.5      .1       0  5000.5     .07       0  5019.2      .1       0
    6001     .16       0
Bank Sta=5000.5,5019.2
XS Rating Curve= 0 ,0
Exp/Cntr=0.3,0.1

Type RM Length L Ch R = 1 ,93630   ,69,69,69
BEGIN DESCRIPTION:
Mapping XS 7271305a
END DESCRIPTION:
XS GIS Cut Line= 5
      1988540.21     13647016.06      1988213.82     13647016.06
      1987734.66     13647134.11      1987526.32      13647373.7
      1986478.82     13647366.76
#Sta/Elev= 30
    4159  798.79  4314.2  795.63  4491.3  793.71  4551.3  792.92  4607.8  792.52
  4708.2  789.44  4803.4   785.5    4962   782.6  4982.4   782.4  4983.9  781.27
  4986.4  780.47  5000.3  780.47  5002.8  781.27  5007.2  782.24  5021.4  782.93
  5064.2  784.22  5163.9   785.5  5178.2  786.03  5184.8  787.09    5199  786.57
  5234.1  788.63  5241.8  787.57  5262.6  788.62  5284.5   788.4  5347.7  790.26
  5447.7  791.66  5807.7  792.73  5907.7  796.87  5947.7   797.6  6343.9  798.65
#Mann= 6 ,-1 , 0
    4159     .05       0  4491.3      .1       0  4551.3     .05       0
    4962      .1       0  4983.9     .04       0  5002.8     .05       0
Bank Sta=4983.9,5002.8
XS Rating Curve= 0 ,0
Exp/Cntr=0.3,0.1

Type RM Length L Ch R = 1 ,93561   ,525,525,525
BEGIN DESCRIPTION:
SF PEREZ CREEK 121.0
END DESCRIPTION:
XS GIS Cut Line= 5
      1988793.72     13646804.24      1988161.74      13646960.5
      1987692.99     13647088.98      1987470.77     13647262.59
      1986449.97       13647273.
#Sta/Elev= 30
  3850.3  808.56  4024.1   803.8  4086.8  800.48  4116.8  801.02  4312.5  796.31
  4353.7  795.71  4366.3  796.49  4384.6  795.54  4487.7  794.25  4549.8  793.63
  4575.4  794.24    4684  792.77  4728.8  790.73  4762.7  786.06  4829.7  783.69
  4964.5  782.83  4987.4  781.63    4988  780.32  4990.5  779.52  5004.4  779.52
  5006.9  780.32  5010.9  782.32    5019  784.36  5054.3  784.13  5197.2  789.84
  5365.1  791.43  5705.1  792.16  5755.1  792.96  5875.2  797.49  6290.2  798.97
#Mann= 5 ,-1 , 0
  3850.3      .1       0  4366.3     .05       0  4762.7      .1       0
    4988     .07       0  5006.9      .1       0
Bank Sta=4988,5006.9
XS Rating Curve= 0 ,0
Exp/Cntr=0.3,0.1

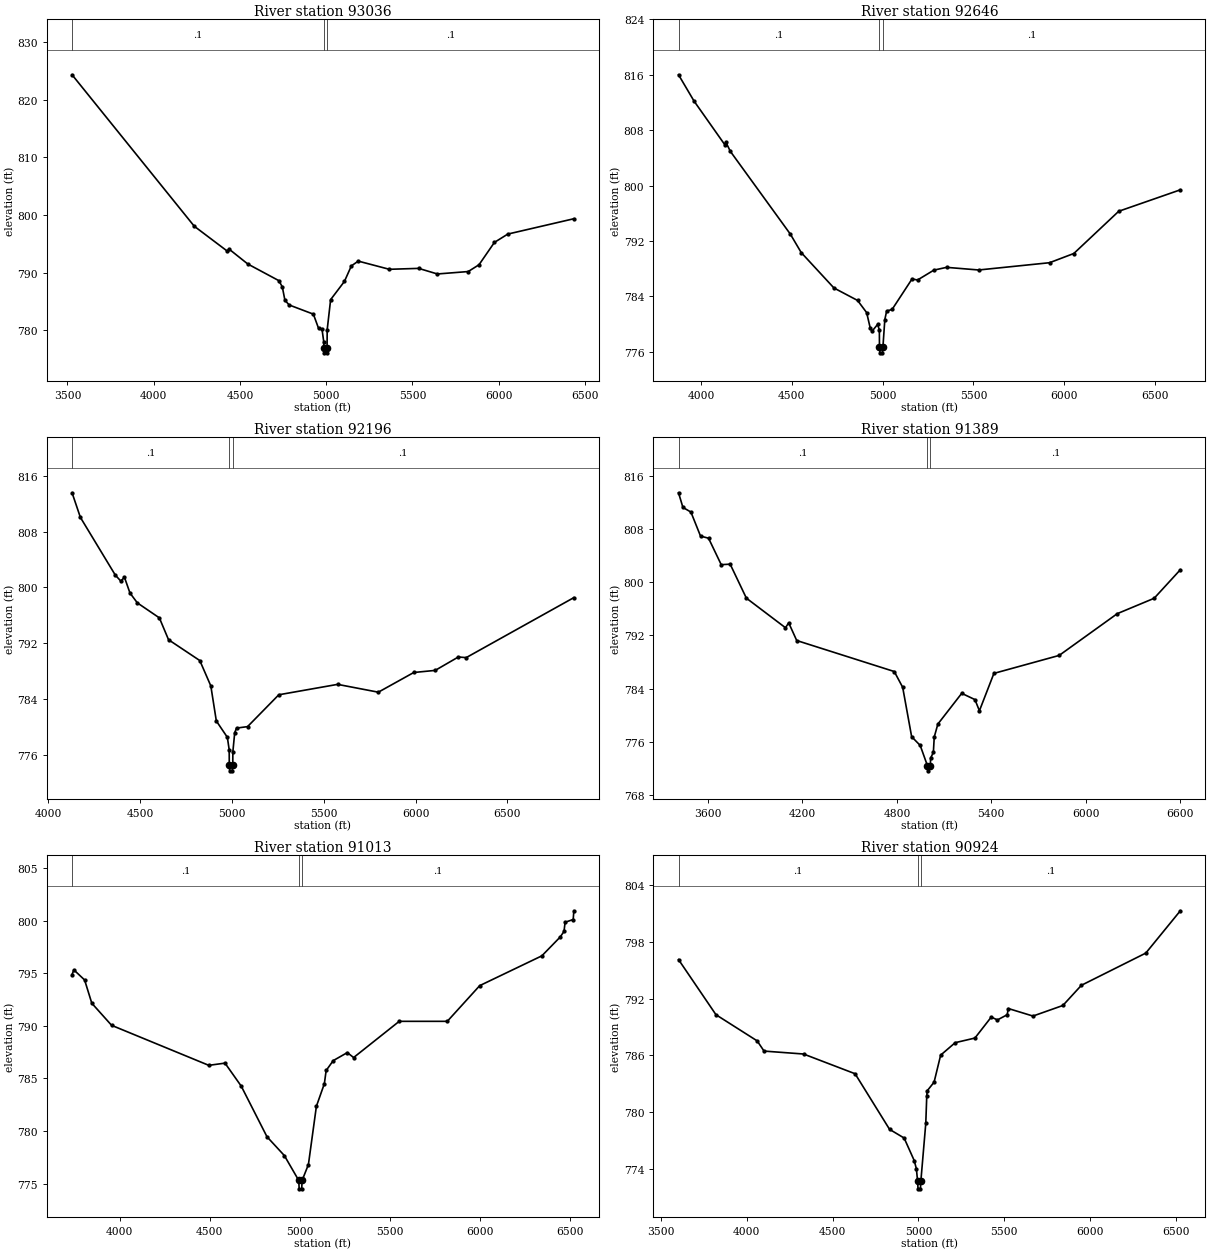
Type RM Length L Ch R = 1 ,93036   ,390,390,390
BEGIN DESCRIPTION:
SF PEREZ CREEK 120.0
END DESCRIPTION:
XS GIS Cut Line= 4
      1989212.91     13646549.05       1988301.5     13646580.29
      1987093.16     13646616.75        1986338.      13646840.7
#Sta/Elev= 30
  3527.1  824.31  4235.4  798.04  4425.5  793.75    4439  794.03  4545.6  791.49
  4725.7   788.6  4745.7  787.52  4760.8   785.2  4785.7  784.38  4925.8  782.79
  4955.8  780.33  4975.8  780.19  4985.8  778.02  4986.3  776.88  4988.8  776.08
  5002.7  776.08  5005.2  776.88  5005.8  780.08  5025.8  785.31  5105.8  788.47
  5145.9  791.16  5185.9  791.99    5366  790.57    5536  790.73  5644.5  789.76
  5823.3  790.18  5885.9  791.36  5975.2  795.24  6052.8  796.68  6435.6  799.34
#Mann= 3 ,-1 , 0
  3527.1      .1       0  4986.3     .07       0  5005.2      .1       0
Bank Sta=4986.3,5005.2
XS Rating Curve= 0 ,0
Exp/Cntr=0.3,0.1

Type RM Length L Ch R = 1 ,92646   ,450,450,450
BEGIN DESCRIPTION:
Mapping XS 1cd177a2
END DESCRIPTION:
XS GIS Cut Line= 3
      1988960.38     13646268.23      1987319.73     13646216.15
      1986251.98     13646559.91
#Sta/Elev= 30
  3876.2     816  3961.6   812.2  4131.1  805.89  4136.1   806.3  4161.7  804.93
  4491.9  792.98  4551.9  790.31    4732   785.2  4862.1   783.4  4912.1  781.64
  4932.1  779.38  4942.1  778.96  4972.1  779.93  4982.1  779.15  4982.7  776.63
  4985.2  775.83  4999.1  775.83  5001.6  776.63  5012.2  780.64  5022.2  781.87
  5052.2   782.1  5162.2  786.51  5192.2  786.35  5282.3  787.78  5352.3  788.18
  5529.1   787.8  5919.2  788.85  6052.8  790.18  6300.1  796.28  6639.4  799.38
#Mann= 3 ,-1 , 0
  3876.2      .1       0  4982.7     .07       0  5001.6      .1       0
Bank Sta=4982.7,5001.6
XS Rating Curve= 0 ,0
Exp/Cntr=0.3,0.1

Type RM Length L Ch R = 1 ,92196   ,807,807,807
BEGIN DESCRIPTION:
Mapping XS 4e27ab71
END DESCRIPTION:
XS GIS Cut Line= 3
      1988830.15     13645799.48      1987127.02     13645830.73
      1986246.83     13646361.97
#Sta/Elev= 30
  4130.5  813.55  4175.7  810.03  4365.7  801.77  4395.7  800.91  4415.7  801.45
  4445.7   799.2  4485.7  797.79  4605.7  795.64  4655.7  792.51  4825.8  789.53
  4885.8   785.9  4915.8  780.88  4975.8  778.54  4985.8  776.76  4986.3  774.54
  4988.8  773.74  5002.7  773.74  5005.2  774.54  5005.8  776.47  5015.8   779.2
  5025.8  779.86  5085.8  780.07  5255.8  784.63  5575.9  786.12  5797.6     785
  5990.6  787.82  6107.1  788.12  6233.2  790.04    6276  789.95    6862  798.54
#Mann= 3 ,-1 , 0
  4130.5      .1       0  4986.3     .07       0  5005.2      .1       0
Bank Sta=4986.3,5005.2
XS Rating Curve= 0 ,0
Exp/Cntr=0.3,0.1

Type RM Length L Ch R = 1 ,91389   ,376,376,376
BEGIN DESCRIPTION:
SF PEREZ CREEK 117.0
END DESCRIPTION:
XS GIS Cut Line= 4
      1988882.25     13645382.82      1987788.48     13645169.27
      1986809.31     13645617.19      1986043.66     13646257.83
#Sta/Elev= 30
  3412.1  813.44  3439.9  811.24  3490.8  810.54  3551.9  806.93  3602.9  806.61
  3683.5  802.63  3740.2  802.71  3843.3   797.6  4091.9  793.15  4112.3  793.89
  4163.3  791.23  4783.3  786.57  4836.8   784.2  4893.8  776.77  4948.2  775.46
  4993.8  772.44  4996.3  771.64  5012.7  772.44  5014.4  773.56  5031.9  774.41
  5037.4  776.72  5060.4  778.67  5212.1  783.29  5296.1  782.35  5324.6  780.67
  5416.7  786.29  5831.5  788.99    6201  795.27  6435.2  797.58  6601.6  801.87
#Mann= 3 ,-1 , 0
  3412.1      .1       0  4993.8     .07       0  5012.7      .1       0
Bank Sta=4993.8,5012.7
XS Rating Curve= 0 ,0
Exp/Cntr=0.3,0.1

Type RM Length L Ch R = 1 ,91013   ,89,89,89
BEGIN DESCRIPTION:
Mapping XS dbc7129f
END DESCRIPTION:
XS GIS Cut Line= 6
      1988284.55     13645098.52      1987301.93     13645091.58
      1987110.96     13645140.19      1986895.68      13645251.3
      1986756.79     13645195.75      1986079.85     13646205.95
#Sta/Elev= 30
  3735.3  794.87  3744.9  795.32  3804.9  794.36  3844.9  792.15  3954.9  790.05
  4494.9  786.25  4584.9  786.46  4674.9  784.28    4818  779.47  4914.6  777.68
  4994.5  775.32    4997  774.52  5010.9  774.52  5013.4  775.32  5048.3  776.83
  5092.6  782.36  5136.9  784.51  5146.8  785.76  5186.3   786.7  5264.4  787.46
  5299.4  786.99  5552.7  790.43  5819.8  790.43  5999.9  793.82  6345.1  796.65
  6447.1  798.44  6468.2  798.97  6474.2  799.84  6519.2   800.1  6522.9  800.93
#Mann= 3 ,-1 , 0
  3735.3      .1       0  4994.5     .07       0  5013.4      .1       0
Bank Sta=4994.5,5013.4
XS Rating Curve= 0 ,0
Exp/Cntr=0.3,0.1

Type RM Length L Ch R = 1 ,90924   ,715,715,715
BEGIN DESCRIPTION:
SF PEREZ CREEK 116.0
END DESCRIPTION:
XS GIS Cut Line= 6
      1988333.13      13645001.3      1987381.79     13644987.41
      1987074.94     13645078.12      1986916.08     13645162.76
      1986775.46     13645110.68      1986039.57     13646209.31
#Sta/Elev= 30
  3602.5  796.13  3820.7  790.29  4060.7  787.52  4100.7  786.44  4330.7  786.13
  4631.2  784.04  4832.1  778.15    4917  777.23  4975.8  774.84  4988.5  773.96
  4995.4  772.65  4997.9  771.85  5011.8  771.85  5014.3  772.65  5043.1  778.79
  5048.8   781.7  5051.7  782.24  5091.5  783.15  5129.7  786.01  5214.4  787.33
  5329.4  787.82  5424.5  790.04  5460.5  789.74  5517.6  790.29  5523.6  790.95
  5667.7  790.15  5841.8  791.27  5949.9  793.41  6325.1  796.82  6526.2   801.3
#Mann= 3 ,-1 , 0
  3602.5      .1       0  4995.4     .07       0  5014.3      .1       0
Bank Sta=4995.4,5014.3
XS Rating Curve= 0 ,0
Exp/Cntr=0.3,0.1

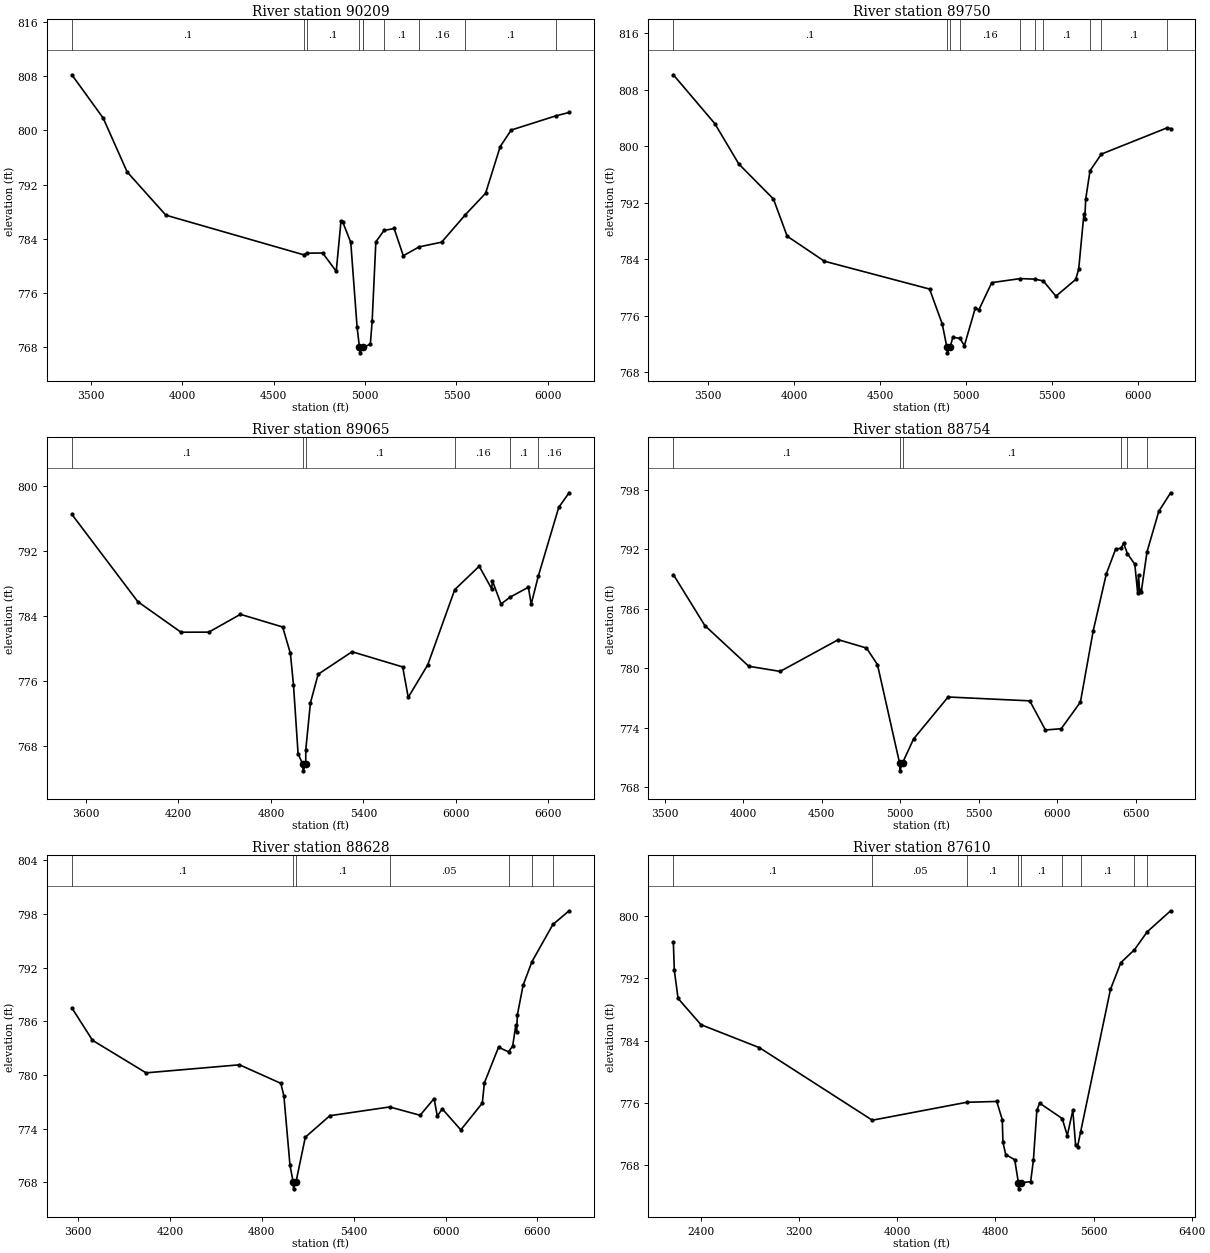
Type RM Length L Ch R = 1 ,90209   ,459,459,459
BEGIN DESCRIPTION:
SF PEREZ CREEK 115.0
END DESCRIPTION:
XS GIS Cut Line= 3
      1988524.98       13644725.        1986975.       13644525.
      1985818.14     13644498.13
#Sta/Elev= 30
  3396.4  808.23  3567.8  801.83  3698.9  793.87  3910.6  787.48  4663.6  781.63
  4680.5  781.86  4768.3  781.89  4842.6  779.18  4868.5  786.59  4878.6  786.44
    4922  783.46  4956.7   770.9  4969.7  767.93  4972.2  767.13  4988.8  767.93
  4991.6  767.96  5029.2  768.41  5039.2  771.91  5059.3  783.54  5104.2  785.22
  5159.3  785.51  5209.3  781.48  5295.8  782.79  5419.3  783.49  5549.3  787.56
  5659.4  790.71  5739.4  797.61  5799.5  800.06    6044  802.16  6116.4  802.66
#Mann= 10 ,-1 , 0
  3396.4      .1       0  4663.6     .16       0  4680.5      .1       0
  4969.7     .07       0  4988.8      .1       0  4991.6     .16       0
  5104.2      .1       0  5295.8     .16       0  5549.3      .1       0
    6044     .16       0
Bank Sta=4969.7,4988.8
XS Rating Curve= 0 ,0
Exp/Cntr=0.3,0.1

Type RM Length L Ch R = 1 ,89750   ,685,685,685
BEGIN DESCRIPTION:
SF PEREZ CREEK 114.0
END DESCRIPTION:
XS GIS Cut Line= 3
      1988575.03     13644675.01      1986949.07     13644059.72
      1985820.62     13644272.39
#Sta/Elev= 30
  3300.3  810.13  3540.7  803.23  3680.8  797.49  3881.3  792.55  3961.1  787.28
  4177.1  783.74  4787.8   779.8  4861.4  774.85  4888.2  771.57  4890.7  770.77
  4907.3  771.57  4922.6  772.98    4964  772.81  4989.7  771.78  5053.1   777.1
  5073.5  776.84    5149  780.71  5314.3  781.28  5400.1   781.2  5447.7  780.95
  5521.2  778.79  5636.2  781.16  5653.5  782.63  5683.6   790.4  5688.7  789.69
  5694.2  792.55  5719.2  796.54    5785   798.9  6166.5  802.62  6187.1  802.51
#Mann= 10 ,-1 , 0
  3300.3      .1       0  4888.2     .07       0  4907.3      .1       0
    4964     .16       0  5314.3      .1       0  5400.1     .16       0
  5447.7      .1       0  5719.2     .16       0    5785      .1       0
  6166.5     .16       0
Bank Sta=4888.2,4907.3
XS Rating Curve= 0 ,0
Exp/Cntr=0.3,0.1

Type RM Length L Ch R = 1 ,89065   ,311,311,311
BEGIN DESCRIPTION:
SF PEREZ CREEK 113.0
END DESCRIPTION:
XS GIS Cut Line= 4
      1988563.63     13643708.16      1987287.61     13643434.72
      1986458.62     13643434.72      1985434.28     13643812.34
#Sta/Elev= 30
  3508.2  796.48  3936.3  785.74  4216.4  781.99  4396.6     782  4601.7  784.19
  4875.8  782.63  4925.8  779.39  4945.8  775.54  4975.8  767.06  5006.2  765.75
  5008.7  764.95  5025.3  765.75  5025.8  767.57  5055.8   773.3  5105.8  776.82
  5325.8  779.59  5654.4  777.72  5690.2  773.98  5816.6  777.97  5992.2  787.23
  6150.6   790.1  6231.3  787.33  6236.6   788.3  6292.2  785.46  6351.2   786.3
  6469.5  787.52    6488  785.44  6533.9  788.88  6666.6  797.34  6733.9  799.13
#Mann= 6 ,-1 , 0
  3508.2      .1       0  5006.2     .07       0  5025.3      .1       0
  5992.2     .16       0  6351.2      .1       0  6533.9     .16       0
Bank Sta=5006.2,5025.3
XS Rating Curve= 0 ,0
Exp/Cntr=0.3,0.1

Type RM Length L Ch R = 1 ,88754   ,126,126,126
BEGIN DESCRIPTION:
Mapping XS 317944aa
END DESCRIPTION:
XS GIS Cut Line= 4
      1988545.39     13643165.62      1987113.13     13643123.96
       1986097.5       13643150.      1985391.11     13643290.24
#Sta/Elev= 30
  3554.8  789.47  3755.3  784.33  4035.4  780.22  4235.5   779.7  4605.6   782.9
  4785.7  782.06  4855.7  780.38  4996.3  770.47  4998.8  769.67  5015.4  770.47
  5085.8  772.89  5305.9  777.12  5826.1  776.73  5926.1  773.79  6026.6  773.92
  6148.9   776.6  6230.5   783.8  6314.4  789.56  6373.2  792.03  6408.7  792.13
  6424.2  792.64  6448.5  791.57  6495.5  790.52    6514  787.59  6519.1  789.43
  6526.1  787.87  6536.3  787.69  6573.3  791.76  6648.5  795.85  6723.8  797.72
#Mann= 6 ,-1 , 0
  3554.8      .1       0  4996.3     .07       0  5015.4      .1       0
  6408.7     .16       0  6448.5      .1       0  6573.3     .16       0
Bank Sta=4996.3,5015.4
XS Rating Curve= 0 ,0
Exp/Cntr=0.3,0.1

Type RM Length L Ch R = 1 ,88628   ,1018,1018,1018
BEGIN DESCRIPTION:
Mapping XS 60a67a15
END DESCRIPTION:
XS GIS Cut Line= 3
      1988529.76     13643009.37      1986206.88     13642998.96
      1985305.85     13643207.29
#Sta/Elev= 30
  3559.4  787.51  3694.2  783.89  4044.2  780.25  4654.2  781.15  4924.2  779.08
  4944.2  777.68  4984.2   769.9  5004.6  768.09  5007.1  767.29  5023.7  768.09
  5084.2  773.06  5244.2  775.46  5634.9  776.44  5834.2  775.51  5925.3  777.38
  5945.8  775.42  5978.7  776.22  6099.8  773.88  6240.2  776.87  6253.7  779.13
  6346.1  783.11  6411.4   782.6  6438.5  783.25  6458.9  785.58  6464.1  784.77
  6469.3  786.74  6506.8  790.06  6564.6  792.68  6701.2  796.83  6807.1  798.36
#Mann= 7 ,-1 , 0
  3559.4      .1       0  5004.6     .07       0  5023.7      .1       0
  5634.9     .05       0  6411.4      .1       0  6564.6     .16       0
  6701.2     .05       0
Bank Sta=5004.6,5023.7
XS Rating Curve= 0 ,0
Exp/Cntr=0.3,0.1

Type RM Length L Ch R = 1 ,87610   ,706,706,706
BEGIN DESCRIPTION:
Mapping XS 807a81a2
END DESCRIPTION:
XS GIS Cut Line= 4
      1988982.89     13642743.74      1986962.09      13642337.5
        1985785.     13642910.42      1985149.75     13643155.15
#Sta/Elev= 30
    2177   796.7    2185  793.03  2215.6  789.43  2401.6  786.07  2878.7  783.11
  3797.8   773.8  4565.6   776.1  4811.5  776.21  4856.6  773.87  4862.1  770.96
  4884.7  769.39  4957.9  768.73  4987.9  765.79  4990.4  764.99    5007  765.79
  5087.6   765.9  5110.1  768.64  5138.2  775.05  5160.8  775.99    5345  774.02
  5386.3  771.83  5431.3  775.08  5453.9  770.62  5469.5  770.39  5494.1  772.24
  5737.9  790.59  5822.5  794.03  5933.6  795.69  6036.7  797.98  6228.1  800.69
#Mann= 9 ,-1 , 0
    2177      .1       0  3797.8     .05       0  4565.6      .1       0
  4987.9     .07       0    5007      .1       0    5345     .05       0
  5494.1      .1       0  5933.6     .05       0  6036.7      .1       0
Bank Sta=4987.9,5007
XS Rating Curve= 0 ,0
Exp/Cntr=0.3,0.1

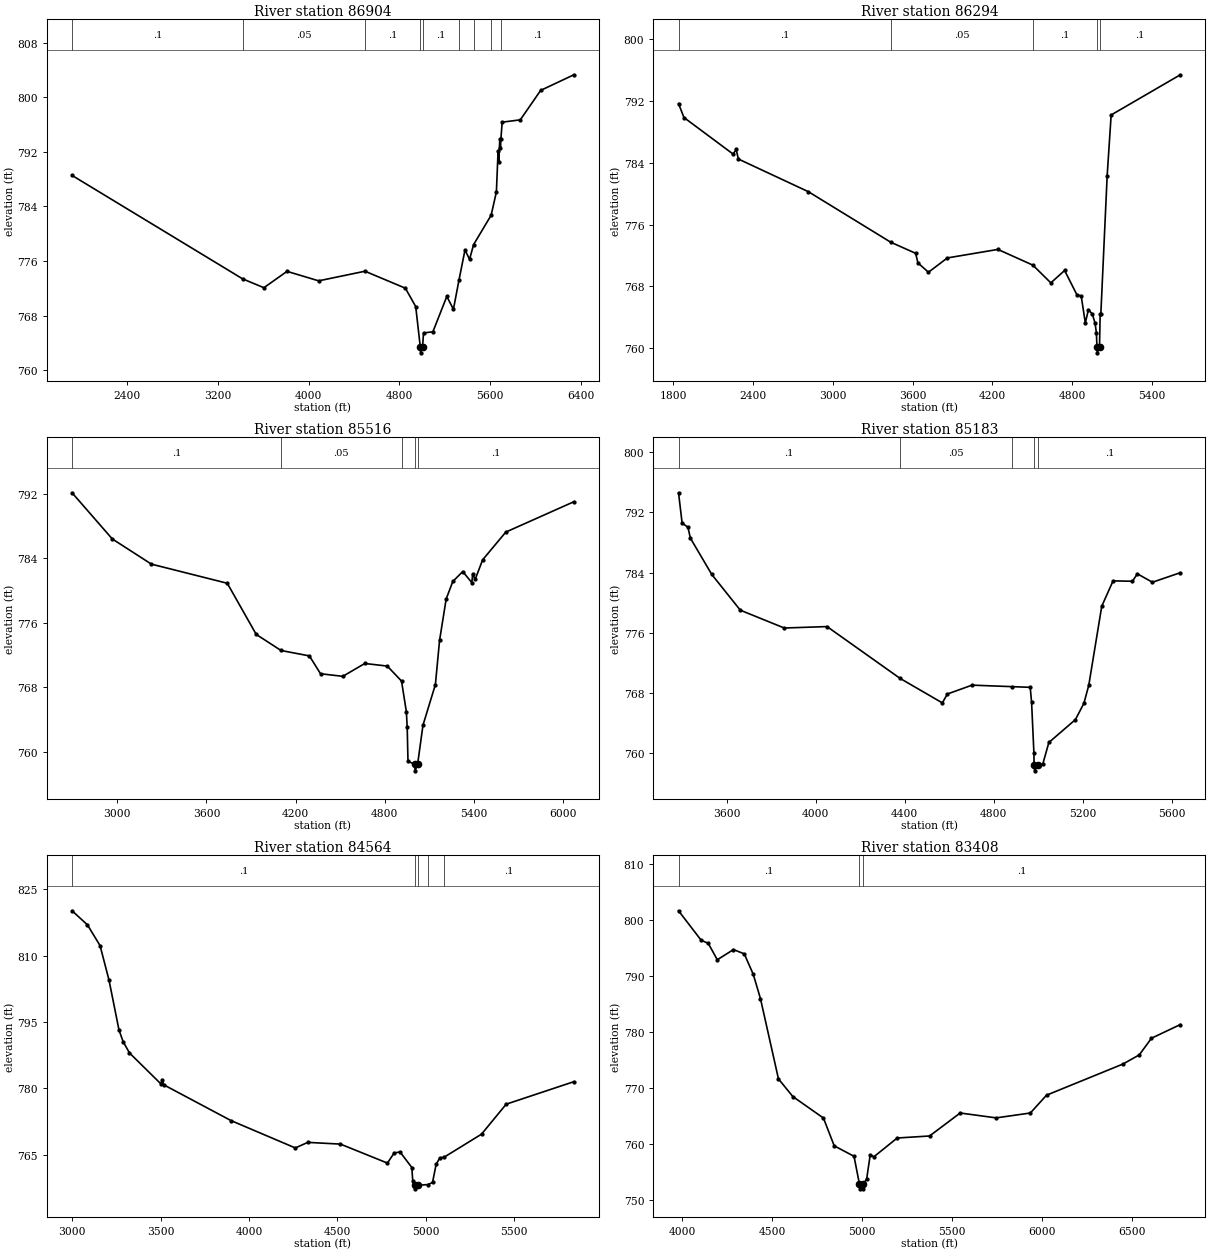
Type RM Length L Ch R = 1 ,86904   ,610,610,610
BEGIN DESCRIPTION:
Mapping XS feb465c6
END DESCRIPTION:
XS GIS Cut Line= 4
      1988894.42     13642561.47      1986732.92     13642123.96
       1985404.8     13642327.08      1984670.45     13641842.73
#Sta/Elev= 30
  1912.4  788.55  3417.6  773.38  3605.5  772.08  3809.5  774.48  4088.7  773.09
  4497.6   774.5  4854.1  772.01  4945.2  769.32  4986.1  763.33  4988.6  762.53
  5005.4  763.33  5014.3  765.44  5096.9  765.62  5219.7   770.8  5278.1  768.92
  5326.7  773.16  5380.2  777.62  5420.6  776.24    5456   778.4    5611  782.71
  5657.3  786.13  5672.3  792.15  5678.3  790.45  5687.4  793.87  5693.4  792.53
  5696.9   793.9  5708.5  796.36  5868.1   796.7    6048  801.02    6341  803.31
#Mann= 9 ,-1 , 0
  1912.4      .1       0  3417.6     .05       0  4497.6      .1       0
  4986.1     .07       0  5005.4      .1       0  5326.7     .05       0
    5456      .1       0    5611     .05       0  5696.9      .1       0
Bank Sta=4986.1,5005.4
XS Rating Curve= 0 ,0
Exp/Cntr=0.3,0.1

Type RM Length L Ch R = 1 ,86294   ,778,778,778
BEGIN DESCRIPTION:
SF PEREZ CREEK 112.0
END DESCRIPTION:
XS GIS Cut Line= 3
      1988982.92     13642519.79        1985925.       13641675.
      1985324.97       13641675.
#Sta/Elev= 30
    1840  791.63  1880.6  789.83    2250  785.11  2273.6   785.7  2289.5  784.47
  2816.9  780.24  3435.2  773.72  3622.3  772.29  3639.8  771.05  3718.9  769.84
  3860.9  771.69  4241.1  772.79  4503.7  770.76    4639  768.47  4742.7  770.07
  4836.1  766.89  4867.2  766.79  4898.3  763.29  4921.4     765  4950.2  764.46
    4971  763.31  4981.3  762.05  4985.6  760.23  4988.1  759.43  5004.9  760.23
  5009.9  764.49    5015  764.49  5062.5  782.33  5092.5  790.16  5612.5  795.35
#Mann= 5 ,-1 , 0
    1840      .1       0  3435.2     .05       0  4503.7      .1       0
  4985.6     .07       0  5004.9      .1       0
Bank Sta=4985.6,5004.9
XS Rating Curve= 0 ,0
Exp/Cntr=0.3,0.1

Type RM Length L Ch R = 1 ,85516   ,333,333,333
BEGIN DESCRIPTION:
SF PEREZ CREEK 111.0
END DESCRIPTION:
XS GIS Cut Line= 3
        1988798.     13642349.64      1986623.55       13641525.
      1985686.02     13641051.03
#Sta/Elev= 30
  2695.9   792.1  2966.5  786.38  3229.6  783.26  3740.1  780.89  3935.1  774.55
  4101.8  772.56  4292.7  771.89  4367.5  769.68  4517.3  769.36  4665.3  770.95
  4816.7  770.63  4912.6  768.77  4945.1  764.97  4950.7  763.04    4956  758.85
  5001.3  758.45  5003.8  757.65  5020.6  758.45  5056.9  763.31  5140.4  768.34
  5168.3   773.8  5212.9  778.94  5257.5  781.11  5324.3  782.34  5385.6  780.97
  5391.2  782.07  5407.9  781.36  5458.1  783.79  5614.1  787.23    6072  790.99
#Mann= 5 ,-1 , 0
  2695.9      .1       0  4101.8     .05       0  4912.6      .1       0
  5001.3     .07       0  5020.6      .1       0
Bank Sta=5001.3,5020.6
XS Rating Curve= 0 ,0
Exp/Cntr=0.3,0.1

Type RM Length L Ch R = 1 ,85183   ,619,619,619
BEGIN DESCRIPTION:
SF PEREZ CREEK 110.0
END DESCRIPTION:
XS GIS Cut Line= 3
      1988475.04     13641875.01        1986925.       13641375.
      1986374.99       13641075.
#Sta/Elev= 30
  3383.8  794.61  3399.9  790.58  3425.9  790.03  3437.2  788.57  3533.3  783.74
  3661.5  778.99    3859  776.62  4051.3  776.81  4379.4  769.92  4569.3  766.66
  4592.2  767.84  4702.8  769.02  4882.3  768.82  4964.4  768.73  4970.5  766.74
    4981  759.98  4981.6  758.42  4984.1  757.62  5000.9  758.42  5020.6  758.49
  5048.1  761.39  5167.7  764.44  5205.7  766.61  5227.5     769  5285.9  779.52
  5336.7  782.89    5424  782.84  5445.8  783.83  5513.7  782.71    5639  783.98
#Mann= 5 ,-1 , 0
  3383.8      .1       0  4379.4     .05       0  4882.3      .1       0
  4981.6     .07       0  5000.9      .1       0
Bank Sta=4981.6,5000.9
XS Rating Curve= 0 ,0
Exp/Cntr=0.3,0.1

Type RM Length L Ch R = 1 ,84564   ,1156,1156,1156
BEGIN DESCRIPTION:
SF PEREZ CREEK 109.0
END DESCRIPTION:
XS GIS Cut Line= 3
       1989092.3     13641629.17      1988326.67     13641092.71
      1986462.12     13640702.09
#Sta/Elev= 30
  2998.5  820.18  3085.5     817    3157  812.29  3207.5   804.5  3264.2  793.19
  3287.7  790.55  3323.5  788.02  3502.2  780.98  3508.3  781.98    3517  780.82
    3898  772.72    4262  766.53  4332.6  767.79  4517.4   767.4  4783.1  763.11
  4821.6   765.4  4854.6  765.62  4921.5   762.1  4926.6  759.05  4936.9  758.08
  4939.4  757.28  4956.2  758.08  5013.7  758.25  5038.5  758.73    5059  762.82
  5079.4  764.27  5104.7  764.45  5315.8  769.65  5455.4  776.43  5838.4  781.52
#Mann= 5 ,-1 , 0
  2998.5      .1       0  4936.9     .07       0  4956.2      .1       0
  5013.7     .08       0  5104.7      .1       0
Bank Sta=4936.9,4956.2
XS Rating Curve= 0 ,0
Exp/Cntr=0.3,0.1

Type RM Length L Ch R = 1 ,83408   ,690,690,690
BEGIN DESCRIPTION:
Mapping XS 1fecfb74
END DESCRIPTION:
XS GIS Cut Line= 3
       1989170.4      13640337.5      1987087.09     13640290.62
      1986451.64     13640597.93
#Sta/Elev= 30
  3978.1  801.62  4103.5  796.38  4143.5   795.8  4193.6  792.88  4283.6   794.7
  4343.6  793.93  4393.6  790.28  4433.6  785.94  4533.6  771.63  4613.7  768.47
  4783.7  764.64  4843.7  759.68  4953.7  757.82  4984.1  752.81  4986.6  752.01
    5001  752.01  5003.5  752.81  5023.8  753.73  5043.8  758.09  5063.8  757.72
  5193.8  761.08  5373.9  761.44  5543.9  765.54  5743.9  764.67    5934  765.54
    6024  768.72  6449.2  774.28  6539.6  775.91  6607.4  778.88  6767.8  781.32
#Mann= 3 ,-1 , 0
  3978.1      .1       0  4984.1     .07       0  5003.5      .1       0
Bank Sta=4984.1,5003.5
XS Rating Curve= 0 ,0
Exp/Cntr=0.3,0.1