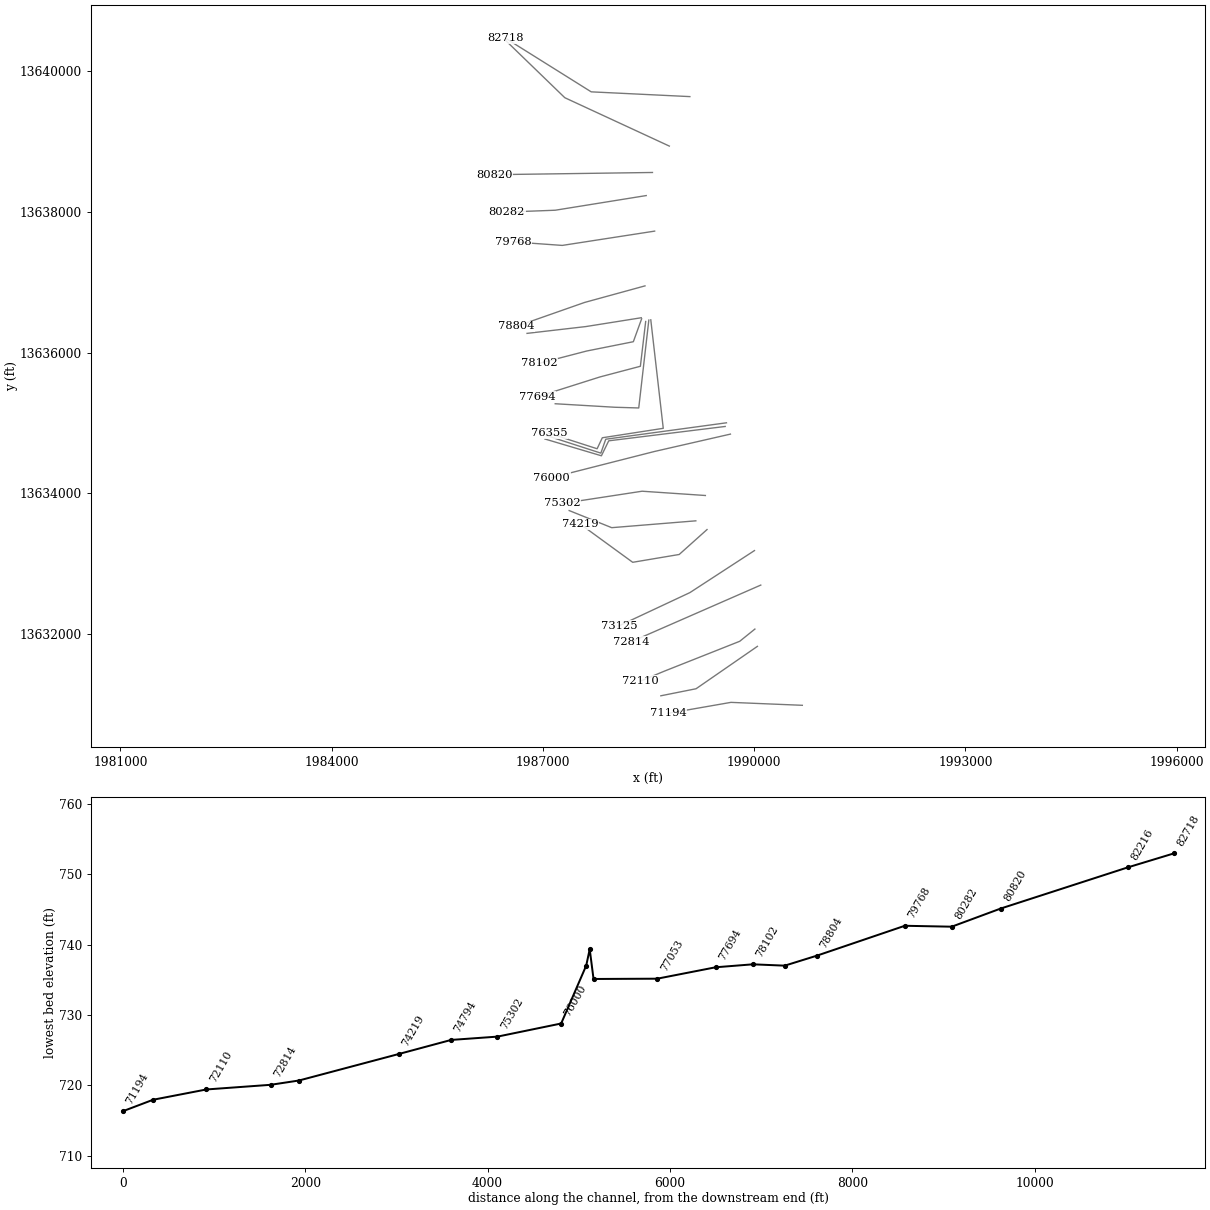
HEC-RAS study SF PEREZ CREEK.prj: SF PEREZ CREEK Base Level Engineering

--- SF PEREZ CREEK.g01 (geometry) --- (continued)

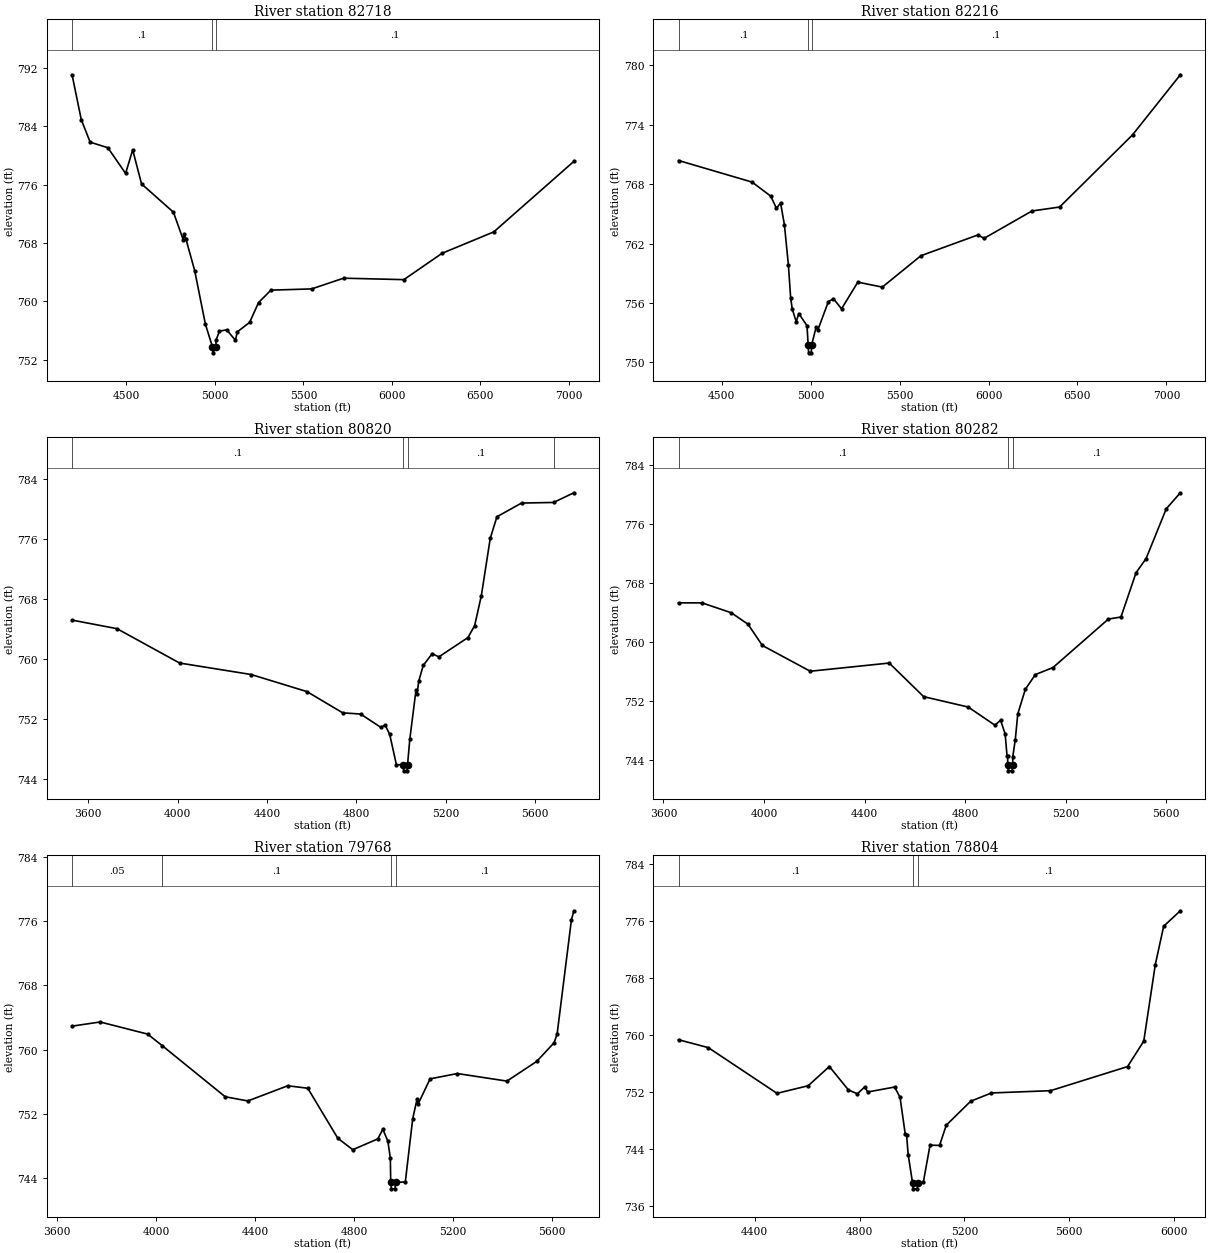
Type RM Length L Ch R = 1 ,82718   ,502,502,502
BEGIN DESCRIPTION:
Mapping XS aa2f589f
END DESCRIPTION:
XS GIS Cut Line= 3
      1989087.06     13639639.58      1987686.05     13639707.29
      1986472.55     13640467.68
#Sta/Elev= 30
  4192.8  791.07  4244.9   784.9    4295  781.83  4395.1  781.06  4495.2  777.54
  4535.3  780.77  4585.3   776.1  4765.5  772.22  4821.7  768.37  4826.8  769.24
  4835.6  768.58  4885.7  764.18  4945.7  756.89    4986  753.73  4988.5  752.93
  5005.5  753.73  5005.8  754.65  5025.4   755.9  5065.9  756.09  5115.9  754.65
  5125.9   755.8    5196  757.11  5246.1  759.82  5316.2  761.53  5546.4   761.7
  5726.5  763.17  6067.1  762.97  6282.8  766.58  6575.1  769.52  7027.5  779.19
#Mann= 3 ,-1 , 0
  4192.8      .1       0    4986     .07       0  5005.5      .1       0
Bank Sta=4986,5005.5
XS Rating Curve= 0 ,0
Exp/Cntr=0.3,0.1

Type RM Length L Ch R = 1 ,82216   ,1396,1396,1396
BEGIN DESCRIPTION:
Mapping XS 7ed5b415
END DESCRIPTION:
XS GIS Cut Line= 3
      1988795.45     13638936.44      1987311.05     13639623.96
      1986459.18     13640449.16
#Sta/Elev= 30
  4256.5  770.39  4669.9  768.21    4775  766.79  4807.4  765.55  4830.1  766.11
  4852.1  763.87  4874.1  759.88  4887.1   756.5  4896.2  755.37  4918.2  754.11
    4933  754.93  4978.8   753.7  4985.6  751.76  4988.1  750.96  5002.6  750.96
  5005.1  751.76  5030.2  753.55  5039.5  753.25  5098.9  756.12  5127.6  756.43
  5173.2  755.41  5264.8   758.1  5402.4   757.6  5619.6  760.77  5939.9  762.87
  5975.2  762.53    6244  765.29  6399.6  765.69  6809.6  772.98  7078.4  779.05
#Mann= 3 ,-1 , 0
  4256.5      .1       0  4985.6     .07       0  5005.1      .1       0
Bank Sta=4985.6,5005.1
XS Rating Curve= 0 ,0
Exp/Cntr=0.3,0.1

Type RM Length L Ch R = 1 ,80820   ,538,538,538
BEGIN DESCRIPTION:
Mapping XS 63b95077
END DESCRIPTION:
XS GIS Cut Line= 2
      1988555.82     13638561.46      1986311.04     13638530.21
#Sta/Elev= 30
  3527.8   765.2  3728.6  764.06  4008.7  759.48  4328.7  757.95  4578.7  755.67
  4738.7  752.84  4818.7  752.68  4908.8  750.91  4928.8  751.19  4948.8  749.98
  4978.8  745.93  5008.9  745.91  5011.4  745.11  5026.2  745.11  5028.7  745.91
  5038.8  749.31  5066.5  755.87  5071.5  755.41  5078.8  757.06  5098.8  759.15
  5138.8  760.73  5168.8   760.3  5298.8  762.87  5328.8  764.45  5358.8  768.44
  5398.8  776.11  5428.8  778.98  5538.8   780.8  5681.9  780.88  5772.8  782.17
#Mann= 4 ,-1 , 0
  3527.8      .1       0  5008.9     .07       0  5028.7      .1       0
  5681.9     .05       0
Bank Sta=5008.9,5028.7
XS Rating Curve= 0 ,0
Exp/Cntr=0.3,0.1

Type RM Length L Ch R = 1 ,80282   ,514,514,514
BEGIN DESCRIPTION:
SF PEREZ CREEK 107.0
END DESCRIPTION:
XS GIS Cut Line= 3
      1988467.26     13638233.33        1987175.       13638025.
      1986489.03     13637998.99
#Sta/Elev= 30
  3660.1  765.28  3753.5  765.28  3869.8  763.94  3936.6  762.38  3993.4  759.51
  4183.8  756.02  4497.9  757.13  4634.8  752.58    4812  751.17  4918.4  748.71
  4940.7  749.38  4958.9  747.53  4966.5  744.52    4969  744.52  4969.1  743.33
  4971.6  742.53  4986.4  742.53  4988.9  743.33  4989.1  744.43  4999.1  746.71
  5009.1  750.24  5039.1  753.57  5079.1  755.57  5149.2  756.52  5369.6  763.09
  5419.4  763.36  5479.4  769.36  5519.4  771.28  5599.5  778.02  5655.5  780.19
#Mann= 3 ,-1 , 0
  3660.1      .1       0  4969.1     .07       0  4988.9      .1       0
Bank Sta=4969.1,4988.9
XS Rating Curve= 0 ,0
Exp/Cntr=0.3,0.1

Type RM Length L Ch R = 1 ,79768   ,964,964,964
BEGIN DESCRIPTION:
SF PEREZ CREEK 106.0
END DESCRIPTION:
XS GIS Cut Line= 3
      1988587.08     13637728.12        1987275.       13637525.
      1986574.99       13637575.
#Sta/Elev= 30
  3660.1  762.91  3773.5  763.43  3965.8  761.92  4025.6  760.46  4279.5  754.12
  4371.2   753.6  4532.4  755.49  4613.4  755.18  4734.8  748.96  4795.5  747.53
  4896.7  748.88    4917  750.08  4937.2   748.6  4947.3  746.51  4948.9  743.46
  4951.4  742.66  4966.2  742.66  4968.7  743.46  5007.9  743.52  5037.9   751.4
  5055.5  753.84  5060.5  753.27  5108.1  756.35  5218.4  757.01  5418.9  756.07
  5539.2  758.52  5609.4  760.83  5621.9  761.93  5679.6  776.11  5689.6  777.27
#Mann= 4 ,-1 , 0
  3660.1     .05       0  4025.6      .1       0  4948.9     .07       0
  4968.7      .1       0
Bank Sta=4948.9,4968.7
XS Rating Curve= 0 ,0
Exp/Cntr=0.3,0.1

Type RM Length L Ch R = 1 ,78804   ,353,353,353
BEGIN DESCRIPTION:
SF PEREZ CREEK 105.0
END DESCRIPTION:
XS GIS Cut Line= 3
        1988450.       13636950.      1987592.19      13636714.6
        1986625.       13636375.
#Sta/Elev= 30
    4109  759.34  4222.7  758.23  4484.6  751.82  4603.5  752.88  4684.5  755.58
  4757.1   752.3  4791.3  751.75  4819.3  752.71  4830.9  752.01  4933.4   752.7
  4954.1  751.27  4973.9  746.13  4979.1  745.98  4985.2  743.22    5002  739.22
  5004.5  738.42  5019.4  738.42  5021.9  739.22  5042.9  739.32  5068.6  744.55
  5104.9  744.51  5130.6  747.35  5223.6  750.71  5302.9  751.87  5528.2  752.19
  5822.2  755.57  5884.1  759.14  5928.2  769.89    5960  775.26  6023.6  777.43
#Mann= 3 ,-1 , 0
    4109      .1       0    5002     .07       0  5021.9      .1       0
Bank Sta=5002,5021.9
XS Rating Curve= 0 ,0
Exp/Cntr=0.3,0.1

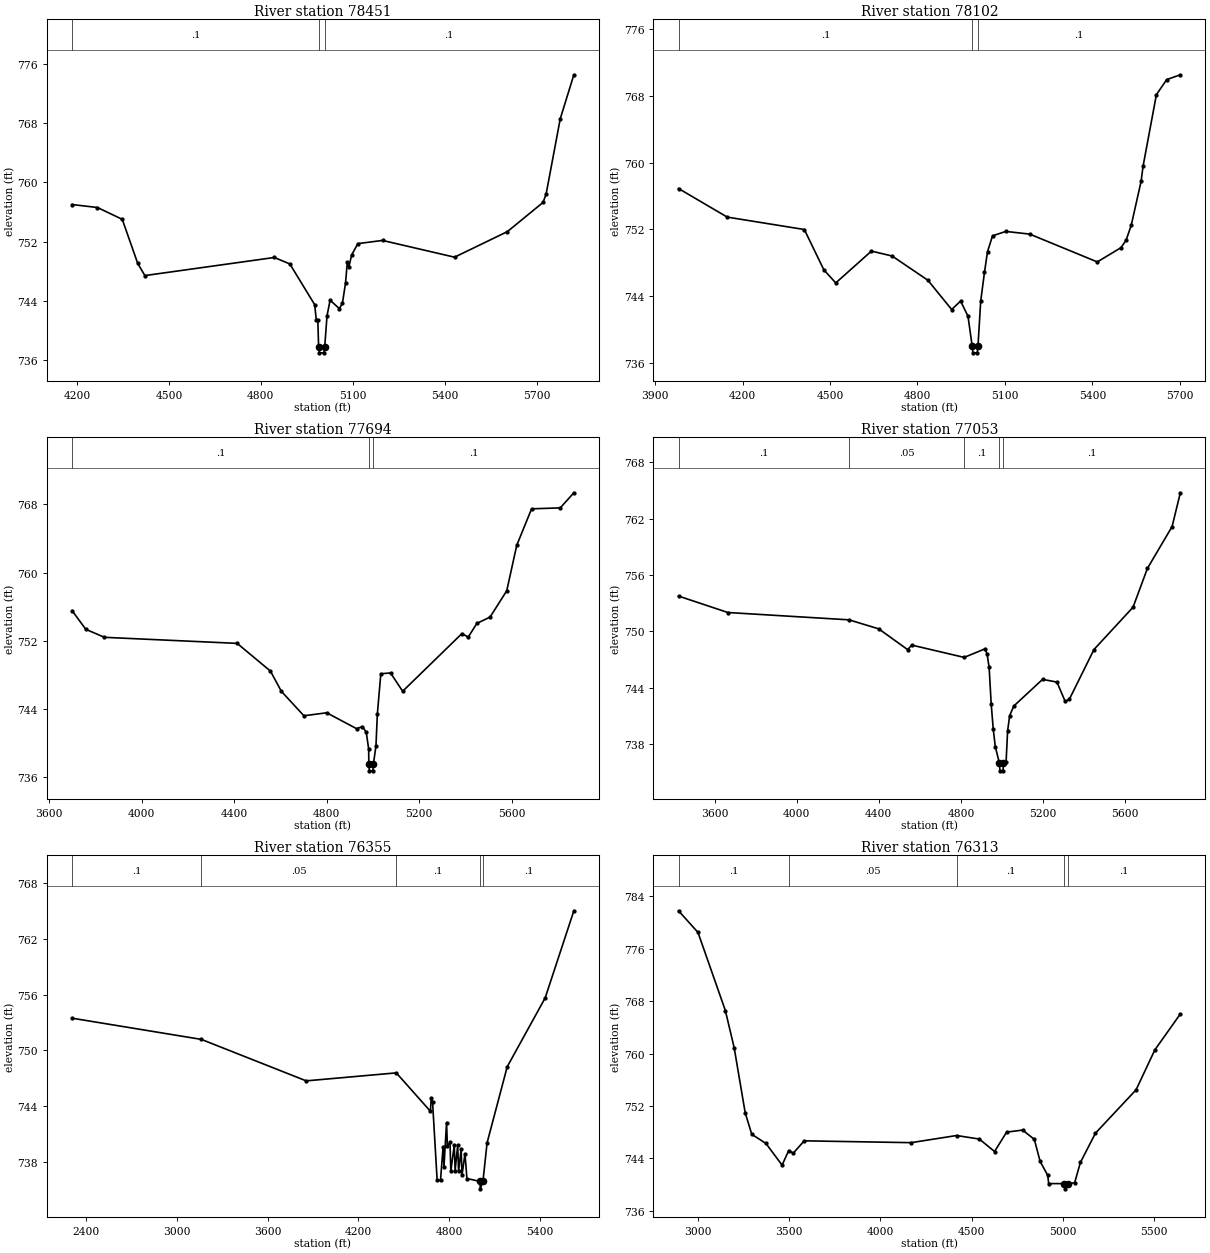
Type RM Length L Ch R = 1 ,78451   ,349,349,349
BEGIN DESCRIPTION:
SF PEREZ CREEK 104.0
END DESCRIPTION:
XS GIS Cut Line= 3
      1988396.66     13636497.04      1987609.55     13636371.72
      1986774.96       13636275.
#Sta/Elev= 30
  4184.1     757  4266.8   756.6  4347.8  755.01  4398.4  749.05  4421.7  747.42
    4844  749.86  4894.6  748.99  4975.6   743.5  4980.9  741.47  4985.9  741.47
  4988.5   737.8    4991     737  5005.9     737  5008.4   737.8  5015.9  741.99
    5026   744.1  5056.2  742.96  5066.2   743.7  5076.3   746.4  5082.1  749.21
  5087.1  748.58  5096.4   750.2  5116.6  751.73  5197.1  752.16    5432   749.9
  5604.5  753.35  5720.6  757.28  5730.7  758.39  5776.9  768.57  5821.3   774.5
#Mann= 3 ,-1 , 0
  4184.1      .1       0  4988.5     .07       0  5008.4      .1       0
Bank Sta=4988.5,5008.4
XS Rating Curve= 0 ,0
Exp/Cntr=0.3,0.1

Type RM Length L Ch R = 1 ,78102   ,408,408,408
BEGIN DESCRIPTION:
SF PEREZ CREEK 103.0
END DESCRIPTION:
XS GIS Cut Line= 4
      1988402.28     13636482.05      1988284.39     13636156.56
      1987622.57     13636024.49      1986944.88     13635848.18
#Sta/Elev= 30
  3980.5  756.91  4147.5  753.48    4412  751.99    4479  747.15  4519.8  745.58
  4642.2   749.4  4713.2  748.81  4835.9   745.9  4917.4  742.39  4948.1   743.4
  4973.5  741.58  4987.8  737.99  4990.3  737.19  5005.2  737.19  5007.7  737.99
    5017  743.39    5030  746.86  5040.4  749.33  5057.5  751.23  5103.2  751.76
    5185  751.44    5417   748.1  5498.1  749.81  5515.7   750.7  5533.4   752.5
  5567.3  757.78    5574  759.59  5619.7  768.17    5655  769.98  5701.8  770.56
#Mann= 3 ,-1 , 0
  3980.5      .1       0  4987.8     .07       0  5007.7      .1       0
Bank Sta=4987.8,5007.7
XS Rating Curve= 0 ,0
Exp/Cntr=0.3,0.1

Type RM Length L Ch R = 1 ,77694   ,641,641,641
BEGIN DESCRIPTION:
SF PEREZ CREEK 102.0
END DESCRIPTION:
XS GIS Cut Line= 4
      1988459.57     13636443.81      1988384.26     13635807.48
       1987809.2     13635655.57       1986919.7     13635373.53
#Sta/Elev= 30
  3699.4  755.54  3758.6  753.35  3839.2  752.41  4412.8   751.7  4556.6  748.46
  4603.8  746.09  4701.4  743.22  4799.9  743.57    4929  741.71  4954.2  741.96
  4970.8   741.3  4981.3  739.33  4981.9  737.57  4984.4  736.77  4999.3  736.77
  5001.8  737.57  5012.8  739.69  5018.8  743.42  5033.8  748.14  5075.7  748.24
  5128.2  746.09  5384.4  752.85  5411.4  752.43  5448.9  754.04  5505.9  754.78
    5578  757.86  5621.3  763.19  5685.4  767.46  5809.2  767.57  5868.1  769.34
#Mann= 3 ,-1 , 0
  3699.4      .1       0  4981.9     .07       0  5001.8      .1       0
Bank Sta=4981.9,5001.8
XS Rating Curve= 0 ,0
Exp/Cntr=0.3,0.1

Type RM Length L Ch R = 1 ,77053   ,698,698,698
BEGIN DESCRIPTION:
SF PEREZ CREEK 101.0
END DESCRIPTION:
XS GIS Cut Line= 4
      1988504.36     13636463.95      1988361.07     13635215.14
        1988025.       13635225.      1987174.99       13635275.
#Sta/Elev= 30
  3424.4  753.76  3664.9  752.01  4254.9  751.23  4399.7  750.27  4540.6  748.06
  4560.8  748.54    4816  747.23  4917.6  748.14  4927.6  747.58  4937.6  746.18
  4947.6   742.3  4957.6  739.59  4967.6  737.74  4987.7  735.95  4990.2  735.15
  5005.1  735.15  5007.6  735.95  5020.1  736.04  5027.6  739.39  5037.7  741.03
  5057.7  742.05  5197.9  744.89  5268.1   744.6  5308.1  742.54  5328.2  742.76
  5448.4  748.07  5638.7  752.57  5708.8  756.71    5829  761.16  5869.1  764.76
#Mann= 5 ,-1 , 0
  3424.4      .1       0  4254.9     .05       0    4816      .1       0
  4987.7     .07       0  5007.6      .1       0
Bank Sta=4987.7,5007.6
XS Rating Curve= 0 ,0
Exp/Cntr=0.3,0.1

Type RM Length L Ch R = 1 ,76355   ,42,42,42
BEGIN DESCRIPTION:
Mapping XS b06b7c25
END DESCRIPTION:
XS GIS Cut Line= 5
      1988532.15     13636467.43      1988709.23      13634925.8
       1987843.8     13634791.62      1987770.02     13634635.37
      1987084.28     13634856.71
#Sta/Elev= 30
  2305.8  753.46  3161.4  751.18  3855.4  746.72  4451.6  747.58  4677.5  743.45
  4682.6  744.88  4691.6  744.43    4722  736.01  4744.2  736.03  4761.4  739.65
    4767  737.47  4784.2  742.24  4789.7  739.72    4807   740.1  4812.5  737.02
  4835.3  739.82  4840.8  737.08    4858  739.81  4863.6  736.98  4880.8  739.39
  4886.3  736.57  4906.1  738.89  4918.9  736.22    5005  735.91  5007.5  735.11
    5025  735.91  5052.3  740.05  5185.7  748.24  5436.8  755.64  5626.7  765.01
#Mann= 5 ,-1 , 0
  2305.8      .1       0  3161.4     .05       0  4451.6      .1       0
    5005     .07       0    5025      .1       0
Bank Sta=5005,5025
XS Rating Curve= 0 ,0
Exp/Cntr=0.3,0.1

Type RM Length L Ch R = 1 ,76313   ,38,38,38
BEGIN DESCRIPTION:
SF PEREZ CREEK 100.0
END DESCRIPTION:
XS GIS Cut Line= 4
      1989606.68      13635004.2      1987892.45     13634770.82
        1987823.     13634573.34       1987054.6     13634821.93
#Sta/Elev= 30
  2895.7  781.79  3002.1  778.49    3152  766.56  3200.2  760.89  3260.7  750.94
  3296.7  747.66  3374.2  746.27  3462.6  742.96  3498.9  745.19    3524  744.79
  3583.7  746.67    4169  746.39  4417.9  747.48  4542.4  746.94  4625.7  745.04
  4691.8     748  4779.4  748.31  4843.5  746.89    4875  743.54  4916.8   741.4
    4922  740.14    5008  740.14  5010.5  739.34    5028  740.14  5064.2  740.27
  5095.7  743.37  5178.1  747.84  5400.5  754.46  5503.4  760.56  5642.7  766.03
#Mann= 5 ,-1 , 0
  2895.7      .1       0  3498.9     .05       0  4417.9      .1       0
    5008     .07       0    5028      .1       0
Bank Sta=5008,5028
XS Rating Curve= 0 ,0
Exp/Cntr=0.3,0.1

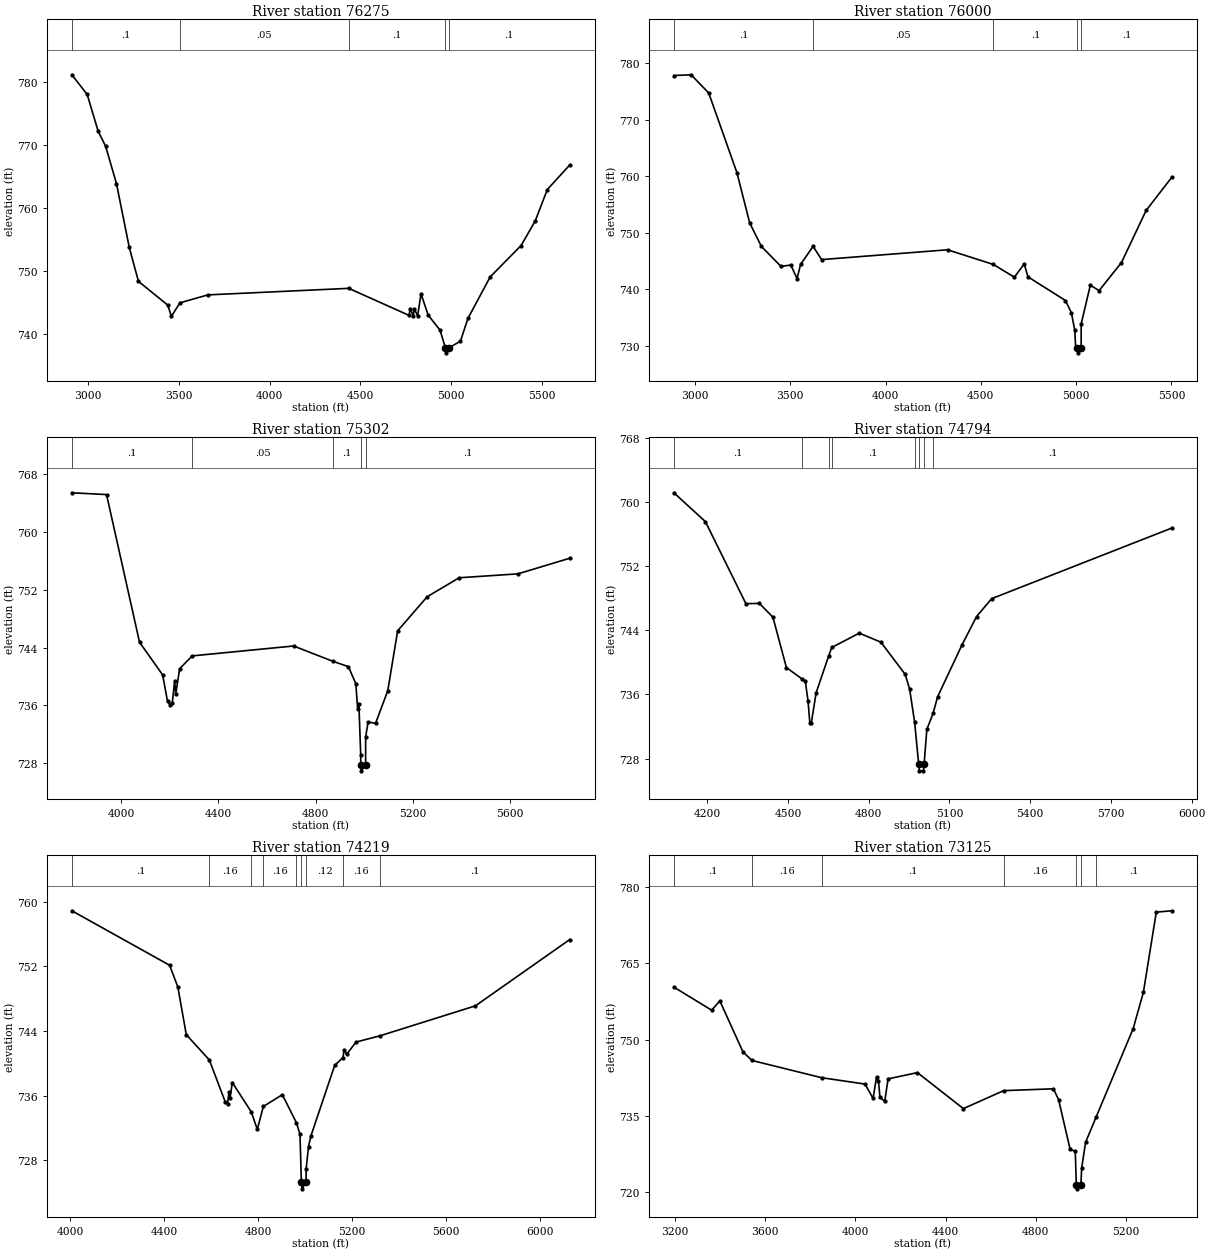
Type RM Length L Ch R = 1 ,76275   ,275,275,275
BEGIN DESCRIPTION:
Mapping XS 1454aecd
END DESCRIPTION:
XS GIS Cut Line= 4
      1989588.63     13634952.21      1987934.95     13634748.21
      1987830.78     13634535.54       1987028.9     13634773.94
#Sta/Elev= 30
  2911.6  781.16  2995.9  778.04  3056.3   772.2  3097.3  769.82  3157.1  763.88
  3227.6  753.75    3278  748.37  3439.2   744.6  3459.4  742.81  3506.2  744.96
  3660.3  746.22  4435.2  747.26    4768  742.96  4773.6  744.05  4790.5  742.93
  4796.1  744.05  4814.6  742.87  4833.3  746.39  4872.8  743.01  4938.1  740.62
  4967.2  737.82  4969.7  737.02  4987.2  737.82  5050.2  738.87  5091.9  742.51
  5214.1  749.08    5384  754.05  5462.1  757.97  5528.5  762.94  5651.2  766.82
#Mann= 5 ,-1 , 0
  2911.6      .1       0  3506.2     .05       0  4435.2      .1       0
  4967.2     .07       0  4987.2      .1       0
Bank Sta=4967.2,4987.2
XS Rating Curve= 0 ,0
Exp/Cntr=0.3,0.1

Type RM Length L Ch R = 1 ,76000   ,698,698,698
BEGIN DESCRIPTION:
SF PEREZ CREEK 99.0
END DESCRIPTION:
XS GIS Cut Line= 3
      1989663.12     13634843.61      1988582.42     13634596.22
      1987125.01       13634225.
#Sta/Elev= 30
  2888.7  777.77  2979.1   777.9  3071.4  774.69  3219.4  760.63  3286.9  751.71
  3348.1  747.58    3451  744.05  3502.3   744.3  3535.2  741.91  3553.6   744.4
  3619.4   747.6    3664  745.26  4324.9  746.99  4565.6   744.4  4675.8  742.15
  4727.4  744.48  4747.3  742.21  4944.1  738.03    4975  735.88  4992.7   732.8
  4997.9  729.63  5006.3  729.59  5008.8  728.79  5026.3  729.59  5026.6  733.91
  5074.5  740.74  5120.5  739.78  5238.1  744.74  5367.2  753.93  5501.3  759.76
#Mann= 5 ,-1 , 0
  2888.7      .1       0  3619.4     .05       0  4565.6      .1       0
  5006.3     .07       0  5026.3      .1       0
Bank Sta=5006.3,5026.3
XS Rating Curve= 0 ,0
Exp/Cntr=0.3,0.1

Type RM Length L Ch R = 1 ,75302   ,508,508,508
BEGIN DESCRIPTION:
SF PEREZ CREEK 98.0
END DESCRIPTION:
XS GIS Cut Line= 3
      1989307.27     13633971.22      1988408.81     13634031.98
      1987276.04     13633858.38
#Sta/Elev= 30
    3798  765.44  3940.6  765.19  4076.1  744.75  4171.1  740.22  4191.2  736.57
  4201.2  736.08  4211.2  736.39  4220.4  739.34  4225.4  737.64  4241.3  741.09
  4292.9  742.85  4709.5  744.22  4871.9  742.09    4935  741.36  4965.4  739.01
    4973  735.54  4978.1  736.19  4985.6  729.15  4985.7  727.73  4988.2  726.93
  5005.7  727.73  5005.9  731.62    5016  733.72  5046.5  733.49  5096.9  738.03
  5137.4  746.32  5258.8  751.04  5390.3  753.67  5631.9  754.21  5844.5  756.37
#Mann= 5 ,-1 , 0
    3798      .1       0  4292.9     .05       0  4871.9      .1       0
  4985.7     .07       0  5005.7      .1       0
Bank Sta=4985.7,5005.7
XS Rating Curve= 0 ,0
Exp/Cntr=0.3,0.1

Type RM Length L Ch R = 1 ,74794   ,575,575,575
BEGIN DESCRIPTION:
SF PEREZ CREEK 97.0
END DESCRIPTION:
XS GIS Cut Line= 3
      1989171.75     13633611.15       1987977.3     13633513.93
      1987373.16     13633756.98
#Sta/Elev= 30
    4076  761.17  4193.1  757.57  4343.6  747.33  4393.8  747.36    4444  745.64
  4494.1  739.35  4552.3  737.93  4564.4  737.63  4574.4  735.19  4581.3  732.39
  4586.4  732.39  4604.5  736.19  4650.8  740.77  4662.5  741.86    4765  743.65
  4845.3  742.52  4935.6   738.5  4951.9  736.68  4970.3   732.6  4985.8  727.26
  4988.3  726.46  5003.3  726.46  5005.8  727.26  5015.9  731.63    5039  733.62
    5056  735.71  5146.3  742.16  5200.5  745.71  5256.6  747.95  5925.6  756.76
#Mann= 8 ,-1 , 0
    4076      .1       0  4552.3     .16       0  4650.8     .05       0
  4662.5      .1       0  4970.3     .12       0  4985.8     .07       0
  5005.8     .12       0    5039      .1       0
Bank Sta=4985.8,5005.8
XS Rating Curve= 0 ,0
Exp/Cntr=0.3,0.1

Type RM Length L Ch R = 1 ,74219   ,1094,1094,1094
BEGIN DESCRIPTION:
SF PEREZ CREEK 96.0
END DESCRIPTION:
XS GIS Cut Line= 4
      1989330.78     13633487.14      1988935.56     13633133.03
      1988275.26     13633021.89      1987532.18     13633563.57
#Sta/Elev= 30
  4006.5  758.86  4422.8  752.12  4457.9  749.42  4493.8  743.53  4591.8  740.41
  4659.4  735.24  4669.5  734.97  4675.3  736.38  4680.3  735.74  4689.8  737.61
  4770.4  733.99  4796.3  731.81  4821.9  734.65  4902.8  736.11  4962.4  732.66
    4978  731.22  4983.9  725.26  4986.4  724.46  5004.1  725.26  5004.2  726.92
  5014.3  729.69  5024.5     731  5125.9  739.74  5160.9  740.69  5166.4  741.68
  5176.6   741.1  5216.9  742.62  5318.4  743.39  5725.2   747.1  6126.3  755.29
#Mann= 9 ,-1 , 0
  4006.5      .1       0  4591.8     .16       0  4770.4      .1       0
  4821.9     .16       0  4962.4     .12       0  4983.9     .07       0
  5004.1     .12       0  5160.9     .16       0  5318.4      .1       0
Bank Sta=4983.9,5004.1
XS Rating Curve= 0 ,0
Exp/Cntr=0.3,0.1

Type RM Length L Ch R = 1 ,73125   ,311,311,311
BEGIN DESCRIPTION:
SF PEREZ CREEK 95.0
END DESCRIPTION:
XS GIS Cut Line= 3
      1990004.46     13633188.58      1989087.76     13632591.33
      1988081.78     13632119.57
#Sta/Elev= 30
  3196.3   760.3  3363.6  755.77  3399.9   757.6  3502.6  747.56  3542.5   745.9
  3850.7  742.52  4043.1  741.27  4078.9  738.45    4094  742.64  4102.7   741.9
  4109.2  738.71  4130.3  737.85  4145.4  742.29  4275.2  743.52  4478.8  736.45
  4657.3  739.98  4877.8  740.34  4900.6  738.22  4951.8  728.45  4974.6  728.06
  4979.1   721.5  4981.6   720.7  4999.4   721.5    5003  724.82  5020.3  729.84
  5066.7  734.77  5231.2  752.17  5276.5  759.32  5333.5  775.02  5401.5  775.29
#Mann= 7 ,-1 , 0
  3196.3      .1       0  3542.5     .16       0  3850.7      .1       0
  4657.3     .16       0  4979.1     .07       0  4999.4     .16       0
  5066.7      .1       0
Bank Sta=4979.1,4999.4
XS Rating Curve= 0 ,0
Exp/Cntr=0.3,0.1

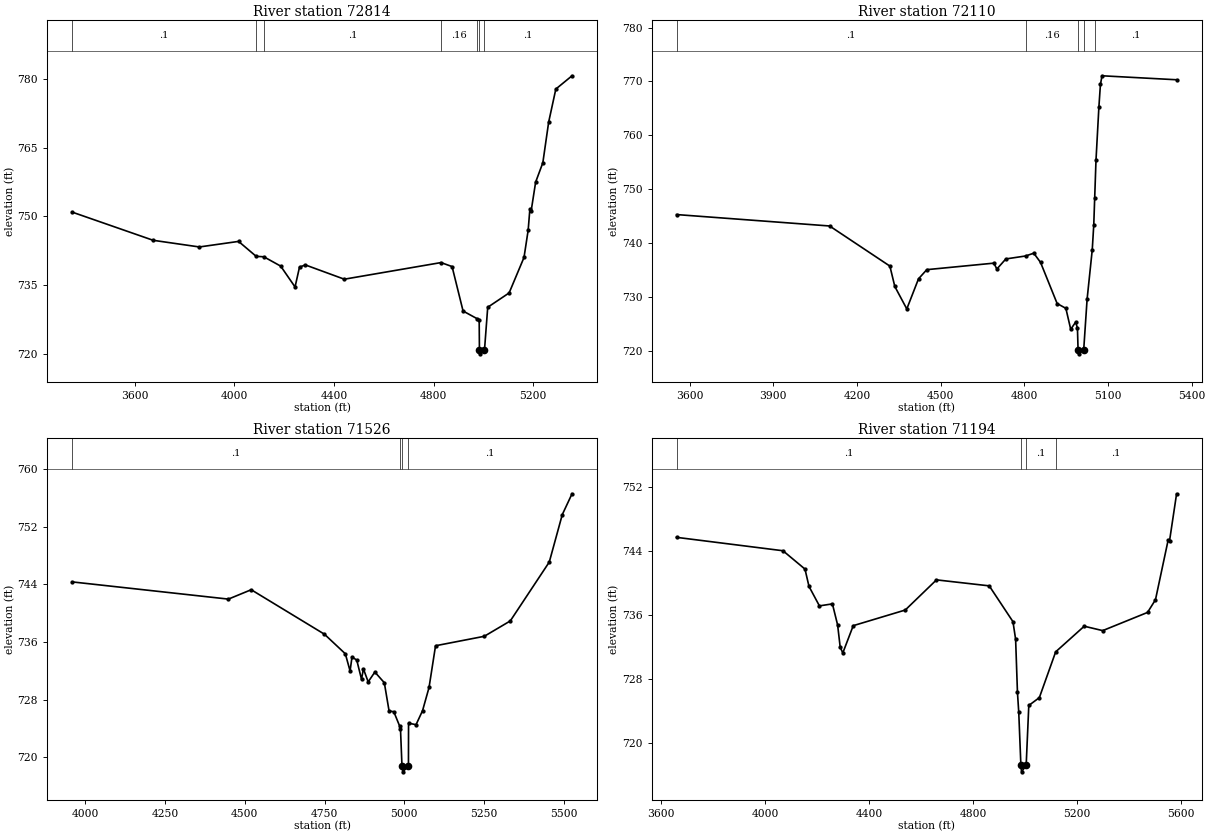
Type RM Length L Ch R = 1 ,72814   ,704,704,704
BEGIN DESCRIPTION:
Mapping XS f1914823
END DESCRIPTION:
XS GIS Cut Line= 2
      1990093.77     13632698.04      1988253.55     13631892.51
#Sta/Elev= 30
  3347.5  750.96  3673.6  744.81  3859.2  743.36  4016.7  744.57  4087.4  741.32
  4118.2  741.22  4185.9  739.19  4243.6  734.65  4261.5  738.97  4284.9  739.45
  4441.5  736.34  4830.1  739.96  4874.4  739.09  4918.6  729.41  4975.1  727.74
  4983.3  727.48  4984.3  720.89  4986.8  720.09  5004.6  720.89  5017.6  730.23
  5103.6  733.35  5163.4  741.08  5180.1  747.02  5186.8  751.53  5192.2  751.24
  5210.1  757.48    5239  761.69  5262.4  770.54  5291.2  777.74  5356.3  780.63
#Mann= 7 ,-1 , 0
  3347.5      .1       0  4087.4     .07       0  4118.2      .1       0
  4830.1     .16       0  4975.1      .1       0  4984.3     .07       0
  5004.6      .1       0
Bank Sta=4984.3,5004.6
XS Rating Curve= 0 ,0
Exp/Cntr=0.3,0.1

Type RM Length L Ch R = 1 ,72110   ,584,584,584
BEGIN DESCRIPTION:
SF PEREZ CREEK 94.0
END DESCRIPTION:
XS GIS Cut Line= 4
      1990010.46     13632073.05       1989795.2     13631899.45
        1988725.       13631475.      1988388.21     13631335.15
#Sta/Elev= 30
  3553.3  745.29    4102  743.17  4318.1  735.72  4335.7  731.94  4378.7  727.77
  4420.7  733.36  4450.4  735.06  4690.7  736.27  4701.6  735.18  4733.7  737.05
  4804.6   737.6  4833.9  738.12  4858.2   736.4  4917.6  728.77  4948.9  727.88
  4966.3  723.98  4983.8  725.31  4990.4  724.25  4992.6  720.23  4995.1  719.43
  5012.9  720.23    5025  729.56  5043.5  738.76  5048.9  743.36  5052.2  748.33
  5056.9   755.4  5067.4  765.35  5072.8  769.46  5078.6  771.06  5345.8  770.32
#Mann= 5 ,-1 , 0
  3553.3      .1       0  4804.6     .16       0  4992.6     .07       0
  5012.9     .16       0  5052.2      .1       0
Bank Sta=4992.6,5012.9
XS Rating Curve= 0 ,0
Exp/Cntr=0.3,0.1

Type RM Length L Ch R = 1 ,71526   ,332,332,332
BEGIN DESCRIPTION:
SF PEREZ CREEK 93.0
END DESCRIPTION:
XS GIS Cut Line= 3
      1990046.13     13631827.47        1989175.       13631225.
      1988674.97     13631124.99
#Sta/Elev= 30
  3957.6  744.32  4448.4  741.93    4520  743.23  4749.8  737.06  4815.4  734.34
  4830.2  731.96  4836.3   733.9  4851.2  733.47  4866.1  730.81  4872.1  732.25
    4887  730.45    4908  731.81  4937.7  730.33  4952.6  726.41  4967.4  726.31
  4986.2  724.27  4988.4  723.95  4993.1  718.77  4995.6  717.97  5013.4  718.77
  5013.7  724.72  5037.2  724.51  5057.6  726.45    5078  729.67  5098.4  735.46
  5251.3  736.77  5332.9   738.9  5455.3  747.07  5496.1  753.65  5526.7  756.54
#Mann= 4 ,-1 , 0
  3957.6      .1       0  4986.2     .16       0  4993.1     .07       0
  5013.4      .1       0
Bank Sta=4993.1,5013.4
XS Rating Curve= 0 ,0
Exp/Cntr=0.3,0.1

Type RM Length L Ch R = 1 ,71194   ,412,412,412
BEGIN DESCRIPTION:
SF PEREZ CREEK 92.0
END DESCRIPTION:
XS GIS Cut Line= 3
      1990684.09     13630989.73       1989670.2     13631031.39
      1988775.01       13630875.
#Sta/Elev= 30
  3660.1  745.73  4069.5  744.05  4154.2  741.75  4169.6  739.58  4209.7  737.14
  4259.7  737.39  4279.7  734.75  4289.7  731.95  4299.7  731.24  4339.8  734.66
  4539.9  736.62    4660   740.4  4862.9  739.65  4954.2  735.16  4964.4  732.96
  4971.5  726.29  4976.5  723.78  4984.7  717.14  4987.2  716.34    5005  717.14
  5015.1  724.66  5055.7  725.64  5118.5  731.38  5228.3  734.59  5299.4  734.04
  5471.9  736.32  5502.4  737.91  5551.3  745.41  5556.4  745.27  5583.6  751.19
#Mann= 4 ,-1 , 0
  3660.1      .1       0  4984.7     .07       0    5005      .1       0
  5118.5      .1       0
Bank Sta=4984.7,5005
XS Rating Curve= 0 ,0
Exp/Cntr=0.3,0.1