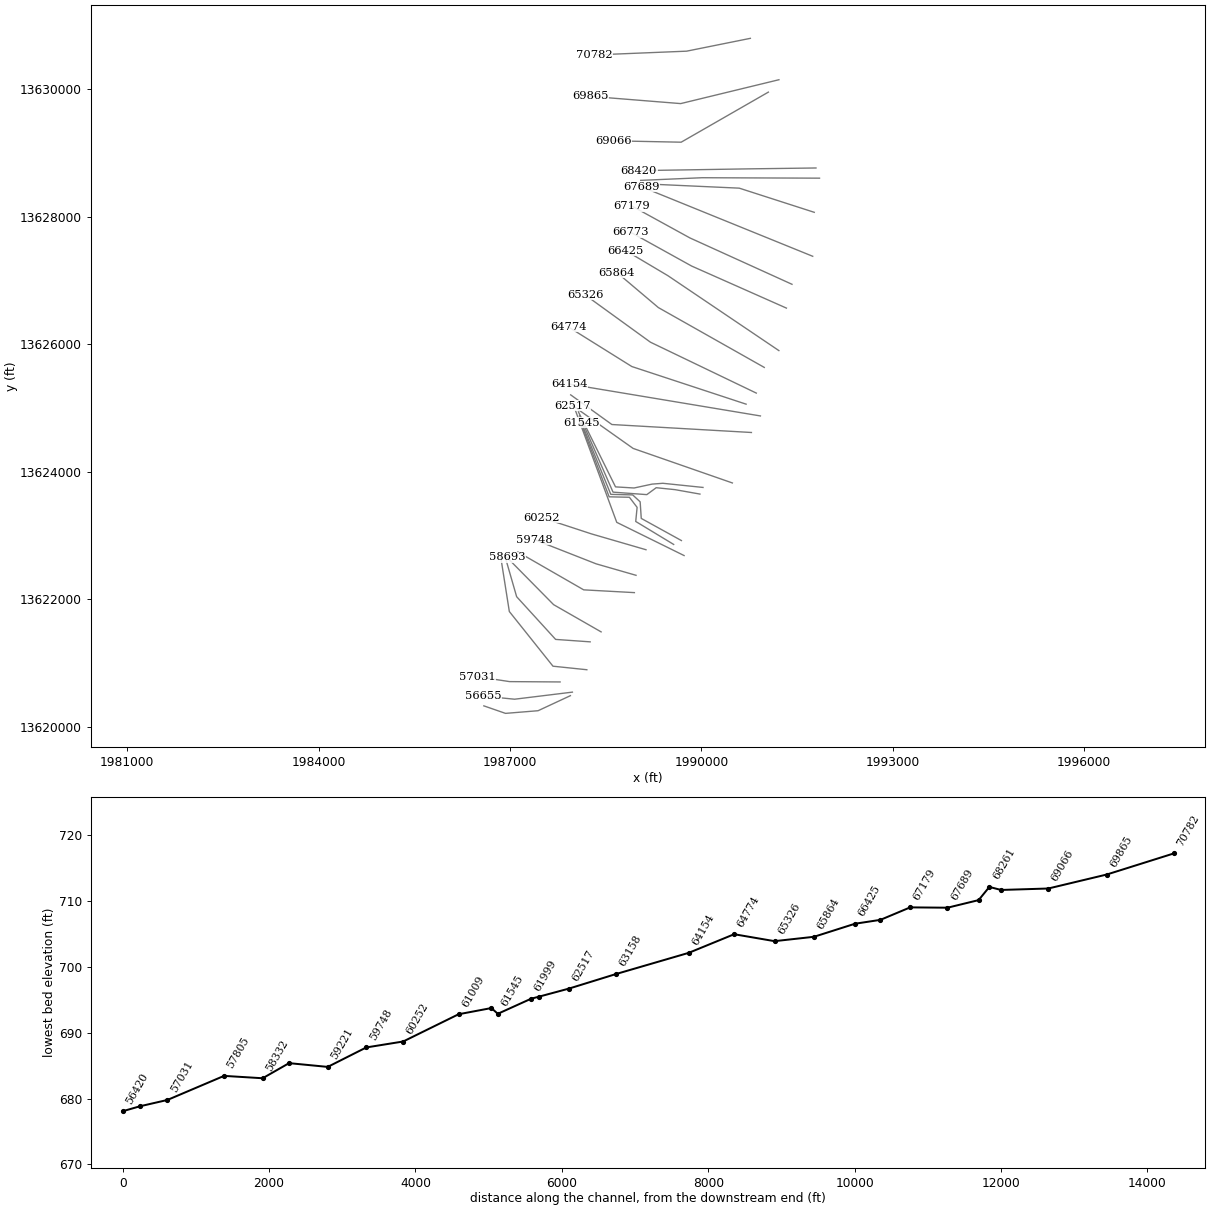
HEC-RAS study SF PEREZ CREEK.prj: SF PEREZ CREEK Base Level Engineering

--- SF PEREZ CREEK.g01 (geometry) --- (continued)

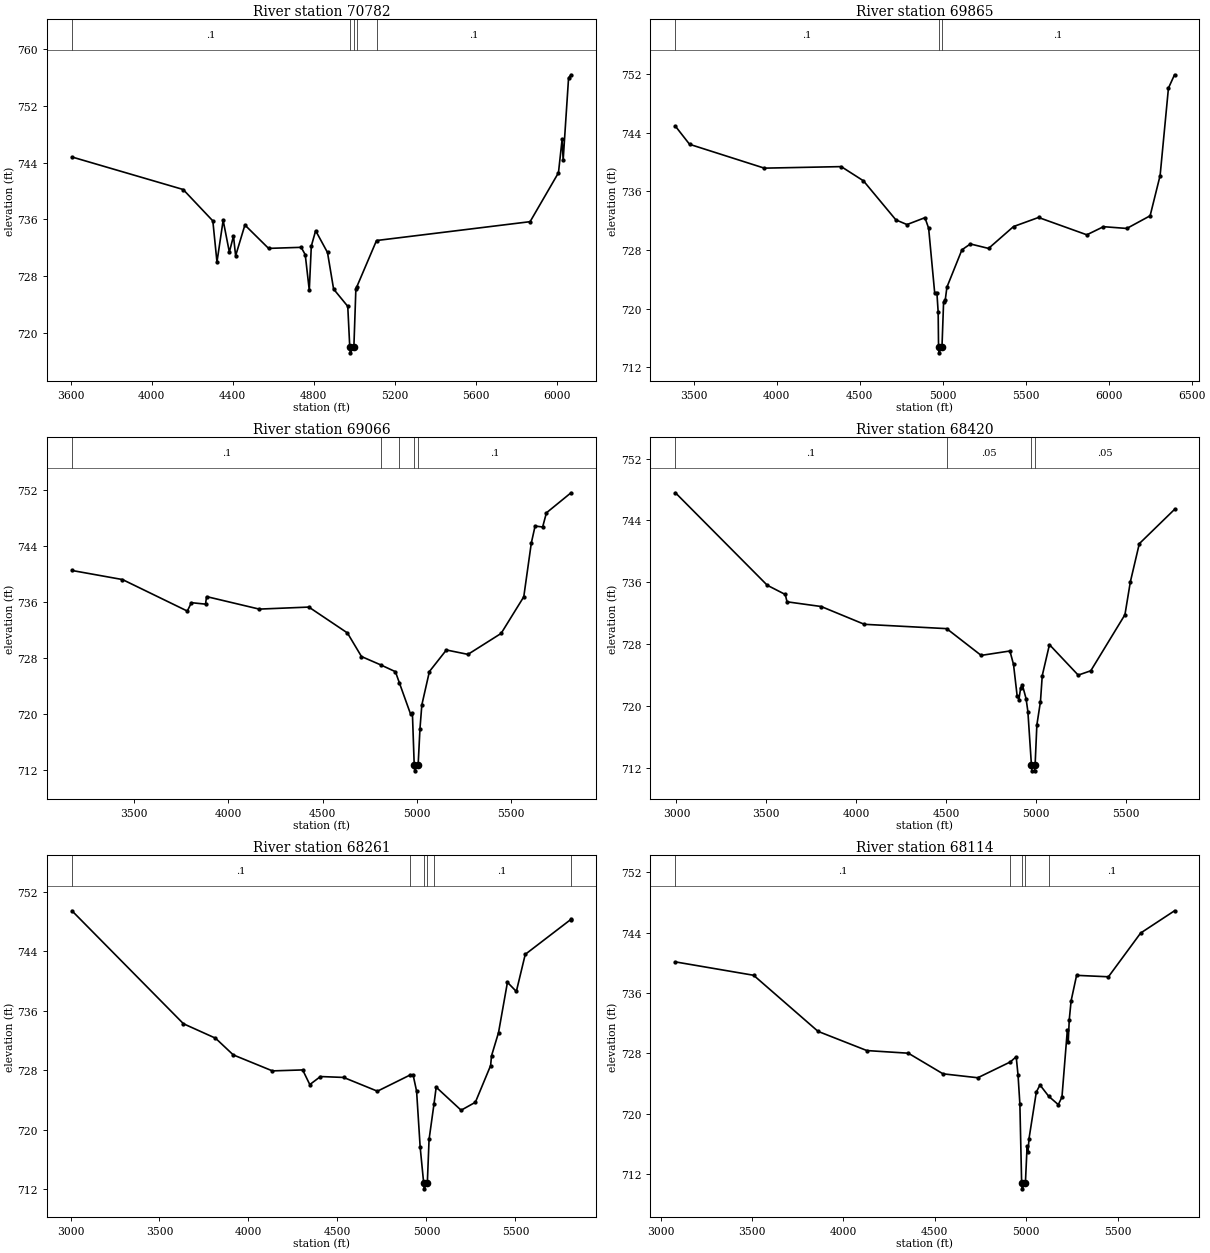
Type RM Length L Ch R = 1 ,70782   ,917,917,917
BEGIN DESCRIPTION:
SF PEREZ CREEK 91.0
END DESCRIPTION:
XS GIS Cut Line= 3
      1990767.37     13630798.75      1989767.42     13630597.37
      1988322.95     13630538.34
#Sta/Elev= 30
  3605.5  744.79    4155   740.2  4301.6  735.77    4322  729.97  4352.6  735.85
  4383.2  731.37  4403.6  733.63  4414.2  730.85    4460  735.19    4577  731.89
    4738  732.04  4758.1     731  4778.1  725.99  4788.1  732.21  4809.5  734.39
  4868.1  731.31  4898.2  726.15  4968.2  723.71  4978.1  717.95  4980.6  717.15
  4998.4  717.95  5008.3   726.2  5011.9   726.4  5110.3     733    5869  735.66
  6009.1  742.56  6027.3  747.31  6032.3  744.34  6059.1  755.96  6071.2  756.39
#Mann= 5 ,-1 , 0
  3605.5      .1       0  4978.1     .07       0  4998.4      .1       0
  5011.9     .07       0  5110.3      .1       0
Bank Sta=4978.1,4998.4
XS Rating Curve= 0 ,0
Exp/Cntr=0.3,0.1

Type RM Length L Ch R = 1 ,69865   ,799,799,799
BEGIN DESCRIPTION:
SF PEREZ CREEK 90.0
END DESCRIPTION:
XS GIS Cut Line= 3
      1991215.36     13630149.46        1989675.       13629775.
      1988258.49     13629888.91
#Sta/Elev= 30
  3390.5  744.92  3475.6  742.45    3926  739.19  4389.1   739.4  4522.9  737.46
  4718.4  732.12  4785.3  731.48  4893.4  732.42  4915.7  730.98  4952.3  722.11
  4965.4  722.18  4973.1  719.53  4975.4  714.75  4977.9  713.95  4996.1  714.75
  5005.8   720.9  5015.8  721.18  5025.9  722.93  5116.2  728.03  5167.1  728.83
  5276.7  728.22  5427.2  731.21  5577.7  732.45  5868.6  730.08  5968.9  731.19
  6109.4  730.95  6249.8  732.68    6310  738.18  6360.2  750.13  6396.8  751.95
#Mann= 3 ,-1 , 0
  3390.5      .1       0  4975.4     .07       0  4996.1      .1       0
Bank Sta=4975.4,4996.1
XS Rating Curve= 0 ,0
Exp/Cntr=0.3,0.1

Type RM Length L Ch R = 1 ,69066   ,646,646,646
BEGIN DESCRIPTION:
SF PEREZ CREEK 89.0
END DESCRIPTION:
XS GIS Cut Line= 3
      1991049.52     13629954.99      1989682.35     13629169.42
      1988614.67     13629191.12
#Sta/Elev= 30
  3171.6  740.51  3439.4  739.21    3783   734.7  3804.6   735.9  3879.4  735.69
  3885.1  736.77    4164  734.98  4427.1  735.27  4631.3  731.57    4706  728.19
  4808.3  726.99  4885.8  726.02  4906.8  724.42  4965.8  719.97  4975.8  720.08
  4985.4  712.63  4987.9  711.83  5006.1  712.63  5015.8  717.85  5025.8  721.27
  5065.8  726.04  5155.8  729.13  5270.1   728.5  5445.9   731.5  5565.9  736.74
  5605.9  744.44  5625.9  746.87  5665.9  746.73  5685.9  748.76  5816.3  751.63
#Mann= 5 ,-1 , 0
  3171.6      .1       0  4808.3     .07       0  4906.8      .1       0
  4985.4     .07       0  5006.1      .1       0
Bank Sta=4985.4,5006.1
XS Rating Curve= 0 ,0
Exp/Cntr=0.3,0.1

Type RM Length L Ch R = 1 ,68420   ,159,159,159
BEGIN DESCRIPTION:
SF PEREZ CREEK 88.0
END DESCRIPTION:
XS GIS Cut Line= 3
      1991796.08      13628764.9      1990733.57     13628751.01
       1989019.1     13628723.25
#Sta/Elev= 30
  2994.5  747.57  3505.6  735.61  3605.6  734.42  3615.6  733.47  3805.7  732.86
  4045.7  730.56  4503.9     730  4695.8  726.54  4855.8  727.11  4875.8  725.38
  4895.8  721.35  4905.8  720.81  4915.8  722.38  4925.8  722.67  4945.8  720.94
  4955.8  719.28  4975.4  712.41  4977.9  711.61  4993.6  711.61  4996.1  712.41
  5005.8  717.55  5025.8  720.57  5035.8  723.93  5075.8  727.93  5235.8  723.99
  5305.8  724.55  5495.9   731.8  5525.9  736.04  5575.9  740.99  5771.8  745.42
#Mann= 4 ,-1 , 0
  2994.5      .1       0  4503.9     .05       0  4975.4     .04       0
  4996.1     .05       0
Bank Sta=4975.4,4996.1
XS Rating Curve= 0 ,0
Exp/Cntr=0.3,0.1

Type RM Length L Ch R = 1 ,68261   ,147,147,147
BEGIN DESCRIPTION:
SF PEREZ CREEK 87.0
END DESCRIPTION:
XS GIS Cut Line= 3
       1991851.6     13628605.18      1990011.34     13628612.12
      1989048.01     13628570.54
#Sta/Elev= 30
    3008  749.46  3634.6  734.27  3814.6  732.33  3914.6  730.08  4134.6  727.93
  4304.6  728.06  4344.6  726.09  4404.6  727.17  4534.6  727.05  4724.6   725.2
  4905.1  727.34  4924.7  727.43  4944.7  725.21  4964.7  717.71  4984.4  712.87
  4986.9  712.07  5005.1  712.87  5014.8  718.71  5042.4  723.46  5054.8  725.74
  5194.9  722.64    5275  723.71  5360.7  728.65  5365.7  729.95  5405.1  733.08
  5455.2  739.84  5505.2  738.61  5555.3   743.6  5809.6  748.26  5812.5  748.38
#Mann= 6 ,-1 , 0
    3008      .1       0  4905.1     .12       0  4984.4     .07       0
  5005.1     .12       0  5042.4      .1       0  5809.6     .05       0
Bank Sta=4984.4,5005.1
XS Rating Curve= 0 ,0
Exp/Cntr=0.3,0.1

Type RM Length L Ch R = 1 ,68114   ,425,425,425
BEGIN DESCRIPTION:
Mapping XS e34fcd88
END DESCRIPTION:
XS GIS Cut Line= 3
      1991769.03     13628069.46      1990593.07     13628448.45
      1989099.84      13628516.5
#Sta/Elev= 30
  3081.5  740.12  3509.2  738.35  3861.8  730.92  4128.8  728.38  4355.6  728.03
  4545.3   725.3  4735.5  724.78  4913.3  726.87  4945.7  727.56  4955.8  725.12
  4965.8   721.3  4975.4  710.87  4977.9  710.07  4996.1  710.87  5005.4  715.76
  5010.4  714.95  5015.8  716.72  5055.9   722.9  5075.9  723.82  5123.4  722.33
    5176  721.22    5196  722.22  5225.4  731.08  5230.4  729.58    5236  732.47
  5246.1  734.97  5276.1  738.34  5450.3  738.15  5626.4  743.94  5811.8  746.89
#Mann= 5 ,-1 , 0
  3081.5      .1       0  4913.3     .12       0  4975.4     .07       0
  4996.1     .12       0  5123.4      .1       0
Bank Sta=4975.4,4996.1
XS Rating Curve= 0 ,0
Exp/Cntr=0.3,0.1

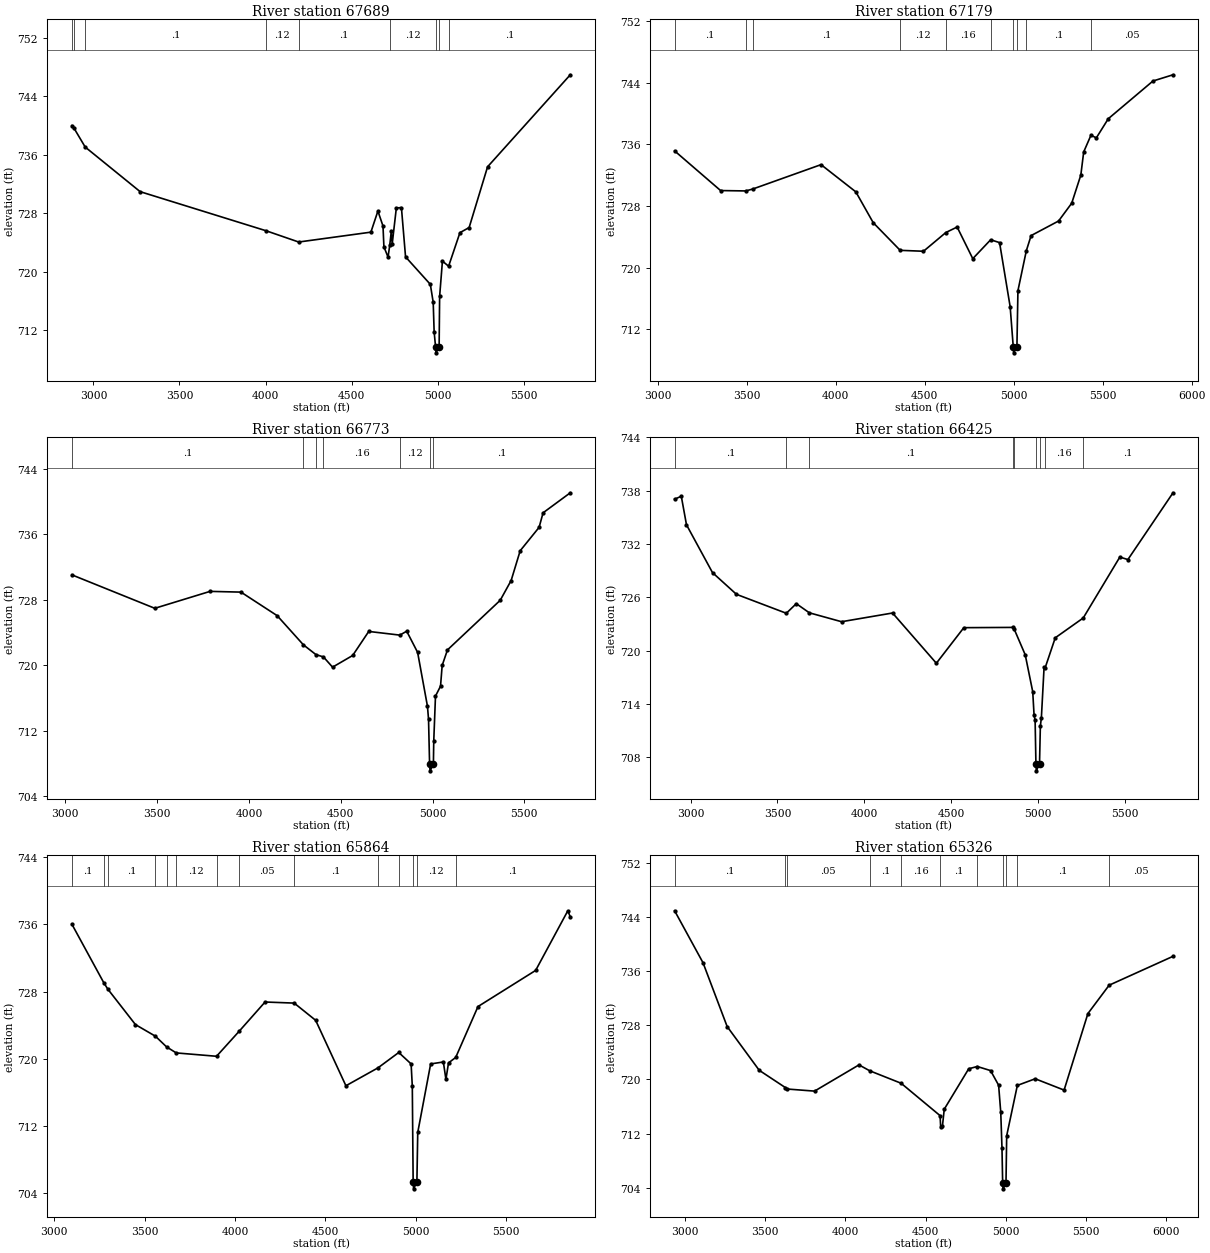
Type RM Length L Ch R = 1 ,67689   ,510,510,510
BEGIN DESCRIPTION:
Mapping XS c8704fbe
END DESCRIPTION:
XS GIS Cut Line= 2
      1991744.69     13627379.65      1989061.53     13628469.62
#Sta/Elev= 30
  2874.8  740.01  2885.6  739.71  2952.1  737.07  3271.4  730.97  4003.2  725.62
  4192.6  724.08  4612.2  725.43    4653  728.32  4682.5  726.27  4687.9  723.42
  4711.9  722.02  4721.9  723.66  4730.6  725.52    4736  723.81  4760.1  728.74
  4789.6  728.79  4813.6  722.05  4957.6  718.29  4974.3  715.83  4979.7  711.82
    4988  709.72  4990.5  708.92  5008.7  709.72  5011.6  716.63  5027.9  721.47
  5063.8  720.77  5129.6  725.36  5183.1  726.06  5290.2  734.37  5770.9  746.96
#Mann= 9 ,-1 , 0
  2874.8      .1       0  2885.6     .16       0  2952.1      .1       0
  4003.2     .12       0  4192.6      .1       0  4721.9     .12       0
    4988     .07       0  5008.7     .12       0  5063.8      .1       0
Bank Sta=4988,5008.7
XS Rating Curve= 0 ,0
Exp/Cntr=0.3,0.1

Type RM Length L Ch R = 1 ,67179   ,406,406,406
BEGIN DESCRIPTION:
Mapping XS bfb4b1e2
END DESCRIPTION:
XS GIS Cut Line= 3
      1991420.11     13626940.25      1989819.99     13627667.39
      1988906.17     13628169.58
#Sta/Elev= 30
    3095  735.15  3353.2  730.01  3494.4  729.96  3534.2  730.21  3917.6  733.37
  4113.1  729.84  4210.9  725.84  4362.2  722.26  4493.2  722.14  4618.9  724.57
  4682.3  725.28  4770.2  721.18  4870.7  723.63  4920.7  723.26  4980.3  714.94
  4997.5  709.77    5000  708.97  5018.2  709.77  5023.9  717.03  5071.1  722.21
  5097.9  724.17  5252.2  726.06  5326.1  728.37  5377.3  732.02  5393.4  735.02
  5434.2  737.18  5464.4  736.84  5531.5  739.32  5782.5  744.21  5895.3  745.02
#Mann= 10 ,-1 , 0
    3095      .1       0  3494.4     .16       0  3534.2      .1       0
  4362.2     .12       0  4618.9     .16       0  4870.7     .12       0
  4997.5     .07       0  5018.2     .12       0  5071.1      .1       0
  5434.2     .05       0
Bank Sta=4997.5,5018.2
XS Rating Curve= 0 ,0
Exp/Cntr=0.3,0.1

Type RM Length L Ch R = 1 ,66773   ,348,348,348
BEGIN DESCRIPTION:
SF PEREZ CREEK 86.0
END DESCRIPTION:
XS GIS Cut Line= 3
      1991332.42     13626566.82      1989846.27     13627226.56
      1988894.87     13627754.35
#Sta/Elev= 30
  3036.1  731.05  3487.5  726.96  3788.5  729.03  3956.8  728.94  4153.9  726.06
  4296.8  722.49  4364.8   721.3    4406  721.01  4455.6  719.76    4565  721.19
  4652.6  724.13    4822  723.68  4859.2  724.16  4918.7  721.57  4972.3  714.98
  4978.2  713.38  4983.9  707.88  4986.4  707.08  5004.6  707.88  5006.6  710.73
    5016  716.22  5043.5  717.44  5052.4  719.97  5081.2  721.87  5368.5  727.94
    5428  730.36  5477.2     734  5580.2  736.86  5601.9  738.64  5750.1  741.09
#Mann= 7 ,-1 , 0
  3036.1      .1       0  4296.8     .16       0  4364.8     .12       0
    4406     .16       0    4822     .12       0  4983.9     .07       0
  5004.6      .1       0
Bank Sta=4983.9,5004.6
XS Rating Curve= 0 ,0
Exp/Cntr=0.3,0.1

Type RM Length L Ch R = 1 ,66425   ,561,561,561
BEGIN DESCRIPTION:
SF PEREZ CREEK 85.0
END DESCRIPTION:
XS GIS Cut Line= 3
       1991214.3     13625900.19        1989475.       13627075.
      1988811.58      13627469.6
#Sta/Elev= 30
  2908.1  737.04  2946.5  737.37  2976.4  734.16  3126.3  728.78  3264.2  726.34
  3551.5  724.21  3608.9  725.29  3684.3  724.26  3869.6  723.26  4163.3  724.24
  4415.7  718.59  4573.9  722.59  4857.1  722.62  4863.5  722.45  4927.6  719.54
  4970.8  715.39  4978.5  712.76  4984.5  712.18  4989.2  707.29  4991.7  706.49
  5009.9  707.29  5014.8  711.54  5020.6  712.45  5036.2  718.15  5041.7  718.04
  5100.5  721.45  5261.7  723.68  5472.5  730.53  5518.9  730.25  5778.9  737.76
#Mann= 9 ,-1 , 0
  2908.1      .1       0  3551.5     .07       0  3684.3      .1       0
  4857.1     .16       0  4863.5     .12       0  4989.2     .07       0
  5009.9     .12       0  5041.7     .16       0  5261.7      .1       0
Bank Sta=4989.2,5009.9
XS Rating Curve= 0 ,0
Exp/Cntr=0.3,0.1

Type RM Length L Ch R = 1 ,65864   ,538,538,538
BEGIN DESCRIPTION:
SF PEREZ CREEK 84.0
END DESCRIPTION:
XS GIS Cut Line= 3
      1990985.18     13625636.27        1989325.       13626575.
      1988674.97     13627125.02
#Sta/Elev= 30
  3097.4  736.01    3274  729.04    3296  728.29  3449.2  724.06  3559.6  722.68
  3621.3  721.41    3675  720.69    3898  720.29  4023.7  723.28  4166.6  726.75
  4327.9  726.62  4446.7  724.57  4614.1  716.78  4791.5  718.91  4906.6  720.74
    4975  719.38  4981.6  716.73  4986.3  705.31  4988.8  704.51    5007  705.31
  5011.7  711.22  5083.2  719.38  5153.5  719.61  5167.7  717.54    5182   719.5
  5221.8  720.15  5345.2  726.21  5664.3  730.51  5842.4  737.61  5856.1  736.88
#Mann= 14 ,-1 , 0
  3097.4      .1       0    3274     .16       0    3296      .1       0
  3559.6     .07       0  3621.3      .1       0    3675     .12       0
    3898      .1       0  4023.7     .05       0  4327.9      .1       0
  4791.5     .16       0  4906.6     .12       0  4986.3     .07       0
    5007     .12       0  5221.8      .1       0
Bank Sta=4986.3,5007
XS Rating Curve= 0 ,0
Exp/Cntr=0.3,0.1

Type RM Length L Ch R = 1 ,65326   ,552,552,552
BEGIN DESCRIPTION:
SF PEREZ CREEK 83.0
END DESCRIPTION:
XS GIS Cut Line= 3
      1990860.14     13625233.51      1989200.43     13626032.12
        1988175.       13626775.
#Sta/Elev= 30
  2934.7  744.88  3111.8  737.21  3262.2   727.8  3462.3  721.34  3626.1  718.78
  3635.6  718.58  3807.3  718.27  4084.4  722.14  4151.3  721.27  4347.1  719.43
  4590.1  714.65  4593.9  712.95  4604.8  713.11  4616.1   715.6  4768.8  721.57
  4822.1   721.9  4904.9   721.3  4955.2  719.14  4968.5  715.13  4976.1  709.91
  4980.4  704.65  4982.9  703.85  5001.1  704.65  5005.5  711.69    5072  719.11
  5183.3  720.09  5363.5  718.42  5511.9  729.71  5644.5   733.9  6042.8  738.16
#Mann= 11 ,-1 , 0
  2934.7      .1       0  3626.1     .07       0  3635.6     .05       0
  4151.3      .1       0  4347.1     .16       0  4590.1      .1       0
  4822.1     .12       0  4980.4     .07       0  5001.1     .12       0
    5072      .1       0  5644.5     .05       0
Bank Sta=4980.4,5001.1
XS Rating Curve= 0 ,0
Exp/Cntr=0.3,0.1

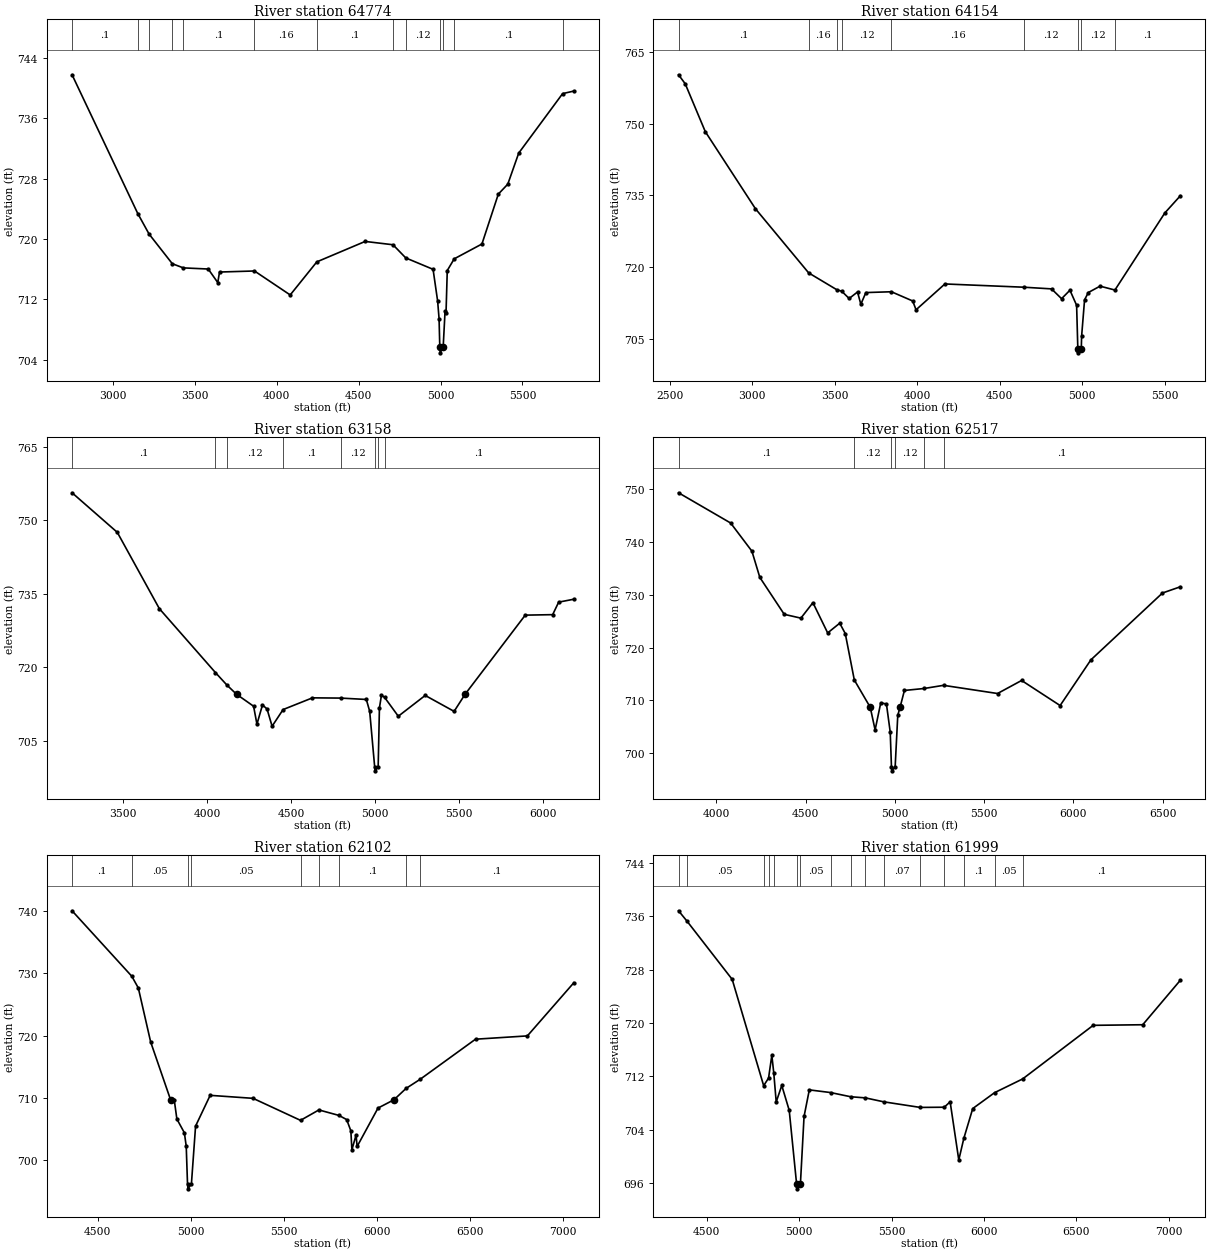
Type RM Length L Ch R = 1 ,64774   ,620,620,620
BEGIN DESCRIPTION:
SF PEREZ CREEK 82.0
END DESCRIPTION:
XS GIS Cut Line= 3
       1990700.4     13625059.91      1988908.77     13625650.17
      1987909.37      13626274.8
#Sta/Elev= 30
  2749.1  741.79  3150.4  723.38  3219.7  720.65  3361.5  716.72  3428.9  716.17
  3580.8  716.02  3639.1  714.22  3649.7  715.62  3863.2  715.76  4081.4  712.58
  4244.1  716.97  4539.2  719.68  4709.2  719.24  4787.5  717.49  4954.1  715.98
  4981.9  711.78  4990.7  709.44  4995.1   705.7  4997.6   704.9  5015.9   705.7
  5027.3  710.42  5033.2   710.2  5040.8  715.82  5083.1  717.37  5252.5  719.34
  5352.7  725.96  5410.5  727.28  5477.2   731.4  5745.3  739.29    5814  739.63
#Mann= 13 ,-1 , 0
  2749.1      .1       0  3150.4     .16       0  3219.7      .1       0
  3361.5     .16       0  3428.9      .1       0  3863.2     .16       0
  4244.1      .1       0  4709.2     .16       0  4787.5     .12       0
  4995.1     .07       0  5015.9     .12       0  5083.1      .1       0
  5745.3     .05       0
Bank Sta=4995.1,5015.9
XS Rating Curve= 0 ,0
Exp/Cntr=0.3,0.1

Type RM Length L Ch R = 1 ,64154   ,996,996,996
BEGIN DESCRIPTION:
SF PEREZ CREEK 81.0
END DESCRIPTION:
XS GIS Cut Line= 3
        1990925.       13624875.        1988525.       13625275.
      1987924.98       13625375.
#Sta/Elev= 30
  2552.5  760.21    2593  758.33  2714.7  748.32  3018.8   732.2  3341.3  718.79
    3511  715.29  3541.9  714.95  3586.6  713.44  3637.3   714.8  3657.5  712.24
  3687.9  714.68  3842.7  714.85  3971.8  712.92  3992.1  711.08    4167  716.48
    4645   715.8  4813.3  715.45  4874.1   713.4  4924.8  715.17  4965.3  712.02
  4972.7  702.88  4975.2  702.08  4993.5  702.88  4995.7   705.6  5013.5  713.16
  5036.3  714.69  5107.3  716.02  5197.5  715.21  5500.1  731.33  5593.9  734.91
#Mann= 9 ,-1 , 0
  2552.5      .1       0  3341.3     .16       0    3511      .1       0
  3541.9     .12       0  3842.7     .16       0    4645     .12       0
  4972.7     .07       0  4993.5     .12       0  5197.5      .1       0
Bank Sta=4972.7,4993.5
XS Rating Curve= 0 ,0
Exp/Cntr=0.3,0.1

Type RM Length L Ch R = 1 ,63158   ,641,641,641
BEGIN DESCRIPTION:
SF PEREZ CREEK 80.0
END DESCRIPTION:
XS GIS Cut Line= 3
      1990783.73     13624615.45      1988596.27     13624740.45
      1987950.44     13625205.72
#Sta/Elev= 30
  3196.3  755.58  3465.5  747.51  3715.9  731.94  4049.6  718.91  4119.3  716.31
 4175.74714.4735  4276.8  712.04  4296.8  708.38  4329.8   712.3  4356.9  711.48
    4387  707.96  4452.5  711.36  4627.4  713.75  4795.6   713.7  4947.9  713.42
  4967.9  711.01  4997.6  699.66  5000.1  698.86  5018.4  699.66  5025.9  711.69
    5038   714.3  5056.9  713.83  5138.2     710  5298.4  714.24  5470.5  710.99
  5535.7714.4738  5893.9  730.62  6057.2  730.72  6092.8  733.27  6183.3  733.87
#Mann= 8 ,-1 , 0
  3196.3      .1       0  4049.6     .16       0  4119.3     .12       0
  4452.5      .1       0  4795.6     .12       0  4997.6     .07       0
  5018.4     .12       0  5056.9      .1       0
Bank Sta=4175.74,5535.7
XS Rating Curve= 0 ,0
Exp/Cntr=0.3,0.1

Type RM Length L Ch R = 1 ,62517   ,415,415,415
BEGIN DESCRIPTION:
SF PEREZ CREEK 79.0
END DESCRIPTION:
XS GIS Cut Line= 3
       1990485.2     13623823.77       1988929.6     13624365.45
      1987979.13     13625038.41
#Sta/Elev= 30
  3787.6  749.34  4079.6  743.61  4198.7  738.28  4243.1  733.31  4379.9  726.31
  4473.2  725.59  4540.6  728.52  4623.3  722.79  4690.8  724.63  4721.9  722.67
  4772.6  713.87 4861.86708.6992  4889.1  704.41  4920.8  709.55  4952.6  709.32
  4973.8  704.01  4980.7  697.46  4983.2  696.66  5001.5  697.46  5016.1  707.18
 5028.95708.6982  5053.3  711.89  5163.5  712.26  5272.4  712.86  5575.1  711.31
    5710  713.78  5925.8  709.03  6098.1  717.68  6499.3  730.35  6599.4  731.53
#Mann= 6 ,-1 , 0
  3787.6      .1       0  4772.6     .12       0  4980.7     .07       0
  5001.5     .12       0  5163.5     .16       0  5272.4      .1       0
Bank Sta=4861.86,5028.95
XS Rating Curve= 0 ,0
Exp/Cntr=0.3,0.1

Type RM Length L Ch R = 1 ,62102   ,103,103,103
BEGIN DESCRIPTION:
Mapping XS 9d96331e
END DESCRIPTION:
XS GIS Cut Line= 6
      1990024.77     13623753.47      1989395.46     13623818.58
      1989226.19     13623805.56      1988944.07     13623744.79
      1988653.27     13623762.15      1988071.67     13624938.37
#Sta/Elev= 30
    4363     740  4683.8   729.5  4718.8  727.62    4785  718.97  4891.9709.7018
  4911.5  709.71  4925.8  706.61    4966  704.41    4976  702.26  4982.9  696.22
  4985.4  695.42  5003.9  696.22  5026.2  705.48  5104.5  710.41  5334.9  709.93
  5589.7   706.4  5688.4  708.07  5796.3  707.19  5837.6  706.52    5860  704.72
  5865.6  701.68    5888  704.05  5893.6  702.21  6005.8  708.37 6091.68709.7025
  6156.4  711.52  6231.1  712.96  6529.4  719.41  6807.9  719.94  7057.5  728.47
#Mann= 9 ,-1 , 0
    4363      .1       0  4683.8     .05       0  4982.9     .04       0
  5003.9     .05       0  5589.7     .08       0  5688.4     .05       0
  5796.3      .1       0  6156.4     .05       0  6231.1      .1       0
Bank Sta=4891.9,6091.68
XS Rating Curve= 0 ,0
Exp/Cntr=0.3,0.1

Type RM Length L Ch R = 1 ,61999   ,454,454,454
BEGIN DESCRIPTION:
Mapping XS b9a7bf40
END DESCRIPTION:
XS GIS Cut Line= 6
       1989977.1      13623649.3      1989586.43     13623718.75
      1989291.29     13623749.13      1989143.72     13623640.62
      1988614.21     13623679.69      1988089.94     13624879.86
#Sta/Elev= 30
  4346.7  736.82  4392.4  735.27  4637.3  726.53  4807.7  710.59  4834.2  711.73
  4851.9  715.14  4862.5  712.48  4875.6  708.15  4905.8  710.62    4946   706.9
  4985.8  695.92  4988.3  695.12  5006.8  695.92  5026.4  705.97  5054.9  709.96
    5170  709.56    5279  708.93  5358.8  708.76  5457.7  708.17  5655.5  707.33
  5785.6  707.36  5817.5  708.17  5864.3  699.45  5891.7   702.7  5939.9  707.16
    6058  709.54    6210   711.6  6592.1  719.64  6860.4  719.73    7064   726.4
#Mann= 16 ,-1 , 0
  4346.7      .1       0  4392.4     .05       0  4807.7      .1       0
  4834.2     .12       0  4862.5     .05       0  4985.8     .04       0
  5006.8     .05       0    5170     .12       0    5279     .05       0
  5358.8      .1       0  5457.7     .07       0  5655.5     .12       0
  5785.6     .05       0  5891.7      .1       0    6058     .05       0
    6210      .1       0
Bank Sta=4985.8,5006.8
XS Rating Curve= 0 ,0
Exp/Cntr=0.3,0.1

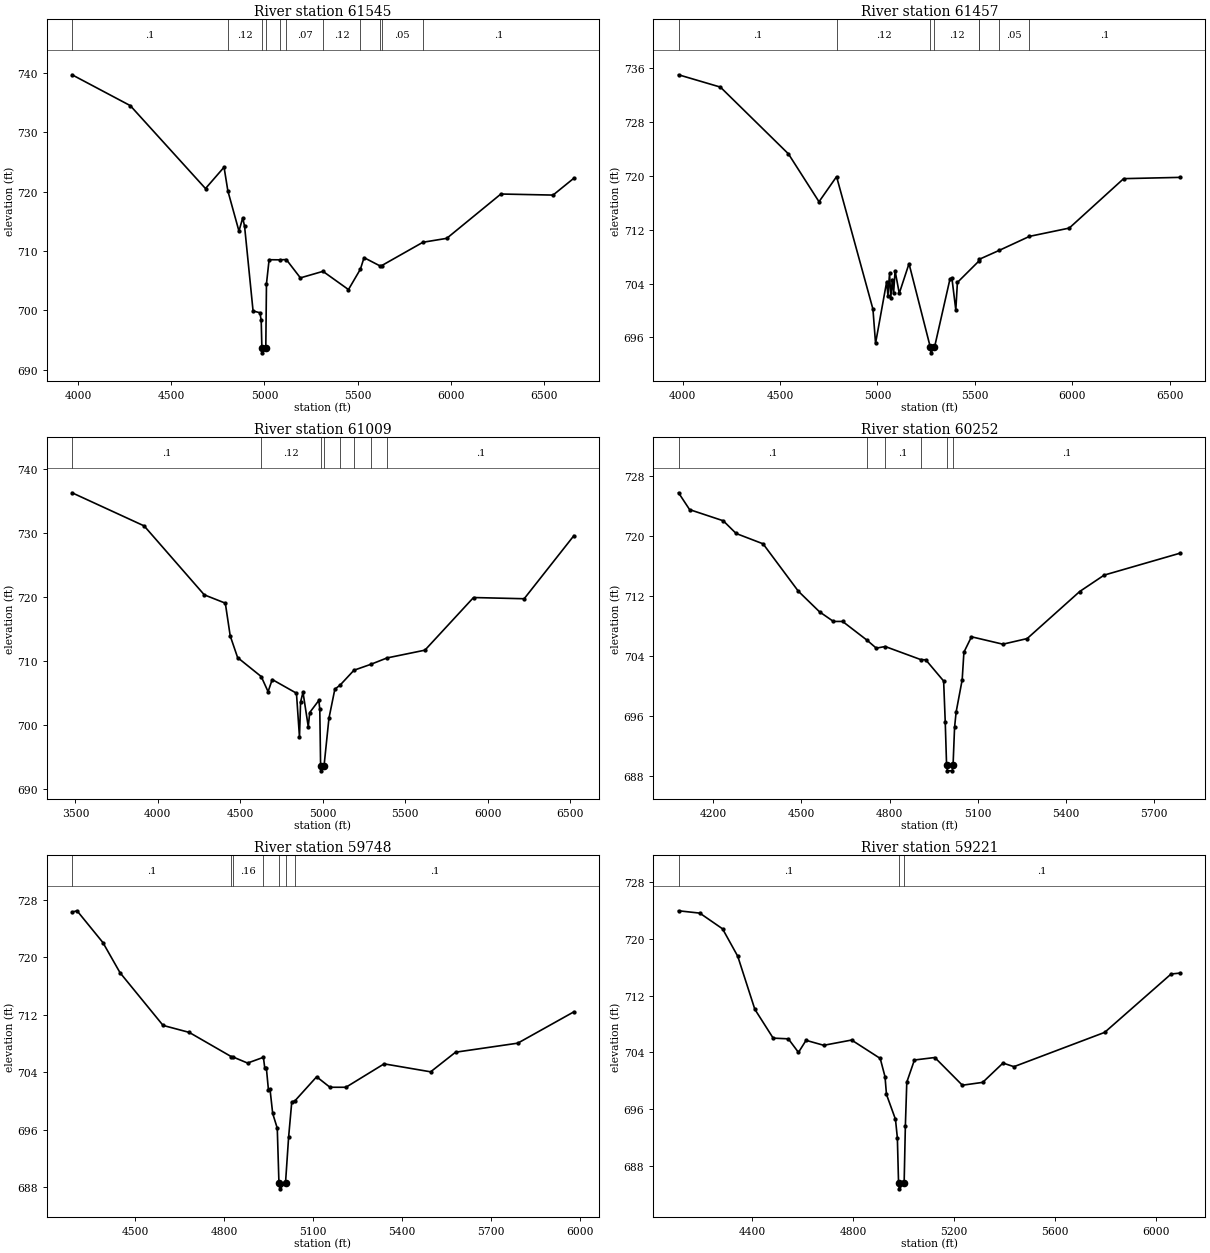
Type RM Length L Ch R = 1 ,61545   ,88,88,88
BEGIN DESCRIPTION:
Mapping XS eea259c9
END DESCRIPTION:
XS GIS Cut Line= 6
      1989686.28     13622920.13      1989056.92     13623267.36
      1989039.55     13623527.78      1988922.37     13623636.28
      1988579.49     13623644.96      1988119.69     13624768.42
#Sta/Elev= 30
  3966.1  739.69    4279  734.49  4683.1  720.52  4782.8  724.12  4803.3  720.12
  4862.9  713.35    4883  715.57    4893  714.19  4938.7   699.9  4975.6  699.59
  4982.4  698.34  4986.1  693.64  4988.6  692.84  5007.1  693.64  5010.7  704.47
  5024.9  708.53  5082.4  708.51  5117.3  708.56    5193  705.47  5314.3  706.57
  5451.3   703.5  5515.5  706.94  5535.1  708.88  5620.6  707.49    5630  707.54
  5851.4  711.47  5979.4  712.13  6270.4   719.6  6550.7  719.42  6662.5  722.26
#Mann= 11 ,-1 , 0
  3966.1      .1       0  4803.3     .12       0  4986.1     .07       0
  5007.1     .12       0  5082.4      .1       0  5117.3     .07       0
  5314.3     .12       0  5515.5     .05       0  5620.6      .1       0
    5630     .05       0  5851.4      .1       0
Bank Sta=4986.1,5007.1
XS Rating Curve= 0 ,0
Exp/Cntr=0.3,0.1

Type RM Length L Ch R = 1 ,61457   ,448,448,448
BEGIN DESCRIPTION:
Mapping XS 2dbf6331
END DESCRIPTION:
XS GIS Cut Line= 6
      1989564.75     13622859.36      1988970.11     13623219.62
      1988991.81     13623440.97       1988870.8     13623599.13
      1988553.62     13623606.42      1988146.16     13624671.78
#Sta/Elev= 30
  3979.2  734.99    4194  733.16    4543  723.25    4700  716.14  4790.1  719.87
  4976.7   700.2  4990.1  695.12  5047.3  704.29  5053.6  702.19  5061.9   705.5
  5068.2  701.91  5076.4  704.59  5082.7  702.54  5090.3  705.89  5111.8  702.54
  5161.8  706.95  5271.4  694.51  5273.9  693.71  5292.4  694.51  5371.9  704.67
  5381.9   704.8  5401.9  700.08  5410.1  704.16  5519.5  707.31  5521.7  707.59
  5623.8  708.91  5779.9     711  5983.9  712.23  6263.1  719.57  6553.9  719.76
#Mann= 8 ,-1 , 0
  3979.2      .1       0  4790.1     .12       0  5271.4     .07       0
  5292.4     .12       0  5519.5     .05       0  5521.7     .08       0
  5623.8     .05       0  5779.9      .1       0
Bank Sta=5271.4,5292.4
XS Rating Curve= 0 ,0
Exp/Cntr=0.3,0.1

Type RM Length L Ch R = 1 ,61009   ,757,757,757
BEGIN DESCRIPTION:
SF PEREZ CREEK 78.0
END DESCRIPTION:
XS GIS Cut Line= 3
      1989728.25     13622684.88      1988672.66     13623205.73
      1988026.81     13624955.76
#Sta/Elev= 30
  3479.8  736.25  3916.8  731.07  4281.5  720.29    4409  718.99  4438.7  713.87
  4483.6  710.48  4626.8  707.51  4668.3  705.15  4693.4  707.05  4840.3  704.91
  4858.7  698.04  4865.4  703.53    4880  705.07  4911.9  699.68  4920.9  701.89
  4975.9  703.78  4981.8  702.42  4986.7  693.57  4989.2  692.77  5007.7  693.57
  5037.3  700.99  5073.1  705.54  5105.2  706.18  5188.9   708.5  5292.7  709.44
    5389  710.42  5619.3  711.64  5913.9  719.87    6221  719.68  6522.3  729.54
#Mann= 8 ,-1 , 0
  3479.8      .1       0  4626.8     .12       0  4986.7     .07       0
  5007.7     .12       0  5105.2      .1       0  5188.9     .08       0
  5292.7     .05       0    5389      .1       0
Bank Sta=4986.7,5007.7
XS Rating Curve= 0 ,0
Exp/Cntr=0.3,0.1

Type RM Length L Ch R = 1 ,60252   ,504,504,504
BEGIN DESCRIPTION:
SF PEREZ CREEK 77.0
END DESCRIPTION:
XS GIS Cut Line= 3
      1989131.23     13622776.13        1988275.       13623025.
      1987499.66     13623279.48
#Sta/Elev= 30
  4081.6  725.79  4119.3  723.54  4233.7  722.05  4277.7  720.35  4369.3  718.97
  4489.3  712.64  4561.6  709.88  4608.8   708.6    4640   708.6  4723.5  706.08
  4754.6  705.03  4784.9  705.25  4905.4  703.51    4923  703.47  4983.8  700.64
  4989.2  695.22  4993.8  689.44  4996.7  688.64    5013  688.64  5015.9  689.44
    5021  694.44  5026.3  696.49  5046.9   700.8  5052.8  704.49  5078.5  706.55
  5185.4  705.56    5268  706.31  5446.9   712.6  5530.1  714.79  5789.3  717.73
#Mann= 6 ,-1 , 0
  4081.6      .1       0  4723.5     .12       0  4784.9      .1       0
  4905.4     .16       0  4993.8     .07       0  5015.9      .1       0
Bank Sta=4993.8,5015.9
XS Rating Curve= 0 ,0
Exp/Cntr=0.3,0.1

Type RM Length L Ch R = 1 ,59748   ,527,527,527
BEGIN DESCRIPTION:
SF PEREZ CREEK 76.0
END DESCRIPTION:
XS GIS Cut Line= 3
      1988974.96     13622375.01      1988349.97     13622554.77
      1987378.85     13622936.29
#Sta/Elev= 30
  4286.1  726.27  4302.9  726.45  4390.1  722.03  4448.1  717.82  4593.3  710.49
  4681.5  709.52  4823.3  706.15  4828.5  706.11  4878.5  705.25  4931.9  706.05
  4936.4   704.6  4941.8   704.6  4948.9  701.52  4954.3  701.57  4963.3  698.23
  4978.7  696.18  4984.4  688.54  4987.3  687.74  5006.5  688.54    5017  694.93
  5027.6  699.82  5038.7  700.01  5111.6  703.34  5156.6  701.88  5210.4  701.88
  5339.3  705.14  5496.4  704.03  5580.4  706.76  5790.5  708.02  5979.8  712.38
#Mann= 7 ,-1 , 0
  4286.1      .1       0  4823.3     .12       0  4828.5     .16       0
  4931.9     .12       0  4984.4     .07       0  5006.5     .12       0
  5038.7      .1       0
Bank Sta=4984.4,5006.5
XS Rating Curve= 0 ,0
Exp/Cntr=0.3,0.1

Type RM Length L Ch R = 1 ,59221   ,528,528,528
BEGIN DESCRIPTION:
SF PEREZ CREEK 75.0
END DESCRIPTION:
XS GIS Cut Line= 3
      1988948.96     13622103.38      1988154.66     13622146.79
      1987122.88     13622740.71
#Sta/Elev= 30
  4108.8  723.94  4192.9  723.61    4283   721.4  4343.1  717.54  4410.8  710.07
  4483.3  706.01  4543.4  705.91  4583.5     704  4613.5   705.7  4683.6     705
  4793.8  705.74    4907  703.15    4926  700.58  4931.8  698.08  4967.4  694.58
  4974.9  691.96  4979.6  685.59  4982.5  684.79  5001.7  685.59  5006.5  693.58
  5012.2  699.81  5042.4  702.93  5123.1  703.28  5232.1  699.38  5312.6  699.78
    5393   702.5  5436.2  701.99  5795.4  706.82  6058.4  715.04  6094.8  715.17
#Mann= 3 ,-1 , 0
  4108.8      .1       0  4979.6     .07       0  5001.7      .1       0
Bank Sta=4979.6,5001.7
XS Rating Curve= 0 ,0
Exp/Cntr=0.3,0.1

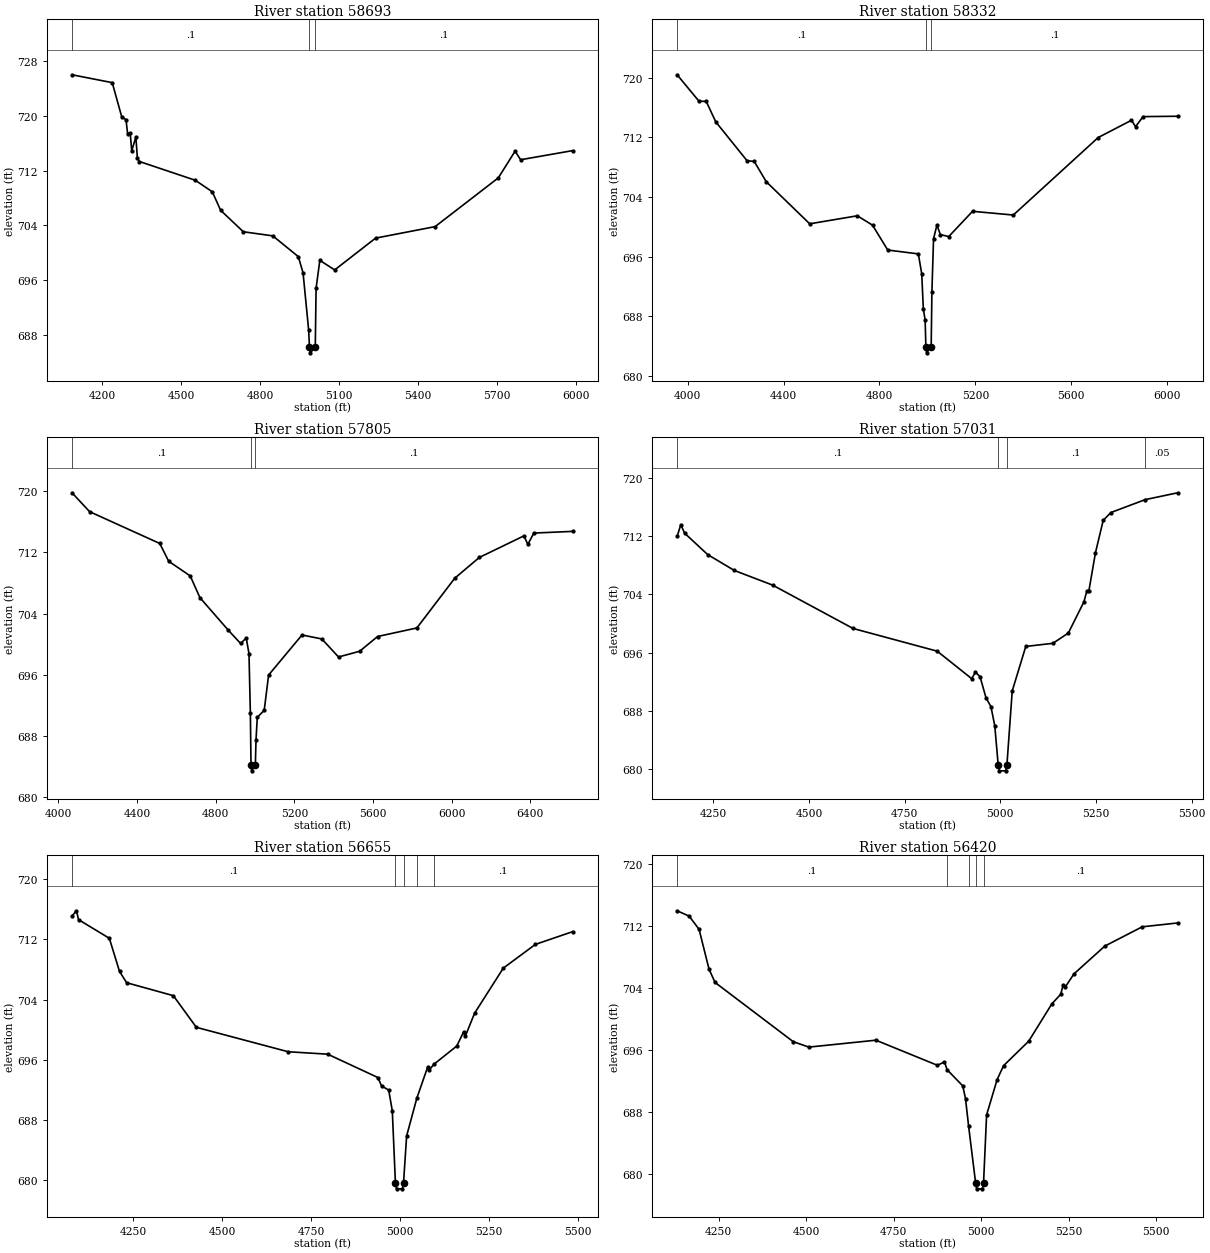
Type RM Length L Ch R = 1 ,58693   ,361,361,361
BEGIN DESCRIPTION:
SF PEREZ CREEK 74.0
END DESCRIPTION:
XS GIS Cut Line= 3
       1988427.6      13621487.4      1987682.81     13621914.48
      1986949.21     13622658.49
#Sta/Elev= 30
  4085.2  726.01  4238.1  724.86  4274.9  719.78  4290.7  719.45  4296.5  717.39
  4306.5  717.47  4312.3   714.9  4328.1  716.91  4333.8  713.78  4341.8  713.33
  4553.9  710.59  4618.7   708.9  4650.3   706.2  4736.6  703.06  4848.8  702.46
  4945.8  699.42  4963.8  697.04    4985   688.7  4988.1  686.16    4991  685.36
  5010.2  686.16  5013.3  694.81  5027.5  698.88    5084  697.48  5239.5  702.13
  5465.8  703.81  5706.2  710.94  5769.9  714.84  5791.1  713.59  5988.6  714.92
#Mann= 3 ,-1 , 0
  4085.2      .1       0  4988.1     .07       0  5010.2      .1       0
Bank Sta=4988.1,5010.2
XS Rating Curve= 0 ,0
Exp/Cntr=0.3,0.1

Type RM Length L Ch R = 1 ,58332   ,527,527,527
BEGIN DESCRIPTION:
SF PEREZ CREEK 73.0
END DESCRIPTION:
XS GIS Cut Line= 4
      1988255.99     13621331.11      1987714.35     13621369.31
      1987103.24     13622039.45      1986926.16     13622654.02
#Sta/Elev= 30
  3955.3  720.42  4046.5  716.87  4076.6  716.85  4116.7  714.09    4247  708.88
  4277.1  708.78  4327.2  706.06  4508.7   700.4  4707.4  701.48  4770.9  700.22
  4834.4  696.88  4962.1  696.36  4976.3  693.69    4983  688.97  4990.5  687.48
  4993.6  683.87  4996.5  683.07  5015.7  683.87  5018.8  691.29  5025.6   698.4
  5039.8  700.24    5054  698.95  5089.1  698.69  5188.4  702.08  5358.6  701.58
  5712.8  711.99  5851.8  714.31  5868.9  713.45  5900.1   714.8  6044.8  714.85
#Mann= 3 ,-1 , 0
  3955.3      .1       0  4993.6     .07       0  5015.7      .1       0
Bank Sta=4993.6,5015.7
XS Rating Curve= 0 ,0
Exp/Cntr=0.3,0.1

Type RM Length L Ch R = 1 ,57805   ,774,774,774
BEGIN DESCRIPTION:
SF PEREZ CREEK 72.0
END DESCRIPTION:
XS GIS Cut Line= 4
      1988203.96     13620893.61      1987672.69     13620949.17
      1986988.66     13621806.81       1986846.3     13622709.57
#Sta/Elev= 30
  4069.3   719.8  4158.7  717.33  4515.5  713.17  4560.9  710.84  4670.2  708.93
  4719.8  706.08  4862.4  701.87  4926.4  700.09  4955.2   700.8  4969.1  698.76
  4976.1  690.98  4979.4  684.23  4982.3  683.43  5001.5  684.23  5004.9   687.5
  5011.3  690.43  5046.5  691.34  5068.9  695.96  5238.7   701.2  5339.6  700.68
  5424.4  698.32  5531.7  699.07    5623     701  5822.7  702.12  6015.2  708.62
  6140.1  711.34  6366.8  714.16  6387.1  713.06  6417.4  714.53  6614.4  714.75
#Mann= 3 ,-1 , 0
  4069.3      .1       0  4979.4     .07       0  5001.5      .1       0
Bank Sta=4979.4,5001.5
XS Rating Curve= 0 ,0
Exp/Cntr=0.3,0.1

Type RM Length L Ch R = 1 ,57031   ,376,376,376
BEGIN DESCRIPTION:
SF PEREZ CREEK 71.0
END DESCRIPTION:
XS GIS Cut Line= 3
      1987784.57     13620702.08      1986992.95     13620707.29
      1986482.54     13620785.42
#Sta/Elev= 30
  4155.6  711.97  4165.2  713.58  4175.2  712.41  4235.2  709.48  4305.2  707.29
  4405.2  705.28  4615.2  699.33  4835.2  696.21  4925.2  692.44  4935.2  693.34
  4947.2  692.69  4962.7   689.8  4975.5  688.61  4985.6  685.97  4994.5  680.58
  4997.6  679.78  5014.1  679.78  5017.3  680.58  5031.2  690.75  5066.6  696.86
  5137.4  697.29  5177.8   698.7  5218.3  702.96  5226.4   704.5  5231.5   704.5
  5248.7  709.73  5268.9  714.17  5289.1  715.25  5378.7  717.02  5463.6  717.96
#Mann= 4 ,-1 , 0
  4155.6      .1       0  4994.5     .07       0  5017.3      .1       0
  5378.7     .05       0
Bank Sta=4994.5,5017.3
XS Rating Curve= 0 ,0
Exp/Cntr=0.3,0.1

Type RM Length L Ch R = 1 ,56655   ,235,235,235
BEGIN DESCRIPTION:
SF PEREZ CREEK 70.0
END DESCRIPTION:
XS GIS Cut Line= 3
      1987977.29     13620542.36      1987071.08     13620431.25
      1986581.48     13620479.86
#Sta/Elev= 30
  4079.2   715.1  4091.6   715.8  4097.6  714.62    4184  712.14  4212.5  707.74
  4232.6  706.23  4363.6  704.51  4428.2   700.3    4686  697.05  4796.8  696.73
  4937.9  693.62  4947.9  692.51  4968.1  691.95  4978.2  689.19  4986.9  679.62
  4990.1  678.82  5006.6  678.82  5009.7  679.62  5018.4  685.85  5047.1  690.89
  5077.2  694.98  5082.2  694.62  5094.5  695.37  5159.1  697.81  5178.1  699.66
  5183.1  699.12  5209.3  702.19  5289.7  708.17  5379.8  711.33  5484.2  713.02
#Mann= 5 ,-1 , 0
  4079.2      .1       0  4986.9     .07       0  5009.7      .1       0
  5047.1     .07       0  5094.5      .1       0
Bank Sta=4986.9,5009.7
XS Rating Curve= 0 ,0
Exp/Cntr=0.3,0.1

Type RM Length L Ch R = 1 ,56420   ,378,378,378
BEGIN DESCRIPTION:
Mapping XS d4a2bd08
END DESCRIPTION:
XS GIS Cut Line= 4
      1987946.08     13620486.81      1987439.14      13620250.7
      1986928.72     13620209.03      1986589.22     13620326.81
#Sta/Elev= 30
  4131.4  713.95  4165.7  713.26  4194.1  711.56  4222.5  706.42  4239.8   704.7
  4463.5  697.05    4508  696.36  4699.5  697.25  4875.4  694.01  4895.5  694.45
    4903  693.44  4947.8  691.35  4955.7  689.68  4964.3  686.21  4984.4  678.87
  4987.5  678.07    5004  678.07  5007.2  678.87  5015.9  687.61    5046  692.17
  5064.5  693.97  5136.2  697.12  5202.1  701.92  5227.9  703.19  5234.7   704.4
    5240  704.07  5265.8  705.82  5353.9   709.4  5460.7  711.88  5562.1  712.38
#Mann= 5 ,-1 , 0
  4131.4      .1       0    4903     .16       0  4964.3      .1       0
  4984.4     .07       0  5007.2      .1       0
Bank Sta=4984.4,5007.2
XS Rating Curve= 0 ,0
Exp/Cntr=0.3,0.1