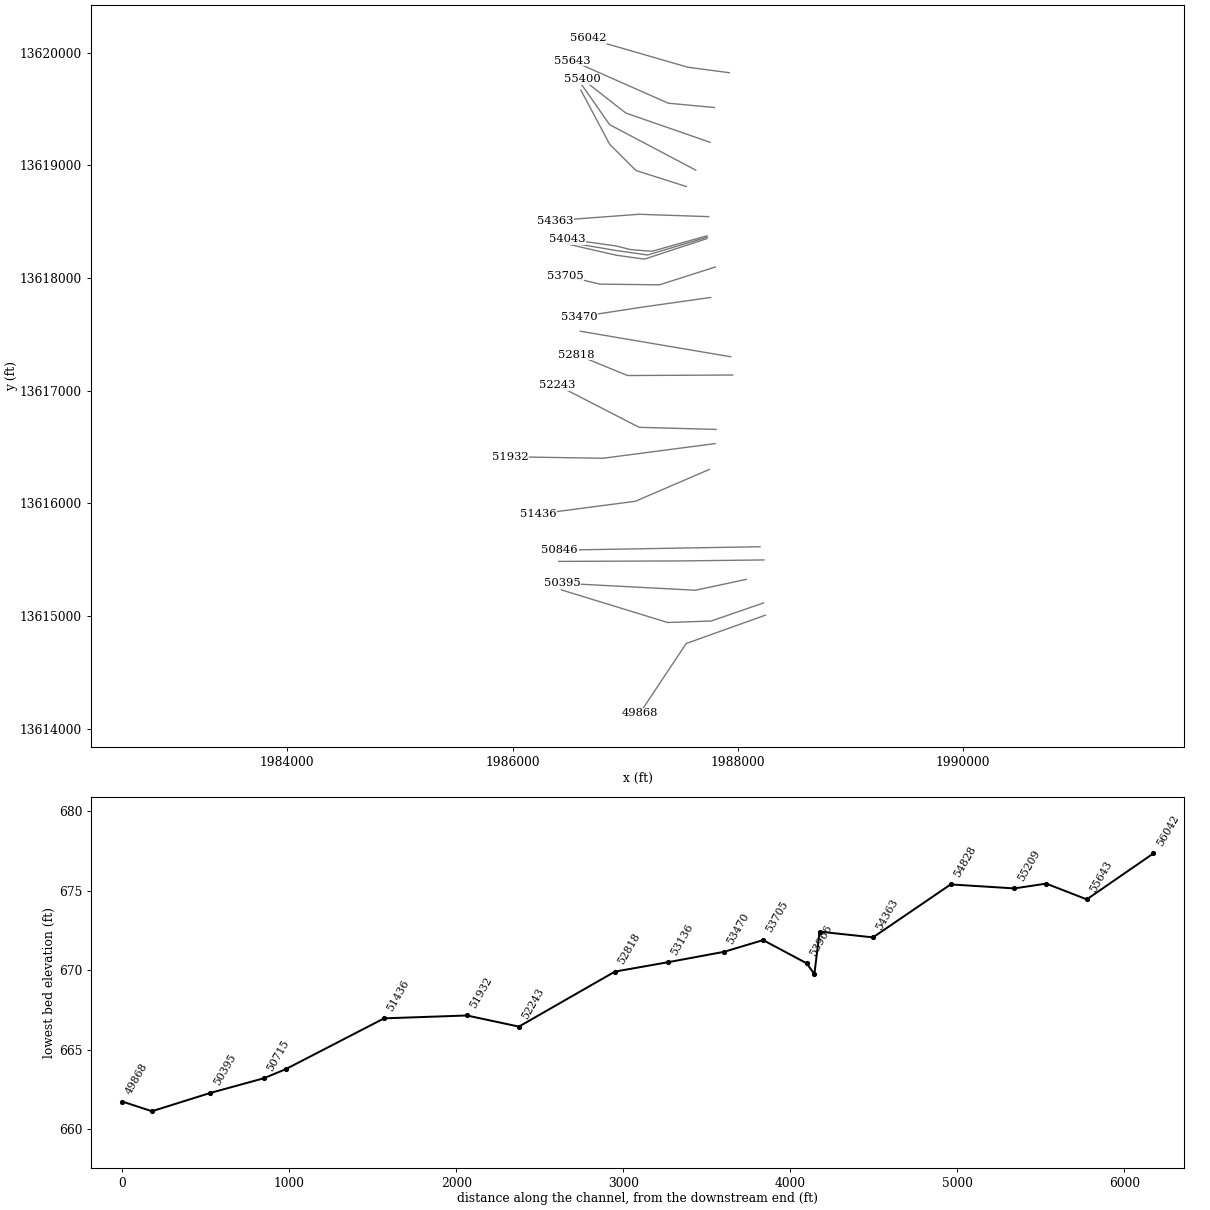
HEC-RAS study SF PEREZ CREEK.prj: SF PEREZ CREEK Base Level Engineering

--- SF PEREZ CREEK.g01 (geometry) --- (continued)

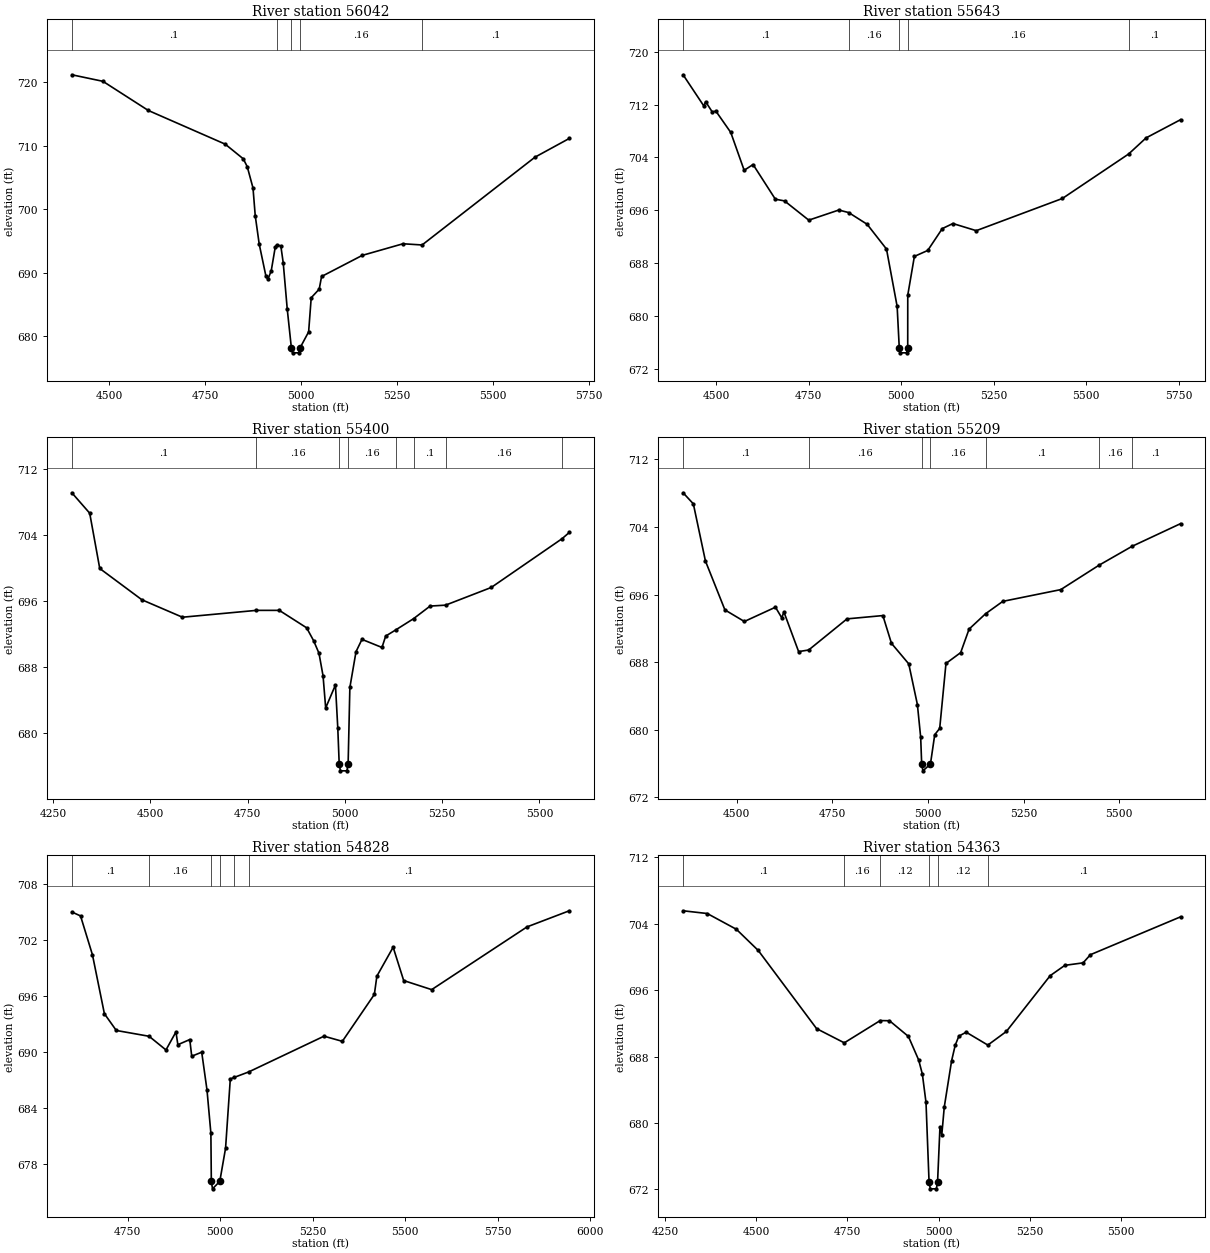
Type RM Length L Ch R = 1 ,56042   ,399,399,399
BEGIN DESCRIPTION:
SF PEREZ CREEK 69.0
END DESCRIPTION:
XS GIS Cut Line= 3
      1987925.24     13619823.61      1987557.19     13619872.22
      1986669.19     13620128.91
#Sta/Elev= 30
  4403.5   721.2  4484.4  720.17  4602.7  715.57  4802.9  710.26  4849.9  707.95
  4860.3  706.71  4875.3  703.35  4881.1  698.99  4891.5  694.49    4909  689.43
  4914.2  688.96  4922.8  690.29  4933.2  694.01    4937  694.38  4947.8   694.2
    4954  691.56  4964.4   684.3  4975.2  678.15  4978.4  677.35  4994.9  677.35
    4998  678.15  5020.2  680.66  5026.9  686.04  5047.7  687.39  5053.9  689.39
  5159.9  692.72    5266  694.55  5315.7  694.36  5609.8  708.21  5699.1  711.16
#Mann= 5 ,-1 , 0
  4403.5      .1       0    4937     .16       0  4975.2     .07       0
    4998     .16       0  5315.7      .1       0
Bank Sta=4975.2,4998
XS Rating Curve= 0 ,0
Exp/Cntr=0.3,0.1

Type RM Length L Ch R = 1 ,55643   ,243,243,243
BEGIN DESCRIPTION:
SF PEREZ CREEK 68.0
END DESCRIPTION:
XS GIS Cut Line= 3
      1987793.35     13619514.58      1987383.58     13619552.78
      1986529.81      13619929.9
#Sta/Elev= 30
  4410.5   716.5  4466.5  711.79  4471.5  712.43  4489.2  710.89  4499.2     711
  4539.4  707.78  4575.6  702.06  4599.7  702.93  4659.9  697.69  4684.7  697.43
  4750.3  694.52  4831.4  696.05  4858.1  695.67    4908   693.9  4960.4  690.15
  4989.2  681.48  4994.9  675.26  4998.1  674.46  5014.6  674.46  5017.8  675.26
  5017.9  683.18  5035.8  689.04  5071.9  689.94  5111.2  693.24  5139.9  694.01
  5203.1  692.93    5436   697.8    5615  704.52  5662.3  706.96  5755.4  709.71
#Mann= 5 ,-1 , 0
  4410.5      .1       0  4858.1     .16       0  4994.9     .07       0
  5017.8     .16       0    5615      .1       0
Bank Sta=4994.9,5017.8
XS Rating Curve= 0 ,0
Exp/Cntr=0.3,0.1

Type RM Length L Ch R = 1 ,55400   ,191,191,191
BEGIN DESCRIPTION:
Mapping XS d11cf1cf
END DESCRIPTION:
XS GIS Cut Line= 3
      1987755.11     13619205.55      1987005.11     13619465.97
      1986623.12     13619764.61
#Sta/Elev= 30
  4298.1   709.1    4344  706.63  4369.8  699.94  4478.2  696.15  4582.4  694.04
  4772.6  694.87  4831.4  694.87  4901.6  692.76  4919.4  691.22  4933.4  689.68
  4943.9  686.94  4950.6  683.06  4975.7  685.84  4981.7  680.67  4985.4  676.25
  4988.6  675.45  5005.1  675.45  5008.3  676.25  5012.8  685.54  5028.6  689.87
  5043.9  691.36  5095.3  690.38  5104.9  691.76  5130.6   692.5  5176.4  693.86
  5219.1  695.39  5258.7   695.5  5376.2  697.64  5558.2  703.54  5576.9   704.3
#Mann= 8 ,-1 , 0
  4298.1      .1       0  4772.6     .16       0  4985.4     .07       0
  5008.3     .16       0  5130.6     .12       0  5176.4      .1       0
  5258.7     .16       0  5558.2      .1       0
Bank Sta=4985.4,5008.3
XS Rating Curve= 0 ,0
Exp/Cntr=0.3,0.1

Type RM Length L Ch R = 1 ,55209   ,381,381,381
BEGIN DESCRIPTION:
Mapping XS 940e35e2
END DESCRIPTION:
XS GIS Cut Line= 3
      1987626.66     13618959.02      1986862.75     13619361.81
      1986612.72     13619719.49
#Sta/Elev= 30
  4360.3  708.03  4387.1  706.72  4418.7  699.96  4469.6  694.18  4520.4  692.81
  4601.7   694.5  4618.1  693.25  4623.8  693.93  4662.2  689.25  4688.5  689.44
  4788.7  693.12  4882.4  693.51  4904.8  690.23    4950   687.8  4972.6  682.99
  4981.2  679.11  4983.8  675.95    4987  675.15  5006.7  675.95  5017.9  679.42
  5030.9  680.17  5047.3  687.85  5085.7  689.13  5107.7  691.91  5150.6  693.72
  5195.8  695.19  5347.3  696.58  5446.7  699.45  5533.2  701.69  5660.3  704.38
#Mann= 7 ,-1 , 0
  4360.3      .1       0  4688.5     .16       0  4983.8     .07       0
  5006.7     .16       0  5150.6      .1       0  5446.7     .16       0
  5533.2      .1       0
Bank Sta=4983.8,5006.7
XS Rating Curve= 0 ,0
Exp/Cntr=0.3,0.1

Type RM Length L Ch R = 1 ,54828   ,465,465,465
BEGIN DESCRIPTION:
Mapping XS f053bb61
END DESCRIPTION:
XS GIS Cut Line= 4
      1987543.32     13618813.19      1987095.39     13618955.56
      1986862.75      13619188.2      1986606.03      13619670.4
#Sta/Elev= 30
  4598.8  704.96  4622.3  704.54  4654.5  700.39  4686.8   694.1    4719  692.31
  4807.7  691.69  4853.3  690.23  4880.3  692.15  4885.5  690.79  4917.7  691.34
    4923  689.56    4950  689.99  4964.3  685.95  4974.8  681.33    4976   676.2
  4979.2   675.4  4998.9   676.2  5014.5  679.74  5027.3  687.13  5037.9   687.3
  5076.9  687.88  5280.8   691.7  5330.3  691.15  5416.9  696.16  5423.7  698.11
  5467.7   701.2  5496.2  697.64  5571.9  696.67  5829.8  703.37  5944.1  705.09
#Mann= 6 ,-1 , 0
  4598.8      .1       0  4807.7     .16       0    4976     .07       0
  4998.9     .16       0  5037.9     .12       0  5076.9      .1       0
Bank Sta=4976,4998.9
XS Rating Curve= 0 ,0
Exp/Cntr=0.3,0.1

Type RM Length L Ch R = 1 ,54363   ,320,320,320
BEGIN DESCRIPTION:
SF PEREZ CREEK 67.0
END DESCRIPTION:
XS GIS Cut Line= 3
      1987741.22     13618545.83      1987123.16     13618566.67
      1986378.33     13618511.24
#Sta/Elev= 30
    4299  705.55  4365.3  705.22  4445.3  703.32  4505.3  700.77  4665.4  691.36
  4741.4  689.65    4840  692.33  4865.5  692.31  4917.4  690.42  4945.6  687.58
  4955.7  685.88  4965.7  682.47  4974.1  672.87  4977.5  672.07  4994.1  672.07
  4997.4  672.87    5004   679.5    5009  678.57  5015.8  681.91  5035.9  687.48
  5045.9  689.37    5056  690.46    5076  690.93  5135.4  689.38  5186.3  691.02
  5306.6  697.74  5346.8  698.98  5396.9  699.28  5416.9  700.26  5664.3  704.82
#Mann= 6 ,-1 , 0
    4299      .1       0  4741.4     .16       0    4840     .12       0
  4974.1     .07       0  4997.4     .12       0  5135.4      .1       0
Bank Sta=4974.1,4997.4
XS Rating Curve= 0 ,0
Exp/Cntr=0.3,0.1

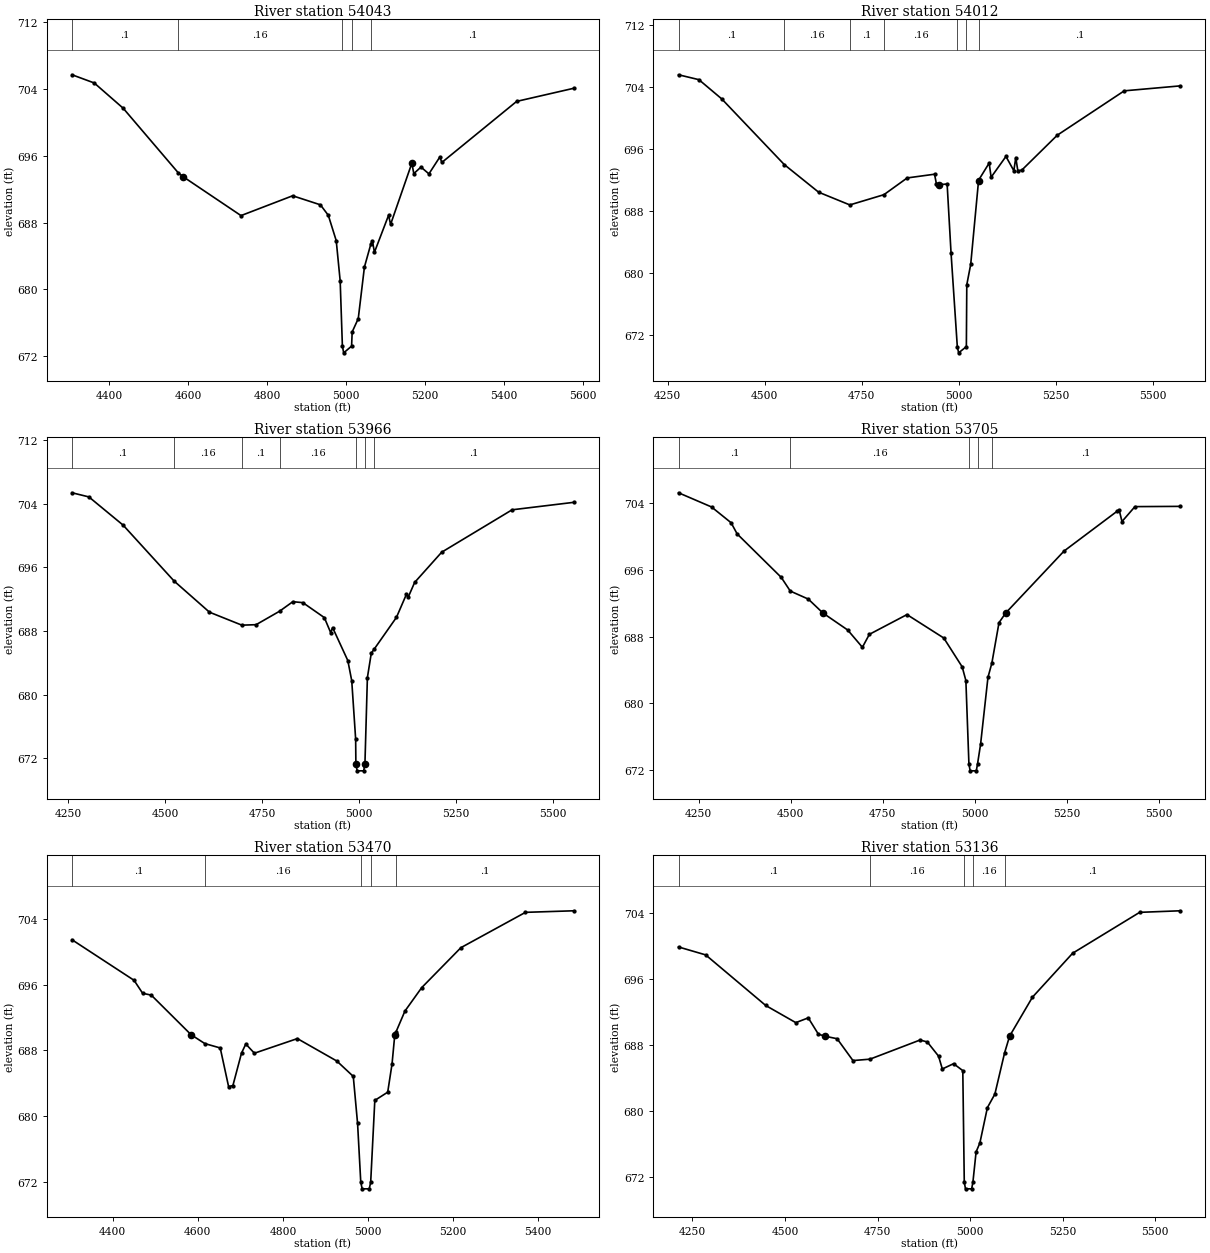
Type RM Length L Ch R = 1 ,54043   ,31,31,31
BEGIN DESCRIPTION:
SF PEREZ CREEK 66.0
END DESCRIPTION:
XS GIS Cut Line= 6
      1987724.97     13618374.99      1987243.65     13618239.66
      1987214.14     13618239.66      1987045.73     13618253.55
      1986922.47      13618284.8      1986481.52     13618347.29
#Sta/Elev= 30
  4305.3  705.66  4361.5  704.68  4434.8  701.66    4574  693.96  4586.6  693.48
  4733.2  688.83    4864   691.2  4934.3  690.12  4954.3  688.87  4974.4  685.84
  4984.4  681.03    4990  673.23  4993.3  672.43  5013.3  673.23  5014.8  674.93
  5030.2  676.52  5045.8  682.68  5062.2  685.45    5066   685.8  5071.2  684.45
    5107  688.87  5112.1  687.78  5165.9  695.09  5170.9  693.85    5189  694.63
  5209.2  693.82  5236.9  695.84  5241.9  695.18  5431.4  702.48  5576.3  704.05
#Mann= 5 ,-1 , 0
  4305.3      .1       0    4574     .16       0    4990     .07       0
  5013.3     .16       0  5062.2      .1       0
Bank Sta=4586.6,5165.9
XS Rating Curve= 0 ,0
Exp/Cntr=0.3,0.1

Type RM Length L Ch R = 1 ,54012   ,46,46,46
BEGIN DESCRIPTION:
Mapping XS 96f5bb7e
END DESCRIPTION:
XS GIS Cut Line= 4
      1987731.53     13618364.67      1987198.51     13618204.93
      1986910.32      13618246.6      1986472.77     13618321.26
#Sta/Elev= 30
  4278.2  705.61  4330.6  704.98  4389.4   702.5  4550.4  694.03  4638.8  690.47
  4719.1  688.83  4806.8  690.15  4866.7  692.31  4937.1  692.79  4942.1   691.5
  4949.3  691.44  4969.5  691.53  4979.6  682.62  4995.7  670.56  4999.1  669.76
    5019  670.56  5020.1  678.54  5030.2  681.17  5050.4  691.97  5051.5   692.1
  5077.7  694.23  5082.7   692.4  5120.9  695.08  5141.2  693.24  5146.2  694.94
  5151.5  693.22  5161.7  693.32    5253  697.82  5425.4  703.54  5569.7  704.18
#Mann= 7 ,-1 , 0
  4278.2      .1       0  4550.4     .16       0  4719.1      .1       0
  4806.8     .16       0  4995.7     .07       0    5019     .16       0
  5051.5      .1       0
Bank Sta=4949.3,5050.4
XS Rating Curve= 0 ,0
Exp/Cntr=0.3,0.1

Type RM Length L Ch R = 1 ,53966   ,261,261,261
BEGIN DESCRIPTION:
Mapping XS d0c0986a
END DESCRIPTION:
XS GIS Cut Line= 4
      1987726.27     13618350.76      1987170.73     13618168.48
      1986920.73      13618203.2      1986474.52     13618305.64
#Sta/Elev= 30
  4259.3  705.39  4302.7  704.87  4391.1  701.32  4522.7  694.29  4613.9  690.38
  4697.5  688.75  4734.2  688.81  4794.7   690.5    4829   691.7  4854.9  691.58
  4910.3   689.7  4926.6  687.82  4931.7  688.44  4970.9   684.3    4981  681.77
  4991.1  674.43  4991.7  671.24  4995.1  670.44  5011.7  670.44    5015  671.24
  5021.4  682.16  5031.5  685.24  5039.4  685.77  5096.4  689.73  5122.2  692.64
  5127.3  692.33  5143.3  694.12  5213.1  697.92  5394.8  703.25  5554.2  704.19
#Mann= 7 ,-1 , 0
  4259.3      .1       0  4522.7     .16       0  4697.5      .1       0
  4794.7     .16       0  4991.7     .07       0    5015     .16       0
  5039.4      .1       0
Bank Sta=4991.7,5015
XS Rating Curve= 0 ,0
Exp/Cntr=0.3,0.1

Type RM Length L Ch R = 1 ,53705   ,235,235,235
BEGIN DESCRIPTION:
Mapping XS c8acb224
END DESCRIPTION:
XS GIS Cut Line= 4
      1987800.94      13618098.6      1987303.98     13617940.18
      1986776.64     13617946.69      1986470.68     13618018.29
#Sta/Elev= 30
  4195.2  705.25  4284.8  703.55  4337.9  701.66  4354.4  700.32  4474.3   695.1
  4498.8  693.46  4547.7   692.5 4587.41690.8313  4654.8  688.79  4694.7  686.72
  4713.6  688.27  4815.8  690.64  4915.8  687.83  4965.8  684.37  4975.8  682.73
  4984.1   672.7  4987.5   671.9  5004.1   671.9  5007.4   672.7  5015.8   675.1
  5035.8  683.11  5046.4  684.82  5065.8  689.67 5084.02690.8317  5242.5  698.26
  5387.4  703.06  5392.6  703.13  5399.9   701.8  5435.1  703.59  5558.4  703.62
#Mann= 5 ,-1 , 0
  4195.2      .1       0  4498.8     .16       0  4984.1     .07       0
  5007.4     .16       0  5046.4      .1       0
Bank Sta=4587.41,5084.02
XS Rating Curve= 0 ,0
Exp/Cntr=0.3,0.1

Type RM Length L Ch R = 1 ,53470   ,334,334,334
BEGIN DESCRIPTION:
SF PEREZ CREEK 65.0
END DESCRIPTION:
XS GIS Cut Line= 3
      1987759.29      13617828.2      1987146.43     13617741.39
      1986592.61     13617656.32
#Sta/Elev= 30
  4304.5  701.46  4450.2  696.53  4470.4  694.95  4490.6  694.73 4584.24689.9105
  4616.6  688.83  4652.7   688.3  4672.4  683.59  4682.5  683.73  4702.7  687.67
  4712.8  688.78    4733  687.66    4834  689.44  4926.7  686.71  4965.4  684.84
  4975.5  679.11    4983  671.96  4986.3  671.16  5002.9  671.16  5006.3  671.96
    5016  681.92  5046.3  682.92  5056.5  686.36 5062.95689.9126  5065.4   690.2
  5086.8  692.79  5126.2  695.64  5218.3   700.5  5370.1   704.8  5483.8  704.99
#Mann= 5 ,-1 , 0
  4304.5      .1       0  4616.6     .16       0    4983     .07       0
  5006.3     .16       0  5065.4      .1       0
Bank Sta=4584.24,5062.95
XS Rating Curve= 0 ,0
Exp/Cntr=0.3,0.1

Type RM Length L Ch R = 1 ,53136   ,318,318,318
BEGIN DESCRIPTION:
Mapping XS 9ac15d84
END DESCRIPTION:
XS GIS Cut Line= 2
      1987937.21     13617301.72      1986601.29     13617528.29
#Sta/Elev= 30
  4212.5  699.85  4285.7  698.89    4448  692.75  4529.2  690.67  4562.8  691.25
    4590  689.28 4607.04689.0336  4640.7  688.72  4683.5  686.07  4729.4  686.24
  4864.5  688.56  4884.2  688.33  4914.6  686.61  4924.8  685.05  4955.2  685.69
  4980.1  684.85  4984.1  671.31  4987.4  670.51    5004  670.51  5007.4  671.31
    5016  674.99  5026.2  676.07  5046.5  680.36  5066.7     682    5093  687.01
 5106.49689.0332  5168.2  693.76  5276.7  699.09  5457.7  704.05  5567.5  704.24
#Mann= 5 ,-1 , 0
  4212.5      .1       0  4729.4     .16       0  4984.1     .07       0
  5007.4     .16       0    5093      .1       0
Bank Sta=4607.04,5106.49
XS Rating Curve= 0 ,0
Exp/Cntr=0.3,0.1

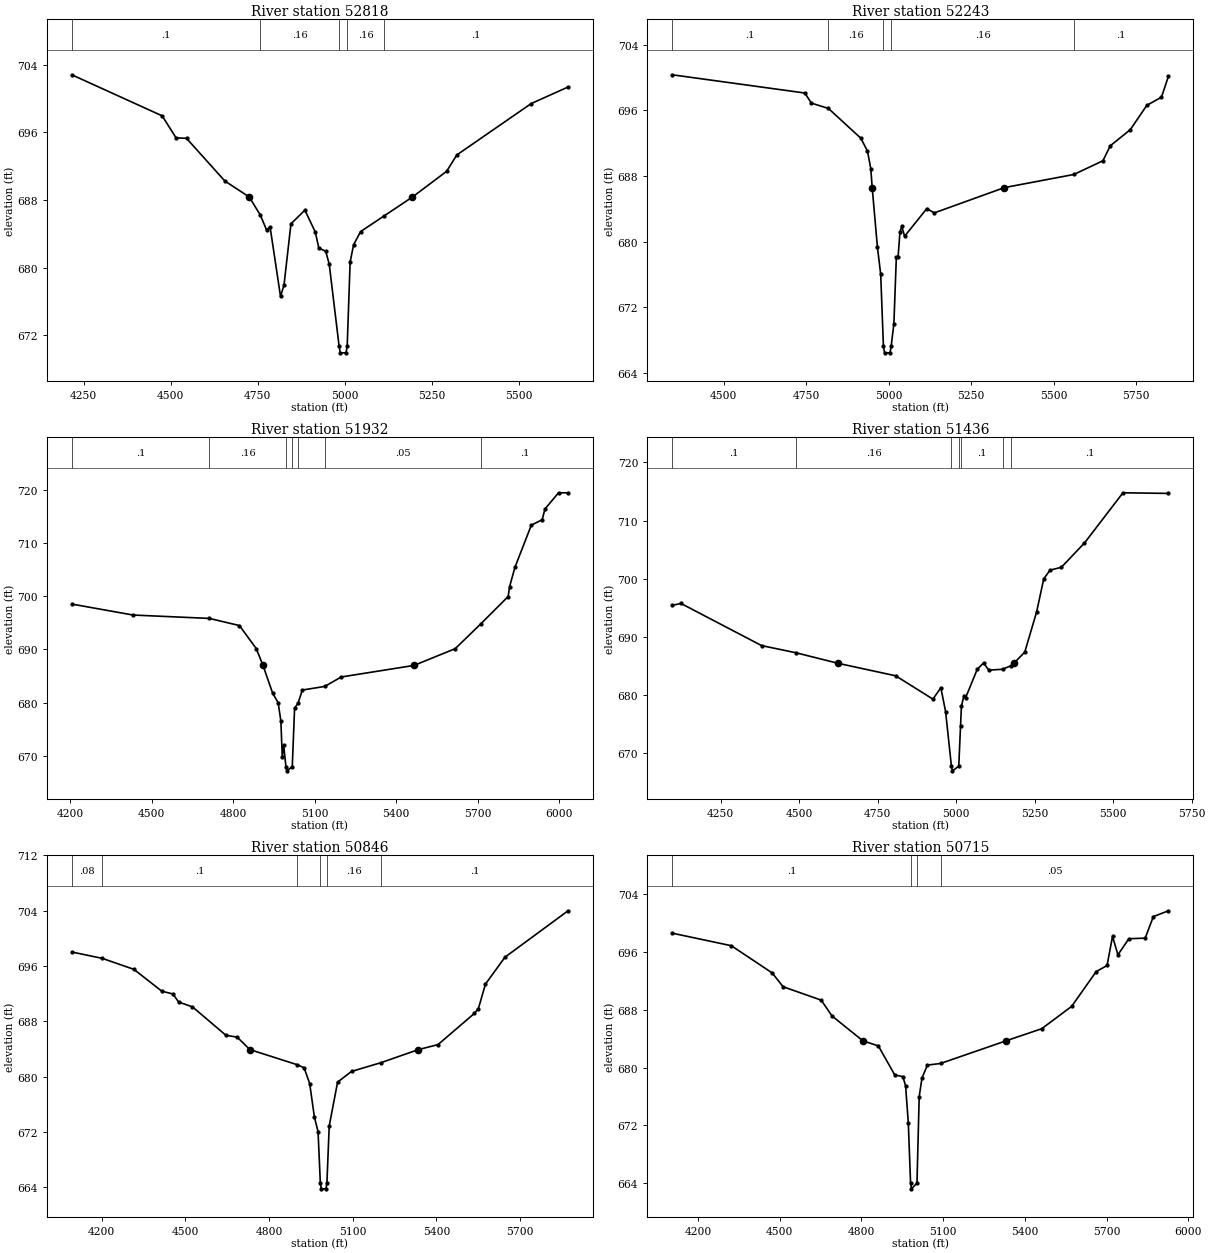
Type RM Length L Ch R = 1 ,52818   ,575,575,575
BEGIN DESCRIPTION:
SF PEREZ CREEK 64.0
END DESCRIPTION:
XS GIS Cut Line= 3
      1987954.59      13617139.4      1987021.43     13617135.06
      1986565.73     13617321.67
#Sta/Elev= 30
  4216.2  702.83  4475.8  697.97  4515.8  695.36  4545.8  695.31  4655.8  690.26
 4726.02688.3637  4757.6  686.24  4775.8  684.46  4785.8  684.84  4815.8   676.6
  4825.8  677.92  4845.8  685.19  4885.8  686.81  4915.8  684.21  4925.8  682.33
  4945.8  681.93  4955.8   680.4  4984.1  670.72  4987.5  669.92  5004.1  669.92
  5007.4  670.72  5015.8  680.66  5025.8  682.71  5045.8  684.27  5113.6  686.13
 5194.87688.3638  5292.9   691.4  5322.3  693.34  5535.9  699.42  5641.8  701.38
#Mann= 5 ,-1 , 0
  4216.2      .1       0  4757.6     .16       0  4984.1     .07       0
  5007.4     .16       0  5113.6      .1       0
Bank Sta=4726.02,5194.87
XS Rating Curve= 0 ,0
Exp/Cntr=0.3,0.1

Type RM Length L Ch R = 1 ,52243   ,311,311,311
BEGIN DESCRIPTION:
SF PEREZ CREEK 63.0
END DESCRIPTION:
XS GIS Cut Line= 3
      1987807.03     13616656.54        1987125.       13616675.
      1986393.55     13617050.75
#Sta/Elev= 30
  4343.3  700.32  4745.5   698.1  4765.5  696.87  4817.1  696.22  4915.5  692.59
  4935.5  691.03  4945.5   688.9 4949.83686.5807  4965.6  679.35  4975.6  676.02
  4983.9  667.26  4987.3  666.46  5003.9  666.46  5007.3  667.26  5015.6  670.02
  5023.1  678.16  5028.4  678.16  5033.9  681.15  5039.5  681.86  5048.1  680.66
  5115.5  684.03    5138   683.5 5350.63 686.582  5561.3  688.18  5649.4  689.85
  5671.6  691.67  5732.5  693.64  5782.5   696.6  5826.9  697.59  5847.9  700.13
#Mann= 5 ,-1 , 0
  4343.3      .1       0  4817.1     .16       0  4983.9     .03       0
  5007.3     .16       0  5561.3      .1       0
Bank Sta=4949.83,5350.63
XS Rating Curve= 0 ,0
Exp/Cntr=0.3,0.1

Type RM Length L Ch R = 1 ,51932   ,496,496,496
BEGIN DESCRIPTION:
SF PEREZ CREEK 62.0
END DESCRIPTION:
XS GIS Cut Line= 3
      1987798.37     13616530.68      1986804.41     13616400.46
      1985979.86     13616413.48
#Sta/Elev= 30
  4205.7  698.51    4431  696.45  4712.4  695.81    4823  694.47  4884.8  690.14
 4909.69686.9778  4945.3  681.75  4965.5  679.97  4975.6  676.48  4980.7  669.67
  4985.7  672.06  4994.1  667.96  4997.5  667.16  5017.5  667.96    5026  678.97
  5038.4  679.82  5054.5  682.35  5137.3  683.03  5197.5   684.8 5465.72686.9774
  5617.6  690.13    5711  694.76  5812.4  699.93  5817.6   701.8  5837.6  705.46
  5897.6  713.34  5937.7  714.37  5947.7  716.37  5997.7  719.42  6032.8  719.43
#Mann= 7 ,-1 , 0
  4205.7      .1       0  4712.4     .16       0  4994.1     .07       0
  5017.5     .16       0  5038.4      .1       0  5137.3     .05       0
    5711      .1       0
Bank Sta=4909.69,5465.72
XS Rating Curve= 0 ,0
Exp/Cntr=0.3,0.1

Type RM Length L Ch R = 1 ,51436   ,590,590,590
BEGIN DESCRIPTION:
SF PEREZ CREEK 61.0
END DESCRIPTION:
XS GIS Cut Line= 3
      1987746.29     13616300.65      1987090.87     13616018.52
      1986231.52     13615905.67
#Sta/Elev= 30
  4095.6  695.42  4123.4  695.76  4380.5  688.51  4490.5  687.27 4623.52685.4696
  4807.3  683.32    4926  679.31  4951.3  681.27  4966.4  677.16  4984.9  667.78
  4988.3  666.98  5008.3  667.78    5014  674.71  5016.8  678.11    5025  679.93
  5030.1  679.54  5067.2  684.44  5087.4  685.53  5103.8  684.29  5147.7  684.44
  5175.6  685.08 5183.72  685.47  5218.5  687.39  5256.2  694.29    5279     700
  5299.2  701.48    5335  701.97  5408.7  706.15  5531.2  714.78  5675.9  714.67
#Mann= 7 ,-1 , 0
  4095.6      .1       0  4490.5     .16       0  4984.9     .07       0
  5008.3     .16       0    5014      .1       0  5147.7     .05       0
  5175.6      .1       0
Bank Sta=4623.52,5183.72
XS Rating Curve= 0 ,0
Exp/Cntr=0.3,0.1

Type RM Length L Ch R = 1 ,50846   ,131,131,131
BEGIN DESCRIPTION:
Mapping XS 25c89fd8
END DESCRIPTION:
XS GIS Cut Line= 2
      1988197.67     13615614.87      1986419.03     13615584.51
#Sta/Elev= 30
    4093  698.03  4202.1  697.11  4315.7  695.52  4415.7  692.36  4455.7  691.96
  4475.7   690.8  4525.7  690.09  4645.7  685.98  4685.8  685.72 4731.43683.9149
  4901.2  681.73  4925.8  681.28  4945.8  679.01  4962.6  674.17  4975.8  672.06
    4984  664.58  4987.5  663.78  5004.1  663.78  5007.5  664.58  5015.8  672.87
  5045.8  679.21  5095.8  680.76    5201  682.02 5335.56 683.915  5405.9  684.64
  5535.9  689.14  5550.5  689.84  5575.9  693.39  5645.9  697.28  5871.9  703.99
#Mann= 6 ,-1 , 0
    4093     .08       0  4202.1      .1       0  4901.2     .16       0
    4984     .07       0  5007.5     .16       0    5201      .1       0
Bank Sta=4731.43,5335.56
XS Rating Curve= 0 ,0
Exp/Cntr=0.3,0.1

Type RM Length L Ch R = 1 ,50715   ,320,320,320
BEGIN DESCRIPTION:
SF PEREZ CREEK 60.0
END DESCRIPTION:
XS GIS Cut Line= 3
      1988232.38     13615497.69      1987516.22     13615489.01
      1986409.74     13615484.67
#Sta/Elev= 30
  4104.6  698.63    4322  696.89    4472  693.12    4512  691.21    4652  689.35
    4692  687.15 4805.32683.7103    4862  683.01    4922     679    4952  678.75
    4962  677.49    4972  672.35  4980.3  664.01  4983.7  663.21  5003.8  664.01
    5012  675.98    5022  678.52    5042  680.35  5090.7  680.58 5330.53683.7103
    5462  685.39    5572  688.49    5662   693.3    5702  694.15    5722  698.18
    5742  695.63    5782  697.86    5842  697.94    5872  700.92  5927.3  701.73
#Mann= 4 ,-1 , 0
  4104.6      .1       0  4980.3     .07       0  5003.8      .1       0
  5090.7     .05       0
Bank Sta=4805.32,5330.53
XS Rating Curve= 0 ,0
Exp/Cntr=0.3,0.1

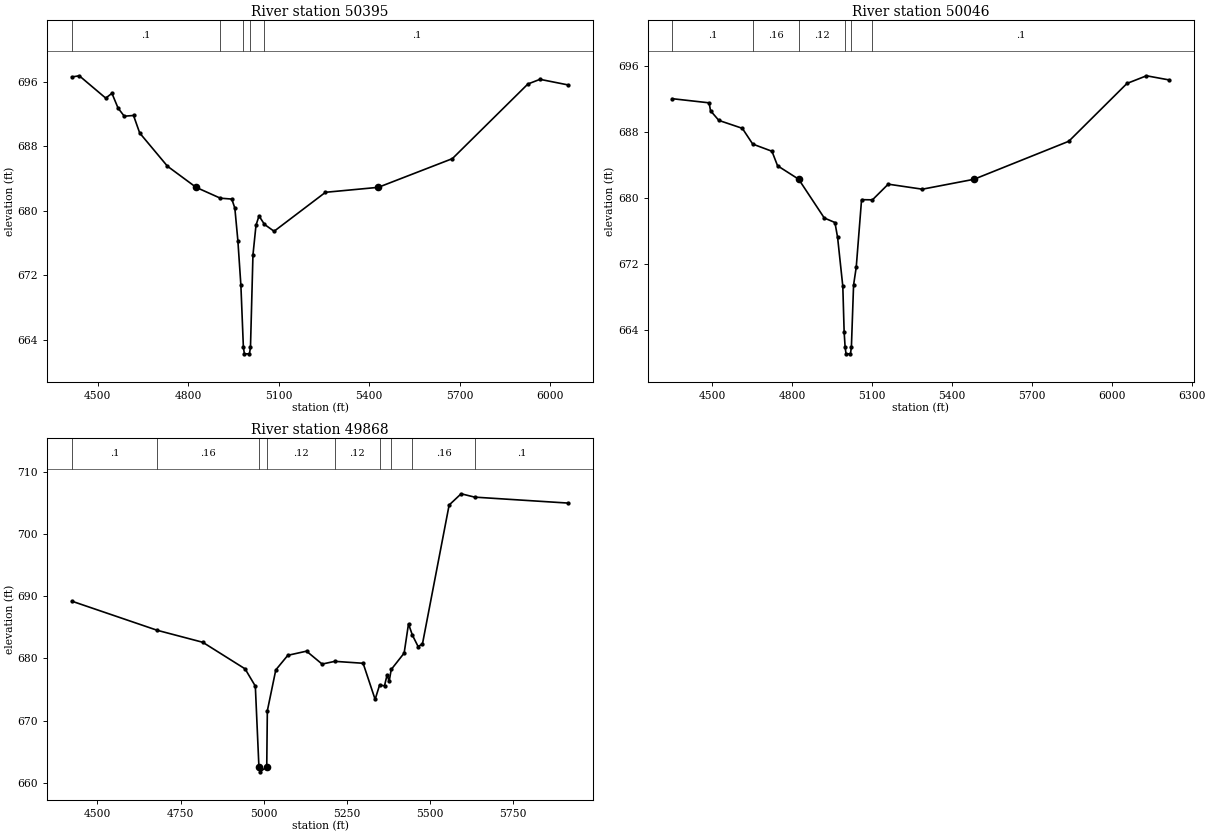
Type RM Length L Ch R = 1 ,50395   ,349,349,349
BEGIN DESCRIPTION:
SF PEREZ CREEK 59.0
END DESCRIPTION:
XS GIS Cut Line= 3
      1988075.05     13615325.01      1987624.73     13615228.59
      1986441.28      13615290.6
#Sta/Elev= 30
  4414.8   696.6  4439.6  696.75  4527.3  693.98  4547.8  694.58  4568.2  692.74
  4588.7  691.74  4619.4  691.83  4639.8  689.66  4731.9  685.54  4826.8682.9246
  4907.1  681.58  4945.1  681.47  4955.2  680.34  4965.2  676.33  4975.2  670.79
  4983.5  663.09  4986.9  662.29  5003.5  662.29    5007  663.09  5015.2  674.54
  5025.3  678.23  5035.3  679.38  5053.4  678.33  5085.3  677.48  5255.6  682.31
 5430.51682.9244  5676.1  686.48  5926.5  695.73  5966.5  696.31  6060.4  695.61
#Mann= 5 ,-1 , 0
  4414.8      .1       0  4907.1     .12       0  4983.5     .07       0
    5007     .12       0  5053.4      .1       0
Bank Sta=4826.8,5430.51
XS Rating Curve= 0 ,0
Exp/Cntr=0.3,0.1

Type RM Length L Ch R = 1 ,50046   ,178,178,178
BEGIN DESCRIPTION:
Mapping XS 31f8d5fc
END DESCRIPTION:
XS GIS Cut Line= 4
      1988228.04     13615115.75      1987763.61     13614955.15
      1987377.33     13614942.13      1986434.36     13615231.57
#Sta/Elev= 30
  4350.4  692.07  4488.1  691.57  4493.4  690.61  4524.6  689.44  4612.8  688.48
  4651.8  686.57    4724   685.7  4745.1  683.94  4824.3  682.31 4824.52 682.299
  4920.5  677.61  4960.5  677.06  4970.5  675.26  4990.1  669.32  4995.1  663.78
  4998.8  661.94  5002.2  661.14  5018.8  661.14  5022.3  661.94  5030.5  669.48
  5040.5  671.64  5060.5  679.83  5101.4  679.81  5160.6  681.71  5288.7   681.1
 5482.36682.2991  5838.6  686.91  6057.1  693.92  6130.4  694.85  6214.7  694.35
#Mann= 6 ,-1 , 0
  4350.4      .1       0  4651.8     .16       0  4824.3     .12       0
  4998.8     .07       0  5022.3     .12       0  5101.4      .1       0
Bank Sta=4824.52,5482.36
XS Rating Curve= 0 ,0
Exp/Cntr=0.3,0.1

Type RM Length L Ch R = 1 ,49868   ,424,424,424
BEGIN DESCRIPTION:
Mapping XS c50c1edb
END DESCRIPTION:
XS GIS Cut Line= 3
      1988245.43     13615007.25      1987542.26      13614755.5
      1987129.37     13614135.23
#Sta/Elev= 30
  4423.3  689.23    4680  684.54  4816.8  682.61    4944  678.33  4974.8  675.55
  4985.6  662.55    4989  661.75  5009.1  662.55  5010.9  671.58  5036.3  678.16
  5072.4  680.51  5128.6  681.18  5175.5   679.1  5213.7  679.54  5298.7  679.23
  5334.8  673.41  5348.1  675.71    5363  675.61  5370.9  677.38  5376.9   676.3
  5383.2  678.23    5422  680.87  5435.1  685.58  5446.6  683.78    5464  681.92
  5477.1  682.36  5557.2  704.71  5593.3  706.52  5633.9  705.98  5915.3  705.02
#Mann= 9 ,-1 , 0
  4423.3      .1       0    4680     .16       0  4985.6     .07       0
  5009.1     .12       0  5213.7     .12       0  5348.1     .16       0
  5383.2     .12       0  5446.6     .16       0  5633.9      .1       0
Bank Sta=4985.6,5009.1
XS Rating Curve= 0 ,0
Exp/Cntr=0.3,0.1