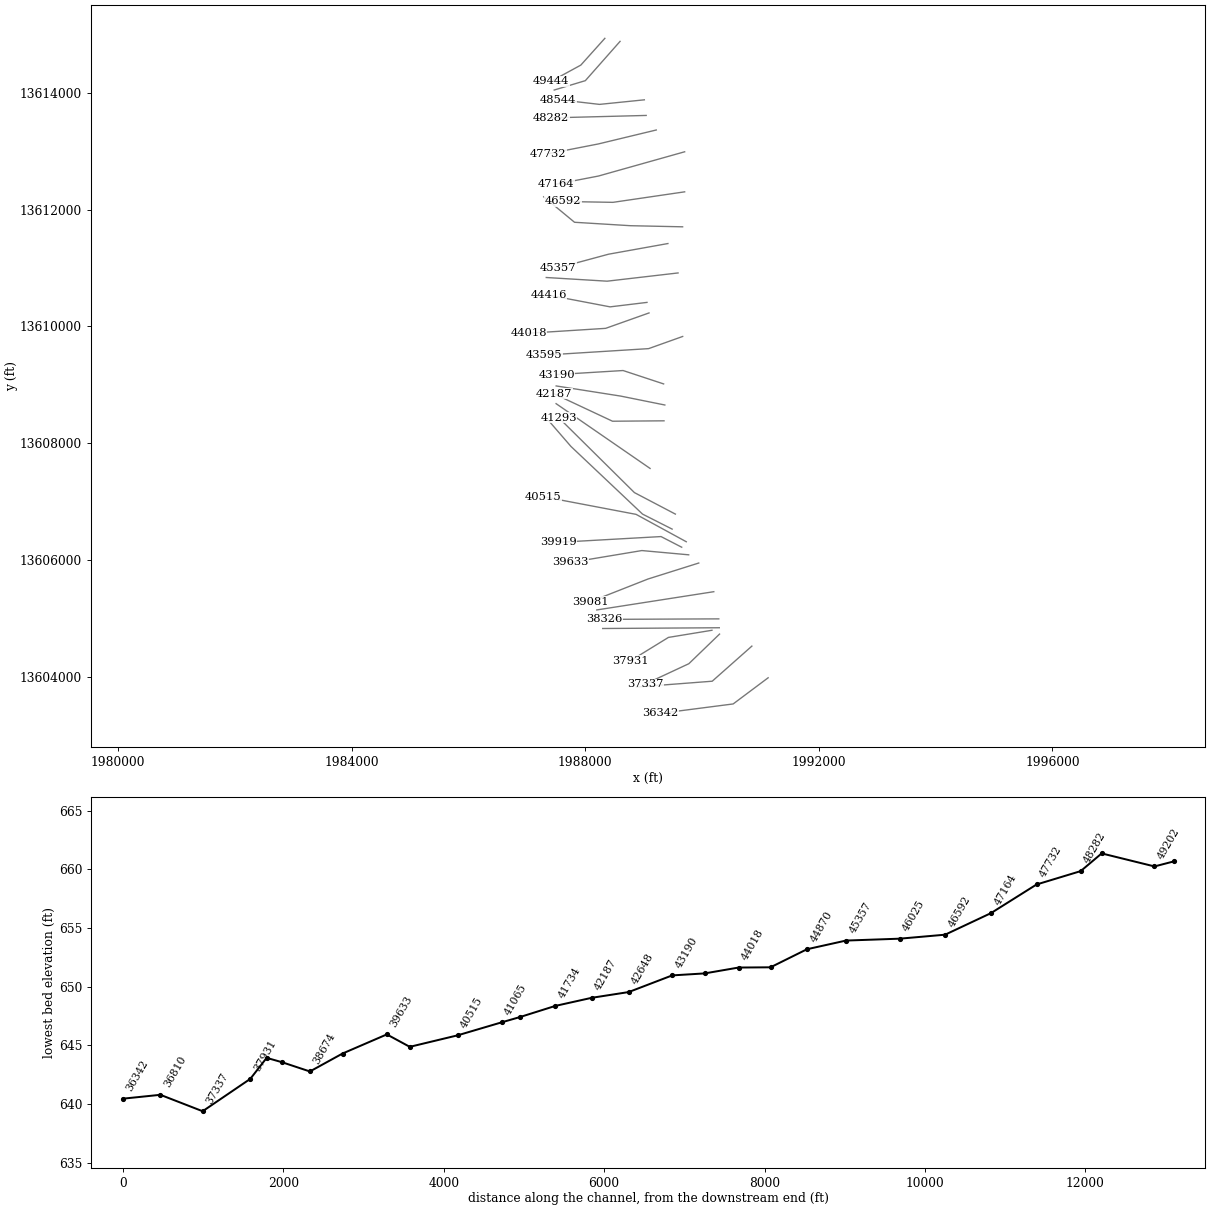
HEC-RAS study SF PEREZ CREEK.prj: SF PEREZ CREEK Base Level Engineering

--- SF PEREZ CREEK.g01 (geometry) --- (continued)

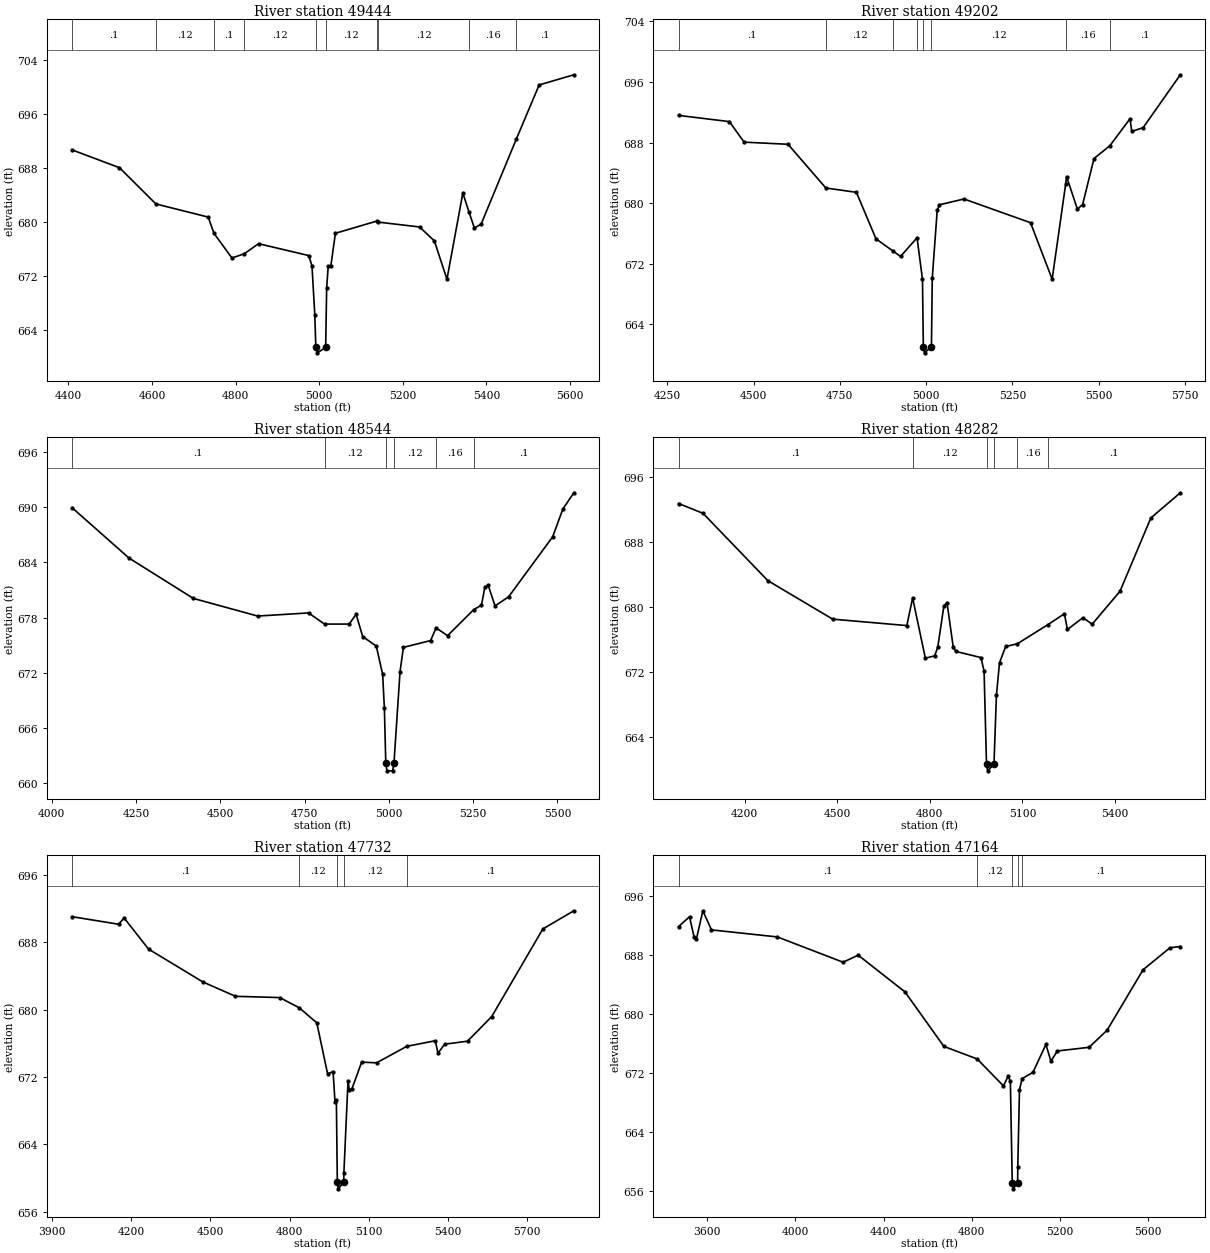
Type RM Length L Ch R = 1 ,49444   ,242,242,242
BEGIN DESCRIPTION:
SF PEREZ CREEK 58.0
END DESCRIPTION:
XS GIS Cut Line= 3
       1988336.5     13614933.42        1987925.       13614475.
      1987412.08     13614195.62
#Sta/Elev= 30
    4409  690.68  4522.3  688.05  4609.5  682.69  4734.6  680.75  4748.5  678.34
  4791.4   674.7    4821  675.34    4855  676.82  4975.3  675.06  4982.8  673.52
  4989.5  666.33    4992  661.49  4995.4  660.69  5015.5  661.49  5017.9  670.32
  5021.7  673.53  5027.9  673.53  5038.8  678.36  5137.9  680.16  5140.9  680.01
  5240.1  679.29  5275.5  677.23  5305.6  671.56  5343.6  684.31  5358.3   681.5
  5371.2  679.13  5387.3  679.71  5471.9  692.34  5526.1  700.28  5609.1  701.78
#Mann= 10 ,-1 , 0
    4409      .1       0  4609.5     .12       0  4748.5      .1       0
    4821     .12       0    4992     .07       0  5015.5     .12       0
  5137.9      .1       0  5140.9     .12       0  5358.3     .16       0
  5471.9      .1       0
Bank Sta=4992,5015.5
XS Rating Curve= 0 ,0
Exp/Cntr=0.3,0.1

Type RM Length L Ch R = 1 ,49202   ,658,658,658
BEGIN DESCRIPTION:
SF PEREZ CREEK 57.0
END DESCRIPTION:
XS GIS Cut Line= 3
      1988596.92     13614881.33      1988002.33     13614208.62
      1987469.24     13614048.26
#Sta/Elev= 30
  4282.4  691.59  4429.9  690.77  4472.5  688.06  4599.7  687.78  4709.4  682.01
    4798  681.44  4854.8   675.3  4904.9  673.66  4925.9  672.98  4973.8  675.45
  4989.5  669.95    4992  661.06  4995.4  660.26  5015.5  661.06  5017.9  670.14
  5032.2  679.07  5038.8   679.8  5109.9  680.56  5302.7  677.43  5365.4  669.98
  5404.7  682.58  5407.2  683.52  5438.5  679.22  5453.7  679.83  5486.7   685.9
  5532.7  687.59    5591  691.14  5596.2  689.47  5629.2  689.98  5736.9  696.95
#Mann= 8 ,-1 , 0
  4282.4      .1       0  4709.4     .12       0  4904.9      .1       0
  4973.8     .12       0    4992     .07       0  5015.5     .12       0
  5404.7     .16       0  5532.7      .1       0
Bank Sta=4992,5015.5
XS Rating Curve= 0 ,0
Exp/Cntr=0.3,0.1

Type RM Length L Ch R = 1 ,48544   ,262,262,262
BEGIN DESCRIPTION:
SF PEREZ CREEK 56.0
END DESCRIPTION:
XS GIS Cut Line= 3
      1989012.76      13613880.5      1988244.52     13613802.37
      1987532.68     13613884.84
#Sta/Elev= 30
  4060.1  689.95  4228.7  684.49  4419.7   680.1  4610.7  678.18  4761.7  678.52
  4809.1  677.31  4882.2  677.31  4902.9  678.37  4922.4  675.95  4962.7  674.92
  4981.6  671.84  4986.7  668.17  4990.9  662.17  4994.6  661.37  5011.4  661.37
  5015.1  662.17  5033.2  672.15  5043.2  674.78  5123.8  675.52  5140.2   676.9
  5174.1  676.05  5251.8  678.88  5274.8  679.36  5284.8  681.32  5294.9  681.51
    5315  679.28  5355.3  680.27  5486.2   686.8  5516.4  689.82  5548.9  691.57
#Mann= 6 ,-1 , 0
  4060.1      .1       0  4809.1     .12       0  4990.9     .07       0
  5015.1     .12       0  5140.2     .16       0  5251.8      .1       0
Bank Sta=4990.9,5015.1
XS Rating Curve= 0 ,0
Exp/Cntr=0.3,0.1

Type RM Length L Ch R = 1 ,48282   ,550,550,550
BEGIN DESCRIPTION:
Mapping XS ea8739a7
END DESCRIPTION:
XS GIS Cut Line= 2
      1989044.17     13613613.13       1987419.6     13613571.47
#Sta/Elev= 30
  3986.3  692.71  4065.5  691.51  4275.6  683.23  4485.6   678.5  4725.7  677.71
  4744.4  681.11  4785.7   673.7  4815.7  673.99  4825.7  675.03  4845.7  680.13
  4855.8  680.53  4875.8   675.1  4884.7  674.53  4965.8  673.78  4975.8  672.12
  4983.7  660.66  4987.4  659.86  5007.9  660.66  5015.8  669.14  5025.8  673.14
  5045.8  675.14  5083.5  675.47  5181.8  677.81  5235.9  679.16  5245.9  677.23
  5295.9  678.68  5325.9  677.88  5415.9  681.92    5516  690.94  5611.4  694.03
#Mann= 6 ,-1 , 0
  3986.3      .1       0  4744.4     .12       0  4983.7     .07       0
  5007.9     .12       0  5083.5     .16       0  5181.8      .1       0
Bank Sta=4983.7,5007.9
XS Rating Curve= 0 ,0
Exp/Cntr=0.3,0.1

Type RM Length L Ch R = 1 ,47732   ,568,568,568
BEGIN DESCRIPTION:
SF PEREZ CREEK 55.0
END DESCRIPTION:
XS GIS Cut Line= 3
      1989216.73       13613364.        1988225.       13613125.
      1987359.54     13612956.11
#Sta/Elev= 30
  3975.6  691.05  4152.2  690.15  4172.8   690.9  4265.4   687.2  4471.1   683.3
    4595  681.59  4762.6  681.44    4837  680.22  4903.1  678.44  4944.3  672.36
  4964.9  672.65  4972.2  669.02  4977.3  669.28    4981  659.52  4984.7  658.72
  5005.3  659.52  5005.9  660.65  5021.5  671.54  5026.6  670.44  5036.5  670.61
  5073.1  673.77  5129.8  673.69  5244.4  675.65  5352.3  676.31  5362.5  674.83
  5387.6   675.9  5474.6  676.26  5566.3  679.19  5759.9  689.59  5877.5  691.75
#Mann= 5 ,-1 , 0
  3975.6      .1       0    4837     .12       0    4981     .07       0
  5005.3     .12       0  5244.4      .1       0
Bank Sta=4981,5005.3
XS Rating Curve= 0 ,0
Exp/Cntr=0.3,0.1

Type RM Length L Ch R = 1 ,47164   ,572,572,572
BEGIN DESCRIPTION:
SF PEREZ CREEK 54.0
END DESCRIPTION:
XS GIS Cut Line= 3
      1989702.86     13612990.74        1988225.       13612575.
      1987499.03     13612435.39
#Sta/Elev= 30
  3470.8  691.79  3520.5  693.13  3541.3  690.39  3552.1  690.14    3581  693.94
  3620.2  691.35  3918.6   690.4  4216.9  686.97    4285  687.93    4497  682.96
  4673.6  675.57  4824.4  673.87  4943.7  670.22  4964.5  671.53  4974.9  670.87
  4983.5  657.08  4987.2  656.28  5007.8  657.08  5008.6   659.3  5016.2  669.71
  5028.3  671.21  5077.3  672.06  5135.9  675.83  5158.8  673.57  5187.8  674.95
  5331.9  675.45  5413.4  677.76  5576.3  685.95  5698.5  688.93  5745.3   689.1
#Mann= 5 ,-1 , 0
  3470.8      .1       0  4824.4     .12       0  4983.5     .07       0
  5007.8     .12       0  5028.3      .1       0
Bank Sta=4983.5,5007.8
XS Rating Curve= 0 ,0
Exp/Cntr=0.3,0.1

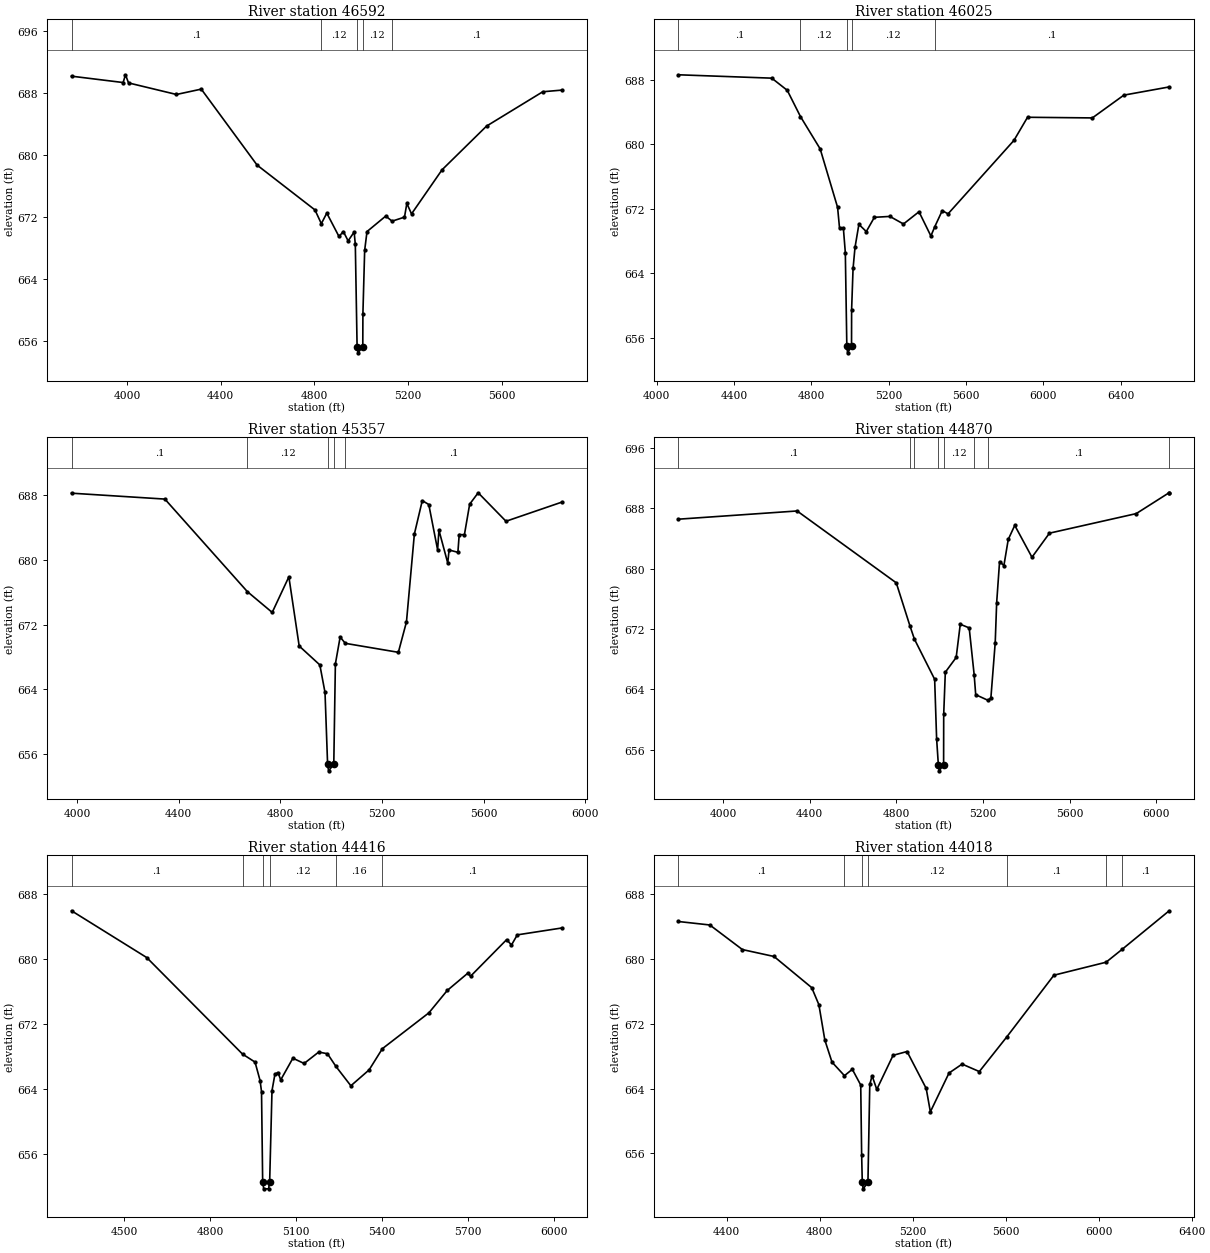
Type RM Length L Ch R = 1 ,46592   ,567,567,567
BEGIN DESCRIPTION:
SF PEREZ CREEK 53.0
END DESCRIPTION:
XS GIS Cut Line= 3
      1989702.88     13612304.98        1988475.       13612125.
      1987621.14     13612140.02
#Sta/Elev= 30
  3763.7  690.12  3983.9   689.3    3994   690.3    4007  689.25  4211.5  687.76
  4317.4  688.45  4555.7  678.65  4802.6  672.87  4829.8   671.1  4853.1  672.46
    4905  669.45  4923.8  670.08  4944.1  668.88  4969.8  670.02  4974.8  668.43
  4982.4  655.24  4986.2  654.44  5006.7  655.24  5007.2  659.48  5014.7  667.66
  5024.7  670.08  5104.7  672.08  5131.6  671.42  5184.7  671.94  5194.7  673.71
  5214.7  672.36  5344.8  678.04  5534.8  683.68  5774.8  688.11  5858.7  688.33
#Mann= 5 ,-1 , 0
  3763.7      .1       0  4829.8     .12       0  4982.4     .07       0
  5006.7     .12       0  5131.6      .1       0
Bank Sta=4982.4,5006.7
XS Rating Curve= 0 ,0
Exp/Cntr=0.3,0.1

Type RM Length L Ch R = 1 ,46025   ,668,668,668
BEGIN DESCRIPTION:
SF PEREZ CREEK 52.0
END DESCRIPTION:
XS GIS Cut Line= 4
       1989668.1     13611706.02        1988775.       13611725.
      1987817.14     13611783.71      1987289.82     13612219.58
#Sta/Elev= 30
  4112.5  688.65  4595.7  688.23  4675.7  686.72  4743.9  683.46  4845.8  679.44
  4935.8  672.18  4945.8  669.62  4965.8  669.57  4975.8  666.56  4983.6   654.9
  4987.4   654.1  5007.9   654.9  5008.3  659.47  5015.8  664.58  5025.8  667.19
  5045.9  670.06  5084.2  669.17    5126  670.94  5206.2  671.05  5276.3  670.11
  5356.5  671.63    5418  668.62  5438.3  669.78  5476.7  671.77  5506.7  671.37
  5847.4   680.5  5917.5  683.37  6252.5  683.29  6415.3  686.12  6649.6  687.14
#Mann= 5 ,-1 , 0
  4112.5      .1       0  4743.9     .12       0  4983.6     .07       0
  5007.9     .12       0  5438.3      .1       0
Bank Sta=4983.6,5007.9
XS Rating Curve= 0 ,0
Exp/Cntr=0.3,0.1

Type RM Length L Ch R = 1 ,45357   ,487,487,487
BEGIN DESCRIPTION:
SF PEREZ CREEK 51.0
END DESCRIPTION:
XS GIS Cut Line= 3
      1989416.43     13611419.57      1988400.77     13611237.27
      1987532.74      13611002.9
#Sta/Elev= 30
  3978.3  688.26  4345.5  687.53  4669.7   676.1  4767.7  673.52  4833.2  677.92
  4873.8  669.37  4955.1  667.03  4975.4  663.63  4985.6  654.74  4989.4  653.94
  5009.9  654.74  5016.2  667.16  5034.9  670.48  5055.2   669.7  5263.9  668.59
  5295.8  672.35  5326.9  683.21    5358  687.34  5383.6  686.86  5418.3  681.26
  5423.5  683.69  5458.2  679.62  5463.4  681.24  5498.1  680.95  5503.3  683.15
  5523.7  683.12  5544.4   686.9  5577.9  688.31  5687.3  684.79  5909.3  687.18
#Mann= 5 ,-1 , 0
  3978.3      .1       0  4669.7     .12       0  4985.6     .07       0
  5009.9     .12       0  5055.2      .1       0
Bank Sta=4985.6,5009.9
XS Rating Curve= 0 ,0
Exp/Cntr=0.3,0.1

Type RM Length L Ch R = 1 ,44870   ,454,454,454
BEGIN DESCRIPTION:
SF PEREZ CREEK 50.0
END DESCRIPTION:
XS GIS Cut Line= 3
      1989590.04     13610916.09        1988375.       13610775.
      1987333.11     13610837.96
#Sta/Elev= 30
  3792.7  686.54  4341.4  687.63  4799.3  678.11  4862.9  672.37    4883  670.66
  4976.6  665.33  4985.7  657.44  4993.7     654  4997.4   653.2    5018     654
  5018.4  660.67  5025.9  666.27    5076  668.22  5094.9  672.62  5136.1  672.14
    5159  665.95  5166.2  663.29  5223.1  662.54  5236.3  662.86  5256.3  670.18
    5263  675.48  5276.4  680.92  5296.4   680.4  5316.5  683.86  5346.5  685.72
    5426   681.5  5506.8  684.69  5907.5  687.28  6058.9  690.04  6059.7  690.04
#Mann= 8 ,-1 , 0
  3792.7      .1       0  4862.9     .16       0    4883     .12       0
  4993.7     .07       0    5018     .12       0    5159     .16       0
  5223.1      .1       0  6058.9     .05       0
Bank Sta=4993.7,5018
XS Rating Curve= 0 ,0
Exp/Cntr=0.3,0.1

Type RM Length L Ch R = 1 ,44416   ,398,398,398
BEGIN DESCRIPTION:
SF PEREZ CREEK 49.0
END DESCRIPTION:
XS GIS Cut Line= 3
      1989058.08     13610411.74      1988426.09     13610335.35
      1987370.52     13610536.74
#Sta/Elev= 30
  4317.3  685.95  4579.5  680.18  4913.3  668.28    4957  667.29  4974.5  665.02
  4979.6  663.65  4983.6  652.46  4987.3  651.66  5004.1  651.66  5007.9  652.46
  5016.1  663.77  5026.3  665.79  5036.8     666  5046.6   665.1  5088.9  667.77
  5128.1  667.12    5179  668.53  5209.5  668.32  5238.9  666.76    5291  664.37
  5354.7  666.33  5400.7  668.94  5563.2  673.37  5626.9  676.12  5698.2  678.24
  5708.3  677.88    5834  682.39  5850.9  681.73  5871.2  682.98  6028.5  683.84
#Mann= 6 ,-1 , 0
  4317.3      .1       0  4913.3     .12       0  4983.6     .07       0
  5007.9     .12       0  5238.9     .16       0  5400.7      .1       0
Bank Sta=4983.6,5007.9
XS Rating Curve= 0 ,0
Exp/Cntr=0.3,0.1

Type RM Length L Ch R = 1 ,44018   ,423,423,423
BEGIN DESCRIPTION:
SF PEREZ CREEK 48.0
END DESCRIPTION:
XS GIS Cut Line= 3
      1989092.79     13610231.19       1988349.7     13609967.29
      1987030.29     13609883.96
#Sta/Elev= 30
  4192.5  684.58  4328.1  684.15  4468.2  681.12    4604  680.27  4766.2  676.43
    4797  674.33  4822.6  669.97  4853.4  667.25    4907  665.58  4940.7  666.37
  4976.9  664.43  4980.9  655.77  4983.6  652.44  4987.4  651.64  5007.9  652.44
  5015.8   664.5  5025.8  665.57  5045.9  663.89    5116  668.09  5176.1  668.56
  5258.4  664.01  5276.3  661.13  5356.5  665.91  5412.8  667.01  5486.8  666.09
  5604.9  670.36  5807.4  677.96  6031.6  679.56  6101.7  681.17  6303.1   685.9
#Mann= 7 ,-1 , 0
  4192.5      .1       0    4907     .12       0  4983.6     .07       0
  5007.9     .12       0  5604.9      .1       0  6031.6     .05       0
  6101.7      .1       0
Bank Sta=4983.6,5007.9
XS Rating Curve= 0 ,0
Exp/Cntr=0.3,0.1

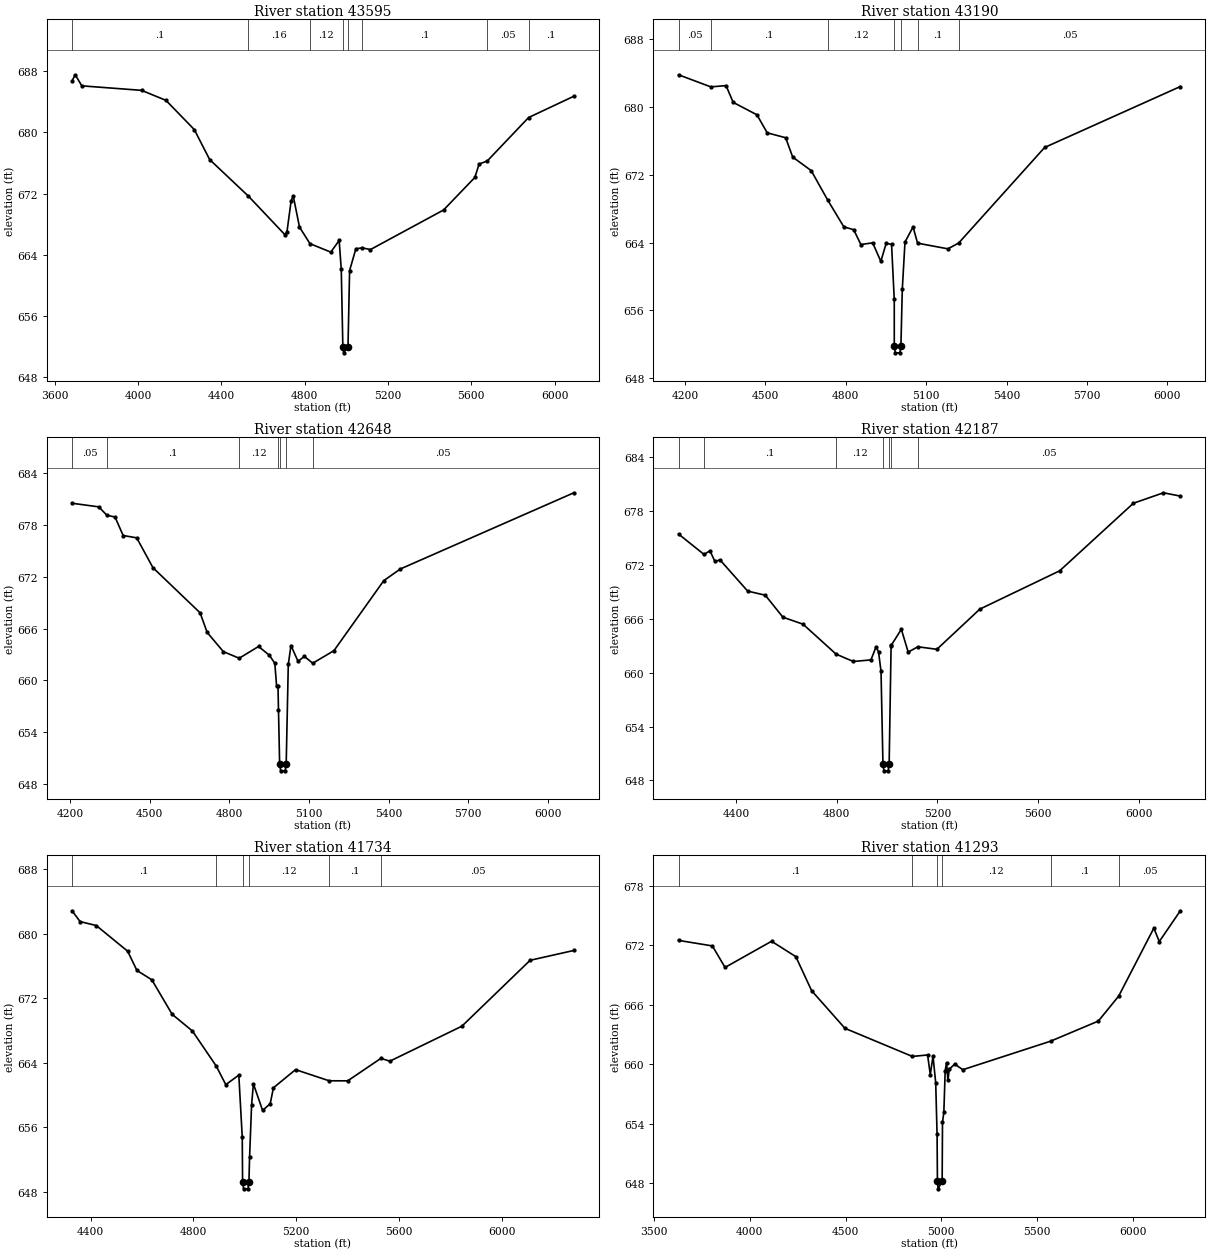
Type RM Length L Ch R = 1 ,43595   ,405,405,405
BEGIN DESCRIPTION:
SF PEREZ CREEK 47.0
END DESCRIPTION:
XS GIS Cut Line= 3
      1989669.17     13609828.41      1989085.82     13609620.07
      1987301.11     13609508.96
#Sta/Elev= 30
  3684.2  686.75  3699.2  687.56  3731.1  686.11  4017.8  685.52  4134.6  684.21
  4270.7  680.38  4344.5  676.45  4530.4  671.66  4705.2  666.62  4715.2  666.98
  4735.3  671.05  4745.3   671.7  4775.4  667.61  4825.6  665.44  4925.7  664.33
  4965.7  665.86  4975.8  662.06  4983.4  651.94  4987.3  651.14  5008.1  651.94
  5015.8  661.92  5045.9  664.77  5075.9  664.89    5116  664.67  5466.7  669.85
    5617  674.12    5637  675.86  5676.6  676.28  5874.6  681.96  6091.8  684.75
#Mann= 8 ,-1 , 0
  3684.2      .1       0  4530.4     .16       0  4825.6     .12       0
  4983.4     .07       0  5008.1     .12       0  5075.9      .1       0
  5676.6     .05       0  5874.6      .1       0
Bank Sta=4983.4,5008.1
XS Rating Curve= 0 ,0
Exp/Cntr=0.3,0.1

Type RM Length L Ch R = 1 ,43190   ,542,542,542
BEGIN DESCRIPTION:
Mapping XS bee22f8f
END DESCRIPTION:
XS GIS Cut Line= 3
      1989342.79     13609015.89      1988648.32     13609245.07
      1987509.74     13609175.65
#Sta/Elev= 30
  4176.1  683.83  4296.4   682.4  4353.4  682.55  4379.9  680.57  4468.6   679.1
  4506.9  676.97  4575.7  676.39  4602.1   674.1  4670.9  672.51  4731.9  669.06
  4792.7  665.86  4829.7  665.52  4856.2  663.77  4900.4  663.97  4930.8  661.78
  4950.8  663.91  4970.8  663.78  4980.9  657.28    4981  651.77  4984.9  650.97
  5001.8  650.97  5005.7  651.77  5010.9  658.49  5020.9  664.06    5051  665.85
  5067.9  663.93  5181.2  663.26  5221.3  663.95  5541.9  675.24  6048.1  682.44
#Mann= 7 ,-1 , 0
  4176.1     .05       0  4296.4      .1       0  4731.9     .12       0
    4981     .07       0  5005.7     .12       0  5067.9      .1       0
  5221.3     .05       0
Bank Sta=4981,5005.7
XS Rating Curve= 0 ,0
Exp/Cntr=0.3,0.1

Type RM Length L Ch R = 1 ,42648   ,461,461,461
BEGIN DESCRIPTION:
SF PEREZ CREEK 46.0
END DESCRIPTION:
XS GIS Cut Line= 3
      1989363.63     13608654.79      1988606.65     13608807.57
      1987502.46     13608981.19
#Sta/Elev= 30
  4207.8  680.49  4308.4  680.07    4339   679.1  4369.6   678.9  4400.2  676.76
  4451.2  676.49  4512.4  673.04    4690  667.82  4716.5  665.56  4777.7  663.33
  4837.4  662.57  4910.3  663.93  4951.1  662.91  4971.5  661.98  4978.3  659.31
  4983.4  659.31  4985.3  656.56  4989.6  650.35  4993.5  649.55  5010.4  649.55
  5014.3  650.35  5022.2  661.85  5032.3  664.04  5058.8  662.22  5082.9  662.78
  5114.2  661.99  5194.3  663.45  5381.8  671.54  5444.3  672.89  6097.8   681.7
#Mann= 7 ,-1 , 0
  4207.8     .05       0    4339      .1       0  4837.4     .12       0
  4985.3      .1       0  4989.6     .07       0  5014.3      .1       0
  5114.2     .05       0
Bank Sta=4989.6,5014.3
XS Rating Curve= 0 ,0
Exp/Cntr=0.3,0.1

Type RM Length L Ch R = 1 ,42187   ,453,453,453
BEGIN DESCRIPTION:
SF PEREZ CREEK 45.0
END DESCRIPTION:
XS GIS Cut Line= 3
      1989349.67     13608383.96      1988467.76     13608377.02
      1987460.83     13608849.23
#Sta/Elev= 30
  4171.1  675.46  4272.7  673.18  4295.8   673.6  4315.8   672.4  4335.8  672.58
  4445.8   669.1  4515.8  668.64  4585.8  666.19  4665.8  665.41  4797.2  662.07
  4865.8  661.25  4935.8  661.43  4955.8  662.87  4965.8  662.34  4975.8  660.16
  4983.4  649.86  4987.3  649.06  5004.2  649.06  5008.1  649.86  5015.8  663.03
  5016.3  663.05  5056.6  664.84  5083.7   662.3  5122.2  662.89  5197.8  662.61
  5368.6  667.09  5685.7  671.36  5978.5  678.89  6098.1  680.06  6165.2  679.69
#Mann= 7 ,-1 , 0
  4171.1     .05       0  4272.7      .1       0  4797.2     .12       0
  4983.4     .07       0  5008.1     .12       0  5016.3      .1       0
  5122.2     .05       0
Bank Sta=4983.4,5008.1
XS Rating Curve= 0 ,0
Exp/Cntr=0.3,0.1

Type RM Length L Ch R = 1 ,41734   ,441,441,441
BEGIN DESCRIPTION:
Mapping XS de8d2bd4
END DESCRIPTION:
XS GIS Cut Line= 2
      1989110.78     13607568.59      1987501.48     13608677.92
#Sta/Elev= 30
  4327.1  682.85  4358.4  681.51  4421.4  681.02  4543.8  677.83  4579.7  675.45
  4637.8  674.29    4717  670.01  4795.7  667.95  4888.4  663.61  4925.9  661.29
  4976.6  662.47    4990  654.78  4991.3  649.17  4995.2  648.37  5012.1  648.37
    5016  649.17  5018.5  652.27  5026.4  658.77  5033.4  661.39  5069.3  658.09
    5099  658.93  5111.4   660.9  5197.7  663.15  5328.3  661.77  5400.6  661.76
  5530.1  664.55  5564.9   664.2  5845.6  668.54  6111.3  676.71  6281.7  677.93
#Mann= 6 ,-1 , 0
  4327.1      .1       0  4888.4     .12       0  4991.3     .07       0
    5016     .12       0  5328.3      .1       0  5530.1     .05       0
Bank Sta=4991.3,5016
XS Rating Curve= 0 ,0
Exp/Cntr=0.3,0.1

Type RM Length L Ch R = 1 ,41293   ,228,228,228
BEGIN DESCRIPTION:
SF PEREZ CREEK 44.0
END DESCRIPTION:
XS GIS Cut Line= 3
      1989544.16     13606786.73      1988842.76     13607154.79
      1987544.17      13608439.5
#Sta/Elev= 30
  3628.4  672.51    3805  671.95  3871.2  669.78  4113.8  672.42  4240.5  670.87
    4323  667.43  4496.9  663.63  4848.7  660.79  4928.2  660.94  4942.3  658.96
  4956.5  660.83  4970.6  658.11  4977.7  652.91  4979.5  648.22  4983.4  647.42
  5004.2  648.22    5006  654.15    5013  655.13  5020.1  659.37  5027.2  660.17
  5034.3  658.37  5041.3  659.49  5069.6  660.02    5112  659.45    5570  662.33
  5819.2  664.36  5925.4  666.88  6109.1  673.75  6137.3  672.39  6247.2   675.5
#Mann= 6 ,-1 , 0
  3628.4      .1       0  4848.7     .12       0  4979.5     .07       0
  5004.2     .12       0    5570      .1       0  5925.4     .05       0
Bank Sta=4979.5,5004.2
XS Rating Curve= 0 ,0
Exp/Cntr=0.3,0.1

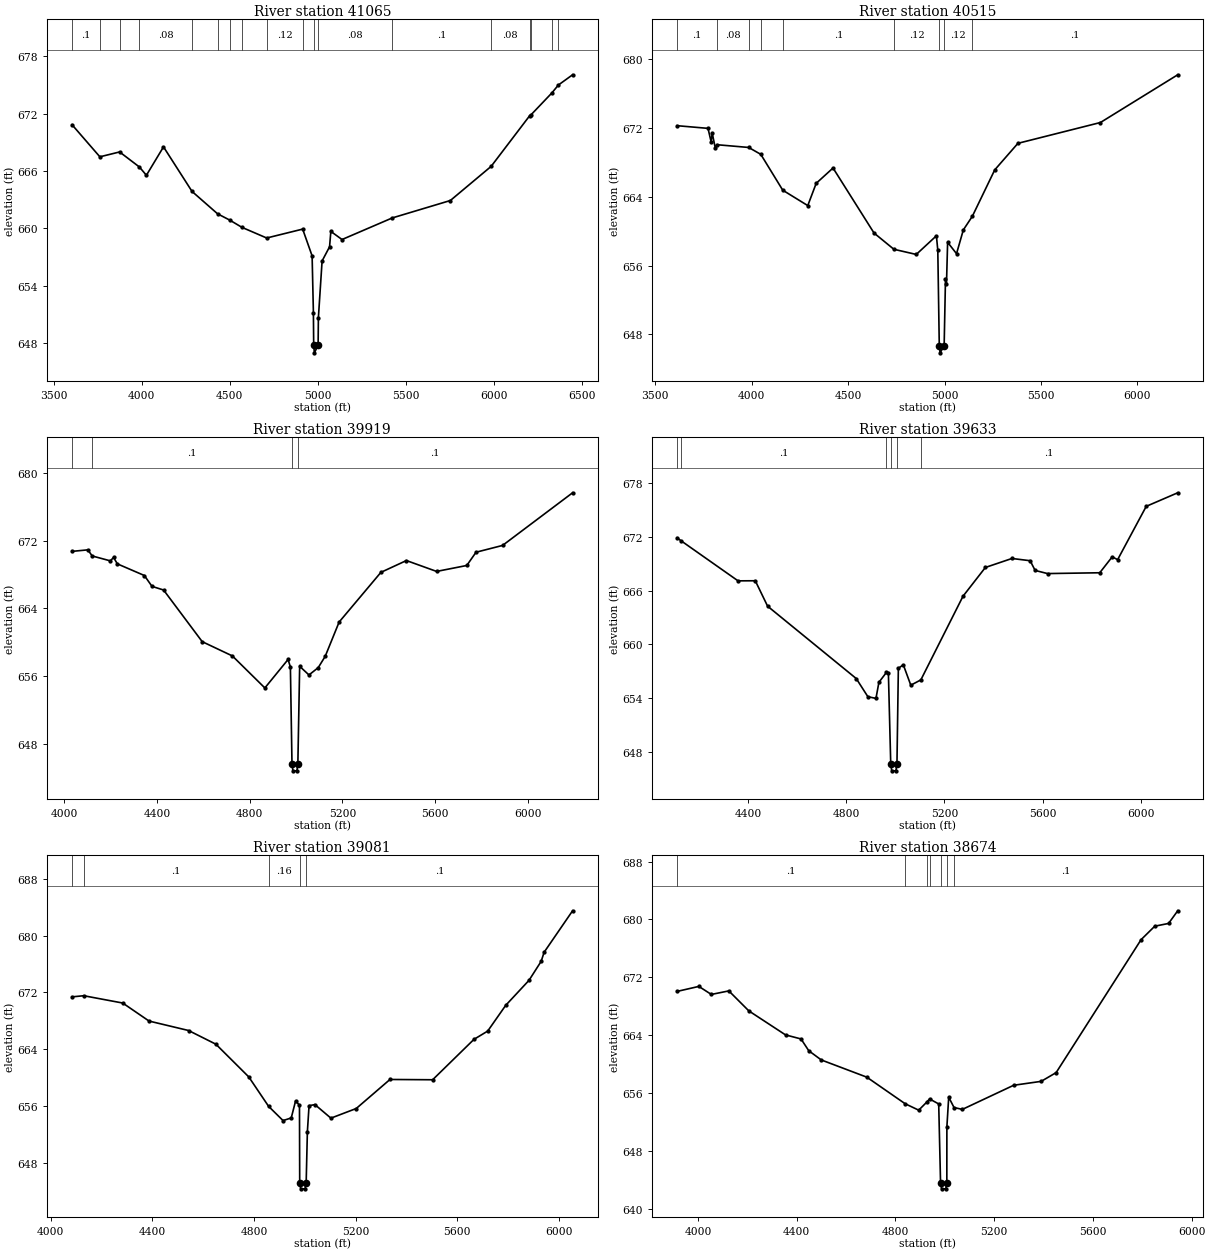
Type RM Length L Ch R = 1 ,41065   ,550,550,550
BEGIN DESCRIPTION:
SF PEREZ CREEK 43.0
END DESCRIPTION:
XS GIS Cut Line= 4
      1989488.57     13606529.81      1988981.65     13606786.74
      1987755.95      13607945.3      1987370.91     13608390.48
#Sta/Elev= 30
  3604.9  670.83  3763.2  667.47  3875.3  667.98  3987.4  666.41  4027.5  665.54
  4124.6  668.51  4286.7  663.85  4431.8  661.51    4500  660.86  4570.6  660.09
  4710.8  658.98  4915.1  659.91  4968.8  657.11  4976.1  651.17  4977.7  647.77
  4981.7  646.97  5002.9  647.77  5004.4  650.64  5025.5  656.58  5067.9  658.06
  5075.2  659.67  5138.7  658.82  5424.3  661.08    5754   662.9  5985.7  666.47
  6203.9  671.75  6211.6  671.85  6330.7  674.15  6367.7  674.98  6448.4  676.05
#Mann= 18 ,-1 , 0
  3604.9      .1       0  3763.2     .08       0  3875.3      .1       0
  3987.4     .08       0  4286.7      .1       0  4431.8     .08       0
    4500      .1       0  4570.6     .08       0  4710.8     .12       0
  4915.1     .08       0  4977.7     .07       0  5002.9     .08       0
  5424.3      .1       0  5985.7     .08       0  6203.9     .05       0
  6211.6      .1       0  6330.7     .08       0  6367.7      .1       0
Bank Sta=4977.7,5002.9
XS Rating Curve= 0 ,0
Exp/Cntr=0.3,0.1

Type RM Length L Ch R = 1 ,40515   ,596,596,596
BEGIN DESCRIPTION:
Mapping XS 3525f32d
END DESCRIPTION:
XS GIS Cut Line= 3
       1989730.6     13606313.36      1988871.23     13606782.11
      1987282.69     13607084.19
#Sta/Elev= 30
  3613.5  672.27  3773.6  671.96  3789.7   670.4  3795.4   671.4  3811.6  669.64
  3819.1  670.06  3984.4  669.74  4047.2  668.94  4161.2  664.77  4290.9  662.98
  4334.6  665.57  4421.9  667.35  4634.5  659.79  4737.5   657.9  4853.5   657.3
    4958  659.47  4965.2  657.78  4972.9  646.66    4977  645.86  4998.1  646.66
  5005.1  654.49  5010.2  653.82  5016.1  658.71  5062.4  657.39  5097.5  660.15
  5144.4  661.74  5260.4  667.13  5380.7  670.22  5808.6  672.64  6209.4  678.19
#Mann= 9 ,-1 , 0
  3613.5      .1       0  3819.1     .08       0  3984.4      .1       0
  4047.2     .08       0  4161.2      .1       0  4737.5     .12       0
  4972.9     .07       0  4998.1     .12       0  5144.4      .1       0
Bank Sta=4972.9,4998.1
XS Rating Curve= 0 ,0
Exp/Cntr=0.3,0.1

Type RM Length L Ch R = 1 ,39919   ,286,286,286
BEGIN DESCRIPTION:
Mapping XS f3d97972
END DESCRIPTION:
XS GIS Cut Line= 3
      1989652.45     13606219.63      1989298.32      13606401.9
      1987538.98       13606303.
#Sta/Elev= 30
  4033.3  670.72  4101.6   670.9  4120.5  670.18  4199.1   669.6  4212.5  670.01
    4229  669.25  4345.5  667.88  4378.6   666.6  4428.6  666.17  4595.2  660.09
  4725.4  658.41  4865.6  654.64  4965.7  657.99  4975.8  657.11  4982.7  645.68
  4986.8  644.88  5003.9  644.88    5008  645.68  5015.8  657.19  5055.9  656.17
  5095.9  657.03    5126  658.36  5186.1   662.4  5366.4  668.25  5476.5  669.64
  5606.8  668.36    5737  669.06    5777  670.62  5891.5  671.42  6193.7  677.62
#Mann= 4 ,-1 , 0
  4033.3     .08       0  4120.5      .1       0  4982.7     .07       0
    5008      .1       0
Bank Sta=4982.7,5008
XS Rating Curve= 0 ,0
Exp/Cntr=0.3,0.1

Type RM Length L Ch R = 1 ,39633   ,552,552,552
BEGIN DESCRIPTION:
Mapping XS eaff526c
END DESCRIPTION:
XS GIS Cut Line= 3
      1989772.24      13606089.4      1988970.19     13606162.32
      1987751.46      13605959.2
#Sta/Elev= 30
  4110.2  671.87  4125.6  671.55  4358.5  667.08  4428.8  667.09    4479  664.26
  4840.4  656.21  4887.8  654.19  4920.8     654  4932.8  655.79  4963.4  656.89
  4971.5  656.79    4981  646.74  4985.1  645.94  5002.2  645.94  5006.4  646.74
  5012.1  657.35  5032.3  657.74  5062.8  655.47  5103.8  656.06  5275.7  665.37
  5366.9  668.57  5475.2  669.57  5549.4  669.32  5569.7  668.24  5620.3  667.89
  5833.2  667.98  5883.9  669.75  5906.1  669.44  6022.7  675.37  6151.1  676.88
#Mann= 6 ,-1 , 0
  4110.2     .08       0  4125.6      .1       0  4963.4     .12       0
    4981     .07       0  5006.4     .12       0  5103.8      .1       0
Bank Sta=4981,5006.4
XS Rating Curve= 0 ,0
Exp/Cntr=0.3,0.1

Type RM Length L Ch R = 1 ,39081   ,407,407,407
BEGIN DESCRIPTION:
SF PEREZ CREEK 42.0
END DESCRIPTION:
XS GIS Cut Line= 3
      1989944.18     13605948.79        1989075.       13605675.
      1988090.03     13605287.33
#Sta/Elev= 30
  4084.2  671.36  4130.4  671.52  4283.8  670.49  4387.4  667.95  4542.8  666.62
  4650.4  664.69  4779.8  660.08  4857.9  655.93  4914.6  653.93  4946.9   654.3
    4964   656.7  4979.3  656.09  4980.2  645.11  4984.3  644.31  5001.4  644.31
  5005.6  645.11  5010.4  652.37    5017  656.03  5040.1  656.18    5103  654.27
  5202.7  655.63  5335.4  659.72  5503.3  659.68  5665.8  665.37    5720  666.54
  5790.7  670.16  5882.5  673.69  5930.4  676.37    5942  677.65    6054  683.49
#Mann= 5 ,-1 , 0
  4084.2     .08       0  4130.4      .1       0  4857.9     .16       0
  4980.2     .07       0  5005.6      .1       0
Bank Sta=4980.2,5005.6
XS Rating Curve= 0 ,0
Exp/Cntr=0.3,0.1

Type RM Length L Ch R = 1 ,38674   ,348,348,348
BEGIN DESCRIPTION:
Mapping XS 6d1b26a0
END DESCRIPTION:
XS GIS Cut Line= 2
      1990201.87     13605457.89      1988198.35     13605145.65
#Sta/Elev= 30
    3916  670.06  4003.9  670.75  4054.5  669.64  4125.4  670.13  4206.3  667.37
    4355  664.05  4417.8  663.49  4449.2  661.86  4499.8  660.59  4684.3  658.21
  4839.5  654.54  4894.5  653.65  4927.3  654.77  4938.6   655.2  4975.5  654.51
    4983  643.58  4987.2  642.78  5004.3  642.78  5008.4  643.58  5008.6  651.33
    5016  655.44  5037.7  654.01  5071.4  653.76  5279.1  657.09  5390.5  657.63
  5451.2  658.84  5795.3  677.21  5850.7  679.07  5906.6  679.45  5943.7   681.2
#Mann= 7 ,-1 , 0
    3916      .1       0  4839.5     .12       0  4927.3     .07       0
  4938.6     .12       0    4983     .07       0  5008.4     .12       0
  5037.7      .1       0
Bank Sta=4983,5008.4
XS Rating Curve= 0 ,0
Exp/Cntr=0.3,0.1

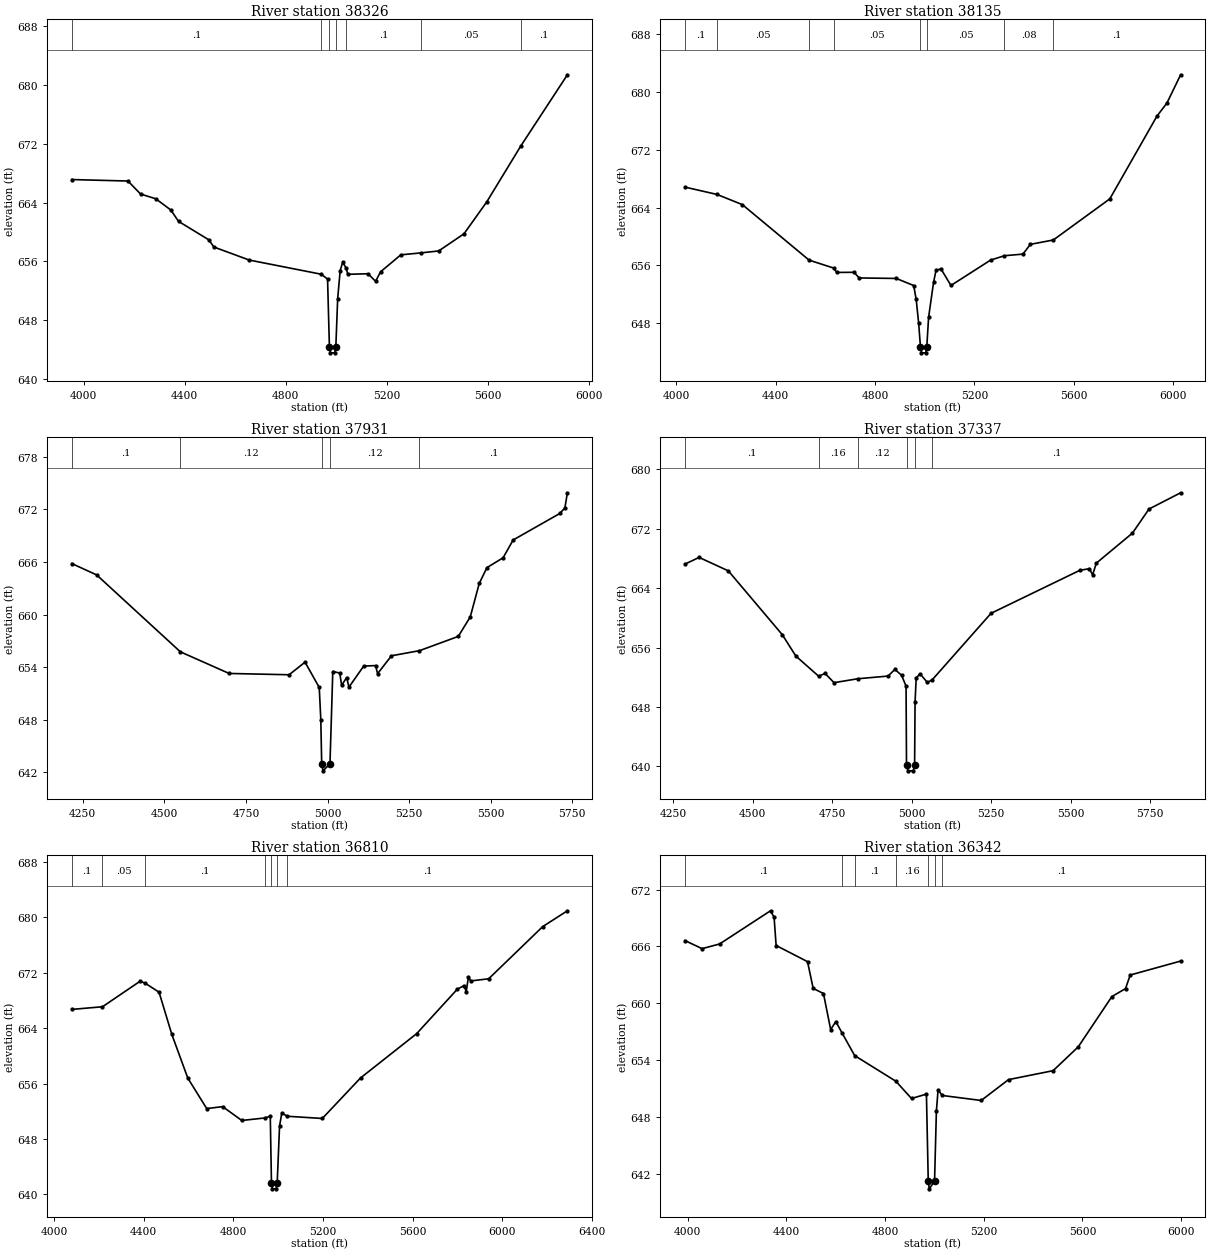
Type RM Length L Ch R = 1 ,38326   ,191,191,191
BEGIN DESCRIPTION:
Mapping XS d1fd08f6
END DESCRIPTION:
XS GIS Cut Line= 2
      1990287.49     13604992.61      1988325.71     13604983.93
#Sta/Elev= 30
  3953.3  667.12  4175.8  666.92  4225.8  665.15  4285.8  664.51  4345.8  662.97
  4375.8  661.44  4495.8  658.93  4515.8  657.95  4655.8  656.18  4941.2  654.25
  4965.8  653.59  4973.1  644.37  4977.2  643.57  4994.3  643.57  4998.5  644.37
  5005.8  650.94  5015.8  654.76  5025.8  655.89  5039.5  655.07  5045.8  654.24
  5125.8  654.32  5155.8  653.29  5175.8  654.59  5255.8  656.89  5334.7  657.15
  5405.8  657.42  5505.8  659.75  5595.8  664.08  5730.4  671.67  5915.1  681.36
#Mann= 7 ,-1 , 0
  3953.3      .1       0  4941.2     .16       0  4973.1     .07       0
  4998.5     .16       0  5039.5      .1       0  5334.7     .05       0
  5730.4      .1       0
Bank Sta=4973.1,4998.5
XS Rating Curve= 0 ,0
Exp/Cntr=0.3,0.1

Type RM Length L Ch R = 1 ,38135   ,204,204,204
BEGIN DESCRIPTION:
Mapping XS 4ec7b3a6
END DESCRIPTION:
XS GIS Cut Line= 2
      1990296.18      13604840.7      1988299.82     13604827.68
#Sta/Elev= 30
  4034.6  666.82  4163.6  665.81  4265.8   664.4  4534.5  656.74  4632.9  655.65
  4645.8  655.04  4715.8  655.06  4735.8  654.28  4885.8  654.21  4955.8  653.23
  4965.8  651.33  4975.8  648.02  4983.1  644.74  4987.2  643.94  5004.3  643.94
  5008.5  644.74  5015.8  648.84  5035.8  653.66  5045.8  655.35  5065.8  655.53
  5105.8  653.24  5265.8  656.75  5321.4  657.35  5395.8  657.57  5425.8  658.92
  5518.2  659.52  5745.8   665.2  5935.8  676.63  5975.8  678.43    6031  682.33
#Mann= 8 ,-1 , 0
  4034.6      .1       0  4163.6     .05       0  4534.5     .08       0
  4632.9     .05       0  4983.1     .04       0  5008.5     .05       0
  5321.4     .08       0  5518.2      .1       0
Bank Sta=4983.1,5008.5
XS Rating Curve= 0 ,0
Exp/Cntr=0.3,0.1

Type RM Length L Ch R = 1 ,37931   ,594,594,594
BEGIN DESCRIPTION:
SF PEREZ CREEK 41.0
END DESCRIPTION:
XS GIS Cut Line= 3
      1990170.31     13604797.31        1989425.       13604675.
        1988775.       13604275.
#Sta/Elev= 30
  4216.3  665.82  4292.6  664.52    4549  655.74  4698.4  653.27  4882.2  653.12
    4931  654.56  4974.5  651.67  4979.3  648.01    4982  642.95  4986.1  642.15
  5007.4  642.95    5016  653.49  5037.3  653.32  5043.1  651.92  5058.5   652.8
  5065.5  651.71  5110.7  654.11  5147.3  654.17  5153.2  653.24  5195.8  655.29
  5281.5  655.87  5400.5   657.5  5437.2  659.73  5464.7  663.55  5488.2  665.35
  5537.8  666.48  5568.6  668.51  5711.7  671.54  5727.1  672.18  5734.8   673.9
#Mann= 5 ,-1 , 0
  4216.3      .1       0    4549     .12       0    4982     .07       0
  5007.4     .12       0  5281.5      .1       0
Bank Sta=4982,5007.4
XS Rating Curve= 0 ,0
Exp/Cntr=0.3,0.1

Type RM Length L Ch R = 1 ,37337   ,527,527,527
BEGIN DESCRIPTION:
SF PEREZ CREEK 40.0
END DESCRIPTION:
XS GIS Cut Line= 3
      1990300.48     13604732.19        1989775.       13604225.
      1989024.97     13603874.99
#Sta/Elev= 30
  4287.6  667.25    4332  668.15  4423.8  666.34  4593.6  657.73    4636  654.86
  4707.8  652.14  4727.9  652.51  4756.2  651.27  4830.6   651.8    4926  652.16
  4947.3  653.06  4968.4  652.27  4982.5  650.81  4983.9  640.19  4988.1  639.39
  5005.3  639.39  5009.4  640.19  5010.8  648.67  5014.4  651.91  5026.6  652.47
  5049.4   651.3  5064.6  651.65  5249.7  660.62  5528.7  666.41  5558.6  666.63
  5568.9  665.81  5580.7  667.38  5694.2  671.43  5746.2  674.67  5845.6  676.86
#Mann= 6 ,-1 , 0
  4287.6      .1       0  4707.8     .16       0  4830.6     .12       0
  4983.9     .07       0  5009.4     .12       0  5064.6      .1       0
Bank Sta=4983.9,5009.4
XS Rating Curve= 0 ,0
Exp/Cntr=0.3,0.1

Type RM Length L Ch R = 1 ,36810   ,468,468,468
BEGIN DESCRIPTION:
SF PEREZ CREEK 39.0
END DESCRIPTION:
XS GIS Cut Line= 3
       1990853.9     13604526.06        1990175.       13603925.
      1988874.98       13603825.
#Sta/Elev= 30
  4079.6   666.7  4216.6  667.08  4384.6  670.77  4408.1  670.46    4469  669.18
  4525.9  663.09    4597  656.79  4681.5  652.38  4752.6  652.66  4837.9  650.66
  4942.1  651.03    4965  651.28  4970.3  641.59  4974.4  640.79  4991.6  640.79
  4995.8  641.59  5006.4  649.88  5016.4  651.73  5041.3  651.27    5197  650.95
  5367.5   656.8  5618.2  663.21  5798.7   669.6  5828.8  670.14  5838.9  669.27
  5848.9  671.41  5858.9  670.81  5939.1  671.12  6179.9  678.65  6290.2  680.94
#Mann= 7 ,-1 , 0
  4079.6      .1       0  4216.6     .05       0  4408.1      .1       0
  4942.1     .16       0  4970.3     .07       0  4995.8     .16       0
  5041.3      .1       0
Bank Sta=4970.3,4995.8
XS Rating Curve= 0 ,0
Exp/Cntr=0.3,0.1

Type RM Length L Ch R = 1 ,36342   ,537,537,537
BEGIN DESCRIPTION:
SF PEREZ CREEK 38.0
END DESCRIPTION:
XS GIS Cut Line= 3
      1991132.45     13603983.69      1990533.53      13603535.8
      1989283.49     13603374.33
#Sta/Elev= 30
  3989.6  666.62  4058.8  665.77  4129.7  666.26  4336.1  669.76  4350.6  669.08
  4358.9   666.1  4486.1   664.4    4509  661.58  4550.7  661.04  4579.9  657.24
  4600.7  658.09  4626.8  656.85  4677.1   654.5    4844   651.8  4907.4  649.98
  4967.9  650.44  4975.3  641.26  4979.5  640.46  5000.8  641.26  5008.2  648.61
  5015.1  650.91  5031.6   650.3  5189.7  649.77  5300.6  651.97  5481.2  652.91
    5583  655.42  5719.3  660.72  5774.6  661.56  5793.6  662.99  5997.9  664.46
#Mann= 7 ,-1 , 0
  3989.6      .1       0  4626.8     .16       0  4677.1      .1       0
    4844     .16       0  4975.3     .07       0  5000.8     .16       0
  5031.6      .1       0
Bank Sta=4975.3,5000.8
XS Rating Curve= 0 ,0
Exp/Cntr=0.3,0.1