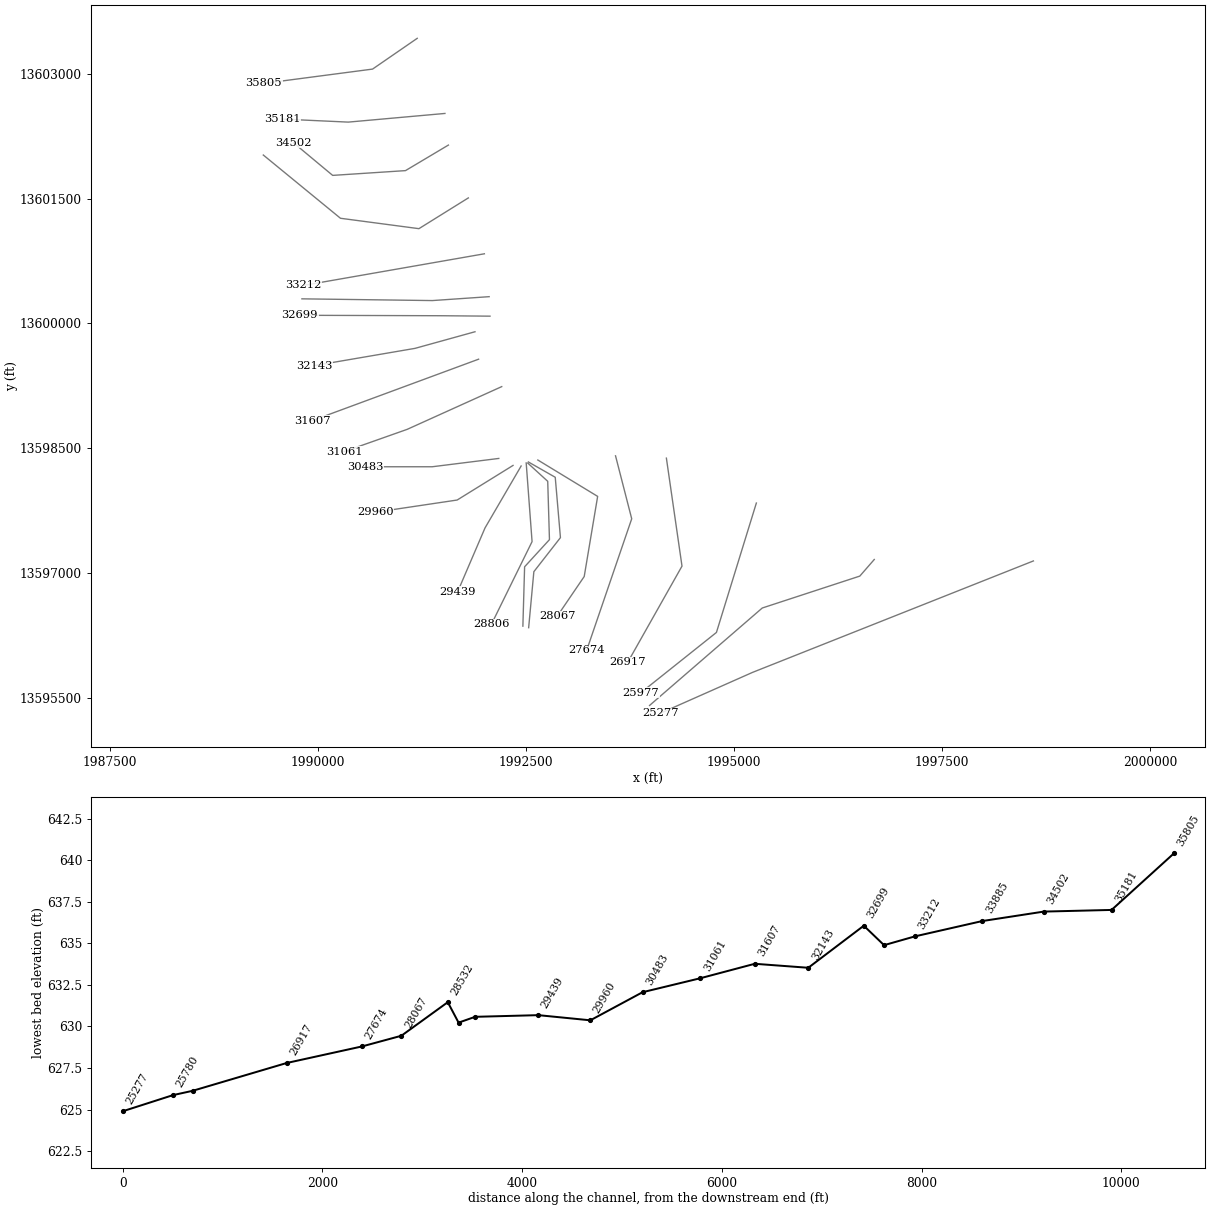
HEC-RAS study SF PEREZ CREEK.prj: SF PEREZ CREEK Base Level Engineering

--- SF PEREZ CREEK.g01 (geometry) --- (continued)

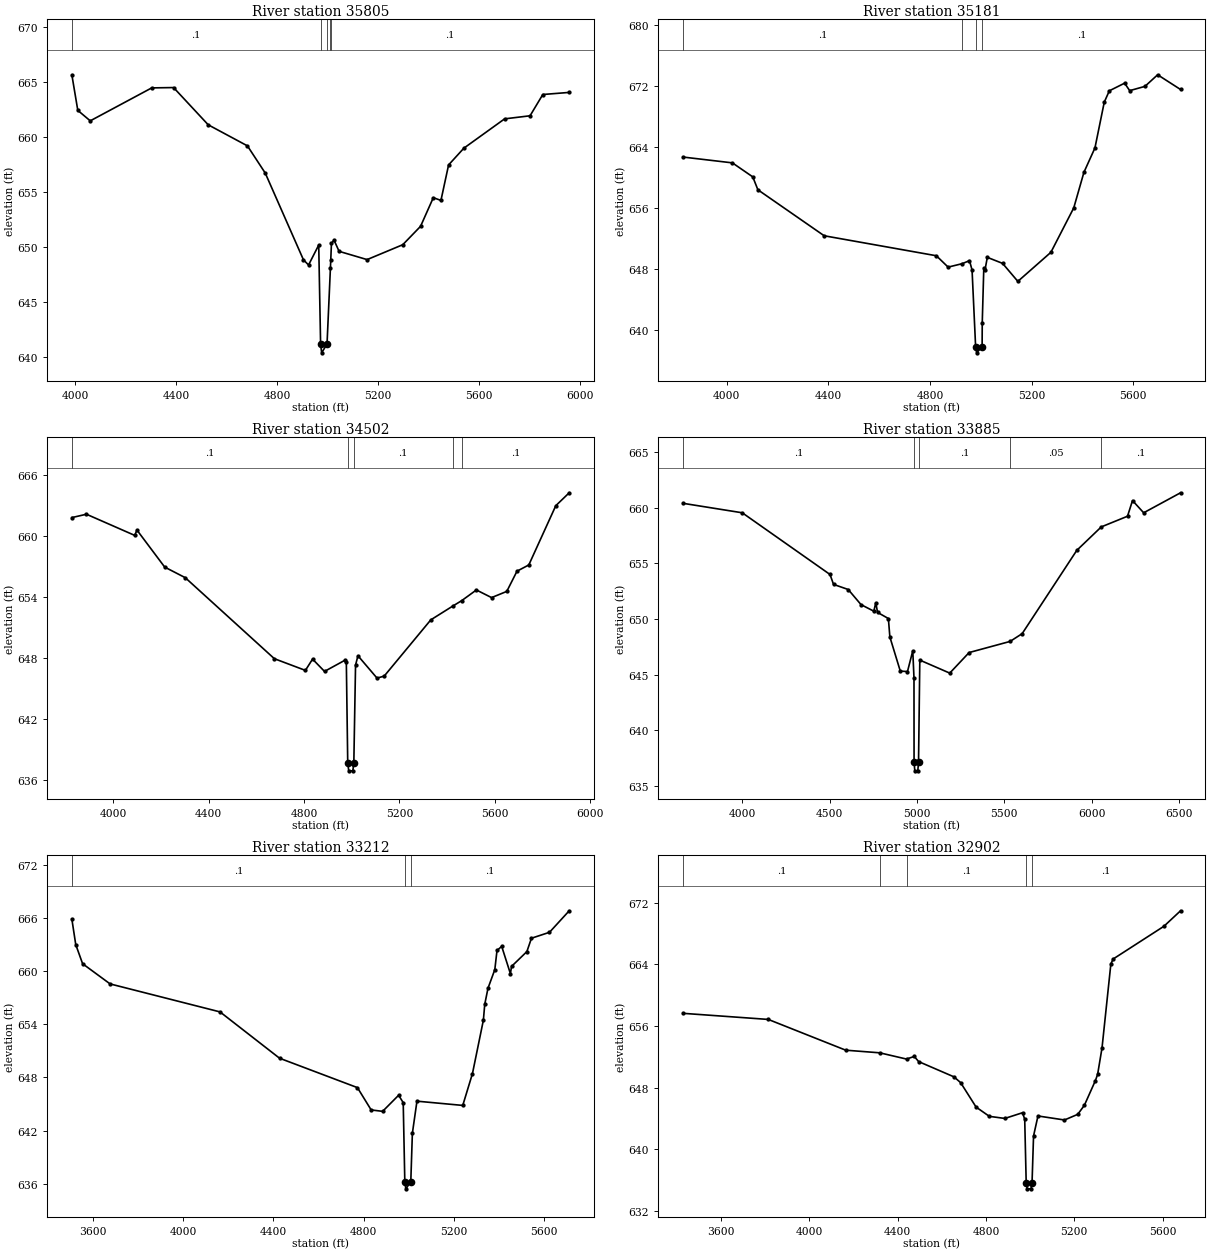
Type RM Length L Ch R = 1 ,35805   ,624,624,624
BEGIN DESCRIPTION:
SF PEREZ CREEK 37.0
END DESCRIPTION:
XS GIS Cut Line= 3
      1991195.01     13603426.44      1990658.53     13603056.63
      1989351.27     13602884.76
#Sta/Elev= 30
  3987.6  665.64  4011.2  662.41  4060.5  661.46    4304  664.45  4390.5  664.48
  4527.8   661.1  4683.1  659.19  4753.7  656.72    4905  648.85  4925.2  648.38
  4965.5  650.19  4972.9  641.21  4977.1  640.41  4998.4  641.21  5011.9  648.15
  5013.2  648.86  5015.9  650.34    5026  650.64  5046.2  649.62  5157.1  648.87
  5298.3  650.22  5368.9  651.89  5419.4  654.49  5449.6  654.24  5479.9  657.46
  5540.4  658.98  5701.8  661.64  5802.6  661.92  5853.1  663.85  5957.7  664.04
#Mann= 5 ,-1 , 0
  3987.6      .1       0  4972.9     .07       0  4998.4      .1       0
  5011.9     .16       0  5013.2      .1       0
Bank Sta=4972.9,4998.4
XS Rating Curve= 0 ,0
Exp/Cntr=0.3,0.1

Type RM Length L Ch R = 1 ,35181   ,679,679,679
BEGIN DESCRIPTION:
SF PEREZ CREEK 36.0
END DESCRIPTION:
XS GIS Cut Line= 3
      1991528.03     13602523.29       1990366.6     13602419.13
      1989574.93     13602455.59
#Sta/Elev= 30
  3828.1  662.68  4021.9  661.92  4102.2  660.08  4122.3  658.39  4383.4  652.36
  4825.1  649.74  4871.4  648.25  4926.6   648.7  4955.6   649.1  4965.7  647.87
  4979.7  637.81  4983.9  637.01  5005.3  637.81  5005.8  640.95  5011.9  648.13
  5016.9  647.93  5025.8  649.53  5085.9  648.74    5146  646.38  5276.1  650.19
  5366.2  656.02  5406.2  660.68  5449.6  663.88  5486.3  669.88  5506.3  671.37
  5566.4  672.37  5586.4  671.39  5646.5  671.95  5696.5  673.47  5786.7  671.54
#Mann= 4 ,-1 , 0
  3828.1      .1       0  4926.6     .12       0  4979.7     .07       0
  5005.3      .1       0
Bank Sta=4979.7,5005.3
XS Rating Curve= 0 ,0
Exp/Cntr=0.3,0.1

Type RM Length L Ch R = 1 ,34502   ,617,617,617
BEGIN DESCRIPTION:
SF PEREZ CREEK 35.0
END DESCRIPTION:
XS GIS Cut Line= 4
      1991569.75      13602143.1       1991054.1      13601835.8
       1990179.1     13601778.51      1989710.37     13602169.12
#Sta/Elev= 30
  3825.2  661.82  3886.5  662.15  4088.9  660.07  4098.5  660.59  4214.9  656.95
  4301.1  655.91  4675.1  647.94  4805.4  646.79  4835.4   647.9  4885.6  646.69
  4972.1   647.8  4977.1  647.64    4983  637.71  4987.2  636.91  5004.4  636.91
  5008.6  637.71  5015.8  647.31  5025.9  648.23    5106  646.03  5136.1  646.23
  5331.6  651.76  5422.7   653.1  5461.3  653.65  5522.9   654.7  5586.7  653.95
  5650.5  654.56  5693.4  656.55  5742.9  657.16  5856.2  662.99  5912.5  664.26
#Mann= 5 ,-1 , 0
  3825.2      .1       0    4983     .07       0  5008.6      .1       0
  5422.7     .05       0  5461.3      .1       0
Bank Sta=4983,5008.6
XS Rating Curve= 0 ,0
Exp/Cntr=0.3,0.1

Type RM Length L Ch R = 1 ,33885   ,673,673,673
BEGIN DESCRIPTION:
SF PEREZ CREEK 34.0
END DESCRIPTION:
XS GIS Cut Line= 4
       1991809.3     13601507.67      1991215.56     13601137.88
      1990272.85     13601262.88      1989345.76      13602023.3
#Sta/Elev= 30
  3660.2   660.4  3998.7  659.55  4501.5     654  4521.6  653.11  4605.7  652.65
  4679.1  651.29  4752.4   650.7  4763.7  651.46  4773.8  650.59  4835.8  650.04
  4844.4  648.38  4904.1  645.31  4945.3  645.27  4975.6  647.14  4982.5   644.7
    4983  637.14  4987.2  636.34  5004.4  636.34  5008.6  637.14  5015.9   646.3
  5187.4  645.13  5298.4  646.98  5533.1  647.98  5602.3  648.68  5915.2  656.17
  6055.5  658.28  6205.8  659.24  6234.5  660.65  6298.4  659.55  6509.7  661.35
#Mann= 5 ,-1 , 0
  3660.2      .1       0    4983     .07       0  5008.6      .1       0
  5533.1     .05       0  6055.5      .1       0
Bank Sta=4983,5008.6
XS Rating Curve= 0 ,0
Exp/Cntr=0.3,0.1

Type RM Length L Ch R = 1 ,33212   ,310,310,310
BEGIN DESCRIPTION:
Mapping XS 313c5cb7
END DESCRIPTION:
XS GIS Cut Line= 2
      1992002.02      13600835.8      1989830.15     13600455.59
#Sta/Elev= 30
  3506.4  665.89  3523.7     663  3554.1  660.84    3676  658.56  4163.3   655.4
  4427.2  650.17  4772.4  646.85  4833.3  644.33  4884.1  644.17  4955.1  645.99
  4975.4  645.15  4982.5  636.22    4987  635.42    5009  636.22    5016  641.69
  5036.3  645.32  5239.4  644.84  5282.4  648.44  5330.8  654.47  5336.8  656.25
  5351.1  658.06  5381.5  660.18  5391.2  662.34    5412   662.8  5450.6  659.72
  5455.7  660.54  5523.6  662.21  5543.9  663.72  5623.9  664.39  5711.3  666.82
#Mann= 3 ,-1 , 0
  3506.4      .1       0  4982.5     .07       0    5009      .1       0
Bank Sta=4982.5,5009
XS Rating Curve= 0 ,0
Exp/Cntr=0.3,0.1

Type RM Length L Ch R = 1 ,32902   ,203,203,203
BEGIN DESCRIPTION:
SF PEREZ CREEK 33.0
END DESCRIPTION:
XS GIS Cut Line= 3
      1992059.31     13600320.17      1991377.02      13600273.3
      1989809.66     13600294.13
#Sta/Elev= 30
  3429.8  657.65    3815  656.86  4165.7  652.87  4319.5  652.53  4440.7  651.72
  4475.8  652.06  4495.8  651.39  4655.8  649.41  4685.8  648.66  4755.8  645.49
  4815.8  644.29  4885.8  644.02  4965.8  644.76  4975.8  643.92  4982.5  635.69
    4987  634.89  5004.5  634.89    5009  635.69  5015.8  641.75  5035.8  644.34
  5155.8  643.82  5215.8  644.55  5245.8  645.72  5295.8  648.93  5305.8  649.73
  5325.8  653.18  5365.7  664.04  5375.8  664.69  5605.9  668.94  5681.2  670.95
#Mann= 5 ,-1 , 0
  3429.8      .1       0  4319.5     .08       0  4440.7      .1       0
  4982.5     .07       0    5009      .1       0
Bank Sta=4982.5,5009
XS Rating Curve= 0 ,0
Exp/Cntr=0.3,0.1

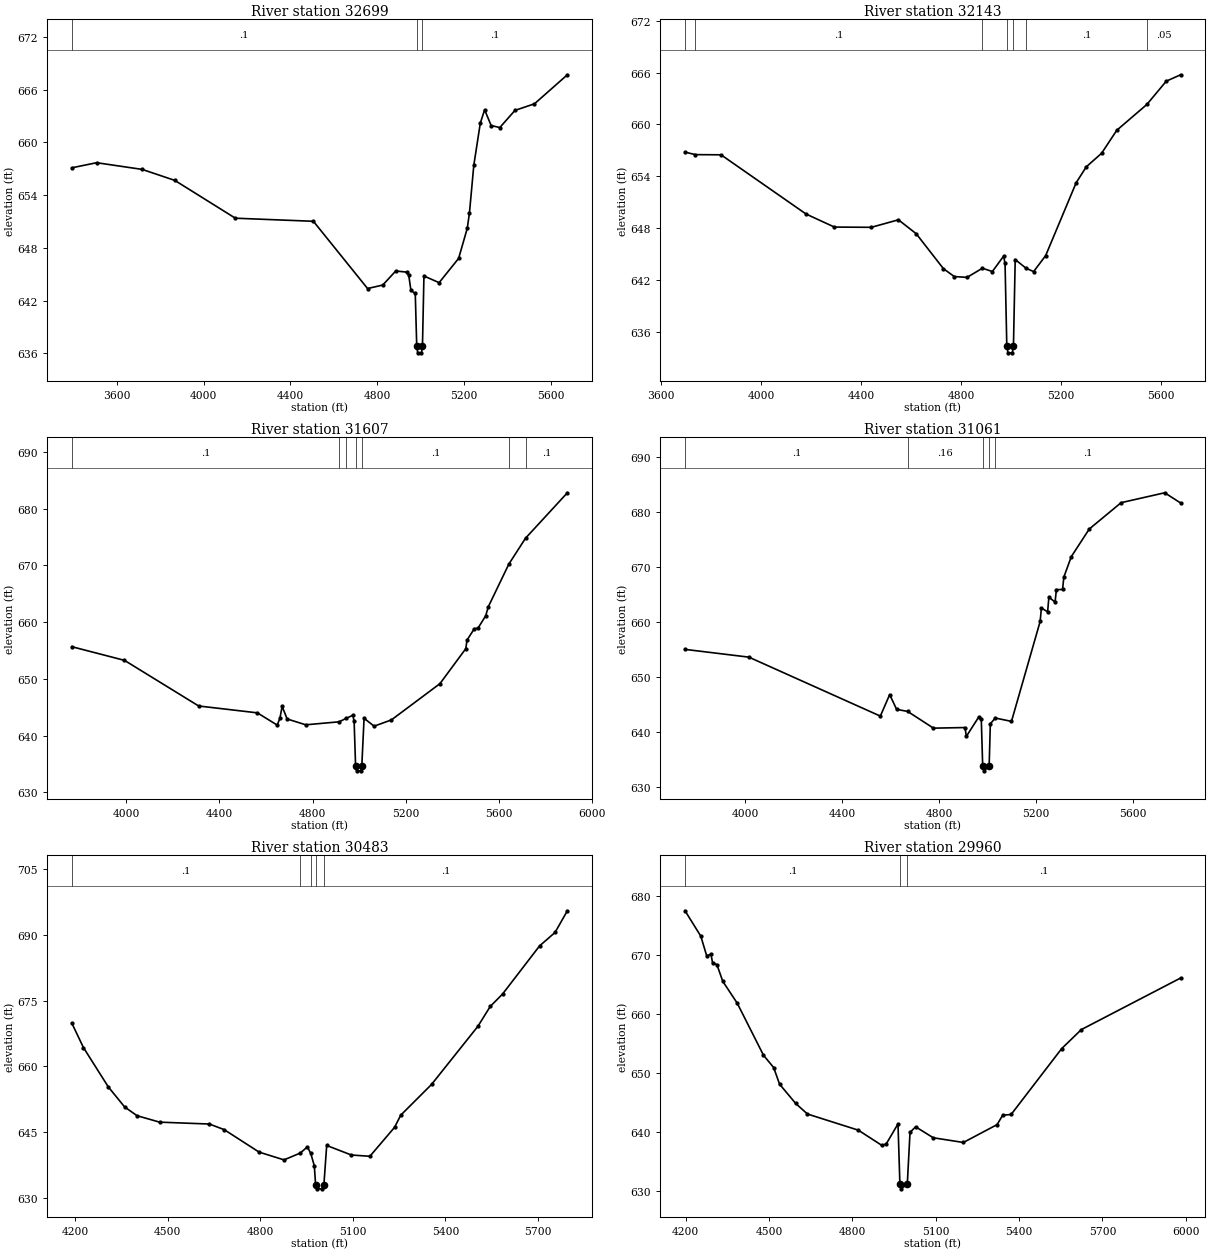
Type RM Length L Ch R = 1 ,32699   ,556,556,556
BEGIN DESCRIPTION:
SF PEREZ CREEK 32.0
END DESCRIPTION:
XS GIS Cut Line= 3
      1992069.77      13600085.8      1991486.39     13600091.01
       1989783.3     13600096.21
#Sta/Elev= 30
    3391   657.1  3505.8  657.68  3715.8  656.92  3866.3  655.67  4145.8  651.37
  4505.8  651.02  4755.8  643.37  4825.8  643.77  4885.8  645.37  4935.8  645.24
  4945.8  644.86  4955.8  643.16  4975.8  642.81  4982.5  636.86    4987  636.06
  5004.5  636.06    5009  636.86  5015.8   644.8  5085.8  644.04  5175.8   646.8
  5215.8  650.23  5225.8  651.98  5245.8  657.38  5275.8  662.18  5295.8   663.7
  5325.8  661.91  5365.8  661.68  5435.8  663.63  5525.8  664.38  5677.5  667.68
#Mann= 3 ,-1 , 0
    3391      .1       0  4982.5     .07       0    5009      .1       0
Bank Sta=4982.5,5009
XS Rating Curve= 0 ,0
Exp/Cntr=0.3,0.1

Type RM Length L Ch R = 1 ,32143   ,536,536,536
BEGIN DESCRIPTION:
SF PEREZ CREEK 31.0
END DESCRIPTION:
XS GIS Cut Line= 3
      1991889.16     13599898.29      1991168.69     13599698.64
      1989953.43     13599490.32
#Sta/Elev= 30
  3696.5  656.78  3738.2  656.49  3840.4  656.47  4180.1  649.61  4293.4   648.1
  4440.9  648.07  4549.3  648.94  4620.3  647.33  4729.4  643.27  4772.5  642.37
  4823.3  642.27  4884.9  643.33  4924.7  642.95  4969.6  644.73  4975.4  643.88
  4982.4  634.33    4987  633.53  5004.5  633.53    5009  634.33    5016  644.34
  5059.3  643.33  5089.6  642.94  5137.8   644.8  5259.5  653.23  5300.1  655.08
    5361  656.64  5421.9  659.31  5542.1   662.3  5619.7     665  5677.1  665.74
#Mann= 7 ,-1 , 0
  3696.5     .08       0  3738.2      .1       0  4884.9     .12       0
  4982.4     .07       0    5009     .12       0  5059.3      .1       0
  5542.1     .05       0
Bank Sta=4982.4,5009
XS Rating Curve= 0 ,0
Exp/Cntr=0.3,0.1

Type RM Length L Ch R = 1 ,31607   ,546,546,546
BEGIN DESCRIPTION:
Mapping XS 37d6787e
END DESCRIPTION:
XS GIS Cut Line= 2
      1991932.55     13599568.43      1989936.03     13598830.58
#Sta/Elev= 30
  3765.7  655.67  3992.1  653.26  4310.7  645.21  4562.7     644    4648  641.84
  4659.7  643.05  4669.3  645.14  4690.6  642.92  4770.7  641.89    4914  642.42
  4944.7  643.04  4972.9  643.57  4978.4  642.48  4984.7  634.57  4989.3  633.77
  5006.8  633.77  5011.3  634.57  5021.1  643.04  5064.2  641.65  5138.4  642.75
    5347  649.15    5458  655.33  5463.3  656.84  5493.8  658.79  5511.5  659.01
  5543.5  661.13  5554.6  662.71  5642.9  670.24  5714.4   674.8  5894.2  682.82
#Mann= 7 ,-1 , 0
  3765.7      .1       0    4914     .16       0  4944.7      .1       0
  4984.7     .07       0  5011.3      .1       0  5642.9     .05       0
  5714.4      .1       0
Bank Sta=4984.7,5011.3
XS Rating Curve= 0 ,0
Exp/Cntr=0.3,0.1

Type RM Length L Ch R = 1 ,31061   ,578,578,578
BEGIN DESCRIPTION:
SF PEREZ CREEK 30.0
END DESCRIPTION:
XS GIS Cut Line= 3
      1992210.39     13599238.59        1991075.       13598725.
      1990319.01     13598457.69
#Sta/Elev= 30
  3750.2  654.98  4013.9  653.57  4557.3  642.85  4595.9  646.76  4624.5  644.08
  4670.1   643.7  4776.8  640.66  4907.2  640.77  4912.7  639.16  4964.4  642.72
  4974.4  642.32  4980.3   633.7  4984.9   632.9  5006.9   633.7  5011.8  641.45
  5032.3   642.5  5099.2  641.89  5217.6  660.05  5222.9  662.51  5248.5   661.8
  5253.8  664.48  5279.4  663.57  5284.7  665.84  5310.3  665.87  5315.6  668.13
  5346.5  671.85  5420.6  676.86  5552.2  681.65  5732.4  683.45  5798.2  681.59
#Mann= 5 ,-1 , 0
  3750.2      .1       0  4670.1     .16       0  4980.3     .07       0
  5006.9     .16       0  5032.3      .1       0
Bank Sta=4980.3,5006.9
XS Rating Curve= 0 ,0
Exp/Cntr=0.3,0.1

Type RM Length L Ch R = 1 ,30483   ,523,523,523
BEGIN DESCRIPTION:
SF PEREZ CREEK 29.0
END DESCRIPTION:
XS GIS Cut Line= 3
      1992175.01       13598375.        1991375.       13598275.
      1990575.04       13598275.
#Sta/Elev= 30
  4189.1   669.9  4226.9  664.31  4307.5  655.33  4360.4  650.75  4400.7  648.75
  4473.8  647.28  4635.1  646.85  4682.9  645.58  4796.3  640.44  4876.9  638.67
  4929.9  640.23  4952.5  641.63  4963.5  640.19  4975.2  637.32  4979.5  632.86
  4984.1  632.06  5001.6  632.06  5006.1  632.86  5015.3  641.96  5095.3  639.78
  5155.3  639.49  5235.3   646.1  5255.3  648.87  5355.3   655.9  5505.3  669.15
  5545.3  673.68  5585.3  676.52  5705.3  687.51  5755.3  690.57  5795.3  695.52
#Mann= 5 ,-1 , 0
  4189.1      .1       0  4929.9     .16       0  4963.5      .1       0
  4979.5     .07       0  5006.1      .1       0
Bank Sta=4979.5,5006.1
XS Rating Curve= 0 ,0
Exp/Cntr=0.3,0.1

Type RM Length L Ch R = 1 ,29960   ,521,521,521
BEGIN DESCRIPTION:
SF PEREZ CREEK 28.0
END DESCRIPTION:
XS GIS Cut Line= 3
      1992346.44     13598291.06        1991675.       13597875.
       1990691.3     13597728.17
#Sta/Elev= 30
  4197.2  677.57    4254  673.26  4275.3  669.91  4290.6   670.2  4296.5  668.71
  4311.9  668.44  4333.1   665.6  4385.2  661.88  4479.7  653.05  4516.3  650.96
  4537.6  648.14  4595.5  644.87    4638  643.07  4821.1  640.33  4906.1  637.74
  4921.5  637.98    4964  641.39  4970.9  631.17  4975.4  630.37  4997.5  631.17
  5007.3  639.96  5027.5   640.9    5091  639.04  5199.4  638.24  5320.8  641.27
    5341  642.87  5371.3  642.99  5553.3  654.17  5624.1   657.4  5981.7  666.16
#Mann= 3 ,-1 , 0
  4197.2      .1       0  4970.9     .07       0  4997.5      .1       0
Bank Sta=4970.9,4997.5
XS Rating Curve= 0 ,0
Exp/Cntr=0.3,0.1

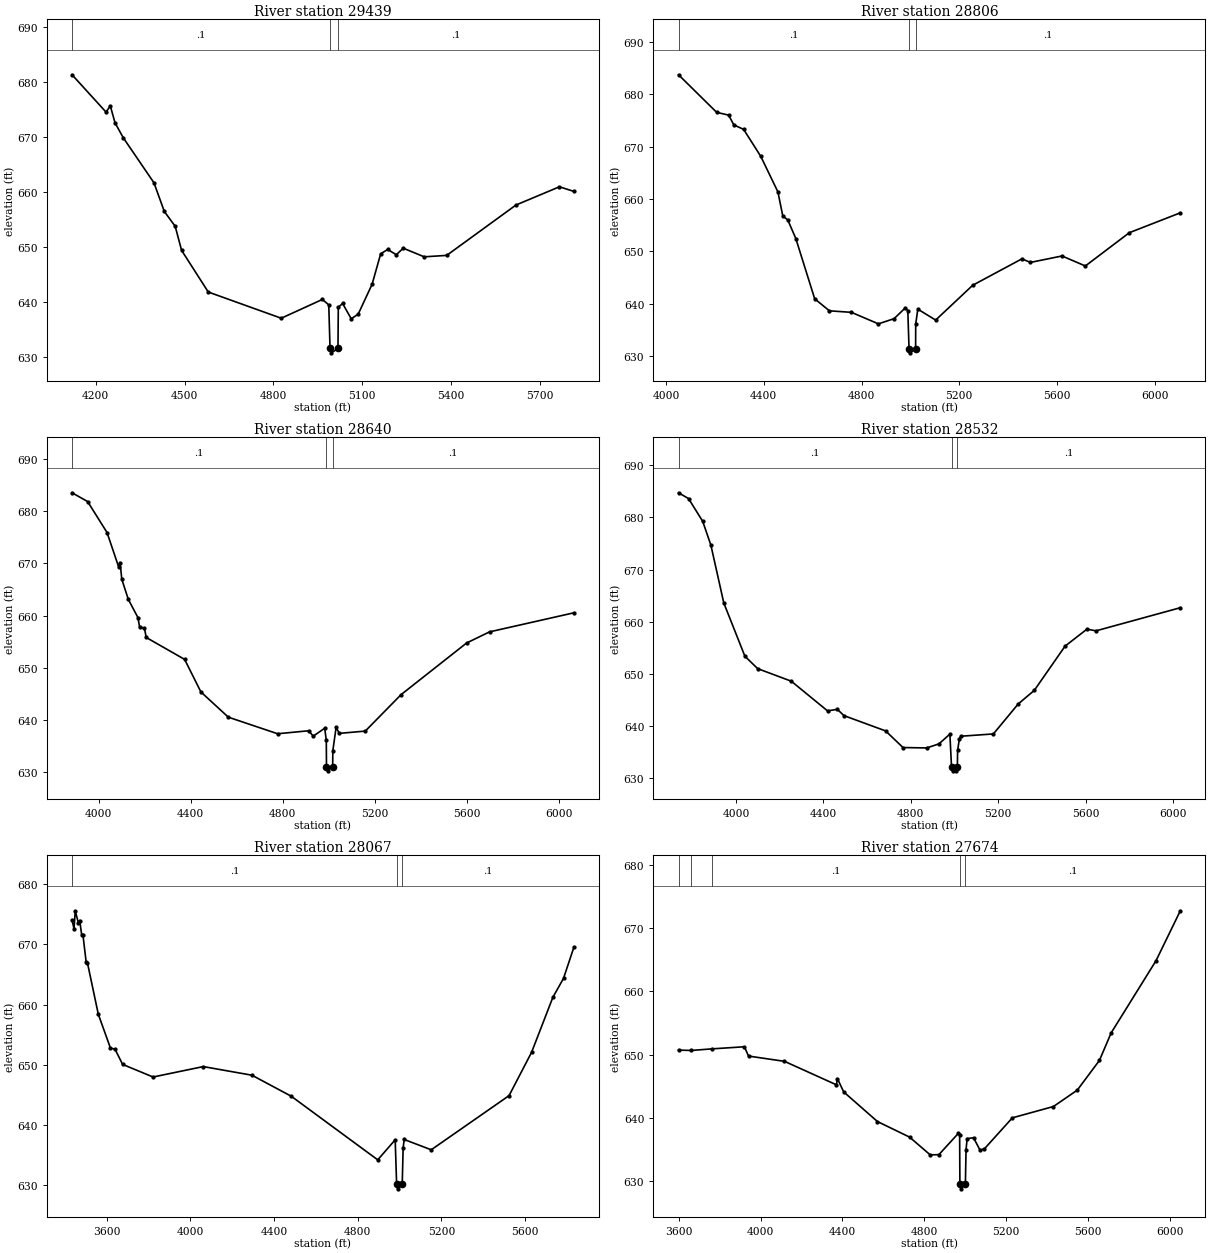
Type RM Length L Ch R = 1 ,29439   ,633,633,633
BEGIN DESCRIPTION:
SF PEREZ CREEK 27.0
END DESCRIPTION:
XS GIS Cut Line= 3
      1992443.66     13598284.09      1992009.64     13597539.33
      1991681.51     13596773.68
#Sta/Elev= 30
    4120   681.3  4234.7  674.51  4249.2  675.64    4265  672.57  4292.6  669.86
  4396.7  661.63  4431.5  656.43  4468.4  653.71  4489.9  649.34  4580.1  641.75
  4826.6  636.98  4965.5   640.4  4987.1  639.41  4991.4  631.48    4996  630.68
  5018.2  631.48  5019.3  638.97  5033.8  639.67  5062.9  636.88  5086.4  637.71
  5133.5  643.17  5162.5  648.71  5186.1   649.5  5215.2  648.54  5238.7  649.73
  5309.4  648.16  5385.5  648.42  5619.5  657.59  5766.3  660.91    5815  660.07
#Mann= 3 ,-1 , 0
    4120      .1       0  4991.4     .07       0  5018.2      .1       0
Bank Sta=4991.4,5018.2
XS Rating Curve= 0 ,0
Exp/Cntr=0.3,0.1

Type RM Length L Ch R = 1 ,28806   ,166,166,166
BEGIN DESCRIPTION:
SF PEREZ CREEK 26.0
END DESCRIPTION:
XS GIS Cut Line= 3
      1992504.44     13598320.56        1992575.       13597375.
      1992087.77     13596383.09
#Sta/Elev= 30
  4051.3  683.72  4207.3  676.54  4256.4  676.01  4277.5  674.14  4317.6  673.29
  4387.8  668.13    4458  661.33    4478  656.71  4498.1     656  4531.2  652.43
  4608.4  640.91  4668.6  638.61  4758.8  638.32  4869.1  636.12  4933.3  637.11
  4979.4  639.18  4989.5  638.66  4994.5  631.38  4999.1  630.58  5021.4  631.38
  5021.8  636.06  5030.4  638.93  5103.4  636.84  5255.2   643.5  5456.3  648.54
  5491.2  647.86  5620.5  649.09    5716  647.18  5895.9  653.54  6104.6  657.34
#Mann= 3 ,-1 , 0
  4051.3      .1       0  4994.5     .07       0  5021.4      .1       0
Bank Sta=4994.5,5021.4
XS Rating Curve= 0 ,0
Exp/Cntr=0.3,0.1

Type RM Length L Ch R = 1 ,28640   ,108,108,108
BEGIN DESCRIPTION:
Mapping XS fb901eca
END DESCRIPTION:
XS GIS Cut Line= 5
      1992523.56     13598318.82      1992763.12     13598100.09
      1992783.95      13597398.7      1992485.34     13597072.31
      1992464.55     13596358.48
#Sta/Elev= 30
  3883.8  683.53  3951.4  681.85  4035.9  675.91  4085.9  669.39  4092.7  670.16
  4100.1  666.95  4128.4   663.1  4170.4   659.6  4177.8  657.73  4198.7  657.61
  4206.1   655.8  4373.4  651.59  4444.2  645.35  4563.4  640.52  4777.7  637.34
  4912.8  637.91  4932.9  636.88  4982.7   638.4  4989.6   636.1  4990.4  631.03
    4995  630.23  5017.3  631.03    5018  634.07  5032.2  638.56  5046.4  637.41
  5159.2  637.85  5315.2  644.85  5599.7  654.73  5699.7  656.87  6066.4  660.52
#Mann= 3 ,-1 , 0
  3883.8      .1       0  4990.4     .07       0  5017.3      .1       0
Bank Sta=4990.4,5017.3
XS Rating Curve= 0 ,0
Exp/Cntr=0.3,0.1

Type RM Length L Ch R = 1 ,28532   ,465,465,465
BEGIN DESCRIPTION:
SF PEREZ CREEK 25.0
END DESCRIPTION:
XS GIS Cut Line= 5
      1992530.44     13598332.75      1992853.39      13598148.7
      1992915.89     13597423.01      1992596.45     13597013.29
      1992533.96     13596339.81
#Sta/Elev= 30
    3737  684.73  3782.7  683.62  3847.6  679.26    3885   674.7  3944.1  663.62
  4040.6  653.42  4099.1  651.04    4253  648.63  4418.7  642.95  4463.7  643.24
  4493.8  642.04  4684.5  639.11  4764.1  635.92  4872.6  635.85  4928.8  636.63
  4978.6   638.5    4986  632.26  4990.6  631.46  5008.2  631.46  5012.9  632.26
  5013.9  635.37    5022  637.55  5028.3  638.09  5177.6  638.53  5291.6  644.29
    5365  646.88  5505.6  655.35    5606  658.61    5647  658.28    6033  662.71
#Mann= 3 ,-1 , 0
    3737      .1       0    4986     .07       0  5012.9      .1       0
Bank Sta=4986,5012.9
XS Rating Curve= 0 ,0
Exp/Cntr=0.3,0.1

Type RM Length L Ch R = 1 ,28067   ,393,393,393
BEGIN DESCRIPTION:
SF PEREZ CREEK 24.0
END DESCRIPTION:
XS GIS Cut Line= 4
      1992644.21     13598356.16      1993362.94     13597918.67
      1993201.48     13596955.13        1992875.       13596475.
#Sta/Elev= 30
  3434.5  674.04  3443.8   672.6  3449.7  675.59  3465.1   673.5    3471  673.97
  3480.6  671.57  3486.5  671.59  3501.9  667.05  3507.8  666.98    3560  658.41
  3618.2  652.78  3639.5  652.63  3676.3  650.09  3821.8     648  4061.8  649.73
  4294.3   648.3  4482.4  644.81  4895.9  634.25  4979.3  637.58  4986.1  630.24
  4990.7  629.44    5013  630.24  5017.3  636.24  5022.4  637.63  5151.6  635.92
  5523.7  644.91  5631.5  652.11  5733.2  661.23  5784.1  664.38  5833.5  669.52
#Mann= 3 ,-1 , 0
  3434.5      .1       0  4986.1     .07       0    5013      .1       0
Bank Sta=4986.1,5013
XS Rating Curve= 0 ,0
Exp/Cntr=0.3,0.1

Type RM Length L Ch R = 1 ,27674   ,757,757,757
BEGIN DESCRIPTION:
SF PEREZ CREEK 23.0
END DESCRIPTION:
XS GIS Cut Line= 3
      1993577.77     13598406.56      1993772.23     13597649.57
      1993231.21     13596068.12
#Sta/Elev= 30
  3599.1  650.72    3662  650.67  3762.9  650.92  3920.8  651.25  3941.4  649.78
  4116.9  648.95  4370.8  645.24    4376  646.21  4406.6  644.11  4571.7  639.43
  4728.2  636.98  4829.4  634.17  4871.7   634.2  4966.8  637.56  4973.3   637.3
  4974.5   629.6  4979.1   628.8  5001.4   629.6  5004.6     635  5009.9  636.73
  5041.2  636.88  5072.5  634.94  5093.2  635.08    5231  640.02  5431.8  641.81
  5548.1  644.39  5656.6  649.09  5713.9  653.44  5933.1  664.84  6052.1  672.74
#Mann= 5 ,-1 , 0
  3599.1      .1       0    3662     .08       0  3762.9      .1       0
  4974.5     .07       0  5001.4      .1       0
Bank Sta=4974.5,5001.4
XS Rating Curve= 0 ,0
Exp/Cntr=0.3,0.1

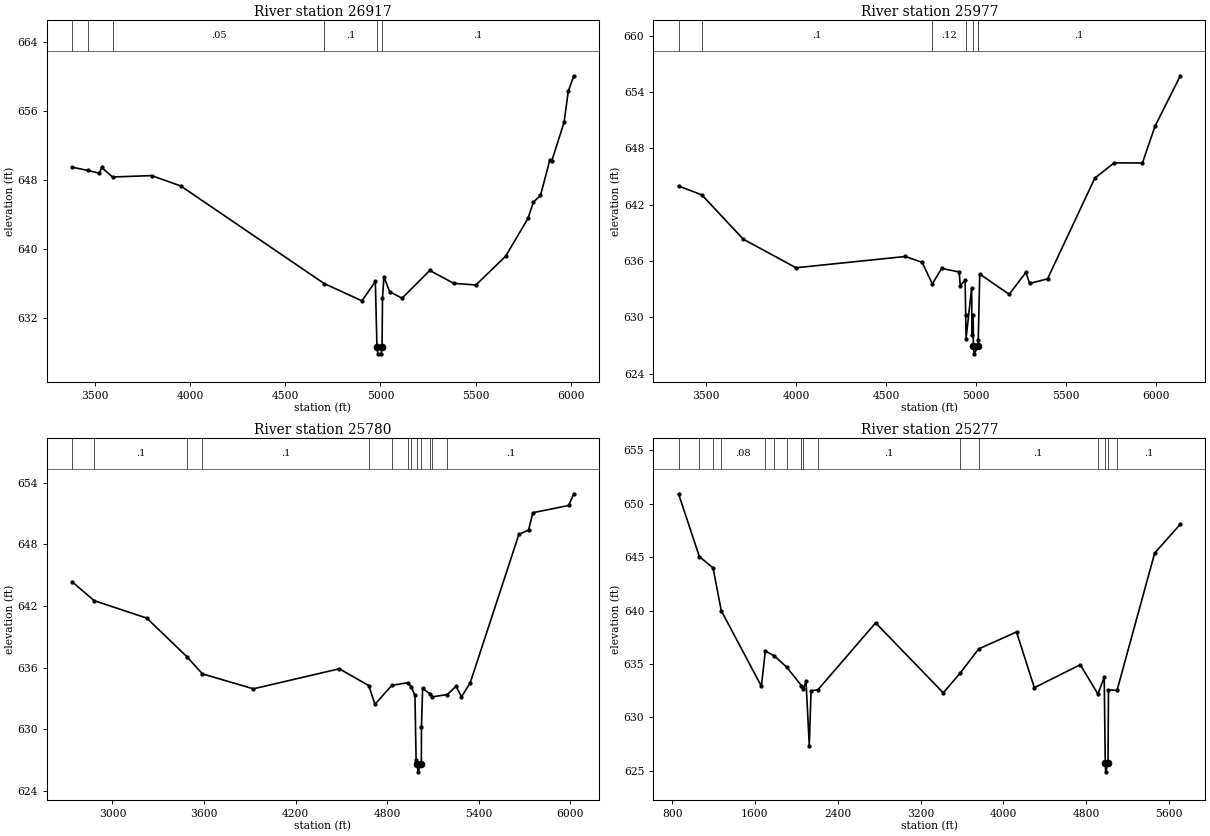
Type RM Length L Ch R = 1 ,26917   ,940,940,940
BEGIN DESCRIPTION:
SF PEREZ CREEK 22.0
END DESCRIPTION:
XS GIS Cut Line= 3
      1994188.89     13598378.77       1994376.4     13597080.13
      1993725.02     13595925.04
#Sta/Elev= 30
  3378.7  649.49    3461  649.11  3522.7  648.79  3534.1  649.46  3591.4  648.35
  3796.8  648.51  3949.8  647.31  4704.7  635.96  4902.5  633.96  4973.2  636.21
  4981.7   628.6  4986.4   627.8    5004   627.8  5008.6   628.6  5010.8  634.26
  5018.2  636.74  5048.4  635.02  5113.4  634.27  5259.2  637.49  5385.5  635.99
  5501.9   635.8    5658  639.14  5775.9  643.54  5803.9  645.43  5841.5  646.21
  5890.7  650.34  5900.7   650.2  5965.7  654.73  5987.3   658.3  6016.9  660.11
#Mann= 6 ,-1 , 0
  3378.7      .1       0    3461     .08       0  3591.4     .05       0
  4704.7      .1       0  4981.7     .07       0  5008.6      .1       0
Bank Sta=4981.7,5008.6
XS Rating Curve= 0 ,0
Exp/Cntr=0.3,0.1

Type RM Length L Ch R = 1 ,25977   ,197,197,197
BEGIN DESCRIPTION:
SF PEREZ CREEK 21.0
END DESCRIPTION:
XS GIS Cut Line= 3
      1995269.83     13597838.77      1994790.19     13596282.72
      1993883.77     13595559.63
#Sta/Elev= 30
  3346.9  643.99  3476.1  643.05  3706.6  638.33  3999.6  635.29  4607.1  636.49
  4699.9  635.87  4757.2  633.57  4808.4  635.22  4906.4  634.84  4911.6  633.38
    4939  633.97  4942.2  630.21  4944.3  627.75  4975.2  633.13  4977.5  628.12
  4983.9  630.27  4984.9  626.93  4989.5  626.13  5011.8  626.93  5012.1   627.6
  5020.2  634.62  5184.1  632.46  5276.1  634.79  5297.8  633.62    5397  634.11
  5659.8  644.83  5766.9  646.45  5923.9  646.44  5994.3  650.36  6134.7  655.72
#Mann= 7 ,-1 , 0
  3346.9     .05       0  3476.1      .1       0  4757.2     .12       0
  4942.2     .16       0  4984.9     .07       0  5011.8     .16       0
  5012.1      .1       0
Bank Sta=4984.9,5011.8
XS Rating Curve= 0 ,0
Exp/Cntr=0.3,0.1

Type RM Length L Ch R = 1 ,25780   ,503,503,503
BEGIN DESCRIPTION:
SF PEREZ CREEK 500.0
END DESCRIPTION:
XS GIS Cut Line= 4
      1996686.51     13597159.97      1996512.89     13596960.32
      1995340.81     13596576.65      1993986.63     13595404.77
#Sta/Elev= 30
  2735.1  644.37  2879.9  642.53  3224.7  640.83  3487.2  637.08  3589.7   635.4
  3923.4  633.95  4486.5   635.9  4679.8  634.26  4720.1  632.44  4831.1  634.29
  4934.6  634.54  4957.7  634.16  4982.2  633.31  4989.9  627.02  4997.3  626.67
  5001.9  625.87  5024.2  626.67    5025  630.25  5032.6  633.99  5083.1  633.43
  5096.9  633.17  5194.2  633.39    5252   634.2  5287.1  633.17  5344.2  634.52
  5663.3  648.97  5726.9   649.4  5755.4  651.09  5989.1  651.79  6023.8  652.93
#Mann= 13 ,-1 , 0
  2735.1     .05       0  2879.9      .1       0  3487.2     .08       0
  3589.7      .1       0  4679.8     .12       0  4831.1     .16       0
  4934.6      .1       0  4957.7     .16       0  4997.3     .07       0
  5024.2     .16       0  5083.1      .1       0  5096.9     .16       0
  5194.2      .1       0
Bank Sta=4997.3,5024.2
XS Rating Curve= 0 ,0
Exp/Cntr=0.3,0.1

Type RM Length L Ch R = 1 ,25277   ,1561,1561,1561
BEGIN DESCRIPTION:
SF PEREZ CREEK 20.0
END DESCRIPTION:
XS GIS Cut Line= 3
      1998598.59     13597142.62      1995223.62     13595802.35
      1994113.29     13595309.64
#Sta/Elev= 30
   862.3  650.94  1063.2  645.06  1195.3     644  1275.1  639.99  1662.4  632.92
  1700.4  636.23  1788.3  635.75  1909.6  634.68  2049.6  632.97  2068.8  632.64
  2093.4   633.4    2125  627.36    2142  632.48  2208.7  632.59  2765.6  638.85
  3418.9   632.3  3582.4  634.15  3760.7  636.41  4126.3     638  4298.5  632.78
  4742.1  634.93  4912.1  632.19  4973.5  633.75  4983.3   625.7  4987.9   624.9
  5010.2   625.7  5014.5  632.58  5096.8  632.52  5460.7  645.39  5708.4  648.09
#Mann= 16 ,-1 , 0
   862.3      .1       0  1063.2     .08       0  1195.3      .1       0
  1275.1     .08       0  1700.4      .1       0  1788.3     .08       0
  1909.6     .05       0  2049.6      .1       0  2068.8     .05       0
  2208.7      .1       0  3582.4     .05       0  3760.7      .1       0
  4912.1     .12       0  4983.3     .07       0  5010.2     .12       0
  5096.8      .1       0
Bank Sta=4983.3,5010.2
XS Rating Curve= 0 ,0
Exp/Cntr=0.3,0.1