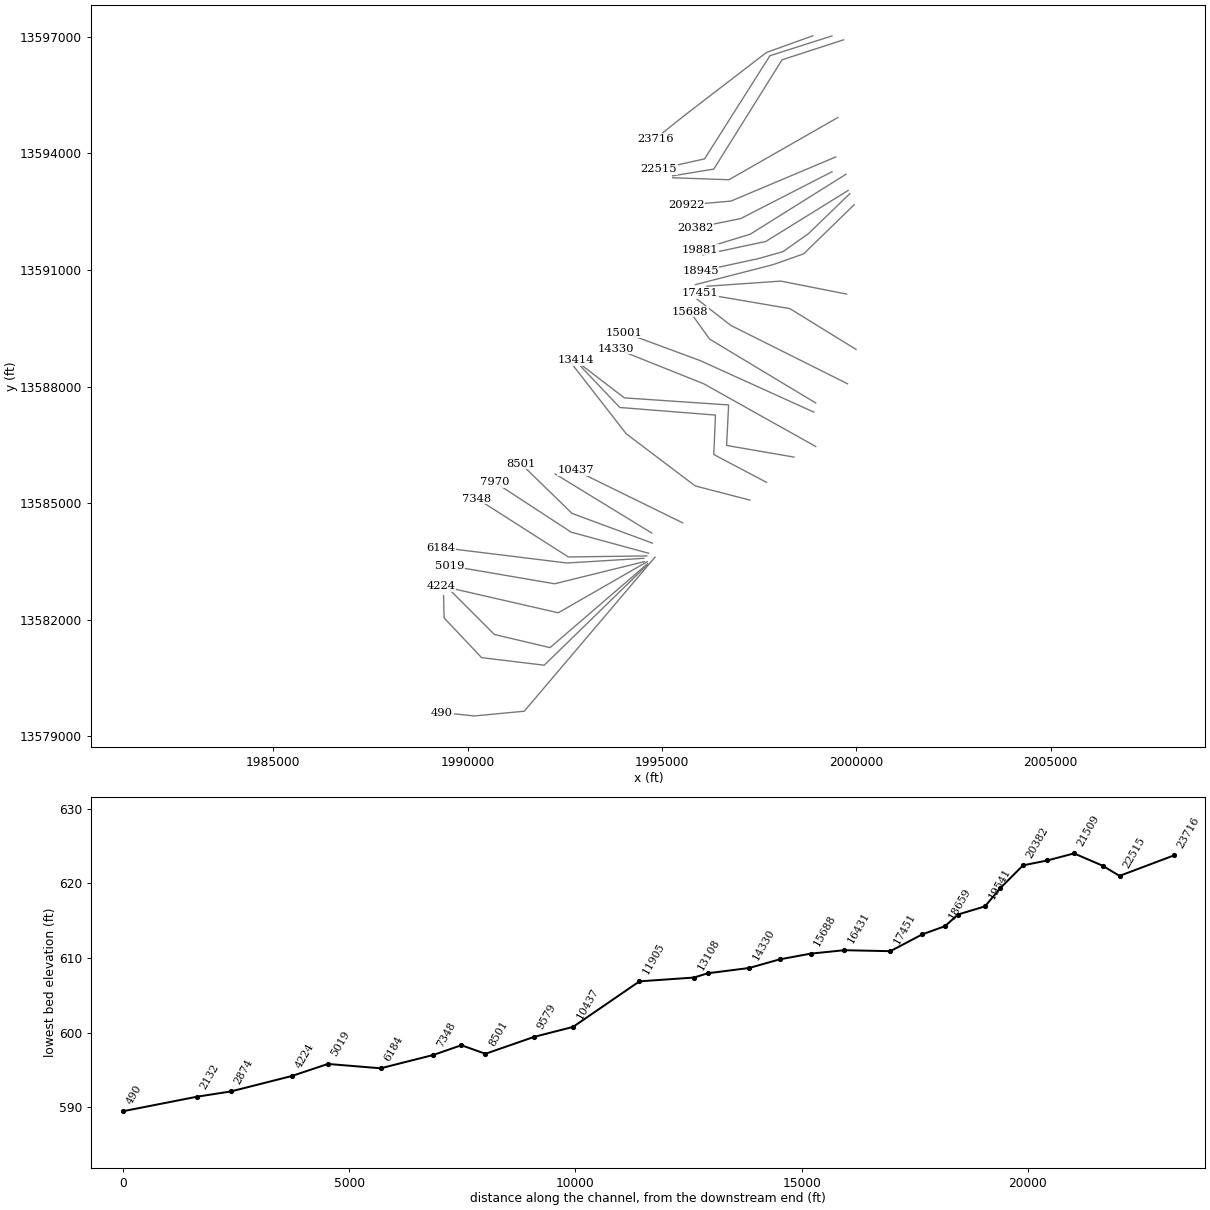
HEC-RAS study SF PEREZ CREEK.prj: SF PEREZ CREEK Base Level Engineering

--- SF PEREZ CREEK.g01 (geometry) --- (continued)

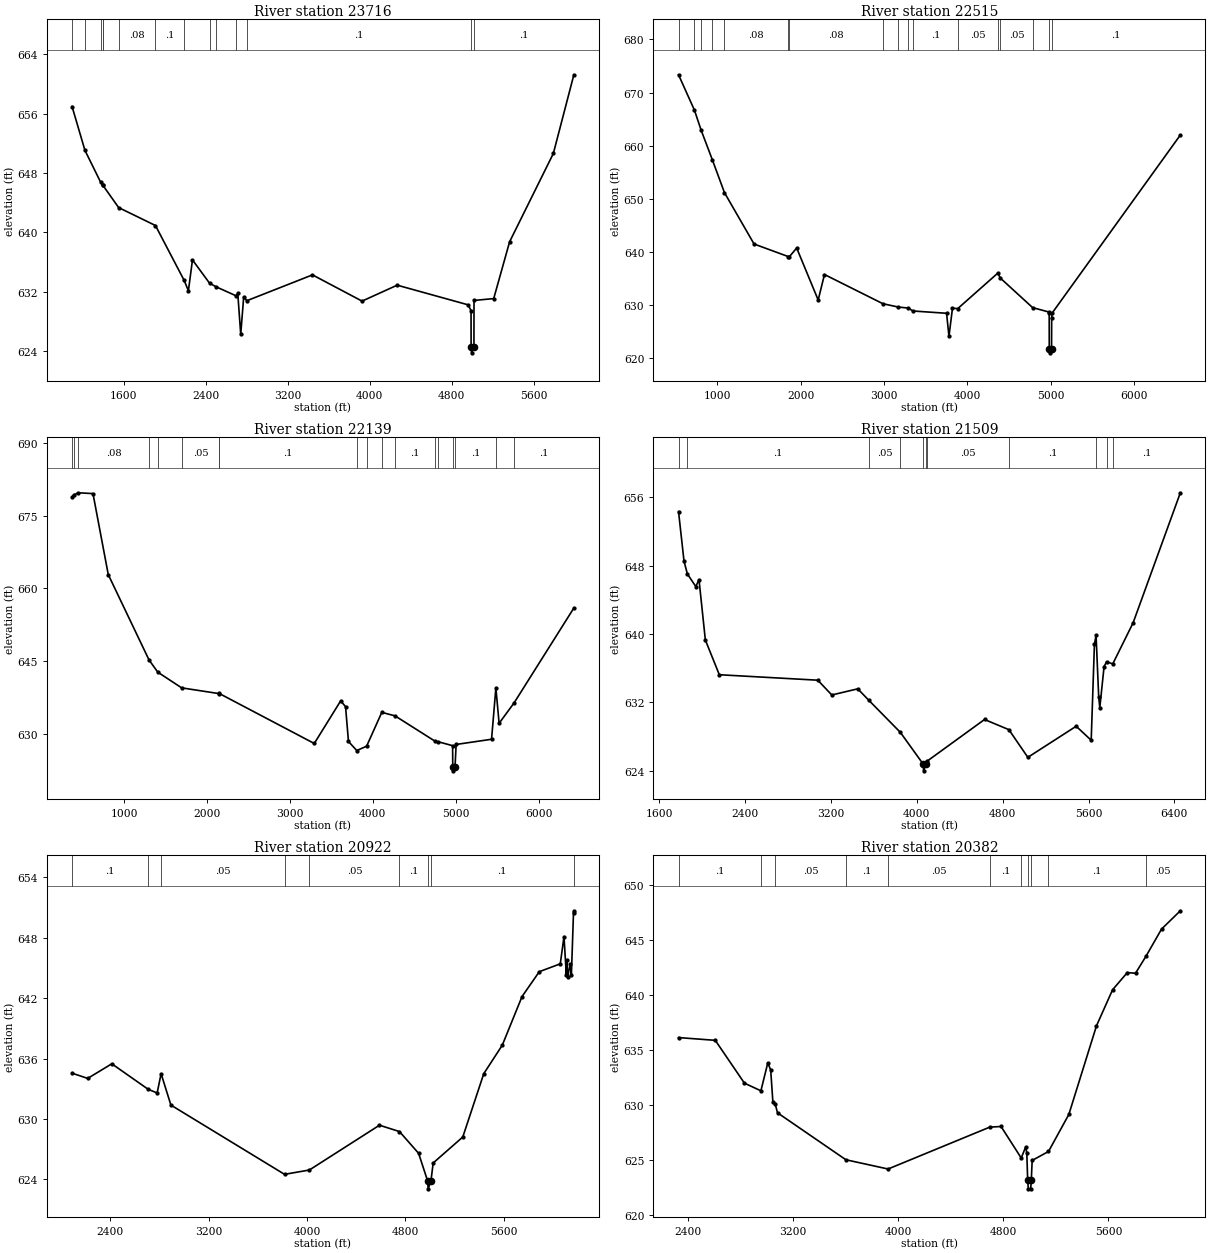
Type RM Length L Ch R = 1 ,23716   ,1201,1201,1201
BEGIN DESCRIPTION:
SF PEREZ CREEK 19.0
END DESCRIPTION:
XS GIS Cut Line= 4
      1998882.61     13597029.19      1997688.18     13596598.64
        1995575.       13594975.      1994825.03     13594375.02
#Sta/Elev= 30
  1097.5  656.96  1222.8  651.06  1376.7  646.74  1394.6  646.35  1397.5  646.35
  1551.9  643.33    1911  640.91  2190.4  633.52  2232.3  632.11  2272.1  636.27
  2438.5  633.13  2502.3  632.64  2698.3  631.42  2713.8  631.77  2742.8  626.23
  2771.8   631.3    2802  630.76  3442.5  634.25  3926.4  630.71    4269  632.86
  4960.5  630.21  4989.5  629.43  4990.2  624.53  4995.1  623.73  5017.7  624.53
  5018.5   630.8  5210.6  631.05  5365.8  638.72  5792.4  650.63  5992.5  661.25
#Mann= 14 ,-1 , 0
  1097.5      .1       0  1222.8     .08       0  1376.7      .1       0
  1394.6     .15       0  1397.5      .1       0  1551.9     .08       0
    1911      .1       0  2190.4     .08       0  2438.5     .05       0
  2502.3      .1       0  2698.3     .05       0    2802      .1       0
  4990.2     .07       0  5017.7      .1       0
Bank Sta=4990.2,5017.7
XS Rating Curve= 0 ,0
Exp/Cntr=0.3,0.1

Type RM Length L Ch R = 1 ,22515   ,376,376,376
BEGIN DESCRIPTION:
SF PEREZ CREEK 17.0
END DESCRIPTION:
XS GIS Cut Line= 4
      1999374.97     13597024.99      1997778.46     13596515.31
       1996097.9     13593862.53       1994924.3     13593598.65
#Sta/Elev= 30
   535.2  673.35   726.5  666.67   805.5  662.95     940  657.37  1086.3  651.15
  1441.3  641.48  1851.2  639.12  1863.1  639.06  1952.3  640.73  2210.3  630.94
  2285.7  635.74  2986.7  630.24  3171.5  629.61  3292.9  629.42  3346.2  628.87
  3750.4  628.44  3778.9  624.11  3821.4   629.4  3884.4  629.32  4364.2  635.99
  4397.2  635.04  4782.9   629.5  4974.7  628.69  4981.5   628.4  4982.1  621.79
    4987  620.99  5009.6  621.79  5011.1   627.6    5017  628.49  6554.3     662
#Mann= 17 ,-1 , 0
   535.2     .08       0   726.5     .05       0   805.5     .08       0
     940      .1       0  1086.3     .08       0  1851.2      .1       0
  1863.1     .08       0  2986.7     .16       0  3171.5      .1       0
  3292.9     .05       0  3346.2      .1       0  3884.4     .05       0
  4364.2     .08       0  4397.2     .05       0  4782.9      .1       0
  4982.1     .07       0  5009.6      .1       0
Bank Sta=4982.1,5009.6
XS Rating Curve= 0 ,0
Exp/Cntr=0.3,0.1

Type RM Length L Ch R = 1 ,22139   ,630,630,630
BEGIN DESCRIPTION:
SF PEREZ CREEK 16.0
END DESCRIPTION:
XS GIS Cut Line= 4
      1999674.98     13596924.99      1998090.96     13596411.14
      1996334.01     13593598.64      1995275.01       13593425.
#Sta/Elev= 30
   371.1  678.83   388.4  679.21   445.8  679.69   623.4  679.52     808  662.81
  1299.5  645.23  1405.6   642.7  1693.3  639.47  2145.9  638.28  2146.9  638.31
  3293.5     628  3611.8  636.78  3670.8  635.61  3706.1  628.42    3806  626.55
  3924.7  627.43  4108.4  634.42  4268.4  633.69  4754.3  628.43  4789.7  628.35
  4962.8  627.55  4964.4  623.16  4969.2  622.36  4991.9  623.16  5005.3   627.8
  5432.6  628.87  5484.7  639.44  5523.8  632.16  5704.1  636.36  6425.7  655.93
#Mann= 18 ,-1 , 0
   371.1     .08       0   388.4     .05       0   445.8     .08       0
  1299.5      .1       0  1405.6     .08       0  1693.3     .05       0
  2145.9     .08       0  2146.9      .1       0    3806     .12       0
  3924.7      .1       0  4108.4     .05       0  4268.4      .1       0
  4754.3     .05       0  4789.7      .1       0  4964.4     .07       0
  4991.9      .1       0  5484.7     .08       0  5704.1      .1       0
Bank Sta=4964.4,4991.9
XS Rating Curve= 0 ,0
Exp/Cntr=0.3,0.1

Type RM Length L Ch R = 1 ,21509   ,587,587,587
BEGIN DESCRIPTION:
SF PEREZ CREEK 15.0
END DESCRIPTION:
XS GIS Cut Line= 3
      1999524.97     13594924.98        1996725.       13593325.
      1995275.03       13593375.
#Sta/Elev= 30
  1779.2  654.35  1830.3  648.54  1861.9  647.04  1940.4  645.57  1969.9  646.39
    2029  639.32  2159.2  635.25    3077  634.61  3207.3  632.88  3449.2   633.6
  3551.3  632.27  3846.4   628.5  4058.1   624.8  4062.9     624  4085.7   624.8
  4091.8   625.1  4630.5  630.01  4857.5  628.82  5034.1  625.58  5484.4  629.22
  5624.4  627.58  5654.5  638.82  5669.8  639.86  5694.5  632.62  5704.5  631.39
  5744.5  636.21  5768.3  636.77  5825.4  636.52  6014.7  641.32  6454.9  656.55
#Mann= 11 ,-1 , 0
  1779.2     .05       0  1861.9      .1       0  3551.3     .05       0
  3846.4      .1       0  4058.1     .07       0  4085.7      .1       0
  4091.8     .05       0  4857.5      .1       0  5669.8     .08       0
  5768.3     .05       0  5825.4      .1       0
Bank Sta=4058.1,4085.7
XS Rating Curve= 0 ,0
Exp/Cntr=0.3,0.1

Type RM Length L Ch R = 1 ,20922   ,540,540,540
BEGIN DESCRIPTION:
SF PEREZ CREEK 14.0
END DESCRIPTION:
XS GIS Cut Line= 3
      1999472.88     13593911.13        1996775.       13592775.
      1995624.98       13592675.
#Sta/Elev= 30
  2089.8  634.55  2216.9  634.03    2413  635.48  2708.7  632.95  2781.9  632.58
    2814   634.5  2893.7  631.38  3818.1   624.5    4020  624.93  4590.3  629.38
  4752.9  628.75  4908.6  626.59  4981.6  623.86  4986.5  623.06  5009.2  623.86
  5027.2  625.63  5268.1  628.21  5438.7   634.5  5589.3  637.33  5749.9  642.16
  5890.4  644.63  6061.1  645.41  6091.2  648.12    6110  644.35    6115  645.82
  6121.3  644.09  6141.4  645.42  6151.4  644.29  6168.6   650.5  6171.5  650.68
#Mann= 9 ,-1 , 0
  2089.8      .1       0  2708.7     .08       0    2814     .05       0
  3818.1      .1       0    4020     .05       0  4752.9      .1       0
  4981.6     .07       0  5009.2      .1       0  6168.6     .08       0
Bank Sta=4981.6,5009.2
XS Rating Curve= 0 ,0
Exp/Cntr=0.3,0.1

Type RM Length L Ch R = 1 ,20382   ,501,501,501
BEGIN DESCRIPTION:
SF PEREZ CREEK 13.0
END DESCRIPTION:
XS GIS Cut Line= 3
       1999375.7     13593529.21        1997025.       13592325.
      1995869.39     13592091.83
#Sta/Elev= 30
    2327  636.13  2606.7  635.88  2828.8  631.99  2954.1   631.3  3006.4  633.83
  3028.6  633.19  3045.2   630.3  3062.9   630.1  3080.6   629.3    3601  625.04
  3922.2   624.2    4696     628  4782.3  628.06  4935.8   625.2  4970.8  626.23
  4978.4  625.61    4985   623.2  4989.9   622.4  5007.8   622.4  5012.6   623.2
  5019.2  624.98  5143.5  625.79  5298.3  629.15  5508.9   637.2  5631.3  640.47
  5743.5  642.03  5806.1  641.97    5886  643.52  6004.2  645.98  6147.1  647.64
#Mann= 11 ,-1 , 0
    2327      .1       0  2954.1     .08       0  3062.9     .05       0
    3601      .1       0  3922.2     .05       0    4696      .1       0
  4935.8     .16       0    4985     .07       0  5012.6     .16       0
  5143.5      .1       0    5886     .05       0
Bank Sta=4985,5012.6
XS Rating Curve= 0 ,0
Exp/Cntr=0.3,0.1

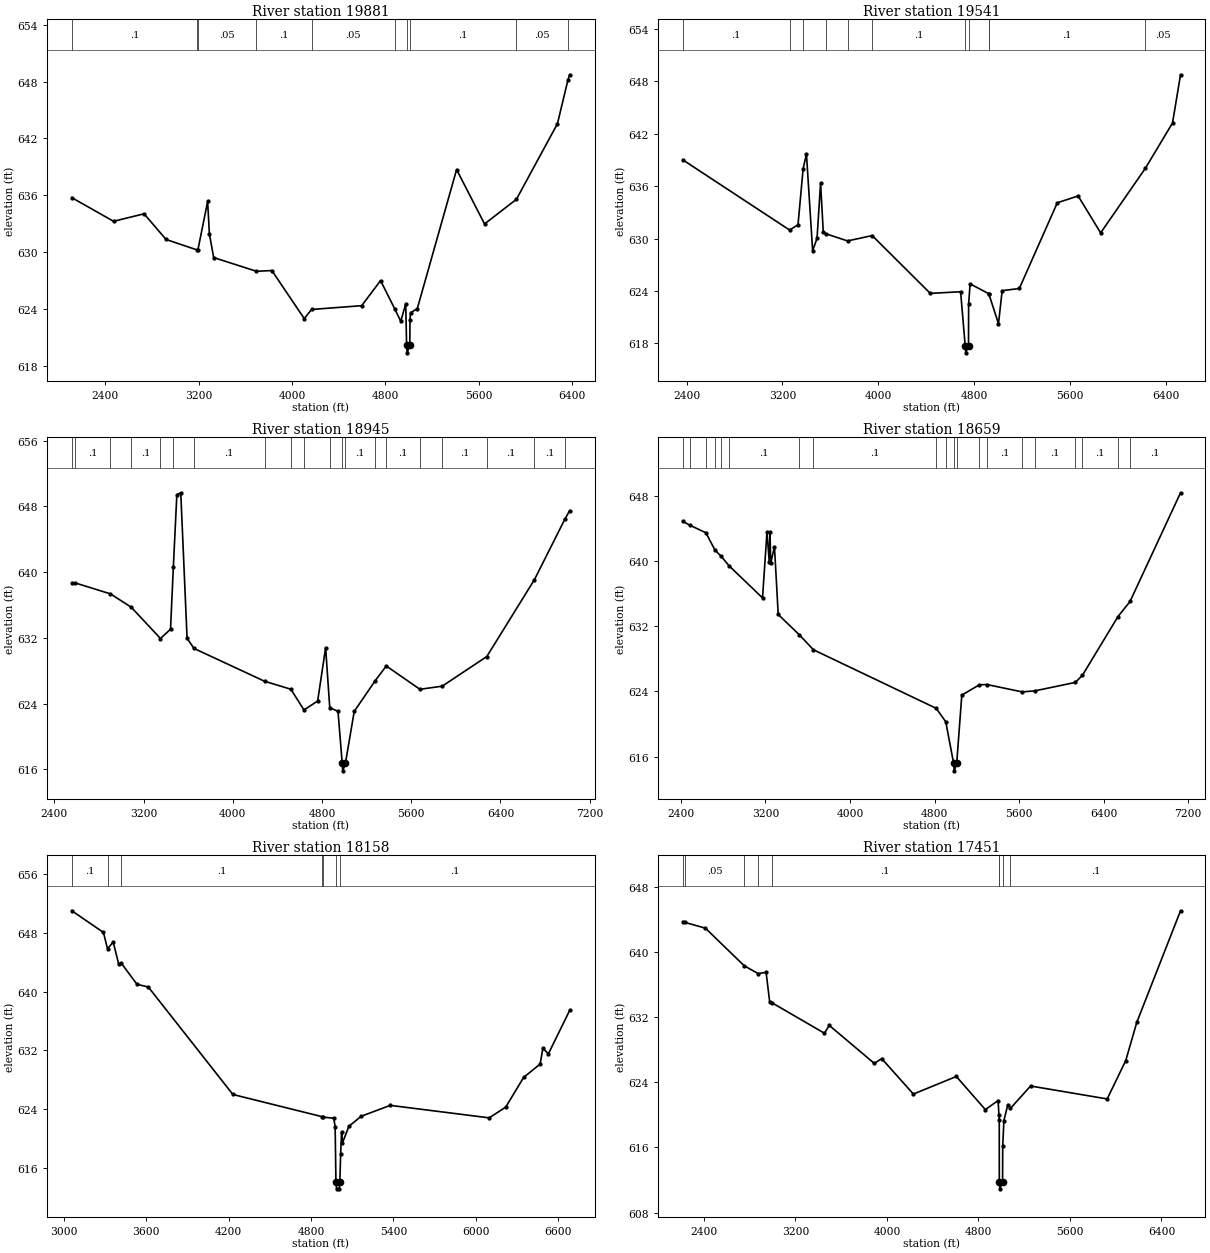
Type RM Length L Ch R = 1 ,19881   ,340,340,340
BEGIN DESCRIPTION:
SF PEREZ CREEK 12.0
END DESCRIPTION:
XS GIS Cut Line= 3
      1999736.78     13593466.69        1997275.       13591925.
      1995975.03     13591525.01
#Sta/Elev= 30
  2113.7  635.74  2470.6  633.25  2732.2  634.04  2920.8  631.33  3185.5  630.23
  3194.2  630.27  3276.8  635.34  3292.1   631.9  3328.7  629.42  3695.5  627.97
  3827.3  628.05  4104.3  622.98  4167.9  623.94    4597  624.34  4758.5  626.99
  4881.6  623.96  4931.7  622.69  4974.2  624.54  4981.6  620.16  4986.5  619.36
  5009.2  620.16  5010.7  622.84  5015.4   623.6  5072.7  624.01  5410.1  638.71
  5649.4  632.97  5922.4  635.57  6273.9  643.55  6363.9  648.17  6378.5  648.72
#Mann= 10 ,-1 , 0
  2113.7      .1       0  3185.5     .08       0  3194.2     .05       0
  3695.5      .1       0  4167.9     .05       0  4881.6      .1       0
  4981.6     .07       0  5009.2      .1       0  5922.4     .05       0
  6363.9      .1       0
Bank Sta=4981.6,5009.2
XS Rating Curve= 0 ,0
Exp/Cntr=0.3,0.1

Type RM Length L Ch R = 1 ,19541   ,596,596,596
BEGIN DESCRIPTION:
SF PEREZ CREEK 11.0
END DESCRIPTION:
XS GIS Cut Line= 3
      1999792.33     13593050.02      1997674.29     13591737.53
      1996049.69      13591390.4
#Sta/Elev= 30
    2368  639.02  3258.9  630.98  3329.5  631.57  3372.4  638.02  3400.1  639.67
  3451.6  628.61  3488.2  630.01  3517.8  636.34  3540.3  630.77  3559.1  630.56
  3742.9  629.73  3948.6  630.34  4433.4  623.72  4686.2  623.91  4724.5  617.71
  4729.3  616.91  4752.1  617.71    4753  622.45  4765.4  624.81  4921.2  623.68
  4921.6  623.67  5002.2  620.25  5032.8  624.03    5176  624.28    5493   634.1
  5666.8  634.88  5854.5  630.65  6227.2  638.04  6454.2  643.24    6521  648.76
#Mann= 11 ,-1 , 0
    2368      .1       0  3258.9     .08       0  3372.4     .05       0
  3559.1      .1       0  3742.9     .05       0  3948.6      .1       0
  4724.5     .07       0  4752.1      .1       0  4921.2     .05       0
  4921.6      .1       0  6227.2     .05       0
Bank Sta=4724.5,4752.1
XS Rating Curve= 0 ,0
Exp/Cntr=0.3,0.1

Type RM Length L Ch R = 1 ,18945   ,286,286,286
BEGIN DESCRIPTION:
SF PEREZ CREEK 10.0
END DESCRIPTION:
XS GIS Cut Line= 5
      1999833.98     13592966.67      1998771.51     13591938.92
      1998111.79     13591473.64       1997472.9     13591293.09
      1995993.71     13590973.64
#Sta/Elev= 30
  2557.6  638.64    2590  638.67  2903.6  637.35  3090.5  635.72  3351.9  631.92
  3442.1  633.05  3467.5  640.66  3498.7   649.4  3533.9  649.65  3590.5  631.94
  3652.7  630.71  4285.1  626.72  4520.6  625.75  4638.4  623.23  4761.1  624.31
  4832.6   630.8  4869.7   623.5  4943.7  623.06  4981.4  616.72  4986.5  615.82
  5009.9  616.72  5089.2  623.06    5275  626.74  5376.3  628.58    5678  625.74
  5877.9  626.12  6277.8  629.73  6705.1  639.09  6977.6  646.44  7020.3  647.47
#Mann= 20 ,-1 , 0
  2557.6     .05       0    2590      .1       0  2903.6     .05       0
  3090.5      .1       0  3351.9     .08       0  3467.5     .05       0
  3652.7      .1       0  4285.1      .1       0  4520.6      .1       0
  4638.4     .05       0  4869.7     .05       0  4981.4     .07       0
  5009.9      .1       0    5275     .05       0  5376.3      .1       0
    5678     .05       0  5877.9      .1       0  6277.8      .1       0
  6705.1      .1       0  6977.6     .05       0
Bank Sta=4981.4,5009.9
XS Rating Curve= 0 ,0
Exp/Cntr=0.3,0.1

Type RM Length L Ch R = 1 ,18659   ,501,501,501
BEGIN DESCRIPTION:
Mapping XS ea8d5b99
END DESCRIPTION:
XS GIS Cut Line= 4
      1999945.15       13592682.      1998646.51     13591418.09
      1997861.79     13591140.31      1995861.75     13590626.41
#Sta/Elev= 30
    2418  644.85  2490.7  644.34  2636.7  643.45  2722.1  641.34  2782.7  640.54
  2855.4  639.41  3172.6  635.46    3215  643.58  3236.3  639.88  3243.3   643.5
  3250.5  639.71  3285.7  641.74  3321.2  633.43  3521.4  630.93  3654.7   629.1
  4816.4  621.92  4906.4  620.27  4981.3  615.16  4986.4  614.26  5009.8  615.16
  5058.2  623.55  5225.3  624.81  5296.4  624.84  5628.3  623.94  5747.6  624.06
  6132.1   625.1  6198.8  625.96  6535.2  633.16  6650.1  635.03  7127.6  648.35
#Mann= 20 ,-1 , 0
    2418      .1       0  2490.7     .08       0  2636.7     .08       0
  2722.1      .1       0  2782.7     .05       0  2855.4      .1       0
  3521.4     .08       0  3654.7      .1       0  4816.4     .08       0
  4906.4      .1       0  4981.3     .07       0  5009.8      .1       0
  5225.3     .05       0  5296.4      .1       0  5628.3     .05       0
  5747.6      .1       0  6132.1     .08       0  6198.8      .1       0
  6535.2     .05       0  6650.1      .1       0
Bank Sta=4981.3,5009.8
XS Rating Curve= 0 ,0
Exp/Cntr=0.3,0.1

Type RM Length L Ch R = 1 ,18158   ,707,707,707
BEGIN DESCRIPTION:
SF PEREZ CREEK 9.0
END DESCRIPTION:
XS GIS Cut Line= 3
       1999750.7     13590383.36      1998056.23      13590716.7
      1996160.36     13590584.75
#Sta/Elev= 30
  3057.1  651.01  3287.1  648.06  3316.8  645.84  3358.5  646.76  3398.2  643.76
  3417.7  643.87  3531.7     641    3614  640.64  4230.6  626.01  4878.2     623
  4889.3  622.93  4965.7  622.78  4975.7  621.63  4981.5  614.07  4986.6  613.17
  5004.9  613.17    5010  614.07  5015.8  617.94  5022.7  620.86  5027.7  619.36
    5076  621.68  5164.9  623.04  5376.7  624.53  6098.4  622.83  6218.7  624.29
  6349.1  628.33  6469.6  630.15  6489.4   632.3  6529.5  631.54  6684.5  637.44
#Mann= 7 ,-1 , 0
  3057.1      .1       0  3316.8     .05       0  3417.7      .1       0
  4878.2     .05       0  4889.3      .1       0  4981.5     .07       0
    5010      .1       0
Bank Sta=4981.5,5010
XS Rating Curve= 0 ,0
Exp/Cntr=0.3,0.1

Type RM Length L Ch R = 1 ,17451   ,1020,1020,1020
BEGIN DESCRIPTION:
SF PEREZ CREEK 8.0
END DESCRIPTION:
XS GIS Cut Line= 3
      1999993.75     13588959.74      1998292.34     13590008.37
      1995972.88      13590404.2
#Sta/Elev= 30
  2214.8  643.73  2234.9  643.63    2413  642.92  2752.4   638.3  2873.7  637.35
  2943.5   637.5  2974.3  633.91  2991.5  633.79  3453.4  630.02  3495.9  630.98
  3889.9  626.31  3953.7  626.91    4231  622.55  4606.3  624.71    4860  620.64
  4971.5  621.75    4979  619.99  4981.7  619.36  4982.1  611.81  4987.2  610.91
  5010.6  611.81  5012.1  616.17  5022.3   619.3  5056.5  621.24  5079.4  620.79
  5255.6  623.54  5925.1  621.95  6087.5  626.66  6184.3  631.37  6566.4  645.06
#Mann= 9 ,-1 , 0
  2214.8      .1       0  2234.9     .05       0  2752.4      .1       0
  2873.7     .05       0  2991.5      .1       0    4979     .12       0
  4982.1     .07       0  5010.6     .12       0  5079.4      .1       0
Bank Sta=4982.1,5010.6
XS Rating Curve= 0 ,0
Exp/Cntr=0.3,0.1

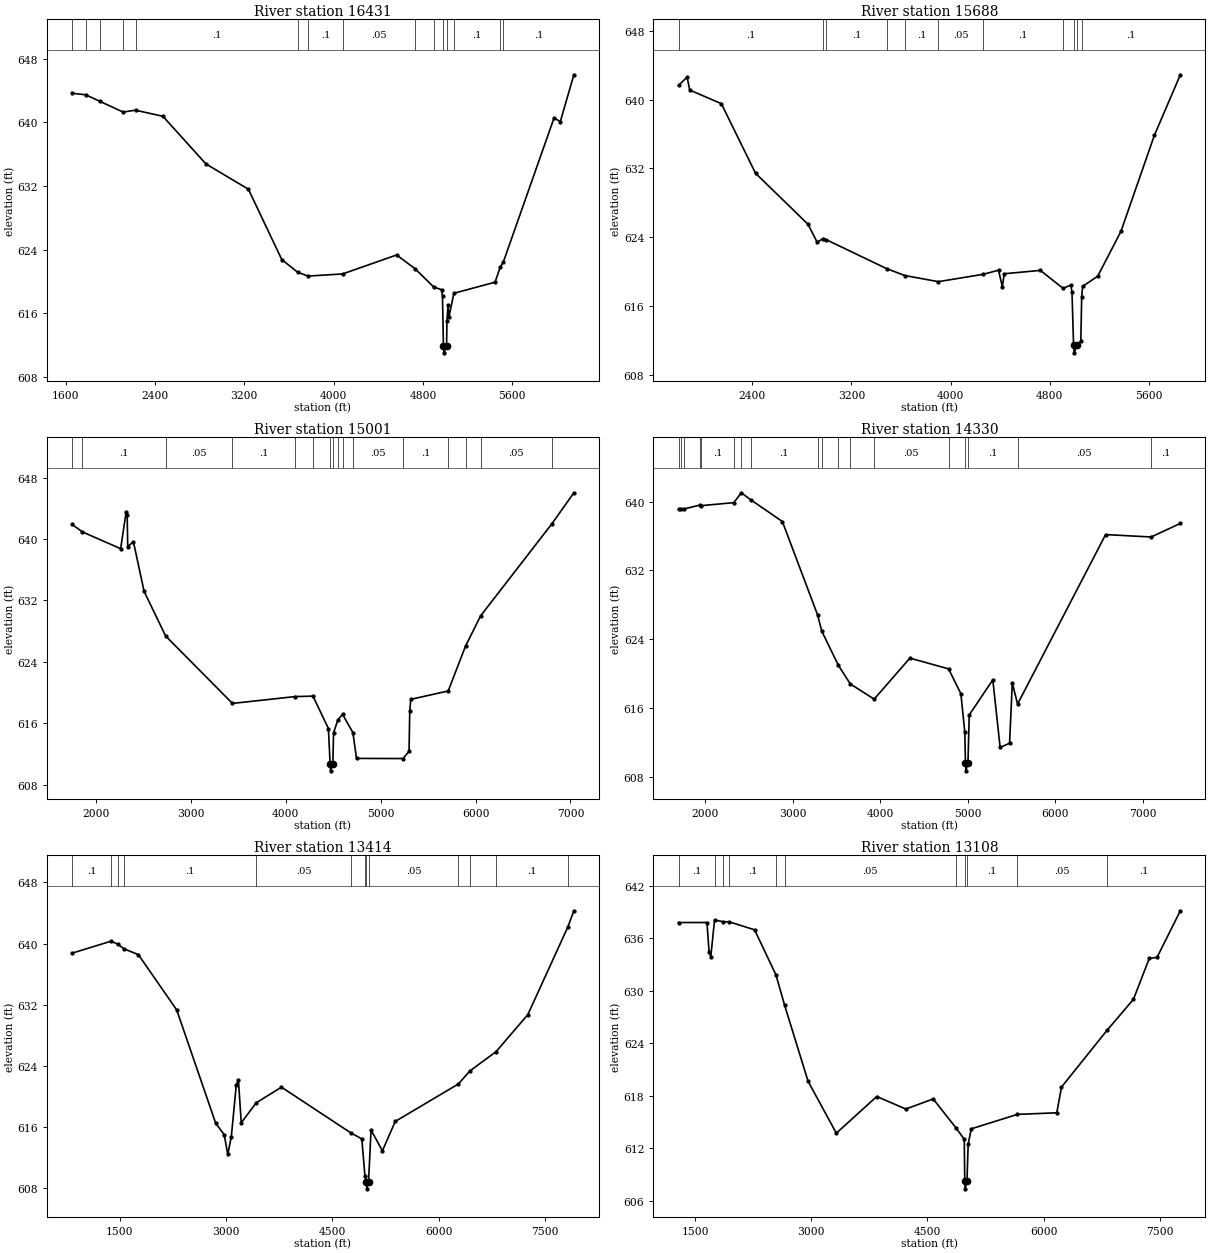
Type RM Length L Ch R = 1 ,16431   ,743,743,743
BEGIN DESCRIPTION:
SF PEREZ CREEK 7.0
END DESCRIPTION:
XS GIS Cut Line= 3
      1999775.02     13588074.99        1996775.       13589575.
        1995875.       13590275.
#Sta/Elev= 30
    1658  643.64  1779.4  643.45  1906.3  642.63  2114.6  641.28  2226.3  641.51
  2471.4  640.75  2857.1  634.76  3237.2  631.59  3536.3  622.75  3678.9  621.16
  3772.2  620.68  4081.1  620.95  4564.9  623.33  4731.1  621.59  4897.8   619.3
  4967.4  618.97  4975.8  618.12  4983.9  611.94    4989  611.04  5012.4  611.94
  5015.3  614.98  5025.7  617.08  5033.8  615.56  5077.5  618.52  5446.5  619.91
  5491.6  621.76  5521.7  622.49  5974.9  640.54    6031  640.08  6152.3  645.96
#Mann= 15 ,-1 , 0
    1658      .1       0  1779.4     .05       0  1906.3      .1       0
  2114.6     .05       0  2226.3      .1       0  3678.9     .05       0
  3772.2      .1       0  4081.1     .05       0  4731.1      .1       0
  4897.8     .12       0  4983.9     .07       0  5012.4     .12       0
  5077.5      .1       0  5491.6     .05       0  5521.7      .1       0
Bank Sta=4983.9,5012.4
XS Rating Curve= 0 ,0
Exp/Cntr=0.3,0.1

Type RM Length L Ch R = 1 ,15688   ,687,687,687
BEGIN DESCRIPTION:
SF PEREZ CREEK 6.0
END DESCRIPTION:
XS GIS Cut Line= 3
      1998955.55     13587582.14        1996225.       13589225.
        1995725.       13589925.
#Sta/Elev= 30
  1806.1  641.65  1875.2  642.62  1896.6  641.11  2151.1  639.54  2426.9  631.45
  2850.3  625.52  2924.1  623.43  2972.3  623.86  2998.6  623.72  3484.9  620.36
  3631.9  619.56  3901.7  618.85  4264.7  619.71  4386.8  620.18  4417.8  618.25
  4432.6  619.77  4724.4  620.16  4906.8  618.08  4969.5  618.44  4979.2  617.65
    4992  611.48  4997.1  610.58  5020.5  611.48  5050.5  611.95  5057.6  617.12
  5065.3   618.3  5186.9  619.49  5373.7  624.68  5644.1  635.87    5853  642.89
#Mann= 11 ,-1 , 0
  1806.1      .1       0  2972.3     .05       0  2998.6      .1       0
  3484.9     .05       0  3631.9      .1       0  3901.7     .05       0
  4264.7      .1       0  4906.8     .12       0    4992     .07       0
  5020.5     .12       0  5057.6      .1       0
Bank Sta=4992,5020.5
XS Rating Curve= 0 ,0
Exp/Cntr=0.3,0.1

Type RM Length L Ch R = 1 ,15001   ,671,671,671
BEGIN DESCRIPTION:
SF PEREZ CREEK 5.0
END DESCRIPTION:
XS GIS Cut Line= 3
      1998903.44     13587347.78        1995975.       13588675.
      1994033.66     13589392.05
#Sta/Elev= 30
  1750.7   641.9  1859.7  640.92  2262.2  638.74  2319.9  643.49  2330.9  643.13
  2336.9  639.02  2396.8  639.64  2509.5  633.17  2736.2  627.37  3439.6  618.59
  4100.2  619.48  4287.9  619.54  4450.2  615.32  4468.5  610.71  4473.6  609.81
  4497.1  610.71  4504.7  614.76  4549.4  616.42  4598.8  617.18  4708.4  614.79
  4746.3  611.43  5236.4  611.41  5299.7  612.35    5307  617.55  5317.7  619.12
  5711.9  620.21  5894.3  626.04  6052.6  629.98  6805.6  642.01  7035.4  646.02
#Mann= 16 ,-1 , 0
  1750.7     .08       0  1859.7      .1       0  2736.2     .05       0
  3439.6      .1       0  4100.2     .05       0  4287.9      .1       0
  4468.5    .033       0  4497.1      .1       0  4549.4     .12       0
  4598.8      .1       0  4708.4     .05       0  5236.4      .1       0
  5711.9     .05       0  5894.3      .1       0  6052.6     .05       0
  6805.6      .1       0
Bank Sta=4468.5,4497.1
XS Rating Curve= 0 ,0
Exp/Cntr=0.3,0.1

Type RM Length L Ch R = 1 ,14330   ,916,916,916
BEGIN DESCRIPTION:
SF PEREZ CREEK 4.0
END DESCRIPTION:
XS GIS Cut Line= 3
      1998955.55     13586462.35        1996075.       13588075.
      1993825.34     13588975.38
#Sta/Elev= 30
  1699.7  639.13  1727.6  639.14  1757.1  639.15  1948.1  639.63  1957.1  639.55
  2330.1   639.9  2416.1  641.05  2521.1  640.25  2884.3   637.7  3285.2  626.85
  3334.1  624.92  3521.6  620.98  3659.5  618.78  3931.5  617.01  4338.8  621.79
  4780.3  620.54  4920.7  617.64  4965.5  613.14  4972.9  609.56  4978.1  608.66
  5001.5  609.56  5015.8  615.17    5285  619.26  5368.4  611.39  5476.1  611.87
  5507.2  618.89  5567.6  616.44  6571.7  636.18    7091   635.9  7424.1  637.48
#Mann= 18 ,-1 , 0
  1699.7      .1       0  1727.6     .08       0  1757.1     .05       0
  1948.1     .08       0  1957.1      .1       0  2330.1     .05       0
  2416.1     .08       0  2521.1      .1       0  3285.2     .05       0
  3334.1      .1       0  3521.6     .05       0  3659.5      .1       0
  3931.5     .05       0  4780.3      .1       0  4972.9     .07       0
  5001.5      .1       0  5567.6     .05       0    7091      .1       0
Bank Sta=4972.9,5001.5
XS Rating Curve= 0 ,0
Exp/Cntr=0.3,0.1

Type RM Length L Ch R = 1 ,13414   ,306,306,306
BEGIN DESCRIPTION:
SF PEREZ CREEK 3.0
END DESCRIPTION:
XS GIS Cut Line= 5
      1998395.67     13586188.92      1996663.87      13586488.4
      1996715.96     13587530.07      1994033.66     13587712.36
      1992775.03     13588674.98
#Sta/Elev= 30
   831.3  638.76  1379.8  640.32  1480.2  639.92  1561.4  639.33  1765.6  638.57
  2306.7  631.33  2855.7  616.53  2975.9  615.03  3025.9  612.45    3076  614.76
  3146.1  621.51  3176.1  622.19  3216.2  616.58  3425.9  619.19  3783.2  621.24
  4760.3  615.27  4915.7  614.48  4960.2  609.59  4981.6  608.85  4986.7  607.95
  5010.2  608.85    5046  615.63  5206.3  612.92  5386.8  616.76  6276.9  621.66
  6440.3  623.37    6808  625.88  7255.6  630.72  7819.8  642.18  7904.8   644.3
#Mann= 13 ,-1 , 0
   831.3      .1       0  1379.8     .05       0  1480.2     .08       0
  1561.4      .1       0  3425.9     .05       0  4760.3      .1       0
  4960.2     .05       0  4981.6    .035       0  5010.2     .05       0
  6276.9      .1       0  6440.3     .05       0    6808      .1       0
  7819.8     .05       0
Bank Sta=4981.6,5010.2
XS Rating Curve= 0 ,0
Exp/Cntr=0.3,0.1

Type RM Length L Ch R = 1 ,13108   ,1203,1203,1203
BEGIN DESCRIPTION:
Mapping XS cf6df77e
END DESCRIPTION:
XS GIS Cut Line= 5
      1997692.49     13585537.89      1996334.23     13586254.76
      1996377.41     13587269.65      1993916.48     13587464.96
      1992913.88     13588519.64
#Sta/Elev= 30
  1288.1  637.78  1654.8  637.78  1682.5  634.41  1704.5   633.9  1752.8  638.06
  1865.9  637.87  1941.3  637.86    2269  636.95  2544.6  631.82  2657.7  628.32
  2959.5  619.66  3324.6  613.73  3845.7  617.92  4220.8  616.49  4574.5  617.64
  4864.7  614.38  4975.7  613.03  4981.5  608.28  4986.6  607.38  5010.1  608.28
  5025.9  612.49    5066  614.23  5661.6  615.88  6169.5  616.06  6229.7  618.99
  6818.1  625.48  7158.3  629.01  7363.4  633.69  7462.5  633.79  7763.6  639.12
#Mann= 11 ,-1 , 0
  1288.1      .1       0  1752.8     .05       0  1865.9     .08       0
  1941.3      .1       0  2544.6     .08       0  2657.7     .05       0
  4864.7      .1       0  4981.5     .07       0  5010.1      .1       0
  5661.6     .05       0  6818.1      .1       0
Bank Sta=4981.5,5010.1
XS Rating Curve= 0 ,0
Exp/Cntr=0.3,0.1

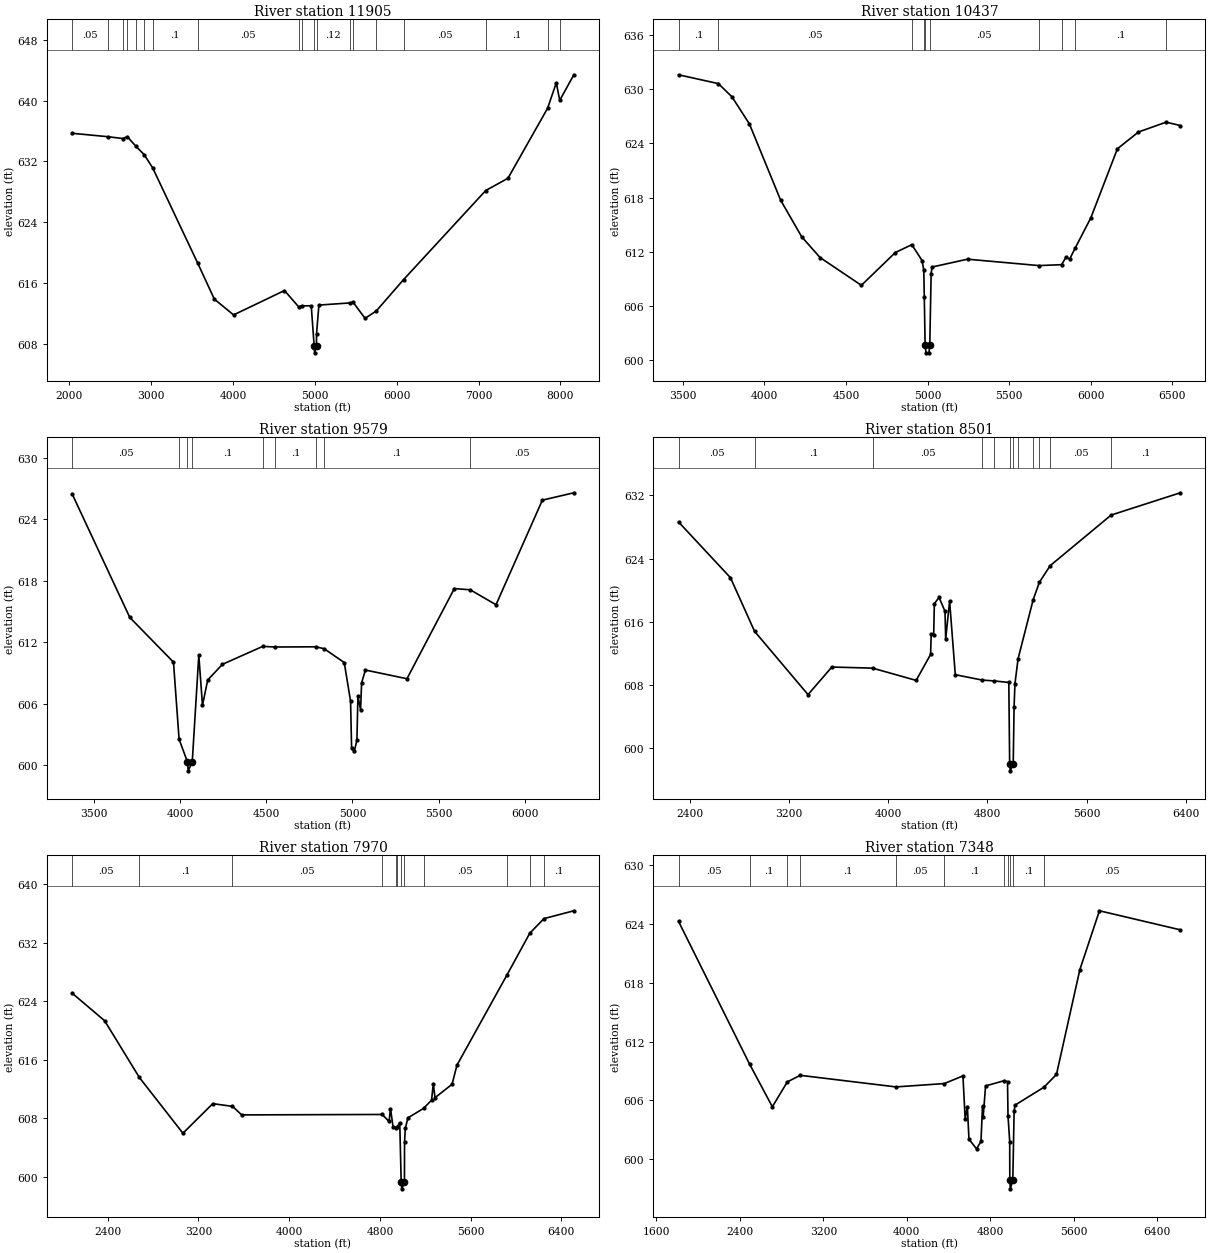
Type RM Length L Ch R = 1 ,11905   ,1468,1468,1468
BEGIN DESCRIPTION:
SF PEREZ CREEK 2.0
END DESCRIPTION:
XS GIS Cut Line= 4
      1997262.82     13585082.15      1995856.58     13585446.74
      1994079.69      13586790.4      1992575.02     13588724.97
#Sta/Elev= 30
  2032.7   635.7  2477.8  635.24    2651  635.01  2708.5  635.25    2811  634.01
  2913.4   632.9  3015.9  631.19  3569.4  618.61  3771.1  613.92  4006.3  611.85
  4628.3  615.05  4801.4  612.91  4837.1  613.04  4955.2  613.05  4990.8  607.77
    4996  606.87  5019.4  607.77  5019.7  609.35  5048.8  613.14    5433  613.43
  5464.6  613.54  5612.7   611.4  5749.3  612.36  6082.7  616.48  7086.9  628.18
  7358.7  629.79  7842.8  638.98  7949.6  642.33  7991.2  640.02    8164  643.38
#Mann= 19 ,-1 , 0
  2032.7     .05       0  2477.8      .1       0    2651     .05       0
  2708.5     .08       0    2811      .1       0  2913.4     .05       0
  3015.9      .1       0  3569.4     .05       0  4801.4      .1       0
  4837.1     .12       0  4990.8     .07       0  5019.4     .12       0
    5433     .07       0  5464.6     .05       0  5749.3      .1       0
  6082.7     .05       0  7086.9      .1       0  7842.8     .05       0
  7991.2      .1       0
Bank Sta=4990.8,5019.4
XS Rating Curve= 0 ,0
Exp/Cntr=0.3,0.1

Type RM Length L Ch R = 1 ,10437   ,858,858,858
BEGIN DESCRIPTION:
Mapping XS f9fbca7e
END DESCRIPTION:
XS GIS Cut Line= 2
      1995534.75     13584496.11      1992774.59     13585850.15
#Sta/Elev= 30
  3473.8  631.62  3717.9  630.64  3801.3  629.17  3907.9  626.17  4099.3  617.71
  4228.6  613.64  4341.1  611.34  4594.1  608.26  4802.1   611.9    4903  612.77
  4966.1  611.01  4976.4  609.91  4979.5  606.99  4984.6  601.67  4989.8  600.77
  5008.1  600.77  5013.2  601.67  5021.4  609.56    5027  610.29  5244.5  611.16
    5682  610.45  5820.5  610.55  5847.8  611.37  5870.3  611.18  5904.5  612.41
  5999.7  615.74  6162.7  623.41  6291.6  625.27    6461  626.36  6548.2  625.99
#Mann= 10 ,-1 , 0
  3473.8      .1       0  3717.9     .05       0    4903     .12       0
  4979.5     .05       0  4984.6    .035       0  5013.2     .05       0
    5682      .1       0  5820.5     .12       0  5904.5      .1       0
    6461     .05       0
Bank Sta=4984.6,5013.2
XS Rating Curve= 0 ,0
Exp/Cntr=0.3,0.1

Type RM Length L Ch R = 1 ,9579    ,1078,1078,1078
BEGIN DESCRIPTION:
Mapping XS d4849d21
END DESCRIPTION:
XS GIS Cut Line= 2
       1994736.1     13584235.72      1992253.48      13585754.8
#Sta/Elev= 30
  3373.7  626.51  3708.4  614.43  3961.9  610.06  3994.4  602.53  4042.3  600.34
  4047.5  599.44  4070.9  600.34  4108.8  610.74  4130.1  605.85  4160.5  608.32
  4246.2  609.85  4479.6   611.6  4551.6  611.54  4787.8  611.56  4836.3  611.37
  4952.4  610.02  4989.1  606.24    4995   601.7  5010.4  601.33  5025.9  602.43
  5031.7  606.77  5047.2  605.39    5053  608.03  5074.9  609.29  5316.1  608.44
  5590.9  617.25  5683.1  617.13  5832.7  615.67  6101.6  625.89  6284.2  626.61
#Mann= 9 ,-1 , 0
  3373.7     .05       0  3994.4      .1       0  4042.3     .07       0
  4070.9      .1       0  4479.6     .05       0  4551.6      .1       0
  4787.8     .16       0  4836.3      .1       0  5683.1     .05       0
Bank Sta=4042.3,4070.9
XS Rating Curve= 0 ,0
Exp/Cntr=0.3,0.1

Type RM Length L Ch R = 1 ,8501    ,531,531,531
BEGIN DESCRIPTION:
Mapping XS ae6fea99
END DESCRIPTION:
XS GIS Cut Line= 3
      1994753.43     13583975.31       1992687.5     13584739.18
      1991368.99     13586022.99
#Sta/Elev= 30
    2311  628.65  2729.3   621.6  2923.5  614.82  3354.2  606.81  3546.1   610.3
  3874.4  610.16  4225.4  608.61  4341.7  611.89    4347  614.51  4366.7  614.39
  4372.1  618.31  4409.7  619.11    4458  617.34  4463.3  613.83    4495  618.64
  4540.8  609.33  4757.9  608.65  4855.1  608.54  4972.1  608.35  4978.8  598.07
    4984  597.17  5007.6  598.07  5014.5  605.27  5021.5  608.19  5046.6  611.34
  5168.4  618.82  5218.4  621.02  5305.2  623.12  5796.2  629.52  6353.9  632.34
#Mann= 12 ,-1 , 0
    2311     .05       0  2923.5      .1       0  3874.4     .05       0
  4757.9      .1       0  4855.1     .12       0  4978.8     .07       0
  5007.6     .12       0  5046.6      .1       0  5168.4     .05       0
  5218.4      .1       0  5305.2     .05       0  5796.2      .1       0
Bank Sta=4978.8,5007.6
XS Rating Curve= 0 ,0
Exp/Cntr=0.3,0.1

Type RM Length L Ch R = 1 ,7970    ,622,622,622
BEGIN DESCRIPTION:
Mapping XS 9caf57aa
END DESCRIPTION:
XS GIS Cut Line= 3
      1994657.95     13583714.89      1992666.72     13584256.52
      1990691.01     13585546.45
#Sta/Elev= 30
  2086.8  625.11  2373.9  621.33    2680  613.56    3064  605.93  3326.9  609.98
  3500.9  609.61  3582.2  608.44  4820.7   608.5  4880.9  607.54  4893.6  609.29
  4916.8  606.75  4946.2  606.65  4951.5  606.79  4975.2  607.38  4987.8  599.22
    4993  598.32  5016.6  599.22  5017.4   604.7  5024.2   606.6  5047.6  608.04
  5184.9  609.33  5255.7  610.46  5270.8  612.72  5285.9  610.79  5436.7  612.64
  5478.9  615.23  5920.6   627.6  6121.4  633.31  6246.6  635.31  6509.9  636.38
#Mann= 12 ,-1 , 0
  2086.8     .05       0    2680      .1       0  3500.9     .05       0
  4820.7      .1       0  4946.2     .12       0  4951.5      .1       0
  4987.8     .07       0  5016.6      .1       0  5184.9     .05       0
  5920.6      .1       0  6121.4     .05       0  6246.6      .1       0
Bank Sta=4987.8,5016.6
XS Rating Curve= 0 ,0
Exp/Cntr=0.3,0.1

Type RM Length L Ch R = 1 ,7348    ,1164,1164,1164
BEGIN DESCRIPTION:
Mapping XS ec88b958
END DESCRIPTION:
XS GIS Cut Line= 3
      1994614.61     13583645.43      1992591.95     13583619.29
      1990240.71     13585120.41
#Sta/Elev= 30
  1811.4  624.22  2494.2  609.67  2711.1  605.36  2854.6  607.89    2978  608.56
  3896.3  607.38    4360  607.72  4539.1   608.5  4560.3   604.1  4581.4  605.37
  4596.7  602.06  4669.4  601.08  4711.7  601.83    4727  605.44  4732.9  604.31
    4756  607.48  4936.6  608.02  4966.4  607.92  4971.2  604.45  4987.5  601.81
  4988.4  597.91  4993.6  597.01  5017.2  597.91  5029.9  604.97  5039.1  605.53
  5316.2  607.35    5436  608.65  5660.2  619.31    5848   625.3  6623.8  623.36
#Mann= 11 ,-1 , 0
  1811.4     .05       0  2494.2      .1       0  2854.6     .05       0
    2978      .1       0  3896.3     .05       0    4360      .1       0
  4936.6     .12       0  4971.2      .1       0  4988.4     .07       0
  5017.2      .1       0  5316.2     .05       0
Bank Sta=4988.4,5017.2
XS Rating Curve= 0 ,0
Exp/Cntr=0.3,0.1

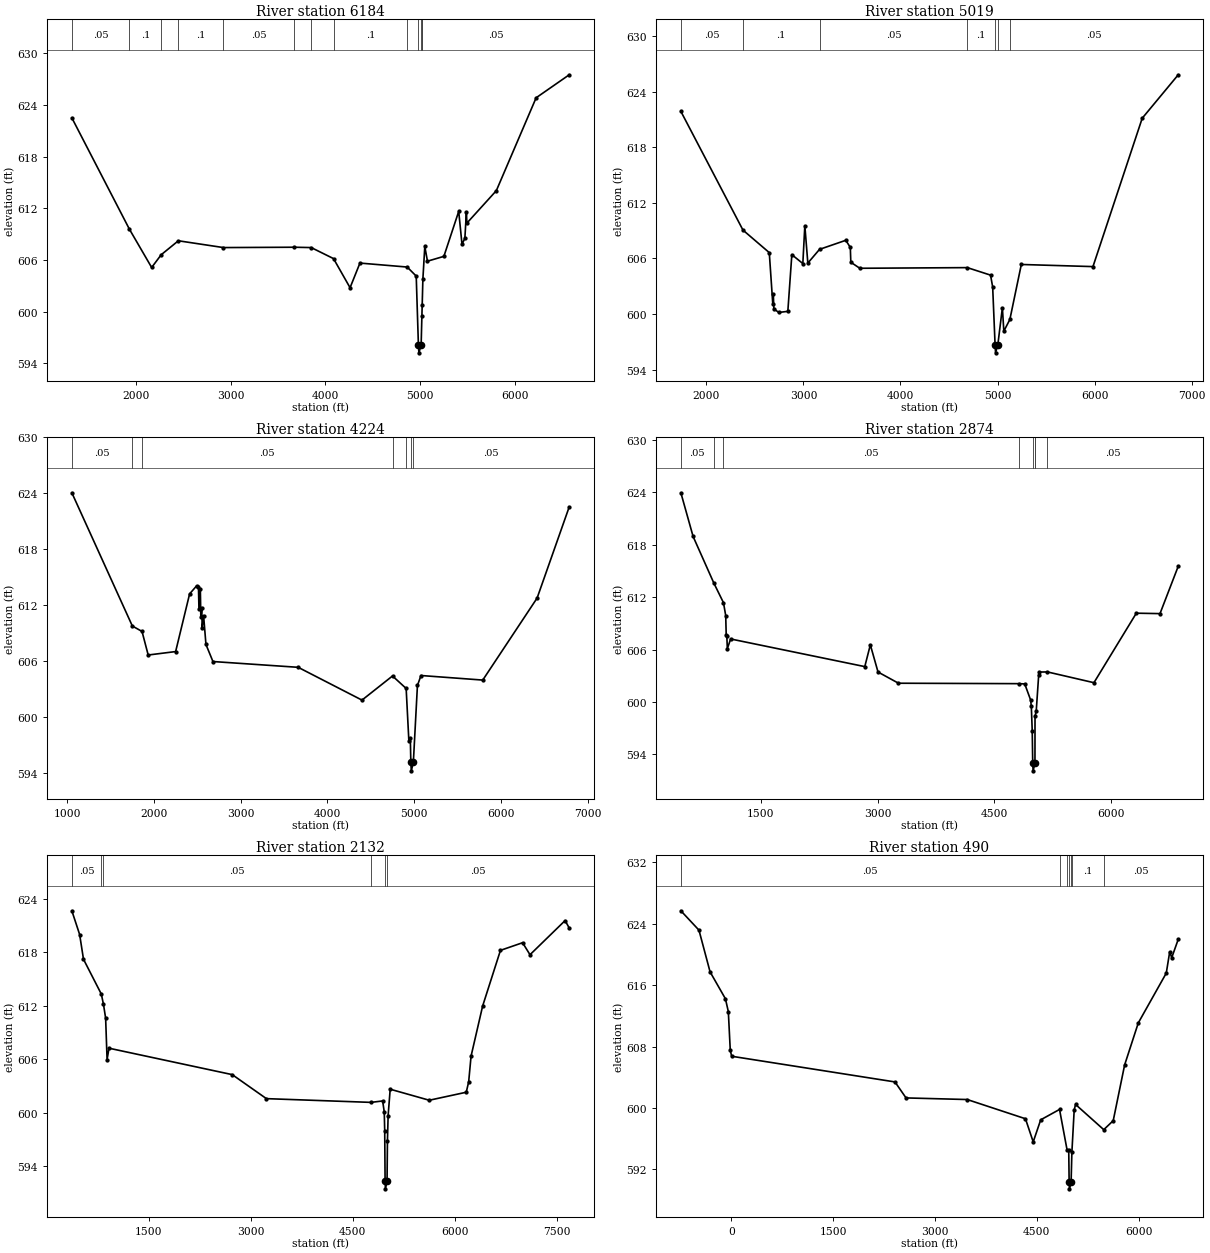
Type RM Length L Ch R = 1 ,6184    ,1165,1165,1165
BEGIN DESCRIPTION:
Mapping XS afe0820f
END DESCRIPTION:
XS GIS Cut Line= 3
      1994536.42     13583584.67      1992557.29     13583463.14
      1989310.81     13583862.44
#Sta/Elev= 30
  1322.5  622.51  1930.7  609.58  2165.5  605.14  2266.5  606.62  2447.6  608.24
  2923.9  607.45  3671.7  607.49  3851.1  607.45  4086.5  606.17  4261.2  602.79
  4365.6  605.65  4864.7  605.19    4960  604.14  4983.2  596.13  4988.4  595.23
    5012  596.13  5020.1  599.55  5023.2  600.82  5030.5  603.81  5050.7  607.58
  5078.8  605.87  5252.2  606.43  5408.9  611.65  5443.6  607.83  5473.9  608.53
  5490.2  611.55  5495.2  610.29  5806.4  614.06  6226.6  624.84  6576.3  627.51
#Mann= 13 ,-1 , 0
  1322.5     .05       0  1930.7      .1       0  2266.5     .05       0
  2447.6      .1       0  2923.9     .05       0  3671.7      .1       0
  3851.1     .05       0  4086.5      .1       0  4864.7     .12       0
  4983.2     .07       0    5012     .12       0  5020.1      .1       0
  5023.2     .05       0
Bank Sta=4983.2,5012
XS Rating Curve= 0 ,0
Exp/Cntr=0.3,0.1

Type RM Length L Ch R = 1 ,5019    ,795,795,795
BEGIN DESCRIPTION:
Mapping XS 7f8271c6
END DESCRIPTION:
XS GIS Cut Line= 3
      1994545.16     13583497.87      1992238.34     13582929.27
      1989528.88     13583393.51
#Sta/Elev= 30
  1737.4  621.88  2377.4  609.06  2648.4  606.63  2684.7  601.06  2689.9  602.19
  2695.4  600.55  2746.9  600.17  2839.6  600.29  2880.8  606.41  2994.1  605.45
  3014.7  609.54  3045.6   605.5  3165.9  606.98  3436.7  607.96  3483.4  607.19
  3488.5  605.59  3581.1  604.94  4688.7  605.01  4928.3   604.2  4950.1  602.92
  4974.8  596.71    4980  595.81  5003.6  596.71  5050.1  600.68  5065.1  598.15
  5127.2  599.41  5245.3  605.35  5983.5  605.12    6491  621.14  6862.2  625.83
#Mann= 7 ,-1 , 0
  1737.4     .05       0  2377.4      .1       0  3165.9     .05       0
  4688.7      .1       0  4974.8     .07       0  5003.6      .1       0
  5127.2     .05       0
Bank Sta=4974.8,5003.6
XS Rating Curve= 0 ,0
Exp/Cntr=0.3,0.1

Type RM Length L Ch R = 1 ,4224    ,1350,1350,1350
BEGIN DESCRIPTION:
Mapping XS 5718e899
END DESCRIPTION:
XS GIS Cut Line= 3
      1994623.28     13583497.87      1992332.58      13582182.7
       1989319.7     13582872.81
#Sta/Elev= 30
  1054.6  624.04    1752  609.74  1863.4  609.16  1934.4  606.63  2250.7     607
  2411.8  613.19  2492.3  614.05  2513.9  613.91  2519.6  611.52  2535.4  613.71
  2541.2  610.66  2551.3  611.72    2557  609.54  2572.8  610.87  2600.2  607.76
  2680.7  605.93  3662.8  605.31  4398.4  601.79  4750.1  604.38  4907.4  603.04
    4939  597.36  4955.4  597.68  4961.5   595.1  4966.7   594.2  4990.3   595.1
  5037.4  603.36  5078.5  604.43  5790.2  603.94  6416.6  612.74  6786.9  622.53
#Mann= 7 ,-1 , 0
  1054.6     .05       0    1752     .08       0  1863.4     .05       0
  4750.1      .1       0  4907.4     .05       0  4961.5    .035       0
  4990.3     .05       0
Bank Sta=4961.5,4990.3
XS Rating Curve= 0 ,0
Exp/Cntr=0.3,0.1

Type RM Length L Ch R = 1 ,2874    ,742,742,742
BEGIN DESCRIPTION:
Mapping XS 69c95804
END DESCRIPTION:
XS GIS Cut Line= 4
      1994634.22     13583447.67      1992121.21     13581286.22
      1990688.92     13581624.76      1989556.09     13582757.59
#Sta/Elev= 30
   472.9  623.93   630.2  618.93   896.7   613.6  1020.1  611.36  1048.9  609.89
  1055.4  607.63  1063.1   607.6  1069.7  606.11  1112.5  607.21  2835.2  604.05
  2906.5  606.54  3005.3  603.43  3268.2  602.15    4818   602.1  4889.6  602.07
  4965.4  600.23  4974.2  599.51  4985.9  596.71  4992.1  593.03  4997.3  592.13
  5020.9  593.03  5021.7  598.35  5037.3  598.96    5069  603.11  5078.4  603.43
    5182  603.44  5778.5  602.21  6322.9  610.16    6627  610.11  6861.4  615.53
#Mann= 8 ,-1 , 0
   472.9     .05       0   896.7     .08       0  1020.1     .05       0
    4818     .16       0  4992.1     .07       0  5020.9     .16       0
  5021.7      .1       0    5182     .05       0
Bank Sta=4992.1,5020.9
XS Rating Curve= 0 ,0
Exp/Cntr=0.3,0.1

Type RM Length L Ch R = 1 ,2132    ,1642,1642,1642
BEGIN DESCRIPTION:
Mapping XS c0b61f06
END DESCRIPTION:
XS GIS Cut Line= 5
      1994624.68     13583417.29       1991971.9     13580833.96
      1990360.79      13581028.4      1989395.52     13582049.24
      1989381.63     13582625.61
#Sta/Elev= 30
   372.4  622.69   486.9  620.02   543.5  617.24   805.1  613.33     837  612.18
   868.8  610.61     890  605.97   918.2  607.24  2728.7  604.27  3230.8  601.57
    4767  601.15  4938.3  601.31  4961.9  600.08  4968.6  597.97  4974.2  592.33
  4979.4  591.43  5003.1  592.33  5008.8  596.85  5018.9  599.67  5049.1  602.63
  5623.1  601.39  6166.5  602.29  6202.1  603.46  6237.3  606.35  6407.2  611.98
    6669  618.24  6994.2   619.1    7103  617.75  7618.9  621.59  7679.5  620.75
#Mann= 6 ,-1 , 0
   372.4     .05       0   805.1     .08       0     837     .05       0
    4767      .1       0  4974.2    .035       0  5003.1     .05       0
Bank Sta=4974.2,5003.1
XS Rating Curve= 0 ,0
Exp/Cntr=0.3,0.1

Type RM Length L Ch R = 1 ,490     ,0,0,0
BEGIN DESCRIPTION:
SF PEREZ CREEK 1.0
END DESCRIPTION:
XS GIS Cut Line= 4
      1994822.06     13583613.77      1991457.15     13579649.93
      1990172.43      13579528.4      1989339.57     13579615.16
#Sta/Elev= 30
  -742.5  625.66  -475.9  623.14  -312.2  617.71     -86  614.21   -43.2  612.54
   -14.6  607.49     6.3  606.73  2411.7  603.39  2574.6  601.31  3476.1   601.1
  4333.9   598.6  4448.2  595.59  4558.5  598.46  4835.9  599.81  4947.7  594.51
  4971.4  594.57  4977.4  590.38  4982.6  589.48  5006.3  590.38  5017.9  594.24
  5051.8  599.74  5071.9  600.46  5487.3  597.18  5626.8  598.35  5795.1  605.61
  5996.2  611.07  6408.4  617.55  6458.7  620.31  6488.9  619.56  6584.8  621.95
#Mann= 7 ,-1 , 0
  -742.5     .05       0  4835.9      .1       0  4947.7     .07       0
  4977.4     .07       0  5006.3     .07       0  5017.9      .1       0
  5487.3     .05       0
Bank Sta=4977.4,5006.3
XS Rating Curve= 0 ,0
Exp/Cntr=0.3,0.1
LCMann Table=0

Chan Stop Cuts=-1
Use User Specified Reach Order=0
Composite Channel Slope=5