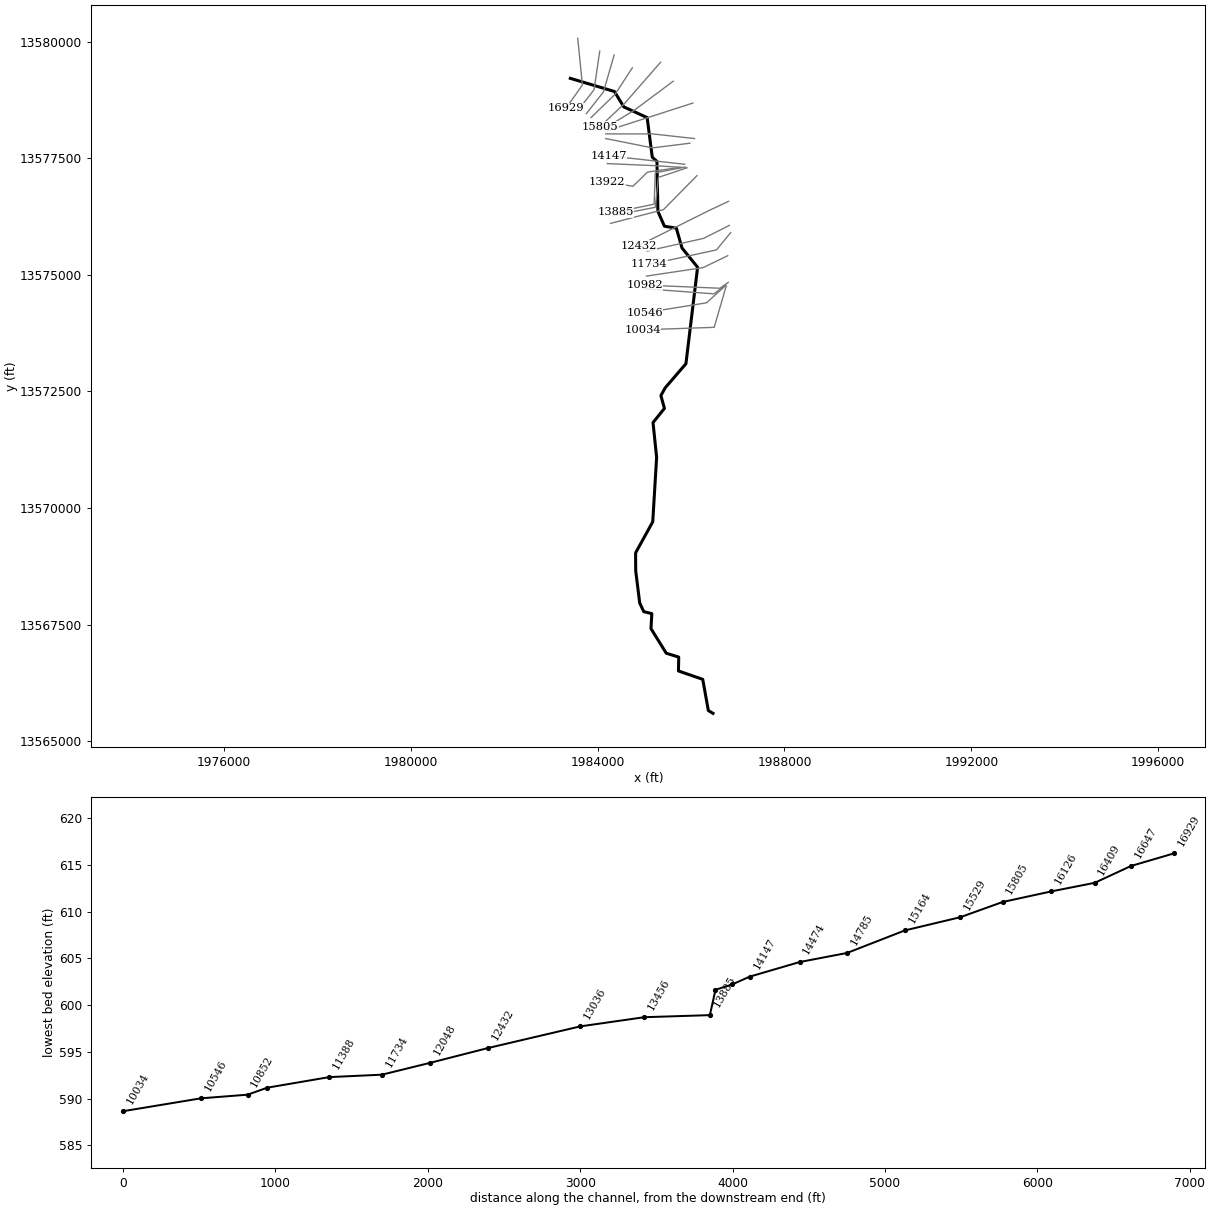
--- UNT 007 in HW.prj (project) ---

Proj Title=UNT 007 in HW Base Level Engineering
Current Plan=p01
Default Exp/Contr=0.3,0.1
English Units
Geom File=g01
Flow File=f01
Plan File=p01
BEGIN DESCRIPTION:
UNT 007 in HW
END DESCRIPTION:

--- UNT 007 in HW.p01 (plan) ---

Plan Title=Multiple Run
Short Identifier=Multiple
Geom File=g01
Flow File=f01
Subcritical Flow
K Sum by GR= 0
Std Step Tol= 0.01
Critical Tol= 0.01
Num of Std Step Trials= 20
Max Error Tol= 0.3
Flow Tol Ratio= 0.001
Split Flow NTrial= 30
Split Flow Tol= 0.02
Split Flow Ratio= 0.02
Log Output Level= 0
Friction Slope Method= 1
Unsteady Friction Slope Method= 2
Unsteady Bridges Friction Slope Method= 1
Parabolic Critical Depth
Global Vel Dist=  1 , 1 , 1
Global Log Level= 0
CheckData=True
Encroach Param= -1, 0, 0, 0
BEGIN DESCRIPTION:
Multiple Run
END DESCRIPTION:

--- UNT 007 in HW.f01 (steady flow) ---

Flow Title=Multiple
Number of Profiles=7
Profile Names=10-year,25-year,50-year,1pct_min,100-year,1pct_plu,500-year
River Rch & RM= UNT 007 in HW,Reach-1,16929
     482     674     833     510    1017    2029    1523
River Rch & RM= UNT 007 in HW,Reach-1,15164
     603     852    1061     653    1304    2601    1979
River Rch & RM= UNT 007 in HW,Reach-1,12432
     835    1198    1505     935    1866    3723    2881
Boundary for River Rch & Prof#=UNT 007 in HW,Reach-1,1
Up Type=0
Dn Type=3
Dn Slope=0.005
Boundary for River Rch & Prof#=UNT 007 in HW,Reach-1,2
Up Type=0
Dn Type=3
Dn Slope=0.005
Boundary for River Rch & Prof#=UNT 007 in HW,Reach-1,3
Up Type=0
Dn Type=3
Dn Slope=0.005
Boundary for River Rch & Prof#=UNT 007 in HW,Reach-1,4
Up Type=0
Dn Type=3
Dn Slope=0.005
Boundary for River Rch & Prof#=UNT 007 in HW,Reach-1,5
Up Type=0
Dn Type=3
Dn Slope=0.005
Boundary for River Rch & Prof#=UNT 007 in HW,Reach-1,6
Up Type=0
Dn Type=3
Dn Slope=0.005
Boundary for River Rch & Prof#=UNT 007 in HW,Reach-1,7
Up Type=0
Dn Type=3
Dn Slope=0.005

--- UNT 007 in HW.g01 (geometry) ---

Geom Title=Existing Conditions

River Reach=UNT 007 in HW,Reach-1
Reach XY= 30
      1983416.51     13579217.10      1984360.80     13578934.54
      1984560.80     13578604.54      1985060.80     13578374.54
      1985170.80     13577524.54      1985270.80     13577434.54
      1985290.80     13576364.54      1985430.80     13576044.54
      1985685.34     13576004.01      1985807.22     13575576.75
      1986140.80     13575164.54      1985890.80     13573094.54
      1985448.88     13572580.22      1985355.13     13572412.17
      1985430.80     13572137.16      1985186.38     13571832.30
      1985263.73     13571087.25      1985180.80     13569704.54
      1984813.90     13569037.86      1984815.99     13568651.75
      1984901.40     13567964.25      1984988.21     13567776.75
      1985160.80     13567734.54      1985143.07     13567412.16
      1985470.15     13566885.08      1985737.02     13566801.37
      1985730.80     13566504.54      1986250.80     13566324.54
      1986370.80     13565654.54      1986470.80     13565594.54

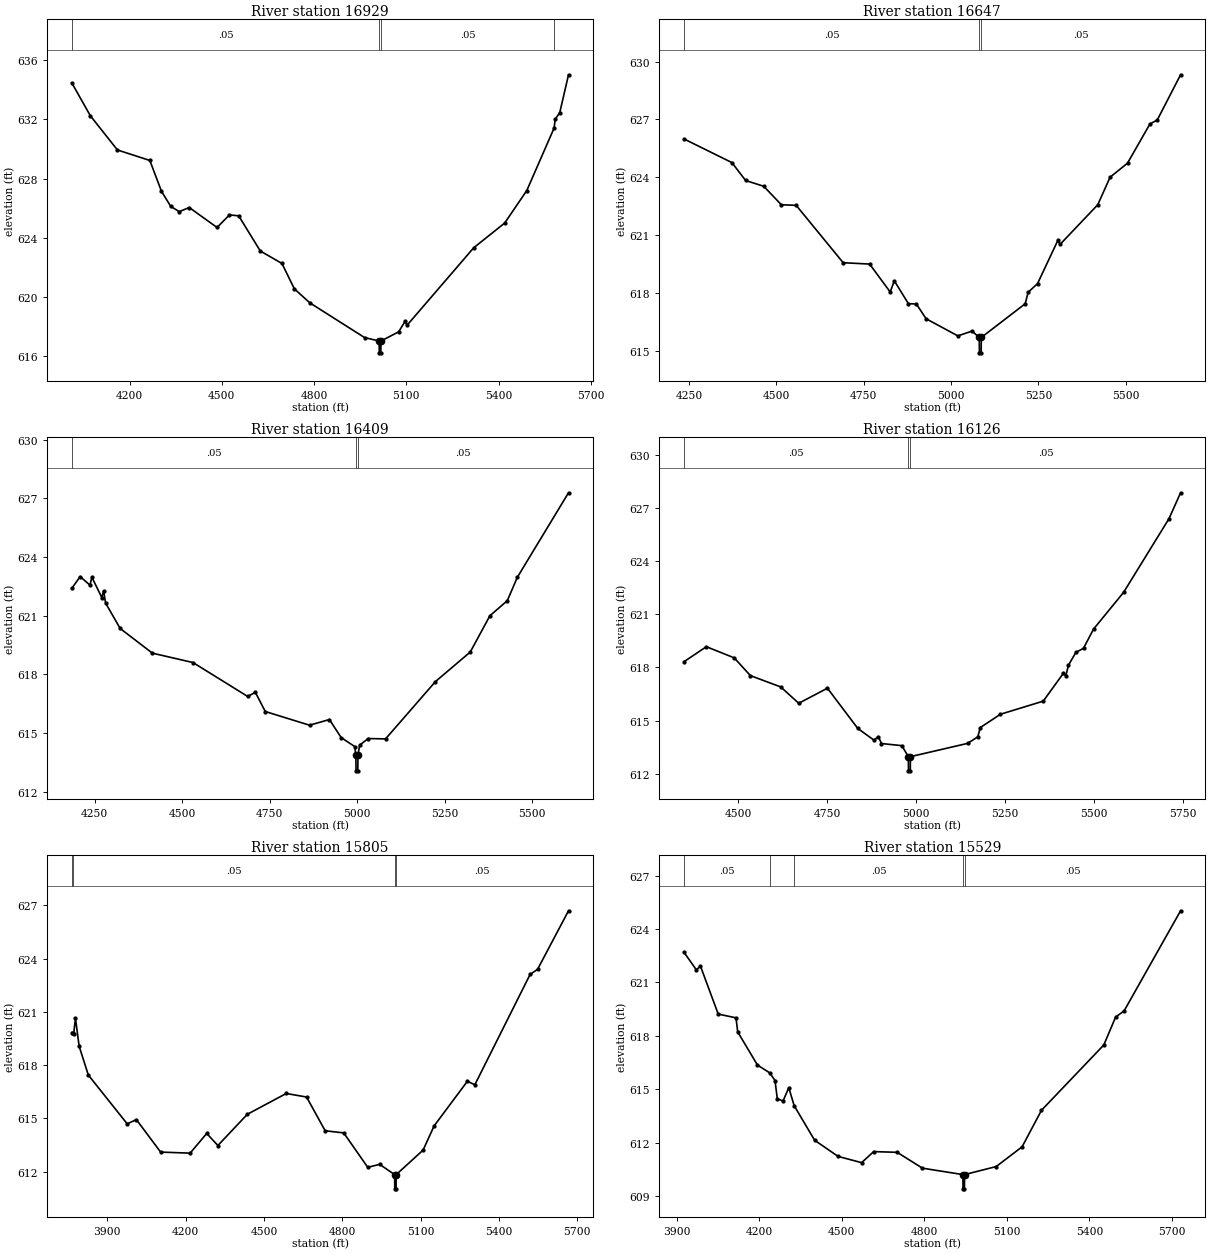
Type RM Length L Ch R = 1,16929,282,282,282
BEGIN DESCRIPTION:
UNT 007 in HW 44.0
END DESCRIPTION:
XS GIS Cut Line= 3
      1983575.00     13580075.04      1983675.00     13579075.00
      1983324.97     13578574.96
#Sta/Elev= 30
  4012.1  634.47  4072.4  632.25  4160.4  629.94  4265.9  629.23  4303.6  627.15
  4333.7  626.13  4361.4  625.77  4394.0  626.05  4484.5  624.70  4524.7  625.55
  4554.8  625.49  4625.2  623.11  4695.5  622.27  4735.7  620.56  4786.0  619.61
  4964.4  617.26  5011.6  617.03  5012.1  616.23  5017.1  616.23  5017.6  617.03
  5075.1  617.65  5096.0  618.36  5102.6  618.10  5319.2  623.33  5419.9  625.00
  5491.9  627.20  5580.6  631.42  5584.3  632.01  5599.1  632.47  5627.5  635.02
#Mann=4,-1,0
  4012.1    0.05       0  5011.6   0.035       0  5017.6    0.05       0
  5580.6     0.1       0
Bank Sta=5011.6,5017.6
Exp/Cntr=0.3,0.1

Type RM Length L Ch R = 1,16647,238,238,238
BEGIN DESCRIPTION:
UNT 007 in HW 43.0
END DESCRIPTION:
XS GIS Cut Line= 3
      1984046.21     13579801.04      1983925.00     13578975.00
      1983567.29     13578509.69
#Sta/Elev= 30
  4235.4  625.99  4372.9  624.76  4412.1  623.83  4463.9  623.53  4514.4  622.57
  4556.8  622.54  4691.4  619.56  4767.1  619.49  4825.9  618.04  4837.8  618.62
  4878.2  617.43  4900.8  617.42  4928.8  616.65  5019.7  615.76  5060.2  616.01
  5080.8  615.68  5081.3  614.88  5086.3  614.88  5086.8  615.68  5212.5  617.43
  5220.7  618.02  5247.9  618.48  5305.9  620.72  5312.2  620.51  5420.1  622.57
  5455.4  624.00  5505.3  624.73  5569.6  626.77  5590.4  626.97  5657.2  629.32
#Mann=3,-1,0
  4235.4    0.05       0  5080.8   0.035       0  5086.8    0.05       0
Bank Sta=5080.8,5086.8
Exp/Cntr=0.3,0.1

Type RM Length L Ch R = 1,16409,283,283,283
BEGIN DESCRIPTION:
UNT 007 in HW 42.0
END DESCRIPTION:
XS GIS Cut Line= 3
      1984355.23     13579717.67      1984125.00     13578925.00
      1983758.03     13578457.32
#Sta/Elev= 30
  4184.5  622.40  4208.3  623.00  4236.6  622.56  4241.8  622.97  4270.2  621.93
  4275.4  622.27  4281.0  621.65  4322.7  620.35  4414.8  619.09  4531.0  618.61
  4687.1  616.88  4709.2  617.09  4737.5  616.11  4864.1  615.41  4920.9  615.70
  4954.4  614.78  4993.2  614.32  4996.5  613.88  4997.0  613.08  5002.0  613.08
  5002.5  613.88  5007.3  614.39  5031.6  614.73  5081.3  614.71  5224.1  617.64
  5323.6  619.15  5379.7  621.00  5429.4  621.77  5458.3  622.97  5604.4  627.28
#Mann=3,-1,0
  4184.5    0.05       0  4996.5   0.035       0  5002.5    0.05       0
Bank Sta=4996.5,5002.5
Exp/Cntr=0.3,0.1

Type RM Length L Ch R = 1,16126,321,321,321
BEGIN DESCRIPTION:
UNT 007 in HW 41.0
END DESCRIPTION:
XS GIS Cut Line= 3
      1984744.13     13579443.40      1984375.00     13578875.00
      1983859.35     13578374.58
#Sta/Elev= 30
  4347.8  618.32  4411.0  619.17  4489.4  618.54  4534.8  617.54  4620.1  616.90
  4670.7  615.98  4751.3  616.83  4836.7  614.56  4882.2  613.90  4894.4  614.10
  4903.3  613.71  4960.6  613.59  4978.7  612.97  4979.2  612.17  4984.2  612.17
  4984.7  612.97  5145.8  613.72  5174.1  614.09  5181.1  614.61  5237.6  615.36
  5358.0  616.10  5414.6  617.67  5421.6  617.53  5428.7  618.12  5449.8  618.85
  5471.2  619.08  5499.3  620.16  5584.1  622.24  5711.5  626.39  5744.1  627.85
#Mann=3,-1,0
  4347.8    0.05       0  4978.7   0.035       0  4984.7    0.05       0
Bank Sta=4978.7,4984.7
Exp/Cntr=0.3,0.1

Type RM Length L Ch R = 1,15805,276,276,276
BEGIN DESCRIPTION:
UNT 007 in HW 40.0
END DESCRIPTION:
XS GIS Cut Line= 3
      1985348.27     13579561.43      1984575.00     13578675.00
      1984046.24     13578176.07
#Sta/Elev= 30
  3763.8  619.83  3766.9  619.80  3771.0  619.76  3777.7  620.64  3791.9  619.06
  3827.0  617.44  3976.1  614.69  4011.2  614.93  4104.1  613.10  4217.2  613.04
  4280.8  614.15  4323.5  613.47  4436.5  615.23  4585.5  616.40  4663.4  616.20
  4734.6  614.30  4805.8  614.18  4897.9  612.24  4943.5  612.41  5000.8  611.83
  5001.3  611.03  5006.3  611.03  5006.8  611.83  5109.8  613.21  5152.3  614.58
  5279.7  617.09  5308.1  616.89  5520.1  623.11  5548.4  623.39  5667.1  626.69
#Mann=4,-1,0
  3763.8    0.08       0  3766.9    0.05       0  5000.8   0.035       0
  5006.8    0.05       0
Bank Sta=5000.8,5006.8
Exp/Cntr=0.3,0.1

Type RM Length L Ch R = 1,15529,365,365,365
BEGIN DESCRIPTION:
UNT 007 in HW 39.0
END DESCRIPTION:
XS GIS Cut Line= 3
      1985619.16     13579155.23      1984775.00     13578525.00
      1984132.98     13578134.35
#Sta/Elev= 30
  3926.4  622.70  3971.9  621.70  3986.5  621.92  4051.2  619.22  4115.8  619.01
  4122.0  618.22  4193.7  616.36  4238.5  615.92  4257.5  615.49  4265.9  614.47
  4286.7  614.34  4307.6  615.09  4327.1  614.08  4401.4  612.14  4486.8  611.23
  4572.3  610.88  4616.1  611.50  4701.6  611.46  4793.3  610.57  4940.4  610.21
  4940.9  609.41  4945.9  609.41  4946.4  610.21  5061.2  610.66  5155.5  611.77
  5225.9  613.82  5452.6  617.49  5495.2  619.05  5526.2  619.40  5731.4  625.02
#Mann=5,-1,0
  3926.4    0.05       0  4238.5    0.08       0  4327.1    0.05       0
  4940.4   0.035       0  4946.4    0.05       0
Bank Sta=4940.4,4946.4
Exp/Cntr=0.3,0.1

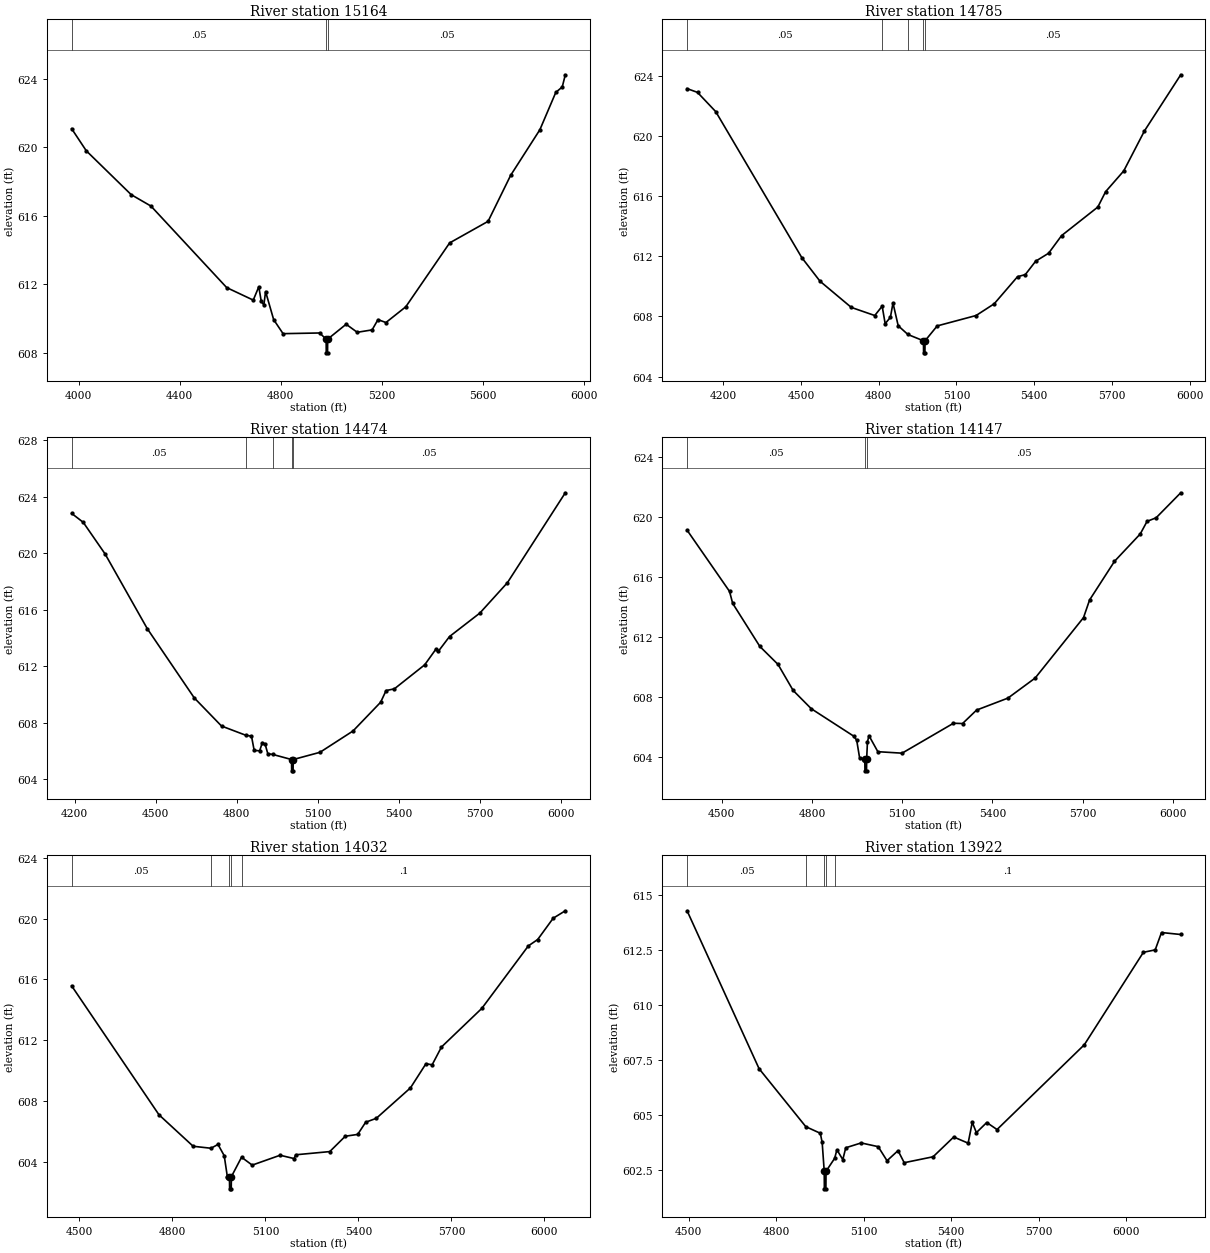
Type RM Length L Ch R = 1,15164,379,379,379
BEGIN DESCRIPTION:
UNT 007 in HW 38.0
END DESCRIPTION:
XS GIS Cut Line= 3
      1986039.23     13578686.45      1985075.00     13578375.00
      1984179.12     13578086.07
#Sta/Elev= 30
  3971.8  621.08  4029.7  619.79  4207.4  617.23  4285.9  616.56  4585.7  611.80
  4690.8  611.07  4712.8  611.85  4722.4  611.00  4732.9  610.79  4739.6  611.57
  4771.6  609.93  4808.9  609.11  4953.6  609.15  4979.4  608.79  4979.9  607.99
  4985.0  607.99  4985.5  608.79  5058.6  609.66  5102.5  609.19  5161.4  609.33
  5184.7  609.93  5216.2  609.76  5294.8  610.68  5468.4  614.41  5620.6  615.67
  5710.1  618.36  5825.7  621.02  5888.7  623.20  5914.3  623.52  5926.4  624.23
#Mann=3,-1,0
  3971.8    0.05       0  4979.4   0.035       0  4985.5    0.05       0
Bank Sta=4979.4,4985.5
Exp/Cntr=0.3,0.1

Type RM Length L Ch R = 1,14785,311,311,311
BEGIN DESCRIPTION:
UNT 007 in HW 37.0
END DESCRIPTION:
XS GIS Cut Line= 3
      1986074.96     13577925.00      1985175.00     13578025.00
      1984175.00     13578025.00
#Sta/Elev= 30
  4060.3  623.14  4100.5  622.89  4170.9  621.61  4503.0  611.91  4573.4  610.34
  4694.1  608.60  4784.7  608.06  4813.3  608.68  4824.9  607.52  4845.1  607.94
  4855.1  608.89  4875.2  607.38  4912.6  606.80  4972.7  606.38  4973.2  605.58
  4978.3  605.58  4978.8  606.38  5025.8  607.37  5175.8  608.06  5245.8  608.84
  5335.8  610.64  5365.8  610.78  5405.8  611.67  5455.8  612.20  5505.8  613.37
  5645.8  615.27  5675.8  616.29  5745.8  617.67  5825.8  620.33  5965.8  624.06
#Mann=5,-1,0
  4060.3    0.05       0  4813.3    0.08       0  4912.6    0.05       0
  4972.7   0.035       0  4978.8    0.05       0
Bank Sta=4972.7,4978.8
Exp/Cntr=0.3,0.1

Type RM Length L Ch R = 1,14474,327,327,327
BEGIN DESCRIPTION:
UNT 007 in HW 36.0
END DESCRIPTION:
XS GIS Cut Line= 3
      1985974.99     13577825.00      1985175.00     13577725.00
      1984175.02     13577925.00
#Sta/Elev= 30
  4189.5  622.82  4232.3  622.19  4312.9  619.96  4469.1  614.67  4643.0  609.77
  4743.8  607.78  4834.6  607.12  4854.6  607.07  4864.7  606.05  4884.9  606.03
  4894.9  606.61  4905.0  606.50  4915.1  605.82  4933.4  605.77  5002.8  605.41
  5003.3  604.61  5008.5  604.61  5009.0  605.41  5107.9  605.92  5230.3  607.43
  5332.3  609.46  5352.6  610.29  5383.2  610.41  5495.4  612.11  5536.2  613.20
  5546.4  613.08  5587.2  614.11  5699.4  615.77  5801.4  617.92  6015.5  624.28
#Mann=5,-1,0
  4189.5    0.05       0  4834.6    0.08       0  4933.4    0.05       0
  5002.8   0.035       0  5009.0    0.05       0
Bank Sta=5002.8,5009
Exp/Cntr=0.3,0.1

Type RM Length L Ch R = 1,14147,115,115,115
BEGIN DESCRIPTION:
Mapping XS d54d376f
END DESCRIPTION:
XS GIS Cut Line= 2
      1985865.63     13577373.96      1984233.69     13577554.52
#Sta/Elev= 30
  4384.3  619.13  4525.5  615.04  4535.9  614.24  4626.4  611.36  4686.8  610.16
  4737.1  608.42  4797.4  607.20  4938.3  605.37  4948.4  605.10  4958.4  603.88
  4975.4  603.85  4975.9  603.05  4981.1  603.05  4981.6  603.85  4984.2  604.98
  4989.2  605.40  5018.8  604.33  5099.3  604.23  5270.3  606.23  5300.5  606.21
  5347.2  607.11  5451.4  607.91  5542.0  609.25  5702.9  613.29  5723.1  614.47
  5805.9  617.05  5891.6  618.88  5914.2  619.72  5944.4  619.96  6026.2  621.63
#Mann=3,-1,0
  4384.3    0.05       0  4975.4    0.04       0  4981.6    0.05       0
Bank Sta=4975.4,4981.6
Exp/Cntr=0.3,0.1

Type RM Length L Ch R = 1,14032,110,110,110
BEGIN DESCRIPTION:
UNT 007 in HW 35.0
END DESCRIPTION:
XS GIS Cut Line= 3
      1985796.18     13577307.99      1985167.74     13577346.18
      1984205.94     13577387.85
#Sta/Elev= 30
  4474.9  615.57  4756.6  607.09  4866.8  605.02  4924.2  604.89  4946.9  605.14
  4967.0  604.40  4977.0  603.03  4983.9  603.02  4984.4  602.22  4989.6  602.22
  4990.1  603.02  5022.9  604.30  5057.2  603.78  5147.3  604.43  5192.5  604.21
  5197.5  604.46  5307.4  604.67  5357.5  605.68  5397.5  605.80  5423.2  606.60
  5457.6  606.86  5567.7  608.86  5617.7  610.45  5637.7  610.38  5667.8  611.55
  5797.9  614.09  5948.0  618.20  5978.1  618.62  6028.1  620.02  6067.2  620.51
#Mann=5,-1,0
  4474.9    0.05       0  4924.2    0.08       0  4983.9    0.07       0
  4990.1    0.08       0  5022.9     0.1       0
Bank Sta=4983.9,4990.1
Exp/Cntr=0.3,0.1

Type RM Length L Ch R = 1,13922,37,37,37
BEGIN DESCRIPTION:
Mapping XS dc639b0d
END DESCRIPTION:
XS GIS Cut Line= 4
      1985753.20     13577305.81      1985069.65     13577205.99
      1984757.15     13576902.17      1984198.61     13576990.93
#Sta/Elev= 30
  4495.1  614.30  4741.9  607.11  4902.1  604.47  4951.8  604.17  4958.2  603.75
  4965.2  602.44  4965.7  601.64  4970.9  601.64  4971.4  602.44  5001.0  603.03
  5008.7  603.42  5028.9  602.97  5039.0  603.51  5091.8  603.73  5150.2  603.56
  5180.5  602.92  5218.2  603.38  5239.4  602.83  5338.4  603.10  5409.1  604.00
  5458.5  603.72  5472.7  604.67  5486.8  604.20  5522.3  604.66  5557.6  604.34
  5856.8  608.20  6059.3  612.41  6099.8  612.52  6121.4  613.31  6187.3  613.22
#Mann=5,-1,0
  4495.1    0.05       0  4902.1    0.08       0  4965.2    0.07       0
  4971.4    0.08       0  5001.0     0.1       0
Bank Sta=4965.2,4971.4
Exp/Cntr=0.3,0.1

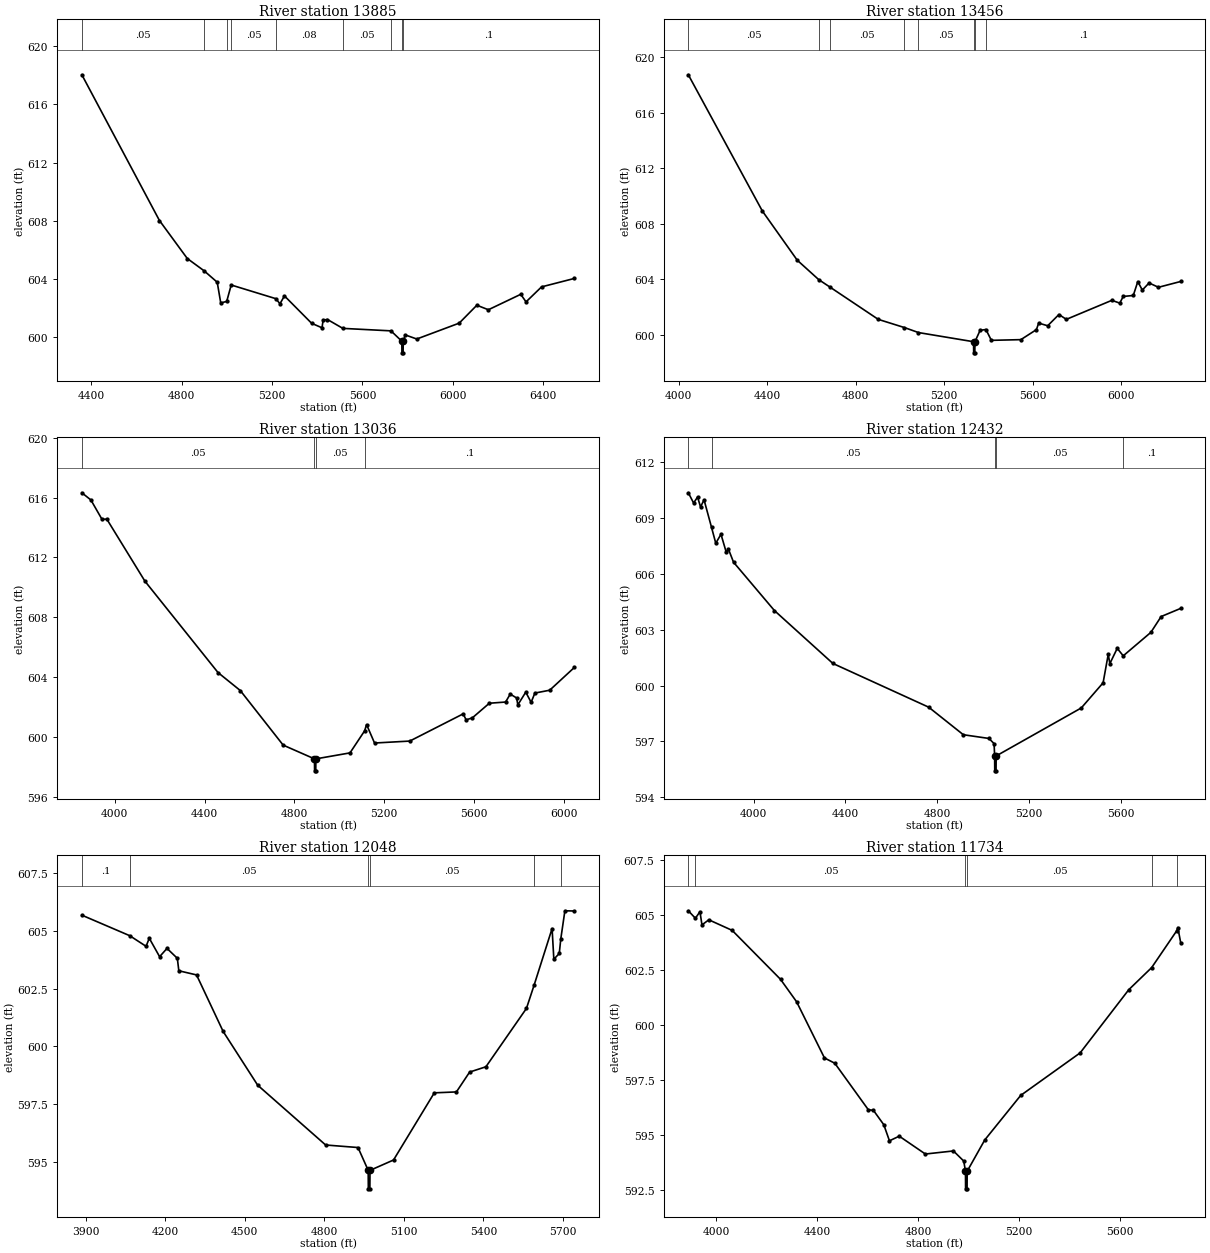
Type RM Length L Ch R = 1,13885,429,429,429
BEGIN DESCRIPTION:
Mapping XS 256e0523
END DESCRIPTION:
XS GIS Cut Line= 4
      1985882.99     13577314.93      1985235.56     13577191.65
      1985209.57     13576517.85      1984382.99     13576346.17
#Sta/Elev= 30
  4359.3  618.03  4702.4  608.02  4825.5  605.41  4900.3  604.56  4957.9  603.78
  4973.4  602.36  4999.8  602.46  5019.7  603.59  5217.2  602.65  5235.2  602.30
  5255.2  602.84  5375.3  600.96  5421.2  600.65  5426.2  601.18  5445.3  601.22
  5513.4  600.61  5726.1  600.44  5774.1  599.73  5774.6  598.93  5779.8  598.93
  5780.3  599.73  5789.3  600.16  5840.3  599.88  6027.8  600.97  6105.9  602.20
  6156.9  601.89  6299.9  602.95  6323.4  602.43  6391.9  603.46  6536.9  604.04
#Mann=9,-1,0
  4359.3    0.05       0  4900.3    0.08       0  4999.8     0.1       0
  5019.7    0.05       0  5217.2    0.08       0  5513.4    0.05       0
  5726.1     0.1       0  5774.1    0.07       0  5780.3     0.1       0
Bank Sta=5774.1,5780.3
Exp/Cntr=0.3,0.1

Type RM Length L Ch R = 1,13456,420,420,420
BEGIN DESCRIPTION:
UNT 007 in HW 34.0
END DESCRIPTION:
XS GIS Cut Line= 4
      1985914.23     13577297.56      1985303.15     13577092.71
      1985233.71     13576450.35      1984314.14     13576269.90
#Sta/Elev= 30
  4043.0  618.73  4377.9  608.92  4535.7  605.38  4633.0  603.98  4683.2  603.45
  4902.2  601.12  5020.5  600.53  5084.1  600.17  5333.3  599.51  5333.8  598.71
  5339.0  598.71  5339.5  599.51  5362.9  600.33  5389.2  600.39  5413.8  599.61
  5547.3  599.66  5617.6  600.38  5627.8  600.85  5668.6  600.66  5719.5  601.47
  5753.0  601.12  5958.8  602.49  5994.7  602.29  6010.3  602.77  6055.8  602.84
  6076.2  603.84  6096.6  603.23  6127.2  603.74  6169.7  603.43  6270.7  603.85
#Mann=8,-1,0
  4043.0    0.05       0  4633.0    0.08       0  4683.2    0.05       0
  5020.5    0.08       0  5084.1    0.05       0  5333.3   0.035       0
  5339.5    0.05       0  5389.2     0.1       0
Bank Sta=5333.3,5339.5
Exp/Cntr=0.3,0.1

Type RM Length L Ch R = 1,13036,604,604,604
BEGIN DESCRIPTION:
UNT 007 in HW 33.0
END DESCRIPTION:
XS GIS Cut Line= 3
      1986126.92     13577130.01      1985410.79     13576400.87
      1984278.98     13576105.99
#Sta/Elev= 30
  3854.0  616.32  3894.2  615.84  3943.8  614.54  3965.0  614.56  4134.7  610.41
  4460.0  604.30  4559.0  603.10  4749.9  599.45  4889.2  598.53  4889.7  597.73
  4894.9  597.73  4895.4  598.53  5047.3  598.93  5112.2  600.40  5121.1  600.82
  5156.5  599.59  5313.3  599.72  5551.1  601.54  5564.0  601.14  5591.6  601.27
  5667.4  602.25  5739.7  602.33  5760.4  602.86  5789.0  602.60  5794.1  602.14
  5829.5  602.99  5853.4  602.31  5870.0  602.93  5936.0  603.12  6045.6  604.64
#Mann=4,-1,0
  3854.0    0.05       0  4889.2   0.035       0  4895.4    0.05       0
  5112.2     0.1       0
Bank Sta=4889.2,4895.4
Exp/Cntr=0.3,0.1

Type RM Length L Ch R = 1,12432,384,384,384
BEGIN DESCRIPTION:
UNT 007 in HW 32.0
END DESCRIPTION:
XS GIS Cut Line= 3
      1986803.16     13576578.82      1986376.74     13576377.08
      1984878.34     13575627.88
#Sta/Elev= 30
  3715.1  610.36  3738.2  609.81  3755.4  610.13  3768.4  609.60  3783.7  609.98
  3816.3  608.50  3834.8  607.65  3857.5  608.13  3880.3  607.17  3890.1  607.33
  3912.2  606.63  4090.6  604.03  4345.3  601.19  4763.1  598.84  4914.1  597.36
  5025.9  597.16  5048.2  596.88  5050.5  596.22  5051.0  595.42  5056.7  595.42
  5057.2  596.22  5428.4  598.80  5523.4  600.15  5545.8  601.68  5552.8  601.18
  5584.9  602.00  5611.2  601.60  5731.7  602.86  5776.4  603.71  5862.1  604.15
#Mann=5,-1,0
  3715.1     0.1       0  3816.3    0.05       0  5050.5   0.035       0
  5057.2    0.05       0  5611.2     0.1       0
Bank Sta=5050.5,5057.2
Exp/Cntr=0.3,0.1

Type RM Length L Ch R = 1,12048,314,314,314
BEGIN DESCRIPTION:
UNT 007 in HW 31.0
END DESCRIPTION:
XS GIS Cut Line= 3
      1986821.39     13576062.33      1986270.17     13575784.55
      1985059.60     13575511.20
#Sta/Elev= 30
  3885.1  605.68  4065.8  604.79  4127.4  604.33  4139.5  604.68  4178.5  603.88
  4206.4  604.24  4245.4  603.81  4251.0  603.27  4317.9  603.09  4418.3  600.64
  4548.7  598.31  4805.0  595.72  4927.2  595.61  4965.6  594.62  4966.1  593.82
  4971.9  593.82  4972.4  594.62  5061.2  595.07  5215.0  597.98  5298.5  598.02
  5348.3  598.88  5409.8  599.11  5562.8  601.64  5592.0  602.66  5659.5  605.10
  5666.1  603.77  5686.6  604.02  5692.2  604.64  5707.8  605.87  5743.4  605.86
#Mann=6,-1,0
  3885.1     0.1       0  4065.8    0.05       0  4965.6   0.035       0
  4972.4    0.05       0  5592.0    0.08       0  5692.2     0.1       0
Bank Sta=4965.6,4972.4
Exp/Cntr=0.3,0.1

Type RM Length L Ch R = 1,11734,346,346,346
BEGIN DESCRIPTION:
UNT 007 in HW 30.0
END DESCRIPTION:
XS GIS Cut Line= 3
      1986848.30     13575906.95      1986546.21     13575537.15
      1985103.47     13575224.65
#Sta/Elev= 30
  3888.9  605.18  3917.0  604.84  3935.1  605.14  3943.0  604.54  3970.3  604.77
  4062.9  604.29  4254.6  602.07  4318.5  601.05  4429.0  598.50  4470.0  598.26
  4603.0  596.15  4623.4  596.12  4664.4  595.47  4686.8  594.74  4725.7  594.95
  4829.3  594.14  4940.6  594.28  4981.6  593.82  4988.4  593.36  4988.9  592.56
  4994.7  592.56  4995.2  593.36  5065.0  594.78  5207.5  596.80  5443.3  598.73
  5636.4  601.60  5726.9  602.60  5826.9  604.28  5830.8  604.42  5842.6  603.71
#Mann=6,-1,0
  3888.9     0.1       0  3917.0    0.05       0  4988.4   0.035       0
  4995.2    0.05       0  5726.9     0.1       0  5826.9    0.05       0
Bank Sta=4988.4,4995.2
Exp/Cntr=0.3,0.1

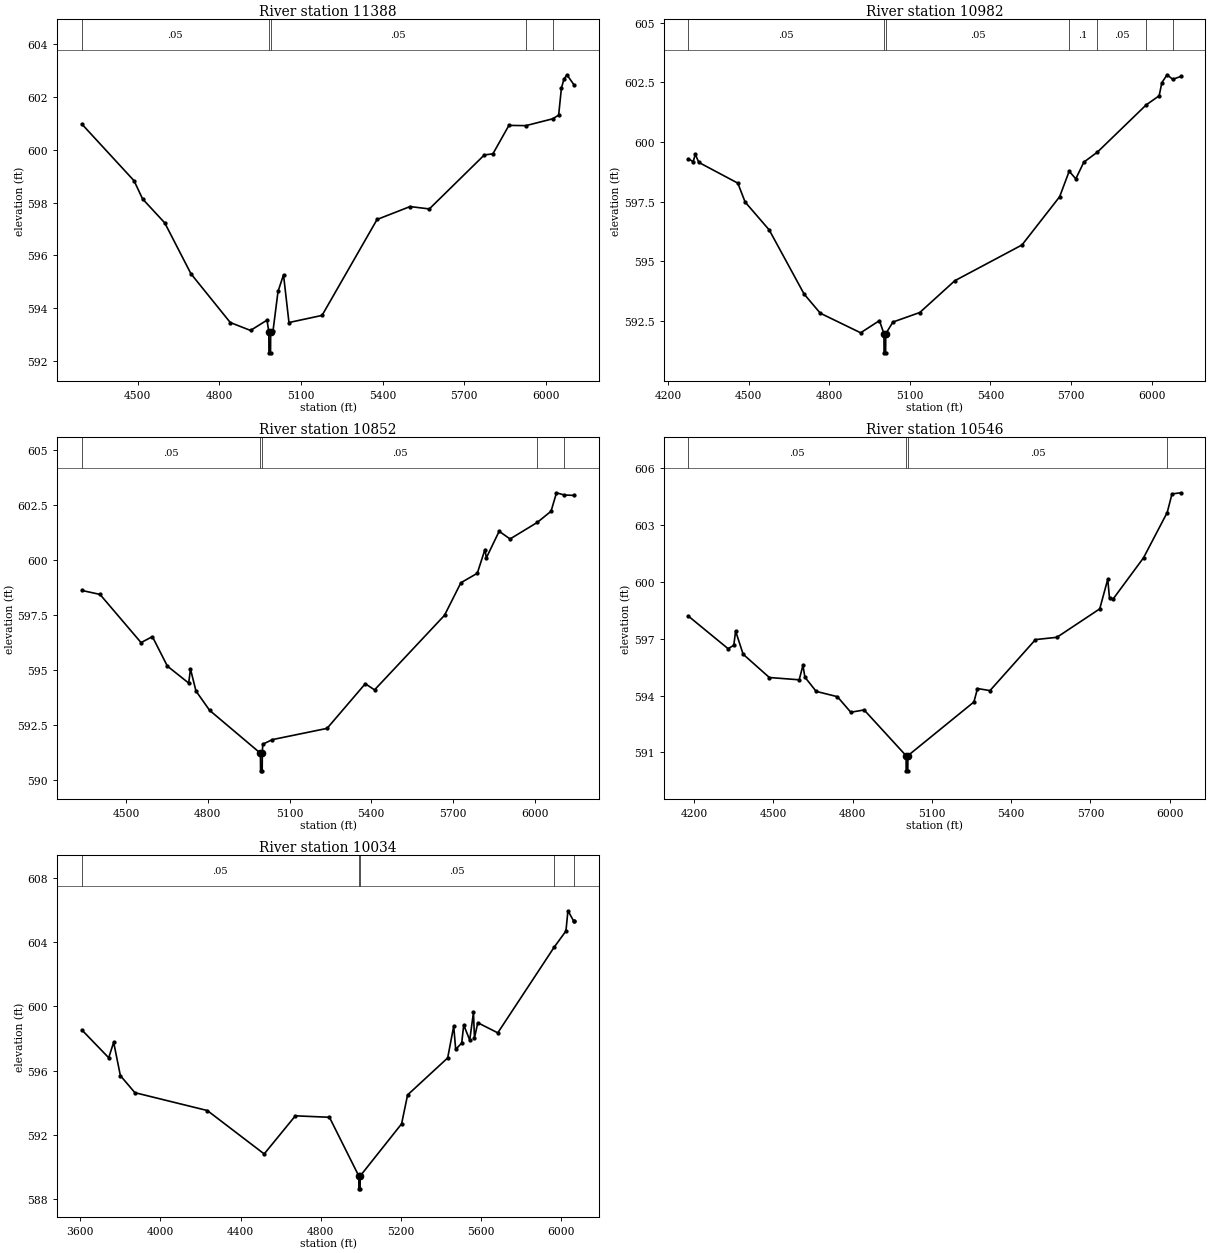
Type RM Length L Ch R = 1,11388,406,406,406
BEGIN DESCRIPTION:
UNT 007 in HW 29.0
END DESCRIPTION:
XS GIS Cut Line= 3
      1986785.82     13575412.17      1986259.75     13575156.94
      1985048.06     13574974.93
#Sta/Elev= 30
  4295.0  600.98  4486.8  598.83  4518.2  598.14  4599.7  597.23  4696.0  595.30
  4840.5  593.45  4914.9  593.15  4975.5  593.54  4982.2  593.10  4982.7  592.30
  4988.5  592.30  4989.0  593.10  4997.3  593.11  5016.0  594.63  5036.2  595.26
  5056.2  593.45  5177.8  593.72  5380.0  597.36  5501.4  597.85  5572.1  597.76
  5774.4  599.81  5805.7  599.85  5864.6  600.93  5926.8  600.92  6025.8  601.18
  6047.4  601.32  6057.5  602.34  6066.7  602.68  6077.8  602.85  6105.0  602.45
#Mann=5,-1,0
  4295.0    0.05       0  4982.2   0.035       0  4989.0    0.05       0
  5926.8     0.1       0  6025.8    0.05       0
Bank Sta=4982.2,4989
Exp/Cntr=0.3,0.1

Type RM Length L Ch R = 1,10982,130,130,130
BEGIN DESCRIPTION:
UNT 007 in HW 28.0
END DESCRIPTION:
XS GIS Cut Line= 3
      1986796.24     13574839.26      1986619.13     13574714.24
      1985004.54     13574781.94
#Sta/Elev= 30
  4275.9  599.30  4293.9  599.18  4301.9  599.49  4314.8  599.15  4460.1  598.28
  4487.2  597.49  4576.9  596.32  4707.0  593.63  4767.1  592.83  4917.2  592.01
  4987.3  592.52  5003.9  591.97  5004.4  591.17  5010.2  591.17  5010.7  591.97
  5037.3  592.46  5137.4  592.86  5267.5  594.19  5517.7  595.69  5657.8  597.71
  5693.4  598.78  5717.9  598.46  5747.9  599.16  5798.4  599.58  5980.1  601.56
  6028.2  601.94  6038.2  602.49  6057.7  602.82  6078.7  602.63  6108.7  602.75
#Mann=7,-1,0
  4275.9    0.05       0  5003.9   0.035       0  5010.7    0.05       0
  5693.4     0.1       0  5798.4    0.05       0  5980.1    0.08       0
  6078.7     0.1       0
Bank Sta=5003.9,5010.7
Exp/Cntr=0.3,0.1

Type RM Length L Ch R = 1,10852,306,306,306
BEGIN DESCRIPTION:
Mapping XS b0674822
END DESCRIPTION:
XS GIS Cut Line= 3
      1986743.51     13574779.37      1986488.92     13574594.44
      1984999.70     13574703.79
#Sta/Elev= 30
  4337.7  598.62  4404.3  598.44  4555.0  596.25  4596.7  596.52  4651.7  595.18
  4729.9  594.41  4736.5  595.05  4756.6  594.05  4806.7  593.17  4993.3  591.22
  4993.8  590.42  4999.7  590.42  5000.2  591.22  5001.8  591.63  5037.3  591.84
  5237.9  592.35  5378.2  594.38  5412.2  594.10  5669.0  597.49  5729.2  598.97
  5789.3  599.40  5817.5  600.48  5822.6  600.10  5869.6  601.31  5909.7  600.96
  6009.3  601.71  6060.1  602.22  6080.1  603.06  6108.2  602.96  6145.6  602.94
#Mann=5,-1,0
  4337.7    0.05       0  4993.3   0.035       0  5000.2    0.05       0
  6009.3    0.08       0  6108.2     0.1       0
Bank Sta=4993.3,5000.2
Exp/Cntr=0.3,0.1

Type RM Length L Ch R = 1,10546,512,512,512
BEGIN DESCRIPTION:
UNT 007 in HW 27.0
END DESCRIPTION:
XS GIS Cut Line= 3
      1986714.81     13574748.07      1986332.67     13574401.74
      1985002.17     13574187.33
#Sta/Elev= 30
  4178.5  598.19  4329.0  596.47  4350.6  596.65  4357.4  597.40  4385.8  596.18
  4485.1  594.95  4598.0  594.83  4612.2  595.59  4619.6  594.97  4662.2  594.22
  4742.5  593.94  4793.2  593.12  4843.8  593.24  5002.4  590.83  5002.9  590.03
  5008.9  590.03  5009.4  590.83  5259.1  593.66  5272.6  594.37  5319.9  594.26
  5492.1  596.95  5573.1  597.07  5735.2  598.57  5765.5  600.13  5772.2  599.13
  5785.8  599.09  5900.8  601.26  5990.5  603.65  6008.6  604.63  6041.9  604.69
#Mann=4,-1,0
  4178.5    0.05       0  5002.4   0.035       0  5009.4    0.05       0
  5990.5    0.08       0
Bank Sta=5002.4,5009.4
Exp/Cntr=0.3,0.1

Type RM Length L Ch R = 1,10034,0,0,0
BEGIN DESCRIPTION:
UNT 007 in HW 26.0
END DESCRIPTION:
XS GIS Cut Line= 3
      1986753.90     13574763.76      1986496.08     13573875.69
      1984963.12     13573822.74
#Sta/Elev= 30
  3607.7  598.53  3741.8  596.80  3766.5  597.76  3800.0  595.69  3872.4  594.63
  4233.9  593.52  4518.0  590.82  4673.6  593.19  4843.7  593.10  4990.3  589.45
  4990.8  588.65  4996.8  588.65  4997.3  589.45  5203.9  592.69  5233.9  594.49
  5434.0  596.79  5464.1  598.76  5474.1  597.32  5504.1  597.72  5514.1  598.84
  5544.1  597.90  5562.8  599.62  5567.8  598.02  5584.1  598.98  5684.2  598.35
  5965.3  603.67  6024.4  604.68  6034.4  605.94  6063.2  605.30  6066.3  605.30
#Mann=5,-1,0
  3607.7    0.05       0  4990.3   0.035       0  4997.3    0.05       0
  5965.3     0.1       0  6063.2    0.05       0
Bank Sta=4990.3,4997.3
Exp/Cntr=0.3,0.1

Chan Stop Cuts=-1