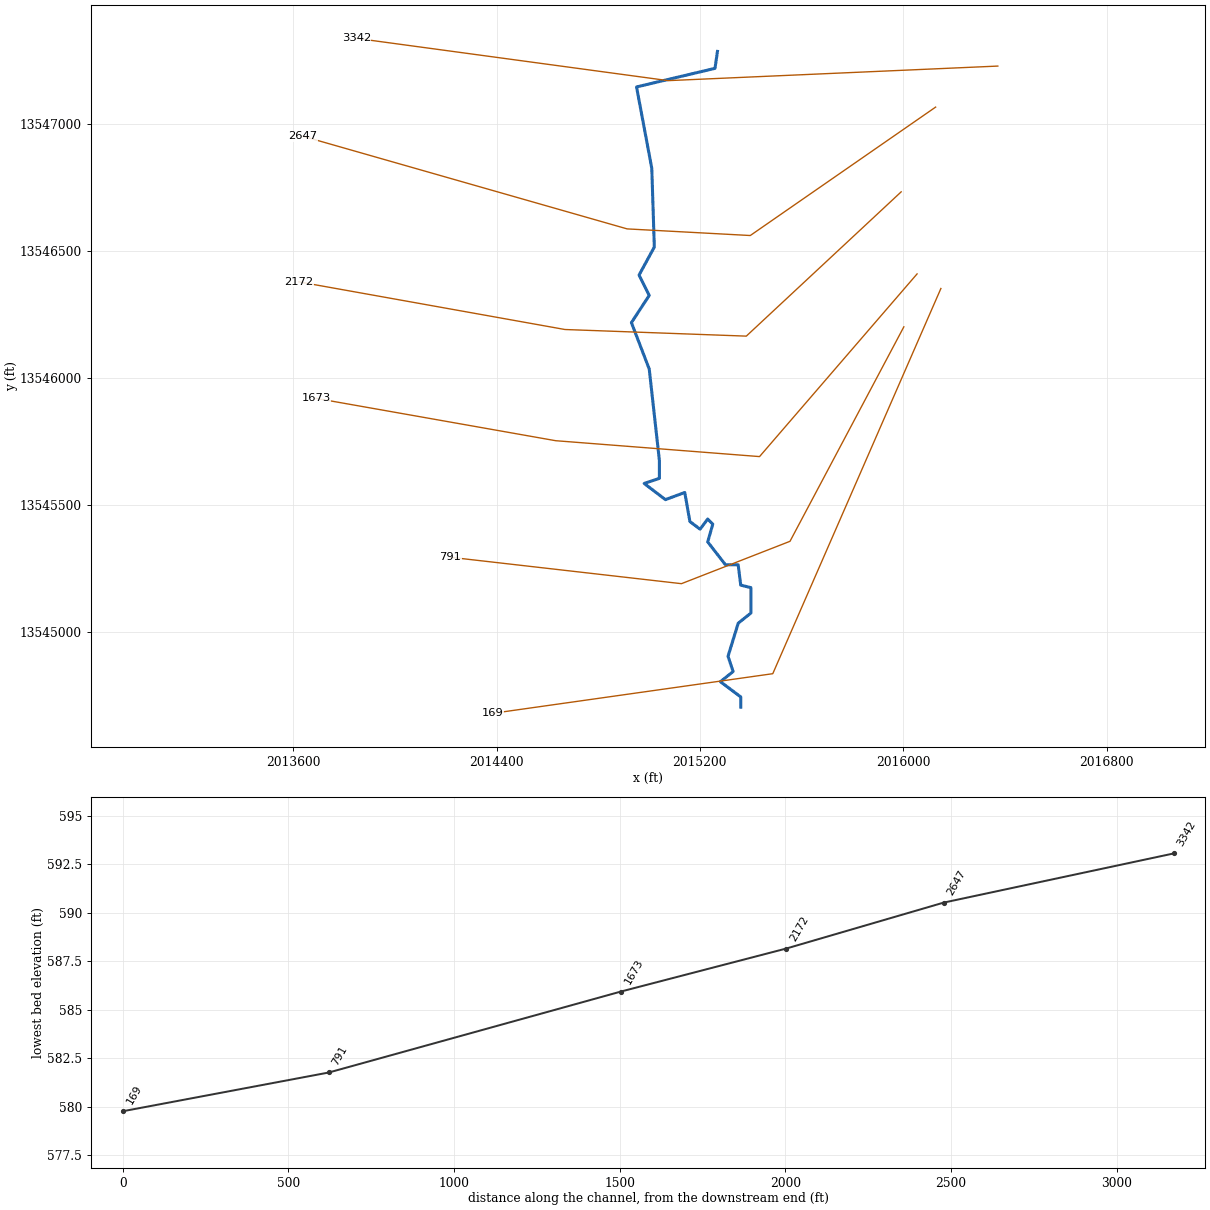
--- UNT 012 in HW.prj (project) ---

Proj Title=UNT 012 in HW Base Level Engineering
Current Plan=p01
Default Exp/Contr=0.3,0.1
English Units
Geom File=g01
Flow File=f01
Plan File=p01
BEGIN DESCRIPTION:
UNT 012 in HW
END DESCRIPTION:

--- UNT 012 in HW.p01 (plan) ---

Plan Title=Multiple Run
Short Identifier=Multiple
Geom File=g01
Flow File=f01
Subcritical Flow
K Sum by GR= 0
Std Step Tol= 0.01
Critical Tol= 0.01
Num of Std Step Trials= 20
Max Error Tol= 0.3
Flow Tol Ratio= 0.001
Split Flow NTrial= 30
Split Flow Tol= 0.02
Split Flow Ratio= 0.02
Log Output Level= 0
Friction Slope Method= 1
Unsteady Friction Slope Method= 2
Unsteady Bridges Friction Slope Method= 1
Parabolic Critical Depth
Global Vel Dist=  1 , 1 , 1
Global Log Level= 0
CheckData=True
Encroach Param= -1, 0, 0, 0
BEGIN DESCRIPTION:
Multiple Run
END DESCRIPTION:

--- UNT 012 in HW.f01 (steady flow) ---

Flow Title=Multiple
Number of Profiles=7
Profile Names=10-year,25-year,50-year,1pct_min,100-year,1pct_plu,500-year
River Rch & RM= UNT 012 in HW,Reach-1,3342
     471     658     813     497     992    1980    1486
River Rch & RM= UNT 012 in HW,Reach-1,2172
     527     745     926     571    1140    2275    1738
Boundary for River Rch & Prof#=UNT 012 in HW,Reach-1,1
Up Type=0
Dn Type=3
Dn Slope=0.005
Boundary for River Rch & Prof#=UNT 012 in HW,Reach-1,2
Up Type=0
Dn Type=3
Dn Slope=0.005
Boundary for River Rch & Prof#=UNT 012 in HW,Reach-1,3
Up Type=0
Dn Type=3
Dn Slope=0.005
Boundary for River Rch & Prof#=UNT 012 in HW,Reach-1,4
Up Type=0
Dn Type=3
Dn Slope=0.005
Boundary for River Rch & Prof#=UNT 012 in HW,Reach-1,5
Up Type=0
Dn Type=3
Dn Slope=0.005
Boundary for River Rch & Prof#=UNT 012 in HW,Reach-1,6
Up Type=0
Dn Type=3
Dn Slope=0.005
Boundary for River Rch & Prof#=UNT 012 in HW,Reach-1,7
Up Type=0
Dn Type=3
Dn Slope=0.005

--- UNT 012 in HW.g01 (geometry) ---

Geom Title=Existing Conditions

River Reach=UNT 012 in HW,Reach-1
Reach XY= 30
      2015269.21     13547284.39      2015259.49     13547217.72
      2014950.80     13547144.54      2015010.80     13546824.54
      2015020.80     13546514.54      2014960.80     13546404.54
      2015000.80     13546324.54      2014930.67     13546217.20
      2015000.80     13546034.54      2015040.80     13545674.54
      2015040.80     13545604.54      2014980.80     13545584.54
      2015064.52     13545520.85      2015140.56     13545548.97
      2015160.80     13545434.54      2015200.80     13545404.54
      2015230.80     13545444.54      2015250.80     13545424.54
      2015230.80     13545354.54      2015300.80     13545264.54
      2015350.80     13545264.54      2015360.80     13545184.54
      2015400.80     13545174.54      2015400.80     13545074.54
      2015350.80     13545034.54      2015310.80     13544904.54
      2015330.80     13544844.54      2015280.80     13544804.54
      2015360.80     13544744.54      2015360.80     13544704.54

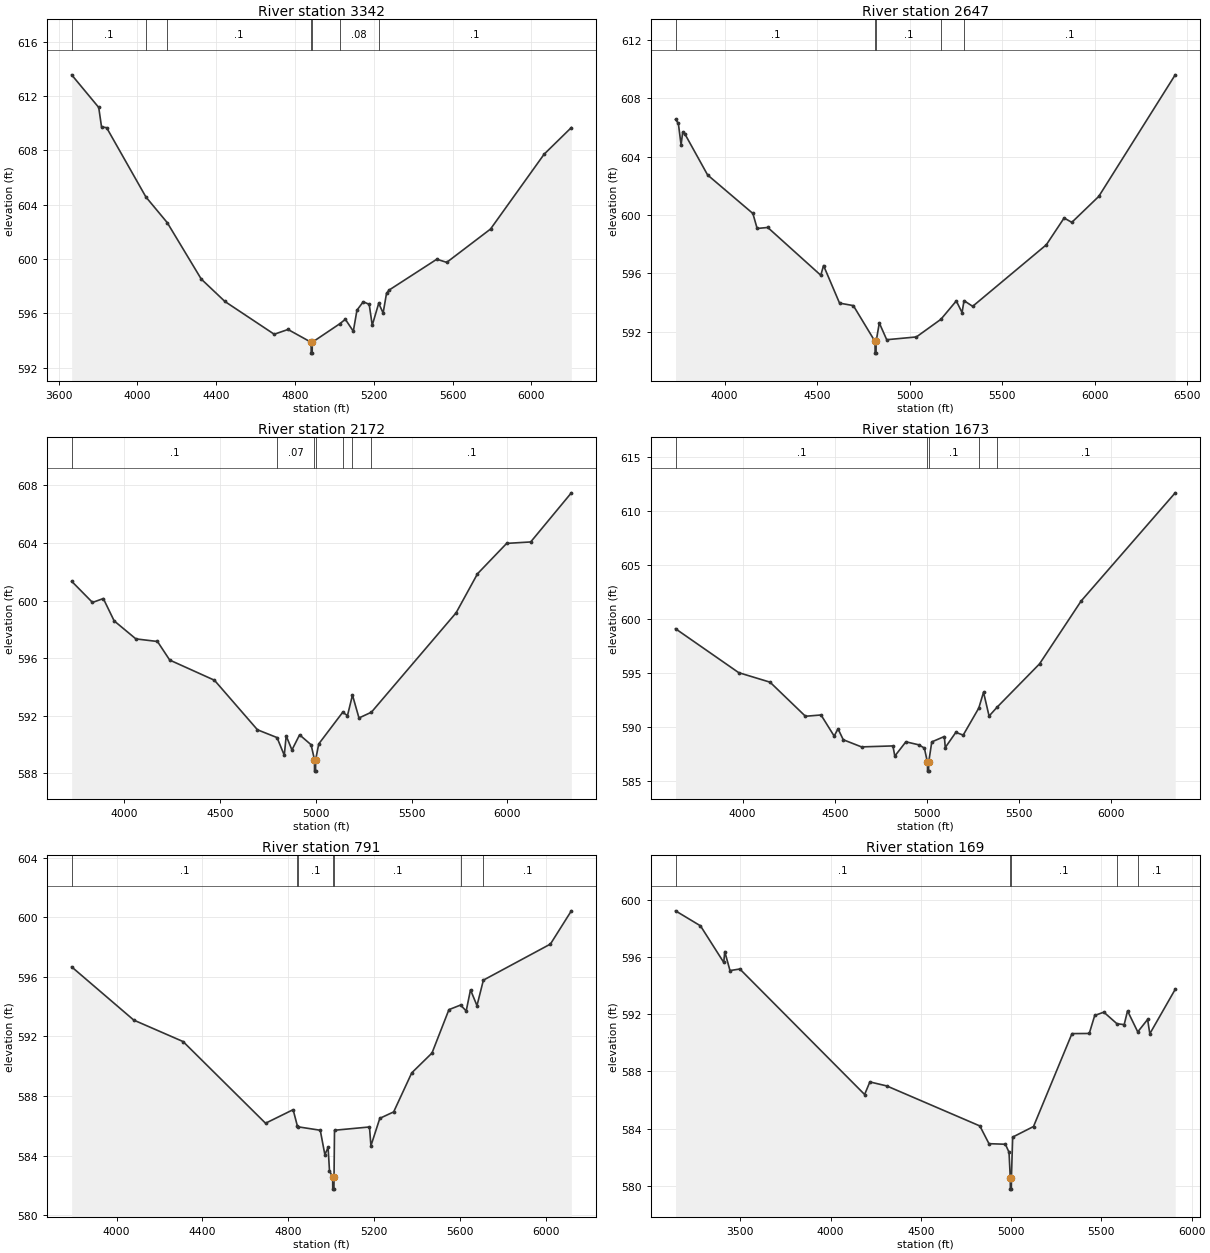
Type RM Length L Ch R = 1,3342,695,695,695
BEGIN DESCRIPTION:
UNT 012 in HW 2.0
END DESCRIPTION:
XS GIS Cut Line= 3
      2016372.30     13547226.66      2015075.41     13547169.37
      2013848.09     13547335.79
#Sta/Elev= 30
  3666.5  613.55  3803.9  611.15  3818.2  609.72  3844.0  609.66  4043.5  604.56
  4151.9  602.67  4324.4  598.52  4444.6  596.87  4694.8  594.46  4764.9  594.81
  4882.0  593.87  4882.5  593.07  4887.5  593.07  4888.0  593.87  5027.5  595.23
  5055.9  595.56  5096.3  594.68  5114.8  596.23  5146.7  596.85  5177.0  596.66
  5192.4  595.12  5225.3  596.74  5247.6  596.02  5264.9  597.47  5277.9  597.71
  5520.1  599.98  5570.6  599.75  5792.8  602.20  6065.0  607.71  6203.2  609.67
#Mann=7,-1,0
  3666.5     0.1       0  4043.5    0.08       0  4151.9     0.1       0
  4882.0    0.07       0  4888.0     0.1       0  5027.5    0.08       0
  5225.3     0.1       0
Bank Sta=4882,4888
Exp/Cntr=0.3,0.1

Type RM Length L Ch R = 1,2647,475,475,475
BEGIN DESCRIPTION:
Mapping XS 23dc3cfc
END DESCRIPTION:
XS GIS Cut Line= 4
      2016127.53     13547065.23      2015398.33     13546560.00
      2014913.95     13546586.04      2013637.91     13546950.62
#Sta/Elev= 30
  3734.8  606.56  3750.1  606.29  3764.9  604.82  3773.7  605.69  3786.5  605.54
  3908.2  602.75  4152.7  600.11  4175.8  599.08  4233.1  599.15  4519.6  595.87
  4534.4  596.54  4620.9  593.96  4695.4  593.79  4812.5  591.33  4813.0  590.53
  4818.0  590.53  4818.5  591.33  4835.6  592.60  4875.6  591.45  5035.9  591.64
  5168.3  592.85  5251.5  594.11  5282.7  593.31  5293.2  594.13  5339.9  593.74
  5737.7  597.96  5833.9  599.80  5875.5  599.50  6021.1  601.28  6434.1  609.62
#Mann=5,-1,0
  3734.8     0.1       0  4812.5    0.07       0  4818.5     0.1       0
  5168.3    0.08       0  5293.2     0.1       0
Bank Sta=4812.5,4818.5
Exp/Cntr=0.3,0.1

Type RM Length L Ch R = 1,2172,499,499,499
BEGIN DESCRIPTION:
Mapping XS ba87fafe
END DESCRIPTION:
XS GIS Cut Line= 4
      2015992.04     13546731.84      2015382.70     13546164.16
      2014669.16     13546190.20      2013622.33     13546377.69
#Sta/Elev= 30
  3724.1  601.34  3832.9  599.87  3889.5  600.14  3946.2  598.59  4059.6  597.34
  4172.4  597.16  4236.4  595.87  4470.0  594.47  4694.7  591.03  4796.9  590.49
  4834.8  589.26  4844.8  590.61  4874.8  589.63  4914.8  590.68  4974.9  589.99
  4992.4  588.96  4992.9  588.16  4998.2  588.16  4998.7  588.96  5014.9  590.05
  5139.7  592.24  5165.0  592.02  5191.0  593.44  5225.0  591.85  5289.9  592.25
  5732.3  599.15  5844.1  601.86  5996.4  603.97  6122.0  604.07  6334.4  607.48
#Mann=7,-1,0
  3724.1     0.1       0  4796.9    0.07       0  4992.4    0.07       0
  4998.7    0.07       0  5139.7    0.08       0  5191.0    0.05       0
  5289.9     0.1       0
Bank Sta=4992.4,4998.7
Exp/Cntr=0.3,0.1

Type RM Length L Ch R = 1,1673,882,882,882
BEGIN DESCRIPTION:
Mapping XS 5798b919
END DESCRIPTION:
XS GIS Cut Line= 4
      2016054.57     13546408.94      2015434.78     13545690.20
      2014632.70     13545752.70      2013689.99     13545919.37
#Sta/Elev= 30
  3635.7  599.10  3978.6  595.04  4148.6  594.16  4340.6  591.01  4425.1  591.13
  4496.4  589.18  4517.3  589.85  4545.8  588.84  4644.7  588.18  4815.2  588.27
  4825.3  587.33  4885.5  588.65  4955.7  588.37  4985.8  588.07  5002.6  586.74
  5003.1  585.94  5008.5  585.94  5009.0  586.74  5025.9  588.64  5094.1  589.14
  5099.1  588.12  5156.3  589.52  5196.4  589.27  5281.0  591.77  5306.7  593.23
  5336.8  591.03  5380.9  591.86  5610.4  595.85  5836.1  601.66  6346.6  611.66
#Mann=5,-1,0
  3635.7     0.1       0  5002.6    0.07       0  5009.0     0.1       0
  5281.0    0.08       0  5380.9     0.1       0
Bank Sta=5002.6,5009
Exp/Cntr=0.3,0.1

Type RM Length L Ch R = 1,791,622,622,622
BEGIN DESCRIPTION:
Mapping XS 4dc94f94
END DESCRIPTION:
XS GIS Cut Line= 4
      2016002.52     13546200.66      2015554.58     13545356.87
      2015127.49     13545190.20      2014217.98     13545294.15
#Sta/Elev= 30
  3790.7  596.67  4080.2  593.10  4310.1  591.66  4694.5  586.18  4823.0  587.09
  4843.1  585.98  4845.9  585.94  4949.5  585.71  4971.0  584.07  4986.0  584.56
  4992.5  582.99  5007.3  582.56  5007.8  581.76  5013.2  581.76  5013.7  582.56
  5015.9  585.71  5178.9  585.93  5185.7  584.67  5227.1  586.51  5291.6  586.94
  5375.9  589.56  5470.3  590.89  5549.2  593.80  5603.6  594.11  5629.7  593.71
  5649.8  595.13  5680.0  594.07  5709.8  595.78  6022.3  598.20  6119.9  600.43
#Mann=7,-1,0
  3790.7     0.1       0  4843.1    0.05       0  4845.9     0.1       0
  5007.3    0.07       0  5013.7     0.1       0  5603.6    0.08       0
  5709.8     0.1       0
Bank Sta=5007.3,5013.7
Exp/Cntr=0.3,0.1

Type RM Length L Ch R = 1,169,0,0,0
BEGIN DESCRIPTION:
UNT 012 in HW 1.0
END DESCRIPTION:
XS GIS Cut Line= 3
      2016148.31     13546351.62      2015486.87     13544836.04
      2014383.49     13544679.90
#Sta/Elev= 30
  3141.0  599.23  3279.2  598.18  3408.2  595.62  3413.7  596.38  3442.8  595.05
  3497.4  595.16  4188.5  586.38  4217.5  587.26  4311.0  586.98  4826.8  584.18
  4877.3  582.94  4968.2  582.90  4988.4  582.34  4995.3  580.56  4995.8  579.76
  5001.2  579.76  5001.7  580.56  5008.6  583.40  5124.0  584.14  5337.1  590.64
  5432.8  590.65  5463.1  591.91  5513.6  592.14  5586.3  591.33  5626.3  591.27
  5644.9  592.23  5701.5  590.76  5756.0  591.63  5768.3  590.63  5909.0  593.74
#Mann=5,-1,0
  3141.0     0.1       0  4995.3    0.07       0  5001.7     0.1       0
  5586.3    0.08       0  5701.5     0.1       0
Bank Sta=4995.3,5001.7
Exp/Cntr=0.3,0.1

Chan Stop Cuts=-1