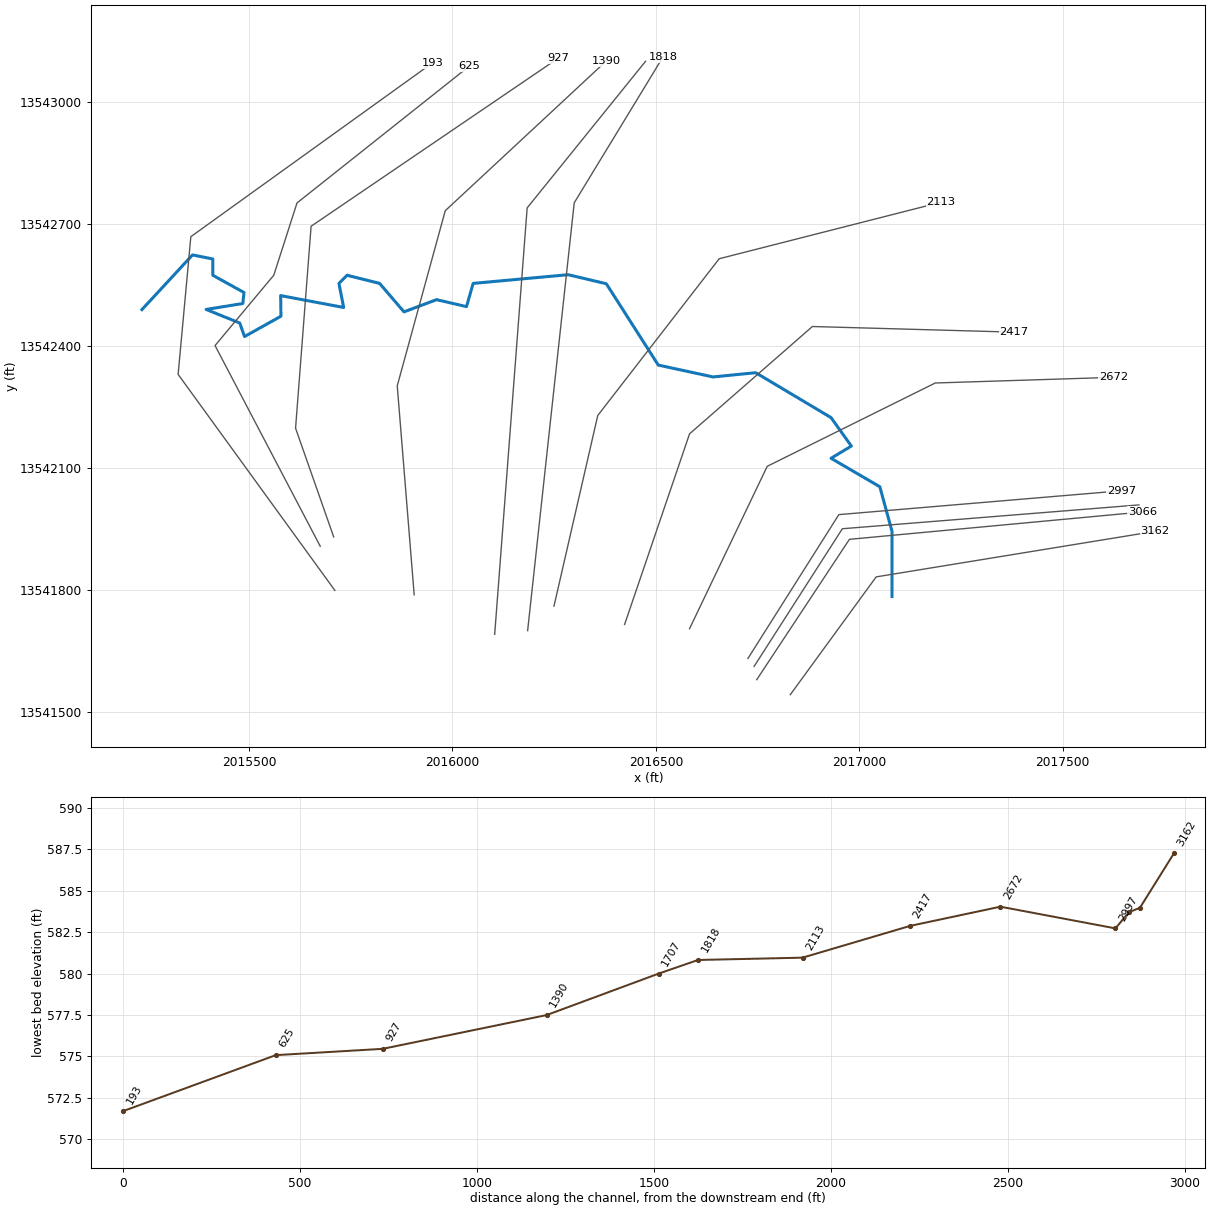
--- UNT 013 in HW.prj (project) ---

Proj Title=UNT 013 in HW Base Level Engineering
Current Plan=p01
Default Exp/Contr=0.3,0.1
English Units
Geom File=g01
Flow File=f01
Plan File=p01
BEGIN DESCRIPTION:
UNT 013 in HW
END DESCRIPTION:

--- UNT 013 in HW.p01 (plan) ---

Plan Title=Multiple Run
Short Identifier=Multiple
Geom File=g01
Flow File=f01
Subcritical Flow
K Sum by GR= 0
Std Step Tol= 0.01
Critical Tol= 0.01
Num of Std Step Trials= 20
Max Error Tol= 0.3
Flow Tol Ratio= 0.001
Split Flow NTrial= 30
Split Flow Tol= 0.02
Split Flow Ratio= 0.02
Log Output Level= 0
Friction Slope Method= 1
Unsteady Friction Slope Method= 2
Unsteady Bridges Friction Slope Method= 1
Parabolic Critical Depth
Global Vel Dist=  1 , 1 , 1
Global Log Level= 0
CheckData=True
Encroach Param= -1, 0, 0, 0
BEGIN DESCRIPTION:
Multiple Run
END DESCRIPTION:

--- UNT 013 in HW.f01 (steady flow) ---

Flow Title=Multiple
Number of Profiles=7
Profile Names=10-year,25-year,50-year,1pct_min,100-year,1pct_plu,500-year
River Rch & RM= UNT 013 in HW,Reach-1,3162
     148     197     237     142     283     564     409
River Rch & RM= UNT 013 in HW,Reach-1,2672
     228     312     380     231     462     921     690
Boundary for River Rch & Prof#=UNT 013 in HW,Reach-1,1
Up Type=0
Dn Type=3
Dn Slope=0.005
Boundary for River Rch & Prof#=UNT 013 in HW,Reach-1,2
Up Type=0
Dn Type=3
Dn Slope=0.005
Boundary for River Rch & Prof#=UNT 013 in HW,Reach-1,3
Up Type=0
Dn Type=3
Dn Slope=0.005
Boundary for River Rch & Prof#=UNT 013 in HW,Reach-1,4
Up Type=0
Dn Type=3
Dn Slope=0.005
Boundary for River Rch & Prof#=UNT 013 in HW,Reach-1,5
Up Type=0
Dn Type=3
Dn Slope=0.005
Boundary for River Rch & Prof#=UNT 013 in HW,Reach-1,6
Up Type=0
Dn Type=3
Dn Slope=0.005
Boundary for River Rch & Prof#=UNT 013 in HW,Reach-1,7
Up Type=0
Dn Type=3
Dn Slope=0.005

--- UNT 013 in HW.g01 (geometry) ---

Geom Title=Existing Conditions

River Reach=UNT 013 in HW,Reach-1
Reach XY= 30
      2017080.80     13541784.54      2017080.80     13541944.54
      2017050.80     13542054.54      2016930.80     13542124.54
      2016980.80     13542154.54      2016930.80     13542224.54
      2016745.62     13542334.93      2016640.80     13542324.54
      2016506.04     13542353.68      2016378.26     13542553.68
      2016284.51     13542575.90      2016050.80     13542554.54
      2016034.51     13542497.43      2015960.80     13542514.54
      2015880.80     13542484.54      2015820.80     13542554.54
      2015740.80     13542574.54      2015720.80     13542554.54
      2015732.43     13542495.35      2015577.57     13542524.52
      2015578.26     13542473.82      2015488.68     13542423.82
      2015476.88     13542457.15      2015394.24     13542490.49
      2015484.51     13542505.07      2015487.29     13542532.15
      2015410.80     13542574.54      2015410.80     13542614.54
      2015360.80     13542624.54      2015236.42     13542490.07

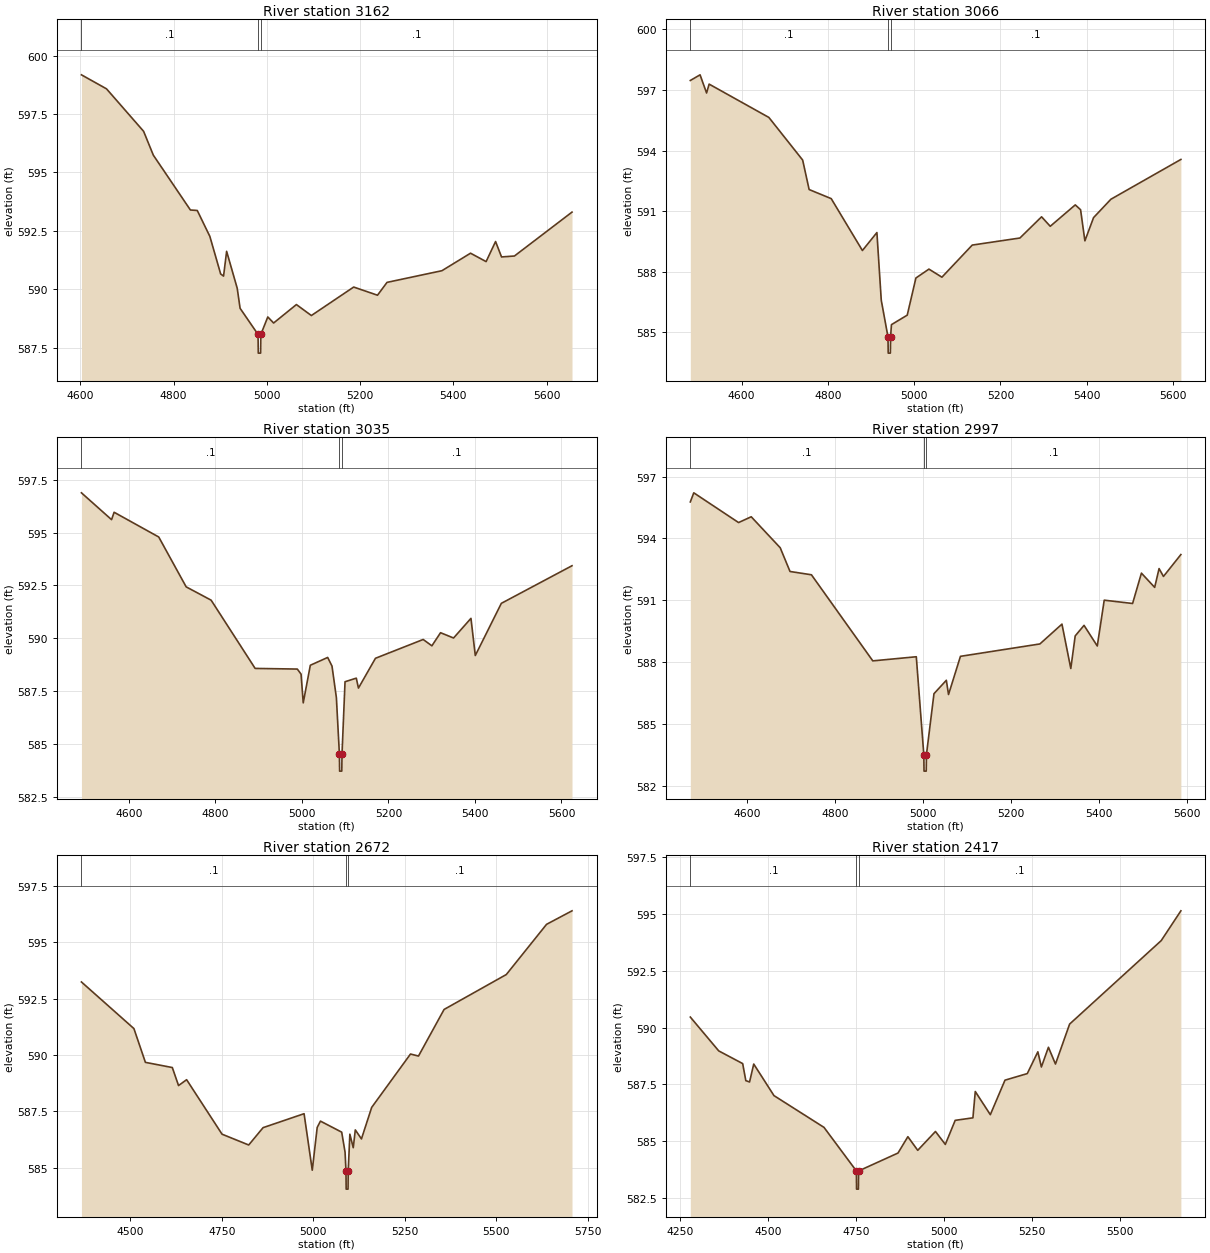
Type RM Length L Ch R = 1,3162,96,96,96
BEGIN DESCRIPTION:
UNT 013 in HW 3.0
END DESCRIPTION:
XS GIS Cut Line= 3
      2016830.64     13541543.31      2017041.84     13541832.90
      2017726.84     13541944.75
#Sta/Elev= 30
  4602.1  599.18  4655.9  598.58  4735.5  596.76  4756.3  595.74  4835.9  593.39
  4850.6  593.37  4877.6  592.26  4900.8  590.65  4907.0  590.56  4913.6  591.62
  4936.3  590.04  4942.5  589.18  4981.0  588.06  4981.5  587.26  4986.5  587.26
  4987.0  588.06  5001.9  588.81  5014.4  588.55  5063.3  589.34  5095.4  588.87
  5186.2  590.09  5237.3  589.74  5257.7  590.29  5375.5  590.79  5436.9  591.54
  5470.3  591.18  5490.6  592.04  5503.4  591.38  5531.1  591.42  5654.6  593.30
#Mann=3,-1,0
  4602.1     0.1       0  4981.0    0.07       0  4987.0     0.1       0
Bank Sta=4981,4987
Exp/Cntr=0.3,0.1

Type RM Length L Ch R = 1,3066,31,31,31
BEGIN DESCRIPTION:
Mapping XS b6bc8e55
END DESCRIPTION:
XS GIS Cut Line= 3
      2016748.17     13541580.21      2016976.02     13541925.23
      2017696.52     13541992.51
#Sta/Elev= 30
  4481.3  597.47  4503.9  597.75  4519.0  596.85  4524.9  597.29  4663.4  595.64
  4741.7  593.53  4756.7  592.07  4807.9  591.62  4880.2  589.05  4913.8  589.94
  4923.9  586.59  4939.5  584.77  4940.0  583.97  4945.0  583.97  4945.5  584.77
  4947.5  585.38  4984.1  585.85  5004.2  587.69  5034.4  588.13  5064.5  587.73
  5134.8  589.32  5245.3  589.67  5295.5  590.72  5315.6  590.25  5373.6  591.31
  5385.9  591.07  5395.9  589.53  5416.0  590.68  5456.2  591.59  5618.4  593.56
#Mann=3,-1,0
  4481.3     0.1       0  4939.5    0.07       0  4945.5     0.1       0
Bank Sta=4939.5,4945.5
Exp/Cntr=0.3,0.1

Type RM Length L Ch R = 1,3035,38,38,38
BEGIN DESCRIPTION:
Mapping XS 5c7d3122
END DESCRIPTION:
XS GIS Cut Line= 3
      2016741.64     13541612.73      2016958.66     13541951.27
      2017687.77     13542009.86
#Sta/Elev= 30
  4490.7  596.88  4560.3  595.61  4566.2  595.96  4669.3  594.79  4732.7  592.43
  4790.4  591.80  4892.1  588.57  4989.5  588.54  4998.2  588.30  5003.2  586.94
  5019.6  588.72  5059.7  589.09  5069.7  588.68  5079.8  587.19  5086.8  584.51
  5087.3  583.71  5092.3  583.71  5092.8  584.51  5099.8  587.94  5125.8  588.11
  5130.8  587.64  5170.1  589.05  5280.4  589.94  5300.5  589.64  5320.5  590.26
  5350.6  590.01  5390.8  590.94  5400.8  589.18  5461.0  591.65  5624.3  593.43
#Mann=3,-1,0
  4490.7     0.1       0  5086.8    0.07       0  5092.8     0.1       0
Bank Sta=5086.8,5092.8
Exp/Cntr=0.3,0.1

Type RM Length L Ch R = 1,2997,325,325,325
BEGIN DESCRIPTION:
Mapping XS d7a51d5a
END DESCRIPTION:
XS GIS Cut Line= 3
      2016726.43     13541632.22      2016949.98     13541985.99
      2017644.42     13542044.59
#Sta/Elev= 30
  4470.3  595.77  4478.2  596.21  4580.0  594.77  4608.8  595.05  4674.7  593.55
  4697.0  592.40  4745.7  592.24  4885.2  588.07  4984.1  588.27  5001.2  583.53
  5001.7  582.73  5006.7  582.73  5007.2  583.53  5024.3  586.48  5052.4  587.13
  5057.4  586.44  5084.5  588.29  5265.1  588.89  5315.3  589.85  5335.4  587.70
  5345.4  589.28  5365.5  589.79  5395.6  588.79  5411.4  591.01  5475.9  590.85
  5496.0  592.32  5526.1  591.63  5536.1  592.54  5546.1  592.16  5585.7  593.22
#Mann=3,-1,0
  4470.3     0.1       0  5001.2    0.07       0  5007.2     0.1       0
Bank Sta=5001.2,5007.2
Exp/Cntr=0.3,0.1

Type RM Length L Ch R = 1,2672,255,255,255
BEGIN DESCRIPTION:
Mapping XS 6a7387b4
END DESCRIPTION:
XS GIS Cut Line= 4
      2016582.95     13541705.50      2016773.90     13542104.77
      2017187.10     13542309.63      2017624.61     13542323.52
#Sta/Elev= 30
  4365.9  593.24  4509.4  591.17  4540.8  589.67  4614.4  589.44  4631.4  588.64
  4653.5  588.90  4750.4  586.48  4823.3  586.00  4862.6  586.77  4974.7  587.39
  4997.1  584.88  5010.6  586.78  5019.5  587.06  5077.6  586.57  5086.8  585.68
  5089.3  584.84  5089.8  584.04  5094.9  584.04  5095.4  584.84  5099.9  586.48
  5109.2  585.88  5114.8  586.67  5131.6  586.27  5159.6  587.67  5265.7  590.04
  5287.6  589.95  5357.6  592.02  5527.7  593.57  5637.8  595.80  5707.4  596.40
#Mann=3,-1,0
  4365.9     0.1       0  5089.3    0.07       0  5095.4     0.1       0
Bank Sta=5089.3,5095.4
Exp/Cntr=0.3,0.1

Type RM Length L Ch R = 1,2417,304,304,304
BEGIN DESCRIPTION:
Mapping XS 5becf197
END DESCRIPTION:
XS GIS Cut Line= 4
      2016423.22     13541715.91      2016582.93     13542184.63
      2016885.02     13542448.52      2017380.73     13542434.66
#Sta/Elev= 30
  4280.2  590.46  4360.8  588.97  4428.8  588.41  4437.7  587.66  4448.3  587.60
  4460.2  588.39  4517.6  587.00  4659.6  585.60  4751.5  583.68  4752.0  582.88
  4757.2  582.88  4757.7  583.68  4869.6  584.47  4897.6  585.19  4925.6  584.59
  4975.9  585.42  5003.9  584.85  5031.9  585.91  5082.2  586.02  5088.9  587.18
  5131.6  586.16  5173.2  587.68  5236.5  587.97  5266.5  588.93  5276.5  588.26
  5296.5  589.13  5316.5  588.39  5356.6  590.15  5616.7  593.83  5672.4  595.14
#Mann=3,-1,0
  4280.2     0.1       0  4751.5    0.07       0  4757.7     0.1       0
Bank Sta=4751.5,4757.7
Exp/Cntr=0.3,0.1

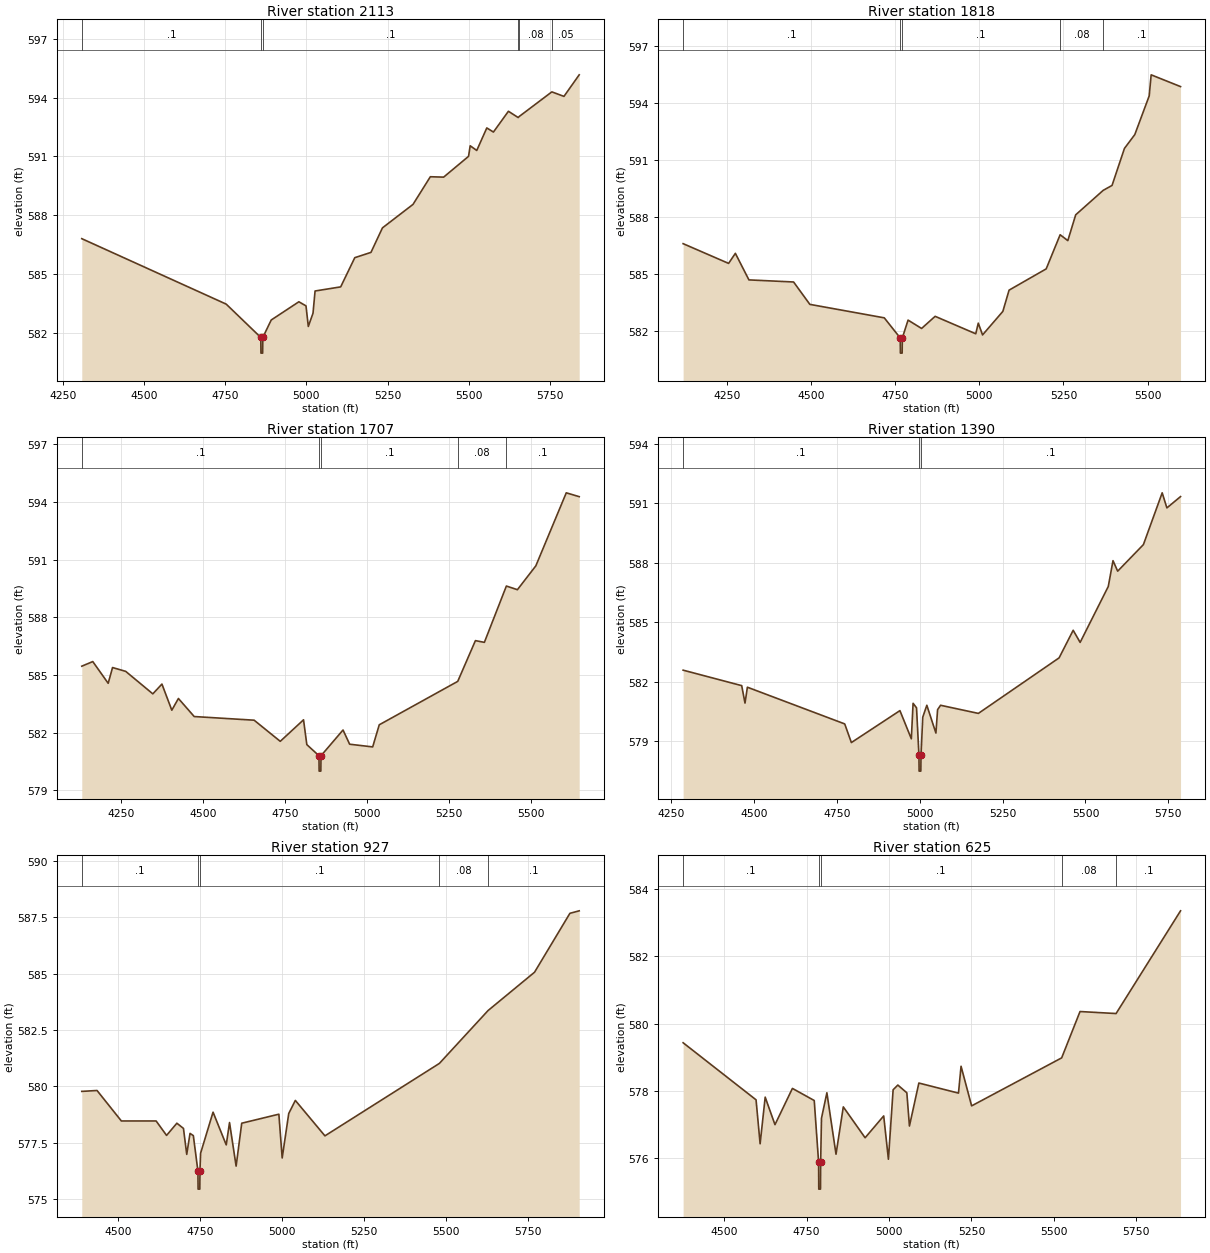
Type RM Length L Ch R = 1,2113,295,295,295
BEGIN DESCRIPTION:
Mapping XS 7e44c766
END DESCRIPTION:
XS GIS Cut Line= 4
      2016249.60     13541761.05      2016357.24     13542229.77
      2016655.85     13542615.19      2017200.47     13542753.94
#Sta/Elev= 30
  4308.9  586.80  4753.3  583.46  4859.7  581.76  4860.2  580.96  4865.4  580.96
  4865.9  581.76  4891.8  582.65  4976.9  583.58  4998.8  583.37  5005.9  582.32
  5020.4  583.00  5026.7  584.13  5105.5  584.34  5148.9  585.83  5198.7  586.10
  5234.0  587.35  5328.1  588.55  5381.4  589.96  5422.3  589.94  5498.9  591.00
  5504.0  591.54  5524.2  591.30  5555.1  592.45  5575.5  592.24  5621.6  593.30
  5651.7  592.98  5654.5  593.03  5755.2  594.29  5792.5  594.06  5839.4  595.16
#Mann=6,-1,0
  4308.9     0.1       0  4859.7    0.07       0  4865.9     0.1       0
  5651.7    0.05       0  5654.5    0.08       0  5755.2    0.05       0
Bank Sta=4859.7,4865.9
Exp/Cntr=0.3,0.1

Type RM Length L Ch R = 1,1818,111,111,111
BEGIN DESCRIPTION:
UNT 013 in HW 2.0
END DESCRIPTION:
XS GIS Cut Line= 3
      2016184.79     13541700.66      2016299.37     13542752.70
      2016517.51     13543111.07
#Sta/Elev= 30
  4120.3  586.59  4255.4  585.55  4275.5  586.08  4315.8  584.68  4448.5  584.57
  4496.8  583.39  4717.9  582.68  4765.3  581.62  4765.8  580.82  4771.0  580.82
  4771.5  581.62  4788.6  582.56  4828.8  582.12  4869.0  582.76  4989.7  581.84
  4997.2  582.40  5009.9  581.78  5070.2  583.02  5088.7  584.14  5198.9  585.26
  5240.4  587.06  5263.2  586.75  5286.6  588.11  5368.3  589.40  5394.6  589.66
  5431.4  591.61  5462.2  592.34  5505.0  594.38  5510.8  595.49  5598.1  594.87
#Mann=5,-1,0
  4120.3     0.1       0  4765.3    0.07       0  4771.5     0.1       0
  5240.4    0.08       0  5368.3     0.1       0
Bank Sta=4765.3,4771.5
Exp/Cntr=0.3,0.1

Type RM Length L Ch R = 1,1707,317,317,317
BEGIN DESCRIPTION:
Mapping XS de6f998d
END DESCRIPTION:
XS GIS Cut Line= 3
      2016103.77     13541691.58      2016183.63     13542740.19
      2016474.77     13543100.65
#Sta/Elev= 30
  4131.4  585.46  4164.9  585.70  4211.8  584.57  4225.1  585.39  4265.2  585.19
  4347.8  584.02  4375.5  584.53  4405.6  583.17  4425.7  583.78  4473.8  582.84
  4656.3  582.65  4735.9  581.55  4806.8  582.67  4816.8  581.38  4853.8  580.80
  4854.3  580.00  4859.5  580.00  4860.0  580.80  4927.1  582.14  4947.2  581.40
  5017.4  581.26  5037.4  582.41  5276.5  584.67  5330.3  586.79  5357.6  586.70
  5424.6  589.63  5458.2  589.44  5514.3  590.68  5607.0  594.48  5646.4  594.28
#Mann=5,-1,0
  4131.4     0.1       0  4853.8    0.07       0  4860.0     0.1       0
  5276.5    0.08       0  5424.6     0.1       0
Bank Sta=4853.8,4860
Exp/Cntr=0.3,0.1

Type RM Length L Ch R = 1,1390,463,463,463
BEGIN DESCRIPTION:
Mapping XS d3e6dffb
END DESCRIPTION:
XS GIS Cut Line= 4
      2015905.85     13541788.81      2015864.18     13542302.69
      2015982.24     13542733.24      2016377.39     13543100.67
#Sta/Elev= 30
  4285.5  582.58  4462.3  581.80  4472.3  580.92  4479.5  581.72  4773.3  579.87
  4793.4  578.93  4940.0  580.54  4974.4  579.12  4979.7  580.91  4990.1  580.68
  4997.4  578.29  4997.9  577.49  5003.1  577.49  5003.6  578.29  5008.9  580.21
  5021.2  580.81  5048.6  579.41  5053.7  580.59  5062.7  580.81  5176.8  580.40
  5420.5  583.20  5463.0  584.59  5484.0  583.98  5569.0  586.80  5583.2  588.10
  5597.3  587.57  5675.0  588.91  5731.7  591.52  5745.9  590.76  5787.1  591.33
#Mann=3,-1,0
  4285.5     0.1       0  4997.4    0.07       0  5003.6     0.1       0
Bank Sta=4997.4,5003.6
Exp/Cntr=0.3,0.1

Type RM Length L Ch R = 1,927,302,302,302
BEGIN DESCRIPTION:
Mapping XS 3851289c
END DESCRIPTION:
XS GIS Cut Line= 4
      2015707.93     13541931.16      2015614.18     13542198.52
      2015652.38     13542695.05      2016259.99     13543108.23
#Sta/Elev= 30
  4389.7  579.78  4436.2  579.82  4510.3  578.47  4616.3  578.47  4648.1  577.83
  4679.5  578.37  4699.6  578.14  4709.6  576.99  4719.6  577.92  4729.7  577.82
  4743.7  576.25  4744.2  575.45  4749.4  575.45  4749.9  576.25  4751.8  577.04
  4789.8  578.86  4830.0  577.41  4840.0  578.40  4860.1  576.47  4877.2  578.37
  4990.4  578.77  5000.5  576.83  5020.5  578.80  5040.6  579.38  5130.8  577.81
  5479.7  581.02  5627.9  583.36  5769.7  585.06  5877.5  587.67  5905.8  587.78
#Mann=5,-1,0
  4389.7     0.1       0  4743.7    0.07       0  4749.9     0.1       0
  5479.7    0.08       0  5627.9     0.1       0
Bank Sta=4743.7,4749.9
Exp/Cntr=0.3,0.1

Type RM Length L Ch R = 1,625,432,432,432
BEGIN DESCRIPTION:
Mapping XS b4a4e5f1
END DESCRIPTION:
XS GIS Cut Line= 5
      2015674.87     13541908.12      2015416.20     13542401.65
      2015560.61     13542574.62      2015617.73     13542752.35
      2016040.70     13543088.18
#Sta/Elev= 30
  4375.3  579.43  4596.6  577.73  4608.9  576.42  4624.3  577.81  4654.0  576.99
  4706.9  578.07  4773.1  577.71  4786.4  575.87  4786.9  575.07  4792.1  575.07
  4792.6  575.87  4795.1  577.18  4811.5  577.94  4839.2  576.11  4861.3  577.52
  4927.5  576.60  4983.9  577.25  4998.2  575.96  5012.5  578.03  5026.8  578.17
  5054.1  577.94  5062.0  576.95  5090.6  578.23  5210.8  577.93  5218.6  578.73
  5250.7  577.55  5523.9  578.98  5579.6  580.36  5689.0  580.30  5884.6  583.36
#Mann=5,-1,0
  4375.3     0.1       0  4786.4    0.07       0  4792.6     0.1       0
  5523.9    0.08       0  5689.0     0.1       0
Bank Sta=4786.4,4792.6
Exp/Cntr=0.3,0.1

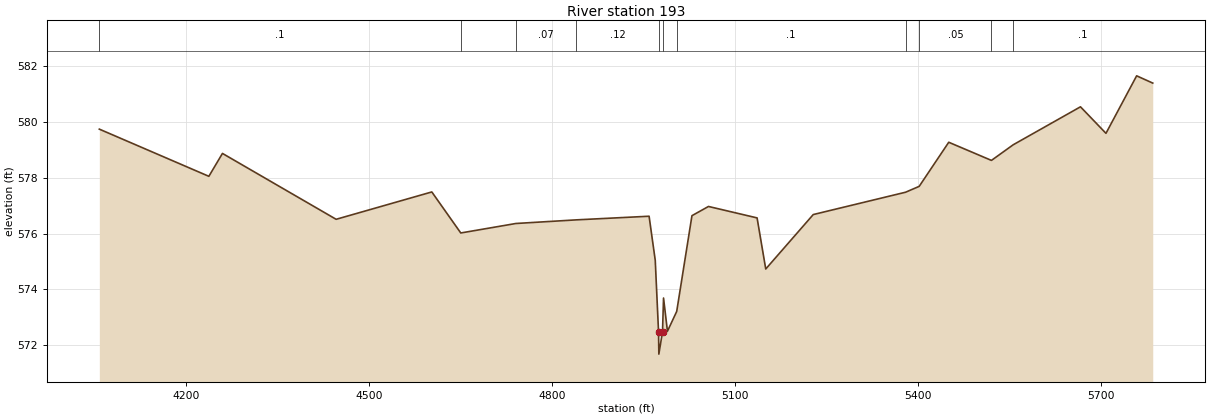
Type RM Length L Ch R = 1,193,0,0,0
BEGIN DESCRIPTION:
UNT 013 in HW 1.0
END DESCRIPTION:
XS GIS Cut Line= 4
      2015710.81     13541799.60      2015325.41     13542330.83
      2015356.66     13542669.37      2015950.18     13543096.29
#Sta/Elev= 30
  4057.9  579.74  4237.5  578.05  4259.8  578.87  4446.2  576.51  4603.1  577.49
  4650.6  576.02  4741.0  576.36  4840.3  576.49  4959.4  576.62  4969.5  575.04
  4974.9  572.48  4975.4  571.68  4981.4  572.48  4983.1  573.69  4989.5  572.50
  5004.7  573.21  5029.7  576.64  5056.8  576.97  5136.5  576.56  5150.7  574.73
  5228.6  576.68  5380.0  577.48  5402.3  577.69  5450.8  579.27  5520.8  578.62
  5556.5  579.18  5666.8  580.54  5708.6  579.59  5758.9  581.65  5785.3  581.39
#Mann=11,-1,0
  4057.9     0.1       0  4650.6    0.12       0  4741.0    0.07       0
  4840.3    0.12       0  4974.9    0.07       0  4981.4    0.12       0
  5004.7     0.1       0  5380.0    0.08       0  5402.3    0.05       0
  5520.8    0.08       0  5556.5     0.1       0
Bank Sta=4974.9,4981.4
Exp/Cntr=0.3,0.1

Chan Stop Cuts=-1