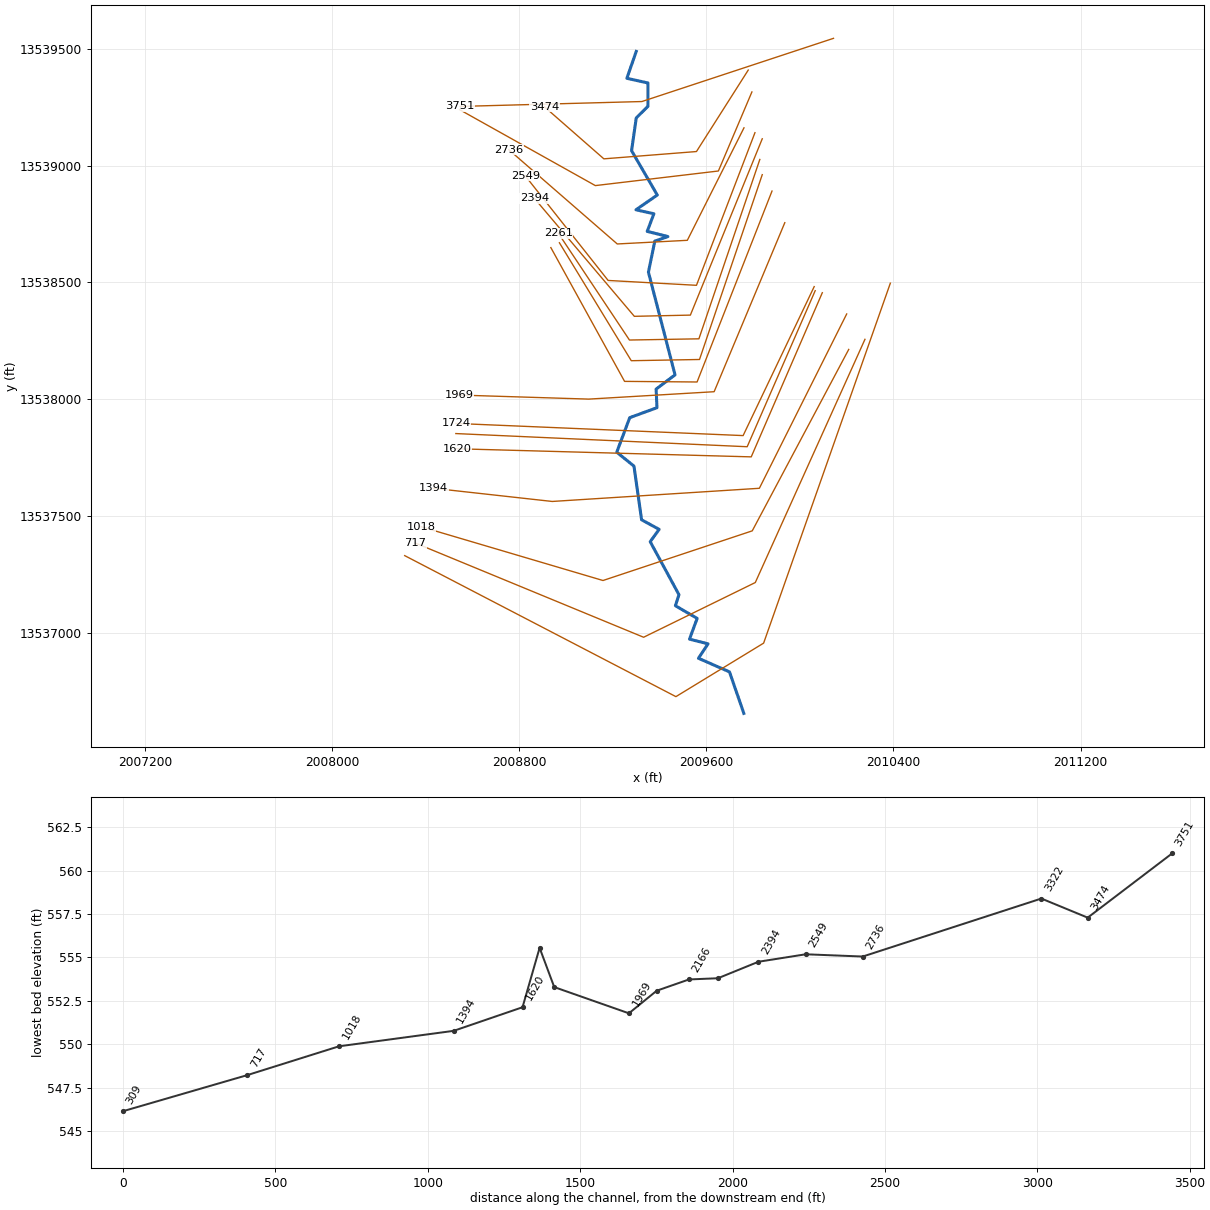
--- UNT 014 in HW.prj (project) ---

Proj Title=UNT 014 in HW Base Level Engineering
Current Plan=p01
Default Exp/Contr=0.3,0.1
English Units
Geom File=g01
Flow File=f01
Plan File=p01
Y Axis Title=Elevation
X Axis Title(PF)=Main Channel Distance
X Axis Title(XS)=Station
BEGIN DESCRIPTION:
UNT 014 in HW
END DESCRIPTION:
DSS Export Rating Curves= 0
DSS Export Rating Curve Sorted= 0
DSS Export Volume Flow Curves= 0
DXF OffsetX= 0
DXF OffsetY= 0
DXF ScaleX= 1
DXF ScaleY= 10

--- UNT 014 in HW.p01 (plan) ---

Plan Title=Multiple Run
Short Identifier=Multiple
Geom File=g01
Flow File=f01
Subcritical Flow
K Sum by GR= 0
Std Step Tol= 0.01
Critical Tol= 0.01
Num of Std Step Trials= 20
Max Error Tol= 0.3
Flow Tol Ratio= 0.001
Split Flow NTrial= 30
Split Flow Tol= 0.02
Split Flow Ratio= 0.02
Log Output Level= 0
Friction Slope Method= 1
Unsteady Friction Slope Method= 2
Unsteady Bridges Friction Slope Method= 1
Parabolic Critical Depth
Global Vel Dist=  1 , 1 , 1
Global Log Level= 0
CheckData=True
Encroach Param= -1, 0, 0, 0
BEGIN DESCRIPTION:
Multiple Run
END DESCRIPTION:

--- UNT 014 in HW.f01 (steady flow) ---

Flow Title=Multiple
Number of Profiles=7
Profile Names=10-year,25-year,50-year,1pct_min,100-year,1pct_plu,500-year
River Rch & RM= UNT 014 in HW,Reach-1,3751
     182     247     299     181     362     722     537
River Rch & RM= UNT 014 in HW,Reach-1,1676
     231     317     388     237     472     943     712
Boundary for River Rch & Prof#=UNT 014 in HW,Reach-1,1
Up Type=0
Dn Type=3
Dn Slope=0.005
Boundary for River Rch & Prof#=UNT 014 in HW,Reach-1,2
Up Type=0
Dn Type=3
Dn Slope=0.005
Boundary for River Rch & Prof#=UNT 014 in HW,Reach-1,3
Up Type=0
Dn Type=3
Dn Slope=0.005
Boundary for River Rch & Prof#=UNT 014 in HW,Reach-1,4
Up Type=0
Dn Type=3
Dn Slope=0.005
Boundary for River Rch & Prof#=UNT 014 in HW,Reach-1,5
Up Type=0
Dn Type=3
Dn Slope=0.005
Boundary for River Rch & Prof#=UNT 014 in HW,Reach-1,6
Up Type=0
Dn Type=3
Dn Slope=0.005
Boundary for River Rch & Prof#=UNT 014 in HW,Reach-1,7
Up Type=0
Dn Type=3
Dn Slope=0.005

--- UNT 014 in HW.g01 (geometry) ---

Geom Title=Existing Conditions
Program Version=5.05

River Reach=UNT 014 in HW   ,Reach-1
Reach XY= 30
       2009300.8     13539489.54       2009260.8     13539374.54
       2009350.8     13539354.54       2009350.8     13539254.54
       2009300.8     13539204.54       2009280.8     13539064.54
       2009390.8     13538874.54       2009299.5     13538811.31
      2009376.32     13538794.38      2009347.68     13538718.86
      2009436.22     13538696.73      2009380.23     13538677.19
      2009352.88     13538544.38       2009466.6     13538104.28
      2009385.87     13538043.51      2009389.34     13537963.65
      2009273.02     13537921.12      2009217.47      13537773.2
      2009291.08     13537713.48      2009323.72     13537483.62
      2009398.72     13537442.65      2009360.52     13537389.87
      2009483.44     13537162.79      2009468.16     13537115.56
      2009561.22      13537061.4      2009528.58     13536972.51
      2009607.75     13536952.37      2009566.77     13536890.56
      2009699.41     13536832.23       2009760.8     13536654.54

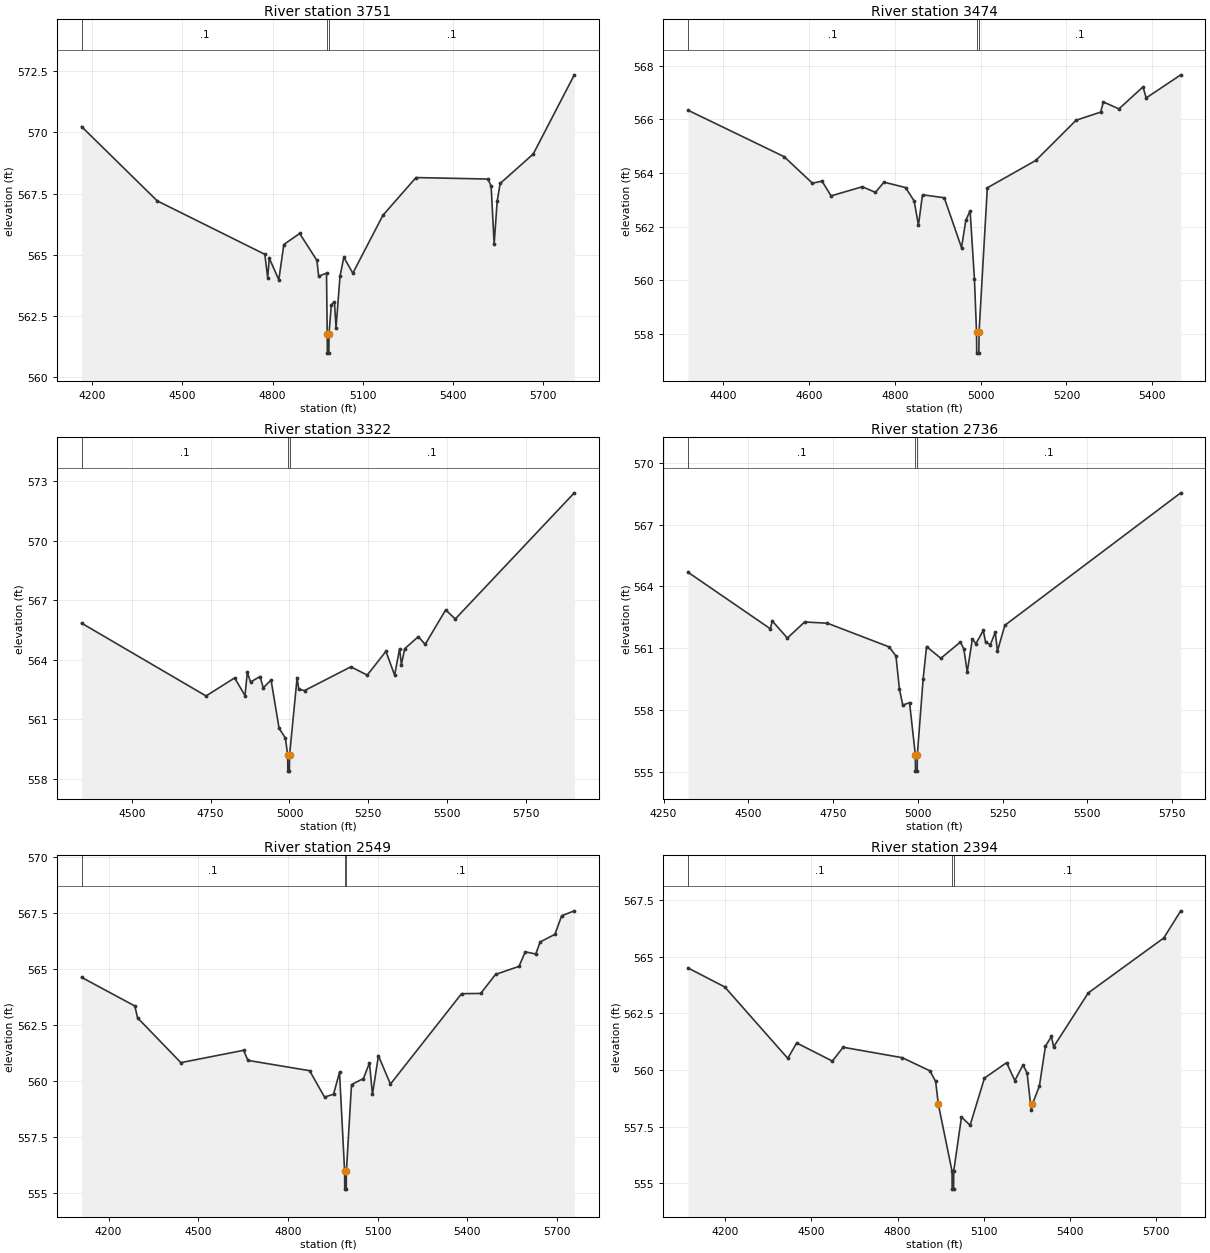
Type RM Length L Ch R = 1 ,3751    ,277,277,277
BEGIN DESCRIPTION:
UNT 014 in HW 3.0
END DESCRIPTION:
XS GIS Cut Line= 3
        2010144.     13539545.68        2009325.       13539275.
      2008548.35     13539254.05
#Sta/Elev= 30
  4164.6  570.23  4416.3   567.2  4774.4  565.02  4783.9  564.06  4789.2  564.86
  4820.9  563.98  4837.6  565.42  4890.3  565.87  4947.8  564.77  4953.4  564.13
  4979.6  564.25    4982  561.79  4982.5  560.99  4987.5  560.99    4988  561.79
  4995.6  562.96    5006  563.09  5011.3  562.02  5024.5  564.12  5037.2   564.9
  5067.2  564.25  5167.2  566.61  5277.3  568.15  5517.3  568.09  5527.4  567.79
  5537.4  565.44  5547.4  567.18  5557.4  567.91  5667.4  569.11  5804.1  572.34
#Mann= 3 ,-1 , 0
  4164.6      .1       0    4982     .07       0    4988      .1       0
Bank Sta=4982,4988
XS Rating Curve= 0 ,0
Exp/Cntr=0.3,0.1

Type RM Length L Ch R = 1 ,3474    ,152,152,152
BEGIN DESCRIPTION:
Mapping XS e19de3b9
END DESCRIPTION:
XS GIS Cut Line= 4
      2009779.59     13539409.77      2009558.24     13539060.83
      2009162.41     13539029.58      2008908.58     13539252.33
#Sta/Elev= 30
  4318.5  566.34  4542.5  564.61  4608.4  563.62  4630.6   563.7  4651.8  563.15
  4724.7  563.49    4755  563.28  4775.1  563.66  4825.3  563.46  4845.3  562.96
  4855.3  562.06  4864.8  563.19  4915.5  563.08  4955.7  561.22  4965.7  562.24
  4975.7  562.59  4985.8  560.05  4990.6  558.09  4991.1  557.29  4996.1  557.29
  4996.6  558.09  5015.8  563.45  5128.8  564.47  5222.8  565.97  5279.7  566.27
  5286.3  566.65  5322.4  566.39  5378.4  567.21    5386   566.8  5466.5  567.66
#Mann= 3 ,-1 , 0
  4318.5      .1       0  4990.6     .07       0  4996.6      .1       0
Bank Sta=4990.6,4996.6
XS Rating Curve= 0 ,0
Exp/Cntr=0.3,0.1

Type RM Length L Ch R = 1 ,3322    ,586,586,586
BEGIN DESCRIPTION:
Mapping XS c6078c59
END DESCRIPTION:
XS GIS Cut Line= 4
      2009795.24     13539316.07      2009651.99      13538977.5
      2009125.95       13538915.      2008545.67     13539240.27
#Sta/Elev= 30
  4340.6  565.85  4735.4  562.18    4826  563.09  4858.9   562.2  4866.3  563.37
  4876.4  562.88  4906.6  563.16  4916.7  562.59  4941.6  562.98    4967  560.55
  4987.2  560.05  4994.2  559.19  4994.7  558.39  4999.7  558.39  5000.2  559.19
  5024.2  563.11  5029.3  562.52  5047.6  562.45  5194.6  563.65  5246.5  563.23
  5305.8  564.43  5333.3  563.23  5349.2  564.56  5354.9  563.76  5365.2  564.56
  5408.6  565.17  5430.2  564.78  5495.3  566.52  5525.7  566.06  5903.2  572.42
#Mann= 3 ,-1 , 0
  4340.6      .1       0  4994.2     .07       0  5000.2      .1       0
Bank Sta=4994.2,5000.2
XS Rating Curve= 0 ,0
Exp/Cntr=0.3,0.1

Type RM Length L Ch R = 1 ,2736    ,187,187,187
BEGIN DESCRIPTION:
Mapping XS 819d3a21
END DESCRIPTION:
XS GIS Cut Line= 4
      2009761.39     13539162.43      2009519.18     13538680.62
       2009219.7       13538665.      2008756.16     13539068.64
#Sta/Elev= 30
    4322  564.69  4564.9  561.95  4570.5  562.33  4615.1   561.5  4666.1  562.28
  4733.2  562.22  4915.5  561.07  4935.5  560.63  4945.6  559.04  4955.6  558.25
  4975.6  558.37  4992.6  555.85  4993.1  555.05  4998.1  555.05  4998.6  555.85
  5015.6   559.5  5025.7  561.09  5067.9  560.52  5125.8  561.31  5135.8  560.97
  5145.8  559.86    5161  561.46  5171.4  561.23  5193.2  561.87  5199.9   561.3
  5214.1  561.18  5228.4  561.78    5235  560.87  5256.8  562.12  5775.8  568.54
#Mann= 3 ,-1 , 0
    4322      .1       0  4992.6     .07       0  4998.6      .1       0
Bank Sta=4992.6,4998.6
XS Rating Curve= 0 ,0
Exp/Cntr=0.3,0.1

Type RM Length L Ch R = 1 ,2549    ,155,155,155
BEGIN DESCRIPTION:
Mapping XS 9dd0cc30
END DESCRIPTION:
XS GIS Cut Line= 4
      2009808.24     13539141.56      2009558.24     13538487.91
      2009180.64     13538508.75      2008826.49     13538956.65
#Sta/Elev= 30
  4109.6  564.64  4287.9  563.36    4297  562.83  4441.9  560.83  4651.9  561.38
  4666.3  560.93  4872.8  560.47  4922.8  559.29  4952.9  559.42  4972.9   560.4
  4989.9  555.98  4990.4  555.18  4995.4  555.18  4995.9  555.98    5013  559.85
    5053  560.12  5073.1  560.82  5083.1  559.41  5103.1  561.14  5143.2  559.87
  5381.3  563.91  5445.4  563.92  5495.1  564.77  5573.6  565.13  5594.4  565.78
  5629.7  565.68  5644.1  566.22  5693.8  566.56  5716.3  567.39  5758.6  567.61
#Mann= 3 ,-1 , 0
  4109.6      .1       0  4989.9     .07       0  4995.9      .1       0
Bank Sta=4989.9,4995.9
XS Rating Curve= 0 ,0
Exp/Cntr=0.3,0.1

Type RM Length L Ch R = 1 ,2394    ,133,133,133
BEGIN DESCRIPTION:
Mapping XS 89ac368d
END DESCRIPTION:
XS GIS Cut Line= 4
      2009839.48     13539115.49       2009532.2     13538360.31
      2009292.62      13538355.1      2008865.65     13538860.17
#Sta/Elev= 30
    4070  564.51    4198  563.67  4417.5  560.52  4448.4   561.2  4572.7   560.4
  4610.3  561.01  4816.2  560.55  4912.5  559.97  4932.5   559.5 4941.95558.4888
  4989.5  555.55    4990  554.75    4995  554.75  4995.5  555.55  5022.5  557.93
  5052.5  557.57  5102.6  559.65  5179.6  560.33  5208.2  559.54  5236.8  560.23
  5251.1  559.87  5265.4  558.22 5269.12 558.489  5293.9   559.3  5314.8  561.05
  5335.6  561.49  5343.4  561.03  5464.2  563.41  5726.9  565.83  5786.3  567.03
#Mann= 3 ,-1 , 0
    4070      .1       0  4989.5     .07       0  4995.5      .1       0
Bank Sta=4941.95,5269.12
XS Rating Curve= 0 ,0
Exp/Cntr=0.3,0.1

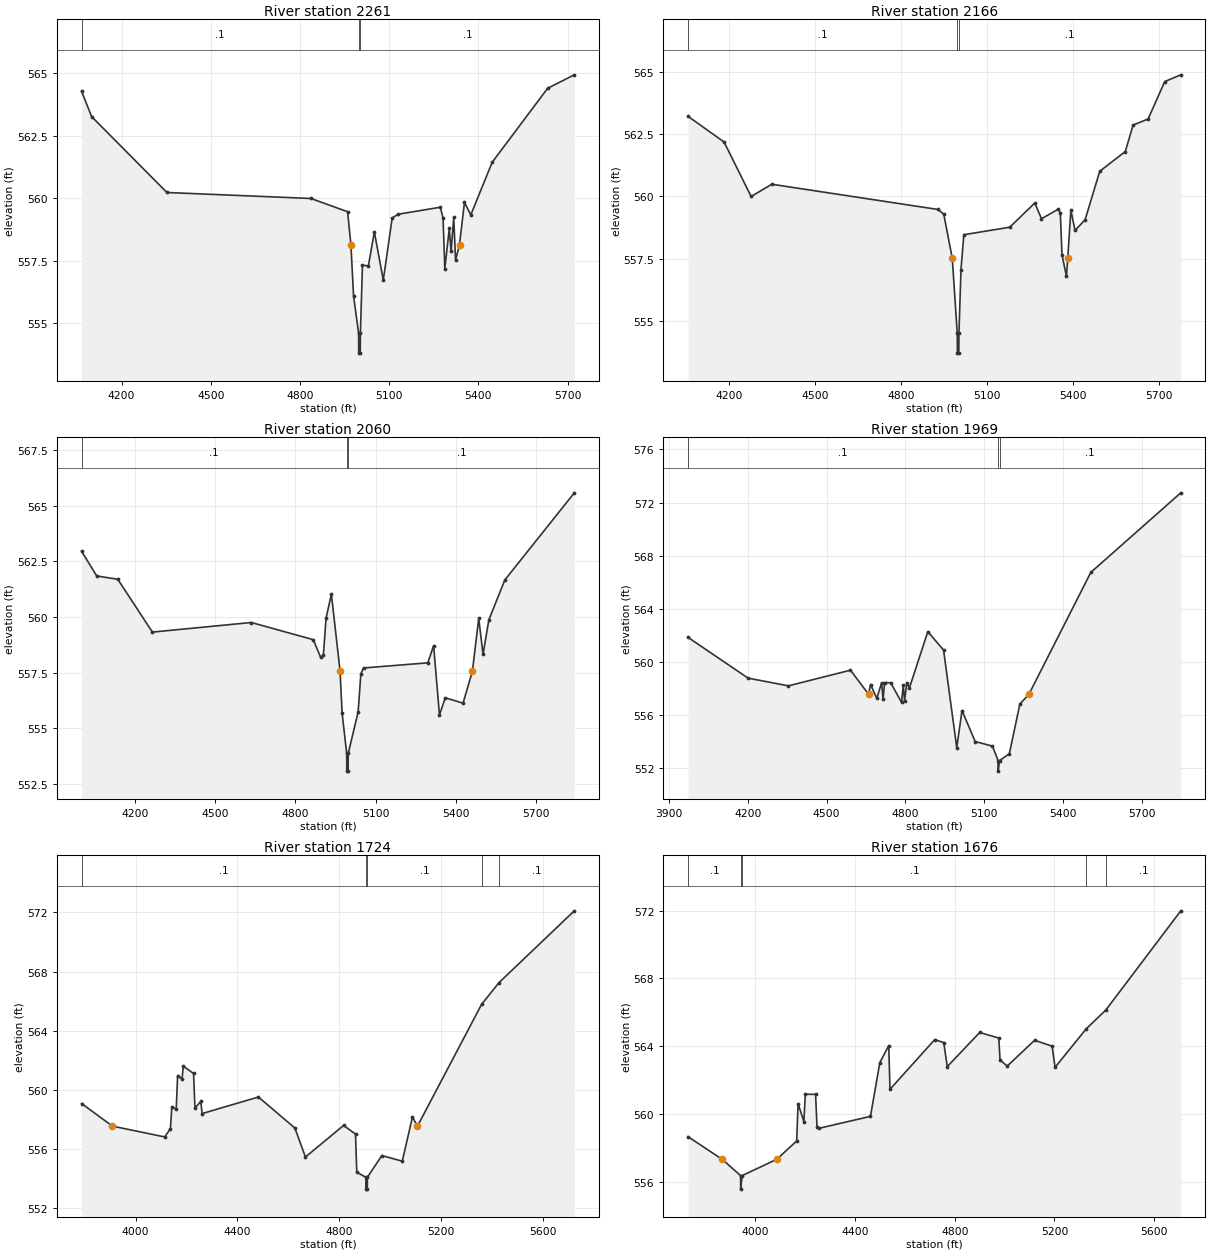
Type RM Length L Ch R = 1 ,2261    ,95,95,95
BEGIN DESCRIPTION:
Mapping XS 8dbf42af
END DESCRIPTION:
XS GIS Cut Line= 4
      2009829.07     13539026.94      2009568.66     13538258.75
      2009271.79     13538253.54      2008967.72     13538710.94
#Sta/Elev= 30
  4065.6  564.29  4099.3  563.27  4352.7  560.23  4837.3  559.99  4960.4  559.46
 4971.51558.1436  4980.4  556.09  4997.4   554.6  4997.9   553.8  5002.9   553.8
  5003.4   554.6  5010.4  557.31  5030.4   557.3  5050.4  558.65  5080.4  556.72
  5110.4  559.21  5130.4  559.36  5272.3  559.64  5281.4  559.21  5287.4  557.18
  5302.4  558.79  5308.4  557.87  5317.4  559.23  5323.4  557.52 5336.77558.1451
  5353.5  559.84  5374.6  559.33  5446.7  561.44  5633.1   564.4  5722.9  564.94
#Mann= 3 ,-1 , 0
  4065.6      .1       0  4997.4     .07       0  5003.4      .1       0
Bank Sta=4971.51,5336.77
XS Rating Curve= 0 ,0
Exp/Cntr=0.3,0.1

Type RM Length L Ch R = 1 ,2166    ,106,106,106
BEGIN DESCRIPTION:
Mapping XS ce24c040
END DESCRIPTION:
XS GIS Cut Line= 4
      2009839.49     13538961.84      2009571.27      13538170.2
       2009279.6       13538165.      2008972.35     13538670.14
#Sta/Elev= 30
    4056  563.21  4181.8  562.18  4276.1     560  4348.3  560.49  4928.1  559.48
  4948.1  559.29 4977.76557.5252  4995.1  554.53  4995.6  553.73  5000.6  553.73
  5001.1  554.53  5008.1  557.07  5018.1  558.47  5178.2  558.77  5265.6  559.74
  5288.9  559.11  5347.4  559.49  5354.6  559.35  5360.5  557.66    5376  556.81
 5380.51557.5247  5391.4  559.45  5405.9  558.64  5441.1  559.07  5492.2  561.01
  5581.3   561.8  5608.5  562.86  5660.7   563.1  5718.9   564.6  5774.8  564.87
#Mann= 3 ,-1 , 0
    4056      .1       0  4995.1     .07       0  5001.1      .1       0
Bank Sta=4977.76,5380.51
XS Rating Curve= 0 ,0
Exp/Cntr=0.3,0.1

Type RM Length L Ch R = 1 ,2060    ,91,91,91
BEGIN DESCRIPTION:
Mapping XS 914aa04f
END DESCRIPTION:
XS GIS Cut Line= 4
      2009881.16     13538891.55      2009560.85     13538073.85
      2009250.95     13538076.45      2008935.83     13538649.41
#Sta/Elev= 30
    4001  562.95  4057.7  561.84  4136.4  561.69  4265.8  559.32  4635.5  559.75
  4867.2  558.98    4895  558.18    4905  558.28    4915  559.95    4935  561.02
 4967.33557.5692    4975  555.69    4992  553.88  4992.5  553.08  4997.5  553.08
    4998  553.88    5035  555.74    5045  557.44    5055  557.71  5295.3  557.94
  5317.1  558.71  5338.9   555.6  5360.7  556.37  5427.1  556.13 5462.09557.5688
  5485.7  559.94  5501.8  558.32  5523.6  559.87  5583.3  561.66    5843  565.57
#Mann= 3 ,-1 , 0
    4001      .1       0    4992     .07       0    4998      .1       0
Bank Sta=4967.33,5462.09
XS Rating Curve= 0 ,0
Exp/Cntr=0.3,0.1

Type RM Length L Ch R = 1 ,1969    ,245,245,245
BEGIN DESCRIPTION:
Mapping XS 9cf93846
END DESCRIPTION:
XS GIS Cut Line= 4
      2009935.85     13538756.14      2009633.77     13538032.18
      2009097.96     13538000.53      2008542.42     13538017.89
#Sta/Elev= 30
  3972.4  561.85  4201.2  558.78  4354.7   558.2  4591.3  559.38 4660.28557.5629
  4667.6   558.3  4691.5  557.26  4709.9  558.43  4715.3  557.19  4721.3  558.45
  4744.5  558.43  4785.7  556.96  4792.3  558.26  4797.3  557.07  4805.7  558.43
  4815.7  558.04  4885.8  562.28  4945.9  560.89    4996  553.55  5016.1  556.34
  5066.2  554.01  5132.2  553.66  5153.3  552.58  5153.8  551.78  5159.3  552.58
  5196.4  553.09  5236.5  556.83 5270.95557.5637  5506.7  566.74  5849.4  572.73
#Mann= 3 ,-1 , 0
  3972.4      .1       0  5153.3     .07       0  5159.3      .1       0
Bank Sta=4660.28,5270.95
XS Rating Curve= 0 ,0
Exp/Cntr=0.3,0.1

Type RM Length L Ch R = 1 ,1724    ,48,48,48
BEGIN DESCRIPTION:
Mapping XS 3e7dfe46
END DESCRIPTION:
XS GIS Cut Line= 3
      2010061.51     13538482.32      2009757.68     13537844.28
      2008529.66     13537896.35
#Sta/Elev= 30
  3787.4  559.08 3908.77557.5492  4113.9  556.82  4136.6  557.38  4142.1  558.85
  4159.3  558.69  4164.8  560.97    4182  560.74  4187.5   561.6  4227.4  561.11
  4232.9  558.77  4255.6  559.22  4261.2   558.4  4482.2  559.52  4625.5  557.42
  4666.9  555.46  4817.1   557.6  4863.6  557.01  4868.6  554.44    4904  554.09
  4904.5  553.29  4909.8  553.29  4910.3  554.09  4967.2  555.56  5047.3  555.18
  5087.3  558.17 5106.97557.5494  5359.1  565.79  5427.7  567.26  5723.2  572.11
#Mann= 5 ,-1 , 0
  3787.4      .1       0    4904     .07       0  4910.3      .1       0
  5359.1     .16       0  5427.7      .1       0
Bank Sta=3908.77,5106.97
XS Rating Curve= 0 ,0
Exp/Cntr=0.3,0.1

Type RM Length L Ch R = 1 ,1676    ,56,56,56
BEGIN DESCRIPTION:
Mapping XS 3e7da67a
END DESCRIPTION:
XS GIS Cut Line= 3
      2010065.84     13538464.94      2009775.04     13537796.54
      2008529.74     13537852.95
#Sta/Elev= 30
  3730.9  558.65 3867.89 557.312  3941.6  556.35  3942.1  555.55  3947.9  556.35
 4086.86557.3118  4166.6   558.4  4172.1   560.6  4195.5  559.54    4201  561.16
  4242.4  561.15  4247.9  559.25  4254.3  559.14  4462.3  559.85  4499.9  563.03
  4535.6  564.03  4540.6  561.45  4720.1  564.39  4756.2  564.21  4770.2  562.79
  4900.3  564.81  4976.8  564.48  4981.8  563.19  5010.4  562.82  5120.5  564.35
  5190.6     564  5202.4  562.75  5328.2  565.04  5405.7  566.13  5706.4     572
#Mann= 5 ,-1 , 0
  3730.9      .1       0  3941.6     .07       0  3947.9      .1       0
  5328.2     .16       0  5405.7      .1       0
Bank Sta=3867.89,4086.86
XS Rating Curve= 0 ,0
Exp/Cntr=0.3,0.1

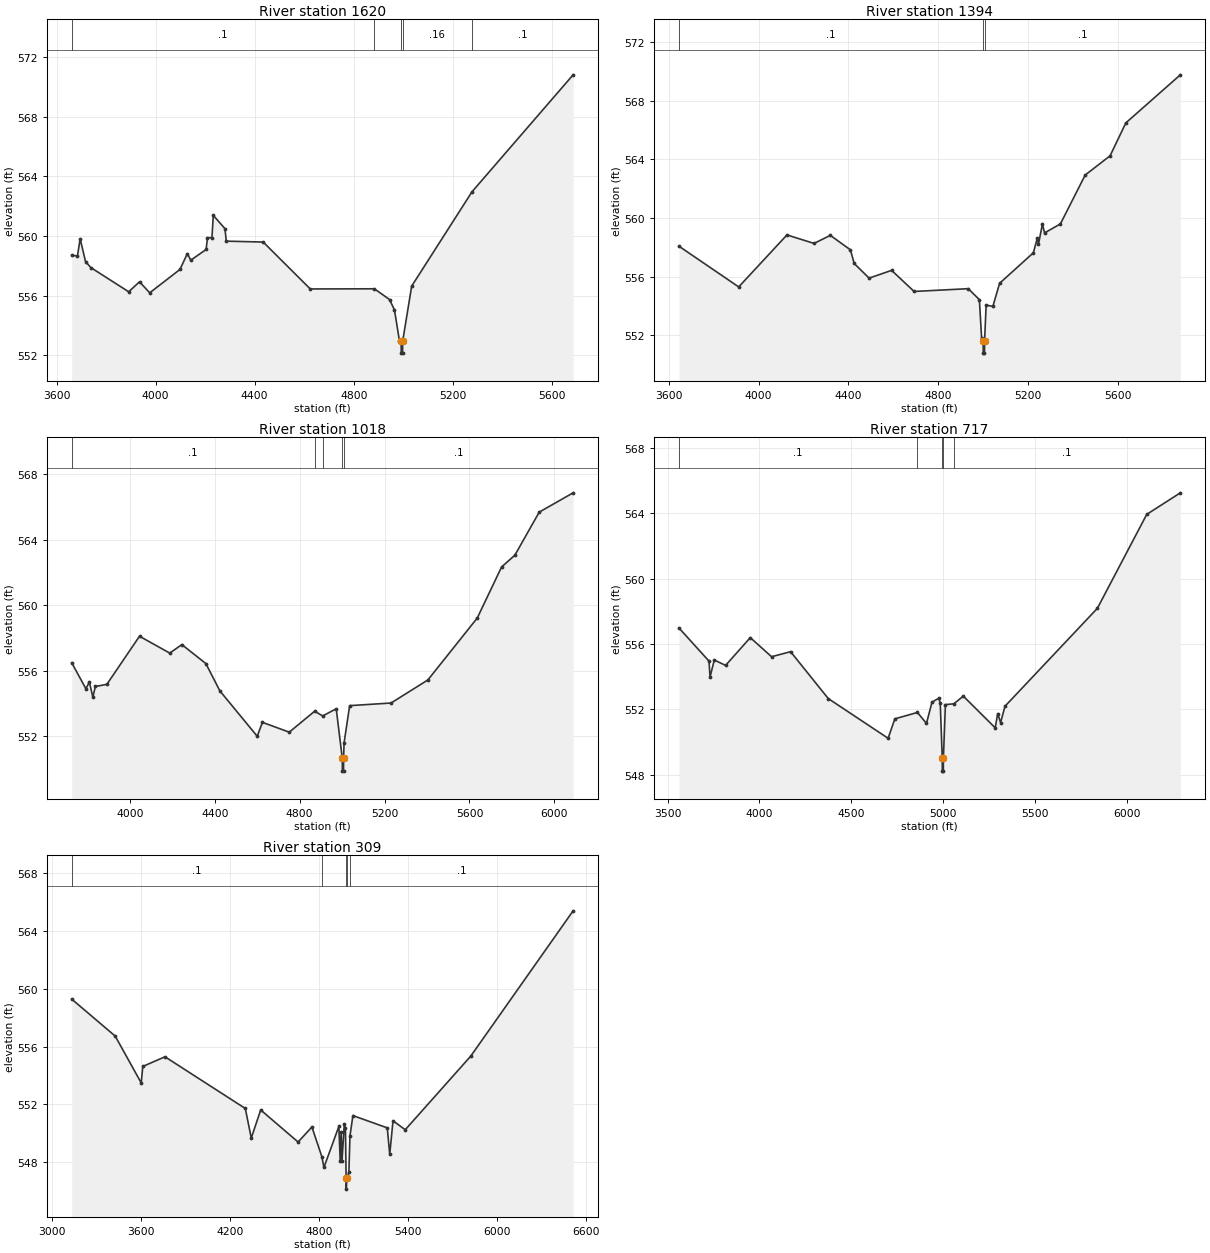
Type RM Length L Ch R = 1 ,1620    ,226,226,226
BEGIN DESCRIPTION:
Mapping XS d77bf6d3
END DESCRIPTION:
XS GIS Cut Line= 3
      2010096.21     13538456.24       2009792.4     13537753.14
      2008533.72     13537787.86
#Sta/Elev= 30
  3661.1  558.69  3684.2  558.66  3695.1  559.81  3716.9  558.27  3738.7  557.87
  3891.2  556.25  3934.8  556.92  3976.1  556.18  4098.2  557.75    4128  558.81
  4141.8  558.37  4203.9  559.09  4209.4  559.88  4227.4  559.88  4232.9  561.38
  4279.9  560.49  4285.3  559.65  4434.4  559.59  4624.5  556.44  4883.6  556.45
  4944.6  555.73  4964.6  555.03  4984.7  552.96  4991.5  552.93    4992  552.13
  4997.3  552.13  4997.8  552.93  5034.1  556.63    5278  562.97  5686.2  570.82
#Mann= 5 ,-1 , 0
  3661.1      .1       0  4883.6     .16       0  4991.5     .07       0
  4997.8     .16       0    5278      .1       0
Bank Sta=4991.5,4997.8
XS Rating Curve= 0 ,0
Exp/Cntr=0.3,0.1

Type RM Length L Ch R = 1 ,1394    ,376,376,376
BEGIN DESCRIPTION:
Mapping XS 59dca4ad
END DESCRIPTION:
XS GIS Cut Line= 4
      2010200.41     13538365.15      2009827.12     13537618.59
      2008941.71     13537562.17      2008433.93     13537618.59
#Sta/Elev= 30
  3645.5  558.07  3911.6  555.29  4126.4  558.84    4247  558.26  4319.7  558.81
  4409.1  557.82  4425.9  556.89  4492.3  555.89  4592.5  556.42  4692.7  554.98
    4934  555.17  4983.3  554.42  4993.3  551.79  5000.2  551.57  5000.7  550.77
    5006  550.77  5006.5  551.57  5013.4  554.05  5043.4  553.96  5073.5  555.54
  5223.8  557.62  5241.5  558.63  5246.5   558.2  5263.9  559.57  5273.9  558.98
  5344.1  559.59  5454.6  562.93  5565.3  564.24  5635.7  566.49  5878.3  569.77
#Mann= 3 ,-1 , 0
  3645.5      .1       0  5000.2     .07       0  5006.5      .1       0
Bank Sta=5000.2,5006.5
XS Rating Curve= 0 ,0
Exp/Cntr=0.3,0.1

Type RM Length L Ch R = 1 ,1018    ,301,301,301
BEGIN DESCRIPTION:
Mapping XS 0c831752
END DESCRIPTION:
XS GIS Cut Line= 4
      2010209.09     13538213.24      2009796.74      13537436.3
      2009158.72     13537223.62      2008381.78     13537453.67
#Sta/Elev= 30
  3726.1   556.5  3792.9  554.91  3809.2  555.33  3825.6  554.39  3837.3  555.05
  3891.5  555.18  4045.4  558.12    4188  557.09  4244.9  557.61  4358.1  556.45
  4424.2  554.78  4600.1  552.01  4624.5  552.86    4751  552.26  4870.7  553.54
  4908.6  553.25  4972.3  553.69  5000.8  550.68  5001.3  549.88  5006.6  549.88
  5007.1  550.68  5009.2   551.6  5035.6  553.88  5230.6  554.04  5404.2  555.45
  5636.7  559.23  5751.4  562.35    5814  563.07  5928.7   565.7  6088.5  566.88
#Mann= 5 ,-1 , 0
  3726.1      .1       0  4870.7     .12       0  4908.6      .1       0
  5000.8     .07       0  5007.1      .1       0
Bank Sta=5000.8,5007.1
XS Rating Curve= 0 ,0
Exp/Cntr=0.3,0.1

Type RM Length L Ch R = 1 ,717     ,408,408,408
BEGIN DESCRIPTION:
Mapping XS 3d1c99ab
END DESCRIPTION:
XS GIS Cut Line= 4
       2010278.5     13538256.59      2009809.76     13537214.94
      2009332.33     13536980.57      2008355.77     13537384.21
#Sta/Elev= 30
  3561.7  556.98  3725.5  554.95    3731  553.98  3754.2  555.02  3815.7  554.69
  3950.3  556.39  4066.1  555.22  4169.7  555.53  4374.9  552.66  4700.9  550.23
  4737.5  551.42  4860.4  551.81  4909.8  551.14  4939.9  552.44  4976.6  552.68
  4984.8  552.39  4995.7  549.02  4996.2  548.22  5001.5  548.22    5002  549.02
  5012.9  552.29    5059  552.34  5110.3  552.81  5284.1  550.87  5297.8  551.74
  5313.5  551.19  5337.4  552.19  5840.4  558.18  6109.4  563.93  6292.5  565.25
#Mann= 5 ,-1 , 0
  3561.7      .1       0  4860.4     .12       0  4995.7     .07       0
    5002     .12       0    5059      .1       0
Bank Sta=4995.7,5002
XS Rating Curve= 0 ,0
Exp/Cntr=0.3,0.1

Type RM Length L Ch R = 1 ,309     ,0,0,0
BEGIN DESCRIPTION:
UNT 014 in HW 1.0
END DESCRIPTION:
XS GIS Cut Line= 4
      2010387.04     13538497.11      2009845.35     13536955.39
      2009470.35     13536726.23      2008311.02     13537330.19
#Sta/Elev= 30
  3132.9  559.29  3426.1  556.73  3601.4  553.49  3612.1  554.63  3761.6   555.3
  4303.4  551.72  4343.4  549.67    4407  551.62  4659.3   549.4  4752.3  550.44
  4819.9  548.37  4833.4  547.64  4934.1  550.48  4943.2  548.09  4949.5  550.08
  4955.4  548.12  4970.8  550.62  4978.4  550.35  4983.1  546.94  4983.6  546.14
  4989.4  546.94  5001.7   547.3  5008.9  549.82  5028.9  551.23  5260.6  550.38
  5277.1  548.54  5299.2  550.87  5381.7  550.25  5823.9  555.35  6513.7   565.4
#Mann= 5 ,-1 , 0
  3132.9      .1       0  4819.9     .12       0  4983.1     .07       0
  4989.4     .12       0  5008.9      .1       0
Bank Sta=4983.1,4989.4
XS Rating Curve= 0 ,0
Exp/Cntr=0.3,0.1
LCMann Table=0

Chan Stop Cuts=-1
Use User Specified Reach Order=0
Composite Channel Slope=5