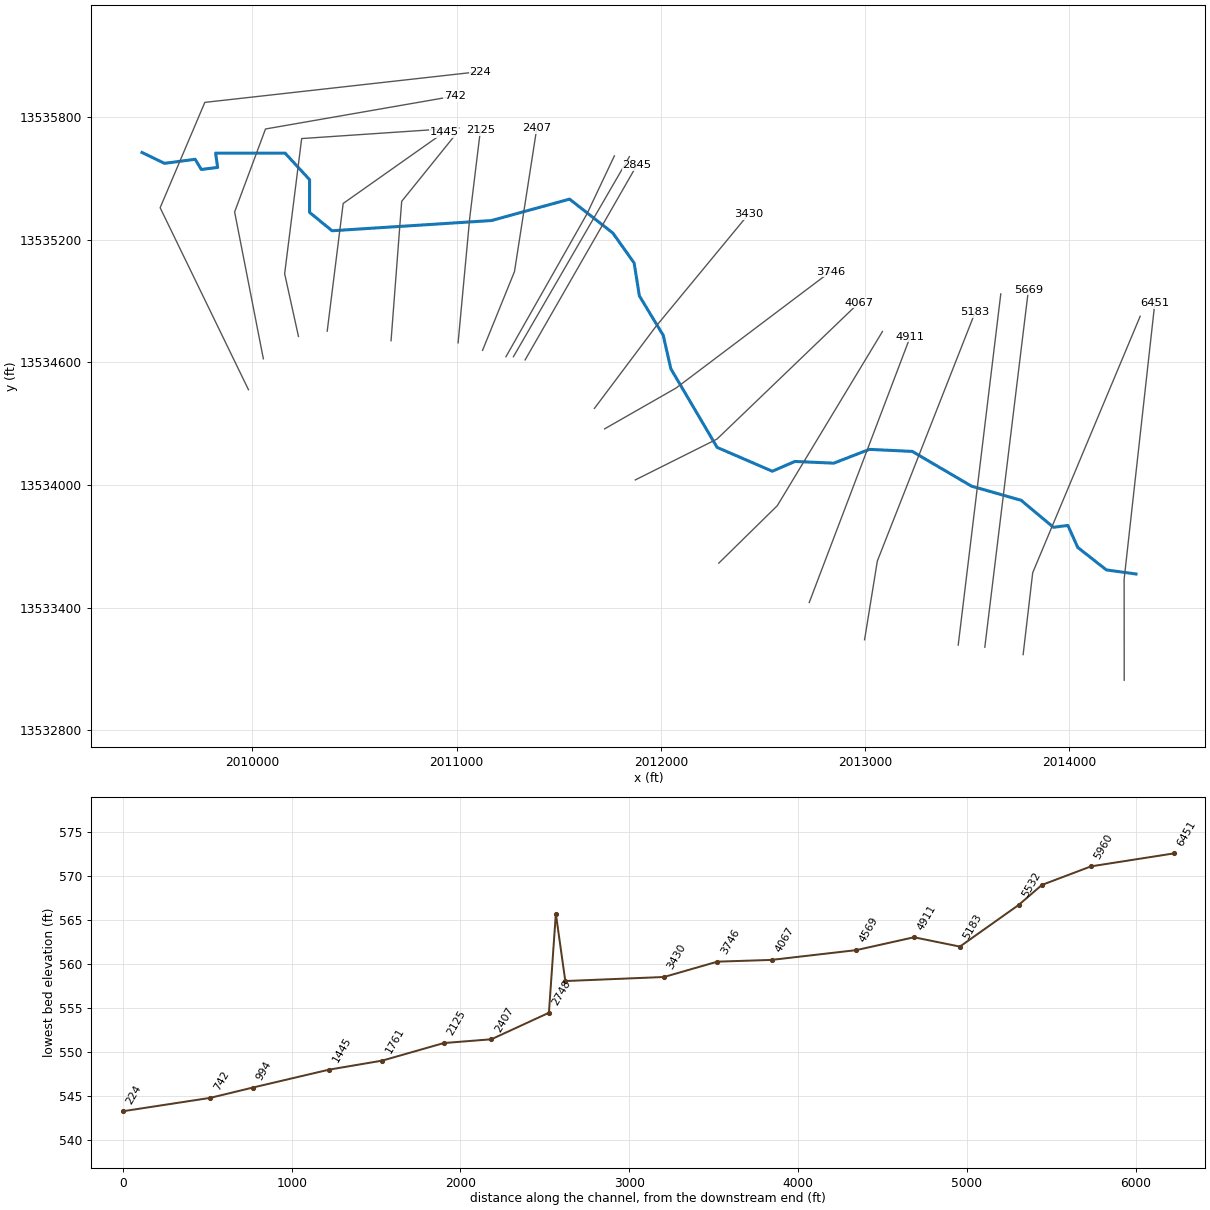
--- UNT 015 in HW.prj (project) ---

Proj Title=UNT 015 in HW Base Level Engineering
Current Plan=p01
Default Exp/Contr=0.3,0.1
English Units
Geom File=g01
Flow File=f01
Plan File=p01
BEGIN DESCRIPTION:
UNT 015 in HW
END DESCRIPTION:

--- UNT 015 in HW.p01 (plan) ---

Plan Title=Multiple Run
Short Identifier=Multiple
Geom File=g01
Flow File=f01
Subcritical Flow
K Sum by GR= 0
Std Step Tol= 0.01
Critical Tol= 0.01
Num of Std Step Trials= 20
Max Error Tol= 0.3
Flow Tol Ratio= 0.001
Split Flow NTrial= 30
Split Flow Tol= 0.02
Split Flow Ratio= 0.02
Log Output Level= 0
Friction Slope Method= 1
Unsteady Friction Slope Method= 2
Unsteady Bridges Friction Slope Method= 1
Parabolic Critical Depth
Global Vel Dist=  1 , 1 , 1
Global Log Level= 0
CheckData=True
Encroach Param= -1, 0, 0, 0
BEGIN DESCRIPTION:
Multiple Run
END DESCRIPTION:

--- UNT 015 in HW.f01 (steady flow) ---

Flow Title=Multiple
Number of Profiles=7
Profile Names=10-year,25-year,50-year,1pct_min,100-year,1pct_plu,500-year
River Rch & RM= UNT 015 in HW,Reach-1,6451
     165     222     267     161     320     639     468
River Rch & RM= UNT 015 in HW,Reach-1,5960
     226     308     375     228     455     908     678
Boundary for River Rch & Prof#=UNT 015 in HW,Reach-1,1
Up Type=0
Dn Type=3
Dn Slope=0.005
Boundary for River Rch & Prof#=UNT 015 in HW,Reach-1,2
Up Type=0
Dn Type=3
Dn Slope=0.005
Boundary for River Rch & Prof#=UNT 015 in HW,Reach-1,3
Up Type=0
Dn Type=3
Dn Slope=0.005
Boundary for River Rch & Prof#=UNT 015 in HW,Reach-1,4
Up Type=0
Dn Type=3
Dn Slope=0.005
Boundary for River Rch & Prof#=UNT 015 in HW,Reach-1,5
Up Type=0
Dn Type=3
Dn Slope=0.005
Boundary for River Rch & Prof#=UNT 015 in HW,Reach-1,6
Up Type=0
Dn Type=3
Dn Slope=0.005
Boundary for River Rch & Prof#=UNT 015 in HW,Reach-1,7
Up Type=0
Dn Type=3
Dn Slope=0.005

--- UNT 015 in HW.g01 (geometry) ---

Geom Title=Existing Conditions

River Reach=UNT 015 in HW,Reach-1
Reach XY= 30
      2014325.80     13533564.54      2014180.80     13533584.54
      2014040.80     13533694.54      2013992.25     13533802.21
      2013921.42     13533793.18      2013763.78     13533925.13
      2013520.80     13533994.54      2013230.80     13534164.54
      2013020.80     13534174.54      2012846.42     13534107.07
      2012656.14     13534115.41      2012545.72     13534067.49
      2012275.58     13534184.16      2012049.19     13534568.88
      2012011.69     13534732.77      2011895.03     13534925.82
      2011869.33     13535086.93      2011765.17     13535233.46
      2011553.36     13535399.43      2011170.80     13535294.54
      2010390.80     13535244.54      2010280.80     13535334.54
      2010280.80     13535494.54      2010160.80     13535624.54
      2009820.80     13535624.54      2009830.80     13535554.54
      2009750.80     13535544.54      2009720.80     13535594.54
      2009570.80     13535574.54      2009460.80     13535627.52

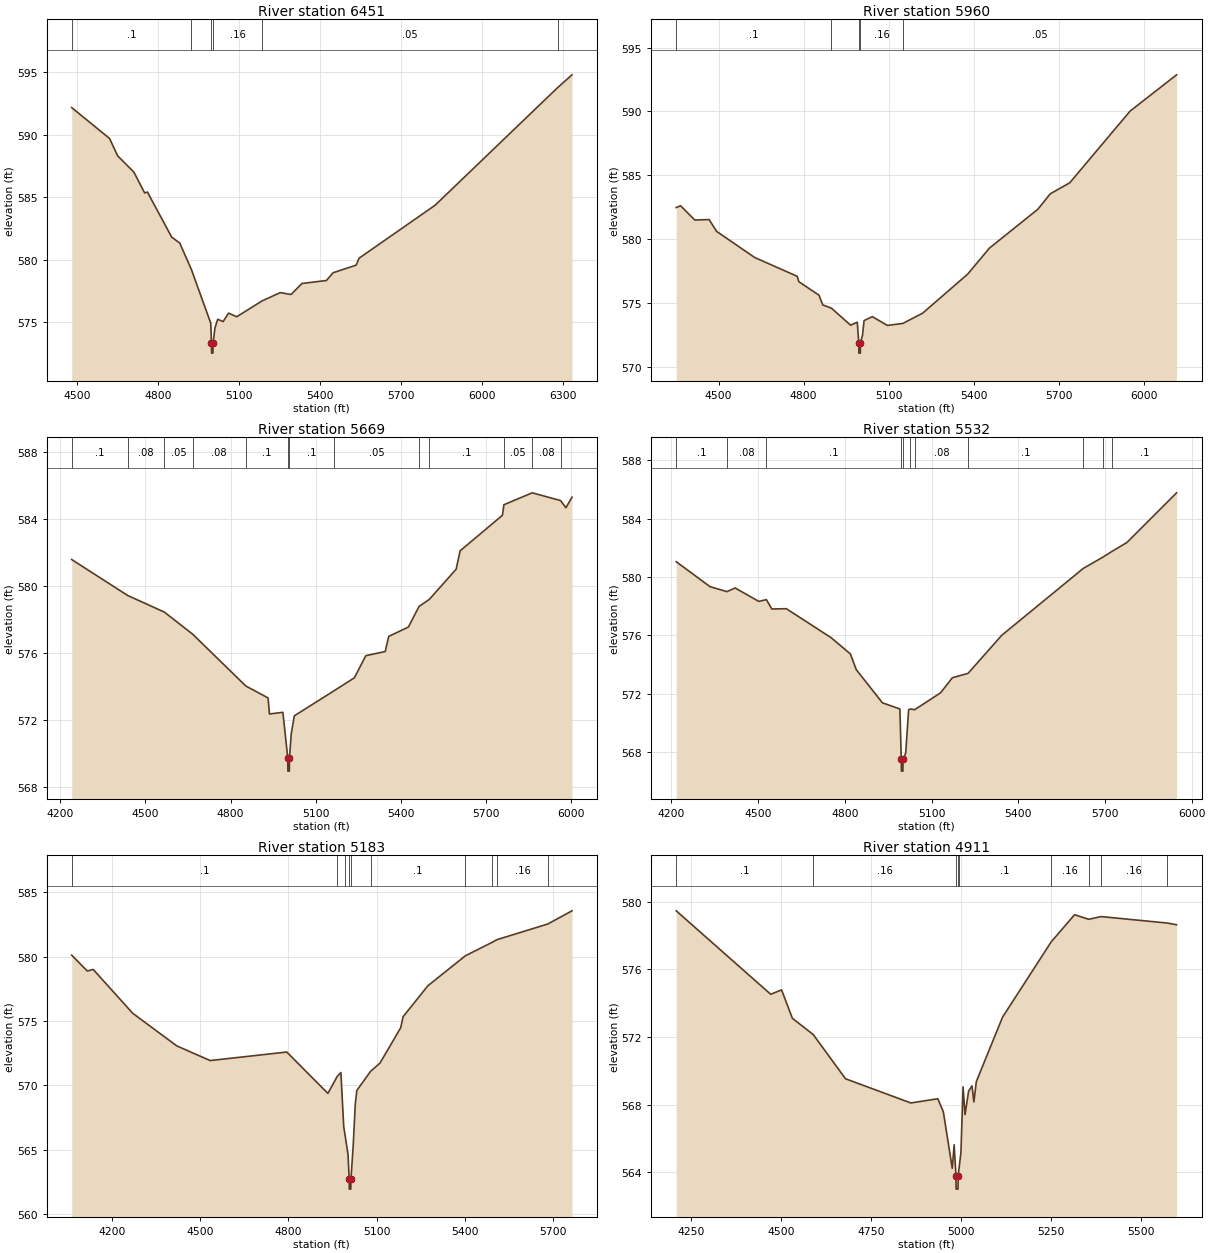
Type RM Length L Ch R = 1,6451,491,491,491
BEGIN DESCRIPTION:
UNT 015 in HW 13.0
END DESCRIPTION:
XS GIS Cut Line= 3
      2014268.10     13533044.78      2014267.71     13533538.54
      2014417.71     13534888.57
#Sta/Elev= 30
  4479.9  592.17  4620.1  589.70  4650.1  588.31  4710.1  587.01  4750.1  585.34
  4760.1  585.42  4850.1  581.81  4880.1  581.33  4923.4  579.20  4994.8  574.92
  4997.3  573.33  4997.8  572.53  5002.8  572.53  5003.3  573.33  5010.3  574.54
  5020.4  575.24  5040.5  575.05  5060.7  575.73  5090.8  575.44  5185.1  576.71
  5251.8  577.37  5292.1  577.22  5332.3  578.10  5422.9  578.34  5447.6  578.96
  5533.1  579.57  5543.6  580.12  5825.3  584.36  6279.9  593.79  6332.0  594.79
#Mann=6,-1,0
  4479.9     0.1       0  4923.4    0.16       0  4997.3    0.07       0
  5003.3    0.16       0  5185.1    0.05       0  6279.9     0.1       0
Bank Sta=4997.3,5003.3
Exp/Cntr=0.3,0.1

Type RM Length L Ch R = 1,5960,291,291,291
BEGIN DESCRIPTION:
Mapping XS 964966b4
END DESCRIPTION:
XS GIS Cut Line= 3
      2013773.31     13533169.83      2013820.18     13533570.85
      2014346.21     13534826.03
#Sta/Elev= 30
  4350.7  582.47  4366.0  582.61  4416.3  581.49  4466.6  581.53  4493.2  580.60
  4627.7  578.55  4777.5  577.08  4783.0  576.66  4854.3  575.60  4867.4  574.84
  4898.3  574.58  4965.7  573.25  4989.4  573.48  4994.5  571.86  4995.0  571.06
  5000.0  571.06  5000.5  571.86  5007.8  572.47  5013.2  573.61  5042.4  573.92
  5095.4  573.23  5150.2  573.39  5219.7  574.19  5378.7  577.25  5455.4  579.29
  5626.4  582.34  5669.7  583.54  5738.7  584.41  5951.6  590.03  6115.4  592.87
#Mann=5,-1,0
  4350.7     0.1       0  4898.3    0.16       0  4994.5    0.07       0
  5000.5    0.16       0  5150.2    0.05       0
Bank Sta=4994.5,5000.5
Exp/Cntr=0.3,0.1

Type RM Length L Ch R = 1,5669,137,137,137
BEGIN DESCRIPTION:
Mapping XS a3a201b7
END DESCRIPTION:
XS GIS Cut Line= 2
      2013585.80     13533206.23      2013799.34     13534956.25
#Sta/Elev= 30
  4240.3  581.58  4438.0  579.43  4567.1  578.44  4666.8  577.12  4854.0  574.03
  4932.3  573.32  4937.3  572.36  4984.5  572.46  5001.6  569.75  5002.1  568.95
  5007.2  568.95  5007.7  569.75  5013.9  571.17  5024.8  572.25  5165.2  573.75
  5236.4  574.52  5276.7  575.84  5345.2  576.09  5357.3  576.99  5426.8  577.55
  5464.3  578.78  5500.5  579.20  5595.0  581.00  5609.1  582.10  5758.1  584.22
  5763.4  584.85  5863.1  585.56  5962.8  585.10  5981.9  584.67  6003.3  585.30
#Mann=13,-1,0
  4240.3     0.1       0  4438.0    0.08       0  4567.1    0.05       0
  4666.8    0.08       0  4854.0     0.1       0  5001.6    0.07       0
  5007.7     0.1       0  5165.2    0.05       0  5464.3    0.08       0
  5500.5     0.1       0  5763.4    0.05       0  5863.1    0.08       0
  5962.8     0.1       0
Bank Sta=5001.6,5007.7
Exp/Cntr=0.3,0.1

Type RM Length L Ch R = 1,5532,349,349,349
BEGIN DESCRIPTION:
Mapping XS bc02f96d
END DESCRIPTION:
XS GIS Cut Line= 2
      2013455.59     13533216.63      2013663.93     13534935.45
#Sta/Elev= 30
  4216.4  581.04  4333.4  579.33  4391.9  578.99  4420.3  579.24  4502.1  578.32
  4528.5  578.44  4547.2  577.80  4597.5  577.82  4752.7  575.83  4819.1  574.72
  4839.6  573.64  4930.0  571.37  4990.4  570.95  4995.2  567.49  4995.7  566.69
  5000.8  566.69  5001.3  567.49  5010.5  567.93  5020.6  570.89  5026.9  570.95
  5041.7  570.90  5131.4  572.06  5172.0  573.09  5226.3  573.39  5343.0  576.00
  5625.0  580.58  5691.6  581.34  5724.7  581.75  5776.1  582.36  5947.8  585.76
#Mann=11,-1,0
  4216.4     0.1       0  4391.9    0.08       0  4528.5     0.1       0
  4995.2    0.07       0  5001.3     0.1       0  5026.9    0.12       0
  5041.7    0.08       0  5226.3     0.1       0  5625.0    0.16       0
  5691.6    0.08       0  5724.7     0.1       0
Bank Sta=4995.2,5001.3
Exp/Cntr=0.3,0.1

Type RM Length L Ch R = 1,5183,272,272,272
BEGIN DESCRIPTION:
Mapping XS 811844c9
END DESCRIPTION:
XS GIS Cut Line= 3
      2012997.26     13533242.70      2013059.76     13533628.14
      2013538.92     13534846.86
#Sta/Elev= 30
  4063.9  580.11  4116.9  578.88  4137.1  579.00  4271.2  575.60  4420.8  573.07
  4534.3  571.93  4794.8  572.59  4934.5  569.38  4966.0  570.69  4978.6  571.00
  4988.3  566.79  4993.3  566.07  5003.0  564.62  5006.7  562.75  5007.2  561.95
  5012.3  561.95  5012.8  562.75  5020.5  565.36  5027.4  568.53  5032.8  569.61
  5079.7  571.10  5111.4  571.73  5181.7  574.47  5190.0  575.33  5274.0  577.73
  5401.5  580.06  5491.3  581.09  5508.7  581.31  5681.8  582.53  5763.9  583.55
#Mann=10,-1,0
  4063.9     0.1       0  4966.0    0.16       0  4993.3    0.07       0
  5006.7    0.07       0  5012.8    0.07       0  5079.7     0.1       0
  5401.5    0.16       0  5491.3     0.1       0  5508.7    0.16       0
  5681.8     0.1       0
Bank Sta=5006.7,5012.8
Exp/Cntr=0.3,0.1

Type RM Length L Ch R = 1,4911,342,342,342
BEGIN DESCRIPTION:
Mapping XS cd5def12
END DESCRIPTION:
XS GIS Cut Line= 2
      2012726.44     13533425.03      2013220.61     13534725.50
#Sta/Elev= 30
  4208.9  579.45  4471.6  574.52  4501.8  574.78  4531.9  573.10  4589.9  572.14
  4679.6  569.53  4861.2  568.10  4936.3  568.35  4951.6  567.58  4976.4  564.24
  4981.7  565.63  4986.7  563.81  4987.2  563.01  4992.4  563.01  4992.9  563.81
  4995.2  564.22  5000.5  565.17  5006.5  569.05  5011.9  567.41  5021.9  568.80
  5031.3  569.11  5036.6  568.16  5043.3  569.36  5116.3  573.17  5251.3  577.61
  5316.5  579.22  5355.9  578.95  5390.4  579.11  5573.4  578.73  5600.1  578.63
#Mann=9,-1,0
  4208.9     0.1       0  4589.9    0.16       0  4986.7    0.07       0
  4992.9    0.16       0  4995.2     0.1       0  5251.3    0.16       0
  5355.9     0.1       0  5390.4    0.16       0  5573.4     0.1       0
Bank Sta=4986.7,4992.9
Exp/Cntr=0.3,0.1

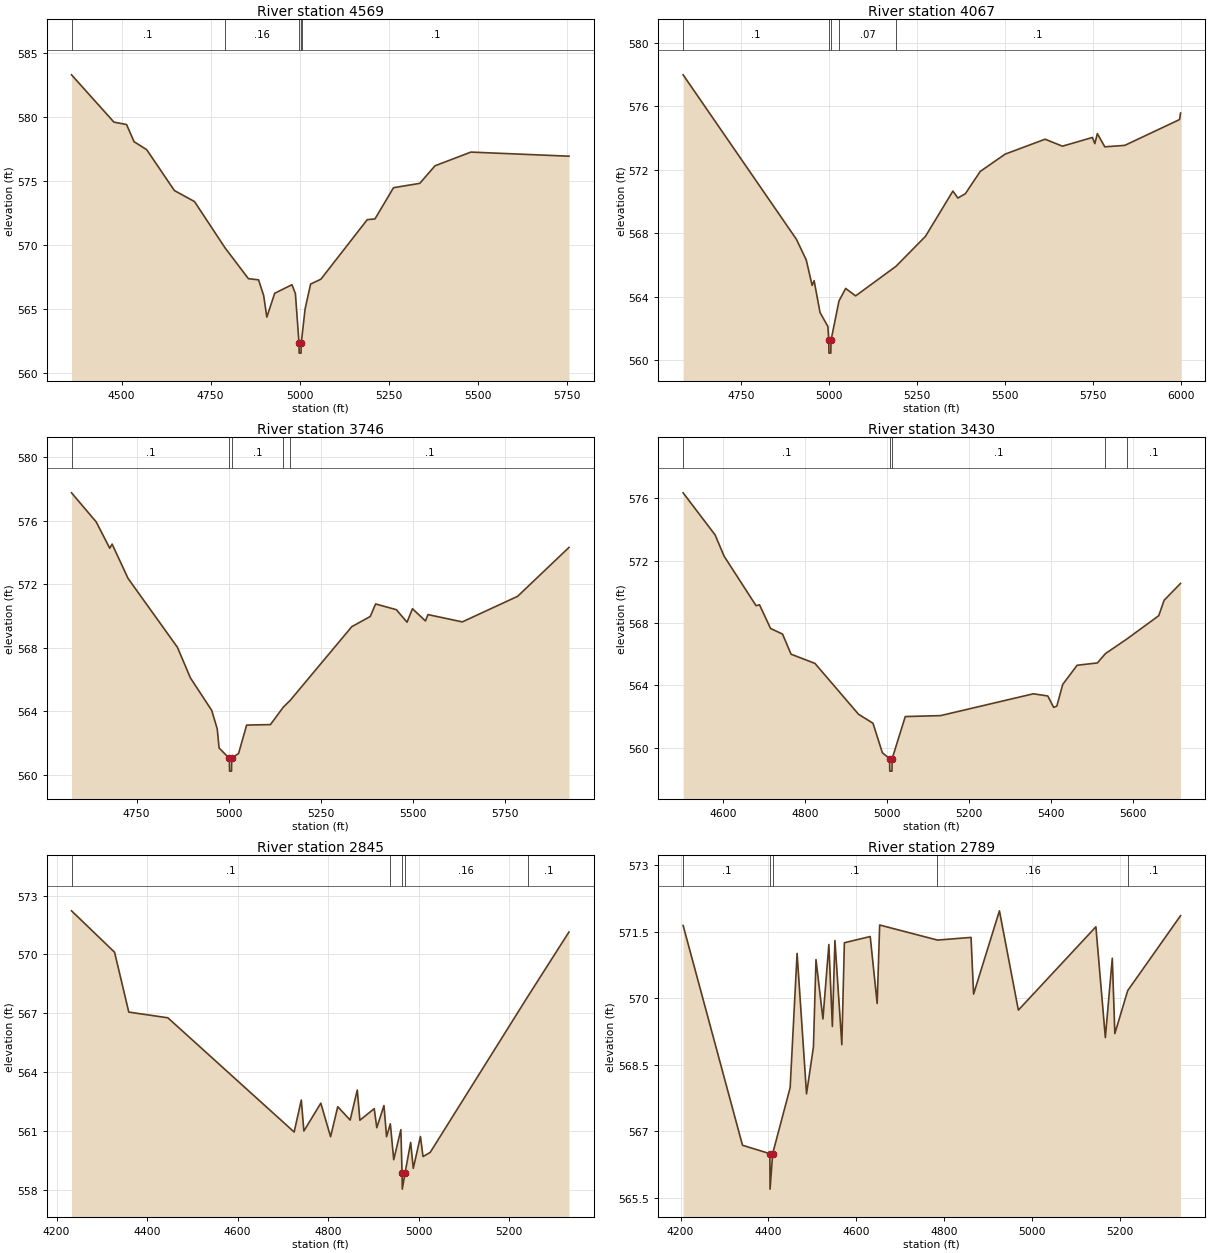
Type RM Length L Ch R = 1,4569,502,502,502
BEGIN DESCRIPTION:
Mapping XS 1024714e
END DESCRIPTION:
XS GIS Cut Line= 3
      2012283.74     13533617.74      2012570.18     13533898.97
      2013084.85     13534751.56
#Sta/Elev= 30
  4359.5  583.27  4478.6  579.58  4514.1  579.39  4535.2  578.05  4570.6  577.43
  4648.4  574.24  4704.9  573.38  4790.4  569.78  4856.4  567.36  4884.8  567.27
  4899.2  566.05  4908.1  564.36  4930.2  566.22  4978.7  566.89  4988.4  566.19
  4998.5  562.35  4999.0  561.55  5004.2  561.55  5004.7  562.35  5005.8  562.58
  5015.6  565.00  5031.1  566.94  5060.0  567.32  5190.3  571.97  5211.8  572.02
  5264.0  574.46  5337.8  574.80  5380.5  576.17  5481.4  577.24  5756.8  576.92
#Mann=5,-1,0
  4359.5     0.1       0  4790.4    0.16       0  4998.5    0.07       0
  5004.7    0.16       0  5005.8     0.1       0
Bank Sta=4998.5,5004.7
Exp/Cntr=0.3,0.1

Type RM Length L Ch R = 1,4067,321,321,321
BEGIN DESCRIPTION:
UNT 015 in HW 7.0
END DESCRIPTION:
XS GIS Cut Line= 3
      2011874.96     13534024.98      2012275.00     13534225.00
      2012970.61     13534893.18
#Sta/Elev= 30
  4585.6  577.99  4907.1  567.62  4935.0  566.32  4951.8  564.71  4957.4  565.01
  4974.2  563.00  4996.5  562.12  4999.0  561.24  4999.5  560.44  5004.8  560.44
  5005.3  561.24  5028.0  563.73  5046.9  564.52  5075.2  564.05  5189.5  565.91
  5273.3  567.80  5351.3  570.66  5365.4  570.22  5386.5  570.49  5428.9  571.90
  5499.7  572.99  5612.9  573.93  5662.3  573.49  5747.2  574.04  5754.1  573.65
  5761.3  574.28  5782.4  573.45  5839.0  573.54  5994.7  575.17  5997.4  575.58
#Mann=5,-1,0
  4585.6     0.1       0  4999.0    0.07       0  5005.3     0.1       0
  5028.0    0.07       0  5189.5     0.1       0
Bank Sta=4999,5005.3
Exp/Cntr=0.3,0.1

Type RM Length L Ch R = 1,3746,316,316,316
BEGIN DESCRIPTION:
UNT 015 in HW 6.0
END DESCRIPTION:
XS GIS Cut Line= 3
      2011725.01     13534275.01      2012075.00     13534475.00
      2012830.30     13535044.58
#Sta/Elev= 30
  4573.7  577.77  4640.6  575.94  4677.3  574.28  4683.8  574.54  4727.0  572.38
  4860.9  568.04  4896.2  566.11  4953.8  564.07  4968.9  562.90  4973.9  561.70
  5001.8  561.04  5002.3  560.24  5007.6  560.24  5008.1  561.04  5026.9  561.36
  5048.6  563.14  5113.1  563.17  5148.1  564.27  5166.5  564.69  5333.8  569.34
  5383.8  569.98  5398.4  570.77  5454.6  570.41  5483.7  569.62  5498.3  570.47
  5533.7  569.70  5540.4  570.10  5633.6  569.64  5783.5  571.25  5922.8  574.33
#Mann=5,-1,0
  4573.7     0.1       0  5001.8    0.07       0  5008.1     0.1       0
  5148.1    0.12       0  5166.5     0.1       0
Bank Sta=5001.8,5008.1
Exp/Cntr=0.3,0.1

Type RM Length L Ch R = 1,3430,585,585,585
BEGIN DESCRIPTION:
UNT 015 in HW 5.0
END DESCRIPTION:
XS GIS Cut Line= 3
      2011675.03     13534375.04      2011975.00     13534775.00
      2012429.56     13535326.06
#Sta/Elev= 30
  4502.7  576.35  4580.8  573.65  4602.7  572.29  4680.8  569.11  4689.1  569.17
  4716.2  567.65  4745.4  567.29  4766.2  566.00  4824.5  565.41  4930.8  562.15
  4966.2  561.57  4989.1  559.68  5006.7  559.30  5007.2  558.50  5012.5  558.50
  5013.0  559.30  5045.0  562.00  5131.0  562.06  5357.7  563.46  5392.9  563.32
  5407.2  562.59  5415.0  562.67  5429.4  564.06  5464.5  565.29  5514.0  565.44
  5533.7  566.04  5585.2  566.96  5663.8  568.47  5676.9  569.46  5717.0  570.54
#Mann=5,-1,0
  4502.7     0.1       0  5006.7    0.07       0  5013.0     0.1       0
  5533.7    0.16       0  5585.2     0.1       0
Bank Sta=5006.7,5013
Exp/Cntr=0.3,0.1

Type RM Length L Ch R = 1,2845,56,56,56
BEGIN DESCRIPTION:
Mapping XS 024ac9cc
END DESCRIPTION:
XS GIS Cut Line= 2
      2011335.81     13534612.52      2011882.70     13535565.67
#Sta/Elev= 30
  4233.2  572.22  4328.3  570.11  4359.7  567.06  4446.0  566.77  4725.0  560.95
  4740.8  562.58  4746.5  561.00  4783.9  562.42  4805.5  560.71  4821.3  562.24
  4848.7  561.56  4864.5  563.09  4870.2  561.55  4901.9  562.14  4907.6  561.17
  4923.4  562.30  4929.2  560.71  4937.5  561.37  4945.0  559.54  4960.8  561.07
  4963.4  558.84  4963.9  558.04  4969.8  558.84  4982.4  560.42  4988.2  559.10
  5004.0  560.72  5009.7  559.70  5025.5  559.91  5241.1  567.85  5332.1  571.14
#Mann=5,-1,0
  4233.2     0.1       0  4937.5    0.16       0  4963.4    0.07       0
  4969.8    0.16       0  5241.1     0.1       0
Bank Sta=4963.4,4969.8
Exp/Cntr=0.3,0.1

Type RM Length L Ch R = 1,2789,41,41,41
BEGIN DESCRIPTION:
Mapping XS 200081cf
END DESCRIPTION:
XS GIS Cut Line= 2
      2011278.53     13534628.16      2011846.22     13535607.30
#Sta/Elev= 30
  4205.9  571.64  4341.0  566.68  4403.2  566.49  4403.7  565.69  4409.6  566.49
  4449.4  567.98  4465.2  571.01  4486.7  567.84  4502.4  568.90  4508.2  570.87
  4524.0  569.53  4537.5  571.21  4545.5  569.36  4551.3  571.30  4567.0  568.95
  4572.8  571.25  4631.6  571.39  4647.4  569.88  4653.1  571.65  4784.6  571.31
  4861.0  571.37  4866.8  570.09  4925.6  571.97  4968.7  569.73  5145.1  571.61
  5166.6  569.11  5182.4  570.90  5188.2  569.20  5217.5  570.17  5337.7  571.86
#Mann=5,-1,0
  4205.9     0.1       0  4403.2    0.07       0  4409.6     0.1       0
  4784.6    0.16       0  5217.5     0.1       0
Bank Sta=4403.2,4409.6
Exp/Cntr=0.3,0.1

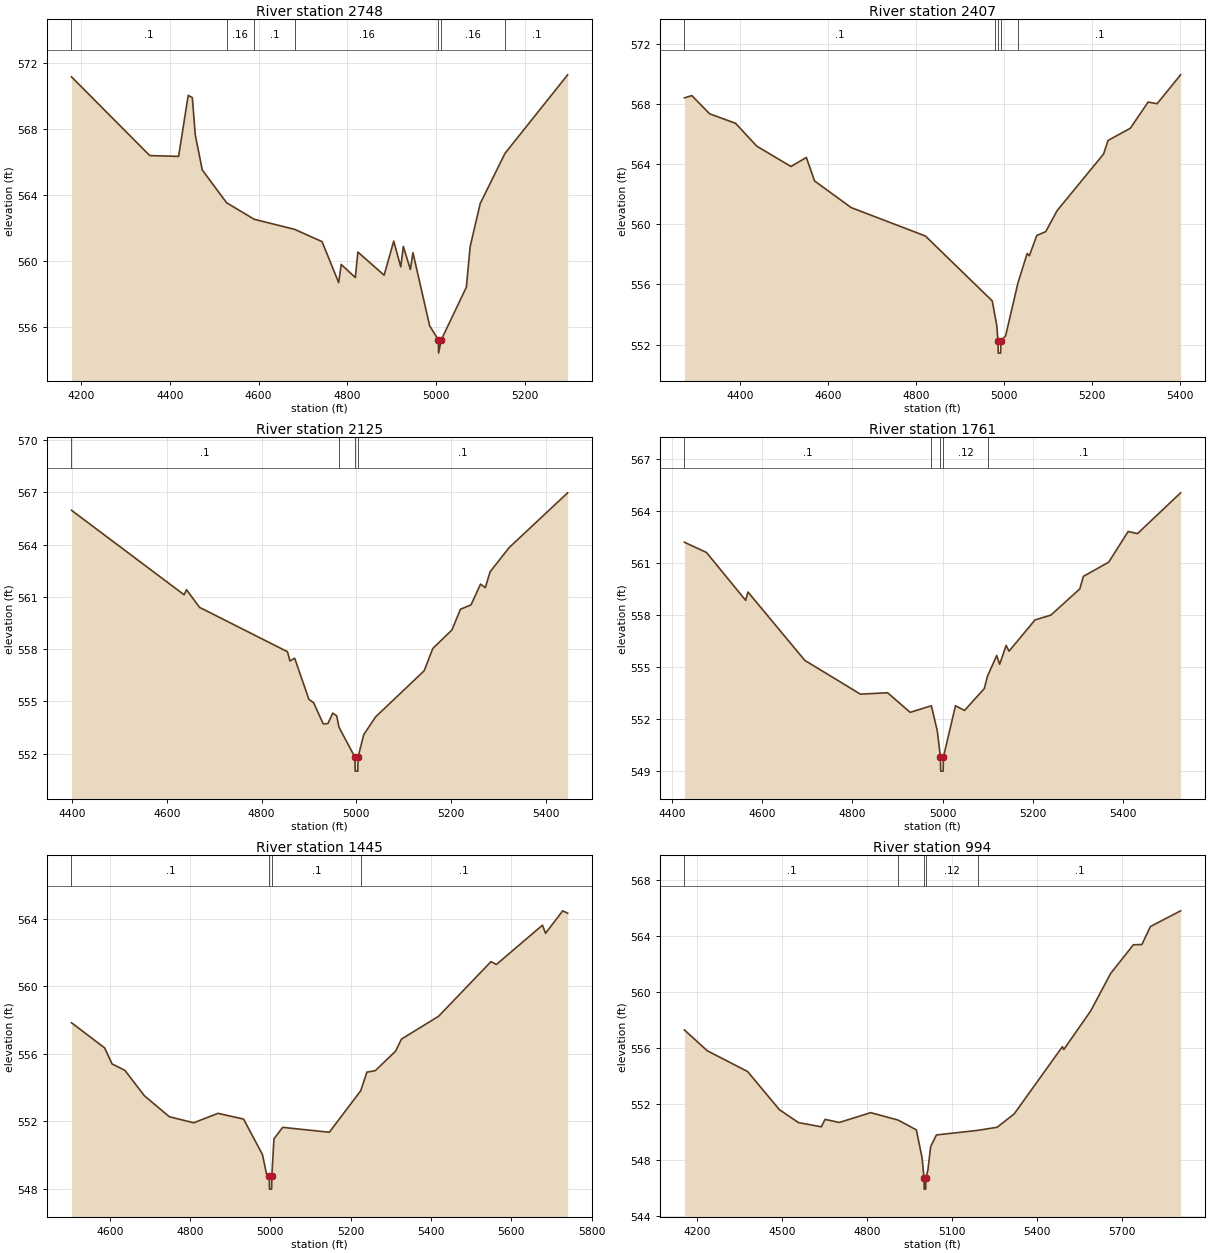
Type RM Length L Ch R = 1,2748,341,341,341
BEGIN DESCRIPTION:
UNT 015 in HW 4.0
END DESCRIPTION:
XS GIS Cut Line= 3
      2011242.04     13534628.12      2011637.89     13535326.05
      2011772.69     13535611.22
#Sta/Elev= 30
  4178.3  571.14  4354.7  566.38  4419.6  566.33  4441.3  570.02  4450.6  569.88
  4457.2  567.63  4473.0  565.51  4527.7  563.53  4589.9  562.53  4681.1  561.92
  4742.8  561.18  4780.3  558.70  4786.0  559.80  4817.8  559.01  4823.5  560.55
  4882.7  559.15  4904.3  561.21  4920.2  559.65  4925.9  560.89  4941.8  559.50
  4947.6  560.51  4985.3  556.09  5004.9  555.24  5005.4  554.44  5011.3  555.24
  5068.0  558.43  5076.4  560.87  5099.1  563.48  5154.9  566.51  5296.1  571.26
#Mann=7,-1,0
  4178.3     0.1       0  4527.7    0.16       0  4589.9     0.1       0
  4681.1    0.16       0  5004.9    0.07       0  5011.3    0.16       0
  5154.9     0.1       0
Bank Sta=5004.9,5011.3
Exp/Cntr=0.3,0.1

Type RM Length L Ch R = 1,2407,282,282,282
BEGIN DESCRIPTION:
Mapping XS 7dc41624
END DESCRIPTION:
XS GIS Cut Line= 3
      2011127.48     13534659.41      2011283.72     13535044.80
      2011393.09     13535747.89
#Sta/Elev= 30
  4274.4  568.39  4291.2  568.54  4331.7  567.33  4390.6  566.70  4438.8  565.18
  4516.5  563.83  4551.4  564.43  4570.1  562.87  4653.2  561.10  4822.0  559.21
  4973.8  554.90  4979.9  553.94  4983.9  553.31  4986.9  552.23  4987.4  551.43
  4992.9  551.43  4993.4  552.23  5004.2  552.58  5032.2  556.09  5053.1  558.05
  5058.1  557.90  5075.0  559.25  5095.3  559.50  5121.0  560.89  5226.8  564.66
  5236.9  565.56  5287.6  566.37  5328.0  568.11  5348.3  568.00  5401.8  569.92
#Mann=5,-1,0
  4274.4     0.1       0  4979.9    0.16       0  4986.9    0.07       0
  4993.4    0.16       0  5032.2     0.1       0
Bank Sta=4986.9,4993.4
Exp/Cntr=0.3,0.1

Type RM Length L Ch R = 1,2125,364,364,364
BEGIN DESCRIPTION:
UNT 015 in HW 3.0
END DESCRIPTION:
XS GIS Cut Line= 3
      2011007.68     13534695.83      2011064.97     13535310.43
      2011117.05     13535737.50
#Sta/Elev= 30
  4398.7  565.97  4636.5  561.12  4641.6  561.41  4669.0  560.40  4854.8  557.85
  4859.9  557.32  4869.9  557.48  4900.0  555.12  4910.1  554.92  4930.2  553.71
  4940.2  553.73  4950.2  554.33  4958.8  554.17  4963.4  553.52  4997.2  551.80
  4997.7  551.00  5003.2  551.00  5003.7  551.80  5015.7  553.09  5040.7  554.11
  5143.3  556.76  5161.6  558.04  5201.9  559.10  5219.9  560.29  5242.2  560.54
  5262.3  561.73  5272.4  561.53  5282.5  562.44  5322.8  563.83  5446.2  566.97
#Mann=4,-1,0
  4398.7     0.1       0  4963.4    0.12       0  4997.2    0.07       0
  5003.7     0.1       0
Bank Sta=4997.2,5003.7
Exp/Cntr=0.3,0.1

Type RM Length L Ch R = 1,1761,316,316,316
BEGIN DESCRIPTION:
UNT 015 in HW 2.0
END DESCRIPTION:
XS GIS Cut Line= 3
      2010679.56     13534706.31      2010731.64     13535388.55
      2010992.07     13535711.49
#Sta/Elev= 30
  4427.8  562.21  4476.6  561.62  4563.4  558.86  4568.5  559.34  4694.3  555.40
  4817.6  553.45  4877.8  553.53  4927.9  552.40  4974.8  552.78  4988.1  551.31
  4994.9  549.81  4995.4  549.01  5000.9  549.01  5001.4  549.81  5028.2  552.78
  5048.3  552.51  5092.0  553.77  5099.2  554.49  5119.6  555.68  5126.0  555.17
  5140.4  556.26  5146.9  555.93  5204.4  557.73  5239.6  558.01  5303.6  559.52
  5311.5  560.24  5367.6  561.06  5410.7  562.83  5431.5  562.71  5526.9  565.06
#Mann=5,-1,0
  4427.8     0.1       0  4974.8    0.12       0  4994.9    0.07       0
  5001.4    0.12       0  5099.2     0.1       0
Bank Sta=4994.9,5001.4
Exp/Cntr=0.3,0.1

Type RM Length L Ch R = 1,1445,451,451,451
BEGIN DESCRIPTION:
Mapping XS 0e7b5824
END DESCRIPTION:
XS GIS Cut Line= 3
      2010367.06     13534753.16      2010445.18     13535378.14
      2010939.97     13535727.09
#Sta/Elev= 30
  4504.8  557.84  4587.3  556.35  4605.8  555.40  4637.7  555.02  4686.4  553.51
  4748.5  552.27  4809.0  551.91  4869.5  552.47  4933.3  552.13  4980.3  550.03
  4990.4  548.88  4997.2  548.78  4997.7  547.98  5003.2  547.98  5003.7  548.78
  5008.9  550.96  5030.7  551.64  5146.7  551.35  5225.0  553.81  5240.2  554.91
  5261.1  555.00  5311.6  556.15  5326.4  556.87  5418.7  558.22  5549.3  561.46
  5562.7  561.29  5677.4  563.62  5685.1  563.14  5727.9  564.47  5740.1  564.33
#Mann=4,-1,0
  4504.8     0.1       0  4997.2    0.07       0  5003.7     0.1       0
  5225.0     0.1       0
Bank Sta=4997.2,5003.7
Exp/Cntr=0.3,0.1

Type RM Length L Ch R = 1,994,252,252,252
BEGIN DESCRIPTION:
Mapping XS 271dbea1
END DESCRIPTION:
XS GIS Cut Line= 4
      2010226.43     13534727.08      2010158.72     13535034.39
      2010242.05     13535695.85      2011011.43     13535747.83
#Sta/Elev= 30
  4155.2  557.29  4235.8  555.81  4378.3  554.33  4490.7  551.61  4558.1  550.69
  4638.5  550.39  4651.9  550.92  4702.3  550.70  4813.2  551.40  4909.9  550.87
  4974.4  550.17  4994.6  548.18  5001.4  546.75  5001.9  545.95  5007.4  545.95
  5007.9  546.75  5014.8  547.27  5024.8  548.97  5045.1  549.81  5192.5  550.14
  5259.8  550.36  5319.9  551.31  5490.1  556.10  5495.1  555.90  5590.5  558.66
  5660.7  561.32  5740.9  563.36  5771.0  563.38  5801.0  564.66  5907.7  565.78
#Mann=5,-1,0
  4155.2     0.1       0  4909.9    0.12       0  5001.4    0.07       0
  5007.9    0.12       0  5192.5     0.1       0
Bank Sta=5001.4,5007.9
Exp/Cntr=0.3,0.1

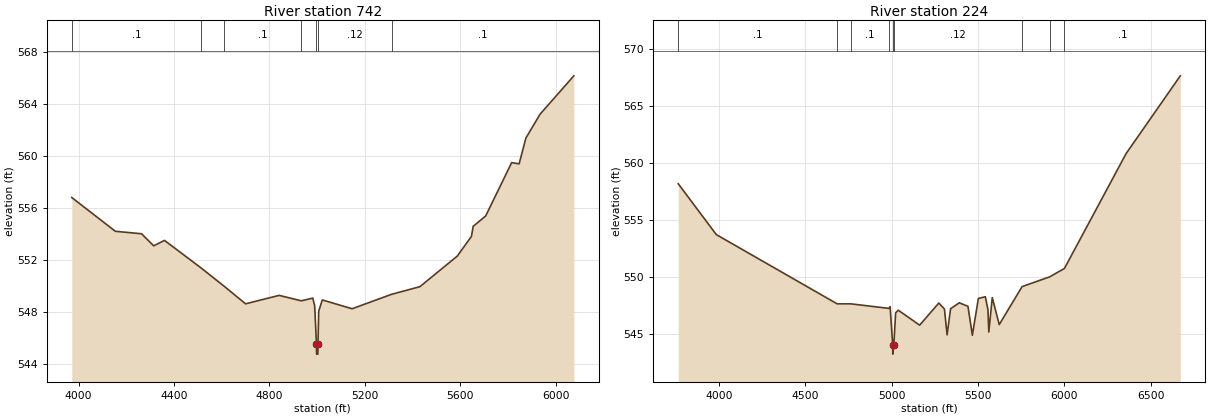
Type RM Length L Ch R = 1,742,518,518,518
BEGIN DESCRIPTION:
Mapping XS 9b3471d5
END DESCRIPTION:
XS GIS Cut Line= 4
      2010054.55     13534617.76      2009913.93     13535336.47
      2010064.97     13535742.72      2010991.07     13535904.01
#Sta/Elev= 30
  3971.0  556.83  4153.8  554.23  4263.7  554.04  4314.6  553.11  4359.9  553.53
  4512.7  551.42  4610.3  550.00  4700.0  548.65  4840.7  549.30  4933.7  548.88
  4981.8  549.09  4989.8  548.50  4997.2  545.58  4997.7  544.78  5003.2  544.78
  5003.7  545.58  5006.8  548.09  5021.8  548.95  5146.9  548.27  5312.1  549.38
  5431.2  549.97  5587.8  552.32  5647.4  553.84  5654.5  554.61  5707.0  555.41
  5816.0  559.51  5847.3  559.42  5875.6  561.40  5935.2  563.24  6076.8  566.19
#Mann=7,-1,0
  3971.0     0.1       0  4512.7    0.05       0  4610.3     0.1       0
  4933.7    0.12       0  4997.2    0.07       0  5003.7    0.12       0
  5312.1     0.1       0
Bank Sta=4997.2,5003.7
Exp/Cntr=0.3,0.1

Type RM Length L Ch R = 1,224,0,0,0
BEGIN DESCRIPTION:
UNT 015 in HW 1.0
END DESCRIPTION:
XS GIS Cut Line= 4
      2009981.62     13534466.71      2009549.35     13535357.30
      2009768.10     13535872.93      2011117.09     13536023.98
#Sta/Elev= 30
  3763.2  558.20  3983.6  553.74  4683.3  547.67  4762.2  547.67  4983.2  547.27
  4990.2  547.42  5005.2  544.06  5005.7  543.26  5011.7  544.06  5022.2  546.88
  5037.5  547.11  5161.3  545.80  5272.2  547.74  5304.7  547.22  5320.2  544.95
  5340.3  547.24  5390.7  547.76  5441.0  547.45  5466.4  544.92  5501.3  548.14
  5541.6  548.29  5556.6  547.17  5561.7  545.20  5581.8  548.22  5622.1  545.85
  5754.5  549.18  5913.4  550.03  5999.7  550.77  6356.7  560.84  6670.7  567.66
#Mann=9,-1,0
  3763.2     0.1       0  4683.3    0.05       0  4762.2     0.1       0
  4983.2    0.12       0  5005.2    0.07       0  5011.7    0.12       0
  5754.5     0.1       0  5913.4    0.12       0  5999.7     0.1       0
Bank Sta=5005.2,5011.7
Exp/Cntr=0.3,0.1

Chan Stop Cuts=-1