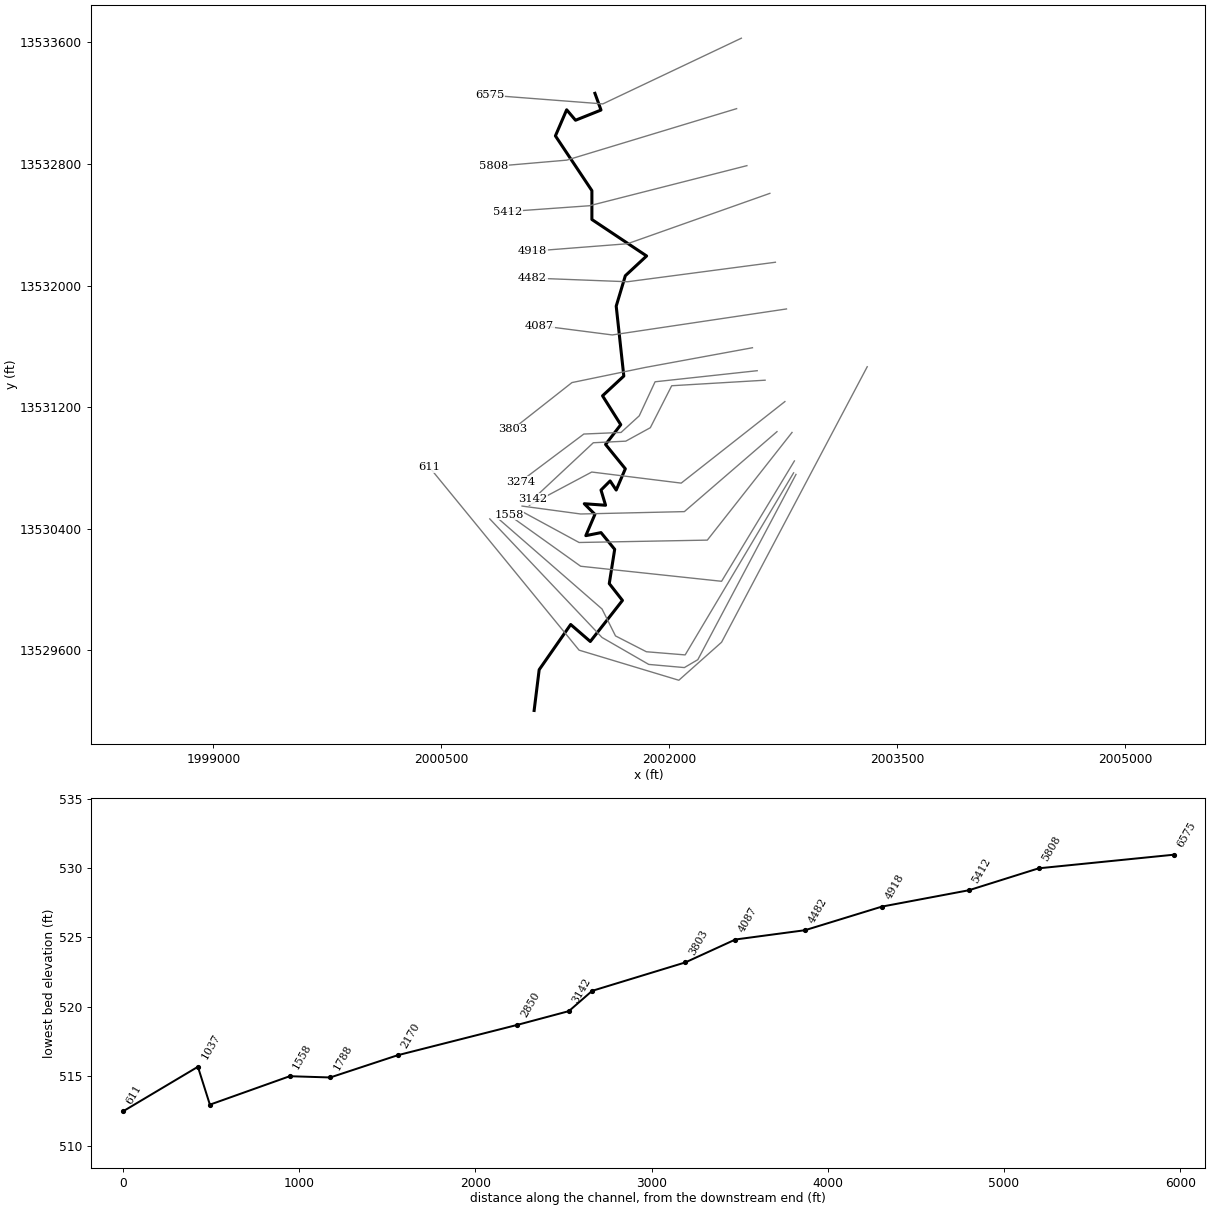
--- UNT 016 in HW.prj (project) ---

Proj Title=UNT 016 in HW Base Level Engineering
Current Plan=p01
Default Exp/Contr=0.3,0.1
English Units
Geom File=g01
Flow File=f01
Plan File=p01
BEGIN DESCRIPTION:
UNT 016 in HW
END DESCRIPTION:

--- UNT 016 in HW.p01 (plan) ---

Plan Title=Multiple Run
Short Identifier=Multiple
Geom File=g01
Flow File=f01
Subcritical Flow
K Sum by GR= 0
Std Step Tol= 0.01
Critical Tol= 0.01
Num of Std Step Trials= 20
Max Error Tol= 0.3
Flow Tol Ratio= 0.001
Split Flow NTrial= 30
Split Flow Tol= 0.02
Split Flow Ratio= 0.02
Log Output Level= 0
Friction Slope Method= 1
Unsteady Friction Slope Method= 2
Unsteady Bridges Friction Slope Method= 1
Parabolic Critical Depth
Global Vel Dist=  1 , 1 , 1
Global Log Level= 0
CheckData=True
Encroach Param= -1, 0, 0, 0
BEGIN DESCRIPTION:
Multiple Run
END DESCRIPTION:

--- UNT 016 in HW.f01 (steady flow) ---

Flow Title=Multiple
Number of Profiles=7
Profile Names=10-year,25-year,50-year,1pct_min,100-year,1pct_plu,500-year
River Rch & RM= UNT 016 in HW,Reach-1,6575
     159     214     259     156     312     622     459
River Rch & RM= UNT 016 in HW,Reach-1,5808
     259     359     441     270     539    1075     817
Boundary for River Rch & Prof#=UNT 016 in HW,Reach-1,1
Up Type=0
Dn Type=3
Dn Slope=0.005
Boundary for River Rch & Prof#=UNT 016 in HW,Reach-1,2
Up Type=0
Dn Type=3
Dn Slope=0.005
Boundary for River Rch & Prof#=UNT 016 in HW,Reach-1,3
Up Type=0
Dn Type=3
Dn Slope=0.005
Boundary for River Rch & Prof#=UNT 016 in HW,Reach-1,4
Up Type=0
Dn Type=3
Dn Slope=0.005
Boundary for River Rch & Prof#=UNT 016 in HW,Reach-1,5
Up Type=0
Dn Type=3
Dn Slope=0.005
Boundary for River Rch & Prof#=UNT 016 in HW,Reach-1,6
Up Type=0
Dn Type=3
Dn Slope=0.005
Boundary for River Rch & Prof#=UNT 016 in HW,Reach-1,7
Up Type=0
Dn Type=3
Dn Slope=0.005

--- UNT 016 in HW.g01 (geometry) ---

Geom Title=Existing Conditions

River Reach=UNT 016 in HW,Reach-1
Reach XY= 30
      2001510.80     13533264.54      2001550.80     13533154.54
      2001383.15     13533087.52      2001324.82     13533156.27
      2001250.80     13532984.54      2001490.80     13532624.54
      2001490.80     13532434.54      2001850.80     13532194.54
      2001710.80     13532064.54      2001650.80     13531864.54
      2001700.80     13531404.54      2001560.80     13531274.54
      2001680.80     13531084.54      2001580.80     13530954.54
      2001710.80     13530794.54      2001650.80     13530654.54
      2001610.80     13530714.54      2001550.80     13530654.54
      2001580.80     13530554.54      2001440.80     13530564.54
      2001510.80     13530494.54      2001450.80     13530354.54
      2001550.80     13530374.54      2001640.80     13530264.54
      2001605.16     13530039.12      2001691.97     13529928.44
      2001480.38     13529658.26      2001351.26     13529770.02
      2001144.01     13529472.71      2001110.80     13529204.54

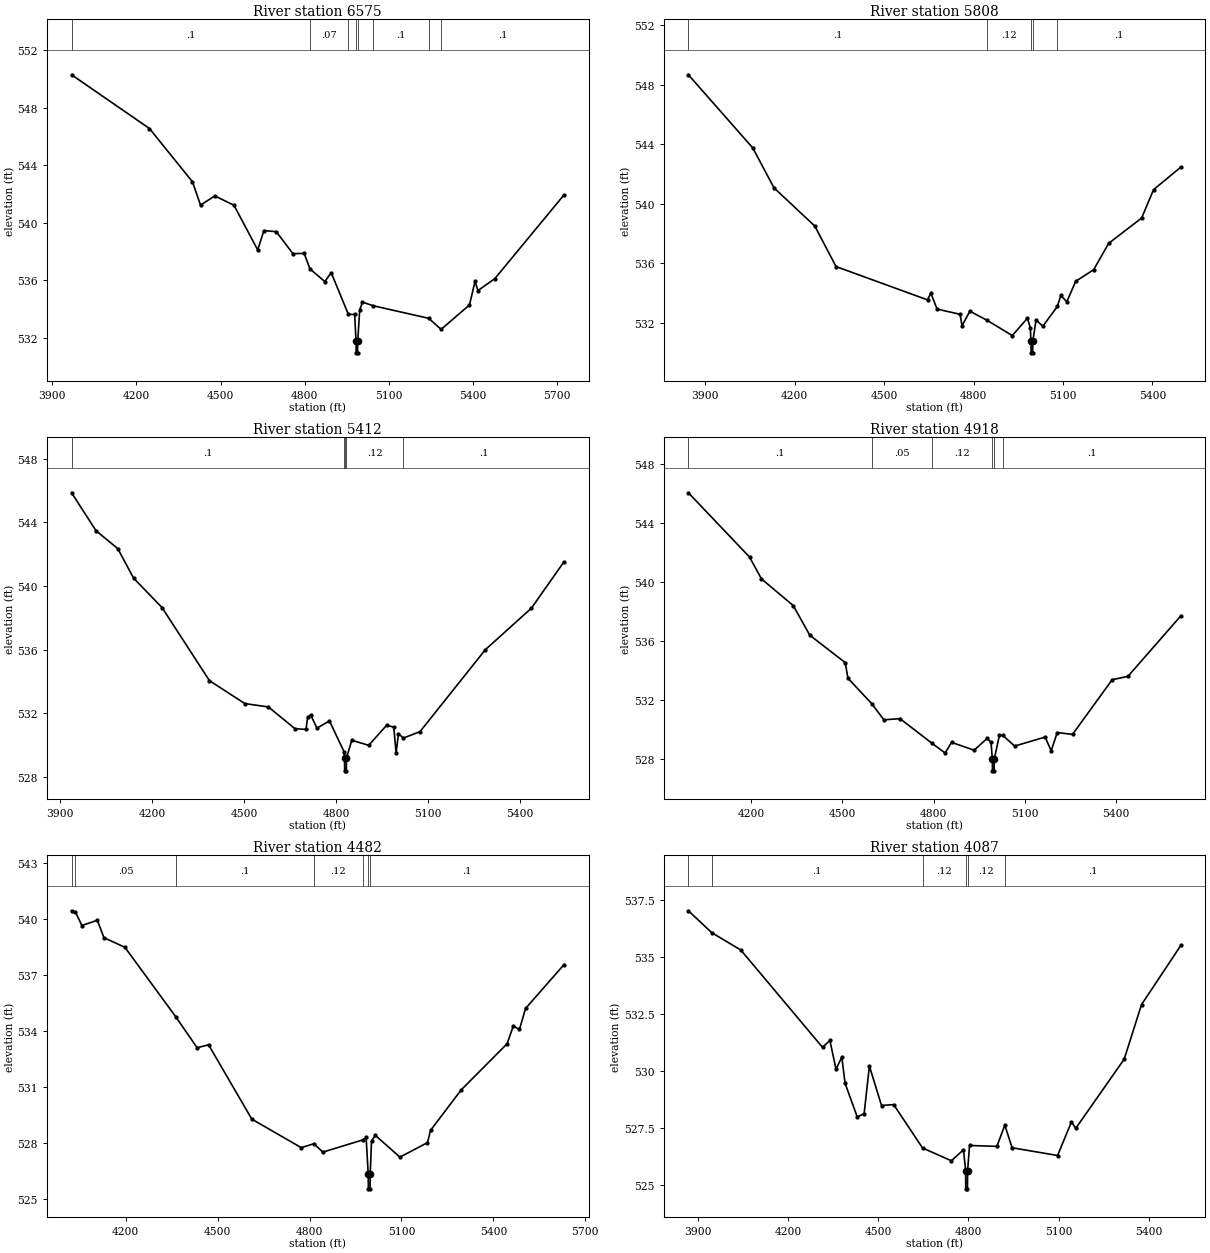
Type RM Length L Ch R = 1,6575,767,767,767
BEGIN DESCRIPTION:
UNT 016 in HW 7.0
END DESCRIPTION:
XS GIS Cut Line= 3
      2002474.22     13533627.25      2001562.80     13533194.98
      2000819.03     13533252.19
#Sta/Elev= 30
  3969.2  550.31  4246.7  546.57  4400.0  542.86  4428.6  541.24  4479.6  541.88
  4547.8  541.23  4632.4  538.12  4654.5  539.47  4698.8  539.39  4757.9  537.86
  4797.9  537.88  4818.6  536.80  4871.6  535.92  4894.3  536.54  4955.4  533.64
  4977.9  533.63  4982.8  531.76  4983.3  530.96  4988.3  530.96  4988.8  531.76
  4995.8  533.94  5005.8  534.49  5043.3  534.24  5242.3  533.36  5285.8  532.59
  5386.9  534.29  5407.0  535.94  5417.0  535.29  5477.2  536.12  5723.9  541.95
#Mann=8,-1,0
  3969.2     0.1       0  4818.6    0.07       0  4955.4    0.12       0
  4982.8    0.07       0  4988.8    0.12       0  5043.3     0.1       0
  5242.3    0.12       0  5285.8     0.1       0
Bank Sta=4982.8,4988.8
Exp/Cntr=0.3,0.1

Type RM Length L Ch R = 1,5808,396,396,396
BEGIN DESCRIPTION:
UNT 016 in HW 6.0
END DESCRIPTION:
XS GIS Cut Line= 3
      2002443.01     13533163.73      2001325.00     13532825.00
      2000844.08     13532783.52
#Sta/Elev= 30
  3844.1  548.67  4060.1  543.75  4131.1  541.07  4268.0  538.50  4339.1  535.78
  4645.8  533.54  4657.0  533.99  4677.9  532.92  4755.0  532.57  4761.5  531.80
  4787.9  532.78  4846.1  532.16  4930.0  531.14  4981.0  532.31  4990.6  531.64
  4992.6  530.78  4993.1  529.98  4998.5  529.98  4999.0  530.78  5009.7  532.19
  5032.4  531.77  5081.4  533.10  5092.6  533.84  5112.7  533.41  5142.8  534.79
  5203.0  535.57  5253.2  537.34  5363.6  539.04  5403.7  540.95  5495.0  542.46
#Mann=5,-1,0
  3844.1     0.1       0  4846.1    0.12       0  4992.6    0.07       0
  4999.0    0.12       0  5081.4     0.1       0
Bank Sta=4992.6,4999
Exp/Cntr=0.3,0.1

Type RM Length L Ch R = 1,5412,494,494,494
BEGIN DESCRIPTION:
UNT 016 in HW 5.0
END DESCRIPTION:
XS GIS Cut Line= 3
      2002510.73     13532788.73      2001475.00     13532525.00
      2000938.95     13532486.73
#Sta/Elev= 30
  3937.2  545.85  4016.8  543.47  4087.6  542.35  4139.5  540.49  4232.1  538.65
  4386.8  534.06  4502.5  532.62  4579.1  532.41  4666.1  531.04  4701.8  531.00
  4707.0  531.76  4717.0  531.91  4737.5  531.08  4778.4  531.53  4825.9  529.60
  4827.4  529.20  4827.9  528.40  4833.3  528.40  4833.8  529.20  4851.2  530.32
  4906.3  530.00  4964.7  531.26  4988.1  531.14  4995.7  529.52  5003.4  530.72
  5019.8  530.46  5073.7  530.86  5286.7  536.00  5437.1  538.61  5543.4  541.52
#Mann=5,-1,0
  3937.2     0.1       0  4825.9    0.12       0  4827.4    0.07       0
  4833.8    0.12       0  5019.8     0.1       0
Bank Sta=4827.4,4833.8
Exp/Cntr=0.3,0.1

Type RM Length L Ch R = 1,4918,436,436,436
BEGIN DESCRIPTION:
UNT 016 in HW 4.0
END DESCRIPTION:
XS GIS Cut Line= 3
      2002661.75     13532606.43      2001725.00     13532275.00
      2001099.65     13532226.26
#Sta/Elev= 30
  3992.7  546.08  4194.0  541.72  4233.2  540.24  4337.9  538.43  4392.3  536.42
  4509.0  534.56  4518.0  533.50  4596.4  531.77  4636.3  530.68  4689.3  530.76
  4795.1  529.08  4837.9  528.43  4859.1  529.15  4933.3  528.62  4976.2  529.42
  4988.9  529.16  4993.2  528.02  4993.7  527.22  4999.1  527.22  4999.6  528.02
  5016.4  529.62  5026.9  529.64  5066.6  528.90  5166.9  529.51  5187.0  528.58
  5207.0  529.82  5257.2  529.69  5387.6  533.40  5439.7  533.63  5613.6  537.73
#Mann=6,-1,0
  3992.7     0.1       0  4596.4    0.05       0  4795.1    0.12       0
  4993.2    0.07       0  4999.6    0.12       0  5026.9     0.1       0
Bank Sta=4993.2,4999.6
Exp/Cntr=0.3,0.1

Type RM Length L Ch R = 1,4482,395,395,395
BEGIN DESCRIPTION:
UNT 016 in HW 3.0
END DESCRIPTION:
XS GIS Cut Line= 3
      2002698.23     13532153.31      2001725.00     13532025.00
      2001099.62     13532049.13
#Sta/Elev= 30
  4023.1  540.44  4035.7  540.37  4056.6  539.65  4107.1  539.93  4128.6  539.00
  4197.1  538.48  4364.1  534.73  4432.9  533.09  4470.2  533.25  4611.4  529.26
  4772.8  527.73  4813.8  527.94  4843.4  527.49  4974.6  528.15  4984.6  528.28
  4991.4  526.32  4991.9  525.52  4997.5  525.52  4998.0  526.32  5002.2  528.09
  5014.8  528.39  5094.8  527.22  5184.9  528.00  5194.9  528.66  5295.0  530.83
  5445.1  533.31  5465.1  534.26  5485.1  534.07  5505.1  535.20  5630.6  537.55
#Mann=7,-1,0
  4023.1     0.1       0  4035.7    0.05       0  4364.1     0.1       0
  4813.8    0.12       0  4974.6     0.1       0  4991.4    0.07       0
  4998.0     0.1       0
Bank Sta=4991.4,4998
Exp/Cntr=0.3,0.1

Type RM Length L Ch R = 1,4087,284,284,284
BEGIN DESCRIPTION:
UNT 016 in HW 2.0
END DESCRIPTION:
XS GIS Cut Line= 3
      2002771.10     13531846.01      2001625.00     13531675.00
      2001148.02     13531736.40
#Sta/Elev= 30
  3867.3  537.03  3945.3  536.07  4041.9  535.31  4313.9  531.05  4338.6  531.35
  4358.8  530.09  4378.2  530.62  4389.1  529.47  4429.6  528.00  4452.5  528.14
  4470.0  530.23  4510.4  528.50  4550.9  528.54  4647.0  526.64  4743.0  526.08
  4783.4  526.56  4790.5  525.65  4791.0  524.85  4796.6  524.85  4797.1  525.65
  4803.6  526.75  4894.6  526.71  4921.0  527.64  4945.2  526.65  5096.7  526.31
  5142.8  527.78  5157.2  527.50  5318.5  530.53  5376.2  532.92  5507.0  535.51
#Mann=6,-1,0
  3867.3    0.05       0  3945.3     0.1       0  4647.0    0.12       0
  4790.5    0.07       0  4797.1    0.12       0  4921.0     0.1       0
Bank Sta=4790.5,4797.1
Exp/Cntr=0.3,0.1

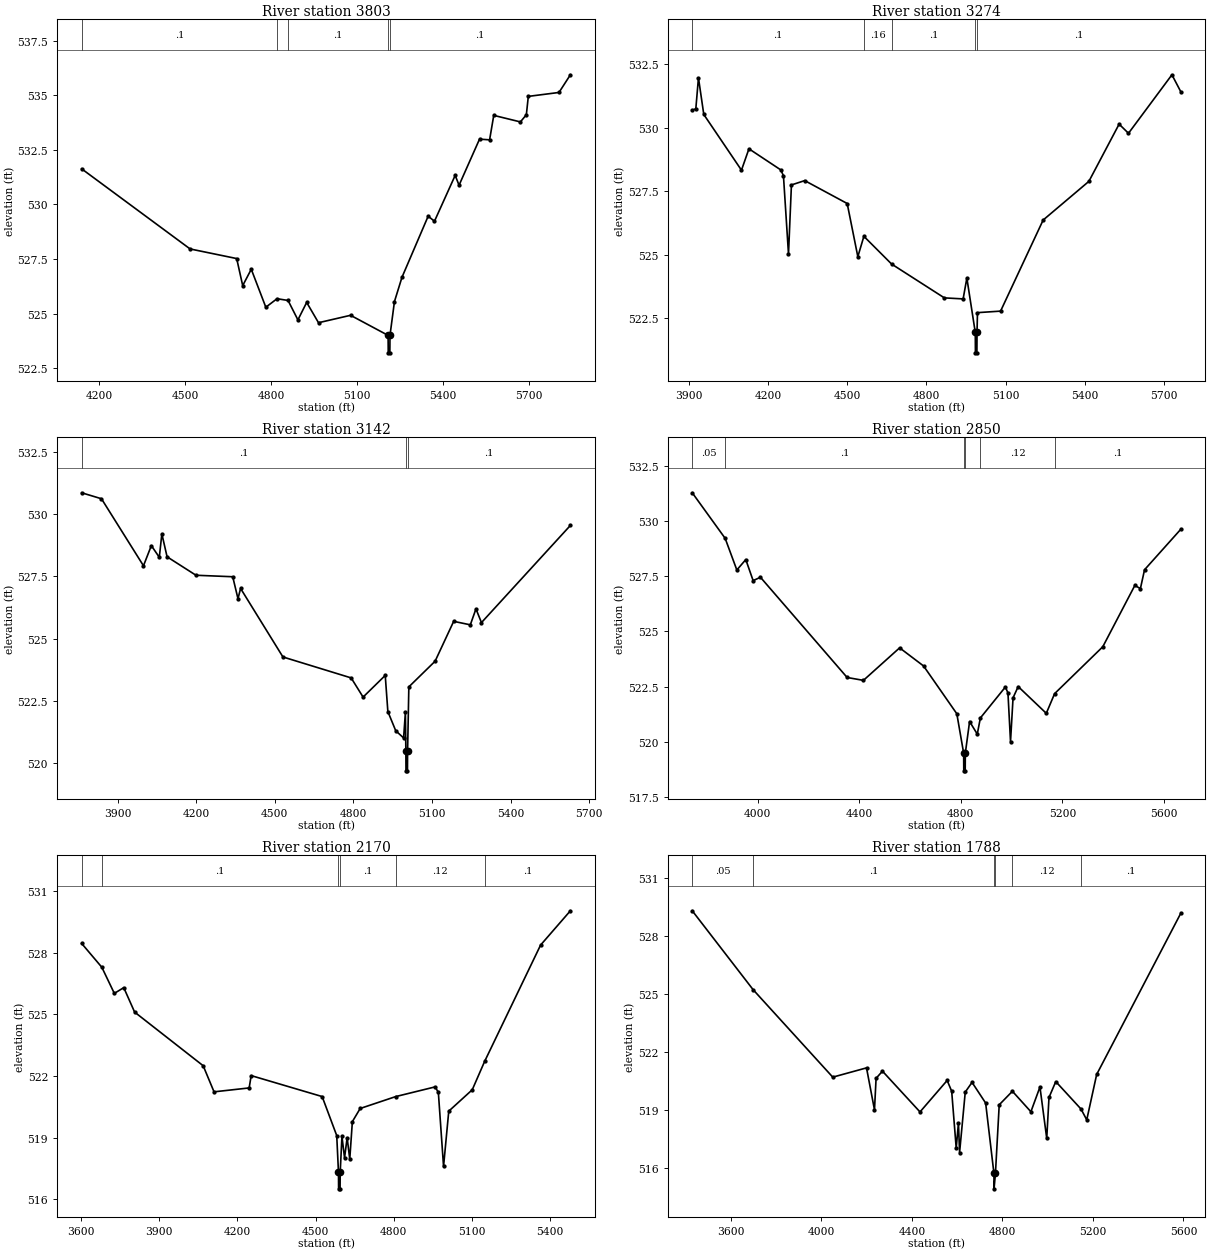
Type RM Length L Ch R = 1,3803,529,529,529
BEGIN DESCRIPTION:
Mapping XS 3444ca06
END DESCRIPTION:
XS GIS Cut Line= 4
      2002547.22     13531590.82      2001838.84     13531460.60
      2001359.68     13531361.64      2000969.54     13531054.74
#Sta/Elev= 30
  4138.8  531.63  4517.3  527.96  4679.9  527.52  4700.9  526.28  4730.8  527.03
  4781.6  525.29  4820.8  525.68  4859.2  525.60  4893.6  524.71  4924.2  525.51
  4965.5  524.58  5077.4  524.92  5208.4  524.00  5208.9  523.20  5214.5  523.20
  5215.0  524.00  5230.6  525.55  5256.8  526.66  5348.2  529.46  5370.3  529.23
  5442.5  531.33  5456.1  530.88  5527.5  532.99  5562.7  532.96  5577.2  534.08
  5670.2  533.78  5691.0  534.11  5697.8  534.95  5804.9  535.13  5844.7  535.94
#Mann=5,-1,0
  4138.8     0.1       0  4820.8    0.16       0  4859.2     0.1       0
  5208.4    0.07       0  5215.0     0.1       0
Bank Sta=5208.4,5215
Exp/Cntr=0.3,0.1

Type RM Length L Ch R = 1,3274,132,132,132
BEGIN DESCRIPTION:
Mapping XS 937fadc2
END DESCRIPTION:
XS GIS Cut Line= 6
      2002578.40     13531439.77      2001906.55     13531366.85
      2001802.38     13531142.89      2001682.59     13531033.52
      2001437.80     13531023.10      2001021.09     13530710.57
#Sta/Elev= 30
  3913.2  530.69  3926.7  530.74  3936.7  531.96  3956.9  530.52  4099.6  528.33
  4127.9  529.17  4248.6  528.34  4258.6  528.11  4277.7  525.03  4288.8  527.75
  4339.1  527.92  4500.0  527.02  4540.3  524.93  4563.2  525.73  4668.2  524.64
  4868.1  523.31  4939.1  523.27  4953.2  524.09  4985.1  521.95  4985.6  521.15
  4991.2  521.15  4991.7  521.95  4993.4  522.73  5080.9  522.79  5242.1  526.37
  5415.3  527.89  5529.8  530.14  5565.3  529.78  5729.8  532.08  5764.1  531.40
#Mann=5,-1,0
  3913.2     0.1       0  4563.2    0.16       0  4668.2     0.1       0
  4985.1    0.07       0  4991.7     0.1       0
Bank Sta=4985.1,4991.7
Exp/Cntr=0.3,0.1

Type RM Length L Ch R = 1,3142,292,292,292
BEGIN DESCRIPTION:
Mapping XS 59515960
END DESCRIPTION:
XS GIS Cut Line= 6
      2002630.48     13531377.27      2002015.93     13531340.81
      2001875.30     13531064.77      2001713.84     13530976.23
      2001500.30     13530965.81      2001104.44     13530595.99
#Sta/Elev= 30
  3762.7  530.85  3838.3  530.61  3998.6  527.92  4028.6  528.73  4059.0  528.26
  4068.7  529.20  4088.7  528.28  4198.9  527.54  4339.2  527.48  4359.2  526.60
  4369.2  527.01  4530.8  524.26  4791.1  523.42  4836.7  522.65  4921.2  523.52
  4931.2  522.07  4961.2  521.30  4991.3  521.01  4998.2  522.05  4999.9  520.49
  5000.4  519.69  5006.0  519.69  5006.5  520.49  5011.3  523.06  5111.5  524.09
  5182.4  525.69  5245.9  525.55  5267.4  526.19  5288.4  525.64  5627.8  529.54
#Mann=3,-1,0
  3762.7     0.1       0  4999.9    0.07       0  5006.5     0.1       0
Bank Sta=4999.9,5006.5
Exp/Cntr=0.3,0.1

Type RM Length L Ch R = 1,2850,680,680,680
BEGIN DESCRIPTION:
Mapping XS b6d94d03
END DESCRIPTION:
XS GIS Cut Line= 4
      2002760.70     13531236.63      2002078.43     13530700.19
      2001489.88     13530773.10      2001079.17     13530554.75
#Sta/Elev= 30
  3741.5  531.27  3871.2  529.21  3917.2  527.78  3952.5  528.25  3981.4  527.30
  4010.3  527.45  4351.9  522.92  4416.1  522.79  4558.8  524.26  4653.2  523.44
  4784.2  521.28  4811.1  519.50  4811.6  518.70  4817.2  518.70  4817.7  519.50
  4834.5  520.93  4864.8  520.36  4877.0  521.09  4975.6  522.49  4985.7  522.22
  4995.8  520.02  5005.8  522.00  5026.0  522.51  5136.8  521.30  5169.6  522.19
  5359.5  524.31  5485.7  527.08  5507.7  526.94  5524.0  527.79  5667.6  529.63
#Mann=6,-1,0
  3741.5    0.05       0  3871.2     0.1       0  4811.1    0.07       0
  4817.7     0.1       0  4877.0    0.12       0  5169.6     0.1       0
Bank Sta=4811.1,4817.7
Exp/Cntr=0.3,0.1

Type RM Length L Ch R = 1,2170,382,382,382
BEGIN DESCRIPTION:
Mapping XS 6b5505dc
END DESCRIPTION:
XS GIS Cut Line= 4
      2002708.63     13531038.73      2002099.26     13530512.69
      2001416.97     13530497.06      2001031.56     13530549.14
#Sta/Elev= 30
  3601.8  528.45  3679.3  527.29  3727.2  526.02  3763.4  526.30  3805.1  525.11
  4068.3  522.50  4110.0  521.23  4244.9  521.42  4252.6  522.02  4525.1  521.00
  4581.1  519.10  4587.8  517.31  4588.3  516.51  4593.9  516.51  4594.4  517.31
  4601.1  519.06  4611.1  518.02  4621.1  519.00  4631.1  517.95  4641.1  519.78
  4671.1  520.42  4807.8  521.00  4958.6  521.47  4971.2  521.21  4991.2  517.60
  5011.2  520.29  5101.4  521.33  5148.9  522.71  5363.7  528.37  5478.2  530.04
#Mann=6,-1,0
  3601.8    0.05       0  3679.3     0.1       0  4587.8    0.07       0
  4594.4     0.1       0  4807.8    0.12       0  5148.9     0.1       0
Bank Sta=4587.8,4594.4
Exp/Cntr=0.3,0.1

Type RM Length L Ch R = 1,1788,230,230,230
BEGIN DESCRIPTION:
Mapping XS fb33358a
END DESCRIPTION:
XS GIS Cut Line= 4
      2002807.59     13531033.52      2002250.30     13530325.19
      2001406.55     13530309.56      2001041.98     13530507.47
#Sta/Elev= 30
  3429.1  529.30  3697.9  525.22  4050.1  520.69  4199.3  521.17  4234.5  519.00
  4241.6  520.63  4269.8  521.00  4435.7  518.89  4555.7  520.52  4575.7  519.96
  4595.7  517.02  4605.6  518.32  4610.6  516.79  4635.7  519.92  4665.7  520.42
  4725.8  519.35  4762.4  515.71  4762.9  514.91  4769.1  515.71  4785.8  519.26
  4844.1  519.96  4925.8  518.90  4965.8  520.18  4995.8  517.52  5005.8  519.64
  5035.8  520.46  5147.3  519.04  5172.6  518.48  5216.5  520.83  5589.1  529.19
#Mann=6,-1,0
  3429.1    0.05       0  3697.9     0.1       0  4762.4    0.07       0
  4769.1     0.1       0  4844.1    0.12       0  5147.3     0.1       0
Bank Sta=4762.4,4769.1
Exp/Cntr=0.3,0.1

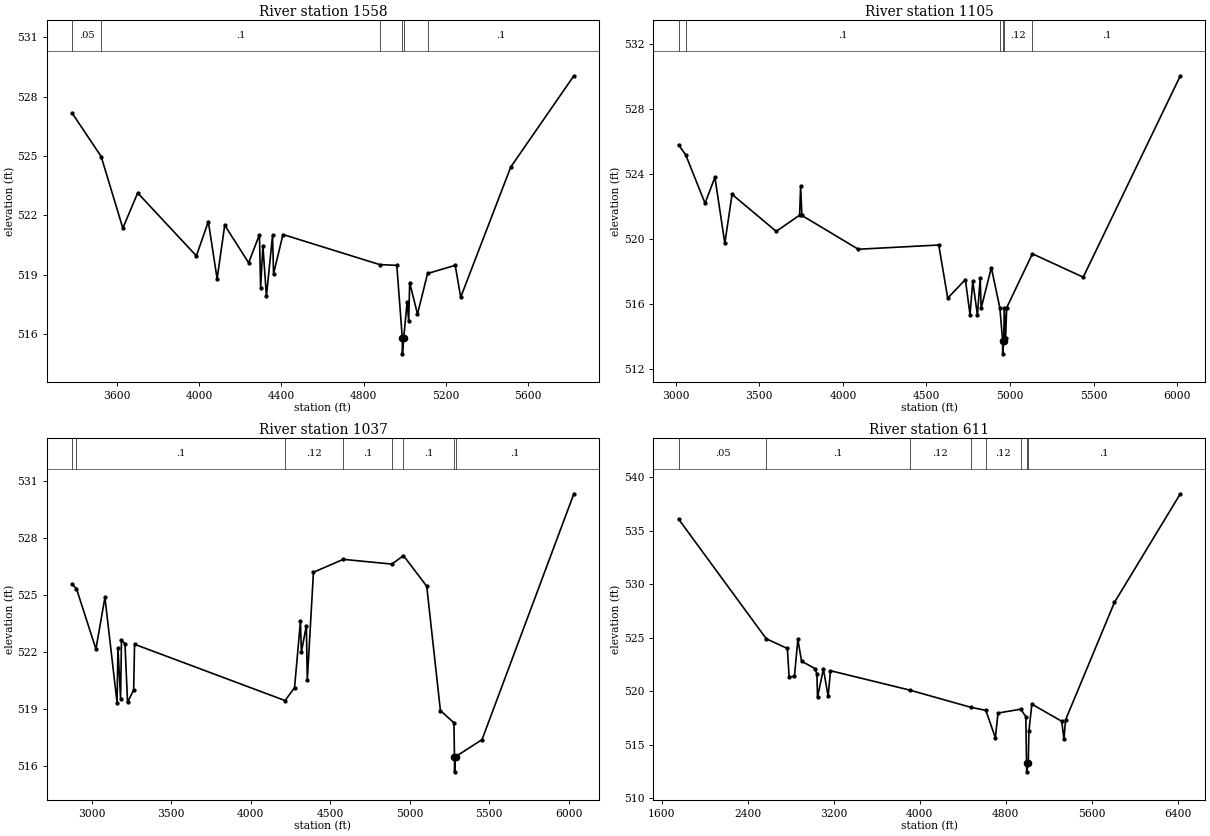
Type RM Length L Ch R = 1,1558,453,453,453
BEGIN DESCRIPTION:
Mapping XS 2d7b1d88
END DESCRIPTION:
XS GIS Cut Line= 4
      2002823.23     13530846.03      2002344.05     13530054.35
      2001416.97     13530153.31      2000944.31     13530490.92
#Sta/Elev= 30
  3383.3  527.17  3524.7  524.97  3630.0  521.35  3702.2  523.13  3987.4  519.95
  4045.5  521.68  4088.2  518.79  4125.1  521.50  4241.5  519.60  4293.8  521.02
  4299.7  518.34  4310.7  520.45  4327.9  517.92  4357.5  520.98  4362.5  519.05
  4408.3  521.03  4878.3  519.51  4961.4  519.47  4988.2  515.80  4988.7  515.00
  4995.0  515.80  5011.7  517.63  5019.1  516.64  5024.1  518.59  5062.0  517.01
  5111.0  519.06  5245.3  519.47  5272.0  517.86  5515.3  524.44  5821.9  529.05
#Mann=6,-1,0
  3383.3    0.05       0  3524.7     0.1       0  4878.3    0.12       0
  4988.2    0.07       0  4995.0    0.12       0  5111.0     0.1       0
Bank Sta=4988.2,4995
Exp/Cntr=0.3,0.1

Type RM Length L Ch R = 1,1105,68,68,68
BEGIN DESCRIPTION:
Mapping XS 41f5ce42
END DESCRIPTION:
XS GIS Cut Line= 6
      2002818.02     13530767.92      2002104.47     13529569.98
      2001849.26     13529590.81      2001646.13     13529694.98
      2001557.59     13529872.06      2000870.64     13530470.54
#Sta/Elev= 30
  3016.4  525.82  3059.4  525.20  3174.9  522.22  3234.1  523.82  3293.3  519.76
  3336.7  522.77  3600.9  520.49  3741.0  521.49  3746.7  523.27  3754.8  521.47
  4091.8  519.39  4573.3  519.65  4627.0  516.38  4732.5  517.52  4760.3  515.37
  4776.9  517.42  4804.7  515.33  4821.3  517.61  4826.9  515.75  4887.9  518.26
  4939.0  515.77  4955.5  513.75  4956.0  512.95  4962.3  513.75  4965.3  515.78
  4973.3  513.90  4979.7  515.79  5133.6  519.11  5437.7  517.67  6018.7  530.07
#Mann=6,-1,0
  3016.4    0.05       0  3059.4     0.1       0  4939.0    0.12       0
  4955.5    0.07       0  4962.3    0.12       0  5133.6     0.1       0
Bank Sta=4955.5,4962.3
Exp/Cntr=0.3,0.1

Type RM Length L Ch R = 1,1037,426,426,426
BEGIN DESCRIPTION:
Mapping XS 560617d8
END DESCRIPTION:
XS GIS Cut Line= 6
      2002833.64     13530757.49      2002187.80     13529538.73
      2002099.26     13529486.64      2001864.88     13529507.48
      2001557.59     13529684.56      2000818.98     13530464.89
#Sta/Elev= 30
  2877.4  525.58  2904.8  525.35  3027.3  522.16  3083.9  524.88  3160.2  519.33
  3165.8  522.22  3182.2  519.54  3187.8  522.61  3209.8  522.45  3226.1  519.35
  3264.5  520.00  3270.1  522.41  4216.0  519.44  4275.6  520.12  4312.8  523.63
  4318.6  522.00  4349.9  523.40  4355.7  520.50  4394.4  526.21  4581.9  526.89
  4887.6  526.64  4960.1  527.09  5106.4  525.47  5192.3  518.91  5277.2  518.27
  5280.7  516.48  5281.2  515.68  5287.6  516.48  5454.0  517.38  6031.0  530.35
#Mann=8,-1,0
  2877.4    0.05       0  2904.8     0.1       0  4216.0    0.12       0
  4581.9     0.1       0  4887.6    0.12       0  4960.1     0.1       0
  5280.7    0.07       0  5287.6     0.1       0
Bank Sta=5280.7,5287.6
Exp/Cntr=0.3,0.1

Type RM Length L Ch R = 1,611,0,0,0
BEGIN DESCRIPTION:
UNT 016 in HW 1.0
END DESCRIPTION:
XS GIS Cut Line= 5
      2003302.40     13531465.84      2002344.05     13529653.31
      2002062.80     13529403.31      2001406.55     13529601.23
      2000422.21     13530804.31
#Sta/Elev= 30
  1756.2  536.11  2571.8  524.91  2768.2  524.00  2784.6  521.34  2834.2  521.39
  2865.7  524.85  2900.3  522.81  3026.7  522.11  3043.0  521.59  3048.7  519.44
  3103.3  522.08  3147.4  519.53  3169.4  521.92  3905.0  520.11  4473.5  518.50
  4613.7  518.21  4702.7  515.65  4727.2  517.96  4938.0  518.32  4986.0  517.63
  4992.2  513.26  4994.0  512.46  5008.5  513.26  5014.7  516.27  5042.0  518.79
  5319.8  517.19  5340.6  515.51  5355.0  517.31  5810.1  528.31  6422.7  538.47
#Mann=8,-1,0
  1756.2    0.05       0  2571.8     0.1       0  3905.0    0.12       0
  4473.5     0.1       0  4613.7    0.12       0  4938.0     0.1       0
  4992.2    0.07       0  5008.5     0.1       0
Bank Sta=4992.2,5008.5
Exp/Cntr=0.3,0.1

Chan Stop Cuts=-1