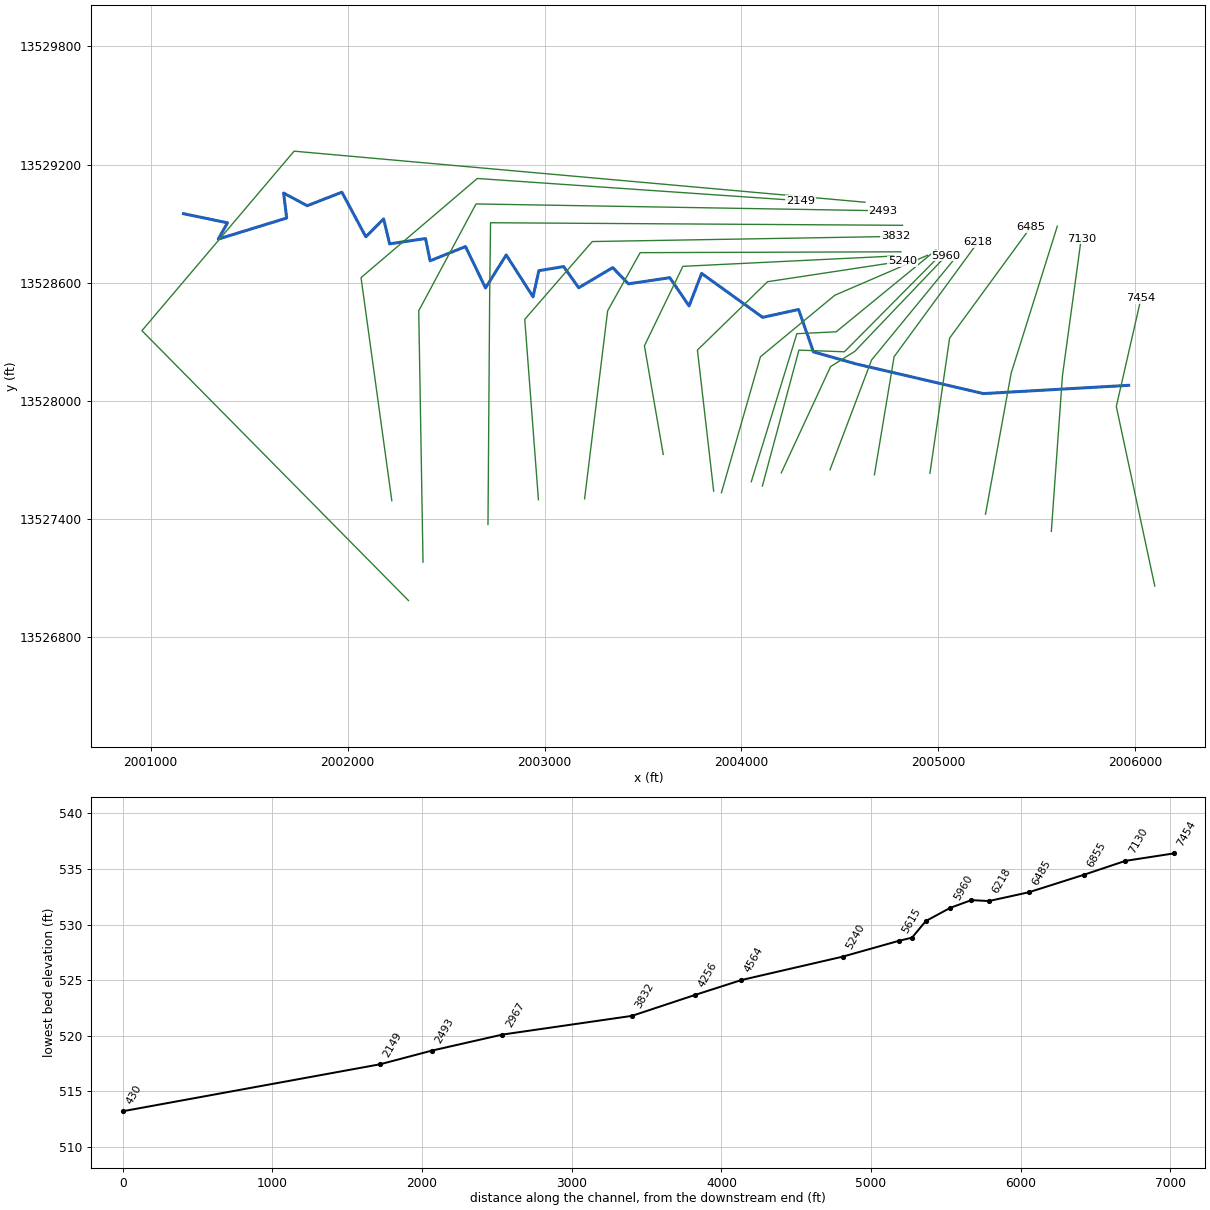
--- UNT 017 in HW.prj (project) ---

Proj Title=UNT 017 in HW Base Level Engineering
Current Plan=p01
Default Exp/Contr=0.3,0.1
English Units
Geom File=g01
Flow File=f01
Plan File=p01
Y Axis Title=Elevation
X Axis Title(PF)=Main Channel Distance
X Axis Title(XS)=Station
BEGIN DESCRIPTION:
UNT 017 in HW
END DESCRIPTION:
DSS Export Rating Curves= 0
DSS Export Rating Curve Sorted= 0
DSS Export Volume Flow Curves= 0
DXF OffsetX= 0
DXF OffsetY= 0
DXF ScaleX= 1
DXF ScaleY= 10

--- UNT 017 in HW.p01 (plan) ---

Plan Title=Multiple Run
Short Identifier=Multiple
Geom File=g01
Flow File=f01
Subcritical Flow
K Sum by GR= 0
Std Step Tol= 0.01
Critical Tol= 0.01
Num of Std Step Trials= 20
Max Error Tol= 0.3
Flow Tol Ratio= 0.001
Split Flow NTrial= 30
Split Flow Tol= 0.02
Split Flow Ratio= 0.02
Log Output Level= 0
Friction Slope Method= 1
Unsteady Friction Slope Method= 2
Unsteady Bridges Friction Slope Method= 1
Parabolic Critical Depth
Global Vel Dist=  1 , 1 , 1
Global Log Level= 0
CheckData=True
Encroach Param= -1, 0, 0, 0
BEGIN DESCRIPTION:
Multiple Run
END DESCRIPTION:

--- UNT 017 in HW.f01 (steady flow) ---

Flow Title=Multiple
Number of Profiles=7
Profile Names=10-year,25-year,50-year,1pct_min,100-year,1pct_plu,500-year
River Rch & RM= UNT 017 in HW,Reach-1,7454
     163     220     266     161     320     639     472
River Rch & RM= UNT 017 in HW,Reach-1,7130
     181     245     296     179     357     713     527
Boundary for River Rch & Prof#=UNT 017 in HW,Reach-1,1
Up Type=0
Dn Type=3
Dn Slope=0.005
Boundary for River Rch & Prof#=UNT 017 in HW,Reach-1,2
Up Type=0
Dn Type=3
Dn Slope=0.005
Boundary for River Rch & Prof#=UNT 017 in HW,Reach-1,3
Up Type=0
Dn Type=3
Dn Slope=0.005
Boundary for River Rch & Prof#=UNT 017 in HW,Reach-1,4
Up Type=0
Dn Type=3
Dn Slope=0.005
Boundary for River Rch & Prof#=UNT 017 in HW,Reach-1,5
Up Type=0
Dn Type=3
Dn Slope=0.005
Boundary for River Rch & Prof#=UNT 017 in HW,Reach-1,6
Up Type=0
Dn Type=3
Dn Slope=0.005
Boundary for River Rch & Prof#=UNT 017 in HW,Reach-1,7
Up Type=0
Dn Type=3
Dn Slope=0.005

--- UNT 017 in HW.g01 (geometry) ---

Geom Title=Existing Conditions
Program Version=5.05

River Reach=UNT 017 in HW   ,Reach-1
Reach XY= 30
       2005965.8     13528079.54      2005228.24     13528037.49
      2004580.67     13528188.53      2004365.39      13528249.3
      2004289.87     13528464.58      2004107.58     13528424.65
      2003797.68     13528647.74        2003734.     13528482.41
      2003636.22     13528626.03      2003426.15     13528594.78
      2003346.29     13528677.25      2003173.55     13528574.82
      2003097.16     13528682.46      2002971.29     13528661.62
      2002941.78     13528528.81      2002805.49     13528741.49
      2002700.46     13528573.95       2002598.9     13528784.02
      2002419.21     13528711.97      2002395.77     13528824.82
      2002213.48     13528797.91       2002183.1     13528924.65
      2002092.82      13528833.5      2001971.29     13529060.06
      2001795.08     13528991.49      2001675.29     13529055.72
      2001690.91     13528928.99      2001343.69     13528822.22
      2001390.56     13528904.68      2001167.24     13528950.98

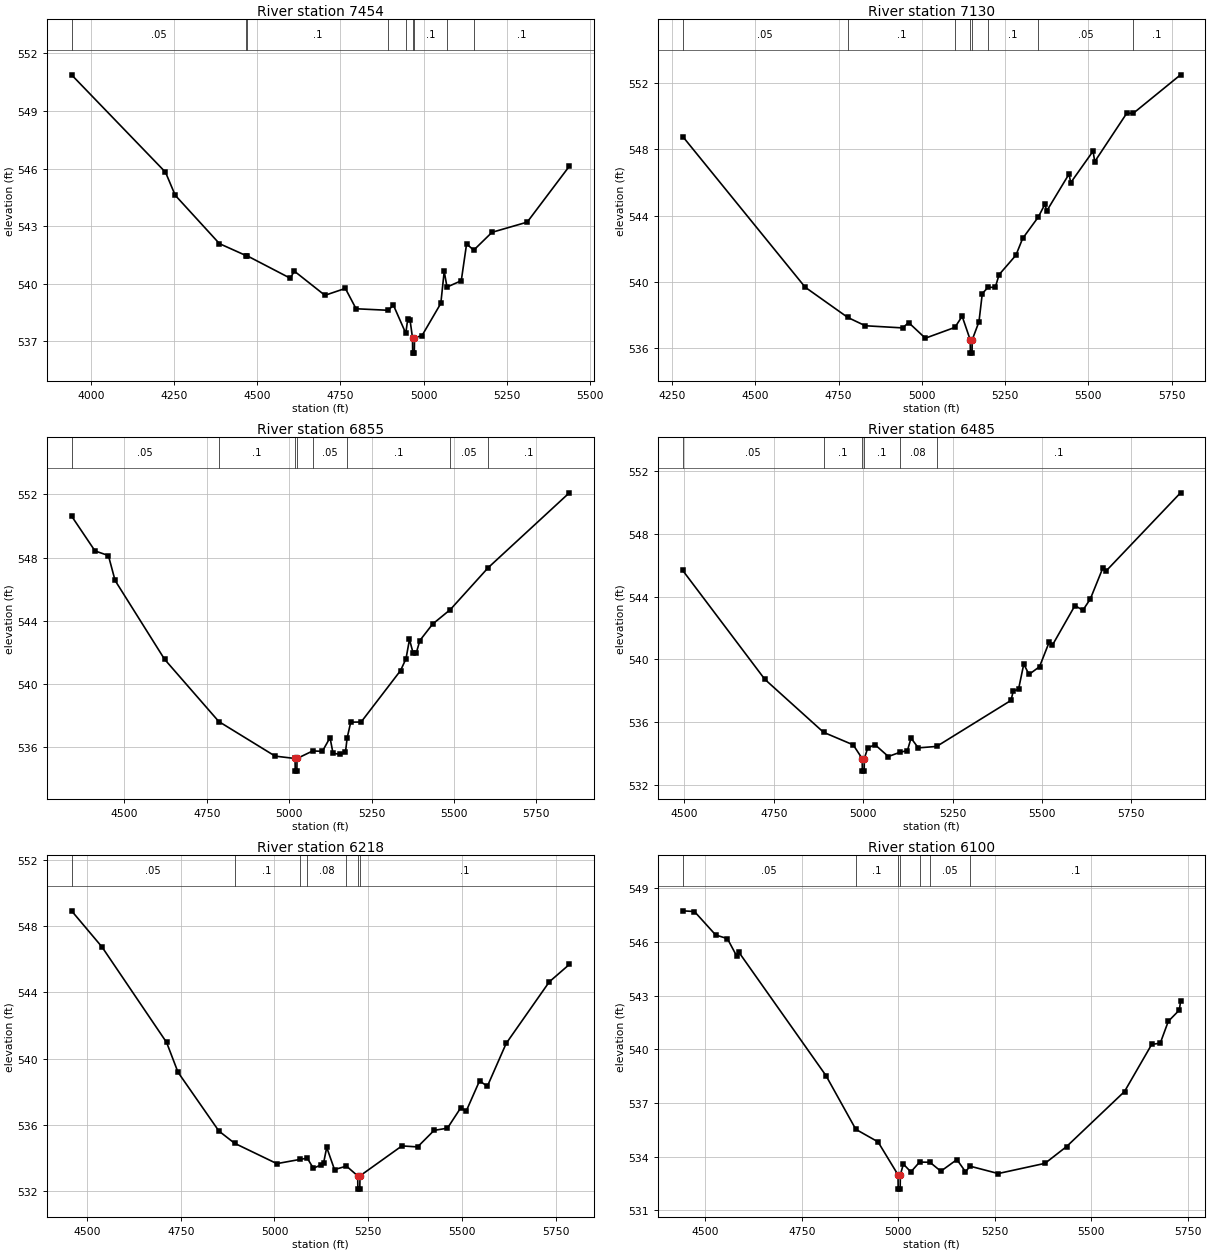
Type RM Length L Ch R = 1 ,7454    ,324,324,324
BEGIN DESCRIPTION:
UNT 017 in HW 5.0
END DESCRIPTION:
XS GIS Cut Line= 3
       2006098.4     13527060.39      2005903.08     13527971.89
      2006028.59     13528521.55
#Sta/Elev= 30
    3942  550.88  4224.3  545.81  4253.5  544.61  4386.5  542.09  4466.2  541.47
  4469.4  541.46  4599.3  540.29  4611.5  540.66  4703.5   539.4  4764.9  539.76
  4797.1   538.7  4893.9  538.62  4909.3  538.89  4946.6  537.42  4952.3  538.16
  4959.4   538.1  4966.7  537.19  4967.2  536.39  4972.2  536.39  4972.7  537.19
  4995.2   537.3  5051.8  538.98    5062  540.65  5070.4  539.83  5113.3  540.16
  5129.3  542.08  5150.6  541.75  5205.6  542.68  5311.4  543.21    5438  546.12
#Mann= 9 ,-1 , 0
    3942     .05       0  4466.2     .12       0  4469.4      .1       0
  4893.9     .07       0  4946.6      .1       0  4966.7     .07       0
  4972.7      .1       0  5070.4     .05       0  5150.6      .1       0
Bank Sta=4966.7,4972.7
XS Rating Curve= 0 ,0
Exp/Cntr=0.3,0.1

Type RM Length L Ch R = 1 ,7130    ,275,275,275
BEGIN DESCRIPTION:
UNT 017 in HW 4.0
END DESCRIPTION:
XS GIS Cut Line= 3
      2005573.21     13527338.16      2005629.64     13528128.14
      2005724.99     13528824.96
#Sta/Elev= 30
  4281.8  548.77  4649.6  539.69  4777.5  537.87    4830  537.37  4941.9  537.24
  4960.4  537.56  5010.5  536.62  5099.2  537.27  5121.1  537.94  5145.3  536.52
  5145.8  535.72  5150.8  535.72  5151.3  536.52  5171.6  537.61  5181.6  539.31
  5199.1  539.69  5220.5  539.68  5232.1  540.45  5282.6  541.62  5302.8  542.63
  5349.8  543.92  5369.9   544.7    5375  544.28  5442.1  546.51  5447.2  545.99
  5514.3  547.89  5519.4  547.26  5615.7  550.18    5635  550.17  5777.1  552.49
#Mann= 8 ,-1 , 0
  4281.8     .05       0  4777.5      .1       0  5099.2     .05       0
  5145.3     .07       0  5151.3     .05       0  5199.1      .1       0
  5349.8     .05       0    5635      .1       0
Bank Sta=5145.3,5151.3
XS Rating Curve= 0 ,0
Exp/Cntr=0.3,0.1

Type RM Length L Ch R = 1 ,6855    ,370,370,370
BEGIN DESCRIPTION:
UNT 017 in HW 3.0
END DESCRIPTION:
XS GIS Cut Line= 3
      2005239.01     13527424.99      2005369.22     13528141.16
      2005603.61     13528887.72
#Sta/Elev= 30
  4339.8  550.63    4411  548.42  4451.6  548.13  4471.9  546.55  4622.1  541.56
  4786.6  537.62  4957.5  535.43    5018  535.28  5018.5  534.48  5023.5  534.48
    5024  535.28  5071.8  535.76  5100.8  535.73  5124.1   536.6  5133.2  535.61
  5155.6  535.54  5170.9  535.67  5176.1  536.59    5187  537.58  5218.5  537.59
  5338.2  540.85  5354.7   541.6  5365.2  542.82  5375.9  541.98  5386.2  541.99
  5396.7  542.75  5435.4  543.79  5489.2  544.71    5604  547.36  5850.2   552.1
#Mann= 8 ,-1 , 0
  4339.8     .05       0  4786.6      .1       0    5018     .07       0
    5024      .1       0  5071.8     .05       0  5176.1      .1       0
  5489.2     .05       0    5604      .1       0
Bank Sta=5018,5024
XS Rating Curve= 0 ,0
Exp/Cntr=0.3,0.1

Type RM Length L Ch R = 1 ,6485    ,267,267,267
BEGIN DESCRIPTION:
Mapping XS b8b26077
END DESCRIPTION:
XS GIS Cut Line= 3
       2004956.9     13527633.36      2005056.72     13528319.11
      2005469.04     13528883.33
#Sta/Elev= 30
  4495.7  545.66  4725.1  538.74  4889.3  535.37  4972.3  534.57  4997.3   533.7
  4997.8   532.9  5002.9   532.9  5003.4   533.7  5012.7  534.36  5032.9  534.59
  5070.4  533.83    5102  534.09  5123.9  534.21    5134     535  5154.2  534.38
  5205.5  534.47  5413.6   537.4  5419.8     538  5434.5   538.1  5449.2  539.71
  5463.8  539.05  5493.2  539.54  5520.2   541.1  5528.7  540.89  5592.3  543.43
  5614.4  543.13  5635.3  543.85  5670.8  545.85    5679  545.62  5887.5   550.6
#Mann= 6 ,-1 , 0
  4495.7     .05       0  4889.3      .1       0  4997.3     .07       0
  5003.4      .1       0    5102     .08       0  5205.5      .1       0
Bank Sta=4997.3,5003.4
XS Rating Curve= 0 ,0
Exp/Cntr=0.3,0.1

Type RM Length L Ch R = 1 ,6218    ,118,118,118
BEGIN DESCRIPTION:
UNT 017 in HW 2.0
END DESCRIPTION:
XS GIS Cut Line= 3
        2004675.     13527624.99        2004775.       13528225.
      2005199.96     13528805.24
#Sta/Elev= 30
  4458.9  548.92    4540  546.74  4712.4  540.97  4742.8  539.17  4851.8  535.62
  4893.7  534.88  5006.4  533.65  5067.1   533.9  5087.5  533.98  5103.8  533.37
  5124.7  533.58  5130.9  533.67  5139.4  534.63  5160.2  533.29  5192.1   533.5
    5222  532.91  5222.5  532.11  5227.6  532.11  5228.1  532.91  5339.9  534.72
  5381.8  534.66  5425.8  535.66  5461.3  535.79  5496.8  537.02  5511.4  536.82
    5547  538.65  5567.8  538.32    5618  540.91    5733  544.63  5786.4  545.68
#Mann= 7 ,-1 , 0
  4458.9     .05       0  4893.7      .1       0  5067.1     .05       0
  5087.5     .08       0  5192.1      .1       0    5222     .07       0
  5228.1      .1       0
Bank Sta=5222,5228.1
XS Rating Curve= 0 ,0
Exp/Cntr=0.3,0.1

Type RM Length L Ch R = 1 ,6100    ,140,140,140
BEGIN DESCRIPTION:
Mapping XS d3bf1b80
END DESCRIPTION:
XS GIS Cut Line= 3
      2004449.58     13527650.79      2004660.51     13528208.08
      2005100.33     13528744.18
#Sta/Elev= 30
  4441.8  547.73  4472.1  547.69  4527.1  546.38  4557.3  546.18  4582.1  545.18
  4587.4  545.41  4812.7  538.53    4890  535.53  4947.5  534.83  4999.3  532.99
  4999.8  532.19  5004.9  532.19  5005.4  532.99  5013.2  533.59  5032.6  533.15
  5055.2   533.7    5082  533.69  5110.3  533.19  5151.9  533.84  5174.1  533.16
  5186.1  533.47  5258.8  533.06  5380.1  533.63  5436.1  534.57    5586  537.64
  5656.4  540.27  5678.6  540.34  5699.4  541.56  5728.1  542.19  5731.1  542.67
#Mann= 7 ,-1 , 0
  4441.8     .05       0    4890      .1       0  4999.3     .07       0
  5005.4      .1       0  5055.2     .08       0    5082     .05       0
  5186.1      .1       0
Bank Sta=4999.3,5005.4
XS Rating Curve= 0 ,0
Exp/Cntr=0.3,0.1

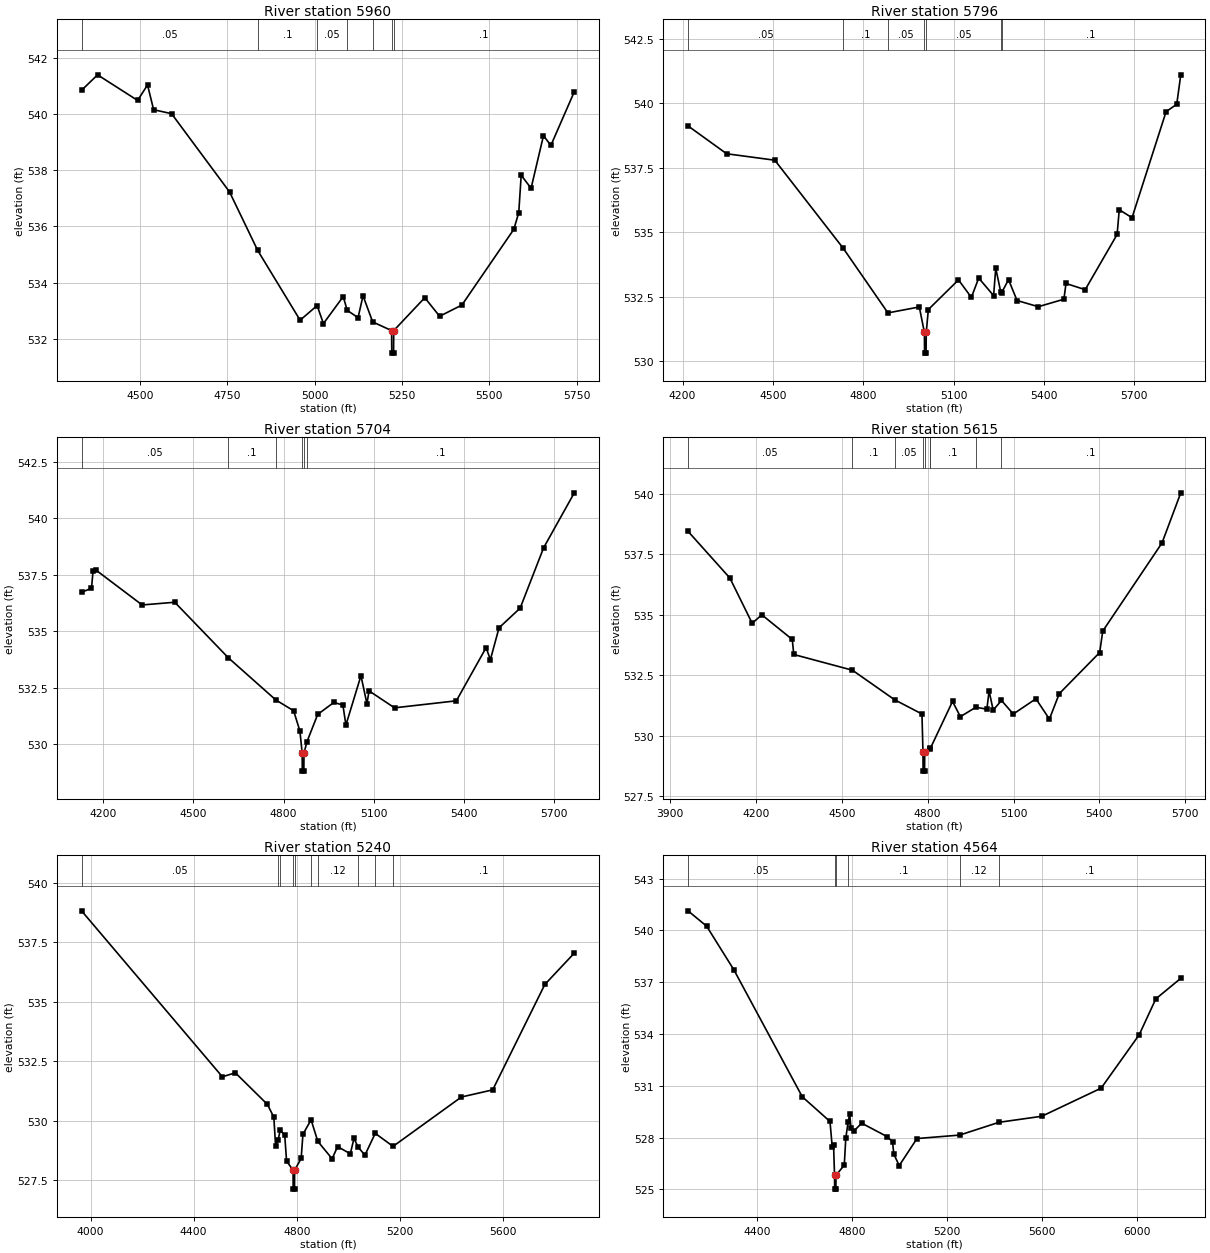
Type RM Length L Ch R = 1 ,5960    ,164,164,164
BEGIN DESCRIPTION:
Mapping XS ec6e4916
END DESCRIPTION:
XS GIS Cut Line= 4
       2004202.2      13527635.2      2004452.18     13528174.22
      2004576.12      13528252.5       2005038.1     13528736.71
#Sta/Elev= 30
  4333.1  540.84  4378.9  541.39  4493.5  540.48  4521.9  541.03  4539.3  540.15
  4590.6  540.01  4756.5  537.23  4837.1  535.15  4958.5  532.67  5007.2  533.19
  5025.2  532.55  5081.8  533.51  5093.3  533.02  5124.3  532.76  5138.5  533.54
  5166.1  532.61  5220.3   532.3  5220.8   531.5  5225.9   531.5  5226.4   532.3
  5315.2  533.47  5357.7  532.81  5421.5  533.21    5570   535.9  5584.1  536.49
  5591.1  537.82  5619.4  537.36  5654.9  539.23    5676  538.88  5743.1  540.79
#Mann= 7 ,-1 , 0
  4333.1     .05       0  4837.1      .1       0  5007.2     .05       0
  5093.3     .08       0  5166.1      .1       0  5220.3     .07       0
  5226.4      .1       0
Bank Sta=5220.3,5226.4
XS Rating Curve= 0 ,0
Exp/Cntr=0.3,0.1

Type RM Length L Ch R = 1 ,5796    ,92,92,92
BEGIN DESCRIPTION:
Mapping XS 1c4aade6
END DESCRIPTION:
XS GIS Cut Line= 4
       2004106.2     13527568.23      2004291.54     13528258.24
      2004522.49     13528249.74      2005008.89     13528740.03
#Sta/Elev= 30
  4218.1  539.12  4346.3  538.04  4506.2  537.79  4733.2  534.38  4881.9  531.87
  4986.1   532.1    5003  531.11  5003.5  530.31  5008.6  530.31  5009.1  531.11
  5016.1     532  5116.2  533.15    5159  532.47  5183.3  533.22  5232.8  532.54
  5239.9   533.6  5256.7  532.67  5259.4  532.65  5282.3  533.16  5310.6  532.35
  5381.3  532.11  5466.2   532.4  5473.2  533.01  5536.9  532.77  5642.9  534.91
    5650  535.87  5692.4  535.56  5805.5  539.67  5840.9  539.96  5854.3   541.1
#Mann= 7 ,-1 , 0
  4218.1     .05       0  4733.2      .1       0  4881.9     .05       0
    5003     .04       0  5009.1     .05       0  5256.7     .08       0
  5259.4      .1       0
Bank Sta=5003,5009.1
XS Rating Curve= 0 ,0
Exp/Cntr=0.3,0.1

Type RM Length L Ch R = 1 ,5704    ,89,89,89
BEGIN DESCRIPTION:
Mapping XS 3ce37c3c
END DESCRIPTION:
XS GIS Cut Line= 4
      2004049.77     13527589.91      2004281.12     13528341.58
      2004480.83     13528351.31       2004987.3     13528766.17
#Sta/Elev= 30
  4127.2  536.73  4160.3  536.91  4165.6  537.69  4174.4  537.72    4329  536.17
  4437.6  536.29  4616.3  533.83    4774  531.97  4833.5  531.49  4854.5  530.59
  4861.9  529.62  4862.4  528.82  4867.5  528.82    4868  529.62  4878.2  530.13
  4913.7  531.33  4967.6  531.86  4997.6  531.74  5007.7  530.86  5057.7  533.04
  5077.7   531.8  5084.7  532.37  5169.5  531.62  5375.4  531.93  5474.5  534.28
  5488.8  533.75  5517.6  535.16  5587.9  536.03  5666.1   538.7  5768.3  541.13
#Mann= 6 ,-1 , 0
  4127.2     .05       0  4616.3      .1       0    4774     .05       0
  4861.9     .07       0    4868     .05       0  4878.2      .1       0
Bank Sta=4861.9,4868
XS Rating Curve= 0 ,0
Exp/Cntr=0.3,0.1

Type RM Length L Ch R = 1 ,5615    ,375,375,375
BEGIN DESCRIPTION:
Mapping XS 08142510
END DESCRIPTION:
XS GIS Cut Line= 4
      2003898.32      13527534.3      2004096.23     13528224.39
      2004473.83     13528536.89      2004945.18     13528740.01
#Sta/Elev= 30
  3962.9  538.44  4109.1  536.51    4187  534.64  4220.7  534.99  4327.1  533.97
  4332.3  533.35  4537.2   532.7  4684.5  531.48  4780.1  530.89  4783.6  529.33
  4784.1  528.53  4789.2  528.53  4789.7  529.33  4807.6  529.47    4809  529.46
  4886.9  531.41  4914.3  530.78  4968.3  531.17  5006.8  531.09  5014.6  531.84
  5028.9  531.05  5057.8  531.45  5099.2  530.89  5178.2  531.52  5225.3  530.68
  5259.7  531.73  5400.8  533.43  5411.8  534.32  5618.7  537.96  5684.2  540.03
#Mann= 9 ,-1 , 0
  3962.9     .05       0  4537.2      .1       0  4684.5     .05       0
  4783.6     .07       0  4789.7     .05       0  4807.6     .08       0
    4809      .1       0  4968.3     .12       0  5057.8      .1       0
Bank Sta=4783.6,4789.7
XS Rating Curve= 0 ,0
Exp/Cntr=0.3,0.1

Type RM Length L Ch R = 1 ,5240    ,676,676,676
BEGIN DESCRIPTION:
Mapping XS 5f0e7d4b
END DESCRIPTION:
XS GIS Cut Line= 4
      2003858.81     13527542.17      2003776.34     13528258.35
      2004132.25     13528605.57      2004818.05     13528709.74
#Sta/Elev= 30
  3965.1  538.83  4511.5  531.84  4561.7  532.01    4686  530.68  4711.1  530.14
    4718  528.92  4727.9  529.19    4736   529.6  4753.5  529.37  4760.5  528.29
  4785.7  527.91  4786.2  527.11  4791.3  527.11  4791.8  527.91  4817.1   528.4
    4824  529.42  4855.6  530.03  4881.8  529.12  4937.2  528.39  4958.5   528.9
  5007.9   528.6  5022.1  529.25    5038  528.88  5064.5  528.54  5104.5  529.46
  5173.6  528.91  5438.9  530.99  5560.3  531.29  5762.6  535.73  5876.9  537.05
#Mann= 10 ,-1 , 0
  3965.1     .05       0  4727.9      .1       0    4736     .05       0
  4785.7     .07       0  4791.8     .05       0  4855.6     .08       0
  4881.8     .12       0    5038      .1       0  5104.5     .12       0
  5173.6      .1       0
Bank Sta=4785.7,4791.8
XS Rating Curve= 0 ,0
Exp/Cntr=0.3,0.1

Type RM Length L Ch R = 1 ,4564    ,308,308,308
BEGIN DESCRIPTION:
Mapping XS dd7291d1
END DESCRIPTION:
XS GIS Cut Line= 4
      2003602.74     13527728.79      2003507.25     13528280.05
      2003702.56     13528683.69       2004770.1     13528735.77
#Sta/Elev= 30
  4108.4  541.13  4186.9  540.24  4301.3  537.72  4589.9  530.36  4706.7  528.93
  4716.2  527.45  4721.7  527.59  4725.9  525.81  4726.4  525.01  4731.5  525.01
    4732  525.81  4766.9   526.4  4773.4  527.98  4783.1  528.89  4789.5  529.37
  4795.6  528.53  4806.5  528.36  4840.2  528.83  4947.6  528.05  4970.2  527.76
  4975.8  527.04  4998.4  526.37  5073.3  527.94    5253  528.14  5418.8  528.88
  5599.3  529.23  5849.6  530.86  6009.8  533.95  6079.9  536.03  6185.1  537.22
#Mann= 6 ,-1 , 0
  4108.4     .05       0  4725.9     .07       0    4732     .05       0
  4783.1      .1       0    5253     .12       0  5418.8      .1       0
Bank Sta=4725.9,4732
XS Rating Curve= 0 ,0
Exp/Cntr=0.3,0.1

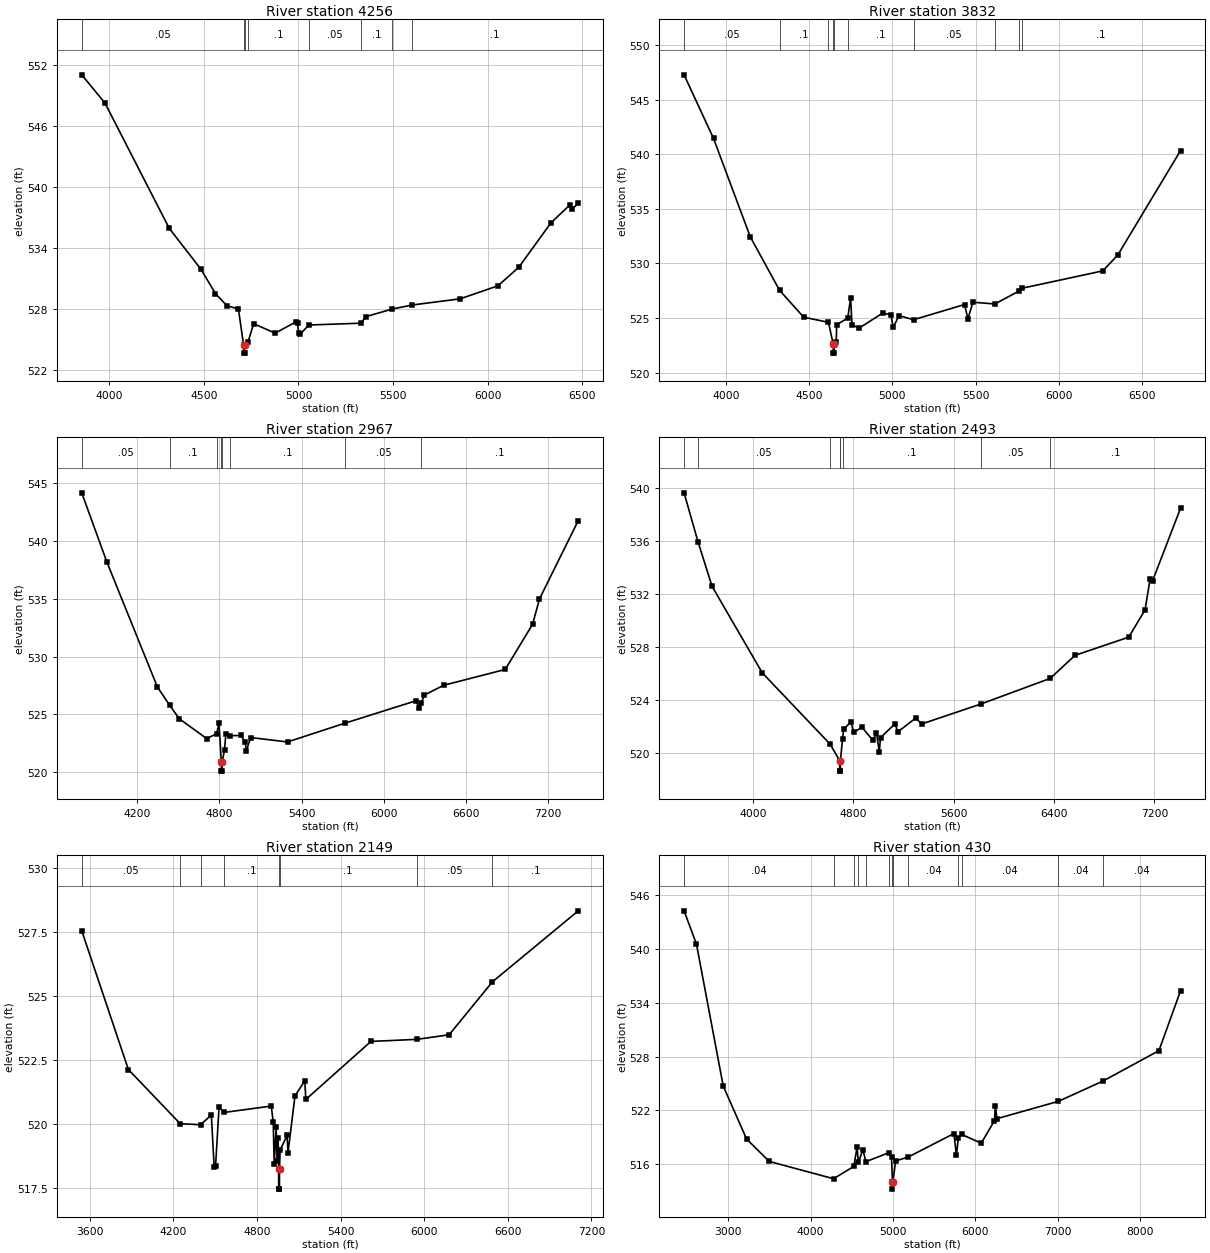
Type RM Length L Ch R = 1 ,4256    ,424,424,424
BEGIN DESCRIPTION:
Mapping XS e53c298b
END DESCRIPTION:
XS GIS Cut Line= 4
      2003203.43     13527503.15      2003320.61       13528458.
      2003485.54     13528753.14      2004809.33     13528757.48
#Sta/Elev= 30
  3854.8     551  3977.6  548.23  4317.2  535.93  4484.9  531.91  4561.2  529.53
  4622.4  528.33  4682.8  528.02    4710  524.48  4710.5  523.68  4715.6  523.68
  4716.1  524.48  4734.2  524.82  4763.4  526.57  4876.7  525.64  4985.2  526.73
  4995.5  526.63  5001.2  525.64  5008.1  525.51  5054.6  526.44  5331.8  526.62
  5354.4  527.25    5496  528.01  5599.4   528.4  5854.4  529.01  6054.4  530.29
  6164.4  532.11  6334.4  536.47  6434.4  538.23  6444.4  537.79  6478.7  538.38
#Mann= 8 ,-1 , 0
  3854.8     .05       0    4710     .07       0  4716.1     .05       0
  4734.2      .1       0  5054.6     .05       0  5331.8      .1       0
    5496     .12       0  5599.4      .1       0
Bank Sta=4710,4716.1
XS Rating Curve= 0 ,0
Exp/Cntr=0.3,0.1

Type RM Length L Ch R = 1 ,3832    ,865,865,865
BEGIN DESCRIPTION:
Mapping XS 4f1e4490
END DESCRIPTION:
XS GIS Cut Line= 4
      2002969.05     13527498.83      2002899.61      13528414.6
      2003242.49     13528809.56      2004781.64     13528835.57
#Sta/Elev= 30
  3749.2  547.27  3925.9  541.45  4146.5  532.44  4322.5  527.54  4467.4  525.08
  4616.1  524.61  4644.8  522.59  4645.3  521.79  4650.5  521.79    4651  522.59
  4662.7   522.8  4665.3   524.4  4731.7  524.99  4749.3  526.88    4757  524.38
  4799.7  524.08  4941.2  525.45  4990.6  525.32  5004.8  524.15  5039.9  525.22
  5127.2  524.85  5433.2  526.24  5453.2  524.93  5483.2  526.45  5615.2  526.29
  5762.1  527.49  5775.5  527.72  6263.3  529.32  6353.3  530.78    6730  540.34
#Mann= 10 ,-1 , 0
  3749.2     .05       0  4322.5      .1       0  4616.1     .05       0
  4644.8     .07       0    4651     .05       0  4731.7      .1       0
  5127.2     .05       0  5615.2      .1       0  5762.1     .12       0
  5775.5      .1       0
Bank Sta=4644.8,4651
XS Rating Curve= 0 ,0
Exp/Cntr=0.3,0.1

Type RM Length L Ch R = 1 ,2967    ,474,474,474
BEGIN DESCRIPTION:
Mapping XS 7f68513a
END DESCRIPTION:
XS GIS Cut Line= 4
      2002712.97     13527372.97      2002721.65     13528549.14
        2002726.     13528905.05      2004818.01     13528892.03
#Sta/Elev= 30
  3795.1  544.14  3977.1  538.21  4347.1  527.38  4436.2  525.81  4507.2  524.63
  4707.2  522.92  4779.6  523.34  4797.2  524.23  4814.1  520.91  4814.6  520.11
  4819.8  520.11  4820.3  520.91  4837.2  521.93  4847.2  523.35  4878.3  523.17
  4957.2  523.19  4987.2  522.62  4997.2  521.86  5027.2  523.01  5297.2  522.63
  5718.8  524.26  6236.3  526.19  6256.3  525.56  6274.2  526.03  6296.3  526.68
  6436.3  527.52  6886.3  528.89  7086.3   532.8  7136.3  534.98  7419.3  541.74
#Mann= 8 ,-1 , 0
  3795.1     .05       0  4436.2      .1       0  4779.6     .05       0
  4814.1     .07       0  4820.3     .05       0  4878.3      .1       0
  5718.8     .05       0  6274.2      .1       0
Bank Sta=4814.1,4820.3
XS Rating Curve= 0 ,0
Exp/Cntr=0.3,0.1

Type RM Length L Ch R = 1 ,2493    ,344,344,344
BEGIN DESCRIPTION:
Mapping XS 4be43645
END DESCRIPTION:
XS GIS Cut Line= 4
      2002383.11     13527181.92      2002361.41       13528458.
      2002652.21     13529000.53       2004718.2     13528965.81
#Sta/Elev= 30
    3451  539.64  3562.4  535.94  3674.1  532.59  4074.2  526.07  4615.5  520.69
  4691.2  519.46  4691.7  518.66  4696.9  518.66  4697.4  519.46  4714.1  521.09
  4723.3   521.8  4780.6  522.38  4803.3  521.59  4869.1  521.96  4956.8  520.98
  4984.8  521.56  5007.5  520.11  5016.9  521.19  5132.3  522.22    5155  521.62
  5296.3  522.65  5346.7  522.22  5820.3  523.73  6369.7  525.65  6567.7  527.39
  6995.8  528.76  7125.9  530.82  7165.9  533.15  7185.9  533.01  7409.1  538.49
#Mann= 8 ,-1 , 0
    3451      .1       0  3562.4     .05       0  4615.5     .08       0
  4691.2     .07       0  4697.4     .08       0  4714.1      .1       0
  5820.3     .05       0  6369.7      .1       0
Bank Sta=4691.2,4697.4
XS Rating Curve= 0 ,0
Exp/Cntr=0.3,0.1

Type RM Length L Ch R = 1 ,2149    ,1719,1719,1719
BEGIN DESCRIPTION:
Mapping XS fdb0fdf2
END DESCRIPTION:
XS GIS Cut Line= 4
       2002224.7     13527493.48      2002068.45      13528626.3
      2002658.73     13529129.77      2004299.37     13529016.92
#Sta/Elev= 30
  3542.1  527.55  3876.8  522.12  4248.9     520  4394.9  519.96  4472.3  520.34
  4492.5  518.32  4502.6  518.34  4527.9  520.66    4563  520.44  4902.5  520.69
  4916.8  520.05  4923.4  518.42  4937.7  519.88  4944.2  518.55  4951.9  519.46
  4955.4  518.24  4955.9  517.44  4961.1  517.44  4961.6  518.24  4966.2  518.97
  5015.6  519.54  5022.8  518.87  5072.7  521.09    5143  521.68  5150.7  520.95
  5618.1  523.22  5947.5   523.3  6179.4  523.48  6489.6  525.55    7106  528.33
#Mann= 8 ,-1 , 0
  3542.1     .05       0  4248.9      .1       0  4394.9     .05       0
    4563      .1       0  4955.4     .07       0  4961.6      .1       0
  5947.5     .05       0  6489.6      .1       0
Bank Sta=4955.4,4961.6
XS Rating Curve= 0 ,0
Exp/Cntr=0.3,0.1

Type RM Length L Ch R = 1 ,430     ,0,0,0
BEGIN DESCRIPTION:
UNT 017 in HW 1.0
END DESCRIPTION:
XS GIS Cut Line= 4
      2002309.32     13526986.65        2000956.     13528357.04
      2001728.57     13529268.49      2004627.07     13529009.21
#Sta/Elev= 30
  2462.8  544.27  2613.2  540.56  2938.4  524.72  3221.3  518.82  3497.1  516.31
  4278.7  514.38  4523.8  515.75  4564.1  517.88  4580.2   516.2  4635.2  517.63
  4670.5  516.28  4954.6   517.3  4982.6   516.8  4993.8  514.02  4994.3  513.22
    5000  514.02    5032  516.36  5187.1  516.81  5740.7  519.42  5770.8  516.99
  5794.8  518.94    5835  519.32    6072  518.34  6232.6  520.85  6243.9  522.55
  6262.8  521.08  7010.4  523.02  7549.8  525.27  8230.6  528.67  8493.7  535.36
#Mann= 13 ,-1 , 0
  2462.8     .04       0  4278.7     .04       0  4523.8     .04       0
  4580.2     .04       0  4670.5     .04       0  4954.6     .04       0
  4993.8     .02       0    5000     .04       0  5187.1     .04       0
  5794.8     .04       0    5835     .04       0  7010.4     .04       0
  7549.8     .04       0
Bank Sta=4993.8,5000
XS Rating Curve= 0 ,0
Exp/Cntr=0.3,0.1
LCMann Table=0

Chan Stop Cuts=-1
Use User Specified Reach Order=0
Composite Channel Slope=5