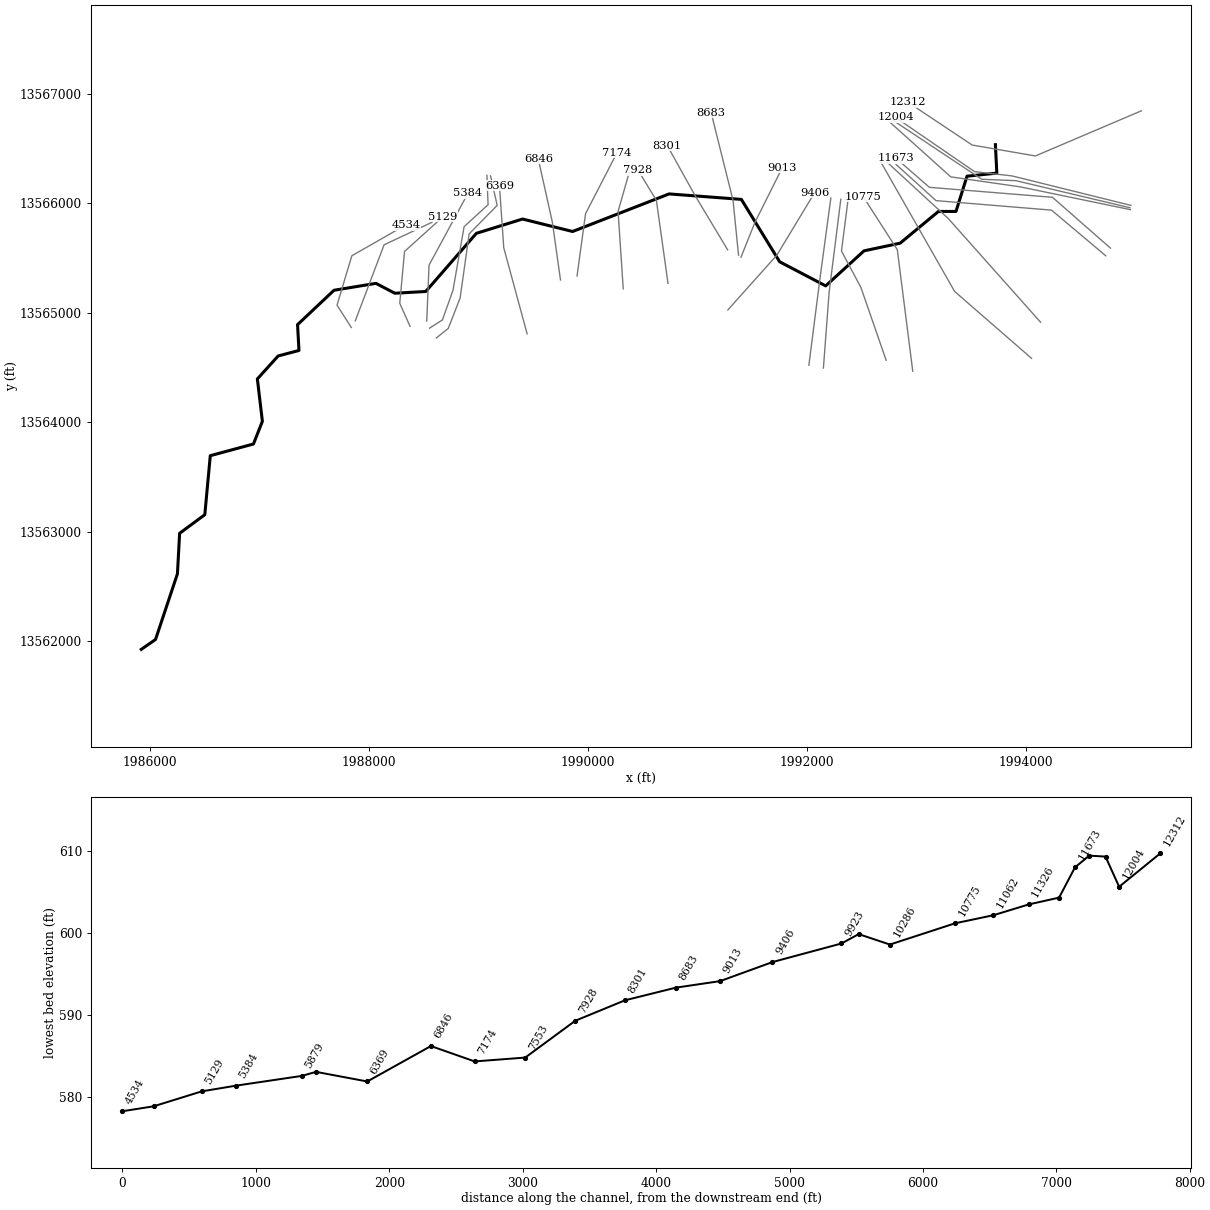
--- UNT 019 in HW.prj (project) ---

Proj Title=UNT 019 in HW Base Level Engineering
Current Plan=p01
Default Exp/Contr=0.3,0.1
English Units
Geom File=g01
Flow File=f01
Plan File=p01
BEGIN DESCRIPTION:
UNT 019 in HW
END DESCRIPTION:

--- UNT 019 in HW.p01 (plan) ---

Plan Title=Multiple Run
Short Identifier=Multiple
Geom File=g01
Flow File=f01
Subcritical Flow
K Sum by GR= 0
Std Step Tol= 0.01
Critical Tol= 0.01
Num of Std Step Trials= 20
Max Error Tol= 0.3
Flow Tol Ratio= 0.001
Split Flow NTrial= 30
Split Flow Tol= 0.02
Split Flow Ratio= 0.02
Log Output Level= 0
Friction Slope Method= 1
Unsteady Friction Slope Method= 2
Unsteady Bridges Friction Slope Method= 1
Parabolic Critical Depth
Global Vel Dist=  1 , 1 , 1
Global Log Level= 0
CheckData=True
Encroach Param= -1, 0, 0, 0
BEGIN DESCRIPTION:
Multiple Run
END DESCRIPTION:

--- UNT 019 in HW.f01 (steady flow) ---

Flow Title=Multiple
Number of Profiles=7
Profile Names=10-year,25-year,50-year,1pct_min,100-year,1pct_plu,500-year
River Rch & RM= UNT 019 in HW,Reach-1,12312
     436     607     749     458     913    1823    1365
River Rch & RM= UNT 019 in HW,Reach-1,12004
     865    1252    1583     990    1976    3942    3092
River Rch & RM= UNT 019 in HW,Reach-1,8301
    1099    1603    2037    1279    2552    5091    4023
Boundary for River Rch & Prof#=UNT 019 in HW,Reach-1,1
Up Type=0
Dn Type=3
Dn Slope=0.005
Boundary for River Rch & Prof#=UNT 019 in HW,Reach-1,2
Up Type=0
Dn Type=3
Dn Slope=0.005
Boundary for River Rch & Prof#=UNT 019 in HW,Reach-1,3
Up Type=0
Dn Type=3
Dn Slope=0.005
Boundary for River Rch & Prof#=UNT 019 in HW,Reach-1,4
Up Type=0
Dn Type=3
Dn Slope=0.005
Boundary for River Rch & Prof#=UNT 019 in HW,Reach-1,5
Up Type=0
Dn Type=3
Dn Slope=0.005
Boundary for River Rch & Prof#=UNT 019 in HW,Reach-1,6
Up Type=0
Dn Type=3
Dn Slope=0.005
Boundary for River Rch & Prof#=UNT 019 in HW,Reach-1,7
Up Type=0
Dn Type=3
Dn Slope=0.005

--- UNT 019 in HW.g01 (geometry) ---

Geom Title=Existing Conditions

River Reach=UNT 019 in HW,Reach-1
Reach XY= 30
      1993720.80     13566534.54      1993733.87     13566274.54
      1993461.53     13566246.21      1993360.80     13565924.54
      1993200.80     13565924.54      1992850.80     13565634.54
      1992520.80     13565564.54      1992170.80     13565244.54
      1991750.80     13565464.54      1991400.80     13566034.54
      1990740.80     13566084.54      1989859.55     13565741.23
      1989402.61     13565855.12      1988980.80     13565724.54
      1988518.58     13565193.31      1988235.94     13565177.34
      1988063.80     13565267.54      1987680.80     13565204.54
      1987347.75     13564890.54      1987360.80     13564654.54
      1987170.80     13564604.54      1986980.80     13564394.54
      1987026.65     13564007.46      1986945.06     13563800.17
      1986550.80     13563693.40      1986500.80     13563154.54
      1986270.80     13562984.54      1986250.80     13562614.54
      1986050.80     13562014.54      1985920.80     13561924.54

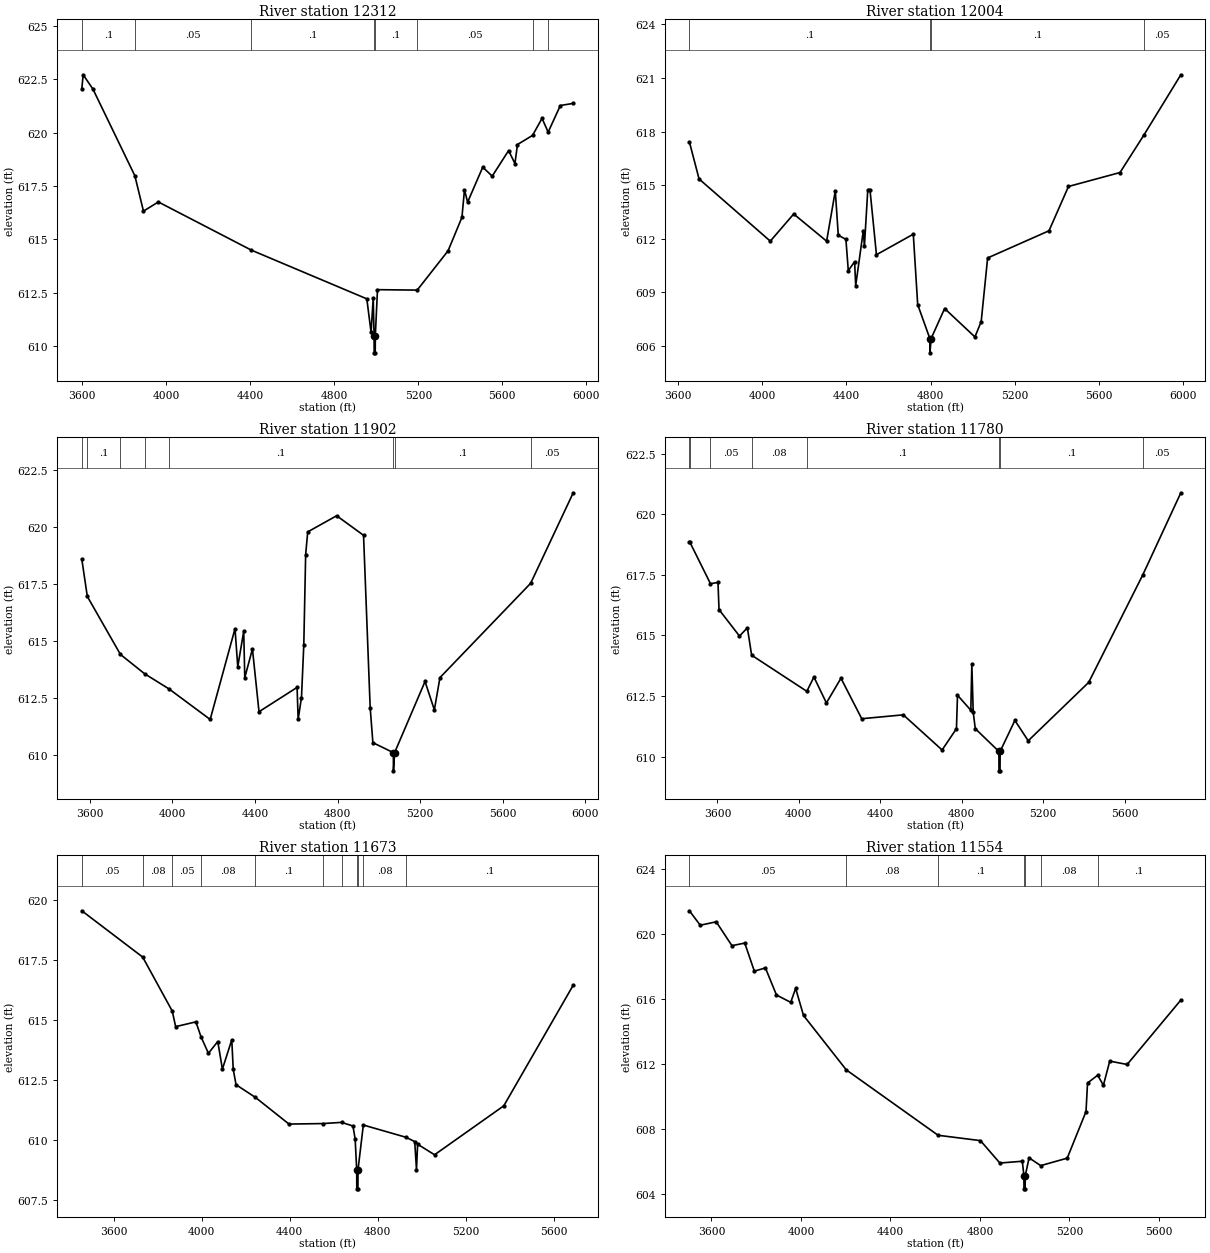
Type RM Length L Ch R = 1,12312,308,308,308
BEGIN DESCRIPTION:
UNT 019 in HW 31.0
END DESCRIPTION:
XS GIS Cut Line= 4
      1995053.80     13566843.57      1994085.92     13566431.25
      1993508.67     13566531.08      1992924.04     13566920.83
#Sta/Elev= 30
  3597.3  622.06  3603.9  622.71  3650.3  622.04  3849.9  617.98  3891.0  616.32
  3961.9  616.75  4405.3  614.49  4954.7  612.21  4975.0  610.64  4985.2  612.26
  4989.2  610.48  4989.7  609.68  4994.7  609.68  4995.2  610.48  5005.5  612.64
  5194.7  612.62  5341.6  614.46  5407.7  616.03  5419.8  617.32  5434.7  616.74
  5506.8  618.38  5551.9  617.96  5630.0  619.16  5660.0  618.55  5672.2  619.44
  5744.0  619.87  5789.2  620.67  5818.2  620.02  5876.4  621.27  5937.8  621.37
#Mann=8,-1,0
  3597.3     0.1       0  3849.9    0.05       0  4405.3     0.1       0
  4989.2    0.07       0  4995.2     0.1       0  5194.7    0.05       0
  5744.0     0.1       0  5818.2    0.05       0
Bank Sta=4989.2,4995.2
Exp/Cntr=0.3,0.1

Type RM Length L Ch R = 1,12004,102,102,102
BEGIN DESCRIPTION:
Mapping XS 37c8c318
END DESCRIPTION:
XS GIS Cut Line= 4
      1994958.35     13565979.85      1993873.25     13566248.96
      1993530.37     13566288.02      1992809.96     13566782.76
#Sta/Elev= 30
  3653.2  617.42  3699.2  615.35  4037.9  611.87  4149.2  613.39  4305.7  611.87
  4347.0  614.68  4361.2  612.20  4397.5  611.97  4408.8  610.22  4438.8  610.72
  4444.0  609.38  4480.2  612.46  4485.4  611.58  4501.5  614.75  4511.8  614.76
  4542.7  611.11  4717.9  612.26  4738.8  608.32  4796.6  606.42  4797.1  605.62
  4802.7  606.42  4866.9  608.10  5011.0  606.51  5040.8  607.37  5071.4  610.93
  5363.2  612.45  5455.9  614.93  5700.9  615.71  5813.6  617.79  5990.2  621.18
#Mann=4,-1,0
  3653.2     0.1       0  4796.6    0.07       0  4802.7     0.1       0
  5813.6    0.05       0
Bank Sta=4796.6,4802.7
Exp/Cntr=0.3,0.1

Type RM Length L Ch R = 1,11902,122,122,122
BEGIN DESCRIPTION:
Mapping XS f6e7317f
END DESCRIPTION:
XS GIS Cut Line= 4
      1994949.59     13565958.17      1993907.97     13566205.56
      1993595.47     13566218.58      1992766.47     13566769.80
#Sta/Elev= 30
  3562.2  618.60  3588.9  616.96  3749.2  614.41  3866.2  613.56  3984.8  612.89
  4183.6  611.55  4303.8  615.54  4317.2  613.87  4346.0  615.43  4351.1  613.39
  4388.2  614.65  4420.0  611.89  4604.3  612.96  4609.5  611.56  4625.6  612.51
  4636.8  614.83  4645.8  618.80  4655.8  619.80  4795.9  620.51  4926.0  619.65
  4958.1  612.07  4971.2  610.53  5070.3  610.09  5070.8  609.29  5076.4  610.09
  5223.7  613.22  5268.8  611.97  5295.8  613.39  5735.0  617.54  5941.1  621.52
#Mann=8,-1,0
  3562.2    0.08       0  3588.9     0.1       0  3749.2    0.05       0
  3866.2    0.08       0  3984.8     0.1       0  5070.3    0.07       0
  5076.4     0.1       0  5735.0    0.05       0
Bank Sta=5070.3,5076.4
Exp/Cntr=0.3,0.1

Type RM Length L Ch R = 1,11780,107,107,107
BEGIN DESCRIPTION:
Mapping XS 2575e718
END DESCRIPTION:
XS GIS Cut Line= 4
      1994953.94     13565940.81      1993947.04     13566149.13
      1993313.35     13566240.28      1992758.90     13566738.42
#Sta/Elev= 30
  3462.4  618.84  3464.8  618.84  3565.9  617.13  3602.8  617.18  3607.9  616.06
  3708.4  614.97  3747.2  615.31  3768.1  614.18  4039.2  612.69  4074.0  613.28
  4135.3  612.21  4206.8  613.23  4308.9  611.56  4512.9  611.72  4703.6  610.27
  4774.1  611.15  4779.2  612.53  4844.6  611.91  4849.6  613.81  4856.4  611.83
  4866.5  611.15  4982.5  610.21  4983.0  609.41  4988.1  609.41  4988.6  610.21
  5061.1  611.49  5126.5  610.65  5423.7  613.06  5689.1  617.49  5876.2  620.88
#Mann=8,-1,0
  3462.4    0.05       0  3464.8    0.08       0  3565.9    0.05       0
  3768.1    0.08       0  4039.2     0.1       0  4982.5    0.07       0
  4988.6     0.1       0  5689.1    0.05       0
Bank Sta=4982.5,4988.6
Exp/Cntr=0.3,0.1

Type RM Length L Ch R = 1,11673,119,119,119
BEGIN DESCRIPTION:
Mapping XS a0b52081
END DESCRIPTION:
XS GIS Cut Line= 4
      1994771.66     13565589.26      1994242.17     13566053.65
      1993118.04     13566144.79      1992814.21     13566409.56
#Sta/Elev= 30
  3454.3  619.57  3731.2  617.64  3865.7  615.39  3881.1  614.74  3973.2  614.94
  3996.4  614.32  4030.1  613.63  4072.8  614.12  4093.7  612.97  4136.4  614.19
  4143.0  612.96  4155.8  612.32  4244.1  611.79  4396.5  610.68  4550.0  610.70
  4635.8  610.75  4687.5  610.60  4697.5  610.06  4704.5  608.78  4705.0  607.98
  4710.1  607.98  4710.6  608.78  4734.7  610.64  4928.4  610.13  4968.4  609.95
  4976.5  608.78  4981.5  609.84  5058.7  609.40  5373.5  611.44  5689.4  616.47
#Mann=11,-1,0
  3454.3    0.05       0  3731.2    0.08       0  3865.7    0.05       0
  3996.4    0.08       0  4244.1     0.1       0  4550.0    0.08       0
  4635.8    0.05       0  4704.5    0.07       0  4710.6    0.05       0
  4734.7    0.08       0  4928.4     0.1       0
Bank Sta=4704.5,4710.6
Exp/Cntr=0.3,0.1

Type RM Length L Ch R = 1,11554,228,228,228
BEGIN DESCRIPTION:
UNT 019 in HW 30.0
END DESCRIPTION:
XS GIS Cut Line= 4
      1994728.26     13565519.81      1994233.49     13565936.46
      1993178.81     13566023.26      1992814.25     13566353.10
#Sta/Elev= 30
  3501.4  621.43  3549.8  620.54  3621.3  620.75  3691.6  619.28  3748.8  619.44
  3791.7  617.71  3841.1  617.91  3890.6  616.24  3954.3  615.79  3976.3  616.65
  4011.5  614.98  4202.6  611.63  4613.0  607.60  4802.4  607.27  4889.2  605.89
  4989.6  606.00  4996.5  605.10  4997.0  604.30  5002.1  604.30  5002.6  605.10
  5019.7  606.21  5071.7  605.73  5190.2  606.19  5274.2  609.06  5281.0  610.82
  5326.4  611.30  5351.9  610.68  5380.3  612.17  5458.1  611.96  5698.1  615.93
#Mann=7,-1,0
  3501.4    0.05       0  4202.6    0.08       0  4613.0     0.1       0
  4996.5    0.07       0  5002.6     0.1       0  5071.7    0.08       0
  5326.4     0.1       0
Bank Sta=4996.5,5002.6
Exp/Cntr=0.3,0.1

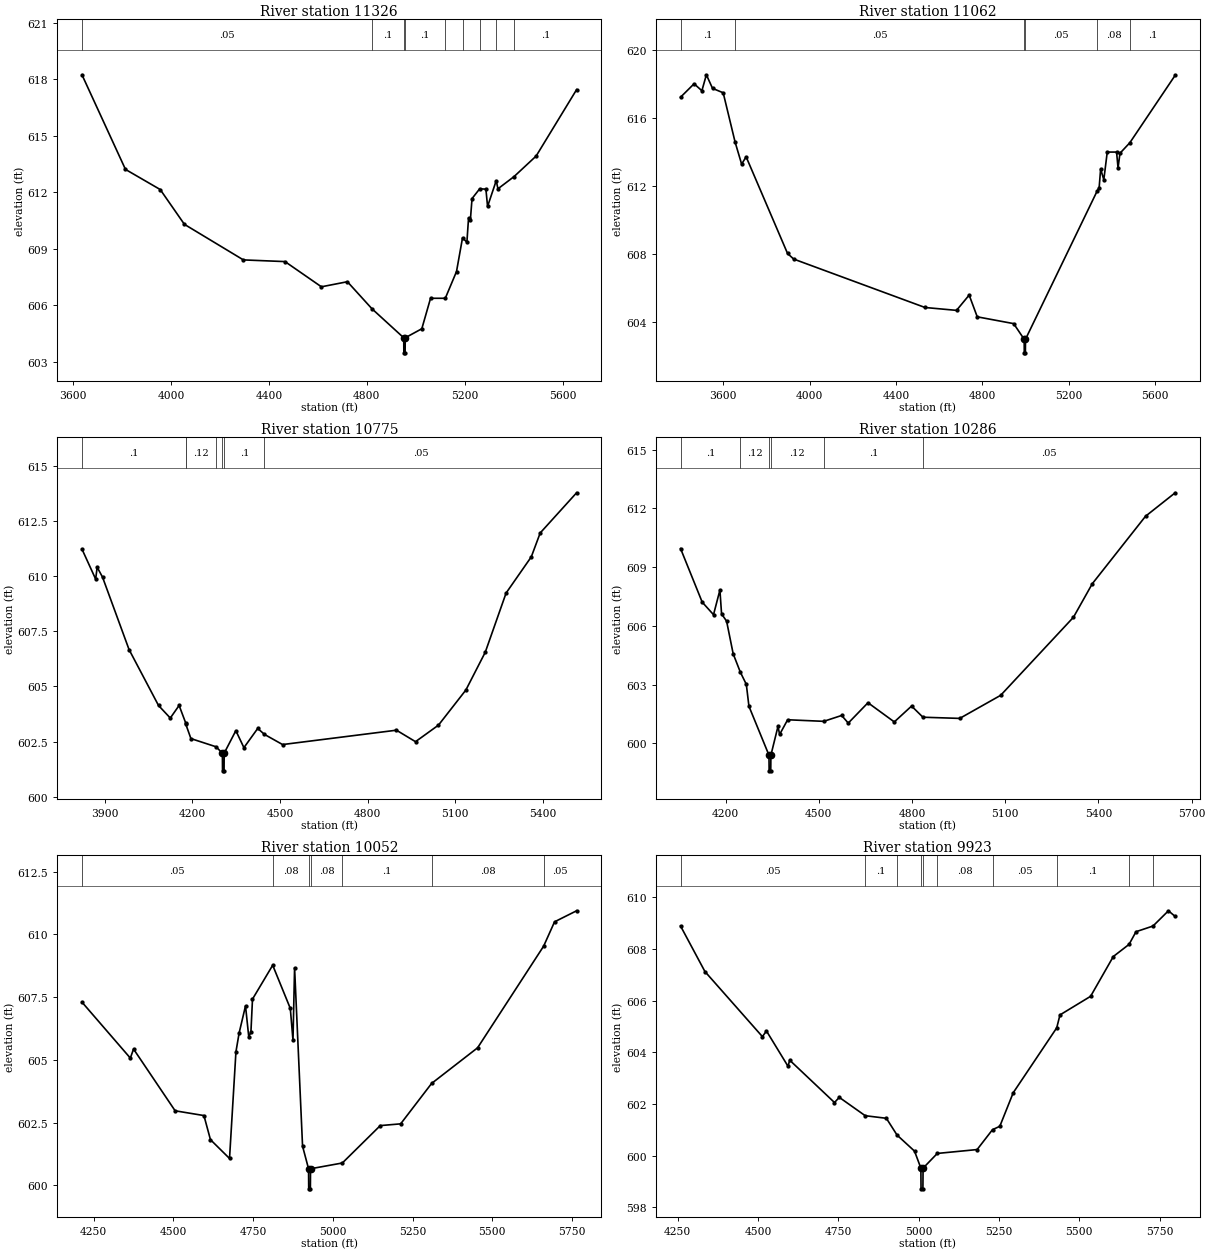
Type RM Length L Ch R = 1,11326,264,264,264
BEGIN DESCRIPTION:
UNT 019 in HW 29.0
END DESCRIPTION:
XS GIS Cut Line= 3
      1994133.69     13564912.12      1993291.65     13565858.33
      1992736.34     13566370.26
#Sta/Elev= 30
  3635.7  618.25  3813.6  613.22  3955.6  612.15  4054.5  610.30  4295.5  608.41
  4465.7  608.32  4614.5  606.98  4720.7  607.25  4821.3  605.81  4951.0  604.27
  4951.5  603.47  4956.6  603.47  4957.1  604.27  5024.9  604.75  5060.6  606.37
  5120.9  606.37  5166.7  607.79  5191.3  609.58  5209.2  609.35  5216.0  610.65
  5223.4  610.53  5230.2  611.67  5261.5  612.19  5286.9  612.17  5293.7  611.25
  5329.0  612.62  5336.2  612.19  5402.1  612.84  5492.2  613.93  5657.6  617.46
#Mann=9,-1,0
  3635.7    0.05       0  4821.3     0.1       0  4951.0    0.07       0
  4957.1     0.1       0  5120.9    0.08       0  5191.3    0.05       0
  5261.5     0.1       0  5329.0    0.08       0  5402.1     0.1       0
Bank Sta=4951,4957.1
Exp/Cntr=0.3,0.1

Type RM Length L Ch R = 1,11062,287,287,287
BEGIN DESCRIPTION:
UNT 019 in HW 28.0
END DESCRIPTION:
XS GIS Cut Line= 3
      1994051.20     13564582.30      1993348.08     13565194.27
      1992675.02     13566374.96
#Sta/Elev= 30
  3402.5  617.21  3465.2  618.00  3501.3  617.59  3522.1  618.53  3550.6  617.73
  3600.0  617.47  3655.1  614.57  3685.4  613.27  3706.3  613.70  3898.1  608.01
  3926.6  607.68  4534.8  604.83  4680.8  604.66  4739.4  605.56  4776.8  604.28
  4945.5  603.88  4994.2  602.96  4994.7  602.16  4999.8  602.16  5000.3  602.96
  5332.0  611.68  5341.5  611.89  5348.4  612.98  5363.1  612.35  5379.0  613.98
  5422.2  613.98  5429.0  613.05  5438.0  613.91  5483.7  614.53  5693.7  618.50
#Mann=6,-1,0
  3402.5     0.1       0  3655.1    0.05       0  4994.2   0.035       0
  5000.3    0.05       0  5332.0    0.08       0  5483.7     0.1       0
Bank Sta=4994.2,5000.3
Exp/Cntr=0.3,0.1

Type RM Length L Ch R = 1,10775,489,489,489
BEGIN DESCRIPTION:
UNT 019 in HW 27.0
END DESCRIPTION:
XS GIS Cut Line= 3
      1992966.13     13564465.11      1992825.00     13565575.00
      1992514.73     13566058.01
#Sta/Elev= 30
  3822.3  611.22  3869.2  609.86  3874.3  610.40  3892.7  609.95  3983.5  606.67
  4084.3  604.14  4124.6  603.57  4154.8  604.14  4177.0  603.36  4178.0  603.28
  4195.2  602.64  4281.1  602.27  4302.9  601.98  4303.4  601.18  4308.6  601.18
  4309.1  601.98  4349.0  603.00  4376.6  602.23  4423.9  603.10  4446.9  602.83
  4508.9  602.37  4898.6  603.02  4963.9  602.50  5042.5  603.25  5136.3  604.84
  5202.6  606.55  5273.9  609.23  5360.2  610.87  5390.6  611.95  5515.2  613.77
#Mann=7,-1,0
  3822.3     0.1       0  4177.0    0.16       0  4178.0    0.12       0
  4281.1     0.1       0  4302.9   0.035       0  4309.1     0.1       0
  4446.9    0.05       0
Bank Sta=4302.9,4309.1
Exp/Cntr=0.3,0.1

Type RM Length L Ch R = 1,10286,234,234,234
BEGIN DESCRIPTION:
Mapping XS d9a86a39
END DESCRIPTION:
XS GIS Cut Line= 4
      1992723.08     13564564.94      1992493.04     13565228.99
      1992315.09     13565563.19      1992380.03     13566069.75
#Sta/Elev= 30
  4054.9  609.95  4124.6  607.21  4161.0  606.57  4181.6  607.83  4186.9  606.61
  4203.1  606.24  4224.3  604.57  4247.4  603.63  4266.6  603.01  4275.0  601.89
  4339.5  599.39  4340.0  598.59  4345.2  598.59  4345.7  599.39  4368.5  600.86
  4373.8  600.45  4399.6  601.20  4515.8  601.12  4573.5  601.42  4594.7  601.03
  4658.2  602.07  4742.9  601.09  4798.5  601.90  4835.1  601.33  4953.5  601.27
  5085.3  602.45  5319.6  606.44  5380.1  608.15  5551.5  611.60  5647.0  612.80
#Mann=6,-1,0
  4054.9     0.1       0  4247.4    0.12       0  4339.5   0.035       0
  4345.7    0.12       0  4515.8     0.1       0  4835.1    0.05       0
Bank Sta=4339.5,4345.7
Exp/Cntr=0.3,0.1

Type RM Length L Ch R = 1,10052,129,129,129
BEGIN DESCRIPTION:
UNT 019 in HW 26.0
END DESCRIPTION:
XS GIS Cut Line= 3
      1992150.16     13564493.79      1992202.24     13565186.46
      1992309.02     13566035.45
#Sta/Elev= 30
  4213.7  607.30  4365.3  605.07  4375.4  605.43  4505.7  602.97  4596.0  602.78
  4616.4  601.82  4676.2  601.07  4696.3  605.32  4706.3  606.07  4726.3  607.15
  4736.4  605.93  4743.2  606.09  4748.2  607.42  4811.5  608.77  4866.7  607.05
  4875.1  605.78  4880.1  608.67  4905.1  601.56  4923.9  600.66  4924.4  599.86
  4929.6  599.86  4930.1  600.66  5029.8  600.89  5148.7  602.38  5212.6  602.45
  5309.6  604.06  5453.7  605.48  5660.7  609.53  5694.9  610.50  5764.0  610.94
#Mann=7,-1,0
  4213.7    0.05       0  4811.5    0.08       0  4923.9    0.07       0
  4930.1    0.08       0  5029.8     0.1       0  5309.6    0.08       0
  5660.7    0.05       0
Bank Sta=4923.9,4930.1
Exp/Cntr=0.3,0.1

Type RM Length L Ch R = 1,9923,517,517,517
BEGIN DESCRIPTION:
UNT 019 in HW 25.0
END DESCRIPTION:
XS GIS Cut Line= 3
      1992017.35     13564519.83      1992116.31     13565293.23
      1992217.86     13566045.80
#Sta/Elev= 30
  4259.3  608.89  4335.1  607.13  4514.0  604.61  4526.6  604.83  4593.8  603.46
  4598.8  603.70  4738.3  602.06  4753.2  602.26  4833.9  601.55  4899.7  601.45
  4933.0  600.80  4987.3  600.18  5007.1  599.52  5007.6  598.72  5013.4  598.72
  5013.9  599.52  5058.2  600.09  5182.1  600.24  5230.0  601.01  5252.7  601.14
  5294.5  602.44  5429.8  604.95  5439.9  605.45  5535.2  606.17  5605.9  607.71
  5654.9  608.18  5676.5  608.67  5729.4  608.89  5777.4  609.48  5798.4  609.26
#Mann=10,-1,0
  4259.3    0.05       0  4833.9     0.1       0  4933.0    0.16       0
  5007.1    0.07       0  5013.9    0.16       0  5058.2    0.08       0
  5230.0    0.05       0  5429.8     0.1       0  5654.9    0.08       0
  5729.4    0.05       0
Bank Sta=5007.1,5013.9
Exp/Cntr=0.3,0.1

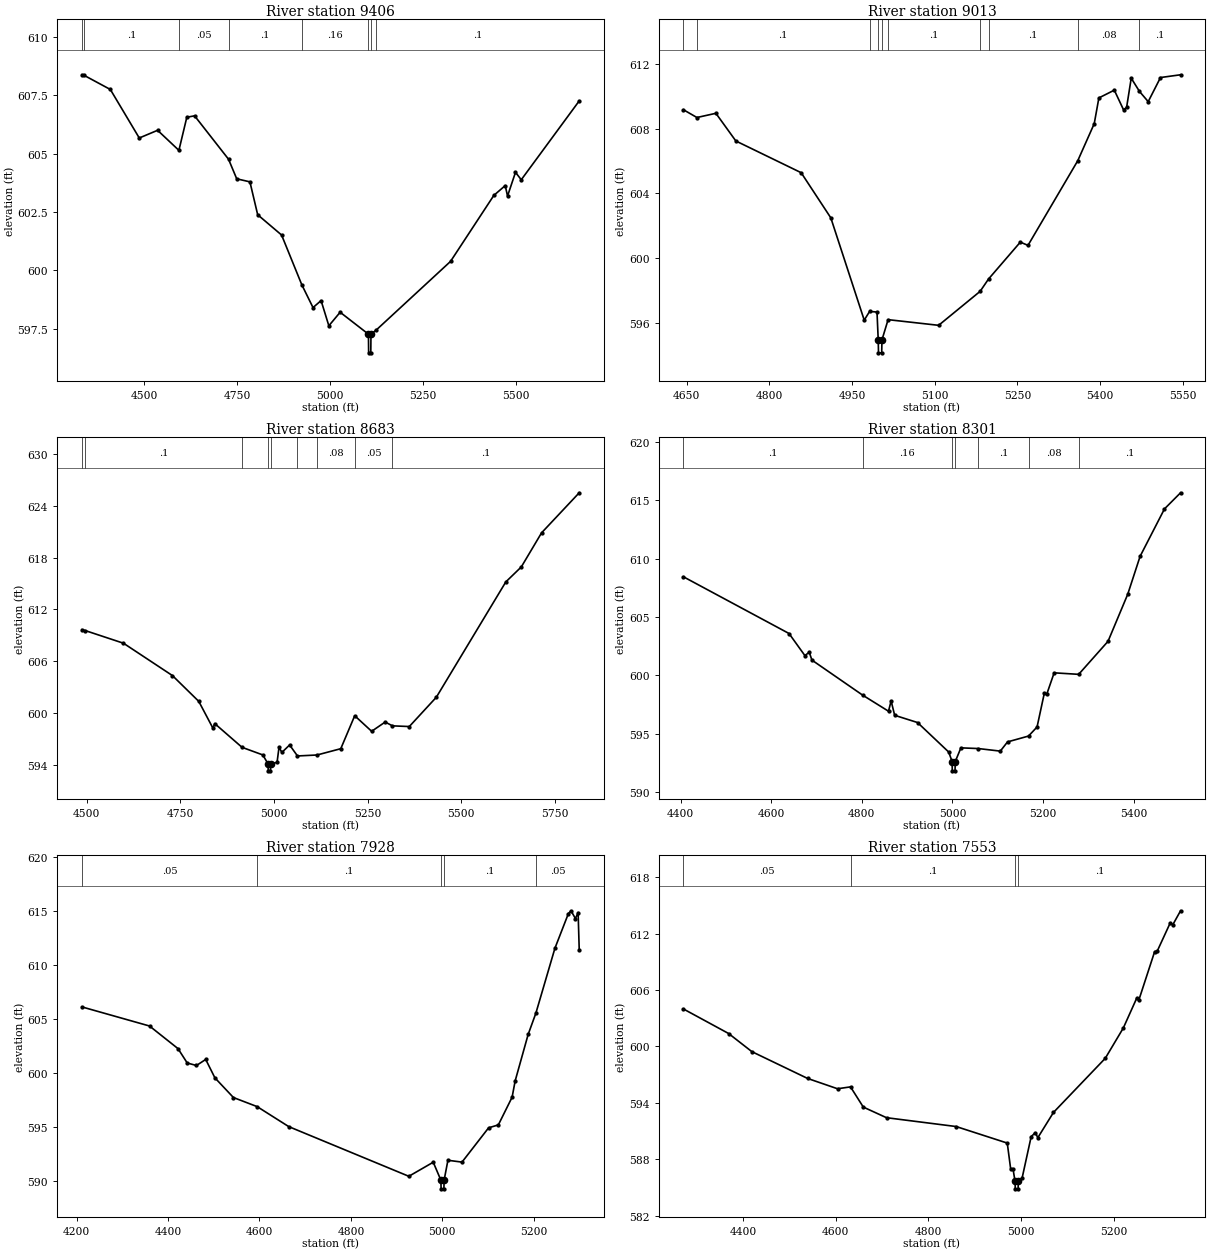
Type RM Length L Ch R = 1,9406,393,393,393
BEGIN DESCRIPTION:
UNT 019 in HW 24.0
END DESCRIPTION:
XS GIS Cut Line= 3
      1991277.79     13565025.02      1991725.00     13565525.00
      1992069.46     13566095.35
#Sta/Elev= 30
  4332.5  608.38  4338.6  608.35  4408.5  607.75  4486.3  605.67  4535.6  606.00
  4592.9  605.14  4614.2  606.56  4635.1  606.62  4726.4  604.76  4748.4  603.92
  4783.9  603.79  4804.8  602.38  4869.1  601.51  4923.4  599.38  4953.6  598.40
  4975.3  598.70  4996.2  597.62  5026.6  598.20  5102.7  597.26  5103.2  596.46
  5109.0  596.46  5109.5  597.26  5123.8  597.44  5323.5  600.38  5440.0  603.21
  5470.6  603.63  5476.8  603.18  5498.2  604.20  5513.7  603.88  5669.6  607.26
#Mann=8,-1,0
  4332.5    0.05       0  4338.6     0.1       0  4592.9    0.05       0
  4726.4     0.1       0  4923.4    0.16       0  5102.7    0.07       0
  5109.5    0.16       0  5123.8     0.1       0
Bank Sta=5102.7,5109.5
Exp/Cntr=0.3,0.1

Type RM Length L Ch R = 1,9013,330,330,330
BEGIN DESCRIPTION:
UNT 019 in HW 23.0
END DESCRIPTION:
XS GIS Cut Line= 3
      1991397.54     13565506.74      1991525.00     13565825.00
      1991775.02     13566325.04
#Sta/Elev= 30
  4644.2  609.16  4668.7  608.68  4703.1  608.94  4739.3  607.23  4857.8  605.27
  4911.6  602.48  4972.2  596.16  4982.0  596.70  4995.4  596.66  4997.6  594.94
  4998.1  594.14  5003.9  594.14  5004.4  594.94  5015.5  596.19  5107.2  595.84
  5182.5  597.94  5197.7  598.70  5255.4  600.98  5269.3  600.78  5359.6  606.01
  5389.5  608.30  5397.9  609.89  5425.9  610.37  5442.6  609.16  5448.2  609.30
  5456.6  611.11  5471.6  610.29  5487.4  609.66  5509.7  611.15  5546.1  611.32
#Mann=10,-1,0
  4644.2    0.05       0  4668.7     0.1       0  4982.0    0.16       0
  4997.6    0.07       0  5004.4    0.16       0  5015.5     0.1       0
  5182.5    0.16       0  5197.7     0.1       0  5359.6    0.08       0
  5471.6     0.1       0
Bank Sta=4997.6,5004.4
Exp/Cntr=0.3,0.1

Type RM Length L Ch R = 1,8683,382,382,382
BEGIN DESCRIPTION:
UNT 019 in HW 22.0
END DESCRIPTION:
XS GIS Cut Line= 3
      1991375.00     13565525.02      1991325.00     13566025.00
      1991125.00     13566825.01
#Sta/Elev= 30
  4487.7  609.66  4496.3  609.56  4598.2  608.10  4728.9  604.36  4799.2  601.38
  4836.9  598.29  4841.9  598.81  4914.6  596.07  4970.1  595.19  4984.2  594.15
  4984.7  593.35  4990.6  593.35  4991.1  594.15  5008.2  594.33  5013.4  596.07
  5021.1  595.48  5041.7  596.34  5062.7  595.07  5114.7  595.18  5178.3  595.91
  5215.5  599.72  5260.7  597.92  5296.8  598.99  5316.3  598.55  5361.2  598.47
  5433.4  601.86  5618.9  615.19  5660.2  616.92  5714.3  620.86  5814.8  625.49
#Mann=9,-1,0
  4487.7    0.05       0  4496.3     0.1       0  4914.6    0.07       0
  4984.2    0.07       0  4991.1    0.07       0  5062.7    0.16       0
  5114.7    0.08       0  5215.5    0.05       0  5316.3     0.1       0
Bank Sta=4984.2,4991.1
Exp/Cntr=0.3,0.1

Type RM Length L Ch R = 1,8301,373,373,373
BEGIN DESCRIPTION:
UNT 019 in HW 21.0
END DESCRIPTION:
XS GIS Cut Line= 3
      1991275.00     13565575.01      1990975.00     13566075.00
      1990724.99     13566525.03
#Sta/Elev= 30
  4406.0  608.44  4639.2  603.58  4674.2  601.69  4683.9  601.97  4689.8  601.30
  4801.7  598.30  4858.9  596.92  4864.7  597.80  4872.5  596.57  4923.0  595.95
  4991.9  593.42  4999.3  592.61  4999.8  591.81  5005.8  591.81  5006.4  592.61
  5018.8  593.78  5057.3  593.72  5105.8  593.50  5121.8  594.29  5168.1  594.79
  5187.0  595.57  5203.0  598.46  5208.7  598.41  5224.7  600.21  5278.9  600.08
  5343.7  602.91  5387.2  606.94  5414.6  610.20  5468.4  614.26  5503.9  615.64
#Mann=7,-1,0
  4406.0     0.1       0  4801.7    0.16       0  4999.3    0.07       0
  5006.4    0.16       0  5057.3     0.1       0  5168.1    0.08       0
  5278.9     0.1       0
Bank Sta=4999.3,5006.4
Exp/Cntr=0.3,0.1

Type RM Length L Ch R = 1,7928,375,375,375
BEGIN DESCRIPTION:
UNT 019 in HW 20.0
END DESCRIPTION:
XS GIS Cut Line= 3
      1990730.89     13565267.22      1990625.00     13566025.00
      1990457.79     13566300.48
#Sta/Elev= 30
  4212.0  606.13  4359.5  604.37  4421.8  602.28  4442.0  600.95  4462.2  600.72
  4482.4  601.28  4502.5  599.58  4543.0  597.76  4594.9  596.92  4664.1  595.07
  4926.7  590.48  4980.1  591.78  4996.8  590.12  4997.3  589.32  5003.4  589.32
  5003.9  590.12  5012.2  591.96  5043.0  591.79  5101.2  594.96  5122.5  595.23
  5152.6  597.79  5159.3  599.30  5187.7  603.59  5204.7  605.57  5246.2  611.55
  5275.7  614.76  5281.5  615.02  5291.1  614.30  5297.0  614.86  5299.4  611.44
#Mann=5,-1,0
  4212.0    0.05       0  4594.9     0.1       0  4996.8    0.07       0
  5003.9     0.1       0  5204.7    0.05       0
Bank Sta=4996.8,5003.9
Exp/Cntr=0.3,0.1

Type RM Length L Ch R = 1,7553,379,379,379
BEGIN DESCRIPTION:
UNT 019 in HW 19.0
END DESCRIPTION:
XS GIS Cut Line= 3
      1990322.04     13565217.67      1990275.00     13565925.00
      1990375.00     13566275.00
#Sta/Elev= 30
  4271.1  603.98  4368.6  601.37  4418.8  599.44  4539.0  596.59  4603.7  595.49
  4631.7  595.69  4659.3  593.54  4709.4  592.41  4859.7  591.47  4970.0  589.71
  4977.5  586.90  4982.6  586.90  4986.8  585.64  4987.3  584.84  4993.4  584.84
  4993.9  585.64  5002.1  586.00  5021.6  590.40  5030.7  590.82  5035.9  590.28
  5069.7  592.97  5181.5  598.73  5220.5  601.96  5249.1  605.10  5254.3  604.98
  5288.1  610.09  5293.3  610.10  5321.9  613.16  5327.1  612.93  5344.0  614.43
#Mann=4,-1,0
  4271.1    0.05       0  4631.7     0.1       0  4986.8    0.07       0
  4993.9     0.1       0
Bank Sta=4986.8,4993.9
Exp/Cntr=0.3,0.1

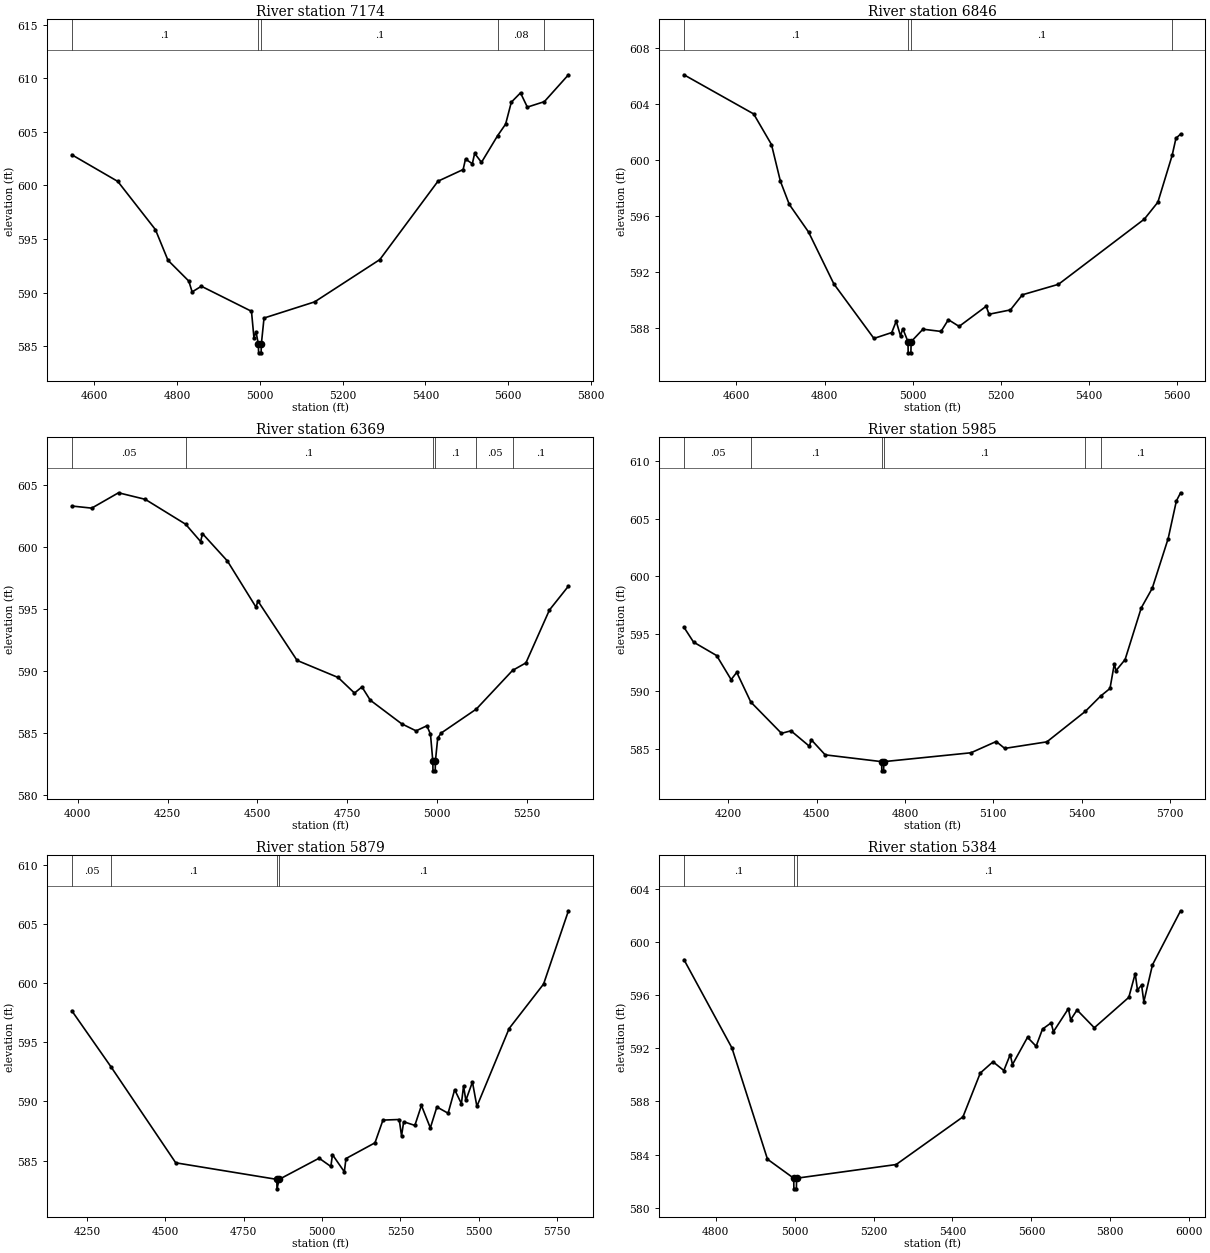
Type RM Length L Ch R = 1,7174,328,328,328
BEGIN DESCRIPTION:
UNT 019 in HW 18.0
END DESCRIPTION:
XS GIS Cut Line= 3
      1989900.16     13565334.89      1989978.29     13565905.21
      1990264.73     13566459.86
#Sta/Elev= 30
  4545.9  602.87  4657.0  600.38  4747.9  595.88  4778.2  593.02  4828.6  591.07
  4836.6  590.06  4858.9  590.59  4980.0  588.25  4985.9  585.80  4991.0  586.33
  4996.6  585.17  4997.2  584.37  5003.3  584.37  5003.8  585.17  5010.3  587.62
  5132.6  589.13  5290.1  593.08  5430.6  600.40  5491.4  601.49  5497.1  602.47
  5513.6  602.03  5519.2  603.00  5535.7  602.16  5574.8  604.66  5594.0  605.73
  5607.8  607.78  5630.0  608.65  5646.5  607.32  5687.6  607.83  5745.8  610.34
#Mann=5,-1,0
  4545.9     0.1       0  4996.6    0.07       0  5003.8     0.1       0
  5574.8    0.08       0  5687.6     0.1       0
Bank Sta=4996.6,5003.8
Exp/Cntr=0.3,0.1

Type RM Length L Ch R = 1,6846,477,477,477
BEGIN DESCRIPTION:
UNT 019 in HW 17.0
END DESCRIPTION:
XS GIS Cut Line= 3
      1989749.12     13565298.42      1989675.00     13565825.00
      1989545.98     13566405.26
#Sta/Elev= 30
  4481.2  606.12  4639.3  603.32  4679.7  601.13  4699.9  598.51  4720.1  596.85
  4763.7  594.88  4821.1  591.17  4912.0  587.27  4952.4  587.69  4962.5  588.50
  4972.3  587.45  4977.4  587.97  4989.2  587.04  4989.7  586.24  4995.8  586.24
  4996.4  587.04  5023.2  587.93  5064.2  587.77  5080.8  588.61  5105.2  588.13
  5166.6  589.57  5173.0  589.00  5221.6  589.31  5248.6  590.39  5330.5  591.14
  5525.2  595.80  5555.9  597.01  5588.2  600.35  5596.9  601.58  5607.4  601.88
#Mann=4,-1,0
  4481.2     0.1       0  4989.2    0.07       0  4996.4     0.1       0
  5588.2    0.05       0
Bank Sta=4989.2,4996.4
Exp/Cntr=0.3,0.1

Type RM Length L Ch R = 1,6369,384,384,384
BEGIN DESCRIPTION:
UNT 019 in HW 16.0
END DESCRIPTION:
XS GIS Cut Line= 3
      1989444.44     13564806.21      1989230.89     13565592.71
      1989191.83     13566157.78
#Sta/Elev= 30
  3983.6  603.32  4039.0  603.15  4113.5  604.39  4187.9  603.86  4300.2  601.85
  4341.9  600.45  4347.1  601.09  4416.4  598.88  4496.0  595.15  4501.2  595.65
  4610.2  590.85  4724.4  589.47  4769.9  588.21  4790.6  588.71  4813.7  587.64
  4901.1  585.73  4941.2  585.16  4971.3  585.57  4981.3  584.88  4987.7  582.73
  4988.2  581.93  4994.4  581.93  4995.0  582.73  5001.4  584.58  5011.4  584.99
  5108.8  586.92  5209.5  590.04  5246.7  590.65  5312.1  594.92  5365.0  596.85
#Mann=6,-1,0
  3983.6    0.05       0  4300.2     0.1       0  4987.7    0.07       0
  4995.0     0.1       0  5108.8    0.05       0  5209.5     0.1       0
Bank Sta=4987.7,4995
Exp/Cntr=0.3,0.1

Type RM Length L Ch R = 1,5985,106,106,106
BEGIN DESCRIPTION:
Mapping XS 62b6a638
END DESCRIPTION:
XS GIS Cut Line= 6
      1988615.41     13564768.90      1988723.94     13564855.73
      1988832.45     13565133.51      1988914.92     13565719.44
      1989170.99     13565979.86      1989110.23     13566248.98
#Sta/Elev= 30
  4049.1  595.58  4081.7  594.29  4160.2  593.12  4209.4  591.03  4228.5  591.66
  4276.3  589.08  4380.5  586.36  4412.8  586.58  4475.7  585.23  4481.1  585.82
  4529.0  584.49  4720.8  583.90  4721.4  583.10  4727.6  583.10  4728.2  583.90
  5024.4  584.67  5110.1  585.65  5139.1  585.05  5282.4  585.62  5412.6  588.26
  5464.6  589.59  5496.8  590.26  5511.5  592.39  5517.3  591.81  5548.1  592.77
  5603.0  597.26  5640.4  598.97  5694.5  603.29  5722.4  606.56  5736.7  607.27
#Mann=6,-1,0
  4049.1    0.05       0  4276.3     0.1       0  4720.8    0.07       0
  4728.2     0.1       0  5412.6    0.05       0  5464.6     0.1       0
Bank Sta=4720.8,4728.2
Exp/Cntr=0.3,0.1

Type RM Length L Ch R = 1,5879,495,495,495
BEGIN DESCRIPTION:
Mapping XS 9d30f80b
END DESCRIPTION:
XS GIS Cut Line= 6
      1988553.79     13564858.33      1988670.99     13564933.85
      1988767.35     13565204.69      1988868.91     13565785.42
      1989087.66     13565985.94      1989077.24     13566254.19
#Sta/Elev= 30
  4201.1  597.66  4327.5  592.87  4532.8  584.81  4855.4  583.41  4856.0  582.61
  4862.8  583.41  4990.4  585.20  5027.9  584.50  5033.0  585.50  5070.9  584.05
  5076.2  585.17  5168.7  586.50  5194.2  588.42  5246.1  588.47  5253.5  587.08
  5260.3  588.28  5296.0  587.97  5317.0  589.66  5345.4  587.76  5366.3  589.53
  5402.1  589.00  5423.1  590.99  5444.6  589.81  5451.4  591.30  5458.8  590.09
  5479.8  591.64  5494.0  589.58  5596.9  596.16  5706.9  599.92  5786.2  606.11
#Mann=4,-1,0
  4201.1    0.05       0  4327.5     0.1       0  4855.4    0.07       0
  4862.8     0.1       0
Bank Sta=4855.4,4862.8
Exp/Cntr=0.3,0.1

Type RM Length L Ch R = 1,5384,255,255,255
BEGIN DESCRIPTION:
Mapping XS 1b7dc029
END DESCRIPTION:
XS GIS Cut Line= 3
      1988527.77     13564923.46      1988548.60     13565433.85
      1988904.62     13566091.33
#Sta/Elev= 30
  4719.6  598.68  4841.2  592.03  4931.3  583.65  4997.7  582.22  4998.2  581.42
  5004.5  581.42  5005.1  582.22  5257.3  583.25  5426.6  586.84  5470.5  590.14
  5502.7  590.99  5530.2  590.33  5546.4  591.53  5552.1  590.78  5590.2  592.83
  5612.0  592.16  5628.2  593.45  5650.1  593.92  5655.8  593.25  5693.8  594.99
  5699.5  594.15  5715.7  594.89  5759.5  593.55  5846.9  595.84  5863.1  597.63
  5868.8  596.40  5879.3  596.76  5885.0  595.51  5906.9  598.29  5978.1  602.36
#Mann=3,-1,0
  4719.6     0.1       0  4997.7    0.07       0  5005.1     0.1       0
Bank Sta=4997.7,5005.1
Exp/Cntr=0.3,0.1

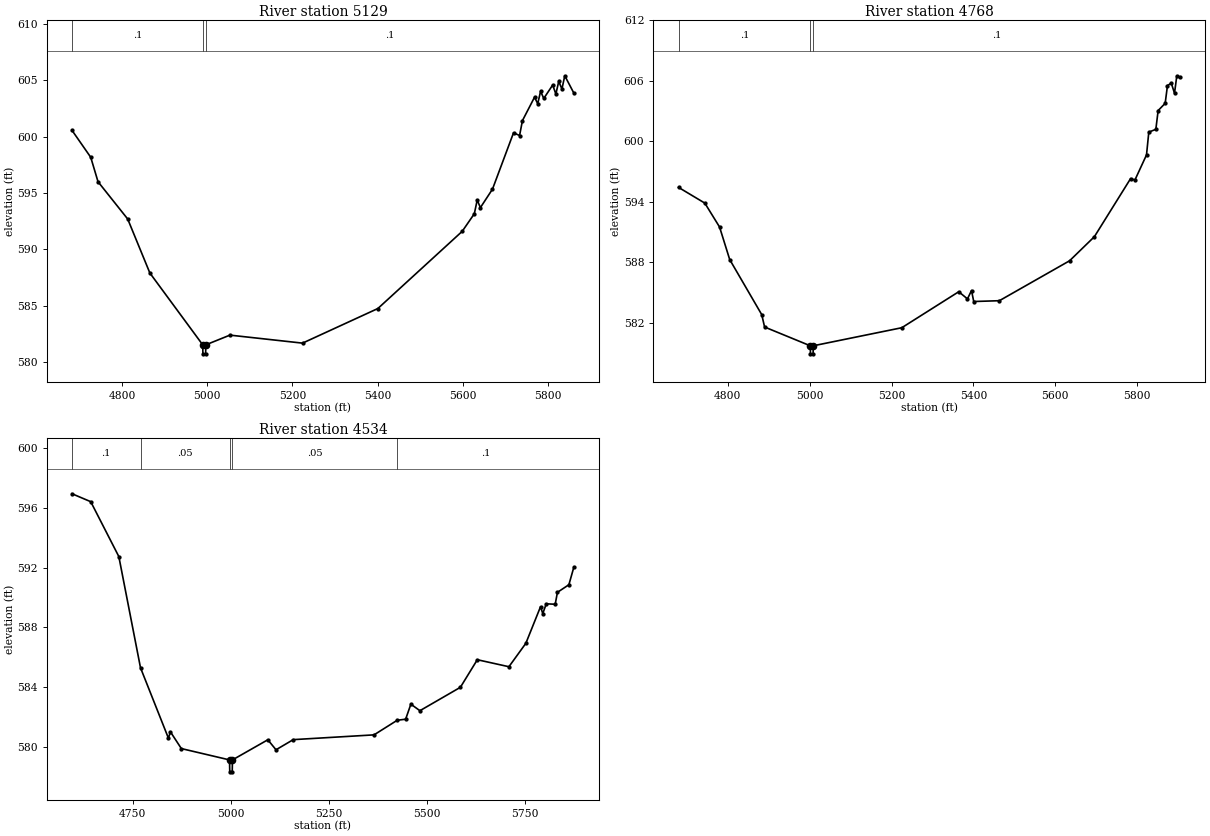
Type RM Length L Ch R = 1,5129,361,361,361
BEGIN DESCRIPTION:
UNT 019 in HW 13.0
END DESCRIPTION:
XS GIS Cut Line= 4
      1988375.01     13564874.98      1988281.24     13565085.76
      1988324.64     13565558.85      1988675.01     13565875.01
#Sta/Elev= 30
  4682.7  600.55  4726.5  598.17  4743.6  596.00  4813.3  592.69  4865.3  587.90
  4989.3  581.53  4989.8  580.73  4996.1  580.73  4996.7  581.53  5053.2  582.39
  5223.6  581.68  5400.4  584.75  5598.4  591.60  5626.8  593.16  5633.6  594.38
  5641.0  593.70  5669.4  595.34  5718.8  600.34  5733.0  600.10  5739.7  601.42
  5768.1  603.50  5775.6  602.92  5782.3  604.02  5789.8  603.39  5810.7  604.58
  5818.2  603.78  5824.9  604.90  5832.4  604.23  5839.1  605.40  5860.4  603.86
#Mann=3,-1,0
  4682.7     0.1       0  4989.3    0.07       0  4996.7     0.1       0
Bank Sta=4989.3,4996.7
Exp/Cntr=0.3,0.1

Type RM Length L Ch R = 1,4768,234,234,234
BEGIN DESCRIPTION:
UNT 019 in HW 12.0
END DESCRIPTION:
XS GIS Cut Line= 3
      1987875.00     13564924.99      1988138.01     13565619.62
      1988575.00     13565825.00
#Sta/Elev= 30
  4679.7  595.42  4743.9  593.86  4779.9  591.49  4804.7  588.26  4882.9  582.80
  4889.9  581.57  5001.4  579.71  5002.0  578.91  5008.3  578.91  5008.9  579.71
  5225.0  581.50  5364.1  585.07  5385.4  584.36  5395.3  585.19  5400.7  584.10
  5463.3  584.18  5634.8  588.14  5695.4  590.53  5783.8  596.29  5794.4  596.15
  5822.7  598.64  5828.3  600.90  5845.5  601.18  5851.1  603.04  5868.3  603.76
  5873.9  605.52  5883.2  605.76  5891.1  604.76  5896.7  606.49  5905.3  606.32
#Mann=3,-1,0
  4679.7     0.1       0  5001.4    0.07       0  5008.9     0.1       0
Bank Sta=5001.4,5008.9
Exp/Cntr=0.3,0.1

Type RM Length L Ch R = 1,4534,0,0,0
BEGIN DESCRIPTION:
UNT 019 in HW 11.0
END DESCRIPTION:
XS GIS Cut Line= 4
      1987838.53     13564864.41      1987708.32     13565068.40
      1987843.55     13565519.59      1988336.01     13565800.97
#Sta/Elev= 30
  4595.0  596.96  4642.6  596.43  4714.3  592.75  4769.6  585.29  4840.8  580.57
  4846.0  580.99  4873.8  579.87  4996.7  579.11  4997.3  578.31  5003.6  578.31
  5004.2  579.11  5094.4  580.46  5115.3  579.79  5159.3  580.47  5365.4  580.79
  5424.6  581.77  5446.0  581.84  5459.4  582.85  5482.4  582.41  5585.7  583.98
  5628.9  585.83  5709.5  585.36  5752.7  586.93  5790.1  589.38  5795.9  588.93
  5804.9  589.58  5827.6  589.55  5833.3  590.35  5862.5  590.86  5875.2  592.04
#Mann=5,-1,0
  4595.0     0.1       0  4769.6    0.05       0  4996.7    0.03       0
  5004.2    0.05       0  5424.6     0.1       0
Bank Sta=4996.7,5004.2
Exp/Cntr=0.3,0.1

Chan Stop Cuts=-1