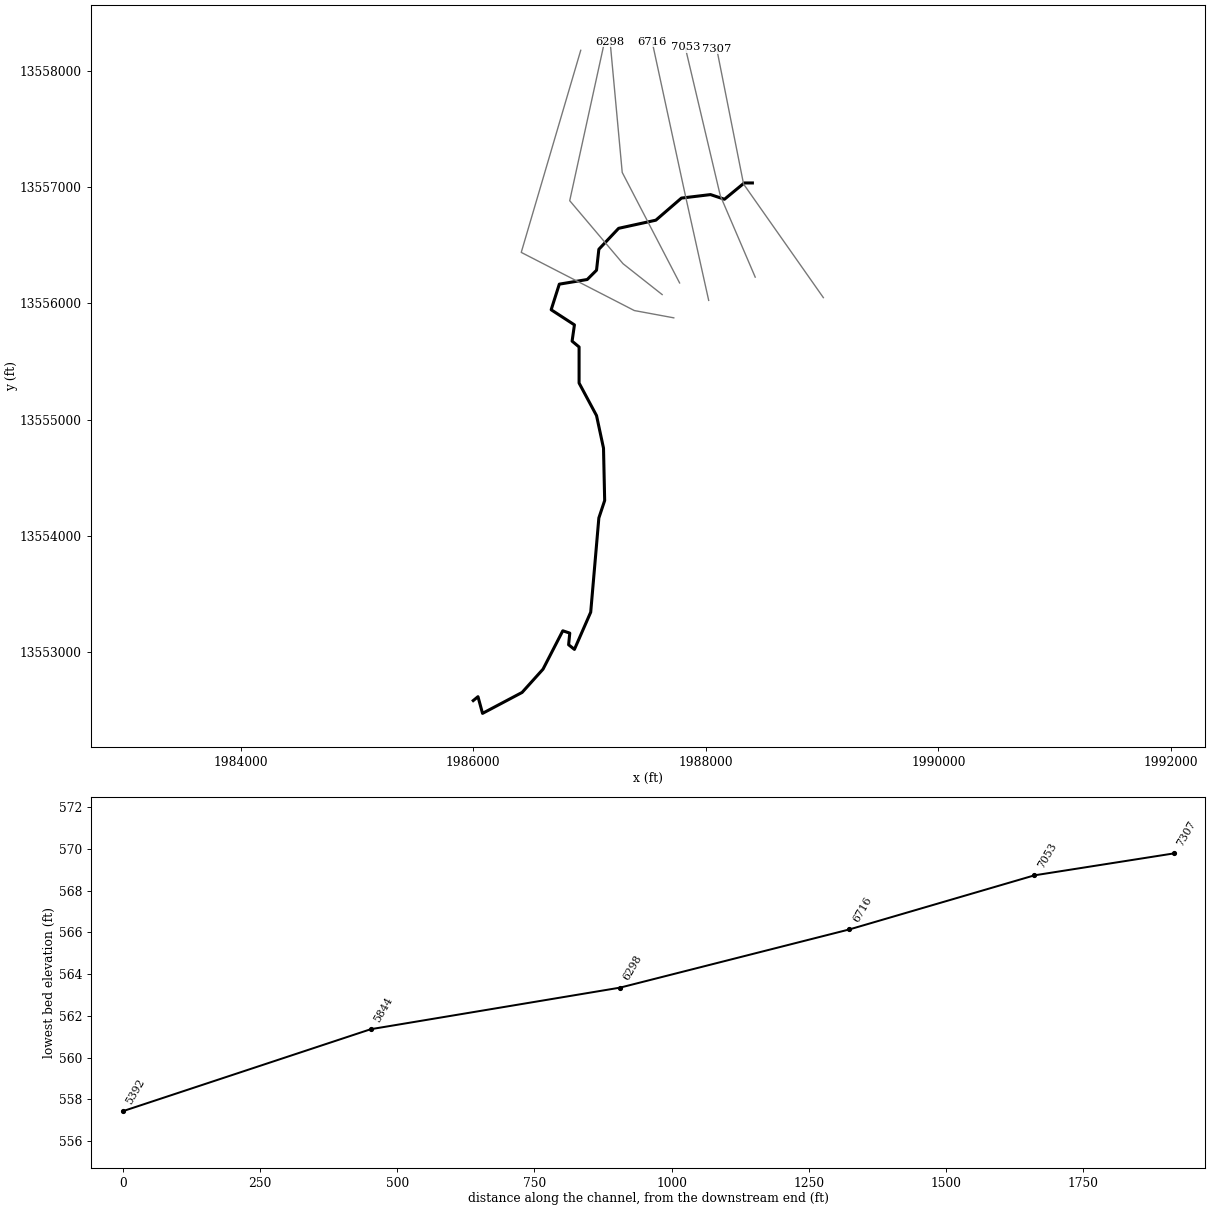
--- UNT 020 in HW.prj (project) ---

Proj Title=UNT 020 in HW Base Level Engineering
Current Plan=p01
Default Exp/Contr=0.3,0.1
English Units
Geom File=g01
Flow File=f01
Plan File=p01
BEGIN DESCRIPTION:
UNT 020 in HW
END DESCRIPTION:

--- UNT 020 in HW.p01 (plan) ---

Plan Title=Multiple Run
Short Identifier=Multiple
Geom File=g01
Flow File=f01
Subcritical Flow
K Sum by GR= 0
Std Step Tol= 0.01
Critical Tol= 0.01
Num of Std Step Trials= 20
Max Error Tol= 0.3
Flow Tol Ratio= 0.001
Split Flow NTrial= 30
Split Flow Tol= 0.02
Split Flow Ratio= 0.02
Log Output Level= 0
Friction Slope Method= 1
Unsteady Friction Slope Method= 2
Unsteady Bridges Friction Slope Method= 1
Parabolic Critical Depth
Global Vel Dist=  1 , 1 , 1
Global Log Level= 0
CheckData=True
Encroach Param= -1, 0, 0, 0
BEGIN DESCRIPTION:
Multiple Run
END DESCRIPTION:

--- UNT 020 in HW.f01 (steady flow) ---

Flow Title=Multiple
Number of Profiles=7
Profile Names=10-year,25-year,50-year,1pct_min,100-year,1pct_plu,500-year
River Rch & RM= UNT 020 in HW,Reach-1,7307
     493     690     853     522    1042    2079    1562
River Rch & RM= UNT 020 in HW,Reach-1,7053
     636     900    1120     689    1376    2745    2085
Boundary for River Rch & Prof#=UNT 020 in HW,Reach-1,1
Up Type=0
Dn Type=3
Dn Slope=0.005
Boundary for River Rch & Prof#=UNT 020 in HW,Reach-1,2
Up Type=0
Dn Type=3
Dn Slope=0.005
Boundary for River Rch & Prof#=UNT 020 in HW,Reach-1,3
Up Type=0
Dn Type=3
Dn Slope=0.005
Boundary for River Rch & Prof#=UNT 020 in HW,Reach-1,4
Up Type=0
Dn Type=3
Dn Slope=0.005
Boundary for River Rch & Prof#=UNT 020 in HW,Reach-1,5
Up Type=0
Dn Type=3
Dn Slope=0.005
Boundary for River Rch & Prof#=UNT 020 in HW,Reach-1,6
Up Type=0
Dn Type=3
Dn Slope=0.005
Boundary for River Rch & Prof#=UNT 020 in HW,Reach-1,7
Up Type=0
Dn Type=3
Dn Slope=0.005

--- UNT 020 in HW.g01 (geometry) ---

Geom Title=Existing Conditions

River Reach=UNT 020 in HW,Reach-1
Reach XY= 30
      1988400.80     13557034.54      1988330.80     13557034.54
      1988160.80     13556894.54      1988040.80     13556934.54
      1987790.80     13556904.54      1987570.80     13556714.54
      1987250.80     13556644.54      1987080.80     13556464.54
      1987060.80     13556284.54      1986980.80     13556204.54
      1986740.80     13556164.54      1986670.80     13555944.54
      1986870.80     13555814.54      1986850.80     13555674.54
      1986910.80     13555624.54      1986910.80     13555314.54
      1987060.80     13555034.54      1987120.80     13554754.54
      1987130.80     13554304.54      1987080.80     13554154.54
      1987010.80     13553344.54      1986870.80     13553024.54
      1986820.80     13553064.54      1986830.80     13553164.54
      1986770.80     13553184.54      1986600.80     13552854.54
      1986420.80     13552654.54      1986080.80     13552474.54
      1986041.72     13552618.01      1986000.80     13552584.54

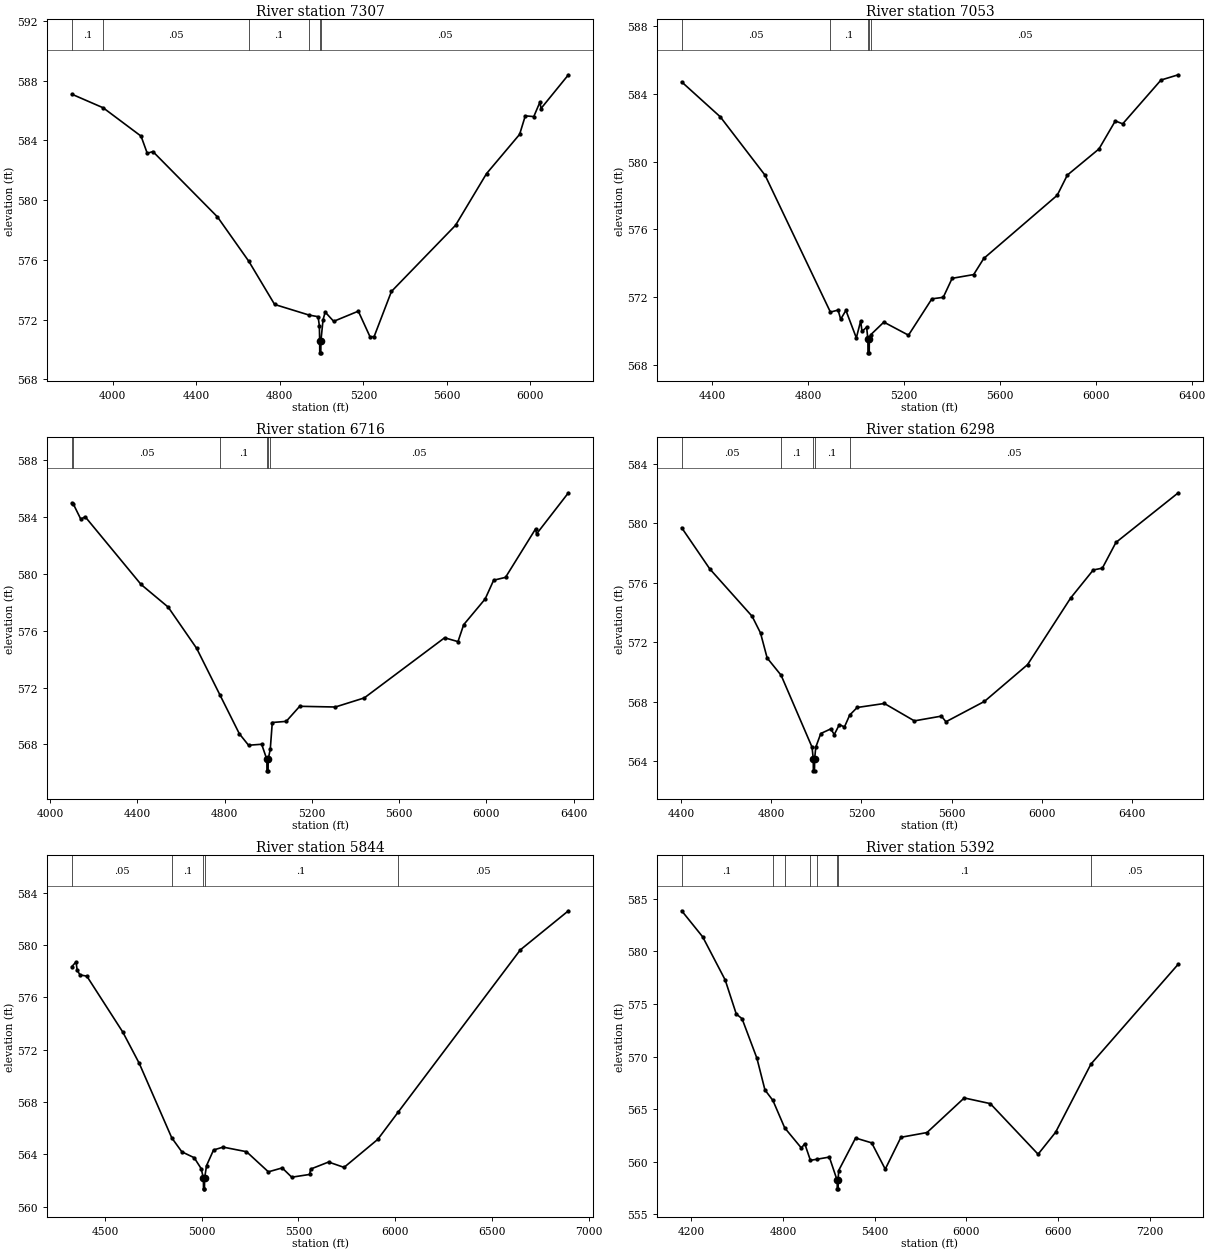
Type RM Length L Ch R = 1,7307,254,254,254
BEGIN DESCRIPTION:
UNT 020 in HW 13.0
END DESCRIPTION:
XS GIS Cut Line= 3
      1989010.81     13556048.80      1988325.00     13557025.00
      1988094.16     13558187.69
#Sta/Elev= 30
  3803.8  587.10  3953.9  586.19  4135.5  584.29  4165.1  583.14  4192.1  583.26
  4501.5  578.88  4651.5  575.91  4775.1  573.02  4939.9  572.31  4983.3  572.20
  4989.4  571.59  4990.8  570.58  4991.3  569.78  4996.3  569.78  4996.8  570.58
  5007.0  571.99  5017.2  572.51  5058.0  571.89  5175.9  572.57  5232.2  570.85
  5251.7  570.87  5334.5  573.89  5641.5  578.32  5789.9  581.78  5948.4  584.41
  5975.6  585.65  6016.3  585.60  6045.7  586.57  6050.8  586.14  6182.2  588.40
#Mann=6,-1,0
  3803.8     0.1       0  3953.9    0.05       0  4651.5     0.1       0
  4939.9    0.05       0  4990.8   0.035       0  4996.8    0.05       0
Bank Sta=4990.8,4996.8
Exp/Cntr=0.3,0.1

Type RM Length L Ch R = 1,7053,337,337,337
BEGIN DESCRIPTION:
UNT 020 in HW 12.0
END DESCRIPTION:
XS GIS Cut Line= 3
      1988424.99     13556225.03      1988125.00     13556925.00
      1987823.51     13558200.82
#Sta/Elev= 30
  4271.6  584.69  4432.9  582.63  4619.7  579.19  4892.3  571.13  4924.3  571.25
  4935.2  570.71  4957.0  571.23  5000.5  569.61  5018.6  570.61  5024.1  569.99
  5043.4  570.24  5048.7  569.53  5049.2  568.73  5054.2  568.73  5054.7  569.53
  5060.9  569.80  5115.3  570.54  5218.1  569.77  5315.7  571.91  5363.2  572.00
  5400.3  573.12  5490.1  573.34  5532.3  574.29  5838.7  578.01  5881.0  579.20
  6013.0  580.74  6081.2  582.39  6112.1  582.22  6271.9  584.80  6344.1  585.11
#Mann=5,-1,0
  4271.6    0.05       0  4892.3     0.1       0  5048.7    0.07       0
  5054.7     0.1       0  5060.9    0.05       0
Bank Sta=5048.7,5054.7
Exp/Cntr=0.3,0.1

Type RM Length L Ch R = 1,6716,418,418,418
BEGIN DESCRIPTION:
UNT 020 in HW 11.0
END DESCRIPTION:
XS GIS Cut Line= 3
      1988025.00     13556024.99      1987825.00     13556925.00
      1987538.64     13558250.05
#Sta/Elev= 30
  4099.0  584.98  4105.6  584.92  4140.0  583.85  4160.5  584.01  4416.6  579.25
  4540.8  577.66  4671.4  574.76  4778.3  571.48  4867.3  568.75  4909.6  567.94
  4969.7  568.01  4993.6  566.94  4994.1  566.14  4999.1  566.14  4999.6  566.94
  5009.3  567.68  5018.4  569.54  5082.3  569.62  5144.1  570.68  5307.4  570.63
  5440.4  571.27  5808.7  575.50  5870.1  575.23  5896.2  576.42  5994.7  578.23
  6033.7  579.55  6088.1  579.75  6225.6  583.15  6230.7  582.81  6376.6  585.70
#Mann=6,-1,0
  4099.0     0.1       0  4105.6    0.05       0  4778.3     0.1       0
  4993.6    0.07       0  4999.6     0.1       0  5009.3    0.05       0
Bank Sta=4993.6,4999.6
Exp/Cntr=0.3,0.1

Type RM Length L Ch R = 1,6298,454,454,454
BEGIN DESCRIPTION:
UNT 020 in HW 10.0
END DESCRIPTION:
XS GIS Cut Line= 3
      1987775.02     13556174.96      1987281.67     13557125.15
      1987177.51     13558250.11
#Sta/Elev= 30
  4403.3  579.70  4527.8  576.93  4715.6  573.74  4752.6  572.62  4782.0  570.94
  4843.8  569.78  4981.0  564.94  4986.3  564.15  4986.8  563.35  4991.8  563.35
  4992.3  564.15  4997.5  564.94  5019.6  565.86  5063.9  566.17  5079.4  565.79
  5101.9  566.46  5124.5  566.30  5147.7  567.10  5180.8  567.61  5301.5  567.88
  5434.2  566.71  5554.1  567.03  5574.2  566.65  5744.9  568.02  5935.7  570.49
  6126.6  574.97  6227.0  576.86  6267.2  576.98  6327.4  578.71  6603.7  582.05
#Mann=5,-1,0
  4403.3    0.05       0  4843.8     0.1       0  4986.3    0.07       0
  4992.3     0.1       0  5147.7    0.05       0
Bank Sta=4986.3,4992.3
Exp/Cntr=0.3,0.1

Type RM Length L Ch R = 1,5844,452,452,452
BEGIN DESCRIPTION:
UNT 020 in HW 9.0
END DESCRIPTION:
XS GIS Cut Line= 4
      1987624.99     13556075.01      1987288.61     13556340.43
      1986830.28     13556882.10      1987135.83     13558277.90
#Sta/Elev= 30
  4328.9  578.35  4350.6  578.71  4356.9  578.06  4371.4  577.72  4406.6  577.62
  4592.6  573.34  4677.6  570.95  4845.5  565.26  4897.7  564.19  4961.5  563.74
  4997.8  562.90  5009.1  562.16  5009.6  561.36  5014.6  561.36  5015.1  562.16
  5025.4  563.14  5061.5  564.33  5110.9  564.55  5231.8  564.20  5344.9  562.66
  5416.4  562.96  5465.6  562.25  5558.0  562.46  5563.2  562.87  5656.0  563.41
  5736.1  563.00  5910.1  565.14  6014.9  567.21  6647.1  579.63  6895.8  582.62
#Mann=5,-1,0
  4328.9    0.05       0  4845.5     0.1       0  5009.1    0.07       0
  5015.1     0.1       0  6014.9    0.05       0
Bank Sta=5009.1,5015.1
Exp/Cntr=0.3,0.1

Type RM Length L Ch R = 1,5392,0,0,0
BEGIN DESCRIPTION:
UNT 020 in HW 8.0
END DESCRIPTION:
XS GIS Cut Line= 4
      1987725.04     13555874.99      1987385.84     13555937.65
      1986413.61     13556437.65      1986925.01     13558175.05
#Sta/Elev= 30
  4137.1  583.86  4274.6  581.38  4421.9  577.28  4494.2  574.05  4532.2  573.60
  4629.2  569.85  4681.9  566.83  4734.1  565.83  4811.0  563.23  4920.2  561.31
  4942.4  561.72  4979.3  560.14  5021.0  560.24  5103.2  560.45  5154.6  558.23
  5155.1  557.43  5160.2  557.43  5160.7  558.23  5164.2  559.17  5275.0  562.26
  5380.3  561.80  5469.0  559.30  5571.7  562.33  5742.1  562.78  5985.9  566.07
  6156.3  565.53  6469.0  560.72  6583.7  562.81  6814.9  569.29  7386.4  578.79
#Mann=8,-1,0
  4137.1     0.1       0  4734.1    0.05       0  4811.0     0.1       0
  4979.3    0.12       0  5021.0     0.1       0  5154.6    0.07       0
  5160.7     0.1       0  6814.9    0.05       0
Bank Sta=5154.6,5160.7
Exp/Cntr=0.3,0.1

Chan Stop Cuts=-1