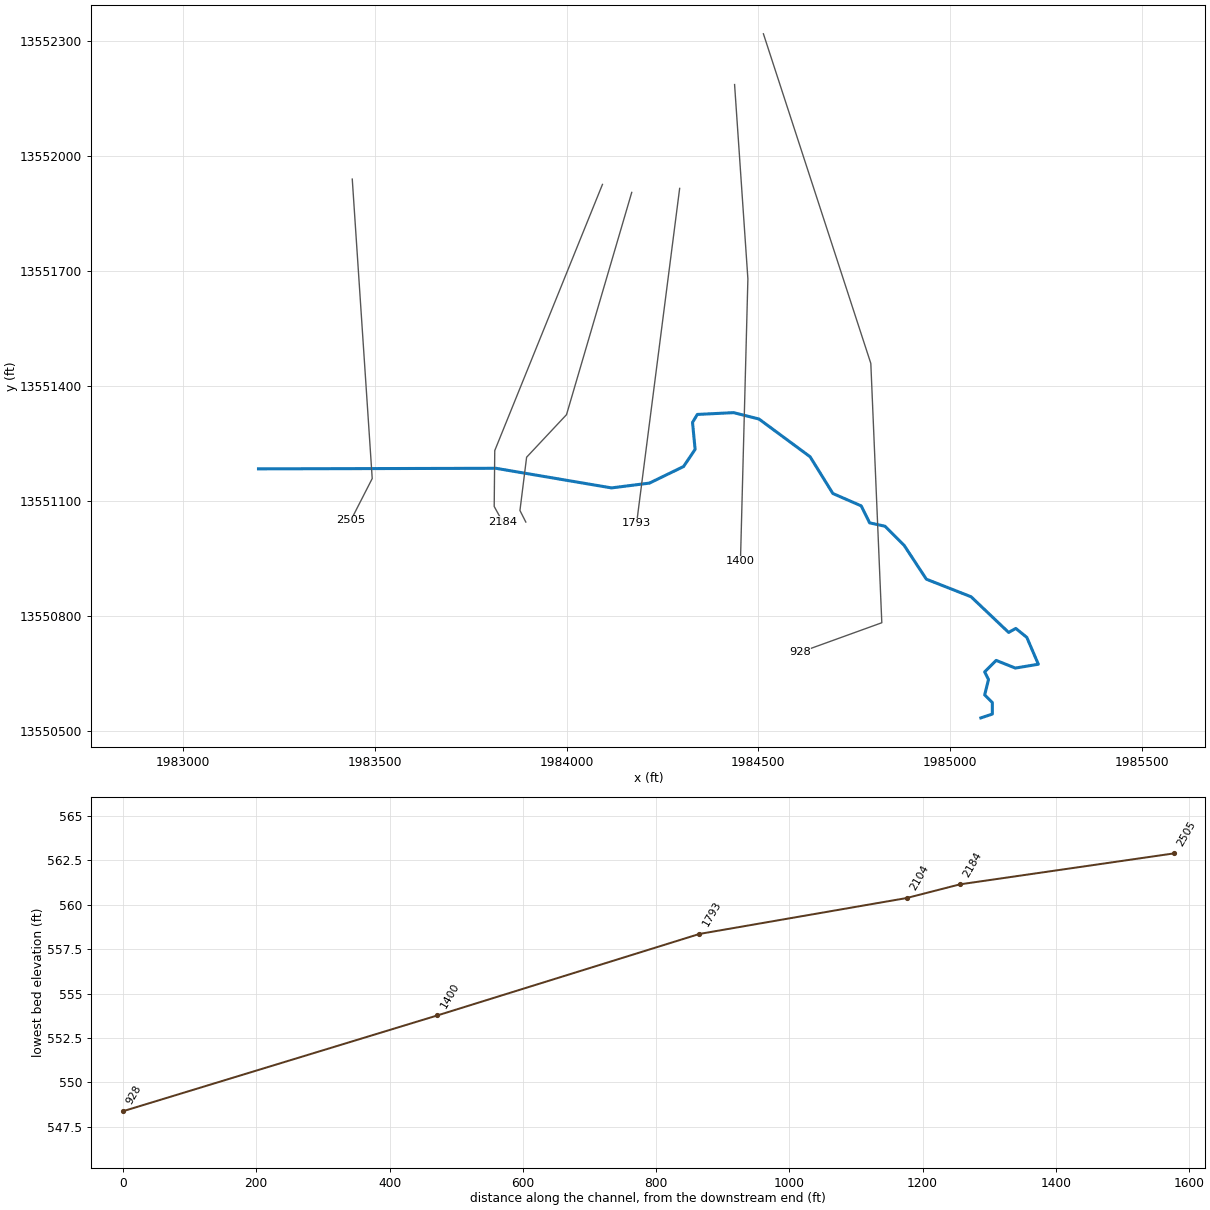
--- UNT 022 in HW.prj (project) ---

Proj Title=UNT 022 in HW Base Level Engineering
Current Plan=p01
Default Exp/Contr=0.3,0.1
English Units
Geom File=g01
Flow File=f01
Plan File=p01
BEGIN DESCRIPTION:
UNT 022 in HW
END DESCRIPTION:

--- UNT 022 in HW.p01 (plan) ---

Plan Title=Multiple Run
Short Identifier=Multiple
Geom File=g01
Flow File=f01
Subcritical Flow
K Sum by GR= 0
Std Step Tol= 0.01
Critical Tol= 0.01
Num of Std Step Trials= 20
Max Error Tol= 0.3
Flow Tol Ratio= 0.001
Split Flow NTrial= 30
Split Flow Tol= 0.02
Split Flow Ratio= 0.02
Log Output Level= 0
Friction Slope Method= 1
Unsteady Friction Slope Method= 2
Unsteady Bridges Friction Slope Method= 1
Parabolic Critical Depth
Global Vel Dist=  1 , 1 , 1
Global Log Level= 0
CheckData=True
Encroach Param= -1, 0, 0, 0
BEGIN DESCRIPTION:
Multiple Run
END DESCRIPTION:

--- UNT 022 in HW.f01 (steady flow) ---

Flow Title=Multiple
Number of Profiles=7
Profile Names=10-year,25-year,50-year,1pct_min,100-year,1pct_plu,500-year
River Rch & RM= UNT 022 in HW,Reach-1,2505
     443     616     758     462     921    1838    1368
River Rch & RM= UNT 022 in HW,Reach-1,1793
     514     722     895     549    1096    2186    1649
Boundary for River Rch & Prof#=UNT 022 in HW,Reach-1,1
Up Type=0
Dn Type=3
Dn Slope=0.005
Boundary for River Rch & Prof#=UNT 022 in HW,Reach-1,2
Up Type=0
Dn Type=3
Dn Slope=0.005
Boundary for River Rch & Prof#=UNT 022 in HW,Reach-1,3
Up Type=0
Dn Type=3
Dn Slope=0.005
Boundary for River Rch & Prof#=UNT 022 in HW,Reach-1,4
Up Type=0
Dn Type=3
Dn Slope=0.005
Boundary for River Rch & Prof#=UNT 022 in HW,Reach-1,5
Up Type=0
Dn Type=3
Dn Slope=0.005
Boundary for River Rch & Prof#=UNT 022 in HW,Reach-1,6
Up Type=0
Dn Type=3
Dn Slope=0.005
Boundary for River Rch & Prof#=UNT 022 in HW,Reach-1,7
Up Type=0
Dn Type=3
Dn Slope=0.005

--- UNT 022 in HW.g01 (geometry) ---

Geom Title=Existing Conditions

River Reach=UNT 022 in HW,Reach-1
Reach XY= 30
      1983196.22     13551184.29      1983815.61     13551185.76
      1984117.13     13551134.59      1984216.08     13551147.09
      1984305.15     13551190.32      1984335.35     13551235.11
      1984328.58     13551305.42      1984341.08     13551326.26
      1984435.88     13551330.94      1984502.02     13551314.28
      1984635.35     13551215.84      1984694.73     13551120.01
      1984768.69     13551087.71      1984790.56     13551043.44
      1984830.80     13551034.54      1984880.80     13550984.54
      1984938.65     13550896.44      1985055.32     13550850.61
      1985153.24     13550757.55      1985171.99     13550767.97
      1985200.80     13550744.54      1985230.80     13550674.54
      1985170.80     13550664.54      1985120.80     13550684.54
      1985090.80     13550654.54      1985100.80     13550634.54
      1985090.80     13550594.54      1985110.80     13550574.54
      1985110.80     13550544.54      1985080.80     13550534.54

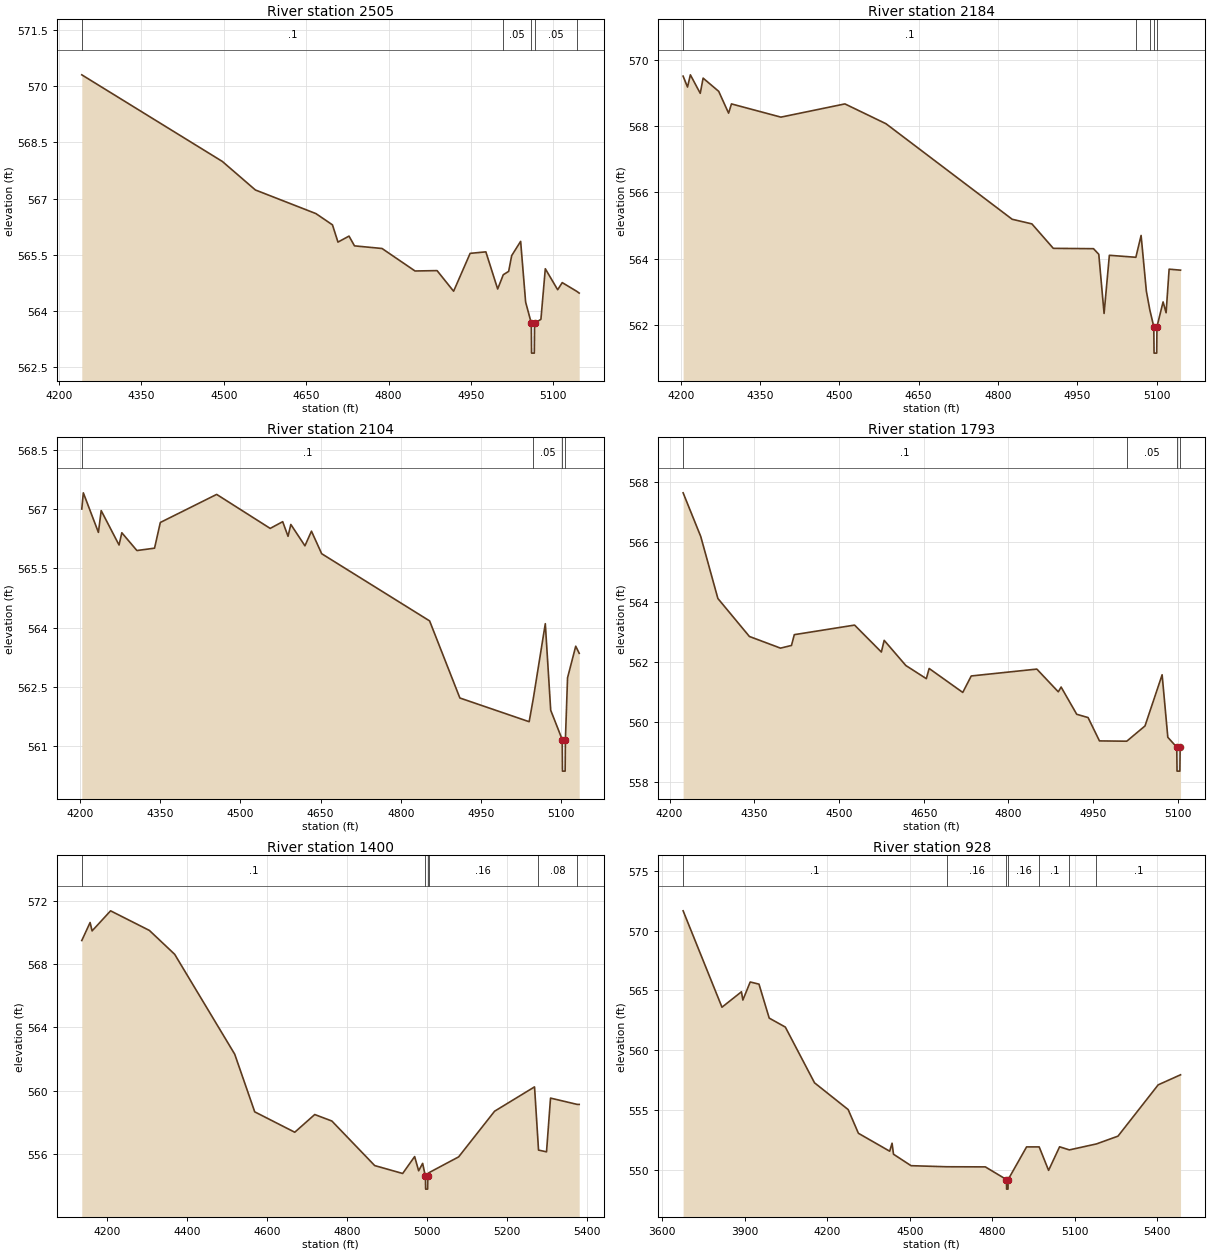
Type RM Length L Ch R = 1,2505,321,321,321
BEGIN DESCRIPTION:
UNT 022 in HW 2.0
END DESCRIPTION:
XS GIS Cut Line= 3
      1983440.84     13551940.30      1983492.92     13551159.06
      1983437.19     13551050.06
#Sta/Elev= 30
  4241.6  570.30  4497.5  567.99  4557.6  567.23  4667.8  566.60  4697.9  566.30
  4707.9  565.84  4728.0  566.00  4738.0  565.74  4788.1  565.67  4848.2  565.07
  4888.3  565.08  4918.4  564.53  4948.5  565.54  4977.1  565.58  4998.6  564.59
  5008.8  564.97  5018.6  565.06  5024.1  565.48  5040.4  565.86  5049.5  564.24
  5059.8  563.68  5060.3  562.88  5065.3  562.88  5065.8  563.68  5077.3  563.78
  5085.3  565.13  5107.8  564.57  5116.1  564.76  5142.3  564.53  5147.0  564.48
#Mann=5,-1,0
  4241.6     0.1       0  5008.8    0.05       0  5059.8    0.07       0
  5065.8    0.05       0  5142.3     0.1       0
Bank Sta=5059.8,5065.8
Exp/Cntr=0.3,0.1

Type RM Length L Ch R = 1,2184,80,80,80
BEGIN DESCRIPTION:
Mapping XS f393f3c9
END DESCRIPTION:
XS GIS Cut Line= 4
      1984093.62     13551926.44      1983812.60     13551231.90
      1983811.18     13551086.12      1983833.21     13551046.10
#Sta/Elev= 30
  4204.6  569.52  4212.9  569.19  4218.3  569.56  4237.0  569.00  4242.4  569.46
  4271.9  569.06  4290.6  568.40  4296.0  568.68  4389.5  568.28  4510.6  568.68
  4588.3  568.08  4826.9  565.19  4864.2  565.05  4904.7  564.31  4980.7  564.30
  4990.7  564.13  5000.7  562.34  5010.7  564.10  5060.8  564.04  5070.7  564.70
  5080.7  563.01  5087.3  562.44  5094.7  561.94  5095.2  561.14  5100.2  561.14
  5100.7  561.94  5112.3  562.69  5118.0  562.36  5123.7  563.68  5145.3  563.65
#Mann=5,-1,0
  4204.6     0.1       0  5060.8    0.05       0  5087.3    0.08       0
  5094.7    0.07       0  5100.7    0.05       0
Bank Sta=5094.7,5100.7
Exp/Cntr=0.3,0.1

Type RM Length L Ch R = 1,2104,311,311,311
BEGIN DESCRIPTION:
Mapping XS 08fa7708
END DESCRIPTION:
XS GIS Cut Line= 5
      1984169.99     13551905.55      1983999.86     13551325.72
      1983895.70     13551214.61      1983878.34     13551075.72
      1983893.61     13551045.51
#Sta/Elev= 30
  4203.4  567.00  4206.3  567.41  4234.5  566.41  4239.7  566.96  4273.1  566.09
  4278.3  566.40  4306.5  565.95  4339.5  566.01  4350.3  566.66  4455.7  567.37
  4555.8  566.51  4579.2  566.68  4589.2  566.31  4594.4  566.61  4620.8  566.07
  4633.0  566.44  4652.1  565.87  4854.0  564.17  4910.6  562.22  5040.2  561.62
  5048.0  562.21  5070.4  564.10  5080.5  561.91  5102.0  561.17  5102.5  560.37
  5107.5  560.37  5108.0  561.17  5112.0  562.73  5127.3  563.53  5133.8  563.35
#Mann=4,-1,0
  4203.4     0.1       0  5048.0    0.05       0  5102.0    0.07       0
  5108.0    0.05       0
Bank Sta=5102,5108
Exp/Cntr=0.3,0.1

Type RM Length L Ch R = 1,1793,393,393,393
BEGIN DESCRIPTION:
Mapping XS cc569aa5
END DESCRIPTION:
XS GIS Cut Line= 2
      1984295.00     13551915.98      1984182.75     13551042.66
#Sta/Elev= 30
  4224.1  567.65  4255.3  566.19  4285.6  564.12  4341.4  562.85  4396.5  562.46
  4415.9  562.55  4420.9  562.91  4527.6  563.23  4575.0  562.33  4580.0  562.72
  4618.3  561.88  4654.6  561.44  4659.6  561.78  4719.1  560.98  4734.1  561.53
  4850.2  561.76  4888.2  561.00  4893.2  561.16  4920.8  560.25  4940.9  560.14
  4961.1  559.36  5009.4  559.35  5041.7  559.86  5072.0  561.57  5082.1  559.48
  5097.9  559.15  5098.4  558.35  5103.4  558.35  5103.9  559.15  5104.6  559.15
#Mann=4,-1,0
  4224.1     0.1       0  5009.4    0.05       0  5097.9    0.07       0
  5103.9    0.05       0
Bank Sta=5097.9,5103.9
Exp/Cntr=0.3,0.1

Type RM Length L Ch R = 1,1400,472,472,472
BEGIN DESCRIPTION:
Mapping XS fa673ca0
END DESCRIPTION:
XS GIS Cut Line= 3
      1984438.32     13552186.93      1984473.04     13551679.95
      1984453.65     13550943.27
#Sta/Elev= 30
  4135.7  569.50  4156.5  570.64  4161.5  570.11  4207.8  571.38  4304.9  570.14
  4368.2  568.63  4518.5  562.31  4568.6  558.66  4668.8  557.37  4718.8  558.49
  4761.7  558.08  4868.9  555.26  4938.9  554.76  4968.9  555.83  4978.9  554.93
  4988.9  555.40  4995.9  554.57  4996.4  553.77  5001.4  553.77  5001.9  554.57
  5003.9  554.80  5079.0  555.81  5169.0  558.70  5269.0  560.24  5277.3  556.92
  5279.0  556.24  5299.0  556.13  5309.0  559.53  5376.0  559.13  5380.8  559.13
#Mann=6,-1,0
  4135.7     0.1       0  4995.9    0.07       0  5001.9     0.1       0
  5003.9    0.16       0  5277.3    0.08       0  5376.0     0.1       0
Bank Sta=4995.9,5001.9
Exp/Cntr=0.3,0.1

Type RM Length L Ch R = 1,928,0,0,0
BEGIN DESCRIPTION:
UNT 022 in HW 1.0
END DESCRIPTION:
XS GIS Cut Line= 4
      1984513.54     13552319.32      1984793.75     13551459.38
      1984822.43     13550782.81      1984608.51     13550705.43
#Sta/Elev= 30
  3675.6  571.65  3816.9  563.59  3887.7  564.88  3892.9  564.19  3919.6  565.70
  3951.5  565.52  3988.7  562.68  4047.3  561.93  4153.5  557.27  4275.9  555.03
  4313.1  553.05  4426.9  551.55  4435.5  552.22  4440.7  551.30  4504.6  550.34
  4634.9  550.25  4774.6  550.24  4851.6  549.18  4852.1  548.38  4857.2  548.38
  4857.7  549.18  4924.7  551.91  4970.6  551.91  5004.8  549.95  5044.8  551.92
  5080.4  551.66  5178.9  552.16  5257.2  552.81  5403.4  557.10  5484.7  557.94
#Mann=7,-1,0
  3675.6     0.1       0  4634.9    0.16       0  4851.6    0.07       0
  4857.7    0.16       0  4970.6     0.1       0  5080.4    0.05       0
  5178.9     0.1       0
Bank Sta=4851.6,4857.7
Exp/Cntr=0.3,0.1

Chan Stop Cuts=-1