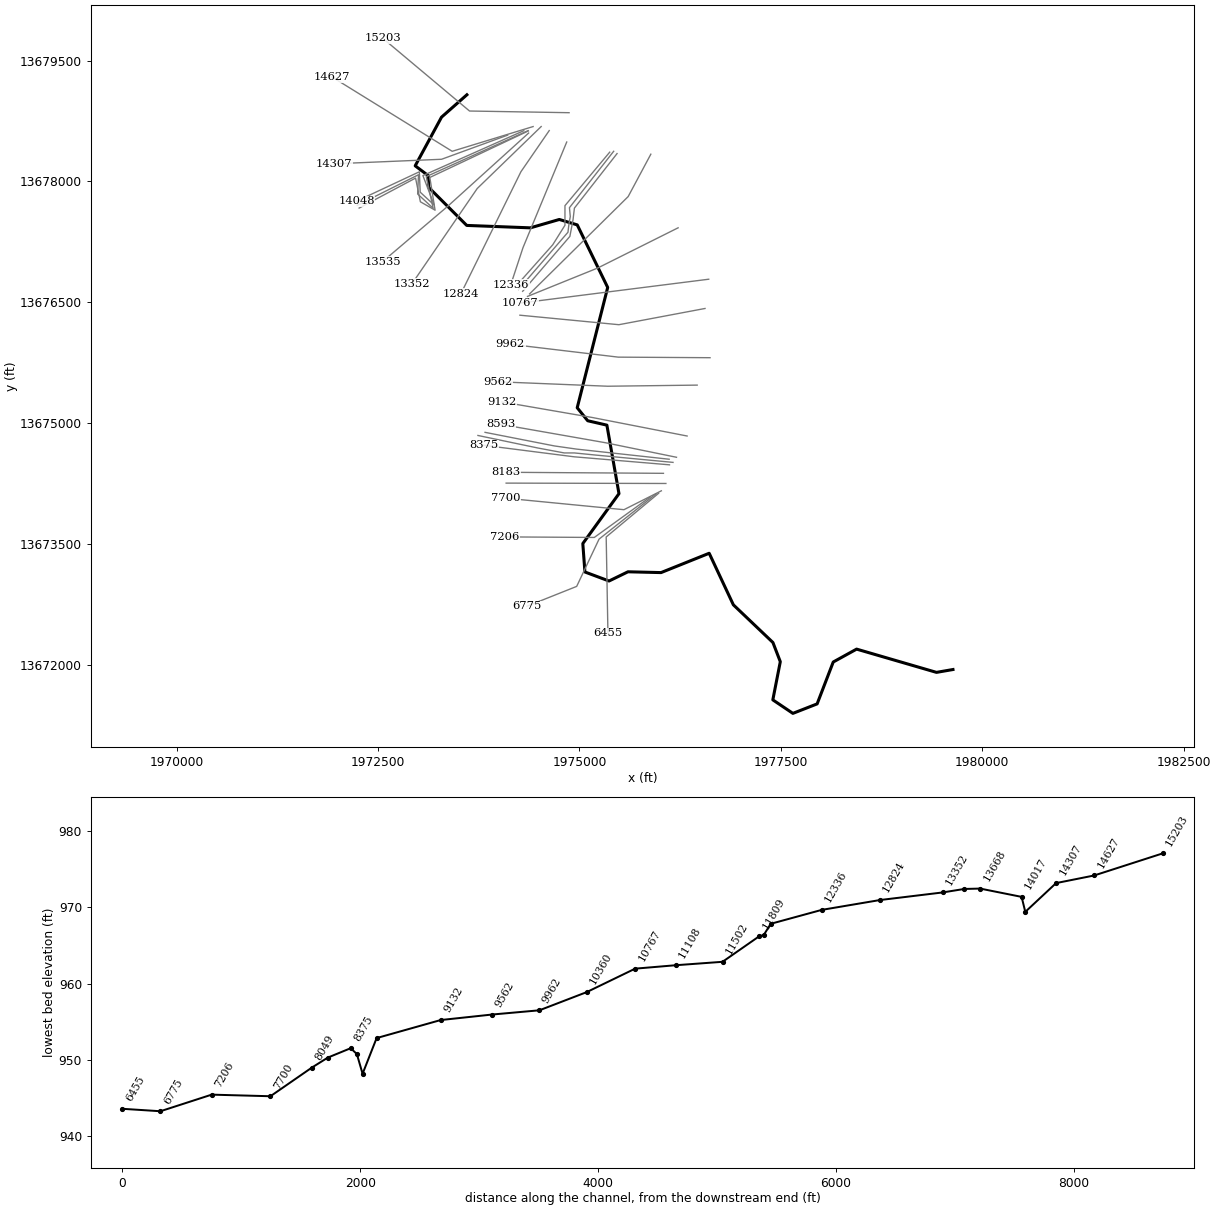
--- UNT 023 in HW.prj (project) ---

Proj Title=UNT 023 in HW Base Level Engineering
Current Plan=p01
Default Exp/Contr=0.3,0.1
English Units
Geom File=g01
Flow File=f01
Plan File=p01
Y Axis Title=Elevation
X Axis Title(PF)=Main Channel Distance
X Axis Title(XS)=Station
BEGIN DESCRIPTION:
UNT 023 in HW
END DESCRIPTION:
DSS Export Rating Curves= 0
DSS Export Rating Curve Sorted= 0
DSS Export Volume Flow Curves= 0
DXF OffsetX= 0
DXF OffsetY= 0
DXF ScaleX= 1
DXF ScaleY= 10

--- UNT 023 in HW.p01 (plan) ---

Plan Title=Multiple Run
Short Identifier=Multiple
Geom File=g01
Flow File=f01
Subcritical Flow
K Sum by GR= 0
Std Step Tol= 0.01
Critical Tol= 0.01
Num of Std Step Trials= 20
Max Error Tol= 0.3
Flow Tol Ratio= 0.001
Split Flow NTrial= 30
Split Flow Tol= 0.02
Split Flow Ratio= 0.02
Log Output Level= 0
Friction Slope Method= 1
Unsteady Friction Slope Method= 2
Unsteady Bridges Friction Slope Method= 1
Parabolic Critical Depth
Global Vel Dist=  1 , 1 , 1
Global Log Level= 0
CheckData=True
Encroach Param= -1, 0, 0, 0
BEGIN DESCRIPTION:
Multiple Run
END DESCRIPTION:

--- UNT 023 in HW.f01 (steady flow) ---

Flow Title=Multiple
Number of Profiles=7
Profile Names=10-year,25-year,50-year,1pct_min,100-year,1pct_plu,500-year
River Rch & RM= UNT 023 in HW,Reach-1,15203
     392     528     636     380     758    1512    1078
River Rch & RM= UNT 023 in HW,Reach-1,14307
     616     852    1045     633    1264    2521    1855
River Rch & RM= UNT 023 in HW,Reach-1,11502
     849    1195    1483     909    1813    3617    2721
River Rch & RM= UNT 023 in HW,Reach-1,7206
    1000    1420    1773    1092    2179    4348    3308
River Rch & RM= UNT 023 in HW,Reach-1,5061
    1156    1654    2075    1284    2562    5112    3924
Boundary for River Rch & Prof#=UNT 023 in HW,Reach-1,1
Up Type=0
Dn Type=3
Dn Slope=0.005
Boundary for River Rch & Prof#=UNT 023 in HW,Reach-1,2
Up Type=0
Dn Type=3
Dn Slope=0.005
Boundary for River Rch & Prof#=UNT 023 in HW,Reach-1,3
Up Type=0
Dn Type=3
Dn Slope=0.005
Boundary for River Rch & Prof#=UNT 023 in HW,Reach-1,4
Up Type=0
Dn Type=3
Dn Slope=0.005
Boundary for River Rch & Prof#=UNT 023 in HW,Reach-1,5
Up Type=0
Dn Type=3
Dn Slope=0.005
Boundary for River Rch & Prof#=UNT 023 in HW,Reach-1,6
Up Type=0
Dn Type=3
Dn Slope=0.005
Boundary for River Rch & Prof#=UNT 023 in HW,Reach-1,7
Up Type=0
Dn Type=3
Dn Slope=0.005

--- UNT 023 in HW.g01 (geometry) ---

Geom Title=Existing Conditions
Program Version=5.05

River Reach=UNT 023 in HW   ,Reach-1
Reach XY= 30
       1973602.7     13679076.44      1973287.81     13678798.61
       1972960.8     13678194.54       1973120.8     13678074.54
       1973130.8     13677924.54       1973600.8     13677454.54
       1974390.8     13677424.54      1974750.28     13677528.44
      1974972.72     13677461.17       1975350.8     13676684.54
      1974972.29     13675191.12       1975102.5     13675029.66
      1975340.78     13674974.97       1975490.8     13674124.54
      1975041.89     13673504.94      1975067.93     13673152.08
      1975367.41      13673040.1      1975602.65     13673154.54
      1976013.07     13673144.54       1976610.8     13673384.54
       1976910.8     13672744.54      1977401.95     13672276.64
      1977493.62     13672038.45       1977400.8     13671564.54
      1977649.87     13671396.78       1977950.8     13671514.54
       1978150.8     13672034.54       1978440.8     13672194.54
      1979432.51     13671905.81      1979637.37     13671941.23

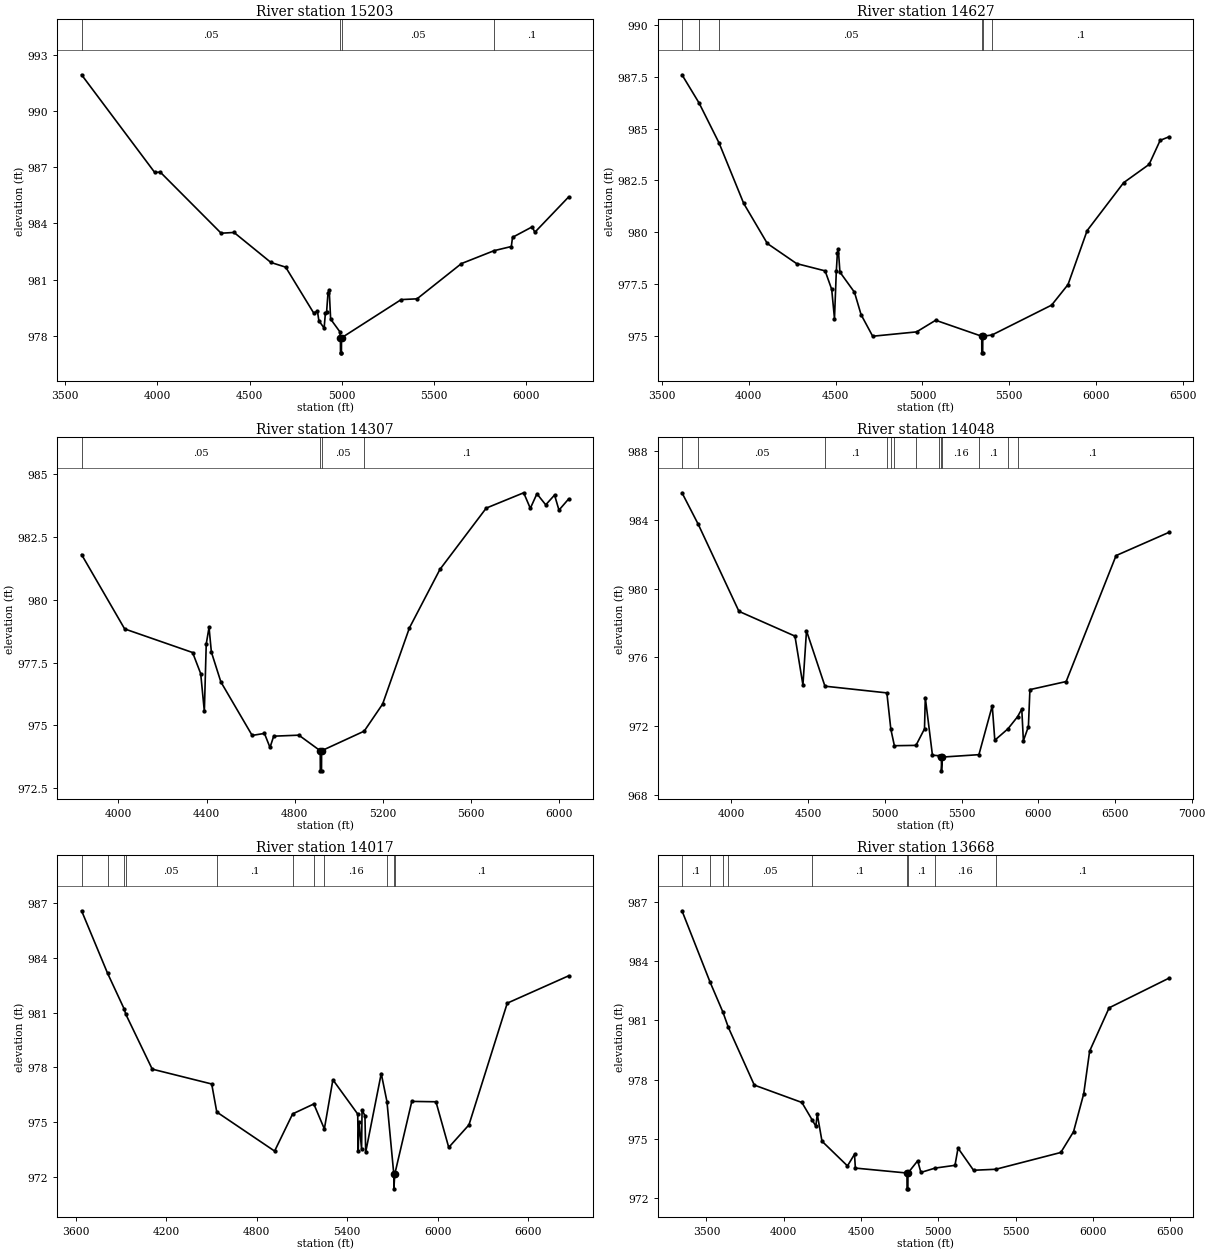
Type RM Length L Ch R = 1 ,15203   ,576,576,576
BEGIN DESCRIPTION:
UNT 023 in HW 28.0
END DESCRIPTION:
XS GIS Cut Line= 3
      1974871.55     13678853.99      1973635.42     13678874.83
      1972559.54     13679777.17
#Sta/Elev= 30
  3588.9  991.92  3985.5  986.71  4015.5  986.73  4345.6  983.47  4415.6  983.51
  4615.6  981.91  4695.6  981.66  4847.1  979.22  4867.9   979.3  4875.7   978.8
  4904.1  978.41  4910.8  979.19  4917.4  979.26  4925.1  980.28  4931.7  980.43
  4939.4  978.89  4988.9  978.22  4992.4  977.89  4992.9  977.09  4997.9  977.09
  4998.4  977.89    5322  979.93  5407.8  979.97  5648.5  981.85  5825.9  982.54
  5919.1  982.76  5925.6  983.25  6032.3  983.81  6046.6  983.52  6229.4   985.4
#Mann= 4 ,-1 , 0
  3588.9     .05       0  4992.4    .035       0  4998.4     .05       0
  5825.9      .1       0
Bank Sta=4992.4,4998.4
XS Rating Curve= 0 ,0
Exp/Cntr=0.3,0.1

Type RM Length L Ch R = 1 ,14627   ,320,320,320
BEGIN DESCRIPTION:
UNT 023 in HW 27.0
END DESCRIPTION:
XS GIS Cut Line= 3
      1974424.98     13678681.94      1973420.14     13678374.83
       1971928.5     13679297.56
#Sta/Elev= 30
    3615  987.59  3713.4  986.23  3828.7   984.3  3970.5  981.39  4106.4  979.46
  4275.3  978.49  4439.3  978.14  4477.3  977.25  4493.3  975.84  4503.8  978.12
  4510.1  979.01  4515.3  979.19  4524.7  978.08  4608.4  977.11  4646.5  976.03
  4713.3  974.99  4966.2   975.2  5076.1  975.76  5341.4  974.99  5341.9  974.19
  5346.9  974.19  5347.4  974.99  5400.5  975.05  5743.9  976.49  5838.4  977.48
  5948.4  980.08  6158.7  982.39  6305.3  983.27  6369.1  984.43  6419.7   984.6
#Mann= 6 ,-1 , 0
    3615     .05       0  3713.4      .1       0  3828.7     .05       0
  5341.4    .035       0  5347.4     .05       0  5400.5      .1       0
Bank Sta=5341.4,5347.4
XS Rating Curve= 0 ,0
Exp/Cntr=0.3,0.1

Type RM Length L Ch R = 1 ,14307   ,259,259,259
BEGIN DESCRIPTION:
Mapping XS 13fe2794
END DESCRIPTION:
XS GIS Cut Line= 3
      1974108.67     13678575.29      1973288.33      13678275.8
      1971951.52     13678219.38
#Sta/Elev= 30
  3832.5   981.8  4028.1  978.84  4336.7   977.9  4373.4  977.06    4390  975.56
  4398.6  978.24  4411.3   978.9  4421.9  977.92    4465  976.73  4607.1   974.6
  4662.9  974.68  4688.1  974.12  4704.9  974.57  4819.2  974.61  4916.2  973.99
  4916.7  973.19    4922  973.19  4922.5  973.99  5115.8  974.77  5199.6  975.85
  5321.2  978.88  5459.8  981.21    5670  983.65  5840.1  984.26  5870.2  983.64
  5900.2  984.22  5940.2  983.78  5980.3  984.17  6000.3  983.57  6043.8  984.01
#Mann= 4 ,-1 , 0
  3832.5     .05       0  4916.2    .035       0  4922.5     .05       0
  5115.8      .1       0
Bank Sta=4916.2,4922.5
XS Rating Curve= 0 ,0
Exp/Cntr=0.3,0.1

Type RM Length L Ch R = 1 ,14048   ,31,31,31
BEGIN DESCRIPTION:
Mapping XS a492ebb9
END DESCRIPTION:
XS GIS Cut Line= 6
      1974309.26     13678630.78      1973056.67     13678073.49
      1973197.29      13677706.3      1973022.81     13677867.76
       1973012.4     13678120.37      1972233.73     13677755.77
#Sta/Elev= 30
  3678.4  985.57  3784.8  983.73  4049.5  978.68  4414.6  977.24  4466.6   974.4
  4489.8  977.55  4610.1  974.33  5013.6  973.94  5039.5  971.83  5062.6  970.87
  5203.4  970.89  5258.9  971.85    5264  973.67  5310.6  970.32    5351  970.29
    5369  970.21  5369.5  969.41  5375.3  970.21  5613.5  970.35  5700.4  973.19
  5717.1  971.19  5802.5  971.85    5865  972.55  5892.8     973  5903.3  971.16
    5936  971.98  5945.9  974.13  6182.1   974.6  6507.3  981.92    6852  983.27
#Mann= 13 ,-1 , 0
  3678.4      .1       0  3784.8     .05       0  4610.1      .1       0
  5013.6     .16       0  5039.5      .1       0  5062.6     .16       0
  5203.4      .1       0    5351     .16       0    5369     .07       0
  5375.3     .16       0  5613.5      .1       0  5802.5     .16       0
    5865      .1       0
Bank Sta=5369,5375.3
XS Rating Curve= 0 ,0
Exp/Cntr=0.3,0.1

Type RM Length L Ch R = 1 ,14017   ,349,349,349
BEGIN DESCRIPTION:
Mapping XS 8c8b6ba7
END DESCRIPTION:
XS GIS Cut Line= 6
      1974361.39      13678630.8      1973098.33     13678060.47
      1973184.27     13677667.24      1972991.56     13677844.32
      1973001.98     13678083.91      1972241.53     13677703.68
#Sta/Elev= 30
  3638.8  986.55  3810.7  983.15  3922.5  981.17  3931.1  980.92  4107.3  977.91
  4501.6   977.1  4535.3  975.57  4918.6  973.44  5038.4  975.47  5178.6  976.01
  5248.5  974.65  5305.1  977.33  5469.8  975.46    5473  973.47  5478.6  975.04
  5495.3  973.55  5498.5  975.68  5517.6  975.37  5522.6  973.38  5625.7  977.67
  5663.6  976.14    5709  972.18  5709.5  971.38  5715.3  972.18  5828.3  976.15
  5988.5  976.13  6073.2  973.64  6207.3  974.87  6461.2  981.51  6867.6     983
#Mann= 11 ,-1 , 0
  3638.8      .1       0  3810.7     .05       0  3922.5      .1       0
  3931.1     .05       0  4535.3      .1       0  5038.4     .16       0
  5178.6      .1       0  5248.5     .16       0  5663.6      .1       0
    5709     .07       0  5715.3      .1       0
Bank Sta=5709,5715.3
XS Rating Curve= 0 ,0
Exp/Cntr=0.3,0.1

Type RM Length L Ch R = 1 ,13668   ,133,133,133
BEGIN DESCRIPTION:
Mapping XS 0cf91959
END DESCRIPTION:
XS GIS Cut Line= 6
      1974366.59     13678628.19       1973142.6     13678050.05
      1973207.71      13677643.8      1973025.42     13677747.97
      1972965.52     13678042.24      1972265.15     13677669.92
#Sta/Elev= 30
  3341.5  986.54  3523.3  982.93    3607   981.4  3641.5  980.64  3809.4  977.72
  4117.4  976.84  4182.9  975.97  4207.5  975.64    4217  976.24  4247.5  974.88
  4412.4  973.63  4457.9  974.22  4463.5  973.52  4797.5  973.27    4798  972.47
  4803.3  972.47  4803.8  973.27  4866.8  973.89  4887.6   973.3  4979.5  973.52
  5108.1  973.66  5127.9  974.53  5228.2  973.41    5372  973.46    5793  974.31
  5875.3  975.36  5941.2  977.28  5979.5  979.44  6105.7  981.63  6492.8  983.13
#Mann= 9 ,-1 , 0
  3341.5      .1       0  3523.3     .05       0    3607      .1       0
  3641.5     .05       0  4182.9      .1       0  4797.5     .07       0
  4803.8      .1       0  4979.5     .16       0    5372      .1       0
Bank Sta=4797.5,4803.8
XS Rating Curve= 0 ,0
Exp/Cntr=0.3,0.1

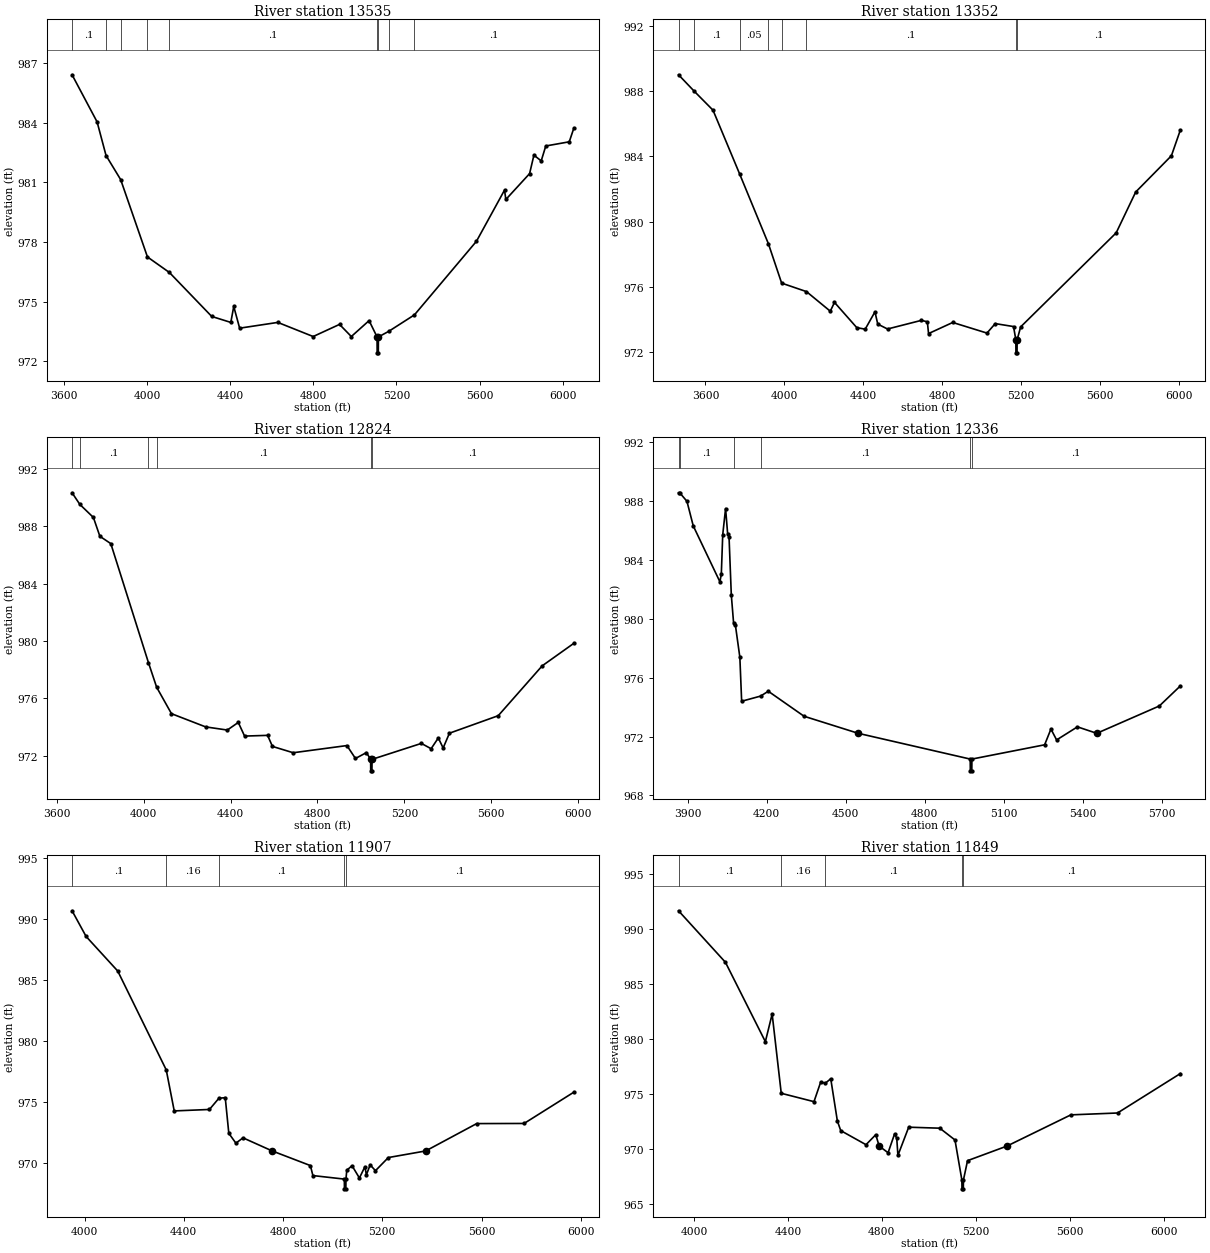
Type RM Length L Ch R = 1 ,13535   ,183,183,183
BEGIN DESCRIPTION:
Mapping XS b18ebe49
END DESCRIPTION:
XS GIS Cut Line= 3
      1974369.05     13678601.32      1973362.11     13677689.86
      1972554.84     13677004.12
#Sta/Elev= 30
  3637.1   986.4  3757.7  984.03  3800.8  982.34  3871.2  981.13  4000.3  977.24
    4106  976.46  4309.9  974.25  4401.8  973.95    4416  974.75  4444.4  973.66
  4628.3  973.95  4798.6  973.24  4925.6  973.85  4982.4  973.24    5068  974.04
  5106.4  973.22  5106.9  972.42  5112.4  972.42  5112.9  973.22  5162.5   973.5
  5286.6  974.33  5585.3  978.03  5720.4   980.6  5726.9  980.13  5841.2  981.43
  5862.1  982.36  5897.2  982.07  5919.2  982.82  6032.3  983.03  6054.5  983.72
#Mann= 9 ,-1 , 0
  3637.1      .1       0  3800.8     .05       0  3871.2      .1       0
  4000.3     .05       0    4106      .1       0  5106.4     .07       0
  5112.9      .1       0  5162.5     .16       0  5286.6      .1       0
Bank Sta=5106.4,5112.9
XS Rating Curve= 0 ,0
Exp/Cntr=0.3,0.1

Type RM Length L Ch R = 1 ,13352   ,528,528,528
BEGIN DESCRIPTION:
UNT 023 in HW 26.0
END DESCRIPTION:
XS GIS Cut Line= 3
      1974525.03     13678681.98       1973730.9     13677912.59
      1972919.29     13676727.72
#Sta/Elev= 30
    3464  988.99  3542.1     988  3638.7  986.82  3774.4  982.89  3919.3  978.64
  3986.3  976.23  4112.1  975.71  4232.7  974.51    4254  975.05  4367.2   973.5
  4409.6  973.41    4459  974.47  4473.2  973.72  4522.6  973.42  4694.6  973.95
  4724.4  973.86  4730.5  973.14    4853  973.82  5026.4  973.17  5068.3  973.75
    5161  973.57  5172.7  972.76  5173.2  971.96  5178.7  971.96  5179.2  972.76
  5197.1  973.55    5681  979.31  5779.8  981.81  5960.7  984.03  6005.9   985.6
#Mann= 8 ,-1 , 0
    3464     .05       0  3542.1      .1       0  3774.4     .05       0
  3919.3      .1       0  3986.3     .05       0  4112.1      .1       0
  5172.7     .07       0  5179.2      .1       0
Bank Sta=5172.7,5179.2
XS Rating Curve= 0 ,0
Exp/Cntr=0.3,0.1

Type RM Length L Ch R = 1 ,12824   ,488,488,488
BEGIN DESCRIPTION:
UNT 023 in HW 25.0
END DESCRIPTION:
XS GIS Cut Line= 3
      1974624.98     13678631.92      1974273.44     13678120.92
      1973527.61     13676605.23
#Sta/Elev= 30
  3670.5  990.32  3706.3  989.51  3768.7   988.6  3798.5  987.29  3848.8  986.78
  4022.1  978.49  4059.8  976.78    4128  974.94  4285.2  974.02    4385   973.8
  4435.5  974.33  4464.5  973.38  4570.4  973.43  4592.8  972.66  4688.3  972.22
  4935.5  972.72  4974.8  971.82  5025.3  972.23  5044.6  971.76  5045.1  970.96
  5050.6  970.96  5051.1  971.76  5278.1  972.87    5323   972.5  5356.1  973.25
  5378.4  972.55  5407.3  973.58    5632   974.8  5834.2  978.27    5980  979.84
#Mann= 6 ,-1 , 0
  3670.5     .05       0  3706.3      .1       0  4022.1     .05       0
  4059.8      .1       0  5044.6     .07       0  5051.1      .1       0
Bank Sta=5044.6,5051.1
XS Rating Curve= 0 ,0
Exp/Cntr=0.3,0.1

Type RM Length L Ch R = 1 ,12336   ,429,429,429
BEGIN DESCRIPTION:
UNT 023 in HW 24.0
END DESCRIPTION:
XS GIS Cut Line= 3
      1974842.02     13678489.87      1974299.48     13677179.08
      1974147.74     13676719.51
#Sta/Elev= 30
    3866  988.57  3870.5  988.57  3897.9  987.99  3921.8  986.32  4022.8  982.52
  4028.2  983.03  4033.6  985.73  4044.4   987.5  4052.1   985.8  4057.5  985.57
  4066.1  981.62  4074.7  979.73  4081.4   979.6  4098.5  977.39  4105.3   974.4
    4177  974.75  4206.3  975.08    4342  973.38 4547.42972.2199  4971.9  970.47
  4972.4  969.67  4977.9  969.67  4978.4  970.47  5254.1  971.44    5278  972.51
  5299.5  971.77  5378.5  972.66 5451.79  972.22  5689.1  974.08  5768.6  975.44
#Mann= 6 ,-1 , 0
    3866     .05       0  3870.5      .1       0  4074.7     .05       0
    4177      .1       0  4971.9     .07       0  4978.4      .1       0
Bank Sta=4547.42,5451.79
XS Rating Curve= 0 ,0
Exp/Cntr=0.3,0.1

Type RM Length L Ch R = 1 ,11907   ,58,58,58
BEGIN DESCRIPTION:
Mapping XS 8dfbb62e
END DESCRIPTION:
XS GIS Cut Line= 5
      1975375.86     13678363.97      1974820.31     13677699.91
      1974820.31     13677456.86       1974668.4      13677213.8
      1974251.77     13676745.08
#Sta/Elev= 30
  3949.6  990.68  4006.2  988.57  4133.7  985.73  4329.2  977.61  4361.4  974.24
  4503.3  974.36  4541.4  975.28    4567  975.33  4581.4   972.4    4610  971.59
  4638.6  972.03 4756.44970.9516  4910.3  969.75  4920.3  968.93    5047  968.64
  5047.5  967.84  5053.1  967.84  5053.6  968.64  5056.9  969.37  5078.1  969.74
  5107.8  968.73    5130  969.66  5135.9  968.99  5151.2  969.81  5172.5  969.33
  5224.4  970.41 5374.96970.9518  5580.6   973.2  5771.6  973.21  5972.2  975.78
#Mann= 5 ,-1 , 0
  3949.6      .1       0  4329.2     .16       0  4541.4      .1       0
    5047     .07       0  5053.6      .1       0
Bank Sta=4756.44,5374.96
XS Rating Curve= 0 ,0
Exp/Cntr=0.3,0.1

Type RM Length L Ch R = 1 ,11849   ,40,40,40
BEGIN DESCRIPTION:
UNT 023 in HW 23.0
END DESCRIPTION:
XS GIS Cut Line= 6
      1975424.98     13678374.97      1974875.87     13677674.74
      1974886.28     13677565.36      1974868.05     13677458.59
      1974857.64     13677370.05      1974243.78     13676659.09
#Sta/Elev= 30
  3934.5  991.64  4134.2  986.96  4304.2  979.75  4333.1  982.26  4371.8  975.06
  4511.2   974.3  4540.1   976.1  4559.2  975.97  4582.6  976.38  4610.7  972.55
  4625.1  971.67  4732.7  970.39  4774.3   971.3 4788.72970.2655  4826.7  969.66
  4854.2  971.36  4863.6  970.97  4868.6  969.42  4914.5  971.98  5046.9  971.89
  5111.5  970.82  5140.9  967.18  5141.4  966.38    5147  966.38  5147.5  967.18
    5165  968.94 5332.88970.2656  5604.9   973.1  5803.5  973.27    6071  976.85
#Mann= 5 ,-1 , 0
  3934.5      .1       0  4371.8     .16       0  4559.2      .1       0
  5140.9     .07       0  5147.5      .1       0
Bank Sta=4788.72,5332.88
XS Rating Curve= 0 ,0
Exp/Cntr=0.3,0.1

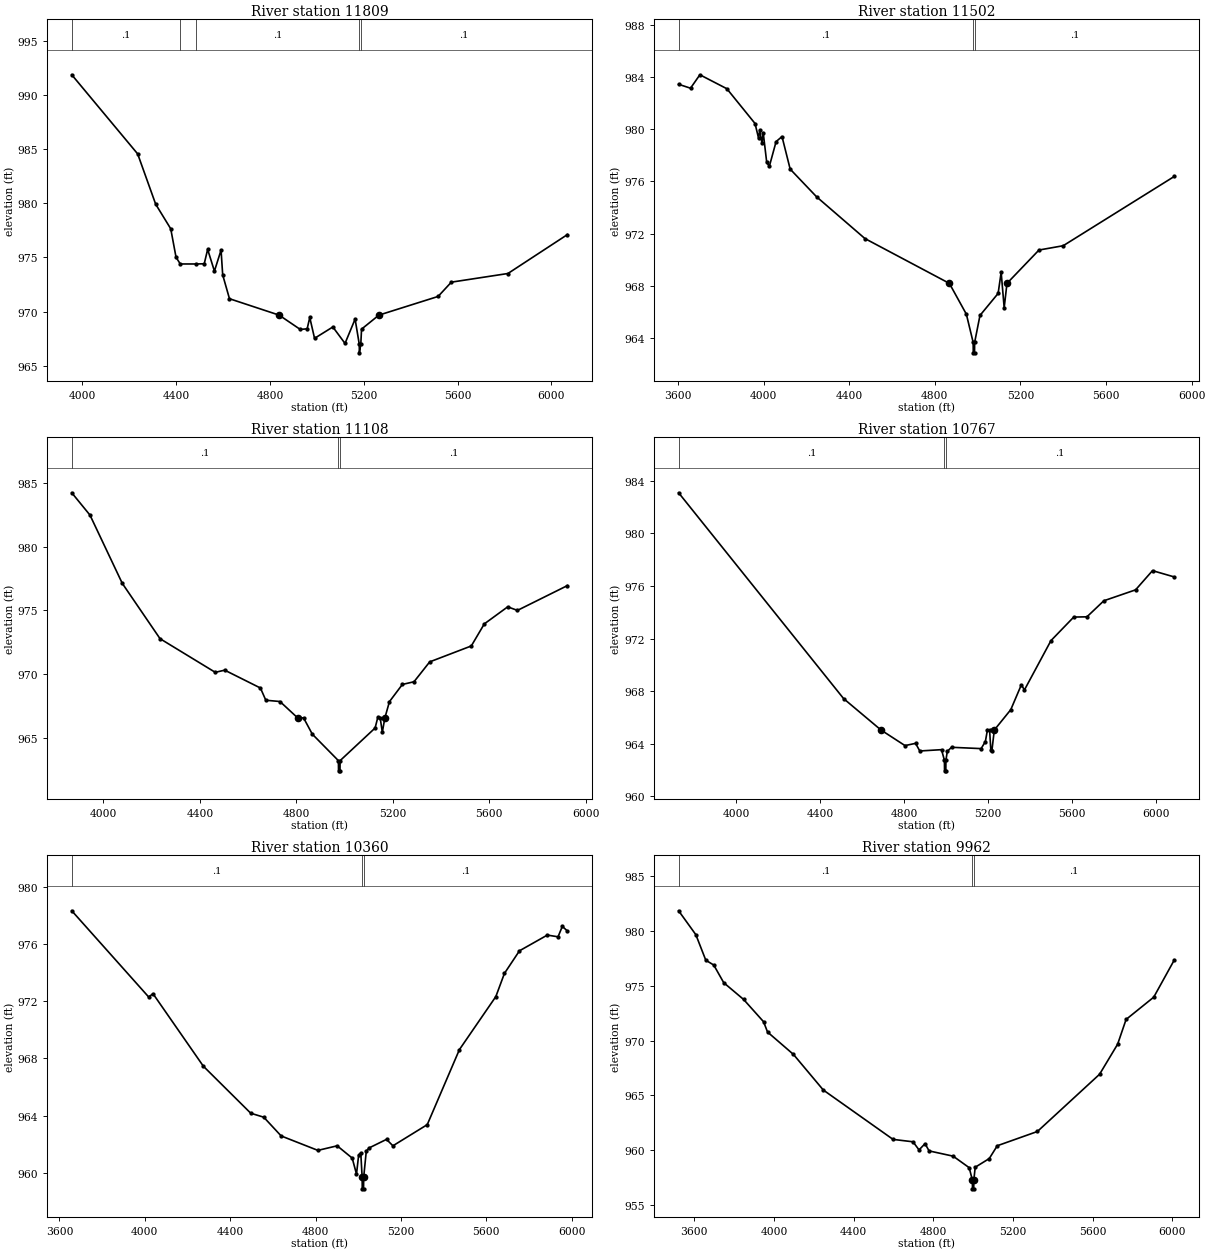
Type RM Length L Ch R = 1 ,11809   ,307,307,307
BEGIN DESCRIPTION:
Mapping XS e8ed93b0
END DESCRIPTION:
XS GIS Cut Line= 5
      1975466.99     13678346.59       1974937.5     13677669.53
      1974920.14     13677521.96      1974881.08     13677317.97
      1974295.14     13676636.55
#Sta/Elev= 30
  3954.5  991.88  4235.6  984.57  4312.5  979.92  4376.7  977.65  4399.3  975.02
  4417.4   974.4  4486.5   974.4  4519.6  974.42  4534.1  975.75    4563  973.74
  4591.3  975.68  4598.3  973.39  4627.2  971.19 4839.16969.6736  4929.3  968.35
  4958.6  968.41  4969.7  969.46  4990.1  967.53  5068.1  968.58  5120.1  967.06
  5163.1  969.31  5180.8  966.99  5181.3  966.19  5187.4  966.99  5190.6  968.38
 5264.51969.6736  5517.1   971.4  5573.6  972.72    5815  973.52    6069  977.12
#Mann= 5 ,-1 , 0
  3954.5      .1       0  4417.4     .16       0  4486.5      .1       0
  5180.8     .07       0  5187.4      .1       0
Bank Sta=4839.16,5264.51
XS Rating Curve= 0 ,0
Exp/Cntr=0.3,0.1

Type RM Length L Ch R = 1 ,11502   ,394,394,394
BEGIN DESCRIPTION:
UNT 023 in HW 22.0
END DESCRIPTION:
XS GIS Cut Line= 3
      1975886.29     13678338.81      1975605.03     13677812.76
       1974381.1     13676604.45
#Sta/Elev= 30
  3602.7  983.46  3658.3  983.16  3702.1  984.19  3828.1  983.12  3959.8  980.45
  3976.1  979.34  3981.7  979.93  3992.3  978.94    3998  979.75  4014.3  977.48
  4026.6  977.16  4058.2  979.06  4085.8  979.45    4124  976.95  4247.1  974.83
  4473.4  971.62 4867.89 968.181  4947.2  965.82  4979.1  963.65  4979.6  962.85
  4985.5  962.85    4986  963.65  5010.9  965.72  5095.7  967.41  5109.9  969.03
    5124  966.31 5137.07968.1802  5286.6  970.74  5399.8  971.07  5919.1  976.39
#Mann= 3 ,-1 , 0
  3602.7      .1       0  4979.1     .07       0    4986      .1       0
Bank Sta=4867.89,5137.07
XS Rating Curve= 0 ,0
Exp/Cntr=0.3,0.1

Type RM Length L Ch R = 1 ,11108   ,341,341,341
BEGIN DESCRIPTION:
UNT 023 in HW 21.0
END DESCRIPTION:
XS GIS Cut Line= 3
        1976225.       13677425.        1975225.       13676925.
      1974355.08     13676573.19
#Sta/Elev= 30
  3868.6  984.22  3944.1  982.47  4078.2  977.11  4234.8  972.77  4463.9  970.13
  4503.1   970.3  4651.2   968.9  4673.6  967.94  4732.3  967.84 4806.71966.5378
  4830.1  966.56  4866.4  965.28  4974.7   963.2  4975.2   962.4  4981.2   962.4
  4981.7   963.2  5126.9  965.76  5138.2   966.6  5148.4  966.51  5156.9  965.43
 5167.21966.5372  5186.4  967.83  5240.1  969.18  5288.3  969.39  5353.4  970.95
    5526   972.2  5579.9  973.93    5677  975.27  5717.4  974.99    5925  976.94
#Mann= 3 ,-1 , 0
  3868.6      .1       0  4974.7     .07       0  4981.7      .1       0
Bank Sta=4806.71,5167.21
XS Rating Curve= 0 ,0
Exp/Cntr=0.3,0.1

Type RM Length L Ch R = 1 ,10767   ,407,407,407
BEGIN DESCRIPTION:
UNT 023 in HW 20.0
END DESCRIPTION:
XS GIS Cut Line= 3
      1976605.05     13676786.72        1975325.       13676625.
      1974261.87     13676489.92
#Sta/Elev= 30
  3725.7  983.09  4511.9  967.44 4689.89965.0552  4804.3  963.87  4854.7  964.04
  4874.8  963.46  4978.3  963.56  4992.2  962.75  4992.7  961.95  4998.8  961.95
  4999.3  962.75  5005.8  963.43    5026  963.74  5167.1  963.64  5187.3  964.18
  5197.4  965.09  5207.5  965.03  5213.4  963.51  5218.4  963.49 5229.91965.0552
  5308.3   966.6  5358.7  968.49  5373.4   968.1  5499.8  971.85  5608.3  973.64
  5671.2  973.66  5751.8  974.88    5903  975.71  5983.6  977.17  6087.6  976.69
#Mann= 3 ,-1 , 0
  3725.7      .1       0  4992.2     .07       0  4999.3      .1       0
Bank Sta=4689.89,5229.91
XS Rating Curve= 0 ,0
Exp/Cntr=0.3,0.1

Type RM Length L Ch R = 1 ,10360   ,398,398,398
BEGIN DESCRIPTION:
UNT 023 in HW 19.0
END DESCRIPTION:
XS GIS Cut Line= 3
      1976559.03     13676423.44      1975489.58     13676222.05
      1974260.98     13676340.05
#Sta/Elev= 30
  3657.9  978.32  4018.2  972.29  4038.5  972.52  4274.3  967.45  4496.4  964.16
  4557.5  963.88  4638.9  962.57    4811  961.56  4901.4  961.88  4971.8  961.02
  4991.9   959.9  5001.9  961.22  5011.9  961.39  5018.4  959.67  5018.9  958.87
    5025  958.87  5025.5  959.67  5037.8  961.51  5052.1  961.74  5132.5  962.33
  5162.6  961.88  5323.4  963.36  5474.1  968.61  5644.8  972.32    5685  973.94
  5755.4  975.52  5885.9  976.62  5936.2   976.5  5956.3  977.23  5980.4   976.9
#Mann= 3 ,-1 , 0
  3657.9      .1       0  5018.4     .07       0  5025.5      .1       0
Bank Sta=5018.4,5025.5
XS Rating Curve= 0 ,0
Exp/Cntr=0.3,0.1

Type RM Length L Ch R = 1 ,9962    ,400,400,400
BEGIN DESCRIPTION:
UNT 023 in HW 18.0
END DESCRIPTION:
XS GIS Cut Line= 3
      1976621.52     13675812.33      1975482.64     13675819.27
      1974142.32       13675979.
#Sta/Elev= 30
  3520.9  981.84  3607.4  979.66  3657.4  977.33  3697.4  976.89  3747.4  975.28
  3847.4  973.75  3947.4  971.72  3967.4  970.78  4097.4  968.74  4247.4  965.49
  4597.4  960.99  4697.7  960.77  4727.9  960.03  4758.1   960.6  4778.3  959.94
  4899.1  959.46  4979.7  958.41  4995.7  957.28  4996.3  956.48  5002.5  956.48
    5003  957.28  5009.9  958.45  5080.4  959.24  5120.7  960.41  5322.1  961.71
  5634.3  966.93  5724.9  969.67  5767.4  971.93  5906.2  973.96  6009.6  977.36
#Mann= 3 ,-1 , 0
  3520.9      .1       0  4995.7     .07       0    5003      .1       0
Bank Sta=4995.7,5003
XS Rating Curve= 0 ,0
Exp/Cntr=0.3,0.1

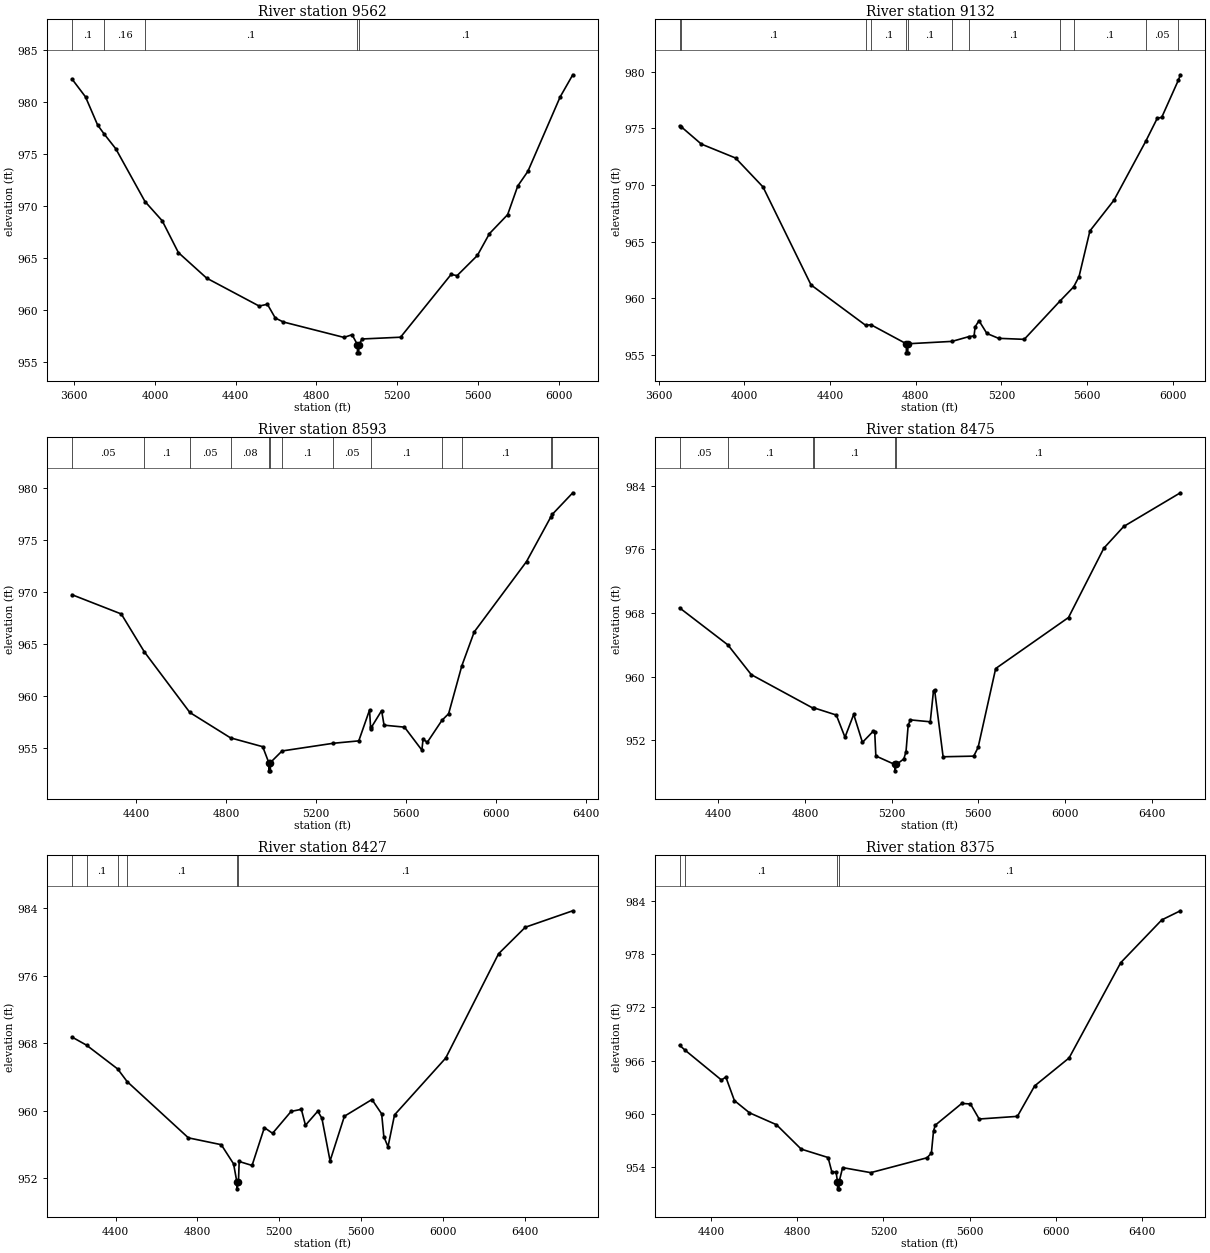
Type RM Length L Ch R = 1 ,9562    ,430,430,430
BEGIN DESCRIPTION:
UNT 023 in HW 17.0
END DESCRIPTION:
XS GIS Cut Line= 3
      1976461.76     13675472.05      1975350.69     13675458.16
      1973982.68     13675513.71
#Sta/Elev= 30
  3589.4  982.19  3656.2  980.48  3716.2  977.78  3748.1  976.93  3806.2   975.5
  3950.8  970.44  4036.2  968.59  4116.2  965.54  4256.2  963.09  4516.2  960.41
  4557.2  960.58  4596.2  959.26  4636.2  958.88  4936.4   957.4  4976.5  957.66
  5002.8  956.72  5003.4  955.92  5009.7  955.92  5010.2  956.72  5026.5  957.25
  5216.7  957.42  5466.9  963.44  5496.9  963.33    5597  965.26    5657  967.36
  5747.1  969.18  5797.2  971.93  5847.2  973.33  6007.3  980.48  6069.7   982.6
#Mann= 5 ,-1 , 0
  3589.4      .1       0  3748.1     .16       0  3950.8      .1       0
  5002.8     .07       0  5010.2      .1       0
Bank Sta=5002.8,5010.2
XS Rating Curve= 0 ,0
Exp/Cntr=0.3,0.1

Type RM Length L Ch R = 1 ,9132    ,539,539,539
BEGIN DESCRIPTION:
UNT 023 in HW 16.0
END DESCRIPTION:
XS GIS Cut Line= 3
      1976336.77     13674840.11      1975163.19     13675069.27
       1974039.1     13675263.56
#Sta/Elev= 30
  3698.5  975.22  3706.3  975.13  3799.7  973.61  3959.5  972.38  4087.5  969.83
  4311.6  961.19  4566.3  957.63  4591.1  957.68  4756.1     956  4756.7   955.2
  4763.1   955.2  4763.7     956  4969.6  956.21  5048.2  956.63  5072.3  956.69
  5077.4   957.5  5095.4  958.03  5132.1  956.91  5186.7  956.48  5306.5  956.39
  5471.8  959.74  5537.2  961.02  5562.2  961.93  5612.9  965.95  5725.1  968.66
  5873.5  973.86  5927.5   975.9  5947.8  975.96  6026.2  979.27    6035  979.72
#Mann= 12 ,-1 , 0
  3698.5     .05       0  3706.3      .1       0  4566.3     .05       0
  4591.1      .1       0  4756.1     .04       0  4763.7      .1       0
  4969.6     .05       0  5048.2      .1       0  5471.8     .05       0
  5537.2      .1       0  5873.5     .05       0  6026.2      .1       0
Bank Sta=4756.1,4763.7
XS Rating Curve= 0 ,0
Exp/Cntr=0.3,0.1

Type RM Length L Ch R = 1 ,8593    ,118,118,118
BEGIN DESCRIPTION:
UNT 023 in HW 15.0
END DESCRIPTION:
XS GIS Cut Line= 3
      1976204.89     13674576.21      1975322.92     13674756.77
      1974018.73      13674985.7
#Sta/Elev= 30
  4115.2  969.76    4334  967.91  4436.4  964.27  4638.6  958.44  4819.3     956
  4962.3  955.15  4989.1  953.63  4989.7  952.83  4996.1  952.83  4996.7  953.63
  5048.2  954.74  5275.7  955.48    5389  955.71  5436.9  958.68  5441.9  956.81
  5444.9  957.01  5490.5  958.62  5501.3  957.22  5592.1  957.03  5669.3  954.82
  5674.4  955.86  5693.6  955.58  5758.6  957.69  5788.1  958.32  5846.8  962.93
  5901.7  966.18  6134.2  972.95  6241.4  977.21  6248.8  977.49  6339.6  979.56
#Mann= 13 ,-1 , 0
  4115.2     .05       0  4436.4      .1       0  4638.6     .05       0
  4819.3     .08       0  4989.1     .07       0  4996.7     .08       0
  5048.2      .1       0  5275.7     .05       0  5444.9      .1       0
  5758.6     .08       0  5846.8      .1       0  6241.4     .08       0
  6248.8     .05       0
Bank Sta=4989.1,4996.7
XS Rating Curve= 0 ,0
Exp/Cntr=0.3,0.1

Type RM Length L Ch R = 1 ,8475    ,48,48,48
BEGIN DESCRIPTION:
Mapping XS 78598dd3
END DESCRIPTION:
XS GIS Cut Line= 4
      1976113.85     13674551.84      1974963.68     13674677.71
      1974690.24     13674716.77      1973828.29      13674885.7
#Sta/Elev= 30
  4221.3  968.64  4444.2  963.98  4552.1  960.24  4834.7  956.06  4841.6  956.06
  4944.6  955.16  4984.7  952.37  5024.9  955.24  5065.2  951.72  5115.5  953.14
    5122     953  5127.1  950.01  5214.5  948.94  5215.1  948.14  5222.1  948.94
  5256.3  949.64  5266.4  950.56  5276.4  953.88  5286.5  954.55  5378.3  954.31
  5393.3  958.23  5398.4  958.29  5437.6  949.91    5579  949.99  5599.2  951.09
  5680.3  961.01  6016.5  967.43  6179.6  976.15  6271.3  978.88  6532.9  983.12
#Mann= 6 ,-1 , 0
  4221.3     .05       0  4444.2      .1       0  4834.7     .05       0
  4841.6      .1       0  5214.5     .07       0  5222.1      .1       0
Bank Sta=5214.5,5222.1
XS Rating Curve= 0 ,0
Exp/Cntr=0.3,0.1

Type RM Length L Ch R = 1 ,8427    ,52,52,52
BEGIN DESCRIPTION:
Mapping XS bb5b1621
END DESCRIPTION:
XS GIS Cut Line= 6
      1976161.64     13674512.78      1975198.05     13674603.93
      1974937.63     13674629.97      1974811.77     13674629.97
      1974486.25     13674690.73      1973739.84     13674846.96
#Sta/Elev= 30
  4186.3  968.71  4257.3  967.75  4409.7  964.93  4455.7  963.44  4755.5  956.77
  4916.2  955.96  4976.5  953.69  4992.7  951.53  4993.3  950.73  5000.3  951.53
  5003.9  953.97  5066.9   953.5  5127.1  957.98  5167.3  957.31  5257.8   959.9
    5308  960.15  5328.1  958.26  5388.4  959.93  5408.5  959.09  5448.5  954.04
  5518.5  959.33  5653.2  961.31  5700.8  959.61  5711.4  956.91  5731.8  955.71
  5763.7  959.49    6014  966.22  6272.6  978.58  6403.3  981.72  6635.5  983.67
#Mann= 6 ,-1 , 0
  4186.3     .05       0  4257.3      .1       0  4409.7     .05       0
  4455.7      .1       0  4992.7     .07       0  5000.3      .1       0
Bank Sta=4992.7,5000.3
XS Rating Curve= 0 ,0
Exp/Cntr=0.3,0.1

Type RM Length L Ch R = 1 ,8375    ,192,192,192
BEGIN DESCRIPTION:
Mapping XS f424dcca
END DESCRIPTION:
XS GIS Cut Line= 3
      1976118.16      13674482.4      1974933.29     13674582.22
      1973809.54     13674725.41
#Sta/Elev= 30
  4254.7  967.72  4280.9  967.15  4448.5   963.8    4469  964.13  4508.8  961.47
  4578.7  960.09  4703.5  958.75  4818.3  955.99    4943  955.04  4960.4  953.43
  4980.4  953.38  4986.6   952.3  4987.3   951.5  4993.7   951.5  4994.3   952.3
  5010.5   953.9    5141  953.33  5401.9  955.01  5422.1  955.54    5432  958.05
  5440.4   958.7    5563  961.15  5603.3  961.09  5643.7  959.39  5820.9  959.69
  5900.8  963.13  6060.6  966.29  6300.2  977.06  6490.5  981.89  6576.6  982.92
#Mann= 4 ,-1 , 0
  4254.7     .05       0  4280.9      .1       0  4986.6     .07       0
  4994.3      .1       0
Bank Sta=4986.6,4994.3
XS Rating Curve= 0 ,0
Exp/Cntr=0.3,0.1

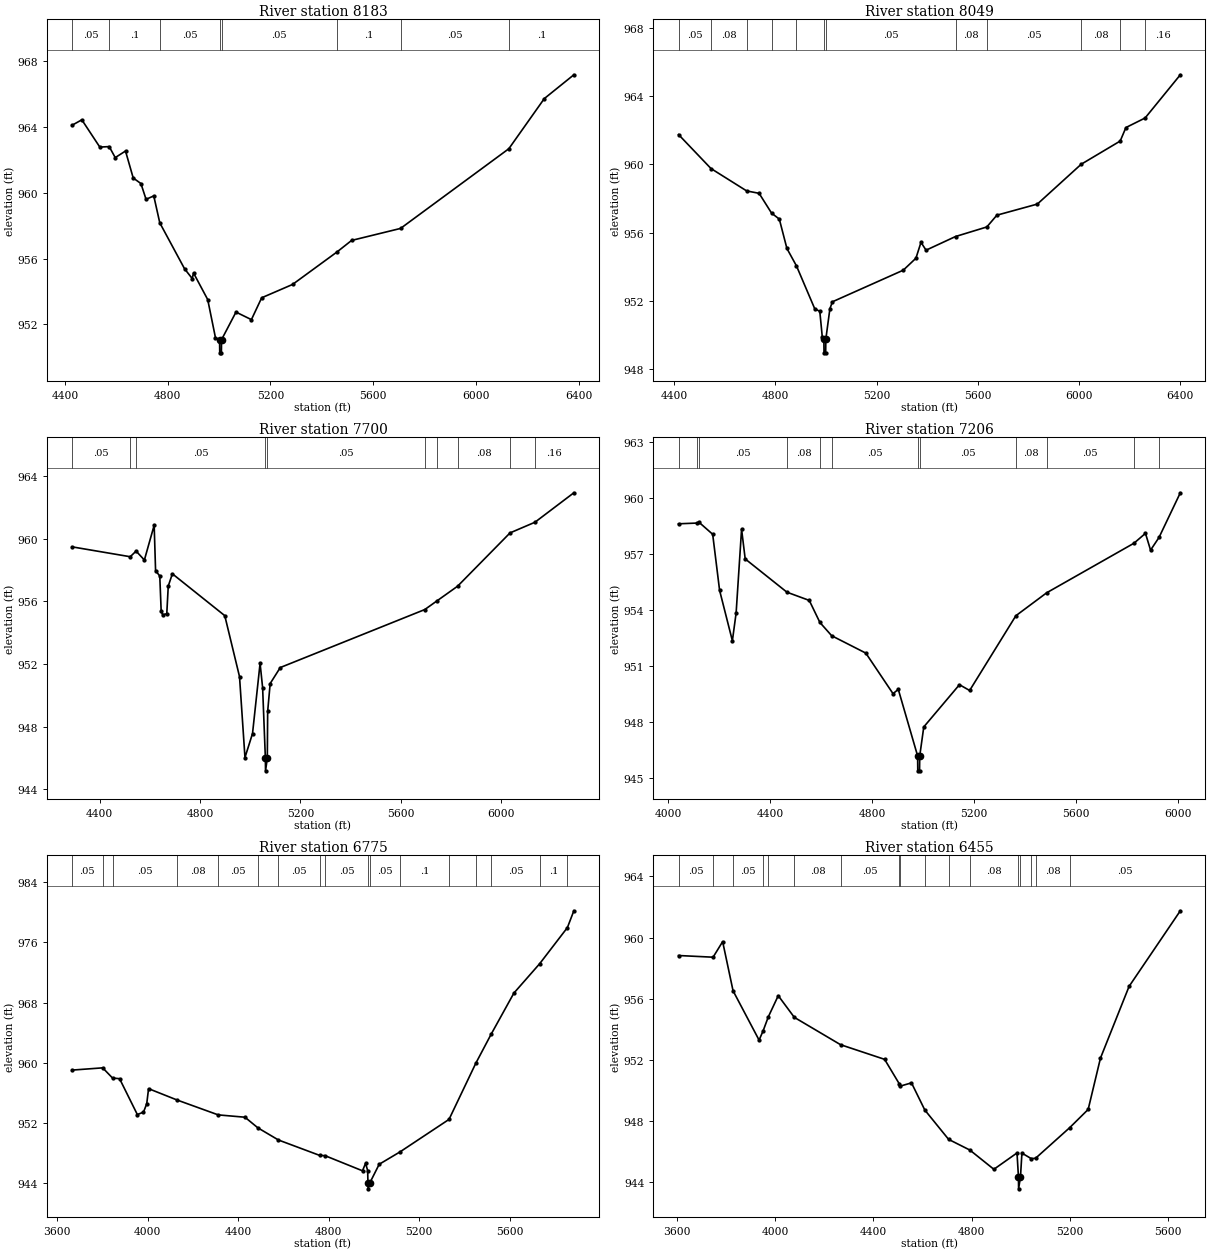
Type RM Length L Ch R = 1 ,8183    ,134,134,134
BEGIN DESCRIPTION:
Mapping XS 8b40c85a
END DESCRIPTION:
XS GIS Cut Line= 2
      1976042.99     13674376.85      1974089.93     13674389.87
#Sta/Elev= 30
    4428  964.12    4466  964.45    4536  962.79  4572.5  962.82    4596  962.15
    4636  962.55    4666  960.91    4696  960.57    4716  959.61    4746  959.82
  4769.4  958.18    4866  955.38  4895.7  954.79  4900.7  955.13    4956  953.51
    4986   951.2  5002.1  951.07  5002.8  950.27  5009.2  950.27  5009.8  951.07
    5066  952.75    5126  952.29    5166  953.62    5286  954.43  5458.5   956.4
    5516  957.11  5706.5  957.84    6128  962.69    6266  965.74  6381.1  967.19
#Mann= 8 ,-1 , 0
    4428     .05       0  4572.5      .1       0  4769.4     .05       0
  5002.1     .04       0  5009.8     .05       0  5458.5      .1       0
  5706.5     .05       0    6128      .1       0
Bank Sta=5002.1,5009.8
XS Rating Curve= 0 ,0
Exp/Cntr=0.3,0.1

Type RM Length L Ch R = 1 ,8049    ,349,349,349
BEGIN DESCRIPTION:
Mapping XS 7d9bc99c
END DESCRIPTION:
XS GIS Cut Line= 2
       1976073.4     13674250.98       1974089.9     13674255.32
#Sta/Elev= 30
  4417.4  961.74  4545.7  959.75  4686.7  958.44  4735.8   958.3  4785.2  957.14
  4815.8  956.79  4845.8  955.07  4883.6  954.05  4955.8  951.54  4975.8  951.39
  4985.8  949.86  4991.9  949.76  4992.5  948.96    4999  948.96  4999.6  949.76
  5015.8  951.55  5025.8  951.95  5305.8   953.8  5355.8   954.5  5375.8  955.43
  5395.8  954.97  5512.3  955.77    5636  956.33  5675.8  957.02  5835.8  957.67
  6008.9     960  6163.2  961.36  6185.8  962.15  6261.7  962.71  6400.9  965.24
#Mann= 12 ,-1 , 0
  4417.4     .05       0  4545.7     .08       0  4686.7     .05       0
  4785.2     .08       0  4883.6     .05       0  4991.9     .04       0
  4999.6     .05       0  5512.3     .08       0    5636     .05       0
  6008.9     .08       0  6163.2     .05       0  6261.7     .16       0
Bank Sta=4991.9,4999.6
XS Rating Curve= 0 ,0
Exp/Cntr=0.3,0.1

Type RM Length L Ch R = 1 ,7700    ,494,494,494
BEGIN DESCRIPTION:
Mapping XS ffcfb2b8
END DESCRIPTION:
XS GIS Cut Line= 3
      1976016.98     13674159.85      1975552.55     13673925.46
      1974081.22     13674068.69
#Sta/Elev= 30
  4290.3  959.48  4521.9  958.85  4545.3  959.21  4578.3  958.64  4617.3  960.86
  4622.9  957.96  4639.6  957.62  4645.2  955.37    4651  955.15  4667.5  955.21
  4673.4  956.98  4689.8  957.76  4898.5  955.09  4957.2   951.2  4978.9  946.04
    5009  947.57  5039.1  952.05  5049.2   950.5  5060.2  945.99  5060.8  945.19
  5067.9  945.99  5069.3  948.98  5079.3  950.76  5119.5  951.78  5695.1  955.48
  5743.3  956.03  5825.8  956.97  6034.6  960.37  6133.8  961.05  6288.8  962.93
#Mann= 10 ,-1 , 0
  4290.3     .05       0  4521.9     .08       0  4545.3     .05       0
  5060.2    .035       0  5067.9     .05       0  5695.1     .08       0
  5743.3      .1       0  5825.8     .08       0  6034.6     .05       0
  6133.8     .16       0
Bank Sta=5060.2,5067.9
XS Rating Curve= 0 ,0
Exp/Cntr=0.3,0.1

Type RM Length L Ch R = 1 ,7206    ,431,431,431
BEGIN DESCRIPTION:
Mapping XS 89c78eb7
END DESCRIPTION:
XS GIS Cut Line= 3
      1975875.45     13674080.84      1975184.49     13673580.84
       1974068.2     13673587.78
#Sta/Elev= 30
  4040.2  958.62  4114.2  958.66  4119.8  958.71  4174.2  958.06  4201.3  955.06
  4251.5  952.36  4266.2  953.85  4287.6  958.33  4301.8  956.74  4465.6  954.96
  4553.2  954.52    4595  953.34  4641.2  952.63  4775.2   951.7  4881.9  949.53
  4902.6  949.76  4978.4   946.2  4979.1   945.4    4986   945.4  4986.8   946.2
  5002.6  947.75  5142.6  950.01  5182.6   949.7    5364   953.7  5485.1  954.93
  5827.4  957.58  5872.6  958.11  5892.6  957.21  5925.8  957.89  6009.4  960.28
#Mann= 12 ,-1 , 0
  4040.2     .05       0  4114.2     .08       0  4119.8     .05       0
  4465.6     .08       0    4595      .1       0  4641.2     .05       0
  4978.4     .04       0  4986.8     .05       0    5364     .08       0
  5485.1     .05       0  5827.4     .16       0  5925.8      .1       0
Bank Sta=4978.4,4986.8
XS Rating Curve= 0 ,0
Exp/Cntr=0.3,0.1

Type RM Length L Ch R = 1 ,6775    ,320,320,320
BEGIN DESCRIPTION:
Mapping XS e7a1d7fb
END DESCRIPTION:
XS GIS Cut Line= 4
      1975951.86     13674122.52      1975243.52     13673560.01
      1974965.74      13672973.2      1974348.86     13672727.15
#Sta/Elev= 30
  3666.1  959.02  3801.4  959.32  3845.1  957.96    3876  957.88  3954.5  953.11
  3981.7  953.42  3996.1  954.54  4004.2  956.55  4131.2  955.03  4312.1  953.06
  4430.3  952.75  4487.2  951.34  4578.2  949.72  4761.3  947.66  4783.7  947.64
  4949.8  945.62  4963.4  946.62  4972.6  945.65  4973.9  944.02  4974.6  943.22
  4982.3  944.02  5023.6  946.49  5115.3  948.13  5332.2  952.46  5450.4  959.92
  5518.3  963.79    5619  969.27  5732.7  973.17  5855.4  977.98    5884  980.22
#Mann= 17 ,-1 , 0
  3666.1     .05       0  3801.4     .08       0  3845.1     .05       0
  4131.2     .08       0  4312.1     .05       0  4487.2     .08       0
  4578.2     .05       0  4761.3     .08       0  4783.7     .05       0
  4973.9     .04       0  4982.3     .05       0  5115.3      .1       0
  5332.2     .05       0  5450.4     .08       0  5518.3     .05       0
  5732.7      .1       0  5855.4     .05       0
Bank Sta=4973.9,4982.3
XS Rating Curve= 0 ,0
Exp/Cntr=0.3,0.1

Type RM Length L Ch R = 1 ,6455    ,106,106,106
BEGIN DESCRIPTION:
Mapping XS 55655d7f
END DESCRIPTION:
XS GIS Cut Line= 3
      1975983.12     13674129.47      1975332.06     13673586.92
      1975353.75      13672389.5
#Sta/Elev= 30
  3605.6  958.82  3746.4  958.71  3785.4  959.73  3827.8  956.51  3933.9  953.28
  3950.4  953.89  3971.7  954.81    4012  956.19  4077.5  954.77  4265.9  952.98
  4445.5  952.02  4504.8  950.43  4509.8  950.27    4555  950.48  4609.4   948.7
  4706.3  946.78  4792.9  946.08  4890.8  944.82  4985.1  945.89  4990.9  944.34
  4991.6  943.54  4999.3  944.34  5005.1  945.88    5043  945.52  5060.6  945.54
  5199.4  947.54  5275.1  948.74  5325.2   952.1  5441.9   956.8  5650.7  961.75
#Mann= 17 ,-1 , 0
  3605.6     .05       0  3746.4     .08       0  3827.8     .05       0
  3950.4     .08       0  3971.7     .05       0  4077.5     .08       0
  4265.9     .05       0  4504.8     .08       0  4509.8     .05       0
  4609.4     .08       0  4706.3     .05       0  4792.9     .08       0
  4990.9     .07       0  4999.3     .08       0    5043      .1       0
  5060.6     .08       0  5199.4     .05       0
Bank Sta=4990.9,4999.3
XS Rating Curve= 0 ,0
Exp/Cntr=0.3,0.1