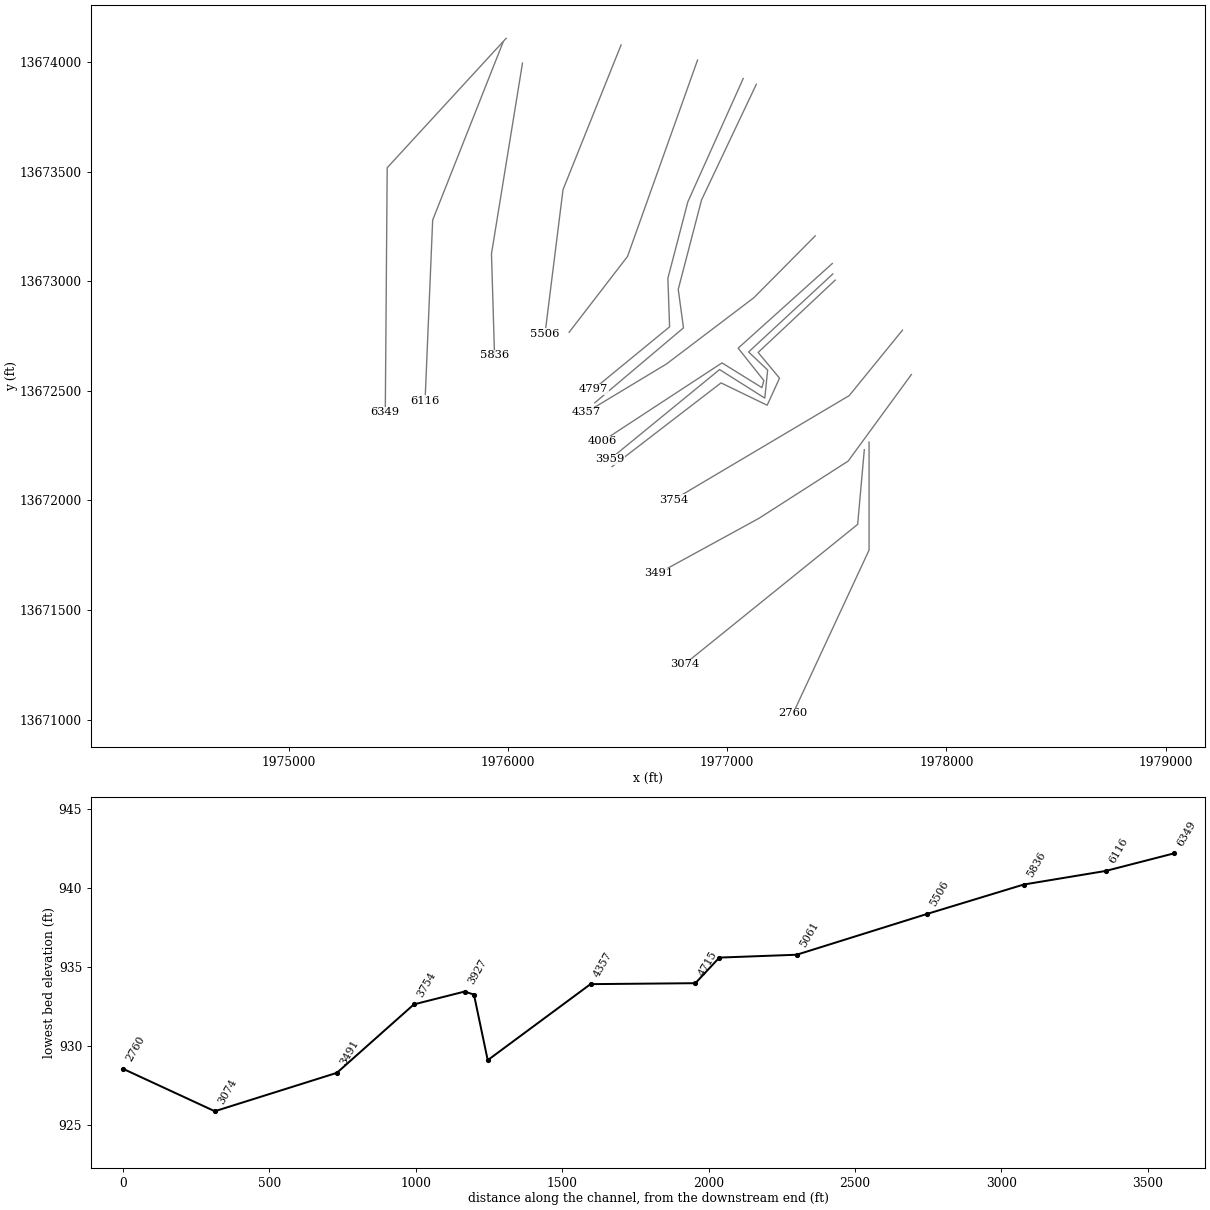
HEC-RAS study UNT 023 in HW.prj: UNT 023 in HW Base Level Engineering

--- UNT 023 in HW.g01 (geometry) --- (continued)

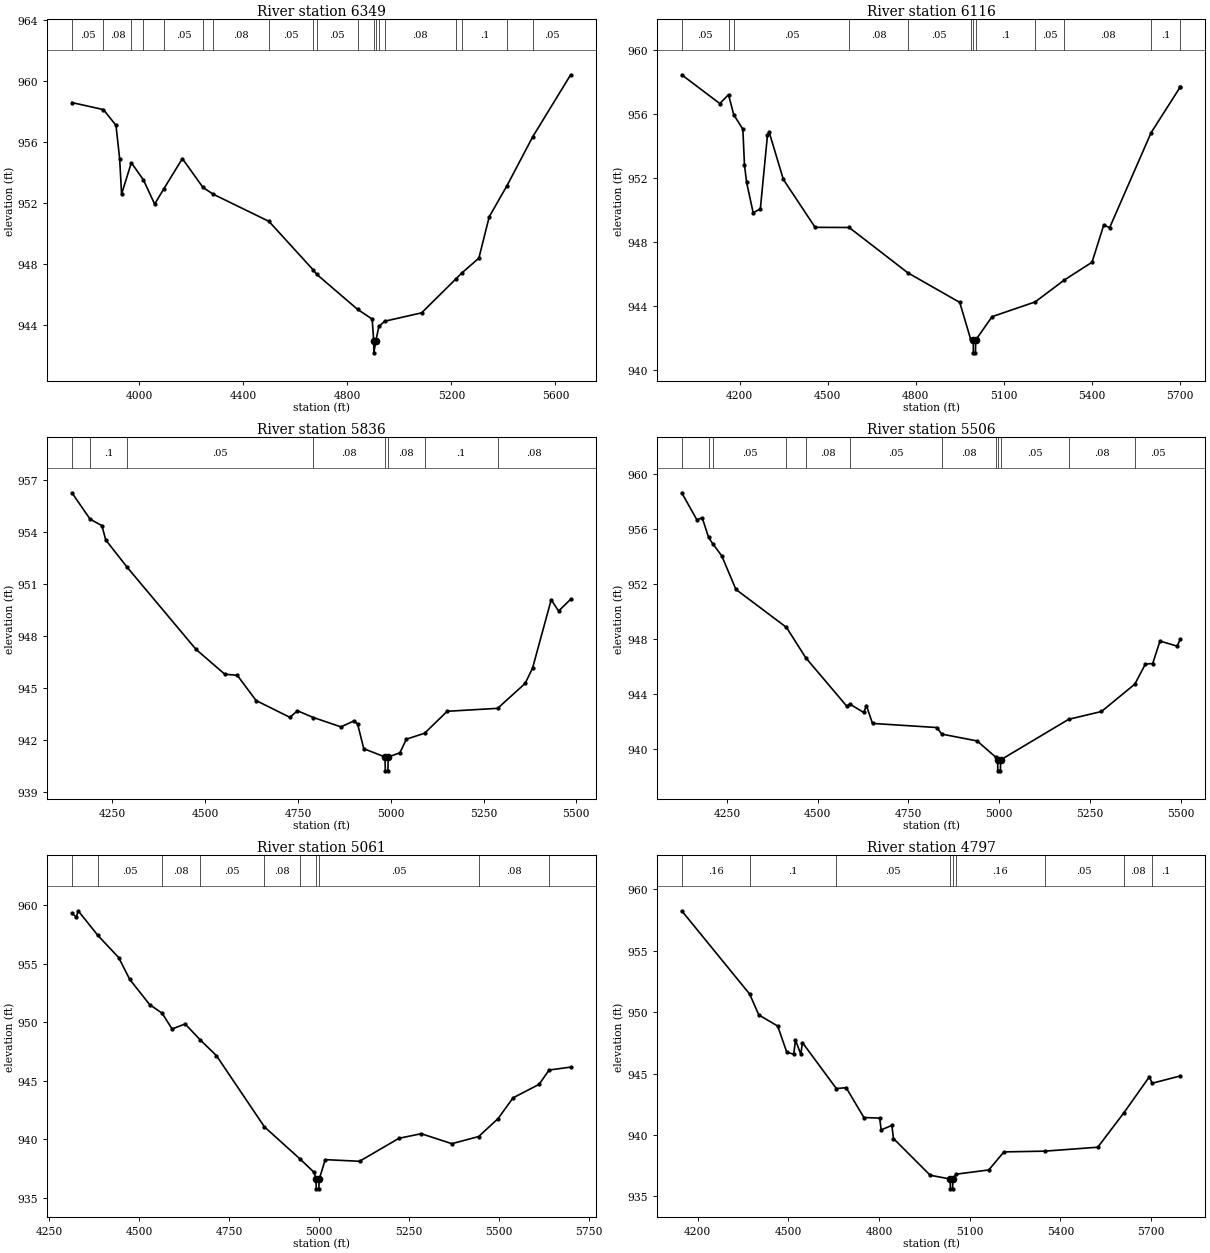
Type RM Length L Ch R = 1 ,6349    ,233,233,233
BEGIN DESCRIPTION:
Mapping XS e2869b2e
END DESCRIPTION:
XS GIS Cut Line= 3
       1975991.8     13674107.77      1975449.25     13673517.48
      1975440.57     13672402.06
#Sta/Elev= 30
  3741.4  958.59  3862.5  958.13  3910.8   957.1    3925  954.89  3932.3   952.6
  3969.8  954.65  4016.5  953.52  4059.4  951.94    4095  952.95    4166  954.92
  4245.3  953.03  4284.4  952.59  4498.8  950.81  4668.4  947.64  4681.8  947.35
  4839.3  945.05  4895.6  944.41  4901.4     943  4902.1   942.2  4909.9     943
  4921.3  943.93  4943.8  944.27  5085.6  944.82  5216.9  947.03  5240.2  947.43
  5305.7   948.4  5345.7  951.12  5413.9  953.15  5512.4  956.34  5658.6  960.41
#Mann= 19 ,-1 , 0
  3741.4     .05       0  3862.5     .08       0  3969.8     .05       0
  4016.5     .08       0    4095     .05       0  4245.3      .1       0
  4284.4     .08       0  4498.8     .05       0  4668.4      .1       0
  4681.8     .05       0  4839.3     .08       0  4901.4     .07       0
  4909.9     .08       0  4921.3     .05       0  4943.8     .08       0
  5216.9     .05       0  5240.2      .1       0  5413.9     .08       0
  5512.4     .05       0
Bank Sta=4901.4,4909.9
XS Rating Curve= 0 ,0
Exp/Cntr=0.3,0.1

Type RM Length L Ch R = 1 ,6116    ,280,280,280
BEGIN DESCRIPTION:
UNT 023 in HW 13.0
END DESCRIPTION:
XS GIS Cut Line= 3
      1975977.89     13674090.39      1975656.71     13673278.76
      1975621.99     13672454.06
#Sta/Elev= 30
  4002.8  958.46  4132.6  956.66  4162.1  957.22  4179.8  955.97    4211  955.06
  4216.4  952.84  4223.7  951.74  4246.1  949.84  4270.5  950.08  4294.8   954.7
  4300.2   954.9  4348.9  951.92    4457  948.93    4573  948.92  4772.7  946.09
  4949.5  944.24  4986.6  941.94  4995.3  941.89    4996  941.09    5003  941.09
  5003.8  941.89  5059.6  943.35  5206.2  944.27  5304.9  945.63  5399.9  946.75
  5439.9  949.08  5459.9  948.91    5601  954.84  5699.7  957.68  5701.1  957.68
#Mann= 12 ,-1 , 0
  4002.8     .05       0  4162.1      .1       0  4179.8     .05       0
    4573     .08       0  4772.7     .05       0  4986.6      .1       0
  4995.3     .07       0  5003.8      .1       0  5206.2     .05       0
  5304.9     .08       0    5601      .1       0  5699.7     .05       0
Bank Sta=4995.3,5003.8
XS Rating Curve= 0 ,0
Exp/Cntr=0.3,0.1

Type RM Length L Ch R = 1 ,5836    ,330,330,330
BEGIN DESCRIPTION:
UNT 023 in HW 12.0
END DESCRIPTION:
XS GIS Cut Line= 3
      1976066.43     13673994.86        1975925.       13673125.
      1975938.83     13672662.49
#Sta/Elev= 30
  4140.8  956.29  4189.7  954.77  4221.7  954.39  4231.8  953.57    4290  951.98
    4475  947.25  4552.8  945.81  4586.4  945.75  4637.1  944.29  4728.3  943.32
  4748.5   943.7  4791.5  943.31  4865.7  942.77  4900.5  943.11  4910.6  942.94
  4927.2  941.51  4984.5  941.03  4985.3  940.23  4992.3  940.23    4993  941.03
  5024.6  941.27  5042.1  942.06  5091.1   942.4  5152.1  943.67    5288  943.84
  5362.2  945.28  5382.2  946.17  5432.3  950.11  5452.3  949.46  5484.8  950.14
#Mann= 8 ,-1 , 0
  4140.8     .05       0  4189.7      .1       0    4290     .05       0
  4791.5     .08       0  4984.5     .04       0    4993     .08       0
  5091.1      .1       0    5288     .08       0
Bank Sta=4984.5,4993
XS Rating Curve= 0 ,0
Exp/Cntr=0.3,0.1

Type RM Length L Ch R = 1 ,5506    ,445,445,445
BEGIN DESCRIPTION:
Mapping XS fb99a26d
END DESCRIPTION:
XS GIS Cut Line= 3
      1976516.08     13674077.34      1976251.33     13673417.65
        1976169.     13672759.01
#Sta/Elev= 30
  4125.3  958.66    4167  956.69  4181.7  956.84  4199.4   955.4  4211.1  954.93
  4235.6  954.06  4274.6  951.61  4413.9  948.84  4467.2  946.62  4580.4  943.08
  4588.2  943.25  4626.9  942.63  4634.3  943.13  4651.1  941.83  4828.2  941.53
  4842.1  941.05  4939.6  940.55  4990.6  939.37  4995.8  939.17  4996.6  938.37
  5003.6  938.37  5004.3  939.17  5191.7  942.13  5282.2   942.7  5374.2   944.7
  5403.2  946.16  5423.3   946.2  5443.5  947.84  5490.3  947.47  5499.9  947.99
#Mann= 12 ,-1 , 0
  4125.3     .05       0  4199.4     .08       0  4211.1     .05       0
  4413.9      .1       0  4467.2     .08       0  4588.2     .05       0
  4842.1     .08       0  4990.6     .05       0  4995.8     .04       0
  5004.3     .05       0  5191.7     .08       0  5374.2     .05       0
Bank Sta=4995.8,5004.3
XS Rating Curve= 0 ,0
Exp/Cntr=0.3,0.1

Type RM Length L Ch R = 1 ,5061    ,264,264,264
BEGIN DESCRIPTION:
Mapping XS 7a80899c
END DESCRIPTION:
XS GIS Cut Line= 3
      1976865.04     13674008.77       1976545.6     13673112.96
      1976279.15     13672766.92
#Sta/Elev= 30
  4312.5  959.29  4324.7  958.96    4330   959.5  4384.4  957.41  4442.6  955.51
  4473.4  953.65  4528.8   951.5  4563.4  950.77  4591.3  949.42  4627.5  949.85
  4669.2   948.5  4714.6  947.15  4848.3  941.07  4946.4  938.36  4986.6  937.19
  4991.6  936.59  4992.4  935.79  4999.6  935.79  5000.4  936.59  5017.4  938.28
  5112.8  938.14  5222.5   940.1  5284.5  940.49  5369.7  939.64  5444.4  940.25
  5498.3  941.78    5540  943.55  5612.5   944.7  5640.2  945.92  5700.3  946.17
#Mann= 10 ,-1 , 0
  4312.5     .16       0  4384.4     .05       0  4563.4     .08       0
  4669.2     .05       0  4848.3     .08       0  4946.4     .05       0
  4991.6     .04       0  5000.4     .05       0  5444.4     .08       0
  5640.2     .05       0
Bank Sta=4991.6,5000.4
XS Rating Curve= 0 ,0
Exp/Cntr=0.3,0.1

Type RM Length L Ch R = 1 ,4797    ,82,82,82
BEGIN DESCRIPTION:
Mapping XS 801a5785
END DESCRIPTION:
XS GIS Cut Line= 5
      1977073.36     13673924.55      1976820.77     13673362.09
      1976729.63     13673013.14      1976737.44     13672791.78
      1976389.26     13672505.96
#Sta/Elev= 30
  4147.8  958.26  4372.6  951.47  4402.5  949.78  4465.2  948.87  4495.2  946.73
  4518.3  946.58  4523.8  947.73  4541.5  946.58    4547  947.52  4659.1  943.78
  4691.5  943.85  4750.2  941.42  4802.3  941.37  4807.4  940.41  4842.7  940.78
  4847.9  939.71  4969.3  936.72  5035.4  936.41  5036.2  935.61  5043.4  935.61
  5044.2  936.41    5054   936.8  5163.2  937.15  5213.2  938.62  5348.4  938.68
  5523.5     939    5610  941.81  5694.3  944.74  5703.1  944.21    5797  944.81
#Mann= 9 ,-1 , 0
  4147.8     .16       0  4372.6      .1       0  4659.1     .05       0
  5035.4     .04       0  5044.2     .05       0    5054     .16       0
  5348.4     .05       0    5610     .08       0  5703.1      .1       0
Bank Sta=5035.4,5044.2
XS Rating Curve= 0 ,0
Exp/Cntr=0.3,0.1

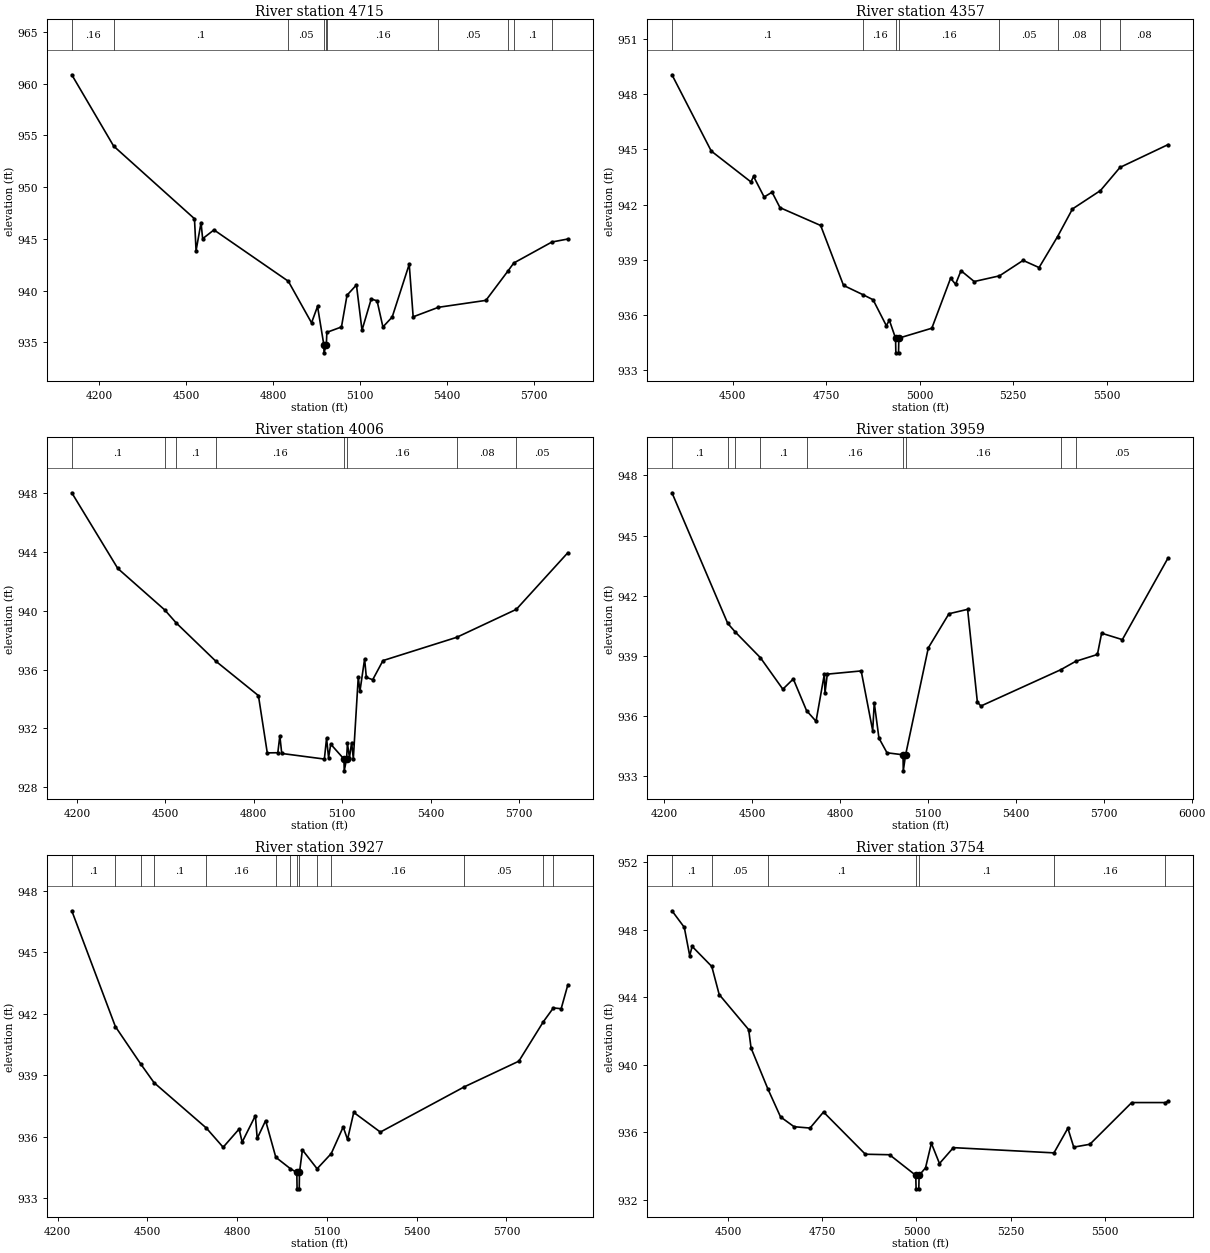
Type RM Length L Ch R = 1 ,4715    ,358,358,358
BEGIN DESCRIPTION:
UNT 023 in HW 11.0
END DESCRIPTION:
XS GIS Cut Line= 5
      1977133.26     13673898.51      1976883.27     13673370.77
      1976776.94     13672962.79      1976800.81     13672787.01
       1976396.3     13672445.43
#Sta/Elev= 30
  4105.6  960.86  4250.1  953.97  4529.1  946.95  4534.6  943.86  4551.8  946.57
  4557.3  945.02  4596.4  945.87    4853  940.91  4933.2  936.89  4953.9  938.48
  4975.5  934.79  4976.3  933.99  4984.3  934.79  4986.1  935.97  5036.5  936.49
  5055.7  939.56  5088.2  940.55  5107.4  936.18  5139.2  939.19  5159.4  939.02
  5179.6  936.49  5211.6  937.45  5270.4  942.55    5284  937.47  5371.1  938.39
  5535.1  939.06    5611  941.89  5631.3  942.67    5763   944.7    5818  944.99
#Mann= 10 ,-1 , 0
  4105.6     .16       0  4250.1      .1       0    4853     .05       0
  4975.5     .07       0  4984.3     .05       0  4986.1     .16       0
  5371.1     .05       0    5611     .08       0  5631.3      .1       0
    5763     .08       0
Bank Sta=4975.5,4984.3
XS Rating Curve= 0 ,0
Exp/Cntr=0.3,0.1

Type RM Length L Ch R = 1 ,4357    ,351,351,351
BEGIN DESCRIPTION:
Mapping XS 86b3411d
END DESCRIPTION:
XS GIS Cut Line= 4
       1977401.8     13673206.66      1977121.82     13672924.51
      1976723.38     13672622.42      1976356.23     13672401.09
#Sta/Elev= 30
  4337.7  949.06  4442.7  944.91  4548.8  943.23  4555.8  943.53  4584.1  942.41
  4605.3  942.67  4626.5  941.83  4735.2  940.86  4796.3   937.6  4849.7  937.08
  4875.3  936.82  4910.7  935.41  4918.9   935.7  4935.4  934.73  4936.2  933.93
  4943.4  933.93  4944.2  934.73  5032.4  935.27  5082.6  937.99  5095.8  937.66
  5110.4   938.4  5145.7  937.81  5213.3  938.12  5276.4  938.96  5319.1  938.57
  5368.4  940.25  5408.4  941.76  5483.2  942.76  5535.5  944.02  5663.9  945.26
#Mann= 8 ,-1 , 0
  4337.7      .1       0  4849.7     .16       0  4935.4     .07       0
  4944.2     .16       0  5213.3     .05       0  5368.4     .08       0
  5483.2      .1       0  5535.5     .08       0
Bank Sta=4935.4,4944.2
XS Rating Curve= 0 ,0
Exp/Cntr=0.3,0.1

Type RM Length L Ch R = 1 ,4006    ,47,47,47
BEGIN DESCRIPTION:
Mapping XS 6f566308
END DESCRIPTION:
XS GIS Cut Line= 6
      1977479.89     13673080.76       1977050.2     13672694.47
      1977167.39      13672546.9      1977158.71     13672514.35
      1976976.42      13672627.2       1976430.4     13672269.69
#Sta/Elev= 30
  4182.6  948.01  4338.6  942.87    4498  940.05  4537.2  939.16  4671.1  936.57
  4815.7  934.23  4845.7  930.34  4881.5  930.35  4888.3   931.5  4894.8   930.3
  5039.4  929.92  5046.8  931.34  5053.6  930.02    5061  930.93  5105.9  929.92
  5106.7  929.12  5114.7  929.92  5117.6  930.99  5124.5  930.02  5131.8  931.04
  5137.6  929.95  5154.3  935.48    5160  934.53  5175.9  936.72  5181.7  935.47
  5203.3  935.31  5238.2  936.61  5488.2  938.19  5690.4  940.09  5865.3  943.94
#Mann= 8 ,-1 , 0
  4182.6      .1       0    4498     .08       0  4537.2      .1       0
  4671.1     .16       0  5105.9     .07       0  5114.7     .16       0
  5488.2     .08       0  5690.4     .05       0
Bank Sta=5105.9,5114.7
XS Rating Curve= 0 ,0
Exp/Cntr=0.3,0.1

Type RM Length L Ch R = 1 ,3959    ,32,32,32
BEGIN DESCRIPTION:
Mapping XS 91f0065e
END DESCRIPTION:
XS GIS Cut Line= 6
      1977482.04     13673032.99      1977097.94     13672677.11
      1977184.75     13672594.65      1977171.73     13672466.61
      1976965.57     13672596.82      1976464.25     13672186.64
#Sta/Elev= 30
  4226.3  947.13  4416.6  940.62  4442.4  940.19  4528.1  938.91  4604.7  937.34
  4640.4  937.85  4685.7  936.27    4718  935.74  4746.4  938.09  4748.5  937.14
  4756.5  938.09  4872.1  938.25  4911.4  935.27  4916.7  936.66  4932.7   934.9
  4960.2  934.17  5014.9  934.07  5015.7  933.27  5023.7  934.07  5101.2   939.4
  5171.6   941.1  5235.3  941.32  5268.6   936.7  5280.6   936.5  5553.2  938.31
  5604.4  938.73  5678.3  939.07  5692.7  940.13  5763.4  939.81  5919.4  943.88
#Mann= 9 ,-1 , 0
  4226.3      .1       0  4416.6     .05       0  4442.4     .08       0
  4528.1      .1       0  4685.7     .16       0  5014.9     .07       0
  5023.7     .16       0  5553.2     .08       0  5604.4     .05       0
Bank Sta=5014.9,5023.7
XS Rating Curve= 0 ,0
Exp/Cntr=0.3,0.1

Type RM Length L Ch R = 1 ,3927    ,173,173,173
BEGIN DESCRIPTION:
Mapping XS bec4bb67
END DESCRIPTION:
XS GIS Cut Line= 6
       1977492.9     13673004.79      1977141.35     13672674.94
        1977239.     13672557.75      1977182.58     13672434.06
      1976972.08     13672536.05      1976475.15     13672154.13
#Sta/Elev= 30
  4247.1  947.03  4392.8  941.38  4477.7  939.55  4522.1  938.64  4696.6  936.43
    4753  935.49  4806.4  936.38  4816.5  935.74  4860.7  937.03  4866.8  935.92
  4894.9  936.79    4929     935    4978  934.44  4999.2  934.26  5000.1  933.46
  5007.3  933.46  5008.1  934.26  5017.9  935.36    5067  934.44  5114.2  935.18
  5154.2  936.48  5168.7  935.87  5189.5  937.19  5278.4  936.23  5559.3  938.44
  5741.3  939.69  5823.4  941.62  5856.7  942.29  5882.7  942.25  5905.1  943.42
#Mann= 14 ,-1 , 0
  4247.1      .1       0  4392.8     .05       0  4477.7     .08       0
  4522.1      .1       0  4696.6     .16       0    4929      .1       0
    4978     .16       0  4999.2     .07       0  5008.1     .16       0
    5067      .1       0  5114.2     .16       0  5559.3     .05       0
  5823.4     .08       0  5856.7     .05       0
Bank Sta=4999.2,5008.1
XS Rating Curve= 0 ,0
Exp/Cntr=0.3,0.1

Type RM Length L Ch R = 1 ,3754    ,263,263,263
BEGIN DESCRIPTION:
UNT 023 in HW 8.0
END DESCRIPTION:
XS GIS Cut Line= 3
      1977799.77     13672776.51      1977556.71     13672477.89
       1976754.6     13672002.18
#Sta/Elev= 30
  4350.8  949.12  4383.5  948.14  4397.9  946.46  4404.4  947.01  4456.6  945.82
  4476.2  944.16  4554.5  942.08  4560.9  940.99  4605.5  938.57  4639.2  936.91
  4675.1  936.33  4717.5  936.25  4753.3   937.2  4864.4   934.7  4928.7  934.67
  4998.3  933.45  4999.2  932.65  5006.4  932.65  5007.2  933.45  5024.2  933.89
  5039.8  935.35  5061.3  934.15  5098.2  935.09  5365.4  934.78  5402.3  936.24
  5417.9  935.12  5460.8  935.29  5571.9  937.76  5661.3  937.76  5668.4  937.83
#Mann= 7 ,-1 , 0
  4350.8      .1       0  4456.6     .05       0  4605.5      .1       0
  4998.3     .07       0  5007.2      .1       0  5365.4     .16       0
  5661.3     .05       0
Bank Sta=4998.3,5007.2
XS Rating Curve= 0 ,0
Exp/Cntr=0.3,0.1

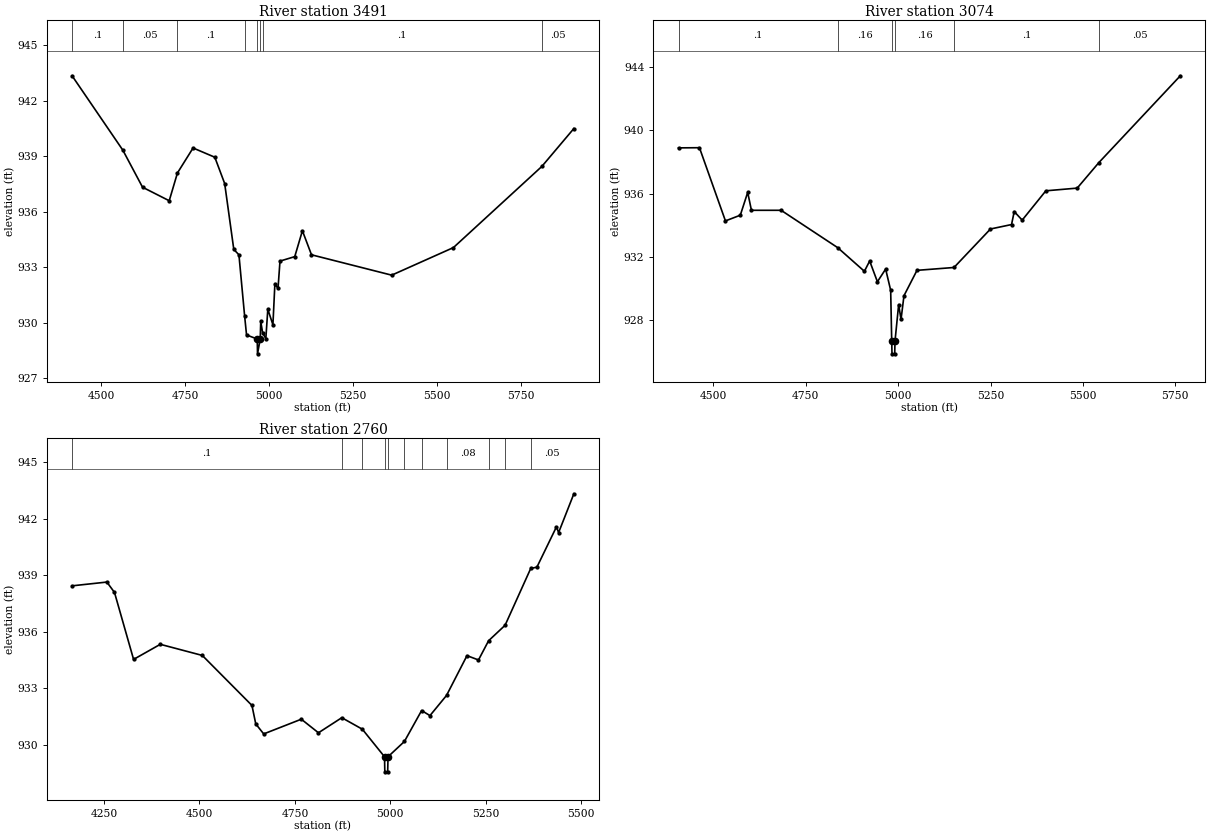
Type RM Length L Ch R = 1 ,3491    ,417,417,417
BEGIN DESCRIPTION:
Mapping XS 6a1ca0b2
END DESCRIPTION:
XS GIS Cut Line= 4
      1977840.58     13672574.26      1977551.94     13672179.28
      1977146.12     13671918.86      1976686.08     13671667.14
#Sta/Elev= 30
    4413  943.34  4564.4  939.32  4623.1  937.32  4702.6  936.59  4727.1  938.09
  4773.7  939.44  4838.5  938.94  4867.9  937.52  4895.1  933.96  4910.4  933.67
  4927.4  930.36  4933.1  929.34    4965  929.12  4965.8  928.32  4973.9  929.12
  4975.4  930.07  4981.1  929.45  4990.6  929.14  4996.5  930.73  5011.7  929.89
  5017.6  932.11  5026.9  931.85  5032.8  933.33  5076.8  933.57  5099.6  934.97
  5126.7  933.67  5365.8  932.57  5549.8  934.06  5813.2  938.44  5908.8  940.49
#Mann= 8 ,-1 , 0
    4413      .1       0  4564.4     .05       0  4727.1      .1       0
  4927.4     .05       0    4965     .07       0  4973.9     .05       0
  4981.1      .1       0  5813.2     .05       0
Bank Sta=4965,4973.9
XS Rating Curve= 0 ,0
Exp/Cntr=0.3,0.1

Type RM Length L Ch R = 1 ,3074    ,314,314,314
BEGIN DESCRIPTION:
Mapping XS 70be4090
END DESCRIPTION:
XS GIS Cut Line= 3
      1977625.73     13672231.41      1977595.34     13671890.65
      1976805.42     13671252.64
#Sta/Elev= 30
    4406  938.89  4462.6   938.9  4532.9  934.28  4573.1  934.64  4593.1  936.08
  4603.2  934.95  4683.5  934.95  4836.7  932.59  4908.8   931.1  4923.1  931.75
    4944  930.44  4966.3  931.24  4979.9   929.9  4982.7  926.69  4983.5  925.89
  4990.8  925.89  4991.6  926.69  5001.5     929  5007.9  928.06  5015.9  929.56
  5051.1  931.16  5151.2  931.34  5249.9  933.77  5306.9  934.05  5314.1  934.87
  5335.7  934.33  5399.7  936.18  5484.5  936.35  5543.1  937.96  5763.5  943.44
#Mann= 6 ,-1 , 0
    4406      .1       0  4836.7     .16       0  4982.7     .07       0
  4991.6     .16       0  5151.2      .1       0  5543.1     .05       0
Bank Sta=4982.7,4991.6
XS Rating Curve= 0 ,0
Exp/Cntr=0.3,0.1

Type RM Length L Ch R = 1 ,2760    ,270,270,270
BEGIN DESCRIPTION:
Mapping XS c114e8c3
END DESCRIPTION:
XS GIS Cut Line= 3
      1977647.42     13672266.05      1977647.42     13671773.47
      1977300.93     13671028.49
#Sta/Elev= 30
  4166.4  938.44  4257.5  938.64  4277.5  938.09  4327.5  934.54  4397.5  935.34
  4507.5  934.75  4637.5   932.1  4647.5  931.12  4668.3  930.59  4766.8  931.37
  4811.7  930.65  4872.8  931.45  4926.6  930.84  4984.7  929.38  4985.5  928.58
    4993  928.58  4993.9  929.38  5036.8  930.19  5081.9  931.83  5103.7  931.56
  5147.1  932.63  5200.7  934.74  5230.8  934.51  5257.3  935.53  5300.5  936.35
  5367.6  939.36  5383.8  939.43  5435.1  941.57  5440.6  941.26  5480.6  943.32
#Mann= 11 ,-1 , 0
  4166.4      .1       0  4872.8     .16       0  4926.6      .1       0
  4984.7     .07       0  4993.9      .1       0  5036.8     .16       0
  5081.9      .1       0  5147.1     .08       0  5257.3      .1       0
  5300.5     .08       0  5367.6     .05       0
Bank Sta=4984.7,4993.9
XS Rating Curve= 0 ,0
Exp/Cntr=0.3,0.1