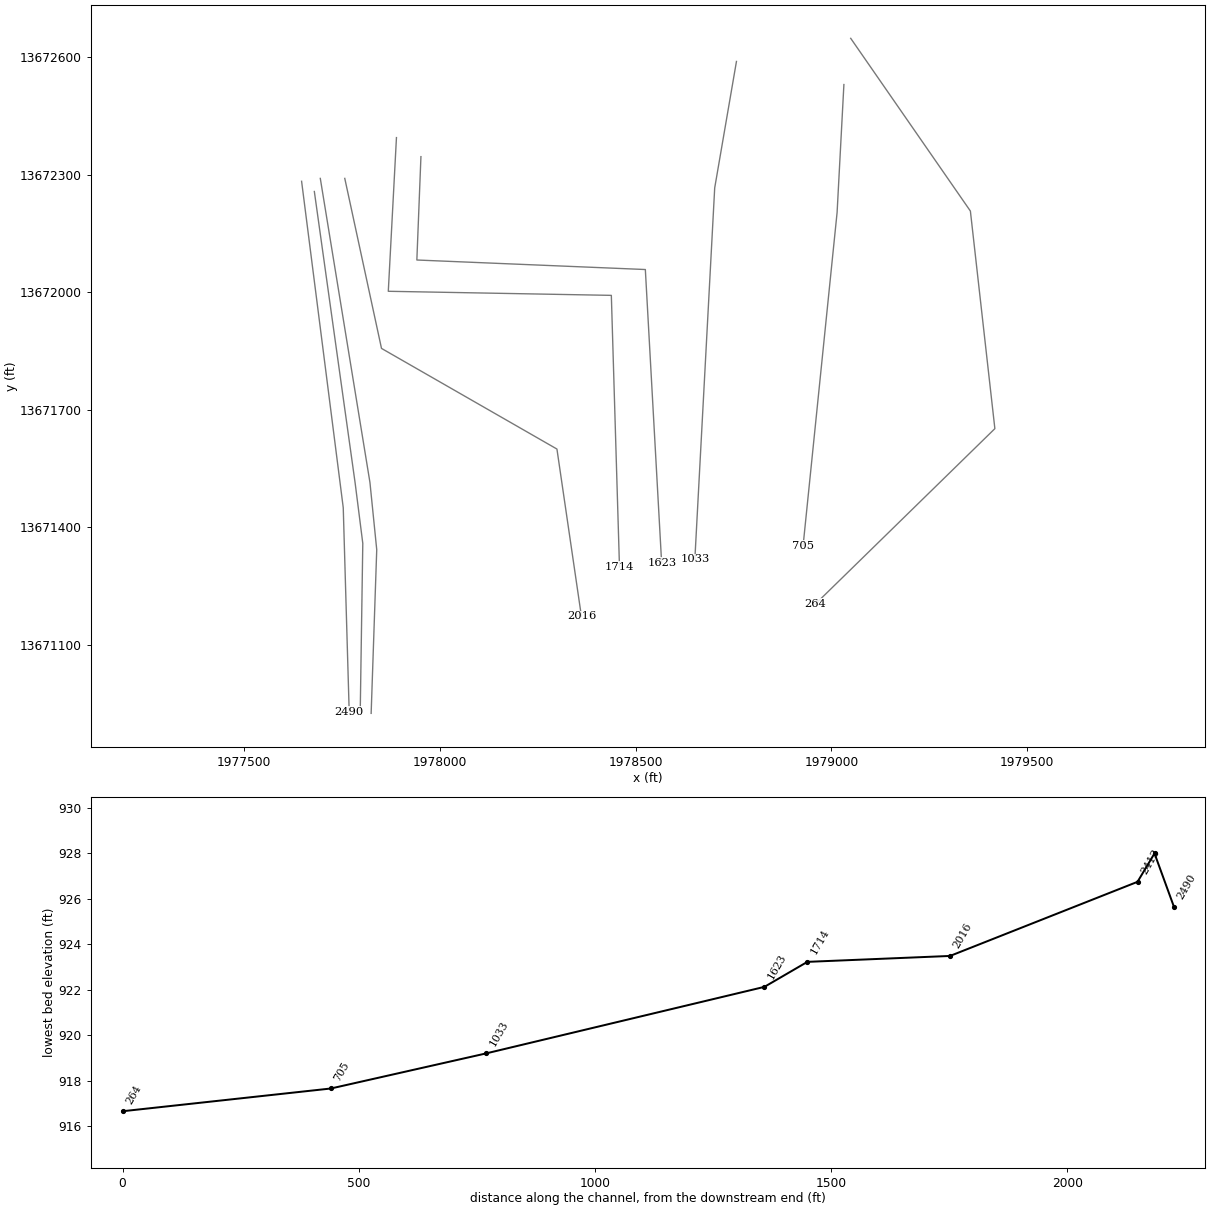
HEC-RAS study UNT 023 in HW.prj: UNT 023 in HW Base Level Engineering

--- UNT 023 in HW.g01 (geometry) --- (continued)

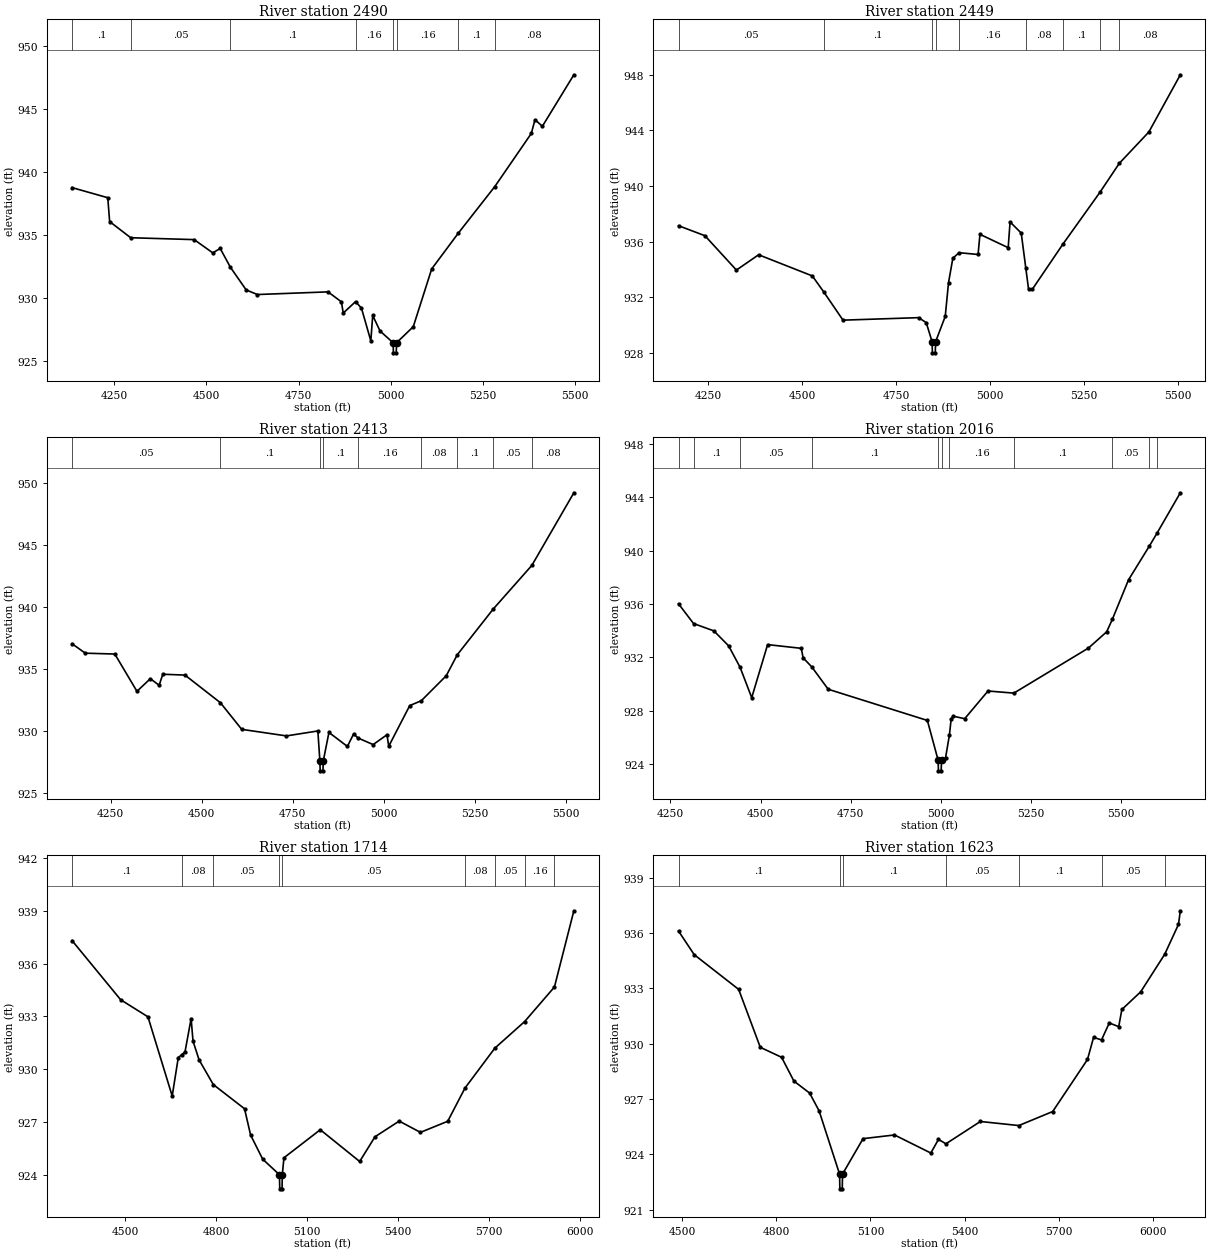
Type RM Length L Ch R = 1 ,2490    ,41,41,41
BEGIN DESCRIPTION:
Mapping XS d857f804
END DESCRIPTION:
XS GIS Cut Line= 3
      1977647.42     13672283.49      1977753.76     13671450.11
      1977768.94     13670929.67
#Sta/Elev= 30
  4135.8  938.75  4232.6  937.95  4237.7  936.06  4294.8  934.78    4467  934.63
  4517.4  933.58  4537.5  933.93  4565.4  932.43  4608.1  930.64  4638.3  930.28
  4829.9  930.49  4866.2   929.7  4871.2  928.81  4904.7  929.72  4920.6   929.2
    4946  926.61  4951.1  928.62    4971  927.39  5006.4  926.46  5007.3  925.66
  5014.9  925.66  5015.8  926.46  5061.1  927.73  5111.1  932.31  5183.7  935.16
  5282.1  938.83  5381.2  943.04  5391.2  944.13  5411.2  943.61  5496.6  947.69
#Mann= 8 ,-1 , 0
  4135.8      .1       0  4294.8     .05       0  4565.4      .1       0
  4904.7     .16       0  5006.4     .07       0  5015.8     .16       0
  5183.7      .1       0  5282.1     .08       0
Bank Sta=5006.4,5015.8
XS Rating Curve= 0 ,0
Exp/Cntr=0.3,0.1

Type RM Length L Ch R = 1 ,2449    ,36,36,36
BEGIN DESCRIPTION:
Mapping XS 203dd5c7
END DESCRIPTION:
XS GIS Cut Line= 4
      1977679.97     13672257.42      1977784.14     13671513.05
      1977803.67     13671358.97      1977797.16     13670931.45
#Sta/Elev= 30
  4171.3  937.14  4241.5  936.42  4325.2  933.95  4384.3  935.05  4527.1  933.53
    4558  932.36  4608.7  930.35  4809.9  930.53  4830.1  930.17  4845.6   928.8
  4846.5     928  4854.1     928    4855   928.8  4880.6  930.62  4889.3  933.04
  4900.8   934.8  4917.4   935.2  4967.9  935.07  4972.9  936.52    5048  935.56
    5053  937.41  5082.7  936.61  5094.9  934.08  5102.2  932.57  5112.2  932.57
  5193.4  935.81    5292  939.54  5343.4  941.62  5422.2  943.88  5505.8  947.99
#Mann= 9 ,-1 , 0
  4171.3     .05       0    4558      .1       0  4845.6     .07       0
    4855      .1       0  4917.4     .16       0  5094.9     .08       0
  5193.4      .1       0    5292     .05       0  5343.4     .08       0
Bank Sta=4845.6,4855
XS Rating Curve= 0 ,0
Exp/Cntr=0.3,0.1

Type RM Length L Ch R = 1 ,2413    ,397,397,397
BEGIN DESCRIPTION:
UNT 023 in HW 7.0
END DESCRIPTION:
XS GIS Cut Line= 4
      1977695.17     13672290.81       1977821.9     13671514.78
      1977839.26     13671342.91        1977825.     13670925.01
#Sta/Elev= 30
  4144.5  937.01  4180.8  936.25  4261.8  936.18  4322.6  933.17  4359.3  934.19
  4383.4  933.66  4393.6  934.55  4454.4  934.48  4551.6  932.25  4610.1   930.1
  4732.9  929.57  4819.1  929.97  4824.6  927.55  4825.5  926.75  4833.1  926.75
    4834  927.55  4849.5  929.85  4900.2  928.72  4917.2  929.73  4929.4   929.4
  4970.8  928.87  5008.7  929.66  5013.7  928.74  5071.3  932.02    5103  932.41
  5171.5  934.43  5201.7  936.12  5300.3  939.81  5406.5  943.34  5521.7   949.2
#Mann= 9 ,-1 , 0
  4144.5     .05       0  4551.6      .1       0  4824.6     .07       0
    4834      .1       0  4929.4     .16       0    5103     .08       0
  5201.7      .1       0  5300.3     .05       0  5406.5     .08       0
Bank Sta=4824.6,4834
XS Rating Curve= 0 ,0
Exp/Cntr=0.3,0.1

Type RM Length L Ch R = 1 ,2016    ,302,302,302
BEGIN DESCRIPTION:
UNT 023 in HW 6.0
END DESCRIPTION:
XS GIS Cut Line= 4
      1977757.67     13672290.81      1977851.42      13671856.8
      1978299.33     13671599.85      1978361.83     13671172.81
#Sta/Elev= 30
  4272.5  936.02  4314.1  934.54  4370.5  933.99  4411.4  932.87  4443.2  931.26
  4475.5  928.98  4519.6  932.96    4613  932.68  4618.1  931.97  4642.3  931.28
  4687.7  929.61  4962.8  927.27  4992.6  924.29  4993.5  923.49  5001.1  923.49
    5002  924.29  5013.1  924.45  5023.8  926.15  5028.9   927.4  5034.7  927.59
  5066.3   927.4    5131  929.48  5202.7  929.32  5409.6   932.7  5460.2  933.92
  5476.3  934.88  5520.8  937.82  5578.1  940.33  5600.9  941.37  5664.5  944.35
#Mann= 11 ,-1 , 0
  4272.5     .05       0  4314.1      .1       0  4443.2     .05       0
  4642.3      .1       0  4992.6     .07       0    5002      .1       0
  5023.8     .16       0  5202.7      .1       0  5476.3     .05       0
  5578.1     .08       0  5600.9     .05       0
Bank Sta=4992.6,5002
XS Rating Curve= 0 ,0
Exp/Cntr=0.3,0.1

Type RM Length L Ch R = 1 ,1714    ,91,91,91
BEGIN DESCRIPTION:
Mapping XS 1bfa7baf
END DESCRIPTION:
XS GIS Cut Line= 4
      1977889.61     13672395.01      1977868.78     13672002.63
      1978438.22     13671992.22      1978459.02      13671298.9
#Sta/Elev= 30
    4325   937.3  4485.2  933.95  4575.4  932.98  4655.5  928.49  4675.5  930.67
  4686.6  930.83  4697.7  930.99  4717.9  932.88  4724.2   931.6  4744.2  930.54
  4791.1  929.14  4894.2  927.77  4914.2  926.28  4954.2  924.91  5009.5  924.03
  5010.4  923.23    5018  923.23  5018.9  924.03  5024.2  924.99  5144.2  926.58
  5274.2  924.78  5324.7  926.18  5404.7  927.07  5474.8  926.43  5564.8  927.06
  5621.7  928.94  5720.1   931.2  5818.6  932.71    5917  934.67  5981.1  938.99
#Mann= 9 ,-1 , 0
    4325      .1       0  4686.6     .08       0  4791.1     .05       0
  5009.5     .04       0  5018.9     .05       0  5621.7     .08       0
  5720.1     .05       0  5818.6     .16       0    5917      .1       0
Bank Sta=5009.5,5018.9
XS Rating Curve= 0 ,0
Exp/Cntr=0.3,0.1

Type RM Length L Ch R = 1 ,1623    ,590,590,590
BEGIN DESCRIPTION:
Mapping XS 57320982
END DESCRIPTION:
XS GIS Cut Line= 4
      1977952.11      13672346.4      1977941.69     13672082.49
      1978525.03     13672058.19      1978566.64     13671309.09
#Sta/Elev= 30
  4488.9   936.1  4538.9  934.82  4680.4  932.94  4749.3   929.8  4817.1  929.26
  4856.4  927.97  4906.4  927.32  4936.5  926.36  5001.8  922.93  5002.7  922.13
  5010.3  922.13  5011.2  922.93  5076.6  924.85  5176.7  925.05  5292.5  924.07
  5316.8  924.81  5340.5  924.57  5450.2  925.78  5572.7  925.56  5680.6  926.32
  5791.4  929.14  5810.8  930.34  5836.1   930.2  5860.8  931.12  5890.9  930.92
  5900.9  931.85    5961  932.81  6037.3  934.84  6081.2  936.46  6087.1   937.2
#Mann= 7 ,-1 , 0
  4488.9      .1       0  5001.8     .07       0  5011.2      .1       0
  5340.5     .05       0  5572.7      .1       0  5836.1     .05       0
  6037.3      .1       0
Bank Sta=5001.8,5011.2
XS Rating Curve= 0 ,0
Exp/Cntr=0.3,0.1

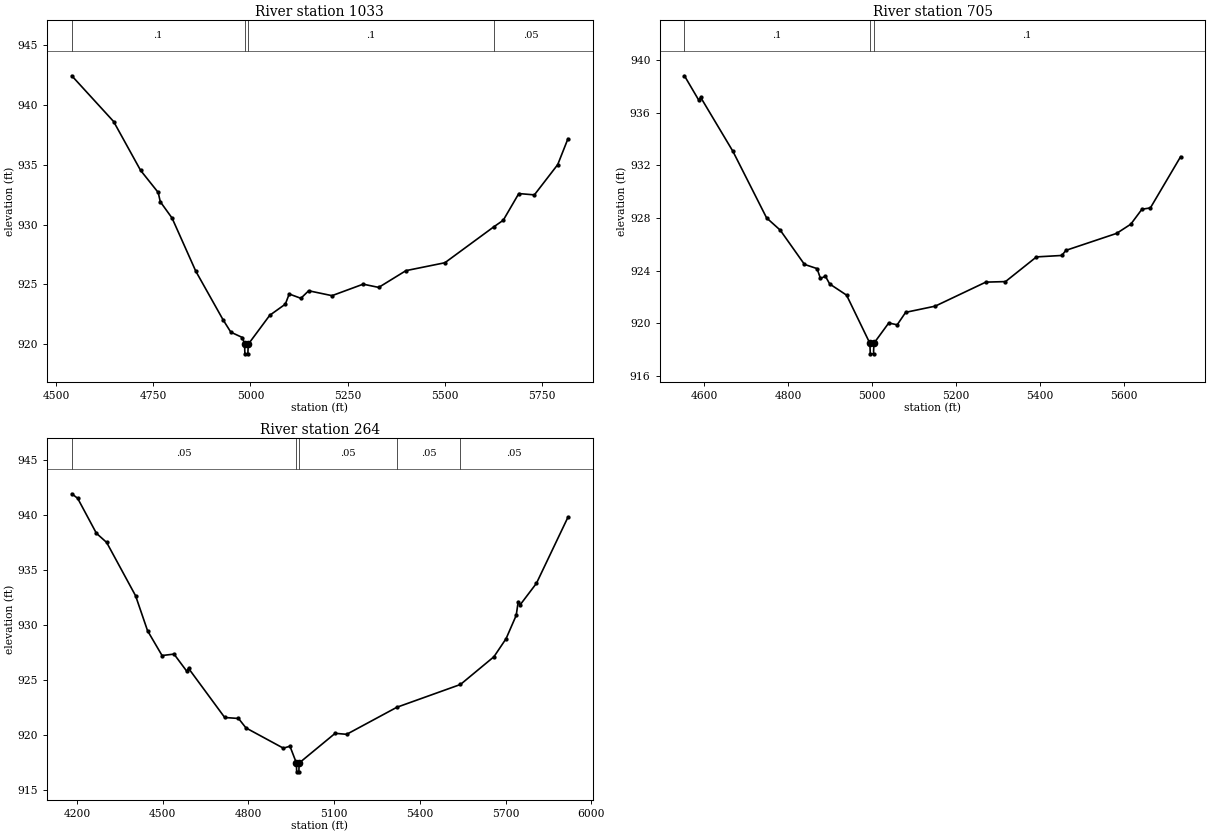
Type RM Length L Ch R = 1 ,1033    ,328,328,328
BEGIN DESCRIPTION:
UNT 023 in HW 3.0
END DESCRIPTION:
XS GIS Cut Line= 3
      1978757.66     13672589.41      1978702.11     13672266.52
      1978651.46      13671318.7
#Sta/Elev= 30
  4540.2  942.43  4647.8  938.61  4717.2  934.53  4762.6  932.68  4767.9  931.91
  4798.3  930.54  4859.2  926.11  4929.4  922.05  4949.5  921.01  4979.5  920.56
  4984.8     920  4985.7   919.2  4993.3   919.2  4994.3     920  5049.6  922.42
  5089.7  923.35  5099.7   924.2  5129.7  923.84  5149.8  924.47  5209.8  924.06
    5290  925.02    5330  924.75  5400.1  926.15  5500.3  926.81  5626.6  929.82
  5650.5  930.36  5690.5  932.59  5730.6  932.48  5790.7  935.01    5817  937.17
#Mann= 4 ,-1 , 0
  4540.2      .1       0  4984.8     .07       0  4994.3      .1       0
  5626.6     .05       0
Bank Sta=4984.8,4994.3
XS Rating Curve= 0 ,0
Exp/Cntr=0.3,0.1

Type RM Length L Ch R = 1 ,705     ,441,441,441
BEGIN DESCRIPTION:
UNT 023 in HW 2.0
END DESCRIPTION:
XS GIS Cut Line= 3
      1979031.97     13672530.46      1979014.61     13672204.02
      1978927.81     13671353.33
#Sta/Elev= 30
    4553  938.83  4586.8  936.99  4591.8  937.18  4668.6  933.07  4748.7  928.01
  4781.1  927.08  4838.9  924.47  4868.9  924.15  4876.9  923.41    4889  923.56
    4899  922.98  4939.2  922.13  4994.8  918.46  4995.7  917.66  5003.4  917.66
  5004.3  918.46  5039.7  920.01  5059.8  919.87    5080  920.82  5150.3  921.29
  5270.9  923.12  5317.8  923.16  5391.6  925.04  5451.9  925.15  5461.9  925.54
  5582.5  926.83  5616.3  927.53  5642.9  928.67    5663  928.77    5735  932.67
#Mann= 3 ,-1 , 0
    4553      .1       0  4994.8     .07       0  5004.3      .1       0
Bank Sta=4994.8,5004.3
XS Rating Curve= 0 ,0
Exp/Cntr=0.3,0.1

Type RM Length L Ch R = 1 ,264     ,0,0,0
BEGIN DESCRIPTION:
UNT 023 in HW 1.0
END DESCRIPTION:
XS GIS Cut Line= 4
      1979049.36     13672648.43      1979354.89     13672207.49
      1979417.39     13671651.94      1978959.53     13671204.48
#Sta/Elev= 30
  4182.3  941.93  4202.8  941.52  4268.4  938.34  4304.2  937.51  4405.5  932.66
  4447.4  929.48  4498.1  927.23    4540  927.36  4584.6   925.8  4590.6  926.07
  4717.2   921.6  4765.5  921.51  4791.7  920.65  4922.5  918.81  4945.5  918.99
  4968.1  917.46    4969  916.66  4976.7  916.66  4977.6  917.46  5103.6  920.16
  5143.9  920.07  5319.6  922.53    5542   924.6  5659.1  927.12  5701.5  928.76
    5737  930.88    5744  932.13  5751.1  931.85  5807.7  933.79    5918   939.8
#Mann= 5 ,-1 , 0
  4182.3     .05       0  4968.1     .04       0  4977.6     .05       0
  5319.6     .05       0    5542     .05       0
Bank Sta=4968.1,4977.6
XS Rating Curve= 0 ,0
Exp/Cntr=0.3,0.1
LCMann Table=0

Chan Stop Cuts=-1
Use User Specified Reach Order=0
Composite Channel Slope=5