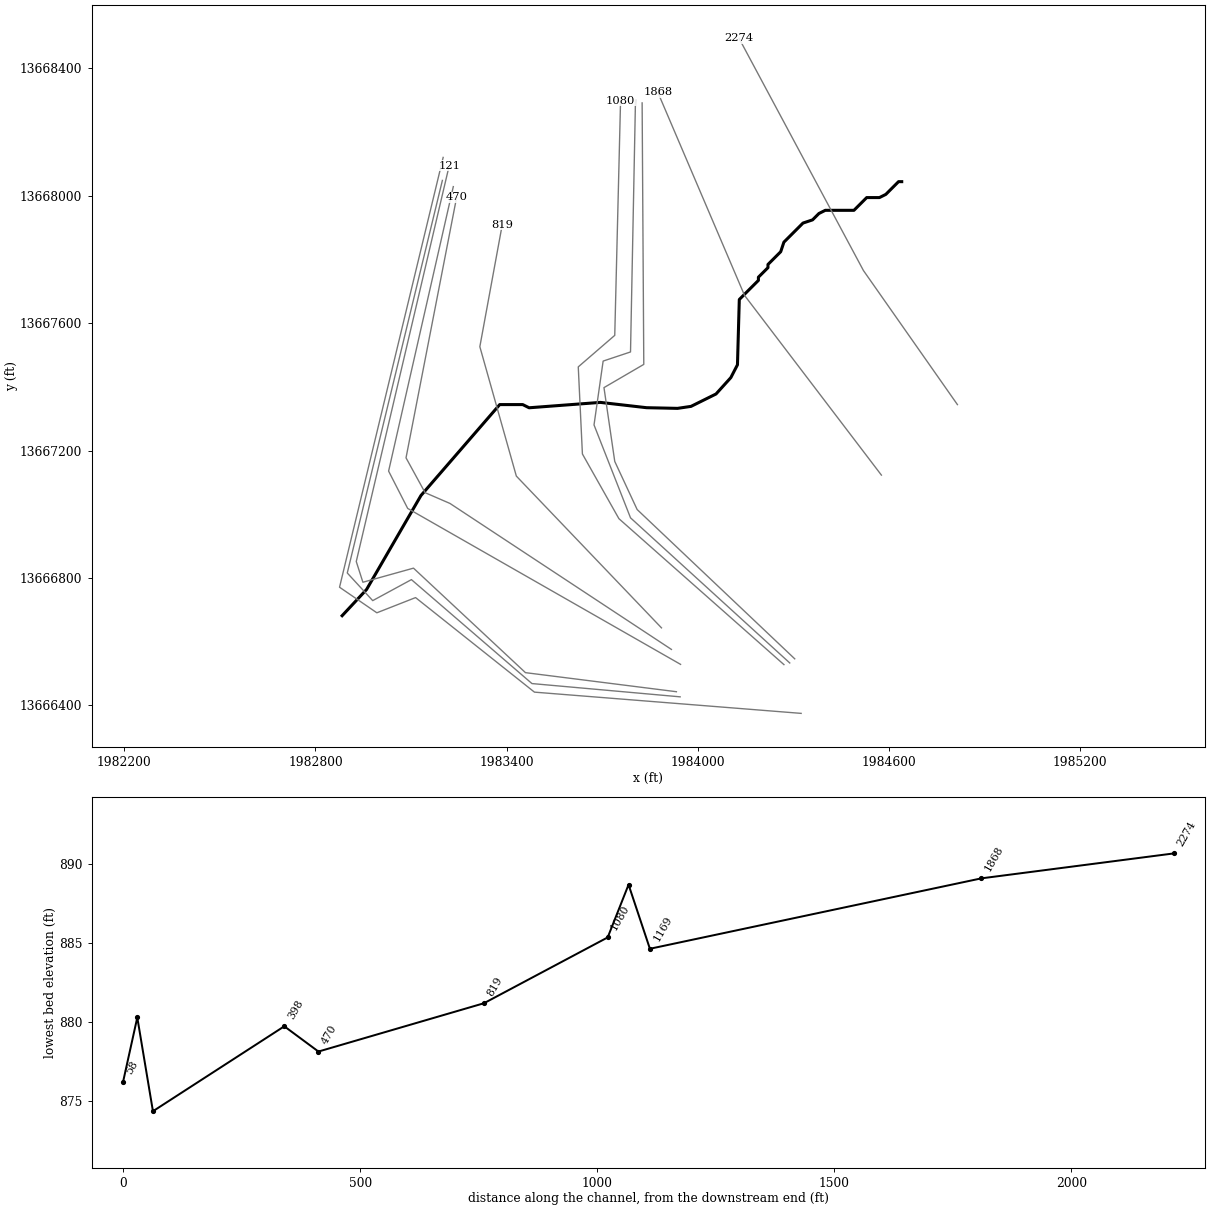
--- UNT 024 in HW.prj (project) ---

Proj Title=UNT 024 in HW Base Level Engineering
Current Plan=p01
Default Exp/Contr=0.3,0.1
English Units
Geom File=g01
Flow File=f01
Plan File=p01
Y Axis Title=Elevation
X Axis Title(PF)=Main Channel Distance
X Axis Title(XS)=Station
BEGIN DESCRIPTION:
UNT 024 in HW
END DESCRIPTION:
DSS Export Rating Curves= 0
DSS Export Rating Curve Sorted= 0
DSS Export Volume Flow Curves= 0
DXF OffsetX= 0
DXF OffsetY= 0
DXF ScaleX= 1
DXF ScaleY= 10

--- UNT 024 in HW.p01 (plan) ---

Plan Title=Multiple Run
Short Identifier=Multiple
Geom File=g01
Flow File=f01
Subcritical Flow
K Sum by GR= 0
Std Step Tol= 0.01
Critical Tol= 0.01
Num of Std Step Trials= 20
Max Error Tol= 0.3
Flow Tol Ratio= 0.001
Split Flow NTrial= 30
Split Flow Tol= 0.02
Split Flow Ratio= 0.02
Log Output Level= 0
Friction Slope Method= 1
Unsteady Friction Slope Method= 2
Unsteady Bridges Friction Slope Method= 1
Parabolic Critical Depth
Global Vel Dist=  1 , 1 , 1
Global Log Level= 0
CheckData=True
Encroach Param= -1, 0, 0, 0
BEGIN DESCRIPTION:
Multiple Run
END DESCRIPTION:

--- UNT 024 in HW.f01 (steady flow) ---

Flow Title=Multiple
Number of Profiles=7
Profile Names=10-year,25-year,50-year,1pct_min,100-year,1pct_plu,500-year
River Rch & RM= UNT 024 in HW,Reach-1,2274
     455     631     777     475     947    1890    1410
Boundary for River Rch & Prof#=UNT 024 in HW,Reach-1,1
Up Type=0
Dn Type=3
Dn Slope=0.005
Boundary for River Rch & Prof#=UNT 024 in HW,Reach-1,2
Up Type=0
Dn Type=3
Dn Slope=0.005
Boundary for River Rch & Prof#=UNT 024 in HW,Reach-1,3
Up Type=0
Dn Type=3
Dn Slope=0.005
Boundary for River Rch & Prof#=UNT 024 in HW,Reach-1,4
Up Type=0
Dn Type=3
Dn Slope=0.005
Boundary for River Rch & Prof#=UNT 024 in HW,Reach-1,5
Up Type=0
Dn Type=3
Dn Slope=0.005
Boundary for River Rch & Prof#=UNT 024 in HW,Reach-1,6
Up Type=0
Dn Type=3
Dn Slope=0.005
Boundary for River Rch & Prof#=UNT 024 in HW,Reach-1,7
Up Type=0
Dn Type=3
Dn Slope=0.005

--- UNT 024 in HW.g01 (geometry) ---

Geom Title=Existing Conditions
Program Version=5.05

River Reach=UNT 024 in HW   ,Reach-1
Reach XY= 30
       1984640.8     13668044.54       1984630.8     13668044.54
       1984590.8     13668004.54       1984570.8     13667994.54
       1984530.8     13667994.54       1984490.8     13667954.54
       1984400.8     13667954.54       1984380.8     13667944.54
       1984360.8     13667924.54       1984330.8     13667914.54
       1984270.8     13667854.54       1984260.8     13667824.54
       1984220.8     13667784.54       1984220.8     13667774.54
       1984190.8     13667744.54       1984190.8     13667734.54
       1984130.8     13667674.54      1984125.03      13667469.5
       1984104.2     13667429.22      1984057.67     13667377.83
       1983979.2     13667338.94      1983936.84     13667332.69
      1983839.61     13667334.78      1983694.47     13667351.44
       1983470.8     13667334.54       1983450.8     13667344.54
       1983378.5     13667344.54      1983131.28     13667059.08
      1982960.45     13666763.94       1982883.7     13666681.64

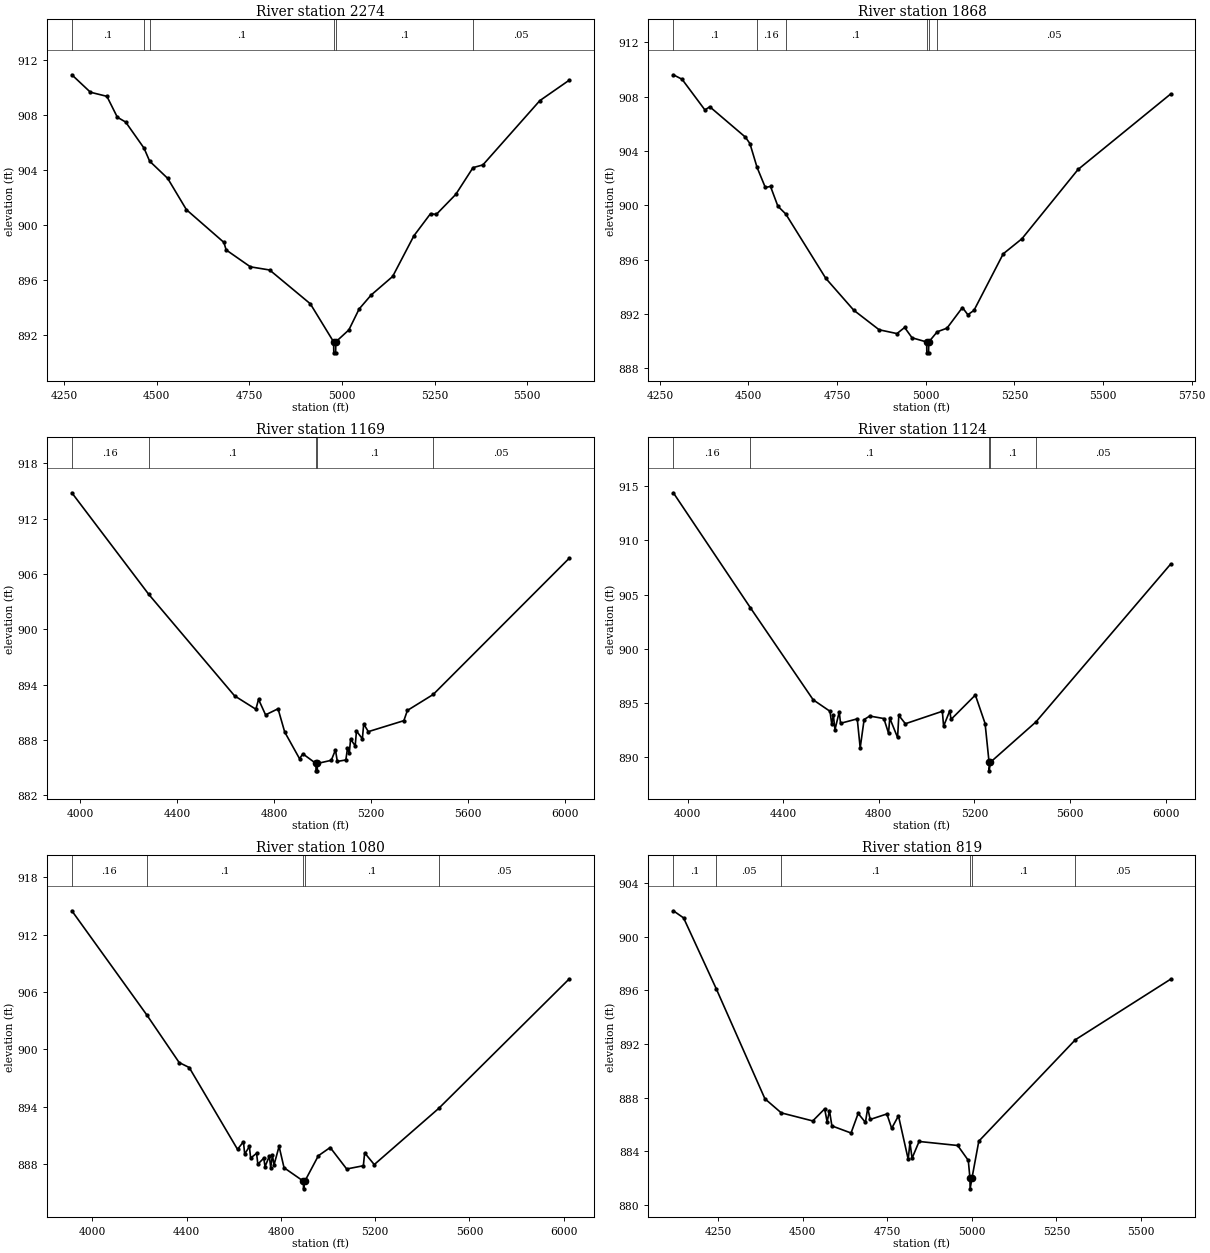
Type RM Length L Ch R = 1 ,2274    ,406,406,406
BEGIN DESCRIPTION:
UNT 024 in HW 4.0
END DESCRIPTION:
XS GIS Cut Line= 3
      1984815.67      13667344.5      1984520.56     13667765.46
      1984129.99     13668494.53
#Sta/Elev= 30
  4271.4  910.94  4321.5  909.67    4366  909.37  4394.1  907.85  4416.5   907.5
  4466.1   905.6  4481.3  904.65  4529.9   903.4  4580.4  901.12  4681.5  898.74
  4687.6  898.19    4753  896.96  4804.9  896.73  4914.6  894.27  4977.4   891.5
  4977.9   890.7  4982.9   890.7  4983.4   891.5  5018.6  892.37  5046.2  893.89
  5078.7  894.91  5136.7  896.26    5194  899.22  5238.8  900.83  5254.2  900.77
  5306.8  902.23  5353.4  904.18  5380.1  904.38  5533.7  909.06  5612.6  910.54
#Mann= 6 ,-1 , 0
  4271.4      .1       0  4466.1     .16       0  4481.3      .1       0
  4977.4     .07       0  4983.4      .1       0  5353.4     .05       0
Bank Sta=4977.4,4983.4
XS Rating Curve= 0 ,0
Exp/Cntr=0.3,0.1

Type RM Length L Ch R = 1 ,1868    ,699,699,699
BEGIN DESCRIPTION:
UNT 024 in HW 3.0
END DESCRIPTION:
XS GIS Cut Line= 3
      1984576.96     13667123.13      1984147.29     13667687.34
      1983874.98     13668325.05
#Sta/Elev= 30
    4288  909.62  4312.6  909.29    4377  907.03  4390.9  907.26  4491.4  905.02
    4504  904.55  4524.2  902.79  4547.5  901.31  4562.1  901.39  4582.9  899.93
    4605  899.36  4718.1  894.61    4797  892.26  4868.5  890.82  4918.8  890.54
  4940.4  890.99  4961.3  890.23  5002.5  889.92    5003  889.12    5008  889.12
  5008.5  889.92  5032.2  890.67  5059.9  890.94  5103.4  892.46  5118.7  891.93
    5136  892.25  5218.5  896.42  5271.2  897.53  5429.6  902.64  5690.6   908.2
#Mann= 6 ,-1 , 0
    4288      .1       0  4524.2     .16       0    4605      .1       0
  5002.5     .07       0  5008.5      .1       0  5032.2     .05       0
Bank Sta=5002.5,5008.5
XS Rating Curve= 0 ,0
Exp/Cntr=0.3,0.1

Type RM Length L Ch R = 1 ,1169    ,45,45,45
BEGIN DESCRIPTION:
Mapping XS e03a73b2
END DESCRIPTION:
XS GIS Cut Line= 6
      1984304.85     13666546.28      1983810.05     13667015.03
      1983739.74     13667166.07      1983705.89     13667397.84
      1983830.89     13667470.76      1983825.69      13668291.8
#Sta/Elev= 30
  3965.9  914.81  4283.2  903.79    4637  892.79  4724.7  891.34  4735.7  892.41
  4764.7  890.73  4816.1  891.39  4843.6  888.87  4904.7  885.98  4918.6   886.5
  4972.3  885.46  4972.8  884.66  4977.8  884.66  4978.3  885.46  5035.6   885.8
  5052.9  886.93  5060.5  885.68  5095.8  885.84  5102.3  887.09    5110   886.6
  5115.3   888.1  5134.2  887.37  5139.5  888.97  5163.9  888.14  5169.3  889.74
  5188.4  888.91  5334.9   890.1  5349.5  891.21  5455.9  892.94  6016.3   907.7
#Mann= 5 ,-1 , 0
  3965.9     .16       0  4283.2      .1       0  4972.3     .07       0
  4978.3      .1       0  5455.9     .05       0
Bank Sta=4972.3,4978.3
XS Rating Curve= 0 ,0
Exp/Cntr=0.3,0.1

Type RM Length L Ch R = 1 ,1124    ,44,44,44
BEGIN DESCRIPTION:
Mapping XS e60edd22
END DESCRIPTION:
XS GIS Cut Line= 6
      1984289.22     13666533.26      1983789.22     13666988.99
      1983674.64     13667280.66      1983703.28     13667481.18
      1983789.22     13667509.82      1983804.83     13668300.75
#Sta/Elev= 30
  3940.4   914.4  4262.7  903.78  4525.3  895.28  4595.6  894.22    4603  893.02
  4609.7  893.87  4616.4  892.52  4634.3  894.16  4639.8  893.11  4709.6  893.52
  4721.9  890.84  4738.4  893.46  4761.7  893.78  4820.9  893.55  4840.4   892.2
  4845.7  893.58  4878.3   891.8  4883.5  893.84  4910.9  893.07  5065.5  894.22
  5070.8  892.84  5096.6  894.27  5101.9  893.47  5203.6  895.72  5244.3  893.09
  5260.9  889.52  5261.4  888.72  5266.9  889.52  5456.6  893.23  6020.2  907.81
#Mann= 5 ,-1 , 0
  3940.4     .16       0  4262.7      .1       0  5260.9     .07       0
  5266.9      .1       0  5456.6     .05       0
Bank Sta=5260.9,5266.9
XS Rating Curve= 0 ,0
Exp/Cntr=0.3,0.1

Type RM Length L Ch R = 1 ,1080    ,261,261,261
BEGIN DESCRIPTION:
Mapping XS eb04e0b5
END DESCRIPTION:
XS GIS Cut Line= 6
      1984270.97     13666528.07      1983752.76     13666986.38
      1983638.18     13667189.51      1983625.16     13667462.95
      1983739.74     13667561.91      1983757.97     13668298.93
#Sta/Elev= 30
  3912.4  914.51    4231  903.58  4367.9  898.61  4410.5  898.09  4615.5  889.52
  4640.7  890.31    4646  889.02  4665.9  889.82  4671.2   888.6  4696.4   889.1
  4701.8  887.96    4727   888.6  4732.3  887.71  4750.7  888.81  4756.4   887.6
  4763.6  888.88  4770.6   887.9  4791.9  889.83    4813  887.59  4895.2  886.18
  4895.7  885.38  4901.2  886.18  4958.7  888.85  5008.8  889.71  5078.8  887.46
  5149.6   887.8  5155.1  889.15  5195.8  887.92  5469.1   893.8  6022.8  907.36
#Mann= 5 ,-1 , 0
  3912.4     .16       0    4231      .1       0  4895.2     .07       0
  4901.2      .1       0  5469.1     .05       0
Bank Sta=4895.2,4901.2
XS Rating Curve= 0 ,0
Exp/Cntr=0.3,0.1

Type RM Length L Ch R = 1 ,819     ,349,349,349
BEGIN DESCRIPTION:
Mapping XS 54fb6a40
END DESCRIPTION:
XS GIS Cut Line= 4
      1983886.47     13666643.47      1983430.71     13667120.07
      1983316.13     13667526.32      1983386.45     13667909.17
#Sta/Elev= 30
  4116.9  901.93  4147.2   901.4  4243.8  896.12  4387.8  887.92  4436.2  886.87
  4529.3  886.27  4564.5  887.17  4571.8   886.2  4578.7  887.04  4585.9   885.9
  4642.5  885.37  4663.6  886.83    4685  886.16  4691.9  887.23  4699.1  886.38
  4748.5  886.79  4762.7  885.72  4782.8  886.65  4811.6  883.41  4816.8  884.67
    4823  883.49  4843.8  884.74    4958  884.44  4989.3  883.33  4994.2  882.01
  4994.7  881.21  5000.2  882.01  5020.4  884.76    5306  892.32  5587.7  896.83
#Mann= 6 ,-1 , 0
  4116.9      .1       0  4243.8     .05       0  4436.2      .1       0
  4994.2     .07       0  5000.2      .1       0    5306     .05       0
Bank Sta=4994.2,5000.2
XS Rating Curve= 0 ,0
Exp/Cntr=0.3,0.1

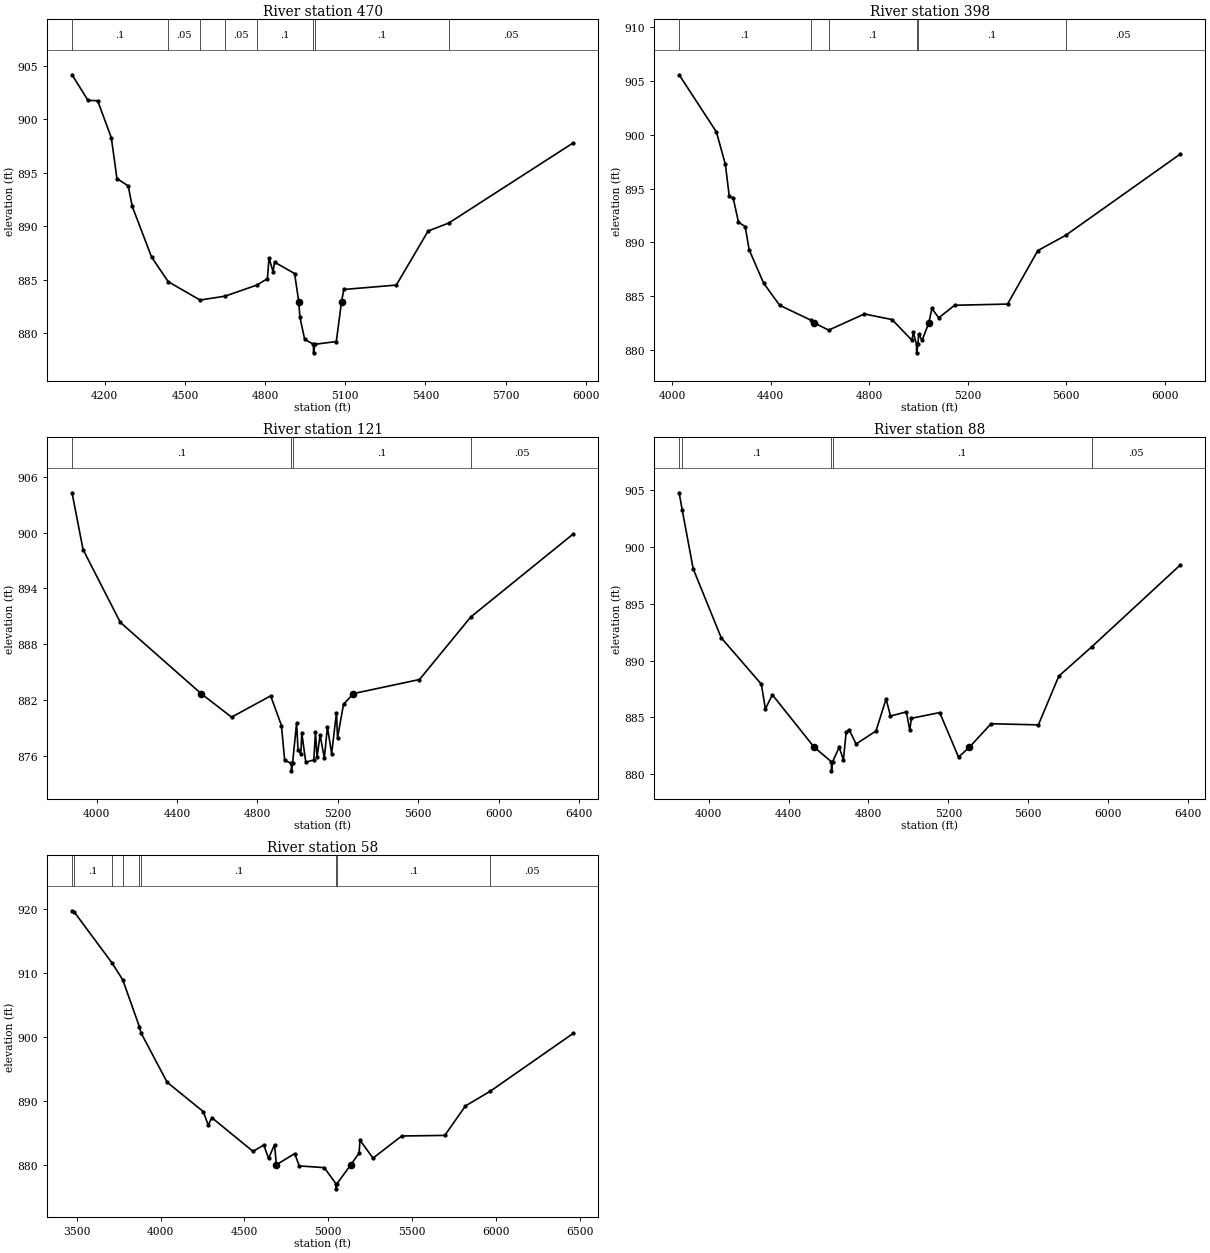
Type RM Length L Ch R = 1 ,470     ,72,72,72
BEGIN DESCRIPTION:
Mapping XS 59f83455
END DESCRIPTION:
XS GIS Cut Line= 5
      1983917.69     13666575.79      1983222.38     13667034.13
      1983144.26     13667067.98      1983084.36     13667177.36
      1983243.21     13667995.04
#Sta/Elev= 30
  4077.5  904.17  4137.1  901.78  4173.3  901.74  4224.5  898.28  4245.5  894.46
  4287.7  893.77  4302.7  891.86    4375  887.12  4437.3  884.81  4556.5  883.09
  4649.6  883.45  4769.2  884.49  4808.6  885.09  4814.6  887.02  4829.7  885.76
  4835.7  886.63  4910.3  885.57 4925.87882.9514  4929.9  881.53  4947.9  879.42
  4980.7  878.95  4981.2  878.15  4986.7  878.95  5066.4  879.21 5086.06882.9521
  5094.6  884.08  5290.9  884.49    5410  889.55  5487.5   890.3  5953.1   897.8
#Mann= 8 ,-1 , 0
  4077.5      .1       0  4437.3     .05       0  4556.5     .08       0
  4649.6     .05       0  4769.2      .1       0  4980.7     .07       0
  4986.7      .1       0  5487.5     .05       0
Bank Sta=4925.87,5086.06
XS Rating Curve= 0 ,0
Exp/Cntr=0.3,0.1

Type RM Length L Ch R = 1 ,398     ,277,277,277
BEGIN DESCRIPTION:
Mapping XS 97df96b8
END DESCRIPTION:
XS GIS Cut Line= 4
      1983946.37      13666528.9      1983089.57      13667018.5
      1983029.67     13667135.69      1983232.81     13668028.96
#Sta/Elev= 30
  4028.9  905.58  4180.2  900.27  4216.5  897.26  4232.4  894.29  4248.2  894.15
  4269.8  891.88  4297.1  891.48    4313  889.33    4372  886.22  4436.8  884.17
  4562.3   882.8 4576.82882.5403  4635.6  881.86  4780.9  883.36  4893.2  882.84
  4973.8  880.92  4979.5  881.64  4992.4  880.55  4992.9  879.75  4998.4  880.55
  5001.1  881.46  5015.5  880.92 5042.37882.5405  5054.9  883.87  5082.7     883
    5147  884.17    5362  884.28    5485  889.25  5597.5  890.66  6063.4  898.22
#Mann= 6 ,-1 , 0
  4028.9      .1       0  4562.3     .08       0  4635.6      .1       0
  4992.4     .07       0  4998.4      .1       0  5597.5     .05       0
Bank Sta=4576.82,5042.37
XS Rating Curve= 0 ,0
Exp/Cntr=0.3,0.1

Type RM Length L Ch R = 1 ,121     ,33,33,33
BEGIN DESCRIPTION:
Mapping XS deb58d62
END DESCRIPTION:
XS GIS Cut Line= 6
      1983933.29     13666442.99      1983459.36     13666502.88
       1983107.8       13666831.      1982948.94     13666786.73
      1982928.11     13666851.84      1983219.77       13668094.
#Sta/Elev= 30
  3878.3   904.3  3933.1  898.19  4118.5  890.35  4520.4882.6844    4672  880.15
  4866.5  882.44  4920.1  879.25  4936.1   875.5  4969.3  875.17  4969.8  874.37
  4975.3  875.17  4995.4   879.5  5002.5  876.65  5016.6  876.18  5021.4  878.43
  5041.3  875.29  5081.1  875.55  5089.5  878.57  5097.1  875.81  5112.3  878.23
  5133.5  875.74  5148.8  879.09  5169.9  876.23    5194  880.64  5199.1  877.92
  5228.9  881.53 5277.92882.6844  5606.9   884.2  5861.9  890.93  6371.9  899.87
#Mann= 4 ,-1 , 0
  3878.3      .1       0  4969.3     .07       0  4975.3      .1       0
  5861.9     .05       0
Bank Sta=4520.4,5277.92
XS Rating Curve= 0 ,0
Exp/Cntr=0.3,0.1

Type RM Length L Ch R = 1 ,88      ,30,30,30
BEGIN DESCRIPTION:
Mapping XS 6c7671fa
END DESCRIPTION:
XS GIS Cut Line= 6
      1983945.07     13666426.92      1983479.76     13666468.59
      1983101.29     13666794.98      1982979.76     13666729.01
       1982899.9     13666815.81      1983198.51     13668048.45
#Sta/Elev= 30
  3851.8  904.75  3866.8  903.28  3922.2  898.07  4062.7     892  4263.5  887.93
  4283.6  885.76  4318.9  886.99 4528.01882.3875  4614.2  881.11  4614.7  880.31
  4620.2  881.11  4653.4  882.39  4674.3  881.27  4688.5  883.73  4702.8  883.93
  4737.9  882.67  4837.6  883.81  4888.1  886.63  4910.2  885.13  4989.5  885.49
  5006.8  883.89  5014.8  884.93  5156.7  885.43  5250.8  881.52  5305.4882.3873
  5413.6  884.45  5650.7  884.35  5753.2  888.64  5919.2  891.23  6361.7  898.41
#Mann= 5 ,-1 , 0
  3851.8     .16       0  3866.8      .1       0  4614.2     .07       0
  4620.2      .1       0  5919.2     .05       0
Bank Sta=4528.01,5305.4
XS Rating Curve= 0 ,0
Exp/Cntr=0.3,0.1

Type RM Length L Ch R = 1 ,58      ,0,0,0
BEGIN DESCRIPTION:
UNT 024 in HW 1.0
END DESCRIPTION:
XS GIS Cut Line= 6
      1984324.99       13666375.      1983487.57     13666441.68
      1983114.31     13666738.55      1982992.78     13666690.81
      1982875.59     13666771.11      1983200.94     13668120.65
#Sta/Elev= 30
  3472.4  919.79  3484.9  919.62  3711.3   911.6  3774.6  908.98  3873.6  901.66
    3883   900.7  4039.3  892.93  4254.9  888.33    4285  886.17    4305  887.39
  4551.4   882.1  4615.5  883.09  4644.4  880.99  4679.6  883.16 4690.74 879.996
    4800  881.75  4827.1  879.82  4976.5  879.55  5045.9  877.03  5046.4  876.23
  5051.9  877.03  5134.4879.9951  5183.9  881.83  5189.3  883.86    5267  881.04
    5438  884.51  5694.8   884.6  5818.1  889.22  5964.2  891.49  6460.9  900.59
#Mann= 9 ,-1 , 0
  3472.4     .16       0  3484.9      .1       0  3711.3     .16       0
  3774.6      .1       0  3873.6     .16       0    3883      .1       0
  5045.9     .07       0  5051.9      .1       0  5964.2     .05       0
Bank Sta=4690.74,5134.4
XS Rating Curve= 0 ,0
Exp/Cntr=0.3,0.1
LCMann Table=0

Chan Stop Cuts=-1
Use User Specified Reach Order=0
Composite Channel Slope=5