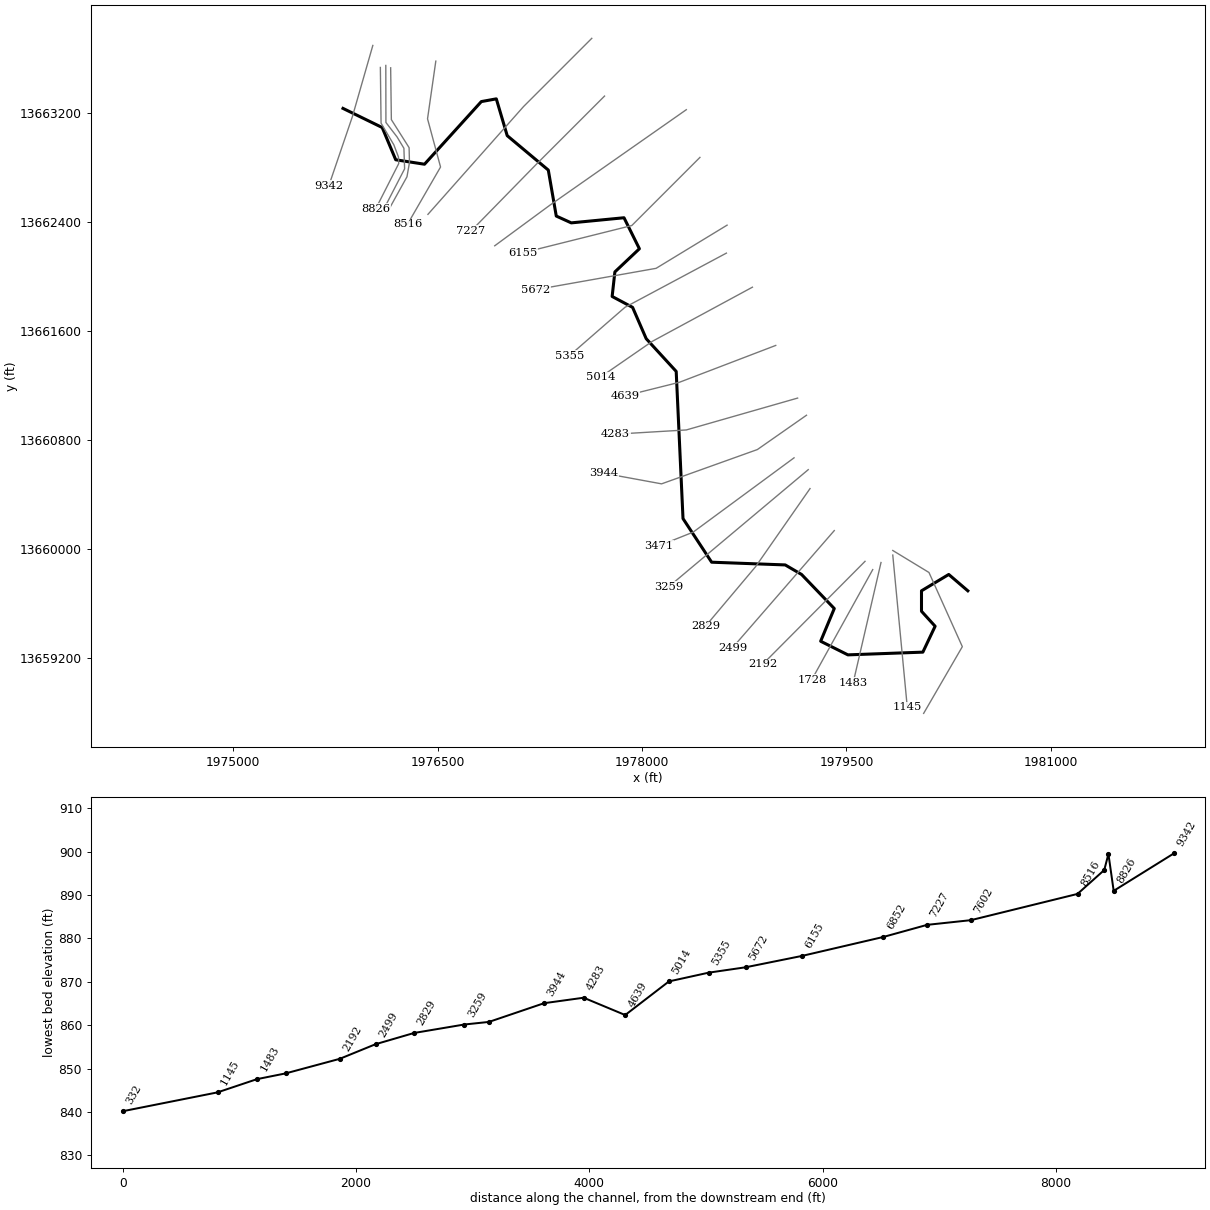
--- UNT 026 in HW.prj (project) ---

Proj Title=UNT 026 in HW Base Level Engineering
Current Plan=p01
Default Exp/Contr=0.3,0.1
English Units
Geom File=g01
Flow File=f01
Plan File=p01
BEGIN DESCRIPTION:
UNT 026 in HW
END DESCRIPTION:

--- UNT 026 in HW.p01 (plan) ---

Plan Title=Multiple Run
Short Identifier=Multiple
Geom File=g01
Flow File=f01
Subcritical Flow
K Sum by GR= 0
Std Step Tol= 0.01
Critical Tol= 0.01
Num of Std Step Trials= 20
Max Error Tol= 0.3
Flow Tol Ratio= 0.001
Split Flow NTrial= 30
Split Flow Tol= 0.02
Split Flow Ratio= 0.02
Log Output Level= 0
Friction Slope Method= 1
Unsteady Friction Slope Method= 2
Unsteady Bridges Friction Slope Method= 1
Parabolic Critical Depth
Global Vel Dist=  1 , 1 , 1
Global Log Level= 0
CheckData=True
Encroach Param= -1, 0, 0, 0
BEGIN DESCRIPTION:
Multiple Run
END DESCRIPTION:

--- UNT 026 in HW.f01 (steady flow) ---

Flow Title=Multiple
Number of Profiles=7
Profile Names=10-year,25-year,50-year,1pct_min,100-year,1pct_plu,500-year
River Rch & RM= UNT 026 in HW,Reach-1,9342
     558     778     960     587    1171    2336    1745
River Rch & RM= UNT 026 in HW,Reach-1,7602
    1017    1464    1846    1150    2294    4578    3559
Boundary for River Rch & Prof#=UNT 026 in HW,Reach-1,1
Up Type=0
Dn Type=3
Dn Slope=0.005
Boundary for River Rch & Prof#=UNT 026 in HW,Reach-1,2
Up Type=0
Dn Type=3
Dn Slope=0.005
Boundary for River Rch & Prof#=UNT 026 in HW,Reach-1,3
Up Type=0
Dn Type=3
Dn Slope=0.005
Boundary for River Rch & Prof#=UNT 026 in HW,Reach-1,4
Up Type=0
Dn Type=3
Dn Slope=0.005
Boundary for River Rch & Prof#=UNT 026 in HW,Reach-1,5
Up Type=0
Dn Type=3
Dn Slope=0.005
Boundary for River Rch & Prof#=UNT 026 in HW,Reach-1,6
Up Type=0
Dn Type=3
Dn Slope=0.005
Boundary for River Rch & Prof#=UNT 026 in HW,Reach-1,7
Up Type=0
Dn Type=3
Dn Slope=0.005

--- UNT 026 in HW.g01 (geometry) ---

Geom Title=Existing Conditions

River Reach=UNT 026 in HW,Reach-1
Reach XY= 30
      1975805.80     13663234.54      1976093.43     13663094.30
      1976192.74     13662857.49      1976403.85     13662824.85
      1976820.80     13663284.54      1976930.80     13663304.54
      1977010.80     13663034.54      1977312.33     13662781.93
      1977370.80     13662444.54      1977480.80     13662394.54
      1977867.89     13662432.10      1977980.80     13662204.54
      1977800.80     13662034.54      1977780.80     13661854.54
      1977930.80     13661774.54      1978030.80     13661544.54
      1978250.80     13661304.54      1978300.80     13660224.54
      1978510.80     13659904.54      1979050.80     13659884.54
      1979170.80     13659814.54      1979410.80     13659564.54
      1979310.80     13659324.54      1979510.80     13659224.54
      1980060.80     13659244.54      1980150.80     13659434.54
      1980050.80     13659544.54      1980050.80     13659694.54
      1980250.80     13659814.54      1980390.80     13659694.54

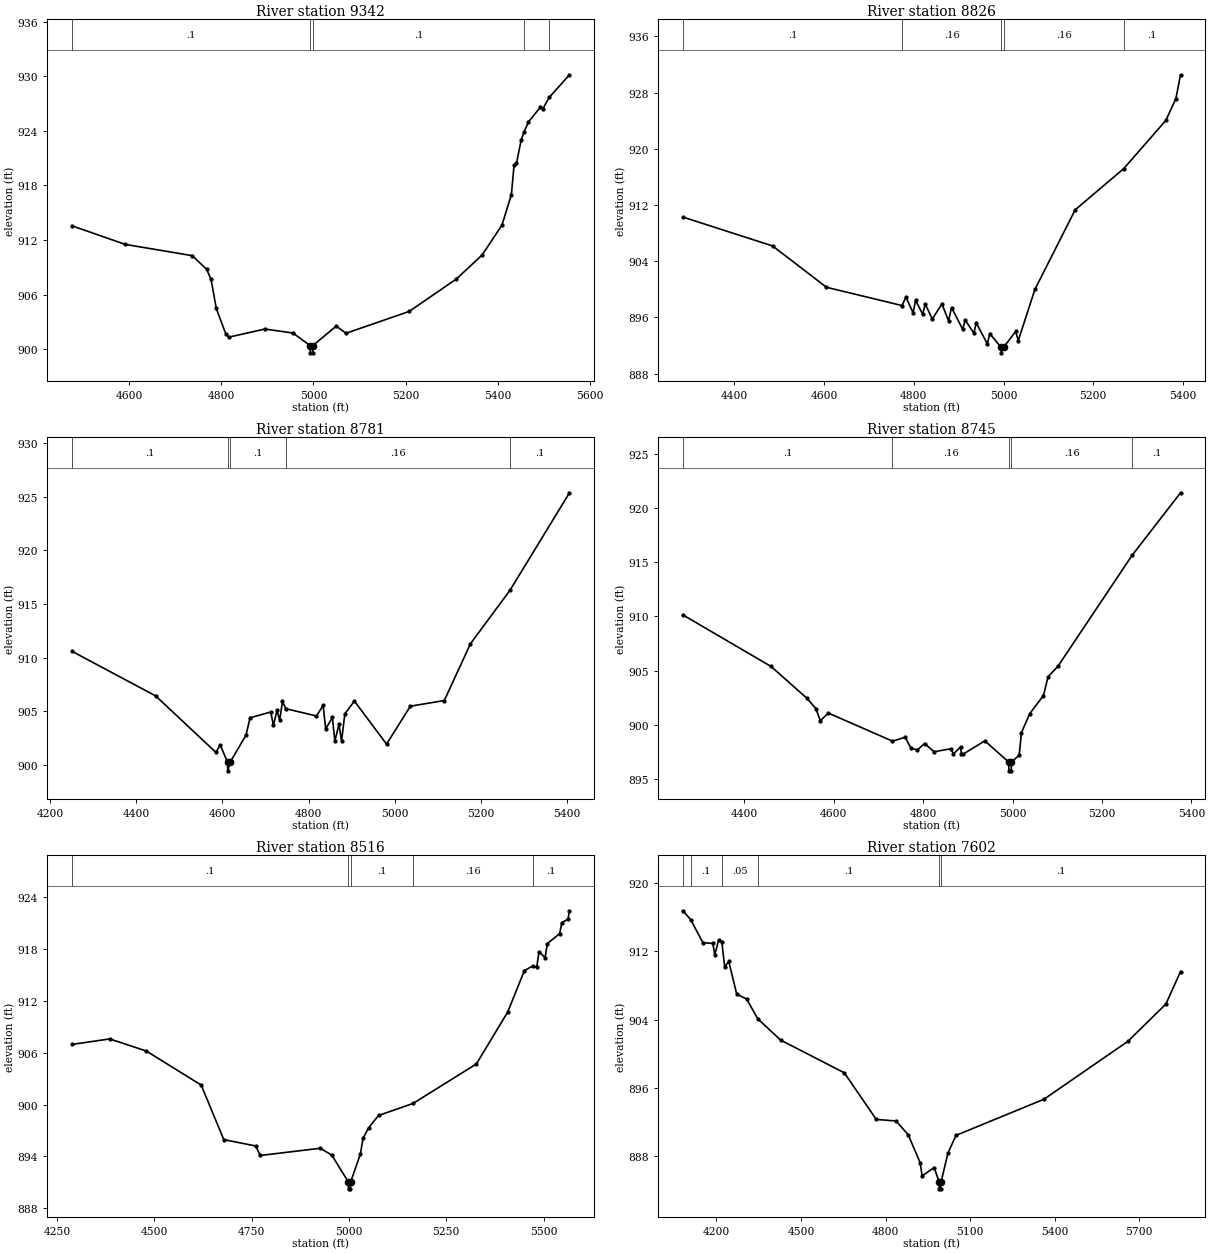
Type RM Length L Ch R = 1,9342,516,516,516
BEGIN DESCRIPTION:
UNT 026 in HW 15.0
END DESCRIPTION:
XS GIS Cut Line= 3
      1976024.65     13663696.43      1975875.00     13663175.00
      1975701.29     13662665.58
#Sta/Elev= 30
  4475.3  913.57  4591.2  911.52  4736.9  910.28  4768.1  908.77  4777.7  907.66
  4788.9  904.47  4809.7  901.66  4816.7  901.32  4894.5  902.21  4955.4  901.77
  4992.7  900.39  4993.2  899.59  4998.2  899.59  4998.7  900.39  5049.5  902.53
  5070.6  901.74  5208.0  904.15  5310.2  907.71  5366.4  910.36  5409.5  913.66
  5429.8  917.00  5435.6  920.21  5440.9  920.44  5451.0  923.00  5457.5  923.92
  5466.9  924.99  5493.0  926.63  5498.3  926.45  5512.1  927.70  5556.0  930.18
#Mann=5,-1,0
  4475.3     0.1       0  4992.7    0.07       0  4998.7     0.1       0
  5457.5    0.16       0  5512.1     0.1       0
Bank Sta=4992.7,4998.7
Exp/Cntr=0.3,0.1

Type RM Length L Ch R = 1,8826,45,45,45
BEGIN DESCRIPTION:
UNT 026 in HW 14.0
END DESCRIPTION:
XS GIS Cut Line= 6
      1976079.98     13663534.88      1976085.18     13663126.07
      1976179.15     13662966.78      1976212.79     13662877.81
      1976214.96     13662830.06      1976046.46     13662498.51
#Sta/Elev= 30
  4285.6  910.28  4485.5  906.17  4605.5  900.29  4773.7  897.69  4782.7  898.88
  4798.4  896.67  4804.2  898.42  4819.8  896.47  4825.6  897.91  4841.3  895.76
  4862.7  897.92  4877.5  895.52  4884.2  897.41  4909.0  894.30  4914.4  895.63
  4933.9  893.78  4939.2  895.23  4964.0  892.22  4969.4  893.70  4994.3  891.76
  4994.8  890.96  5000.3  891.76  5027.0  894.01  5032.9  892.71  5069.9  899.98
  5159.7  911.32  5267.8  917.17  5361.6  924.03  5384.0  927.13  5394.4  930.53
#Mann=5,-1,0
  4285.6     0.1       0  4773.7    0.16       0  4994.3    0.07       0
  5000.3    0.16       0  5267.8     0.1       0
Bank Sta=4994.3,5000.3
Exp/Cntr=0.3,0.1

Type RM Length L Ch R = 1,8781,36,36,36
BEGIN DESCRIPTION:
UNT 026 in HW 13.0
END DESCRIPTION:
XS GIS Cut Line= 6
      1976119.91     13663549.66      1976120.77     13663131.28
      1976202.37     13663025.37      1976252.72     13662942.04
      1976257.93     13662791.00      1976094.72     13662475.00
#Sta/Elev= 30
  4250.0  910.59  4444.7  906.43  4584.7  901.17  4594.7  901.87  4611.7  900.25
  4612.2  899.45  4617.7  900.25  4654.7  902.78  4664.0  904.39  4712.1  904.93
  4718.4  903.69  4726.6  905.08  4732.9  904.18  4739.4  905.92  4747.1  905.24
  4818.4  904.56  4833.9  905.54  4839.8  903.35  4855.3  904.42  4861.1  902.23
  4870.8  903.80  4876.6  902.21  4884.3  904.76  4906.5  905.95  4981.2  901.94
  5036.6  905.47  5115.4  906.00  5176.2  911.29  5268.4  916.29  5406.3  925.35
#Mann=5,-1,0
  4250.0     0.1       0  4611.7    0.07       0  4617.7     0.1       0
  4747.1    0.16       0  5268.4     0.1       0
Bank Sta=4611.7,4617.7
Exp/Cntr=0.3,0.1

Type RM Length L Ch R = 1,8745,229,229,229
BEGIN DESCRIPTION:
Mapping XS 35fc4fc5
END DESCRIPTION:
XS GIS Cut Line= 6
      1976155.50     13663532.28      1976160.71     13663152.11
      1976290.91     13662946.38      1976293.52     13662837.01
      1976275.29     13662732.84      1976142.46     13662493.23
#Sta/Elev= 30
  4262.7  910.14  4460.0  905.38  4540.0  902.45  4560.0  901.50  4570.0  900.38
  4588.2  901.08  4731.5  898.49  4760.0  898.85  4773.0  897.83  4787.4  897.68
  4803.2  898.27  4824.7  897.51  4862.1  897.79  4867.9  897.31  4883.7  897.95
  4885.8  897.30  4889.9  897.30  4938.1  898.52  4991.6  896.55  4992.1  895.75
  4997.1  895.75  4997.6  896.55  5014.9  897.20  5020.0  899.28  5038.7  901.04
  5069.2  902.70  5079.5  904.43  5101.8  905.41  5267.5  915.64  5375.8  921.41
#Mann=5,-1,0
  4262.7     0.1       0  4731.5    0.16       0  4991.6    0.07       0
  4997.6    0.16       0  5267.5     0.1       0
Bank Sta=4991.6,4997.6
Exp/Cntr=0.3,0.1

Type RM Length L Ch R = 1,8516,914,914,914
BEGIN DESCRIPTION:
Mapping XS 2abb8f59
END DESCRIPTION:
XS GIS Cut Line= 4
      1976486.87     13663581.34      1976426.11     13663158.19
      1976521.60     13662804.45      1976279.25     13662384.67
#Sta/Elev= 30
  4288.0  906.96  4385.3  907.60  4479.2  906.20  4620.3  902.26  4678.3  895.95
  4760.2  895.21  4772.3  894.11  4926.7  894.95  4956.2  894.13  4998.3  891.05
  4998.8  890.25  5003.8  890.25  5004.3  891.05  5029.5  894.30  5036.0  896.09
  5050.2  897.30  5075.9  898.74  5164.5  900.13  5327.3  904.70  5407.7  910.70
  5450.8  915.51  5472.5  916.05  5482.4  915.87  5488.1  917.69  5503.9  917.00
  5509.7  918.63  5541.2  919.78  5547.0  921.07  5562.8  921.45  5566.6  922.43
#Mann=5,-1,0
  4288.0     0.1       0  4998.3    0.07       0  5004.3     0.1       0
  5164.5    0.16       0  5472.5     0.1       0
Bank Sta=4998.3,5004.3
Exp/Cntr=0.3,0.1

Type RM Length L Ch R = 1,7602,375,375,375
BEGIN DESCRIPTION:
UNT 026 in HW 12.0
END DESCRIPTION:
XS GIS Cut Line= 3
      1977631.28     13663748.64      1977131.25     13663248.61
      1976429.05     13662457.04
#Sta/Elev= 30
  4081.2  916.75  4108.6  915.72  4151.9  913.03  4187.2  912.92  4194.3  911.63
  4208.4  913.34  4219.3  913.09  4229.6  910.15  4243.8  910.83  4272.1  906.99
  4307.4  906.41  4346.9  904.10  4427.6  901.62  4653.9  897.78  4767.0  892.33
  4837.7  892.14  4880.4  890.53  4923.0  887.25  4929.7  885.71  4972.4  886.69
  4990.3  885.00  4990.8  884.20  4996.5  884.20  4997.0  885.00  5021.7  888.42
  5050.1  890.46  5362.1  894.69  5659.8  901.47  5794.5  905.83  5846.5  909.64
#Mann=6,-1,0
  4081.2    0.16       0  4108.6     0.1       0  4219.3    0.05       0
  4346.9     0.1       0  4990.3    0.07       0  4997.0     0.1       0
Bank Sta=4990.3,4997
Exp/Cntr=0.3,0.1

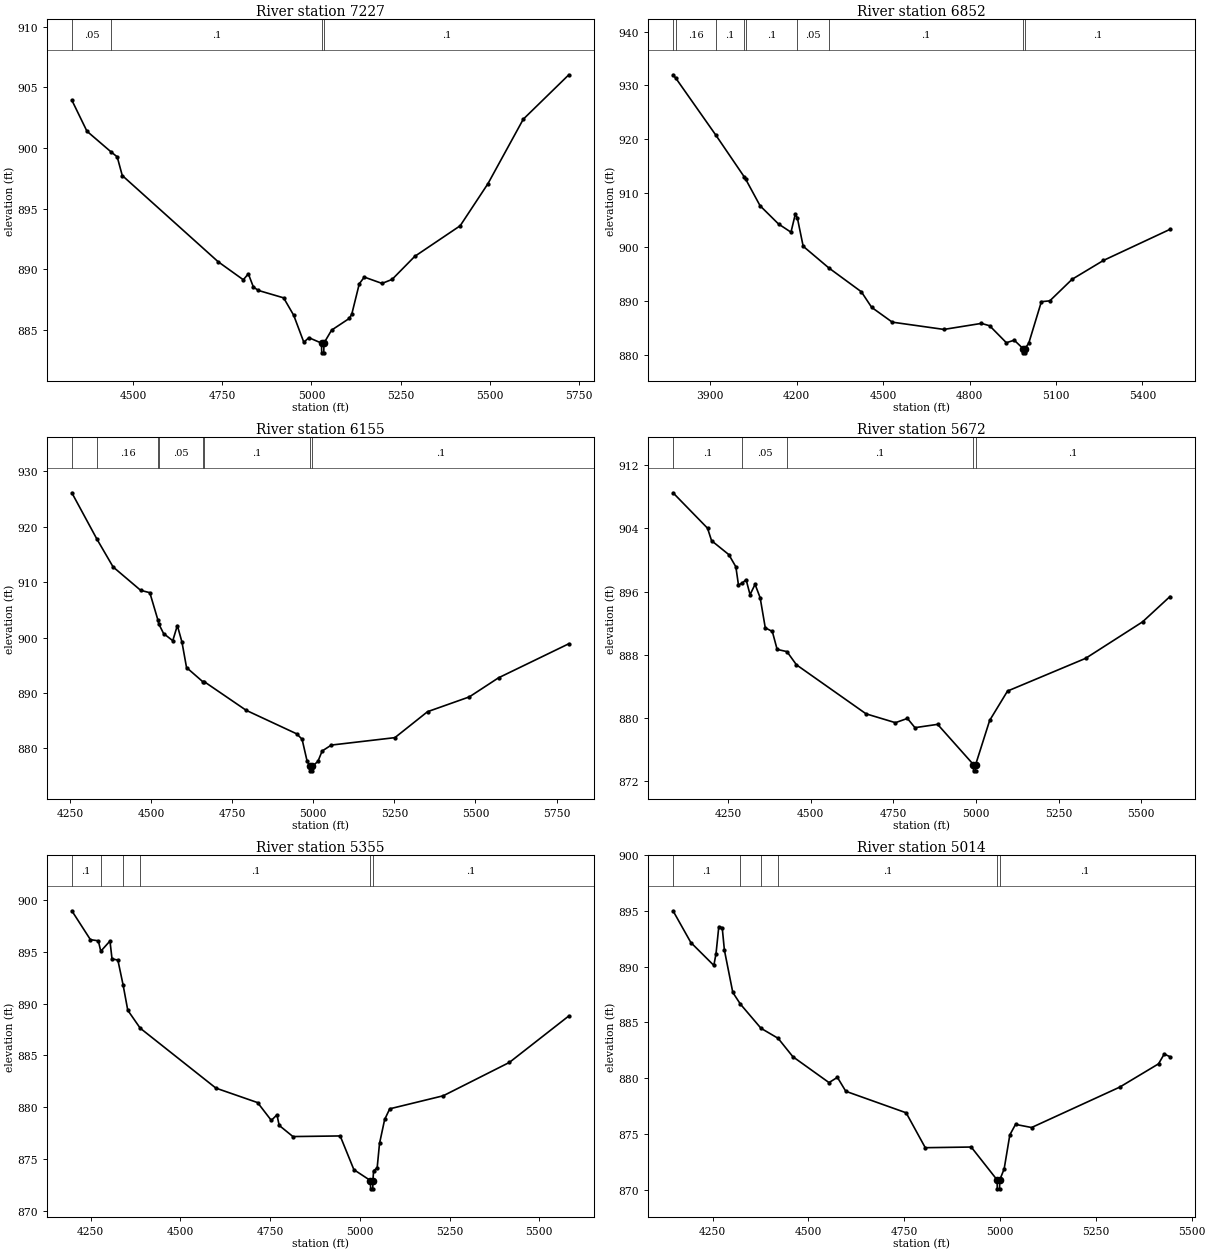
Type RM Length L Ch R = 1,7227,375,375,375
BEGIN DESCRIPTION:
UNT 026 in HW 11.0
END DESCRIPTION:
XS GIS Cut Line= 3
      1977724.97     13663324.97      1977225.00     13662825.00
      1976744.90     13662334.39
#Sta/Elev= 30
  4328.1  903.94  4370.5  901.38  4439.1  899.65  4455.3  899.27  4469.5  897.73
  4738.2  890.63  4808.9  889.14  4823.0  889.63  4837.2  888.54  4851.3  888.26
  4922.0  887.65  4950.3  886.21  4978.6  883.99  4992.7  884.37  5028.2  883.92
  5028.7  883.12  5034.5  883.12  5035.0  883.92  5056.4  884.99  5105.8  885.95
  5113.0  886.30  5134.1  888.81  5148.2  889.36  5197.8  888.84  5226.1  889.17
  5289.7  891.07  5417.0  893.59  5494.9  897.06  5593.9  902.37  5721.6  906.03
#Mann=4,-1,0
  4328.1    0.05       0  4439.1     0.1       0  5028.2    0.07       0
  5035.0     0.1       0
Bank Sta=5028.2,5035
Exp/Cntr=0.3,0.1

Type RM Length L Ch R = 1,6852,697,697,697
BEGIN DESCRIPTION:
UNT 026 in HW 10.0
END DESCRIPTION:
XS GIS Cut Line= 3
      1978324.99     13663224.99      1977325.00     13662525.00
      1976919.25     13662226.43
#Sta/Elev= 30
  3771.2  931.98  3781.0  931.34  3920.3  920.73  4017.8  913.06  4023.7  912.55
  4073.3  907.65  4137.4  904.26  4180.5  902.74  4195.4  906.07  4202.5  905.43
  4222.8  900.13  4312.1  896.09  4424.7  891.67  4460.4  888.78  4531.9  886.03
  4711.1  884.68  4841.4  885.80  4869.8  885.36  4927.8  882.21  4955.2  882.68
  4985.4  881.13  4985.9  880.33  4991.7  880.33  4992.2  881.13  5005.4  882.10
  5049.3  889.83  5078.6  889.99  5155.8  893.99  5264.5  897.49  5495.6  903.27
#Mann=9,-1,0
  3771.2     0.1       0  3781.0    0.16       0  3920.3     0.1       0
  4017.8    0.16       0  4023.7     0.1       0  4202.5    0.05       0
  4312.1     0.1       0  4985.4    0.07       0  4992.2     0.1       0
Bank Sta=4985.4,4992.2
Exp/Cntr=0.3,0.1

Type RM Length L Ch R = 1,6155,483,483,483
BEGIN DESCRIPTION:
UNT 026 in HW 9.0
END DESCRIPTION:
XS GIS Cut Line= 3
      1978424.97     13662874.97      1977925.00     13662375.00
      1977124.99     13662175.00
#Sta/Elev= 30
  4256.1  926.13  4333.6  917.75  4383.3  912.75  4468.2  908.53  4496.5  908.10
  4521.5  903.15  4524.3  902.45  4538.9  900.73  4567.2  899.44  4581.3  902.18
  4595.5  899.20  4609.6  894.60  4659.2  892.07  4664.1  892.05  4793.5  886.88
  4949.0  882.64  4965.7  881.67  4981.2  877.71  4990.7  876.76  4991.2  875.96
  4997.0  875.96  4997.5  876.76  5014.7  877.69  5027.6  879.54  5055.9  880.61
  5251.8  881.95  5352.3  886.63  5481.1  889.30  5571.3  892.75  5787.8  898.89
#Mann=8,-1,0
  4256.1     0.1       0  4333.6    0.16       0  4521.5     0.1       0
  4524.3    0.05       0  4659.2    0.08       0  4664.1     0.1       0
  4990.7    0.07       0  4997.5     0.1       0
Bank Sta=4990.7,4997.5
Exp/Cntr=0.3,0.1

Type RM Length L Ch R = 1,5672,317,317,317
BEGIN DESCRIPTION:
UNT 026 in HW 8.0
END DESCRIPTION:
XS GIS Cut Line= 3
      1978624.27     13662377.82      1978103.41     13662060.97
      1977222.32     13661904.71
#Sta/Elev= 30
  4083.0  908.51  4187.5  904.03  4199.7  902.45  4251.9  900.69  4273.2  899.15
  4281.1  896.86  4292.5  897.08  4304.2  897.53  4316.2  895.62  4331.4  896.93
  4346.8  895.23  4362.3  891.43  4383.6  890.97  4398.2  888.70  4427.9  888.42
  4456.7  886.75  4667.4  880.55  4756.3  879.43  4792.6  879.97  4815.4  878.80
  4884.0  879.22  4992.3  874.14  4992.8  873.34  4998.7  873.34  4999.2  874.14
  5041.6  879.72  5095.6  883.43  5332.1  887.57  5504.3  892.18  5587.5  895.39
#Mann=5,-1,0
  4083.0     0.1       0  4292.5    0.05       0  4427.9     0.1       0
  4992.3    0.07       0  4999.2     0.1       0
Bank Sta=4992.3,4999.2
Exp/Cntr=0.3,0.1

Type RM Length L Ch R = 1,5355,341,341,341
BEGIN DESCRIPTION:
UNT 026 in HW 7.0
END DESCRIPTION:
XS GIS Cut Line= 3
      1978619.14     13662172.59      1977875.00     13661775.00
      1977466.87     13661419.56
#Sta/Elev= 30
  4197.2  898.96  4249.0  896.17  4271.0  896.06  4277.9  895.05  4303.5  896.04
  4309.2  894.31  4325.5  894.20  4340.1  891.79  4353.1  889.35  4387.7  887.62
  4598.7  881.83  4714.9  880.43  4753.1  878.71  4768.8  879.25  4775.0  878.23
  4813.3  877.15  4945.0  877.21  4983.2  873.95  5029.3  872.90  5029.8  872.10
  5035.7  872.10  5036.2  872.90  5038.1  873.85  5048.0  874.12  5054.6  876.48
  5068.9  878.80  5083.1  879.83  5232.2  881.09  5416.4  884.31  5582.1  888.80
#Mann=6,-1,0
  4197.2     0.1       0  4277.9    0.05       0  4340.1    0.08       0
  4387.7     0.1       0  5029.3    0.07       0  5036.2     0.1       0
Bank Sta=5029.3,5036.2
Exp/Cntr=0.3,0.1

Type RM Length L Ch R = 1,5014,375,375,375
BEGIN DESCRIPTION:
UNT 026 in HW 6.0
END DESCRIPTION:
XS GIS Cut Line= 3
      1978810.14     13661922.60      1978075.00     13661525.00
      1977695.51     13661262.85
#Sta/Elev= 30
  4146.5  895.02  4193.1  892.17  4253.0  890.12  4258.7  891.16  4266.0  893.60
  4274.9  893.50  4280.6  891.49  4302.5  887.70  4322.1  886.66  4376.1  884.48
  4420.8  883.58  4459.3  881.93  4553.6  879.61  4575.5  880.08  4597.4  878.83
  4754.9  876.90  4804.8  873.77  4924.7  873.83  4992.3  870.88  4992.8  870.08
  4998.7  870.08  4999.2  870.88  5010.7  871.87  5025.5  874.92  5040.4  875.86
  5082.3  875.58  5312.1  879.20  5413.5  881.29  5428.4  882.17  5443.5  881.93
#Mann=6,-1,0
  4146.5     0.1       0  4322.1    0.08       0  4376.1    0.05       0
  4420.8     0.1       0  4992.3    0.07       0  4999.2     0.1       0
Bank Sta=4992.3,4999.2
Exp/Cntr=0.3,0.1

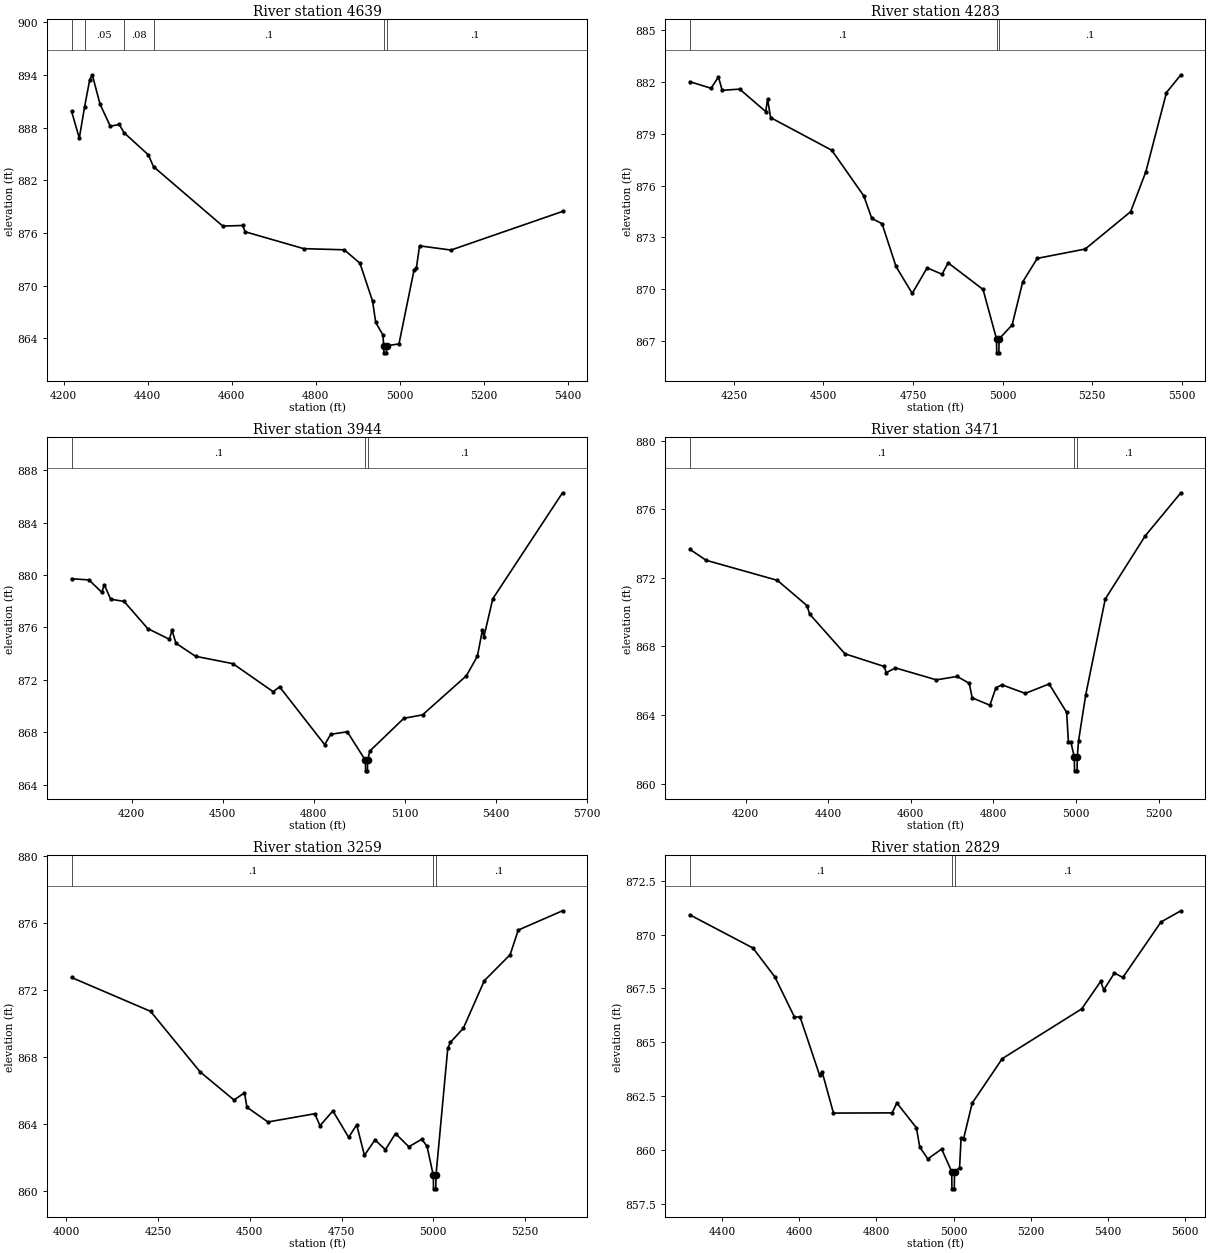
Type RM Length L Ch R = 1,4639,356,356,356
BEGIN DESCRIPTION:
UNT 026 in HW 5.0
END DESCRIPTION:
XS GIS Cut Line= 3
      1978981.16     13661495.09      1978275.00     13661225.00
      1977874.97     13661124.99
#Sta/Elev= 30
  4219.0  889.86  4237.5  886.79  4250.1  890.36  4262.2  893.42  4268.4  894.01
  4286.9  890.65  4311.3  888.15  4332.7  888.35  4343.6  887.43  4401.7  884.89
  4414.1  883.54  4578.9  876.77  4626.1  876.84  4632.4  876.12  4771.6  874.20
  4868.0  874.07  4905.3  872.54  4935.3  868.24  4942.9  865.79  4960.0  864.37
  4961.9  863.13  4962.4  862.33  4968.4  862.33  4968.9  863.13  4998.2  863.35
  5034.3  871.82  5039.5  871.94  5047.2  874.52  5121.9  874.04  5387.4  878.44
#Mann=6,-1,0
  4219.0     0.1       0  4250.1    0.05       0  4343.6    0.08       0
  4414.1     0.1       0  4961.9    0.07       0  4968.9     0.1       0
Bank Sta=4961.9,4968.9
Exp/Cntr=0.3,0.1

Type RM Length L Ch R = 1,4283,339,339,339
BEGIN DESCRIPTION:
UNT 026 in HW 4.0
END DESCRIPTION:
XS GIS Cut Line= 3
      1979141.68     13661108.78      1978325.00     13660875.00
      1977804.90     13660844.04
#Sta/Elev= 30
  4127.2  882.02  4186.2  881.64  4207.0  882.29  4217.4  881.52  4266.1  881.59
  4338.9  880.29  4344.1  881.01  4352.6  879.94  4523.3  878.05  4612.6  875.41
  4635.1  874.10  4663.6  873.80  4702.6  871.32  4747.8  869.76  4789.5  871.24
  4831.1  870.87  4848.1  871.53  4945.5  869.99  4983.2  867.12  4983.7  866.32
  4989.7  866.32  4990.2  867.12  5026.8  867.94  5056.3  870.43  5096.9  871.79
  5230.6  872.33  5357.4  874.49  5399.9  876.80  5457.5  881.39  5497.7  882.42
#Mann=3,-1,0
  4127.2     0.1       0  4983.2    0.07       0  4990.2     0.1       0
Bank Sta=4983.2,4990.2
Exp/Cntr=0.3,0.1

Type RM Length L Ch R = 1,3944,473,473,473
BEGIN DESCRIPTION:
Mapping XS a0963226
END DESCRIPTION:
XS GIS Cut Line= 4
      1979206.87     13660982.95      1978846.58     13660731.19
      1978143.46     13660479.45      1977719.02     13660557.41
#Sta/Elev= 30
  4002.0  879.72  4059.4  879.63  4101.9  878.68  4109.9  879.27  4130.9  878.16
  4175.1  877.99  4253.0  875.92  4324.5  875.10  4333.2  875.79  4345.9  874.80
  4410.8  873.80  4533.8  873.24  4666.3  871.10  4687.6  871.47  4836.2  867.06
  4856.3  867.85  4910.6  868.04  4970.5  865.86  4971.0  865.06  4977.1  865.06
  4977.6  865.86  4984.9  866.57  5097.1  869.07  5158.6  869.33  5302.9  872.31
  5339.3  873.80  5356.0  875.81  5361.1  875.31  5390.1  878.19  5619.9  886.28
#Mann=3,-1,0
  4002.0     0.1       0  4970.5    0.07       0  4977.6     0.1       0
Bank Sta=4970.5,4977.6
Exp/Cntr=0.3,0.1

Type RM Length L Ch R = 1,3471,212,212,212
BEGIN DESCRIPTION:
UNT 026 in HW 3.0
END DESCRIPTION:
XS GIS Cut Line= 3
      1979115.66     13660670.41      1978375.00     13660125.00
      1978124.97     13660024.99
#Sta/Elev= 30
  4064.9  873.67  4104.2  873.03  4276.8  871.86  4348.7  870.38  4354.9  869.89
  4440.5  867.57  4534.6  866.84  4540.8  866.47  4562.5  866.75  4661.9  866.05
  4712.1  866.25  4741.4  865.85  4748.7  865.00  4791.5  864.57  4806.1  865.59
  4820.8  865.76  4877.1  865.26  4935.0  865.81  4977.4  864.15  4981.6  862.44
  4987.4  862.44  4995.9  861.54  4996.5  860.74  5002.6  860.74  5003.1  861.54
  5006.2  862.49  5023.7  865.19  5070.9  870.77  5167.8  874.46  5254.0  876.97
#Mann=3,-1,0
  4064.9     0.1       0  4995.9    0.07       0  5003.1     0.1       0
Bank Sta=4995.9,5003.1
Exp/Cntr=0.3,0.1

Type RM Length L Ch R = 1,3259,430,430,430
BEGIN DESCRIPTION:
Mapping XS 349cfa1f
END DESCRIPTION:
XS GIS Cut Line= 2
      1979219.84     13660583.61      1978195.58     13659724.28
#Sta/Elev= 30
  4014.7  872.75  4229.9  870.73  4364.8  867.12  4457.1  865.44  4485.7  865.87
  4492.3  865.01  4549.5  864.13  4677.0  864.62  4691.3  863.91  4726.4  864.79
  4769.4  863.21  4791.2  863.96  4812.3  862.14  4840.9  863.06  4869.5  862.48
  4896.9  863.44  4933.2  862.65  4968.4  863.10  4982.7  862.68  4999.9  860.94
  5000.4  860.14  5006.6  860.14  5007.1  860.94  5039.2  868.52  5046.4  868.88
  5081.6  869.72  5138.8  872.56  5209.1  874.11  5231.2  875.58  5351.7  876.73
#Mann=3,-1,0
  4014.7     0.1       0  4999.9    0.07       0  5007.1     0.1       0
Bank Sta=4999.9,5007.1
Exp/Cntr=0.3,0.1

Type RM Length L Ch R = 1,2829,330,330,330
BEGIN DESCRIPTION:
UNT 026 in HW 2.0
END DESCRIPTION:
XS GIS Cut Line= 3
      1979232.85     13660444.71      1978833.56     13659871.82
      1978464.61     13659433.41
#Sta/Elev= 30
  4317.2  870.92  4480.5  869.38  4537.2  868.04  4587.8  866.18  4602.6  866.17
  4653.3  863.46  4659.4  863.64  4689.0  861.71  4840.9  861.72  4853.2  862.18
  4903.7  861.03  4912.4  860.13  4933.3  859.58  4969.1  860.04  4995.1  858.99
  4995.7  858.19  5001.9  858.19  5002.4  858.99  5015.5  859.17  5019.5  860.56
  5026.0  860.52  5048.1  862.17  5126.1  864.24  5331.6  866.55  5381.0  867.83
  5388.8  867.43  5416.5  868.22  5438.2  868.01  5537.1  870.59  5588.5  871.11
#Mann=3,-1,0
  4317.2     0.1       0  4995.1    0.07       0  5002.4     0.1       0
Bank Sta=4995.1,5002.4
Exp/Cntr=0.3,0.1

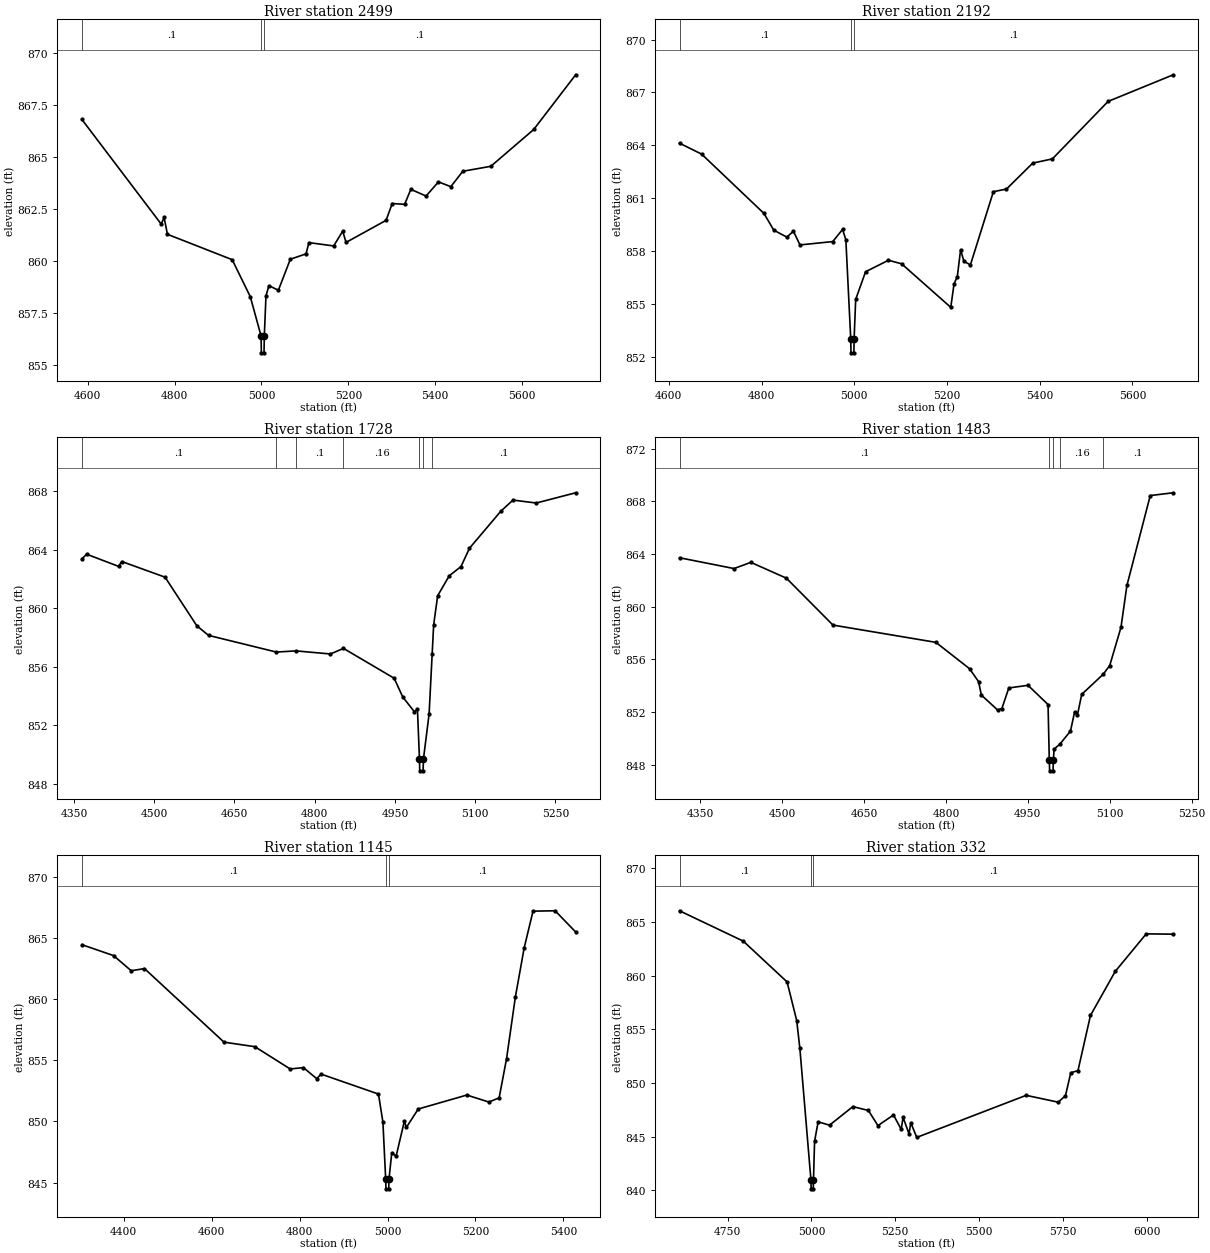
Type RM Length L Ch R = 1,2499,307,307,307
BEGIN DESCRIPTION:
Mapping XS 00f2a9a9
END DESCRIPTION:
XS GIS Cut Line= 2
      1979410.80     13660136.55      1978665.48     13659278.57
#Sta/Elev= 30
  4586.7  866.82  4769.2  861.79  4775.9  862.11  4783.5  861.30  4932.6  860.08
  4974.3  858.30  4999.2  856.40  4999.7  855.60  5005.9  855.60  5006.5  856.40
  5010.4  858.34  5017.1  858.83  5038.9  858.61  5066.4  860.10  5102.6  860.36
  5109.2  860.90  5166.2  860.74  5187.0  861.45  5194.7  860.91  5286.8  861.97
  5301.0  862.78  5329.5  862.74  5343.8  863.46  5378.9  863.14  5407.4  863.82
  5435.9  863.59  5463.4  864.33  5528.0  864.57  5626.7  866.34  5723.2  868.97
#Mann=3,-1,0
  4586.7     0.1       0  4999.2    0.07       0  5006.5     0.1       0
Bank Sta=4999.2,5006.5
Exp/Cntr=0.3,0.1

Type RM Length L Ch R = 1,2192,464,464,464
BEGIN DESCRIPTION:
Mapping XS c2e57fb2
END DESCRIPTION:
XS GIS Cut Line= 2
      1979636.54     13659910.90      1978885.64     13659155.67
#Sta/Elev= 30
  4623.1  864.12  4670.8  863.50  4805.1  860.14  4826.4  859.19  4854.6  858.79
  4868.8  859.13  4882.9  858.35  4953.6  858.54  4974.8  859.23  4981.9  858.64
  4992.4  853.03  4993.0  852.23  4999.2  852.23  4999.7  853.03  5003.1  855.26
  5024.4  856.83  5073.8  857.48  5102.1  857.28  5208.2  854.81  5215.3  856.15
  5222.3  856.55  5229.4  858.08  5236.5  857.42  5250.6  857.22  5300.1  861.37
  5328.4  861.52  5385.0  862.99  5427.4  863.23  5547.6  866.49  5688.1  868.00
#Mann=3,-1,0
  4623.1     0.1       0  4992.4    0.07       0  4999.7     0.1       0
Bank Sta=4992.4,4999.7
Exp/Cntr=0.3,0.1

Type RM Length L Ch R = 1,1728,245,245,245
BEGIN DESCRIPTION:
Mapping XS a3103fab
END DESCRIPTION:
XS GIS Cut Line= 2
      1979692.95     13659850.14      1979245.91     13659042.85
#Sta/Elev= 30
  4364.9  863.36  4373.7  863.68  4433.3  862.85  4439.4  863.18  4520.3  862.11
  4579.8  858.78  4601.6  858.13  4728.4  856.99  4765.0  857.07  4829.4  856.86
  4853.8  857.24  4948.5  855.20  4964.5  853.92  4986.3  852.91  4992.0  853.08
  4995.8  849.67  4996.3  848.87  5002.6  848.87  5003.2  849.67  5013.8  852.76
  5019.5  856.84  5022.3  858.85  5029.8  860.84  5051.5  862.21  5073.3  862.83
  5089.3  864.09  5148.1  866.63  5170.6  867.38  5214.1  867.18  5287.7  867.88
#Mann=7,-1,0
  4364.9     0.1       0  4728.4    0.16       0  4765.0     0.1       0
  4853.8    0.16       0  4995.8    0.07       0  5003.2    0.16       0
  5019.5     0.1       0
Bank Sta=4995.8,5003.2
Exp/Cntr=0.3,0.1

Type RM Length L Ch R = 1,1483,338,338,338
BEGIN DESCRIPTION:
Mapping XS 563f7e8a
END DESCRIPTION:
XS GIS Cut Line= 2
      1979753.71     13659902.24      1979549.85     13659021.73
#Sta/Elev= 30
  4312.4  863.72  4412.2  862.90  4443.0  863.37  4508.0  862.17  4593.3  858.61
  4781.7  857.30  4843.3  855.30  4859.8  854.32  4864.9  853.30  4894.6  852.17
  4902.5  852.28  4915.2  853.84  4950.3  854.04  4987.0  852.58  4989.3  848.35
  4989.9  847.55  4996.2  847.55  4996.7  848.35  4998.1  849.20  5009.0  849.59
  5028.1  850.57  5035.7  852.04  5040.8  851.78  5048.6  853.35  5088.0  854.88
  5099.9  855.54  5120.5  858.44  5131.4  861.62  5174.1  868.44  5216.2  868.65
#Mann=5,-1,0
  4312.4     0.1       0  4989.3    0.07       0  4996.7     0.1       0
  5009.0    0.16       0  5088.0     0.1       0
Bank Sta=4989.3,4996.7
Exp/Cntr=0.3,0.1

Type RM Length L Ch R = 1,1145,813,813,813
BEGIN DESCRIPTION:
Mapping XS a057914a
END DESCRIPTION:
XS GIS Cut Line= 2
      1979840.07     13659956.70      1979946.69     13658838.47
#Sta/Elev= 30
  4304.7  864.44  4376.7  863.55  4416.9  862.31  4447.0  862.49  4627.9  856.48
  4698.2  856.11  4778.5  854.29  4808.7  854.40  4838.8  853.50  4848.9  853.87
  4979.4  852.24  4989.5  849.95  4995.8  845.30  4996.4  844.50  5002.7  844.50
  5003.3  845.30  5009.6  847.42  5019.6  847.17  5038.1  850.00  5043.1  849.53
  5069.9  851.02  5180.4  852.16  5230.6  851.59  5253.9  851.93  5270.8  855.13
  5290.9  860.18  5310.9  864.18  5331.0  867.18  5381.3  867.21  5428.0  865.48
#Mann=3,-1,0
  4304.7     0.1       0  4995.8    0.07       0  5003.3     0.1       0
Bank Sta=4995.8,5003.3
Exp/Cntr=0.3,0.1

Type RM Length L Ch R = 1,332,0,0,0
BEGIN DESCRIPTION:
UNT 026 in HW 1.0
END DESCRIPTION:
XS GIS Cut Line= 4
      1979840.04     13659990.54      1980105.70     13659829.06
      1980350.49     13659284.79      1980066.63     13658795.20
#Sta/Elev= 30
  4606.2  866.05  4796.6  863.22  4927.3  859.42  4955.9  855.83  4965.4  853.23
  4998.5  840.95  4999.1  840.15  5005.4  840.15  5006.0  840.95  5009.3  844.59
  5019.9  846.39  5054.0  846.08  5123.5  847.81  5169.8  847.45  5198.4  846.04
  5244.8  847.03  5267.9  845.69  5273.4  846.81  5291.1  845.28  5296.5  846.31
  5314.2  844.94  5640.8  848.86  5736.6  848.22  5758.1  848.83  5773.9  850.96
  5795.4  851.16  5832.7  856.30  5906.6  860.40  5999.1  863.90  6079.8  863.87
#Mann=3,-1,0
  4606.2     0.1       0  4998.5    0.07       0  5006.0     0.1       0
Bank Sta=4998.5,5006
Exp/Cntr=0.3,0.1

Chan Stop Cuts=-1