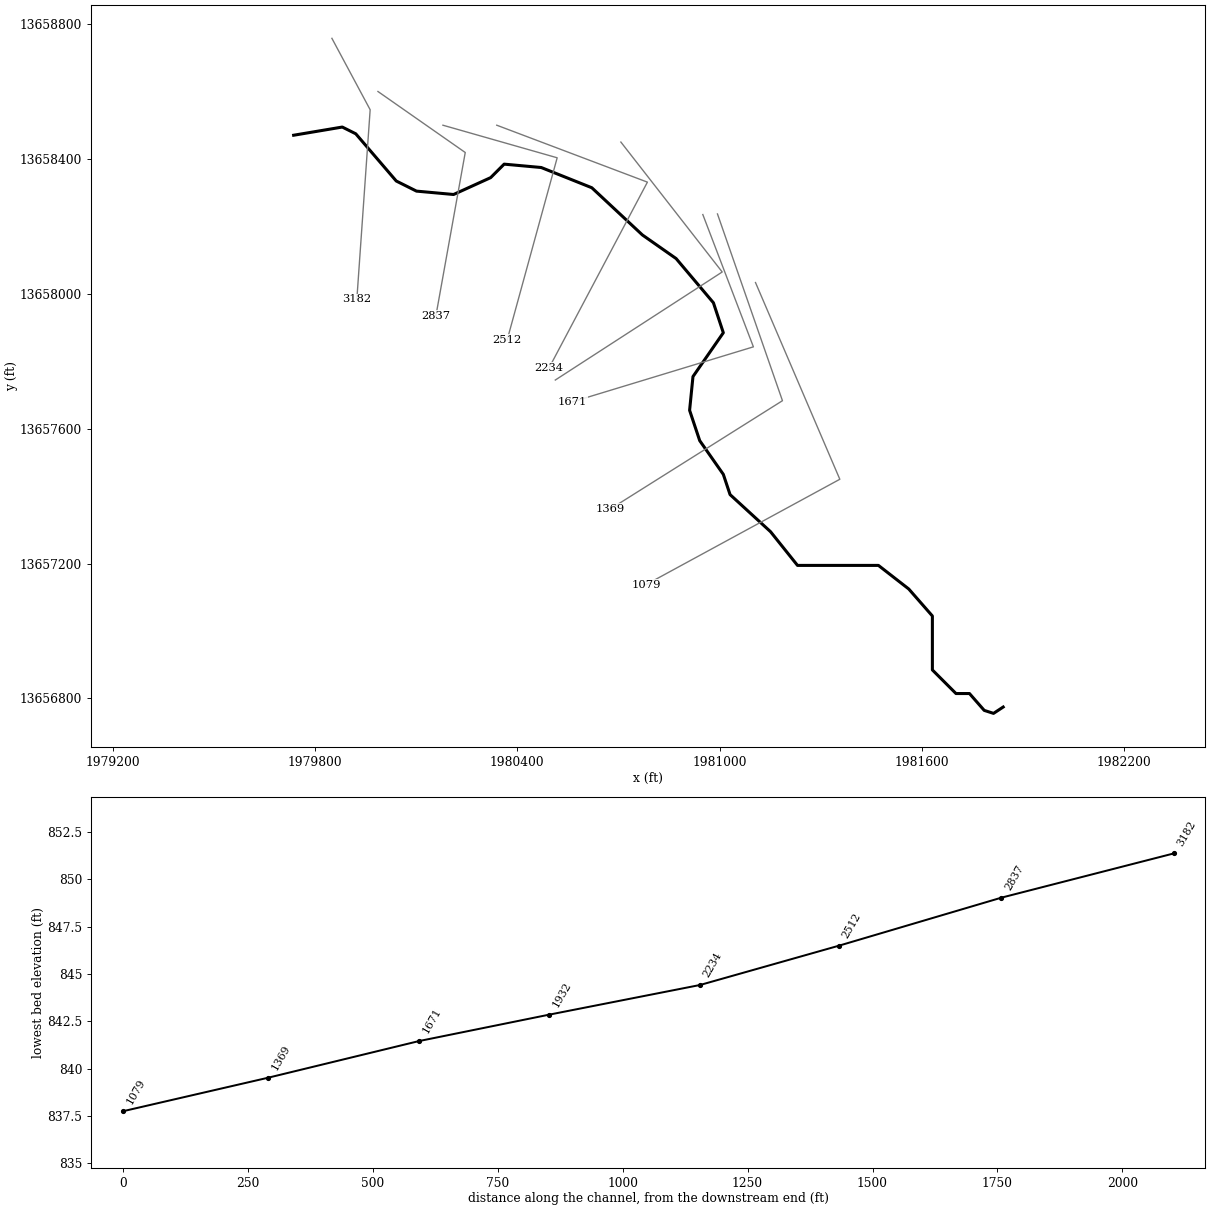
--- UNT 027 in HW.prj (project) ---

Proj Title=UNT 027 in HW Base Level Engineering
Current Plan=p01
Default Exp/Contr=0.3,0.1
English Units
Geom File=g01
Flow File=f01
Plan File=p01
BEGIN DESCRIPTION:
UNT 027 in HW
END DESCRIPTION:

--- UNT 027 in HW.p01 (plan) ---

Plan Title=Multiple Run
Short Identifier=Multiple
Geom File=g01
Flow File=f01
Subcritical Flow
K Sum by GR= 0
Std Step Tol= 0.01
Critical Tol= 0.01
Num of Std Step Trials= 20
Max Error Tol= 0.3
Flow Tol Ratio= 0.001
Split Flow NTrial= 30
Split Flow Tol= 0.02
Split Flow Ratio= 0.02
Log Output Level= 0
Friction Slope Method= 1
Unsteady Friction Slope Method= 2
Unsteady Bridges Friction Slope Method= 1
Parabolic Critical Depth
Global Vel Dist=  1 , 1 , 1
Global Log Level= 0
CheckData=True
Encroach Param= -1, 0, 0, 0
BEGIN DESCRIPTION:
Multiple Run
END DESCRIPTION:

--- UNT 027 in HW.f01 (steady flow) ---

Flow Title=Multiple
Number of Profiles=7
Profile Names=10-year,25-year,50-year,1pct_min,100-year,1pct_plu,500-year
River Rch & RM= UNT 027 in HW,Reach-1,3182
     575     804     994     609    1215    2424    1820
Boundary for River Rch & Prof#=UNT 027 in HW,Reach-1,1
Up Type=0
Dn Type=3
Dn Slope=0.005
Boundary for River Rch & Prof#=UNT 027 in HW,Reach-1,2
Up Type=0
Dn Type=3
Dn Slope=0.005
Boundary for River Rch & Prof#=UNT 027 in HW,Reach-1,3
Up Type=0
Dn Type=3
Dn Slope=0.005
Boundary for River Rch & Prof#=UNT 027 in HW,Reach-1,4
Up Type=0
Dn Type=3
Dn Slope=0.005
Boundary for River Rch & Prof#=UNT 027 in HW,Reach-1,5
Up Type=0
Dn Type=3
Dn Slope=0.005
Boundary for River Rch & Prof#=UNT 027 in HW,Reach-1,6
Up Type=0
Dn Type=3
Dn Slope=0.005
Boundary for River Rch & Prof#=UNT 027 in HW,Reach-1,7
Up Type=0
Dn Type=3
Dn Slope=0.005

--- UNT 027 in HW.g01 (geometry) ---

Geom Title=Existing Conditions

River Reach=UNT 027 in HW,Reach-1
Reach XY= 30
      1979736.52     13658470.26      1979880.80     13658494.54
      1979920.80     13658474.54      1980040.80     13658334.54
      1980100.80     13658304.54      1980210.80     13658294.54
      1980320.80     13658344.54      1980360.80     13658384.54
      1980470.80     13658374.54      1980620.80     13658314.54
      1980770.80     13658174.54      1980870.80     13658104.54
      1980981.43     13657973.42      1981010.80     13657884.54
      1980920.80     13657754.54      1980910.80     13657654.54
      1980940.80     13657564.54      1981010.80     13657464.54
      1981030.80     13657404.54      1981150.80     13657294.54
      1981230.80     13657194.54      1981470.80     13657194.54
      1981560.80     13657124.54      1981630.80     13657044.54
      1981630.80     13656884.54      1981700.80     13656814.54
      1981740.80     13656814.54      1981784.56     13656764.56
      1981812.16     13656755.71      1981840.80     13656774.54

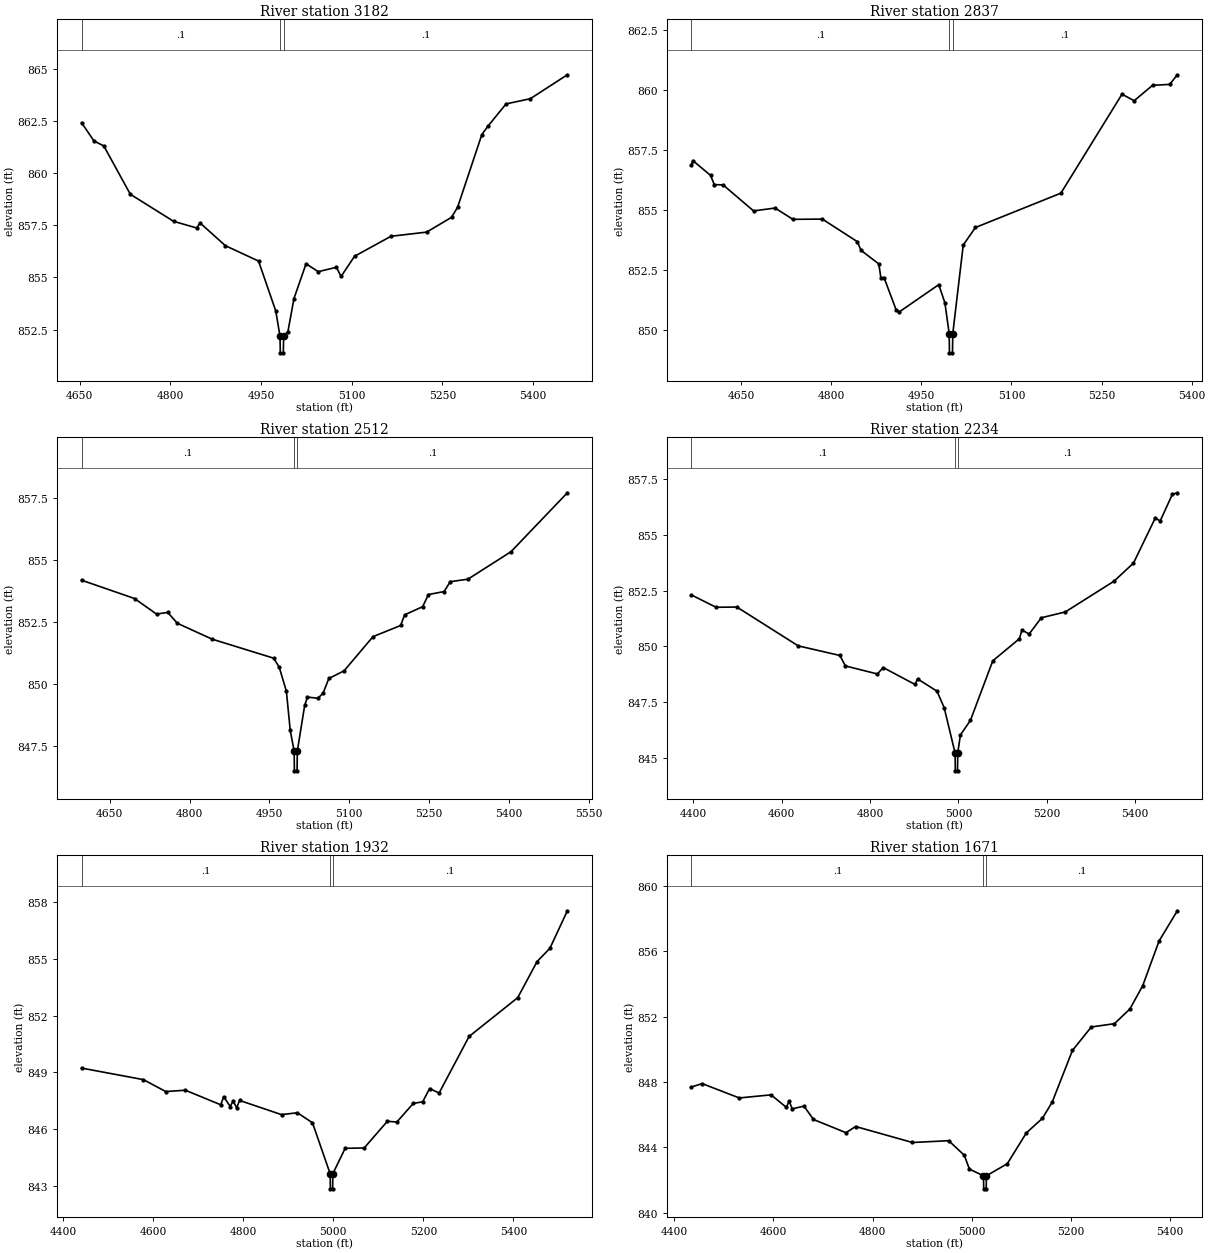
Type RM Length L Ch R = 1,3182,345,345,345
BEGIN DESCRIPTION:
UNT 027 in HW 1.0
END DESCRIPTION:
XS GIS Cut Line= 3
      1979850.00     13658757.64      1979963.44     13658545.87
      1979923.96     13657983.90
#Sta/Elev= 30
  4653.0  862.44  4673.6  861.56  4689.9  861.32  4733.7  859.00  4805.2  857.70
  4843.4  857.38  4849.1  857.62  4890.9  856.53  4945.8  855.79  4974.3  853.39
  4981.3  852.18  4981.8  851.38  4986.8  851.38  4987.3  852.18  4994.4  852.40
  5004.4  853.99  5024.4  855.66  5044.5  855.28  5074.6  855.49  5082.3  855.05
  5104.6  856.02  5164.8  856.98  5223.8  857.18  5265.0  857.89  5275.1  858.38
  5315.2  861.87  5325.2  862.27  5355.2  863.34  5395.3  863.59  5456.6  864.74
#Mann=3,-1,0
  4653.0     0.1       0  4981.3    0.07       0  4987.3     0.1       0
Bank Sta=4981.3,4987.3
Exp/Cntr=0.3,0.1

Type RM Length L Ch R = 1,2837,325,325,325
BEGIN DESCRIPTION:
UNT 027 in HW 2.0
END DESCRIPTION:
XS GIS Cut Line= 3
      1979986.55     13658599.98      1980245.44     13658419.05
      1980158.33     13657934.37
#Sta/Elev= 30
  4567.8  856.85  4569.9  857.05  4599.5  856.43  4605.6  856.05  4620.5  856.03
  4671.1  854.95  4706.8  855.07  4736.5  854.60  4785.5  854.61  4843.7  853.67
  4849.8  853.31  4879.5  852.74  4882.8  852.17  4888.2  852.17  4908.1  850.84
  4913.8  850.75  4979.2  851.88  4989.4  851.12  4996.5  849.84  4997.0  849.04
  5002.0  849.04  5002.5  849.84  5019.9  853.53  5040.2  854.26  5182.4  855.69
  5284.0  859.81  5304.3  859.54  5334.8  860.18  5363.4  860.22  5376.1  860.62
#Mann=3,-1,0
  4567.8     0.1       0  4996.5    0.07       0  5002.5     0.1       0
Bank Sta=4996.5,5002.5
Exp/Cntr=0.3,0.1

Type RM Length L Ch R = 1,2512,278,278,278
BEGIN DESCRIPTION:
UNT 027 in HW 3.0
END DESCRIPTION:
XS GIS Cut Line= 3
      1980179.24     13658500.00      1980518.08     13658403.39
      1980369.65     13657862.84
#Sta/Elev= 30
  4597.0  854.20  4696.6  853.46  4737.9  852.83  4759.0  852.90  4777.0  852.46
  4842.2  851.82  4958.0  851.05  4968.4  850.69  4981.9  849.72  4989.2  848.13
  4996.5  847.30  4997.0  846.50  5002.0  846.50  5002.5  847.30  5016.3  849.14
  5021.5  849.48  5041.0  849.43  5050.8  849.63  5061.7  850.23  5090.4  850.54
  5144.7  851.92  5196.6  852.37  5204.1  852.80  5238.0  853.13  5248.9  853.62
  5278.2  853.74  5289.9  854.14  5323.0  854.24  5404.0  855.35  5509.9  857.73
#Mann=3,-1,0
  4597.0     0.1       0  4996.5    0.07       0  5002.5     0.1       0
Bank Sta=4996.5,5002.5
Exp/Cntr=0.3,0.1

Type RM Length L Ch R = 1,2234,302,302,302
BEGIN DESCRIPTION:
UNT 027 in HW 4.0
END DESCRIPTION:
XS GIS Cut Line= 3
      1980338.92     13658500.01      1980785.68     13658331.18
      1980494.28     13657780.76
#Sta/Elev= 30
  4395.5  852.30  4451.1  851.75  4498.2  851.76  4637.2  850.02  4731.5  849.59
  4744.1  849.12  4816.7  848.76  4829.6  849.05  4901.8  848.29  4907.5  848.54
  4951.5  847.99  4967.8  847.25  4992.5  845.22  4993.0  844.42  4998.0  844.42
  4998.5  845.22  5004.6  846.03  5027.2  846.68  5077.9  849.35  5138.2  850.34
  5143.9  850.73  5160.2  850.55  5187.9  851.28  5242.2  851.54  5352.6  852.92
  5396.6  853.73  5446.2  855.76  5456.9  855.61  5484.6  856.81  5495.9  856.88
#Mann=3,-1,0
  4395.5     0.1       0  4992.5    0.07       0  4998.5     0.1       0
Bank Sta=4992.5,4998.5
Exp/Cntr=0.3,0.1

Type RM Length L Ch R = 1,1932,261,261,261
BEGIN DESCRIPTION:
UNT 027 in HW 5.0
END DESCRIPTION:
XS GIS Cut Line= 3
      1980706.97     13658450.04      1981007.49     13658064.72
      1980512.50     13657744.29
#Sta/Elev= 30
  4441.3  849.23  4578.6  848.62  4628.3  847.99  4671.7  848.06  4750.4  847.29
  4756.8  847.72  4771.3  847.20  4777.6  847.48  4785.7  847.14  4792.1  847.52
  4885.2  846.77  4920.5  846.87  4953.9  846.34  4993.1  843.65  4993.6  842.85
  4998.6  842.85  4999.1  843.65  5026.4  844.99  5068.7  845.01  5120.1  846.42
  5141.2  846.38  5177.5  847.36  5198.6  847.45  5213.8  848.15  5234.9  847.91
  5301.5  850.90  5409.4  852.95  5452.5  854.86  5480.9  855.56  5519.6  857.54
#Mann=3,-1,0
  4441.3     0.1       0  4993.1    0.07       0  4999.1     0.1       0
Bank Sta=4993.1,4999.1
Exp/Cntr=0.3,0.1

Type RM Length L Ch R = 1,1671,302,302,302
BEGIN DESCRIPTION:
UNT 027 in HW 6.0
END DESCRIPTION:
XS GIS Cut Line= 3
      1980950.02     13658235.03      1981100.00     13657842.71
      1980563.35     13657679.60
#Sta/Elev= 30
  4434.5  847.69  4455.9  847.90  4530.9  847.02  4595.1  847.21  4626.2  846.44
  4631.5  846.83  4637.9  846.35  4661.6  846.52  4680.8  845.70  4746.4  844.89
  4765.8  845.27  4880.6  844.29  4953.8  844.40  4985.2  843.51  4995.6  842.66
  5024.0  842.25  5024.5  841.45  5029.5  841.45  5030.0  842.25  5072.1  842.99
  5110.6  844.88  5143.0  845.77  5162.8  846.77  5203.6  849.93  5241.7  851.37
  5288.3  851.57  5319.6  852.47  5345.5  853.90  5378.4  856.63  5415.4  858.49
#Mann=3,-1,0
  4434.5     0.1       0  5024.0    0.07       0  5030.0     0.1       0
Bank Sta=5024,5030
Exp/Cntr=0.3,0.1

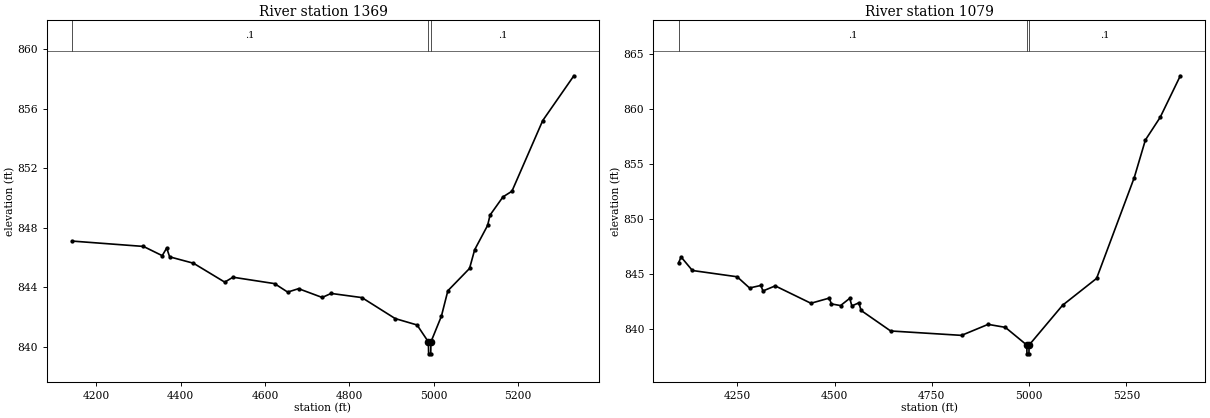
Type RM Length L Ch R = 1,1369,290,290,290
BEGIN DESCRIPTION:
Mapping XS e9516035
END DESCRIPTION:
XS GIS Cut Line= 3
      1980993.45     13658236.83      1981186.17     13657682.99
      1980675.73     13657361.79
#Sta/Elev= 30
  4142.5  847.09  4311.6  846.73  4356.2  846.11  4366.8  846.62  4373.8  846.03
  4430.3  845.60  4504.4  844.33  4523.9  844.66  4622.5  844.23  4653.6  843.66
  4679.4  843.89  4735.4  843.30  4756.6  843.57  4829.6  843.29  4908.5  841.88
  4960.3  841.45  4987.2  840.31  4987.7  839.51  4992.7  839.51  4993.2  840.31
  5018.0  842.04  5033.3  843.75  5084.7  845.25  5096.9  846.51  5127.5  848.14
  5133.4  848.84  5164.0  850.06  5185.2  850.44  5258.2  855.19  5332.0  858.20
#Mann=3,-1,0
  4142.5     0.1       0  4987.2    0.07       0  4993.2     0.1       0
Bank Sta=4987.2,4993.2
Exp/Cntr=0.3,0.1

Type RM Length L Ch R = 1,1079,0,0,0
BEGIN DESCRIPTION:
UNT 027 in HW 7.0
END DESCRIPTION:
XS GIS Cut Line= 3
      1981106.24     13658033.40      1981356.31     13657450.00
      1980780.96     13657137.22
#Sta/Elev= 30
  4099.1  846.01  4105.7  846.55  4134.7  845.32  4249.7  844.75  4281.6  843.73
  4310.6  843.96  4316.1  843.46  4347.6  843.92  4439.3  842.34  4486.5  842.81
  4491.9  842.28  4515.5  842.13  4539.1  842.79  4544.5  842.10  4562.6  842.38
  4568.1  841.69  4644.2  839.82  4826.4  839.42  4894.7  840.42  4938.9  840.15
  4994.1  838.54  4994.6  837.74  4999.6  837.74  5000.1  838.54  5086.1  842.16
  5173.5  844.60  5270.3  853.77  5298.9  857.19  5336.9  859.25  5388.7  863.03
#Mann=3,-1,0
  4099.1     0.1       0  4994.1    0.07       0  5000.1     0.1       0
Bank Sta=4994.1,5000.1
Exp/Cntr=0.3,0.1

Chan Stop Cuts=-1