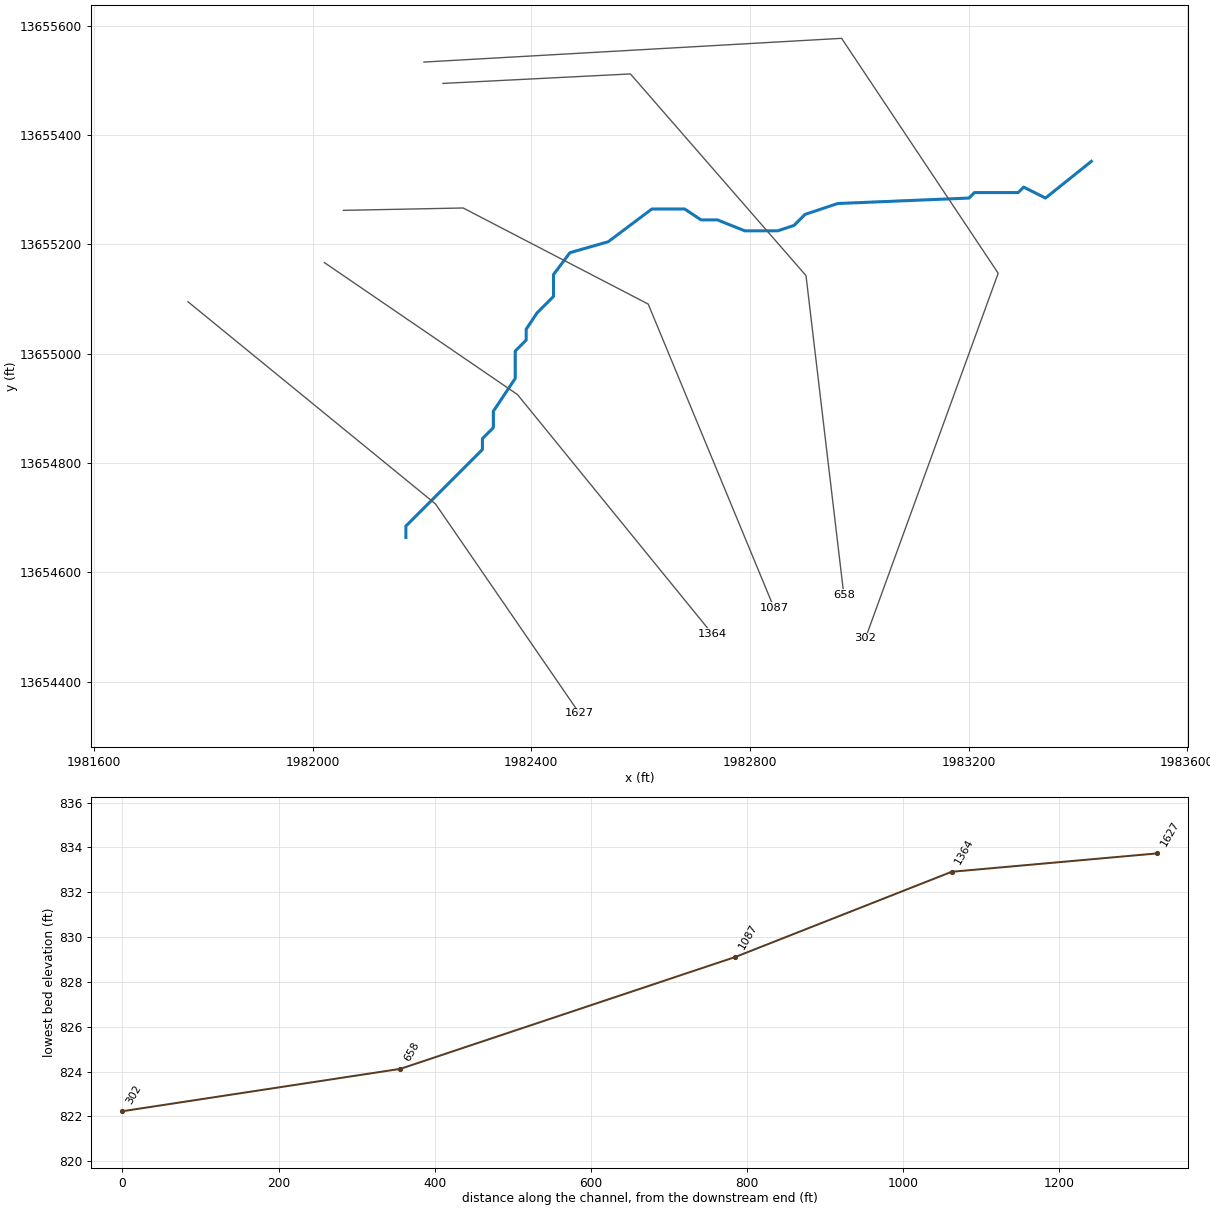
--- UNT 028 in HW.prj (project) ---

Proj Title=UNT 028 in HW Base Level Engineering
Current Plan=p01
Default Exp/Contr=0.3,0.1
English Units
Geom File=g01
Flow File=f01
Plan File=p01
BEGIN DESCRIPTION:
UNT 028 in HW
END DESCRIPTION:

--- UNT 028 in HW.p01 (plan) ---

Plan Title=Multiple Run
Short Identifier=Multiple
Geom File=g01
Flow File=f01
Subcritical Flow
K Sum by GR= 0
Std Step Tol= 0.01
Critical Tol= 0.01
Num of Std Step Trials= 20
Max Error Tol= 0.3
Flow Tol Ratio= 0.001
Split Flow NTrial= 30
Split Flow Tol= 0.02
Split Flow Ratio= 0.02
Log Output Level= 0
Friction Slope Method= 1
Unsteady Friction Slope Method= 2
Unsteady Bridges Friction Slope Method= 1
Parabolic Critical Depth
Global Vel Dist=  1 , 1 , 1
Global Log Level= 0
CheckData=True
Encroach Param= -1, 0, 0, 0
BEGIN DESCRIPTION:
Multiple Run
END DESCRIPTION:

--- UNT 028 in HW.f01 (steady flow) ---

Flow Title=Multiple
Number of Profiles=7
Profile Names=10-year,25-year,50-year,1pct_min,100-year,1pct_plu,500-year
River Rch & RM= UNT 028 in HW,Reach-1,1627
     565     792     981     602    1201    2397    1808
Boundary for River Rch & Prof#=UNT 028 in HW,Reach-1,1
Up Type=0
Dn Type=3
Dn Slope=0.005
Boundary for River Rch & Prof#=UNT 028 in HW,Reach-1,2
Up Type=0
Dn Type=3
Dn Slope=0.005
Boundary for River Rch & Prof#=UNT 028 in HW,Reach-1,3
Up Type=0
Dn Type=3
Dn Slope=0.005
Boundary for River Rch & Prof#=UNT 028 in HW,Reach-1,4
Up Type=0
Dn Type=3
Dn Slope=0.005
Boundary for River Rch & Prof#=UNT 028 in HW,Reach-1,5
Up Type=0
Dn Type=3
Dn Slope=0.005
Boundary for River Rch & Prof#=UNT 028 in HW,Reach-1,6
Up Type=0
Dn Type=3
Dn Slope=0.005
Boundary for River Rch & Prof#=UNT 028 in HW,Reach-1,7
Up Type=0
Dn Type=3
Dn Slope=0.005

--- UNT 028 in HW.g01 (geometry) ---

Geom Title=Existing Conditions

River Reach=UNT 028 in HW,Reach-1
Reach XY= 30
      1982170.80     13654663.52      1982170.80     13654684.54
      1982310.80     13654824.54      1982310.80     13654844.54
      1982330.80     13654864.54      1982330.80     13654894.54
      1982370.80     13654954.54      1982370.80     13655004.54
      1982390.80     13655024.54      1982390.80     13655044.54
      1982410.80     13655074.54      1982440.80     13655104.54
      1982440.80     13655144.54      1982470.80     13655184.54
      1982540.80     13655204.54      1982620.80     13655264.54
      1982680.80     13655264.54      1982710.80     13655244.54
      1982740.80     13655244.54      1982790.80     13655224.54
      1982850.80     13655224.54      1982880.80     13655234.54
      1982900.80     13655254.54      1982960.80     13655274.54
      1983200.80     13655284.54      1983210.80     13655294.54
      1983290.80     13655294.54      1983300.80     13655304.54
      1983340.80     13655284.54      1983424.81     13655351.81

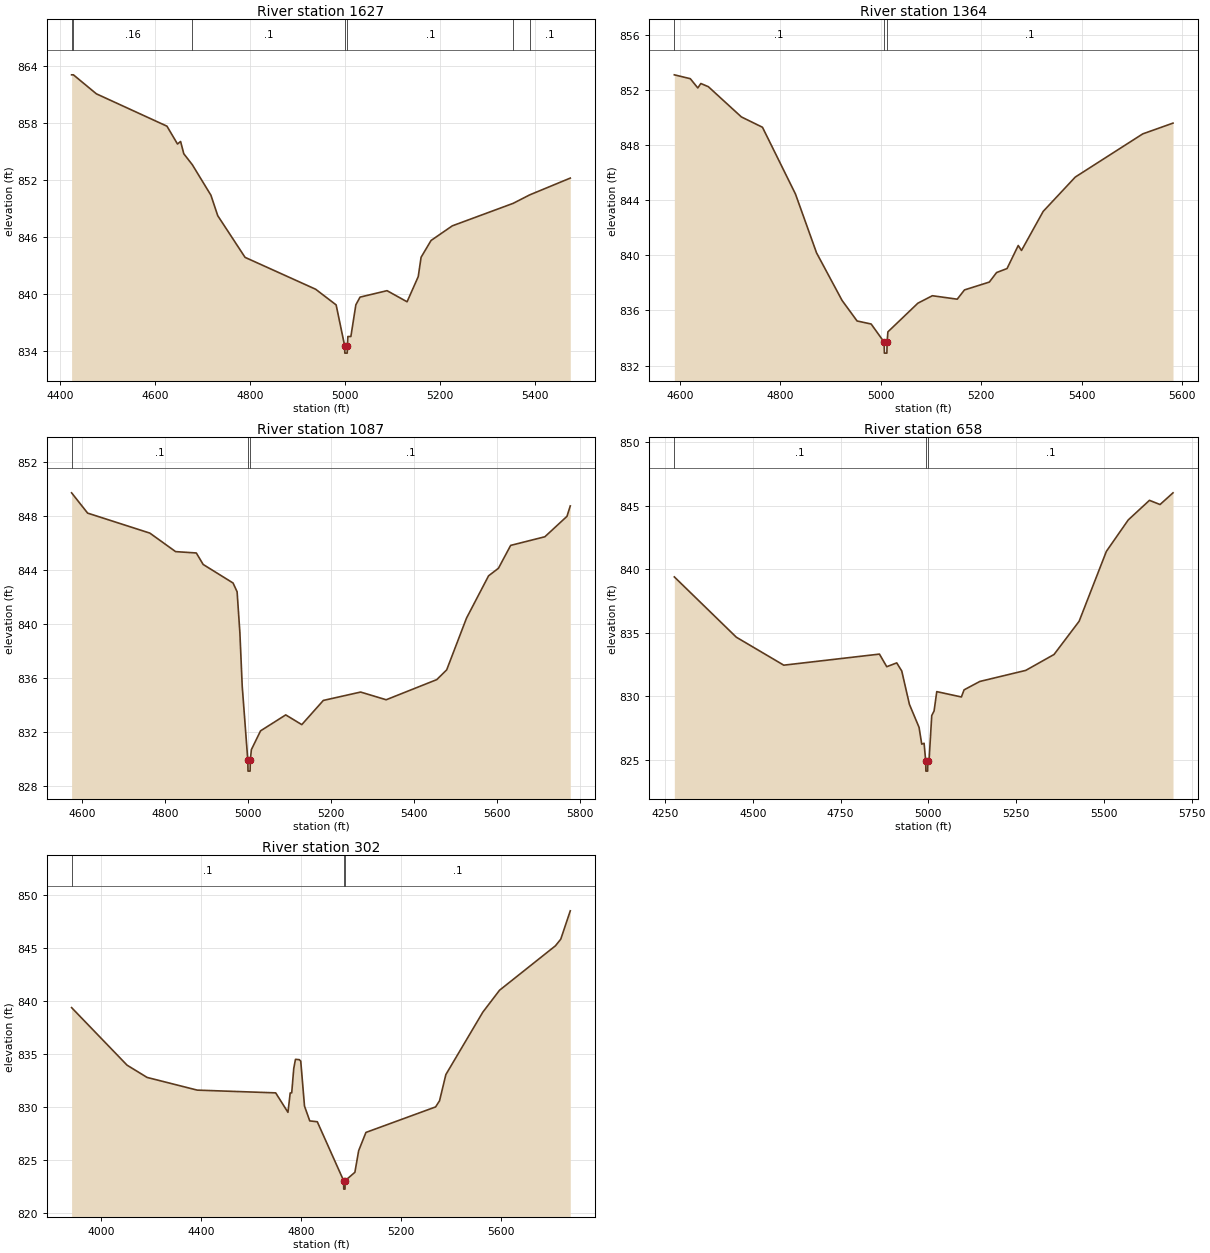
Type RM Length L Ch R = 1,1627,263,263,263
BEGIN DESCRIPTION:
UNT 028 in HW 3.0
END DESCRIPTION:
XS GIS Cut Line= 3
      1981772.10     13655094.90      1982225.00     13654725.00
      1982488.23     13654341.88
#Sta/Elev= 30
  4425.0  863.05  4428.8  863.05  4477.1  861.05  4625.7  857.64  4647.9  855.76
  4654.4  856.03  4661.2  854.73  4679.1  853.58  4718.3  850.36  4732.6  848.21
  4790.1  843.82  4938.7  840.46  4981.8  838.81  4999.6  834.53  5000.1  833.73
  5005.1  833.73  5005.6  834.53  5006.5  835.48  5012.8  835.48  5023.3  838.82
  5032.1  839.63  5088.9  840.31  5131.1  839.14  5154.6  841.79  5160.6  843.83
  5181.6  845.60  5226.3  847.14  5354.4  849.51  5389.1  850.40  5474.6  852.17
#Mann=7,-1,0
  4425.0     0.1       0  4428.8    0.16       0  4679.1     0.1       0
  4999.6    0.07       0  5005.6     0.1       0  5354.4    0.16       0
  5389.1     0.1       0
Bank Sta=4999.6,5005.6
Exp/Cntr=0.3,0.1

Type RM Length L Ch R = 1,1364,277,277,277
BEGIN DESCRIPTION:
UNT 028 in HW 2.0
END DESCRIPTION:
XS GIS Cut Line= 3
      1982021.66     13655166.53      1982375.00     13654925.00
      1982731.28     13654487.27
#Sta/Elev= 30
  4589.2  853.08  4621.0  852.80  4635.9  852.13  4642.0  852.45  4656.9  852.22
  4722.6  850.03  4764.6  849.28  4830.3  844.44  4872.2  840.18  4923.0  836.73
  4952.9  835.24  4980.9  835.02  5006.7  833.71  5007.2  832.91  5012.2  832.91
  5012.7  833.71  5014.2  834.45  5073.9  836.53  5102.7  837.07  5152.2  836.82
  5166.6  837.49  5216.1  838.06  5230.5  838.75  5251.3  839.04  5273.6  840.71
  5280.1  840.35  5323.2  843.18  5387.1  845.67  5521.4  848.80  5581.6  849.58
#Mann=3,-1,0
  4589.2     0.1       0  5006.7    0.07       0  5012.7     0.1       0
Bank Sta=5006.7,5012.7
Exp/Cntr=0.3,0.1

Type RM Length L Ch R = 1,1087,429,429,429
BEGIN DESCRIPTION:
Mapping XS 07db2530
END DESCRIPTION:
XS GIS Cut Line= 4
      1982056.39     13655262.03      1982275.54     13655266.37
      1982614.08     13655090.59      1982844.10     13654535.07
#Sta/Elev= 30
  4575.3  849.70  4613.9  848.20  4763.9  846.72  4826.0  845.35  4875.9  845.25
  4892.4  844.40  4964.4  843.03  4974.2  842.38  4980.9  839.35  4986.5  835.41
  5000.0  829.91  5000.5  829.11  5005.5  829.11  5006.0  829.91  5008.6  830.70
  5030.7  832.09  5091.4  833.27  5130.1  832.55  5182.0  834.34  5271.9  834.96
  5333.5  834.39  5455.4  835.88  5479.3  836.60  5527.1  840.43  5580.3  843.56
  5604.1  844.12  5633.5  845.81  5716.0  846.45  5769.2  847.96  5777.2  848.73
#Mann=3,-1,0
  4575.3     0.1       0  5000.0    0.07       0  5006.0     0.1       0
Bank Sta=5000,5006
Exp/Cntr=0.3,0.1

Type RM Length L Ch R = 1,658,356,356,356
BEGIN DESCRIPTION:
Mapping XS 96092e7b
END DESCRIPTION:
XS GIS Cut Line= 4
      1982238.67     13655494.23      1982581.53     13655511.59
      1982902.71     13655142.67      1982971.96     13654558.40
#Sta/Elev= 30
  4276.1  839.39  4452.7  834.65  4587.9  832.45  4860.5  833.32  4881.3  832.33
  4909.8  832.63  4924.1  831.99  4945.9  829.37  4973.4  827.56  4981.0  826.24
  4987.7  826.31  4992.3  824.92  4992.8  824.12  4997.8  824.12  4998.3  824.92
  5001.9  824.98  5009.5  828.49  5016.2  828.85  5023.8  830.37  5094.0  829.95
  5101.6  830.51  5146.5  831.17  5277.4  832.04  5357.9  833.29  5429.4  835.90
  5507.1  841.40  5569.4  843.87  5629.8  845.41  5660.0  845.08  5696.9  846.00
#Mann=3,-1,0
  4276.1     0.1       0  4992.3    0.07       0  4998.3     0.1       0
Bank Sta=4992.3,4998.3
Exp/Cntr=0.3,0.1

Type RM Length L Ch R = 1,302,0,0,0
BEGIN DESCRIPTION:
UNT 028 in HW 1.0
END DESCRIPTION:
XS GIS Cut Line= 4
      1982203.88     13655533.29      1982967.82     13655576.70
      1983254.27     13655147.01      1983011.46     13654479.28
#Sta/Elev= 30
  3883.7  839.39  4105.2  833.95  4185.3  832.79  4385.6  831.59  4699.0  831.33
  4748.0  829.49  4757.0  831.32  4763.0  831.33  4771.1  833.63  4778.0  834.50
  4793.1  834.47  4799.1  834.33  4814.1  830.08  4835.1  828.68  4865.2  828.60
  4970.4  823.03  4970.9  822.23  4975.9  822.23  4976.4  823.03  5015.4  823.82
  5030.4  825.86  5059.5  827.59  5337.7  830.00  5353.5  830.58  5378.8  833.06
  5526.4  838.96  5593.1  841.03  5816.4  845.23  5837.8  845.86  5875.8  848.54
#Mann=3,-1,0
  3883.7     0.1       0  4970.4    0.07       0  4976.4     0.1       0
Bank Sta=4970.4,4976.4
Exp/Cntr=0.3,0.1

Chan Stop Cuts=-1