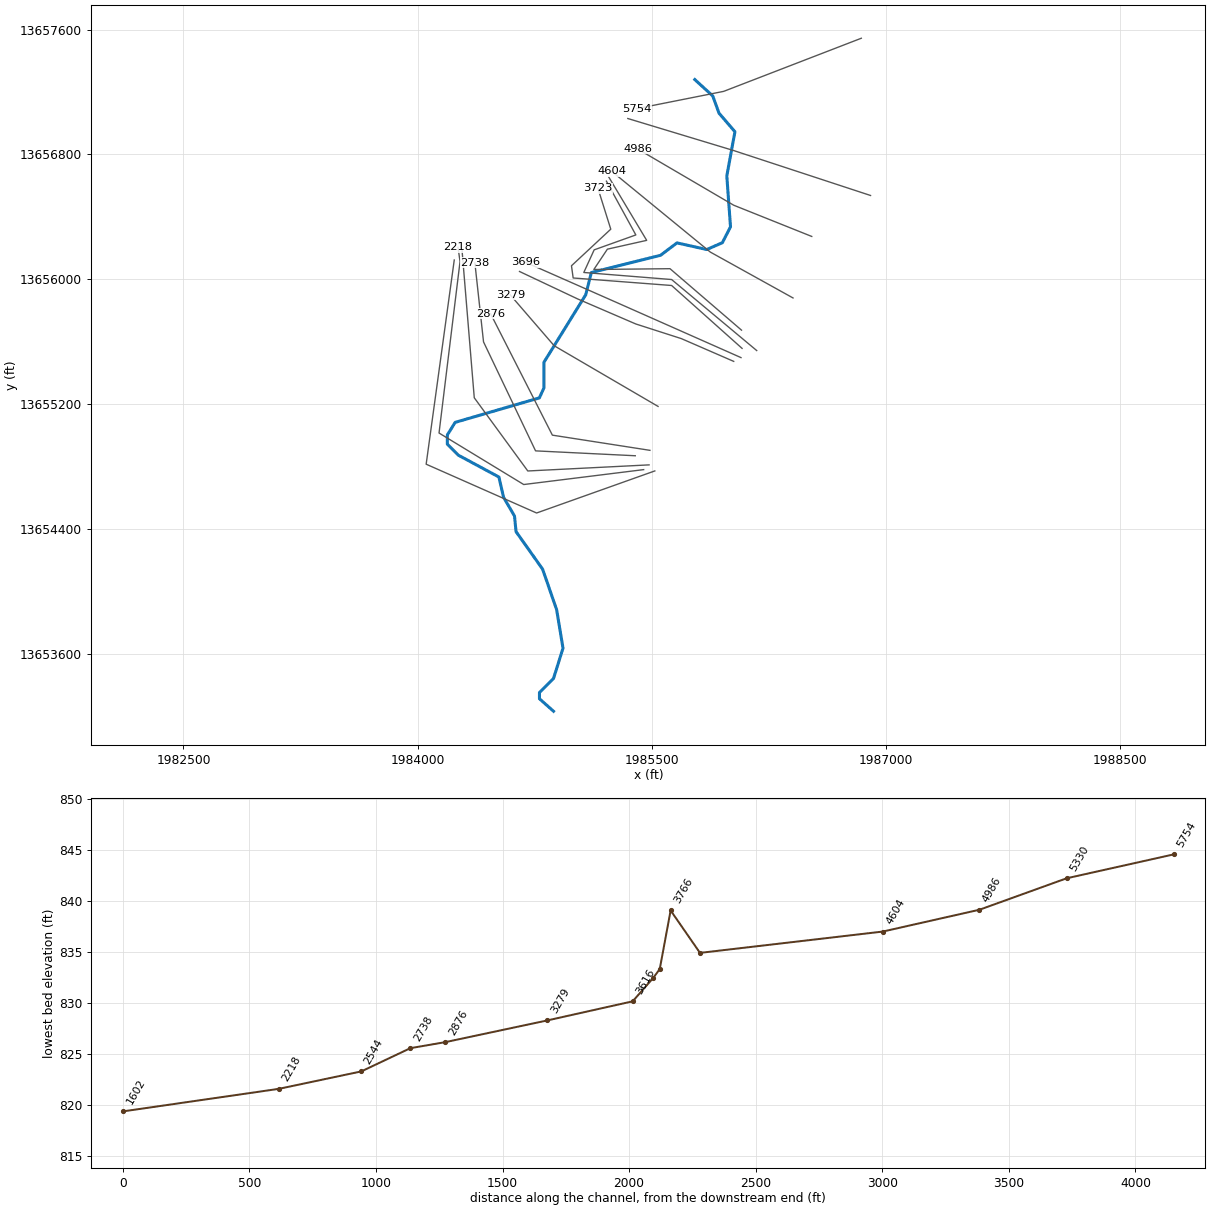
--- UNT 029 in HW.prj (project) ---

Proj Title=UNT 029 in HW Base Level Engineering
Current Plan=p01
Default Exp/Contr=0.3,0.1
English Units
Geom File=g01
Flow File=f01
Plan File=p01
BEGIN DESCRIPTION:
UNT 029 in HW
END DESCRIPTION:

--- UNT 029 in HW.p01 (plan) ---

Plan Title=Multiple Run
Short Identifier=Multiple
Geom File=g01
Flow File=f01
Subcritical Flow
K Sum by GR= 0
Std Step Tol= 0.01
Critical Tol= 0.01
Num of Std Step Trials= 20
Max Error Tol= 0.3
Flow Tol Ratio= 0.001
Split Flow NTrial= 30
Split Flow Tol= 0.02
Split Flow Ratio= 0.02
Log Output Level= 0
Friction Slope Method= 1
Unsteady Friction Slope Method= 2
Unsteady Bridges Friction Slope Method= 1
Parabolic Critical Depth
Global Vel Dist=  1 , 1 , 1
Global Log Level= 0
CheckData=True
Encroach Param= -1, 0, 0, 0
BEGIN DESCRIPTION:
Multiple Run
END DESCRIPTION:

--- UNT 029 in HW.f01 (steady flow) ---

Flow Title=Multiple
Number of Profiles=7
Profile Names=10-year,25-year,50-year,1pct_min,100-year,1pct_plu,500-year
River Rch & RM= UNT 029 in HW,Reach-1,5754
     668     952    1192     741    1478    2948    2276
River Rch & RM= UNT 029 in HW,Reach-1,5330
     899    1297    1639    1025    2045    4079    3193
Boundary for River Rch & Prof#=UNT 029 in HW,Reach-1,1
Up Type=0
Dn Type=3
Dn Slope=0.005
Boundary for River Rch & Prof#=UNT 029 in HW,Reach-1,2
Up Type=0
Dn Type=3
Dn Slope=0.005
Boundary for River Rch & Prof#=UNT 029 in HW,Reach-1,3
Up Type=0
Dn Type=3
Dn Slope=0.005
Boundary for River Rch & Prof#=UNT 029 in HW,Reach-1,4
Up Type=0
Dn Type=3
Dn Slope=0.005
Boundary for River Rch & Prof#=UNT 029 in HW,Reach-1,5
Up Type=0
Dn Type=3
Dn Slope=0.005
Boundary for River Rch & Prof#=UNT 029 in HW,Reach-1,6
Up Type=0
Dn Type=3
Dn Slope=0.005
Boundary for River Rch & Prof#=UNT 029 in HW,Reach-1,7
Up Type=0
Dn Type=3
Dn Slope=0.005

--- UNT 029 in HW.g01 (geometry) ---

Geom Title=Existing Conditions

River Reach=UNT 029 in HW,Reach-1
Reach XY= 30
      1985775.80     13657279.54      1985890.80     13657174.54
      1985930.80     13657064.54      1986032.85     13656945.76
      1985980.80     13656662.43      1986004.47     13656336.60
      1985952.38     13656235.04      1985852.56     13656191.20
      1985661.58     13656233.74      1985556.55     13656154.31
      1985112.97     13656043.89      1985077.17     13655901.74
      1984809.15     13655468.80      1984809.33     13655305.35
      1984780.16     13655241.28      1984240.80     13655084.54
      1984190.80     13655004.54      1984190.80     13654944.54
      1984260.80     13654874.54      1984520.80     13654734.54
      1984550.80     13654604.54      1984620.80     13654484.54
      1984630.80     13654384.54      1984800.80     13654144.54
      1984890.80     13653884.54      1984931.45     13653638.20
      1984870.80     13653444.54      1984780.80     13653354.54
      1984780.80     13653314.54      1984870.80     13653234.54

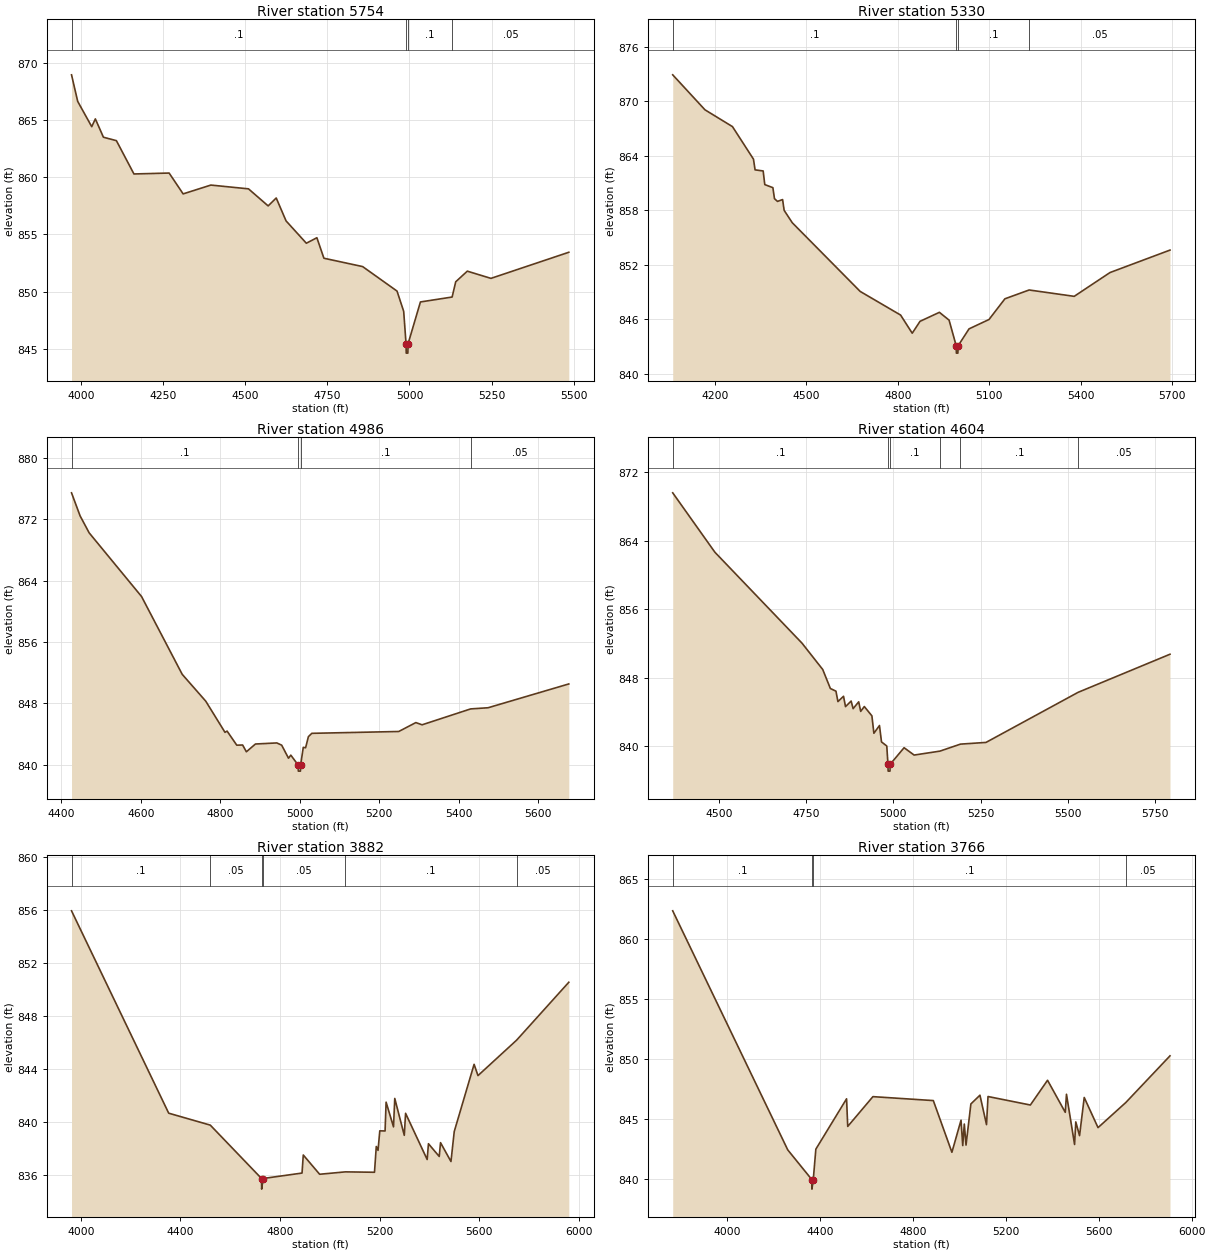
Type RM Length L Ch R = 1,5754,424,424,424
BEGIN DESCRIPTION:
UNT 029 in HW 9.0
END DESCRIPTION:
XS GIS Cut Line= 3
      1986842.50     13657544.28      1985960.58     13657204.01
      1985401.59     13657092.91
#Sta/Elev= 30
  3970.3  868.93  3989.1  866.61  4031.9  864.40  4042.9  865.08  4067.5  863.48
  4107.0  863.18  4160.5  860.27  4267.7  860.35  4310.4  858.53  4394.9  859.30
  4509.5  858.97  4569.4  857.48  4594.0  858.17  4624.0  856.17  4685.8  854.22
  4717.9  854.70  4739.3  852.91  4857.3  852.18  4962.1  850.04  4982.4  848.27
  4989.6  845.42  4990.1  844.62  4995.1  844.62  4995.6  845.42  5033.4  849.09
  5130.0  849.52  5140.9  850.85  5176.2  851.78  5248.3  851.15  5485.5  853.43
#Mann=4,-1,0
  3970.3     0.1       0  4989.6    0.07       0  4995.6     0.1       0
  5130.0    0.05       0
Bank Sta=4989.6,4995.6
Exp/Cntr=0.3,0.1

Type RM Length L Ch R = 1,5330,344,344,344
BEGIN DESCRIPTION:
UNT 029 in HW 8.0
END DESCRIPTION:
XS GIS Cut Line= 3
      1986901.55     13656537.35      1986025.00     13656825.00
      1985346.70     13657030.19
#Sta/Elev= 30
  4061.4  872.90  4167.2  869.05  4257.4  867.20  4326.3  863.62  4331.6  862.44
  4358.1  862.32  4363.4  860.82  4390.0  860.48  4395.2  859.27  4405.1  858.97
  4421.8  859.17  4427.0  857.98  4453.6  856.62  4676.4  849.06  4808.9  846.46
  4847.1  844.46  4872.6  845.77  4936.2  846.76  4968.0  845.90  4991.4  843.07
  4991.9  842.27  4996.9  842.27  4997.4  843.07  5033.4  844.94  5098.9  845.97
  5151.1  848.25  5230.6  849.22  5378.4  848.52  5495.9  851.14  5692.6  853.61
#Mann=4,-1,0
  4061.4     0.1       0  4991.4    0.07       0  4997.4     0.1       0
  5230.6    0.05       0
Bank Sta=4991.4,4997.4
Exp/Cntr=0.3,0.1

Type RM Length L Ch R = 1,4986,382,382,382
BEGIN DESCRIPTION:
UNT 029 in HW 7.0
END DESCRIPTION:
XS GIS Cut Line= 3
      1986524.97     13656275.01      1986025.00     13656475.00
      1985409.26     13656835.51
#Sta/Elev= 30
  4425.3  875.42  4446.8  872.43  4469.7  870.21  4601.6  861.92  4704.0  851.79
  4763.2  848.30  4811.7  844.24  4817.0  844.40  4841.3  842.57  4856.1  842.59
  4865.5  841.71  4888.4  842.72  4942.2  842.86  4954.4  842.57  4971.6  840.87
  4977.4  841.27  4995.8  839.99  4996.3  839.19  5001.6  839.19  5002.1  839.99
  5008.8  842.29  5014.6  842.23  5021.7  843.68  5030.3  844.11  5249.2  844.35
  5292.2  845.51  5307.9  845.22  5430.2  847.29  5474.0  847.44  5677.3  850.54
#Mann=4,-1,0
  4425.3     0.1       0  4995.8    0.07       0  5002.1     0.1       0
  5430.2    0.05       0
Bank Sta=4995.8,5002.1
Exp/Cntr=0.3,0.1

Type RM Length L Ch R = 1,4604,722,722,722
BEGIN DESCRIPTION:
UNT 029 in HW 6.0
END DESCRIPTION:
XS GIS Cut Line= 3
      1986405.03     13655881.09      1985875.00     13656175.00
      1985241.84     13656693.59
#Sta/Elev= 30
  4368.1  869.62  4488.9  862.67  4738.4  852.03  4797.9  848.94  4819.7  846.72
  4835.7  846.41  4841.4  845.19  4857.4  845.81  4863.1  844.60  4879.2  845.25
  4884.9  844.36  4900.9  845.16  4906.6  844.04  4916.9  844.61  4938.7  843.52
  4944.4  841.48  4960.4  842.39  4966.2  840.47  4981.3  839.99  4984.7  837.85
  4985.2  837.05  4990.5  837.05  4991.0  837.85  5030.9  839.79  5059.6  838.93
  5133.5  839.39  5192.4  840.21  5265.6  840.41  5529.3  846.27  5792.6  850.73
#Mann=6,-1,0
  4368.1     0.1       0  4984.7    0.07       0  4991.0     0.1       0
  5133.5    0.05       0  5192.4     0.1       0  5529.3    0.05       0
Bank Sta=4984.7,4991
Exp/Cntr=0.3,0.1

Type RM Length L Ch R = 1,3882,116,116,116
BEGIN DESCRIPTION:
UNT 029 in HW 5.0
END DESCRIPTION:
XS GIS Cut Line= 6
      1986075.00     13655675.00      1985616.83     13656068.60
      1985128.96     13656063.32      1985215.76     13656193.53
      1985467.50     13656249.95      1985224.43     13656655.79
#Sta/Elev= 30
  3962.9  855.92  4353.0  840.68  4520.0  839.78  4725.7  835.76  4726.2  834.96
  4732.0  835.76  4888.3  836.17  4893.3  837.53  4959.0  836.08  5062.4  836.26
  5179.2  836.23  5186.4  838.17  5193.4  837.88  5200.5  839.35  5221.7  839.34
  5225.8  841.51  5255.5  839.65  5260.6  841.79  5298.8  839.01  5304.0  840.67
  5390.7  837.19  5395.8  838.38  5439.1  837.42  5444.3  838.46  5486.2  837.04
  5499.4  839.30  5579.1  844.36  5594.7  843.51  5749.8  846.18  5959.3  850.54
#Mann=6,-1,0
  3962.9     0.1       0  4520.0    0.05       0  4725.7   0.033       0
  4732.0    0.05       0  5062.4     0.1       0  5749.8    0.05       0
Bank Sta=4725.7,4732
Exp/Cntr=0.3,0.1

Type RM Length L Ch R = 1,3766,43,43,43
BEGIN DESCRIPTION:
UNT 029 in HW 4.0
END DESCRIPTION:
XS GIS Cut Line= 6
      1986172.38     13655544.30      1985627.25     13655999.15
      1985064.75     13656044.29      1985131.13     13656189.19
      1985398.05     13656284.67      1985209.65     13656629.00
#Sta/Elev= 30
  3765.2  862.38  4260.6  842.40  4364.2  839.92  4364.7  839.12  4370.5  839.92
  4381.6  842.46  4513.9  846.67  4518.9  844.36  4627.4  846.85  4887.5  846.52
  4967.5  842.20  5006.8  844.88  5014.2  842.76  5020.9  844.56  5028.3  842.80
  5049.3  846.24  5088.3  846.97  5116.6  844.51  5123.0  846.86  5305.4  846.15
  5379.4  848.22  5455.7  845.54  5460.9  847.05  5495.8  842.85  5501.0  844.74
  5517.2  843.59  5537.4  846.78  5596.8  844.26  5716.5  846.36  5906.7  850.26
#Mann=4,-1,0
  3765.2     0.1       0  4364.2    0.07       0  4370.5     0.1       0
  5716.5    0.05       0
Bank Sta=4364.2,4370.5
Exp/Cntr=0.3,0.1

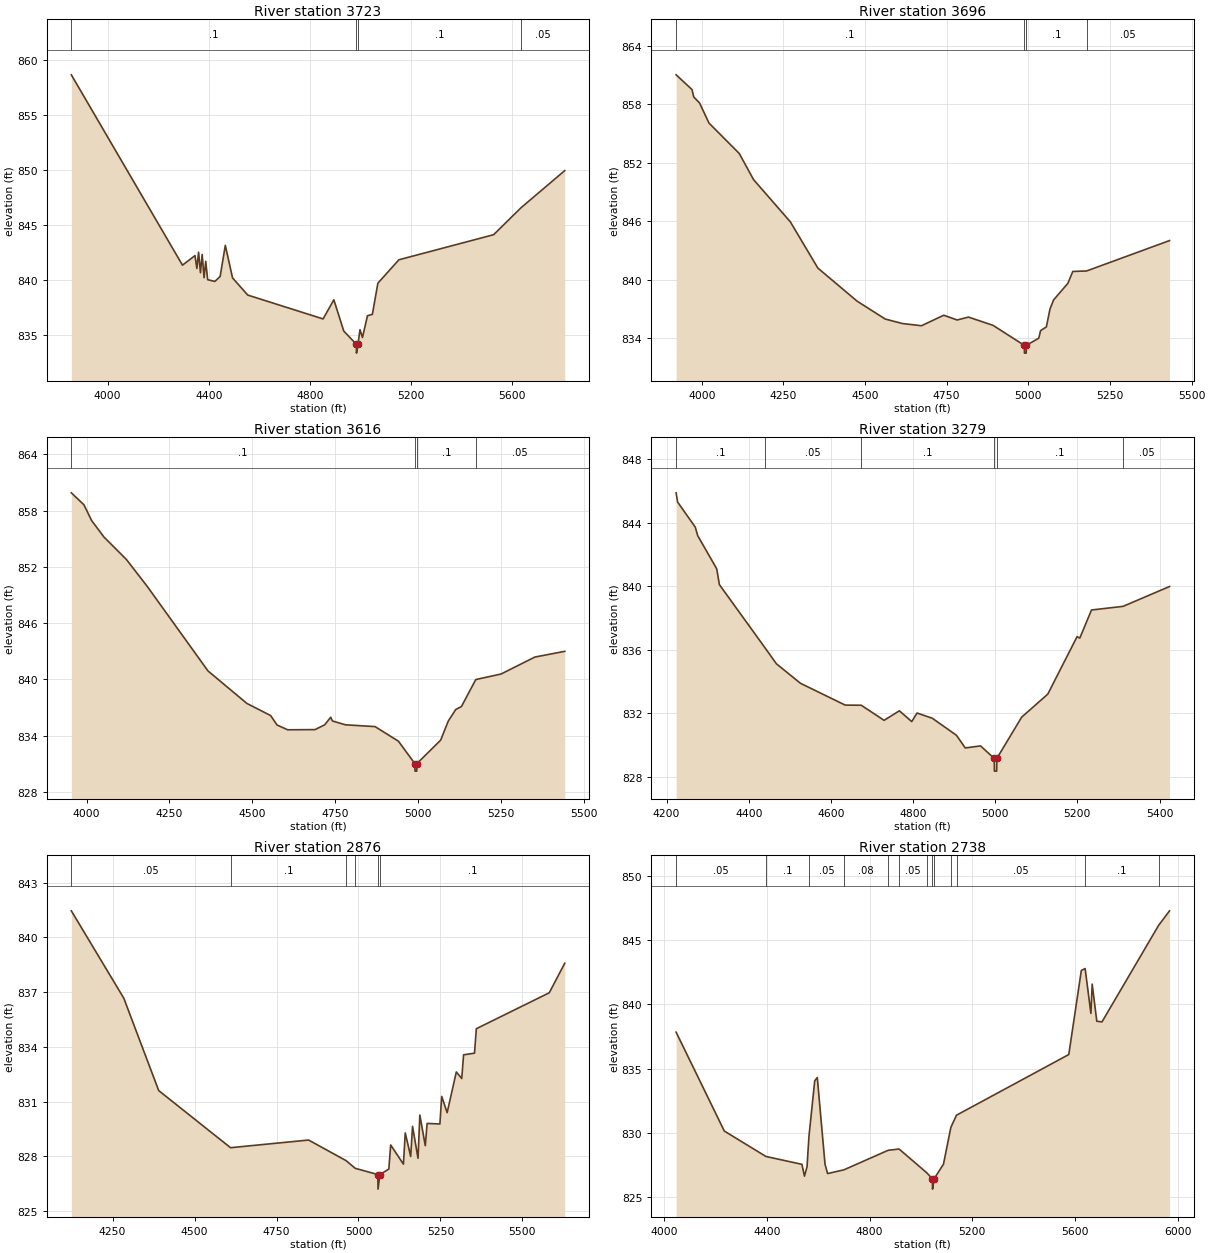
Type RM Length L Ch R = 1,3723,27,27,27
BEGIN DESCRIPTION:
Mapping XS 07eb090f
END DESCRIPTION:
XS GIS Cut Line= 6
      1986078.61     13655558.21      1985627.25     13655960.96
      1984996.58     13656009.06      1984985.73     13656087.19
      1985237.46     13656321.56      1985155.01     13656584.11
#Sta/Elev= 30
  3857.0  858.68  4296.3  841.37  4345.7  842.24  4353.2  841.07  4359.9  842.55
  4367.4  840.68  4374.1  842.35  4381.6  840.23  4388.3  841.72  4395.8  840.05
  4424.2  839.89  4445.2  840.34  4465.6  843.17  4494.2  840.21  4554.3  838.65
  4852.1  836.48  4894.6  838.22  4933.8  835.38  4983.6  834.17  4984.1  833.37
  4989.9  834.17  4998.0  835.50  5007.7  834.79  5027.5  836.77  5046.9  836.90
  5068.6  839.73  5151.8  841.86  5526.1  844.14  5635.3  846.61  5807.3  849.97
#Mann=4,-1,0
  3857.0     0.1       0  4983.6    0.07       0  4989.9     0.1       0
  5635.3    0.05       0
Bank Sta=4983.6,4989.9
Exp/Cntr=0.3,0.1

Type RM Length L Ch R = 1,3696,80,80,80
BEGIN DESCRIPTION:
Mapping XS 24ee836b
END DESCRIPTION:
XS GIS Cut Line= 3
      1986071.72     13655499.14      1985280.03     13655849.85
      1984690.17     13656110.08
#Sta/Elev= 30
  3921.7  861.03  3970.3  859.52  3975.7  858.76  3993.5  858.14  4022.3  856.08
  4115.0  852.96  4158.7  850.28  4271.5  845.94  4355.6  841.20  4475.9  837.80
  4561.8  835.97  4613.9  835.51  4672.8  835.28  4741.2  836.36  4782.1  835.87
  4816.6  836.17  4892.0  835.32  4987.6  833.27  4988.1  832.47  4993.4  832.47
  4993.9  833.27  5031.9  834.00  5037.4  834.78  5055.2  835.16  5066.3  837.00
  5077.3  837.93  5121.0  839.63  5136.1  840.85  5178.3  840.90  5432.3  844.02
#Mann=4,-1,0
  3921.7     0.1       0  4987.6    0.07       0  4993.9     0.1       0
  5178.3    0.05       0
Bank Sta=4987.6,4993.9
Exp/Cntr=0.3,0.1

Type RM Length L Ch R = 1,3616,337,337,337
BEGIN DESCRIPTION:
UNT 029 in HW 3.0
END DESCRIPTION:
XS GIS Cut Line= 5
      1986024.98     13655475.01      1985689.75     13655620.68
      1985398.08     13655714.43      1985025.00     13655875.00
      1984652.90     13656050.60
#Sta/Elev= 30
  3953.9  859.90  3991.8  858.63  4015.2  856.94  4052.0  855.20  4119.9  852.80
  4182.8  849.93  4366.4  840.90  4483.9  837.43  4555.5  836.14  4574.9  835.13
  4607.0  834.62  4689.7  834.64  4718.7  835.15  4736.8  835.96  4742.2  835.56
  4781.5  835.15  4870.8  834.96  4941.4  833.40  4990.8  831.01  4991.3  830.21
  4996.6  830.21  4997.1  831.01  5068.9  833.52  5091.6  835.54  5114.4  836.79
  5131.5  837.10  5174.8  839.98  5251.1  840.57  5353.2  842.38  5443.4  842.99
#Mann=4,-1,0
  3953.9     0.1       0  4990.8    0.07       0  4997.1     0.1       0
  5174.8    0.05       0
Bank Sta=4990.8,4997.1
Exp/Cntr=0.3,0.1

Type RM Length L Ch R = 1,3279,403,403,403
BEGIN DESCRIPTION:
UNT 029 in HW 2.0
END DESCRIPTION:
XS GIS Cut Line= 3
      1985540.42     13655186.66      1984875.00     13655575.00
      1984593.38     13655900.94
#Sta/Elev= 30
  4223.2  845.87  4226.8  845.29  4269.8  843.71  4275.8  843.17  4322.1  841.08
  4328.5  840.09  4440.1  836.09  4467.4  835.10  4526.1  833.87  4634.7  832.50
  4673.9  832.49  4729.5  831.54  4766.7  832.14  4796.8  831.46  4809.7  832.00
  4846.9  831.67  4905.6  830.60  4927.1  829.80  4964.3  829.93  4997.6  829.14
  4998.1  828.34  5003.5  828.34  5004.0  829.14  5064.4  831.74  5128.0  833.19
  5199.3  836.81  5205.9  836.72  5234.4  838.49  5311.4  838.72  5424.4  839.97
#Mann=6,-1,0
  4223.2     0.1       0  4440.1    0.05       0  4673.9     0.1       0
  4997.6    0.07       0  5004.0     0.1       0  5311.4    0.05       0
Bank Sta=4997.6,5004
Exp/Cntr=0.3,0.1

Type RM Length L Ch R = 1,2876,138,138,138
BEGIN DESCRIPTION:
Mapping XS 2783f75b
END DESCRIPTION:
XS GIS Cut Line= 3
      1985488.33     13654905.41      1984863.36     13655002.62
      1984467.62     13655780.22
#Sta/Elev= 30
  4124.2  841.46  4284.3  836.67  4390.7  831.61  4609.8  828.48  4847.9  828.90
  4962.3  827.77  4990.0  827.35  5059.1  827.01  5059.6  826.21  5065.5  827.01
  5092.6  827.31  5098.2  828.63  5137.1  827.58  5142.7  829.29  5159.3  828.00
  5164.9  829.65  5181.6  827.90  5187.2  830.27  5203.8  828.59  5209.4  829.81
  5248.3  829.78  5253.9  831.29  5270.5  830.40  5298.4  832.63  5315.0  832.27
  5320.6  833.57  5353.9  833.66  5359.5  835.00  5582.0  836.97  5629.2  838.59
#Mann=6,-1,0
  4124.2    0.05       0  4609.8     0.1       0  4962.3    0.08       0
  4990.0     0.1       0  5059.1    0.07       0  5065.5     0.1       0
Bank Sta=5059.1,5065.5
Exp/Cntr=0.3,0.1

Type RM Length L Ch R = 1,2738,194,194,194
BEGIN DESCRIPTION:
Mapping XS 3b8a7f7a
END DESCRIPTION:
XS GIS Cut Line= 4
      1985394.57     13654870.68      1984755.72     13654901.93
      1984422.39     13655599.85      1984366.83     13656106.77
#Sta/Elev= 30
  4045.7  837.83  4233.5  830.14  4395.8  828.16  4535.9  827.55  4545.9  826.63
  4555.9  827.36  4563.3  829.70  4585.9  834.05  4595.9  834.30  4626.0  827.56
  4636.0  826.83  4699.5  827.12  4871.9  828.64  4914.6  828.74  5022.1  826.90
  5044.6  826.42  5045.1  825.62  5051.0  826.42  5087.6  827.56  5116.3  830.42
  5138.4  831.37  5576.0  836.09  5624.9  842.63  5639.8  842.78  5662.2  839.29
  5667.2  841.57  5685.2  838.68  5705.4  838.63  5926.1  846.14  5968.7  847.27
#Mann=13,-1,0
  4045.7    0.05       0  4395.8     0.1       0  4563.3    0.05       0
  4699.5    0.08       0  4871.9     0.1       0  4914.6    0.05       0
  5022.1    0.08       0  5044.6    0.04       0  5051.0    0.08       0
  5116.3     0.1       0  5138.4    0.05       0  5639.8     0.1       0
  5926.1    0.05       0
Bank Sta=5044.6,5051
Exp/Cntr=0.3,0.1

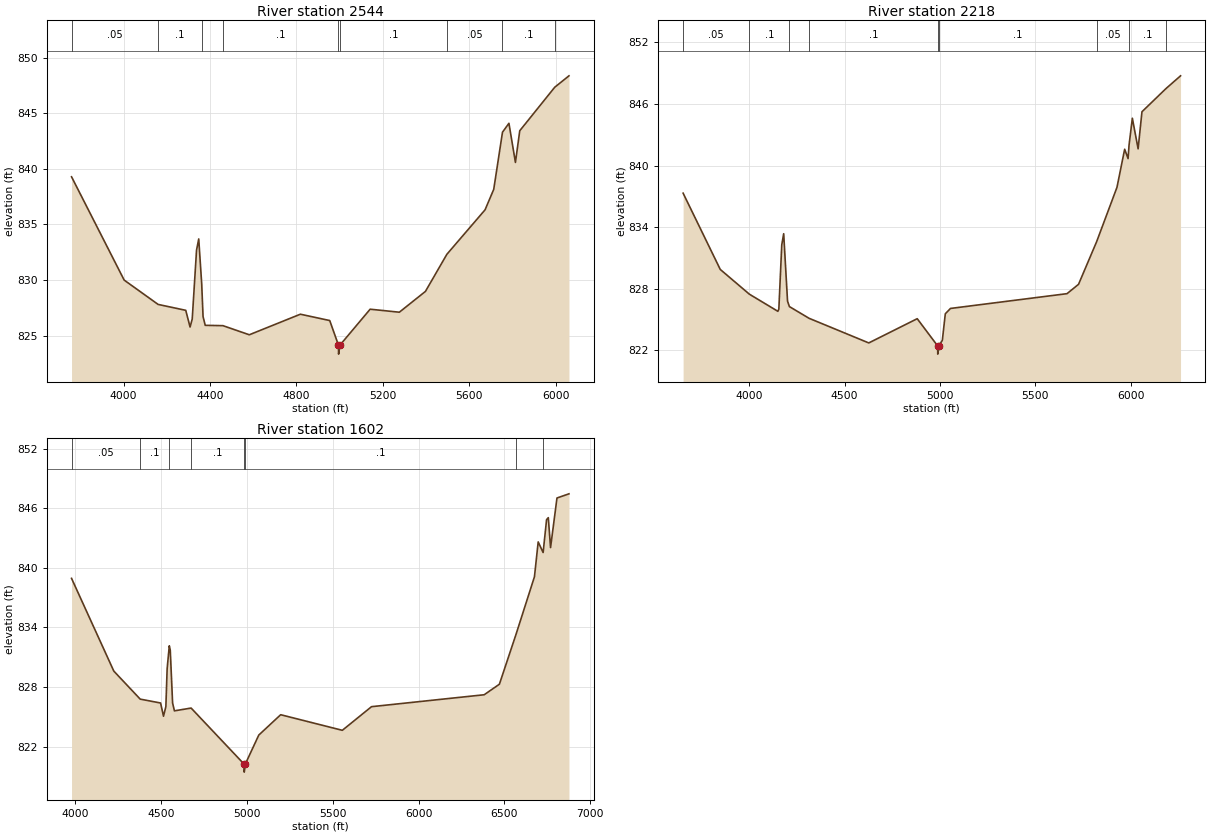
Type RM Length L Ch R = 1,2544,326,326,326
BEGIN DESCRIPTION:
Mapping XS f56613f6
END DESCRIPTION:
XS GIS Cut Line= 4
      1985482.81     13654812.25      1984705.94     13654773.19
      1984363.06     13655241.94      1984285.09     13656181.89
#Sta/Elev= 30
  3759.4  839.29  4002.9  830.00  4160.1  827.81  4287.9  827.28  4307.9  825.78
  4317.9  826.50  4337.9  832.70  4348.0  833.70  4361.8  829.64  4368.0  826.72
  4378.0  825.93  4460.1  825.90  4582.0  825.08  4818.3  826.93  4954.2  826.36
  4994.7  824.14  4995.2  823.34  5001.1  824.14  5141.2  827.38  5276.3  827.11
  5397.0  828.98  5496.3  832.32  5673.0  836.32  5713.1  838.16  5753.6  843.30
  5783.4  844.10  5813.5  840.58  5833.5  843.43  5995.2  847.34  6061.2  848.37
#Mann=9,-1,0
  3759.4    0.05       0  4160.1     0.1       0  4361.8    0.08       0
  4460.1     0.1       0  4994.7    0.07       0  5001.1     0.1       0
  5496.3    0.05       0  5753.6     0.1       0  5995.2    0.05       0
Bank Sta=4994.7,5001.1
Exp/Cntr=0.3,0.1

Type RM Length L Ch R = 1,2218,616,616,616
BEGIN DESCRIPTION:
Mapping XS 11d694dc
END DESCRIPTION:
XS GIS Cut Line= 5
      1985448.18     13654781.88      1984679.90     13654686.38
      1984137.37     13655016.25      1984271.92     13656114.34
      1984258.90     13656205.47
#Sta/Elev= 30
  3653.4  837.31  3848.1  829.88  4000.7  827.47  4150.2  825.80  4155.2  826.01
  4170.5  832.27  4180.6  833.36  4200.8  826.79  4210.6  826.26  4313.7  825.12
  4626.7  822.72  4880.6  825.08  4987.7  822.43  4988.2  821.63  4994.2  822.43
  5012.3  822.98  5027.8  825.56  5055.0  826.08  5665.8  827.52  5726.2  828.43
  5821.0  832.58  5927.7  837.88  5968.0  841.59  5985.9  840.68  5991.0  841.99
  6008.3  844.61  6038.5  841.63  6058.7  845.24  6184.1  847.49  6260.9  848.74
#Mann=9,-1,0
  3653.4    0.05       0  4000.7     0.1       0  4210.6    0.05       0
  4313.7     0.1       0  4987.7    0.07       0  4994.2     0.1       0
  5821.0    0.05       0  5991.0     0.1       0  6184.1    0.05       0
Bank Sta=4987.7,4994.2
Exp/Cntr=0.3,0.1

Type RM Length L Ch R = 1,1602,0,0,0
BEGIN DESCRIPTION:
UNT 029 in HW 1.0
END DESCRIPTION:
XS GIS Cut Line= 4
      1985519.59     13654773.45      1984762.37     13654504.09
      1984054.90     13654816.59      1984234.89     13656124.15
#Sta/Elev= 30
  3978.7  838.93  4225.0  829.59  4378.6  826.77  4497.3  826.38  4514.3  825.05
  4528.1  826.02  4535.5  829.83  4548.1  832.14  4553.7  831.69  4567.3  826.38
  4577.9  825.59  4675.2  825.87  4984.0  820.22  4984.5  819.42  4990.5  820.22
  5069.2  823.15  5196.7  825.20  5555.8  823.63  5725.8  826.01  6381.9  827.21
  6470.5  828.27  6568.3  833.34  6674.7  839.09  6696.5  842.60  6725.2  841.53
  6745.3  844.84  6755.4  845.04  6768.5  842.03  6805.9  847.02  6875.7  847.44
#Mann=8,-1,0
  3978.7    0.05       0  4378.6     0.1       0  4548.1    0.05       0
  4675.2     0.1       0  4984.0    0.07       0  4990.5     0.1       0
  6568.3    0.05       0  6725.2     0.1       0
Bank Sta=4984,4990.5
Exp/Cntr=0.3,0.1

Chan Stop Cuts=-1