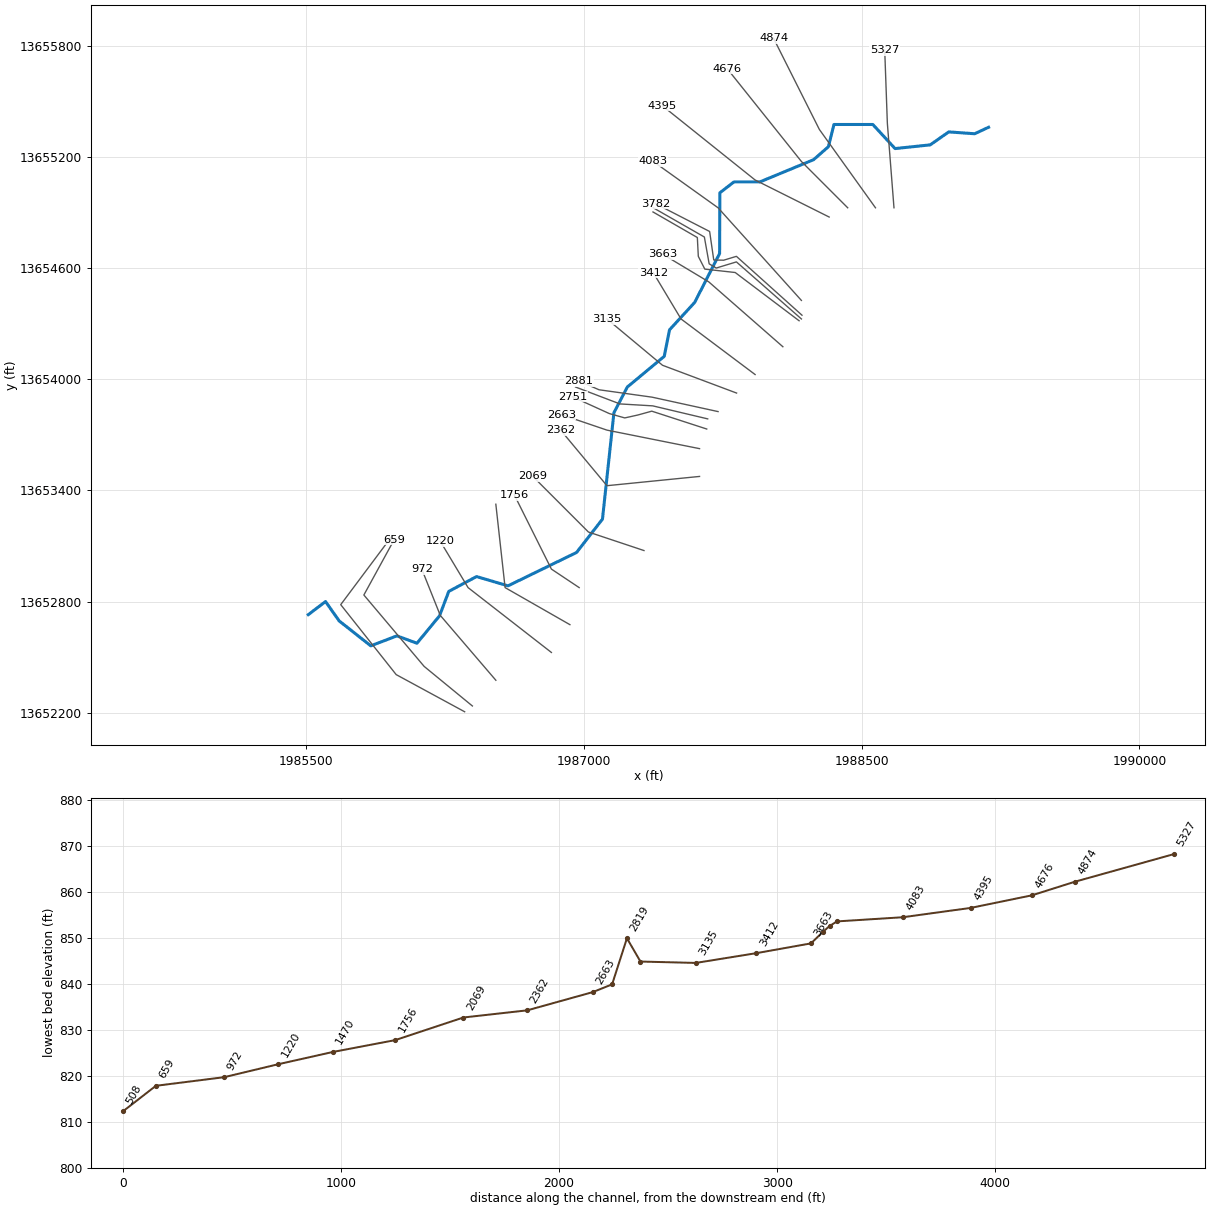
--- UNT 030 in HW.prj (project) ---

Proj Title=UNT 030 in HW Base Level Engineering
Current Plan=p01
Default Exp/Contr=0.3,0.1
English Units
Geom File=g01
Flow File=f01
Plan File=p01
BEGIN DESCRIPTION:
UNT 030 in HW
END DESCRIPTION:

--- UNT 030 in HW.p01 (plan) ---

Plan Title=Multiple Run
Short Identifier=Multiple
Geom File=g01
Flow File=f01
Subcritical Flow
K Sum by GR= 0
Std Step Tol= 0.01
Critical Tol= 0.01
Num of Std Step Trials= 20
Max Error Tol= 0.3
Flow Tol Ratio= 0.001
Split Flow NTrial= 30
Split Flow Tol= 0.02
Split Flow Ratio= 0.02
Log Output Level= 0
Friction Slope Method= 1
Unsteady Friction Slope Method= 2
Unsteady Bridges Friction Slope Method= 1
Parabolic Critical Depth
Global Vel Dist=  1 , 1 , 1
Global Log Level= 0
CheckData=True
Encroach Param= -1, 0, 0, 0
BEGIN DESCRIPTION:
Multiple Run
END DESCRIPTION:

--- UNT 030 in HW.f01 (steady flow) ---

Flow Title=Multiple
Number of Profiles=7
Profile Names=10-year,25-year,50-year,1pct_min,100-year,1pct_plu,500-year
River Rch & RM= UNT 030 in HW,Reach-1,5327
     337     459     559     338     674    1345     983
Boundary for River Rch & Prof#=UNT 030 in HW,Reach-1,1
Up Type=0
Dn Type=3
Dn Slope=0.005
Boundary for River Rch & Prof#=UNT 030 in HW,Reach-1,2
Up Type=0
Dn Type=3
Dn Slope=0.005
Boundary for River Rch & Prof#=UNT 030 in HW,Reach-1,3
Up Type=0
Dn Type=3
Dn Slope=0.005
Boundary for River Rch & Prof#=UNT 030 in HW,Reach-1,4
Up Type=0
Dn Type=3
Dn Slope=0.005
Boundary for River Rch & Prof#=UNT 030 in HW,Reach-1,5
Up Type=0
Dn Type=3
Dn Slope=0.005
Boundary for River Rch & Prof#=UNT 030 in HW,Reach-1,6
Up Type=0
Dn Type=3
Dn Slope=0.005
Boundary for River Rch & Prof#=UNT 030 in HW,Reach-1,7
Up Type=0
Dn Type=3
Dn Slope=0.005

--- UNT 030 in HW.g01 (geometry) ---

Geom Title=Existing Conditions

River Reach=UNT 030 in HW,Reach-1
Reach XY= 30
      1989185.80     13655359.54      1989110.80     13655324.54
      1988970.80     13655334.54      1988870.80     13655264.54
      1988680.80     13655244.54      1988560.80     13655374.54
      1988350.80     13655374.54      1988320.80     13655254.54
      1988240.80     13655184.54      1987950.80     13655064.54
      1987810.80     13655064.54      1987734.67     13655005.85
      1987733.37     13654678.16      1987598.82     13654414.27
      1987462.97     13654266.26      1987434.32     13654123.04
      1987235.10     13653957.67      1987162.62     13653818.78
      1987100.80     13653244.54      1986960.80     13653064.54
      1986590.80     13652884.54      1986420.80     13652934.54
      1986270.80     13652854.54      1986220.90     13652722.67
      1986099.03     13652574.75      1985990.80     13652614.54
      1985849.55     13652560.69      1985678.71     13652695.58
      1985605.28     13652799.75      1985512.05     13652728.92

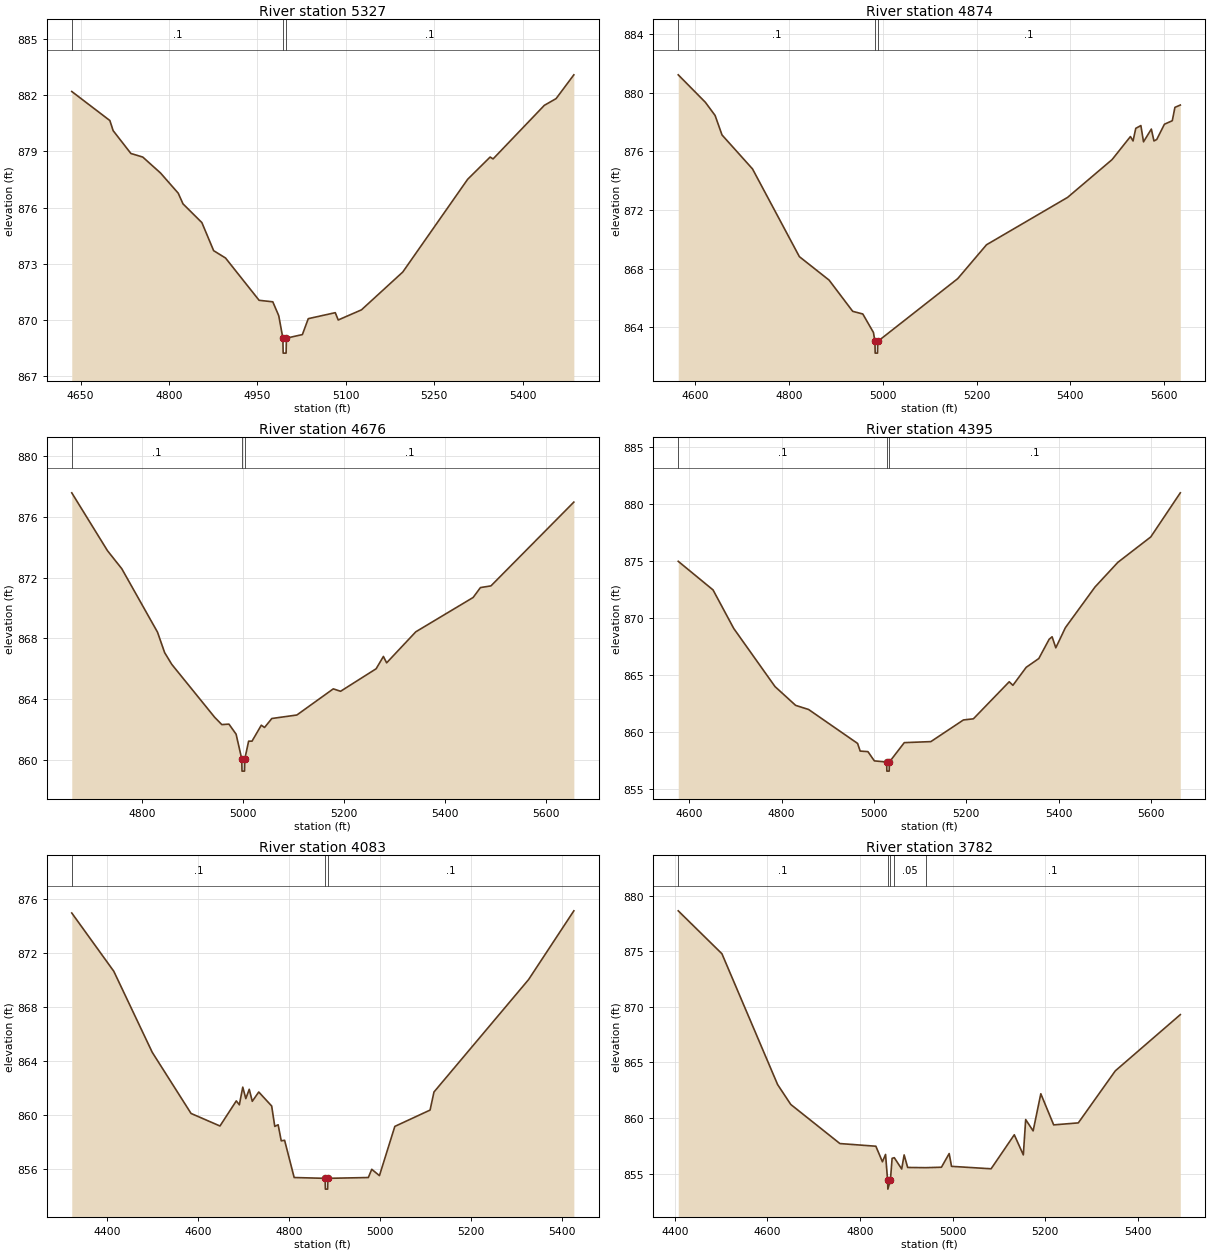
Type RM Length L Ch R = 1,5327,453,453,453
BEGIN DESCRIPTION:
UNT 030 in HW 18.0
END DESCRIPTION:
XS GIS Cut Line= 3
      1988675.00     13654925.00      1988639.18     13655381.62
      1988625.00     13655775.04
#Sta/Elev= 30
  4635.0  882.20  4699.6  880.65  4705.2  880.11  4735.3  878.89  4755.4  878.70
  4785.5  877.85  4815.6  876.77  4823.7  876.20  4855.7  875.20  4875.7  873.70
  4895.8  873.31  4952.8  871.05  4976.0  870.97  4986.1  870.23  4993.1  869.03
  4993.6  868.23  4998.6  868.23  4999.1  869.03  5026.2  869.22  5036.2  870.07
  5082.0  870.39  5087.0  870.00  5126.4  870.54  5196.5  872.56  5306.5  877.51
  5344.7  878.70  5349.7  878.60  5436.6  881.46  5456.6  881.82  5486.7  883.09
#Mann=3,-1,0
  4635.0     0.1       0  4993.1    0.07       0  4999.1     0.1       0
Bank Sta=4993.1,4999.1
Exp/Cntr=0.3,0.1

Type RM Length L Ch R = 1,4874,198,198,198
BEGIN DESCRIPTION:
UNT 030 in HW 17.0
END DESCRIPTION:
XS GIS Cut Line= 3
      1988575.02     13654924.97      1988272.00     13655347.76
      1988024.62     13655839.92
#Sta/Elev= 30
  4563.6  881.22  4621.4  879.35  4642.2  878.45  4657.0  877.12  4722.1  874.80
  4822.0  868.82  4885.4  867.22  4935.8  865.09  4957.3  864.91  4980.0  863.65
  4983.2  863.04  4983.7  862.24  4988.7  862.24  4989.2  863.04  5159.8  867.32
  5221.2  869.63  5394.1  872.86  5489.1  875.44  5528.2  877.01  5533.8  876.71
  5539.6  877.57  5550.5  877.76  5556.1  876.65  5572.8  877.52  5578.4  876.71
  5584.3  876.81  5600.7  877.85  5617.5  878.09  5623.1  879.00  5634.6  879.16
#Mann=3,-1,0
  4563.6     0.1       0  4983.2    0.07       0  4989.2     0.1       0
Bank Sta=4983.2,4989.2
Exp/Cntr=0.3,0.1

Type RM Length L Ch R = 1,4676,281,281,281
BEGIN DESCRIPTION:
UNT 030 in HW 16.0
END DESCRIPTION:
XS GIS Cut Line= 3
      1988425.03     13654924.97      1988175.00     13655175.00
      1987775.01     13655674.99
#Sta/Elev= 30
  4661.2  877.57  4732.0  873.76  4760.2  872.58  4830.9  868.41  4845.1  867.06
  4859.2  866.29  4944.1  862.81  4958.2  862.33  4972.4  862.36  4986.5  861.70
  4997.7  860.07  4998.2  859.27  5003.2  859.27  5003.7  860.07  5011.3  861.24
  5018.0  861.24  5036.4  862.29  5042.8  862.14  5057.2  862.73  5106.8  862.96
  5178.9  864.68  5193.3  864.52  5263.7  866.00  5278.1  866.81  5284.5  866.39
  5342.2  868.43  5455.8  870.69  5470.2  871.34  5491.0  871.45  5655.1  876.96
#Mann=3,-1,0
  4661.2     0.1       0  4997.7    0.07       0  5003.7     0.1       0
Bank Sta=4997.7,5003.7
Exp/Cntr=0.3,0.1

Type RM Length L Ch R = 1,4395,312,312,312
BEGIN DESCRIPTION:
UNT 030 in HW 15.0
END DESCRIPTION:
XS GIS Cut Line= 3
      1988324.98     13654875.01      1987925.00     13655075.00
      1987425.01     13655475.00
#Sta/Elev= 30
  4576.2  874.94  4651.6  872.43  4696.4  869.05  4785.8  863.95  4830.5  862.30
  4858.5  861.94  4964.7  858.96  4970.3  858.29  4987.1  858.24  5001.0  857.43
  5027.6  857.33  5028.1  856.53  5033.1  856.53  5033.6  857.33  5065.8  859.03
  5123.4  859.12  5193.9  861.02  5215.5  861.12  5293.1  864.37  5301.1  864.06
  5329.9  865.64  5357.2  866.41  5379.6  868.10  5386.0  868.32  5394.0  867.35
  5414.8  869.12  5478.8  872.68  5528.4  874.85  5599.7  877.08  5663.7  880.95
#Mann=3,-1,0
  4576.2     0.1       0  5027.6    0.07       0  5033.6     0.1       0
Bank Sta=5027.6,5033.6
Exp/Cntr=0.3,0.1

Type RM Length L Ch R = 1,4083,301,301,301
BEGIN DESCRIPTION:
UNT 030 in HW 14.0
END DESCRIPTION:
XS GIS Cut Line= 3
      1988175.02     13654424.98      1987725.00     13654925.00
      1987375.02     13655174.99
#Sta/Elev= 30
  4322.9  874.97  4415.2  870.65  4499.7  864.64  4584.9  860.11  4648.4  859.18
  4684.3  861.04  4691.0  860.75  4698.5  862.06  4705.2  861.21  4712.7  861.90
  4719.4  861.01  4733.6  861.70  4762.0  860.66  4768.8  859.15  4776.2  859.27
  4783.0  858.08  4790.4  858.12  4811.4  855.36  4879.4  855.30  4879.9  854.50
  4884.9  854.50  4885.4  855.30  4974.3  855.36  4981.8  855.97  4998.7  855.50
  5032.5  859.15  5109.9  860.36  5118.5  861.70  5326.2  870.03  5425.7  875.13
#Mann=3,-1,0
  4322.9     0.1       0  4879.4    0.07       0  4885.4     0.1       0
Bank Sta=4879.4,4885.4
Exp/Cntr=0.3,0.1

Type RM Length L Ch R = 1,3782,34,34,34
BEGIN DESCRIPTION:
Mapping XS f00cc2d6
END DESCRIPTION:
XS GIS Cut Line= 6
      1988178.22     13654345.19      1987824.08     13654662.87
      1987755.07     13654642.03      1987701.68     13654643.34
      1987679.55     13654796.98      1987388.96     13654946.17
#Sta/Elev= 30
  4407.4  878.64  4501.8  874.78  4622.1  863.01  4650.5  861.22  4756.7  857.70
  4834.4  857.46  4848.6  856.06  4855.3  856.72  4859.8  854.40  4860.3  853.60
  4865.8  854.40  4869.5  856.37  4874.2  856.43  4890.2  855.41  4895.5  856.68
  4903.1  855.55  4942.0  855.53  4976.1  855.57  4992.8  856.80  4997.9  855.65
  5083.4  855.43  5133.5  858.49  5153.0  856.68  5158.1  859.86  5174.2  858.84
  5190.8  862.18  5218.6  859.38  5271.8  859.56  5351.7  864.24  5492.2  869.30
#Mann=5,-1,0
  4407.4     0.1       0  4859.8    0.07       0  4865.8     0.1       0
  4874.2    0.05       0  4942.0     0.1       0
Bank Sta=4859.8,4865.8
Exp/Cntr=0.3,0.1

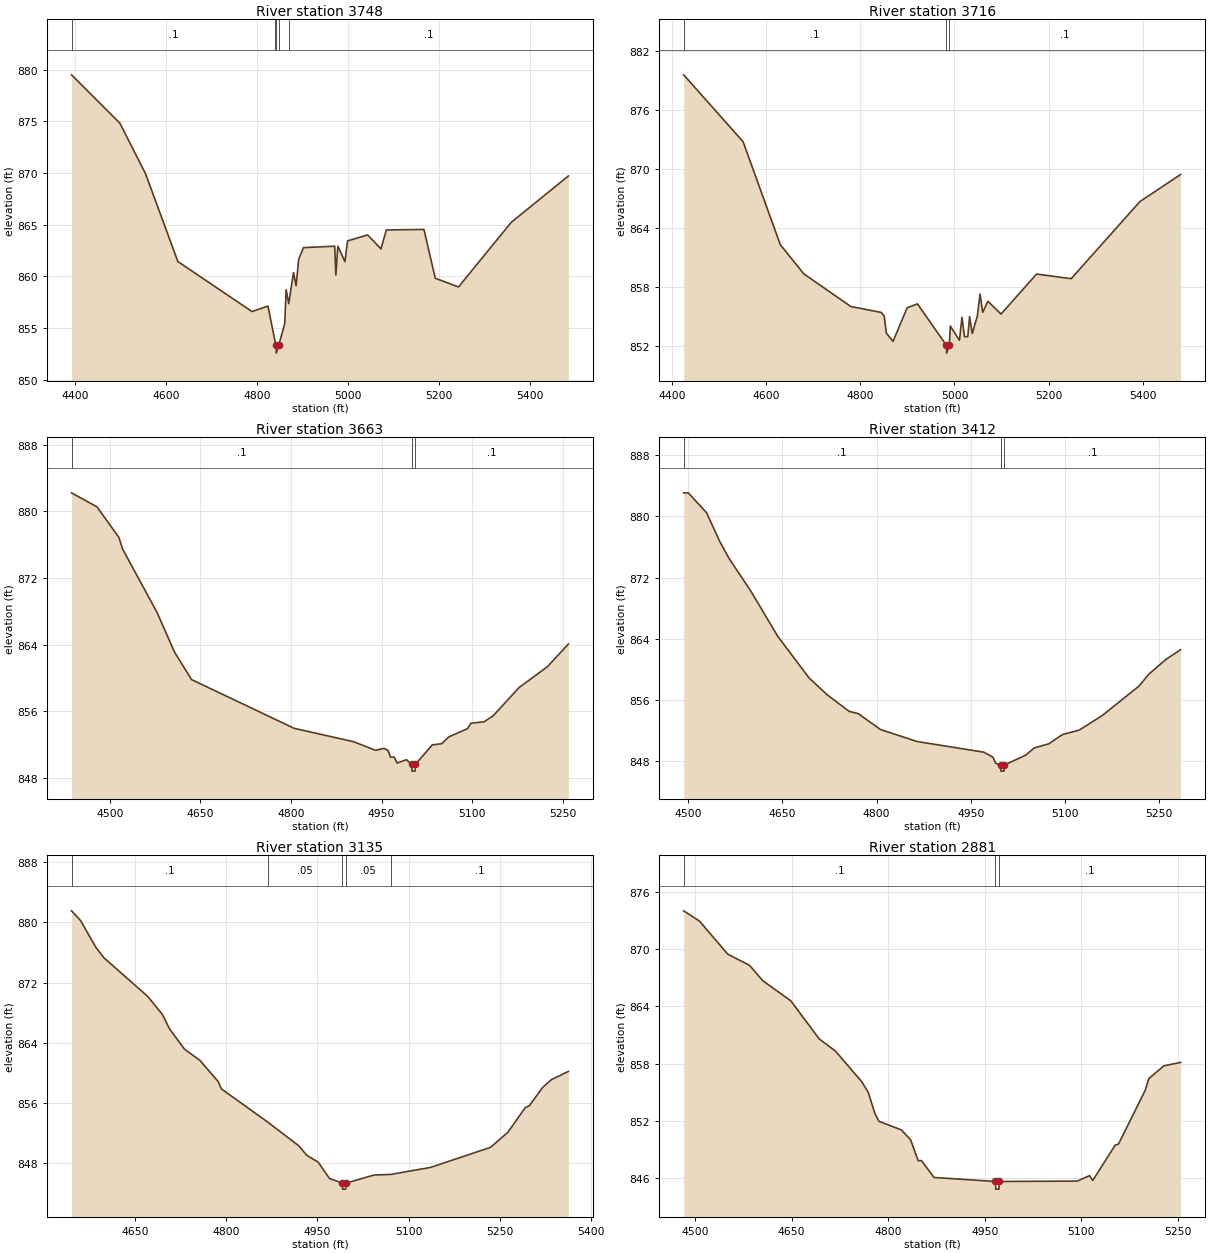
Type RM Length L Ch R = 1,3748,32,32,32
BEGIN DESCRIPTION:
UNT 030 in HW 13.0
END DESCRIPTION:
XS GIS Cut Line= 6
      1988175.03     13654324.97      1987824.08     13654632.92
      1987715.09     13654599.72      1987676.94     13654622.50
      1987651.04     13654767.27      1987375.02     13654924.99
#Sta/Elev= 30
  4392.0  879.50  4498.5  874.82  4554.8  869.95  4626.0  861.45  4789.2  856.61
  4824.3  857.14  4839.9  853.74  4842.2  853.39  4842.7  852.59  4848.2  853.39
  4861.2  855.43  4864.3  858.73  4870.0  857.38  4880.5  860.38  4886.2  859.11
  4892.0  861.67  4902.4  862.79  4971.2  862.93  4973.7  860.14  4978.1  862.93
  4993.7  861.44  4999.5  863.44  5043.6  864.02  5073.0  862.67  5084.8  864.50
  5167.6  864.55  5192.5  859.83  5243.7  858.99  5359.5  865.23  5485.5  869.72
#Mann=5,-1,0
  4392.0     0.1       0  4839.9    0.05       0  4842.2    0.07       0
  4848.2    0.05       0  4870.0     0.1       0
Bank Sta=4842.2,4848.2
Exp/Cntr=0.3,0.1

Type RM Length L Ch R = 1,3716,53,53,53
BEGIN DESCRIPTION:
Mapping XS 86049a15
END DESCRIPTION:
XS GIS Cut Line= 6
      1988162.60     13654315.23      1987817.57     13654575.63
      1987653.51     13654593.86      1987618.35     13654662.87
      1987613.14     13654764.43      1987373.60     13654902.43
#Sta/Elev= 30
  4424.6  879.62  4550.9  872.80  4630.0  862.30  4680.0  859.33  4779.9  856.00
  4844.4  855.40  4850.7  855.04  4855.3  853.29  4869.5  852.45  4899.5  855.87
  4921.4  856.27  4982.9  852.05  4983.4  851.25  4988.9  852.05  4991.3  854.01
  5010.7  852.56  5016.0  854.90  5021.4  852.93  5028.3  852.93  5032.2  854.98
  5037.8  853.25  5048.6  855.03  5054.4  857.27  5060.1  855.41  5071.1  856.54
  5098.9  855.23  5174.6  859.31  5248.1  858.84  5393.9  866.69  5480.5  869.46
#Mann=3,-1,0
  4424.6     0.1       0  4982.9    0.07       0  4988.9     0.1       0
Bank Sta=4982.9,4988.9
Exp/Cntr=0.3,0.1

Type RM Length L Ch R = 1,3663,251,251,251
BEGIN DESCRIPTION:
UNT 030 in HW 12.0
END DESCRIPTION:
XS GIS Cut Line= 3
      1988074.97     13654175.03      1987675.00     13654525.00
      1987425.01     13654674.99
#Sta/Elev= 30
  4436.5  882.23  4478.7  880.55  4514.8  876.90  4521.4  875.44  4578.4  867.84
  4606.8  863.15  4635.3  859.81  4805.2  853.96  4903.9  852.35  4940.0  851.32
  4954.2  851.55  4960.8  851.30  4964.6  850.51  4970.9  850.51  4975.7  849.79
  4991.3  850.19  5000.0  849.62  5000.5  848.82  5005.5  848.82  5006.0  849.62
  5034.0  851.97  5049.6  852.11  5061.3  852.93  5092.4  853.92  5098.2  854.58
  5119.6  854.73  5135.1  855.48  5177.9  858.86  5224.5  861.34  5259.5  864.08
#Mann=3,-1,0
  4436.5     0.1       0  5000.0    0.07       0  5006.0     0.1       0
Bank Sta=5000,5006
Exp/Cntr=0.3,0.1

Type RM Length L Ch R = 1,3412,277,277,277
BEGIN DESCRIPTION:
UNT 030 in HW 11.0
END DESCRIPTION:
XS GIS Cut Line= 3
      1987924.99     13654025.01      1987525.00     13654325.00
      1987375.01     13654574.98
#Sta/Elev= 30
  4492.7  883.07  4500.0  883.08  4529.1  880.49  4550.0  876.75  4564.6  874.55
  4600.0  870.19  4642.7  864.30  4692.7  858.85  4720.8  856.71  4756.2  854.51
  4770.8  854.21  4806.2  852.13  4864.6  850.56  4970.8  849.17  4985.4  848.51
  4989.6  847.72  4997.5  847.49  4998.0  846.69  5003.0  846.69  5003.5  847.49
  5037.4  848.77  5051.0  849.72  5074.3  850.26  5095.7  851.46  5122.9  852.06
  5159.8  853.98  5218.1  857.82  5233.7  859.37  5260.9  861.30  5284.2  862.57
#Mann=3,-1,0
  4492.7     0.1       0  4997.5    0.07       0  5003.5     0.1       0
Bank Sta=4997.5,5003.5
Exp/Cntr=0.3,0.1

Type RM Length L Ch R = 1,3135,254,254,254
BEGIN DESCRIPTION:
UNT 030 in HW 10.0
END DESCRIPTION:
XS GIS Cut Line= 3
      1987825.01     13653925.00      1987425.00     13654075.00
      1987125.02     13654324.98
#Sta/Elev= 30
  4545.3  881.55  4560.4  880.24  4585.4  876.69  4598.7  875.31  4670.8  870.17
  4694.8  867.79  4706.4  865.89  4731.3  863.16  4756.2  861.71  4786.5  858.88
  4791.8  857.90  4868.0  853.49  4919.1  850.34  4932.5  849.06  4951.2  848.16
  4969.8  845.99  4991.0  845.37  4991.5  844.57  4996.5  844.57  4997.0  845.37
  5043.5  846.45  5070.3  846.52  5135.9  847.45  5234.8  850.12  5263.4  852.12
  5292.1  855.41  5298.6  855.65  5320.7  858.09  5335.0  859.12  5363.0  860.21
#Mann=5,-1,0
  4545.3     0.1       0  4868.0    0.05       0  4991.0   0.033       0
  4997.0    0.05       0  5070.3     0.1       0
Bank Sta=4991,4997
Exp/Cntr=0.3,0.1

Type RM Length L Ch R = 1,2881,62,62,62
BEGIN DESCRIPTION:
UNT 030 in HW 9.0
END DESCRIPTION:
XS GIS Cut Line= 4
      1987725.02     13653825.00      1987368.79     13653902.80
      1987082.33     13653942.73      1986974.65     13653989.62
#Sta/Elev= 30
  4482.6  873.99  4507.1  872.92  4551.0  869.46  4585.0  868.28  4605.4  866.68
  4649.1  864.56  4693.0  860.59  4718.0  859.33  4759.0  856.11  4769.2  854.99
  4779.5  852.76  4785.9  851.96  4820.4  851.07  4834.9  850.03  4846.6  847.85
  4851.7  847.85  4871.2  846.09  4966.5  845.67  4967.0  844.87  4972.0  844.87
  4972.5  845.67  5093.4  845.71  5112.6  846.28  5117.6  845.78  5152.3  849.46
  5157.7  849.60  5199.0  855.21  5204.6  856.44  5228.0  857.77  5253.9  858.13
#Mann=3,-1,0
  4482.6     0.1       0  4966.5    0.07       0  4972.5     0.1       0
Bank Sta=4966.5,4972.5
Exp/Cntr=0.3,0.1

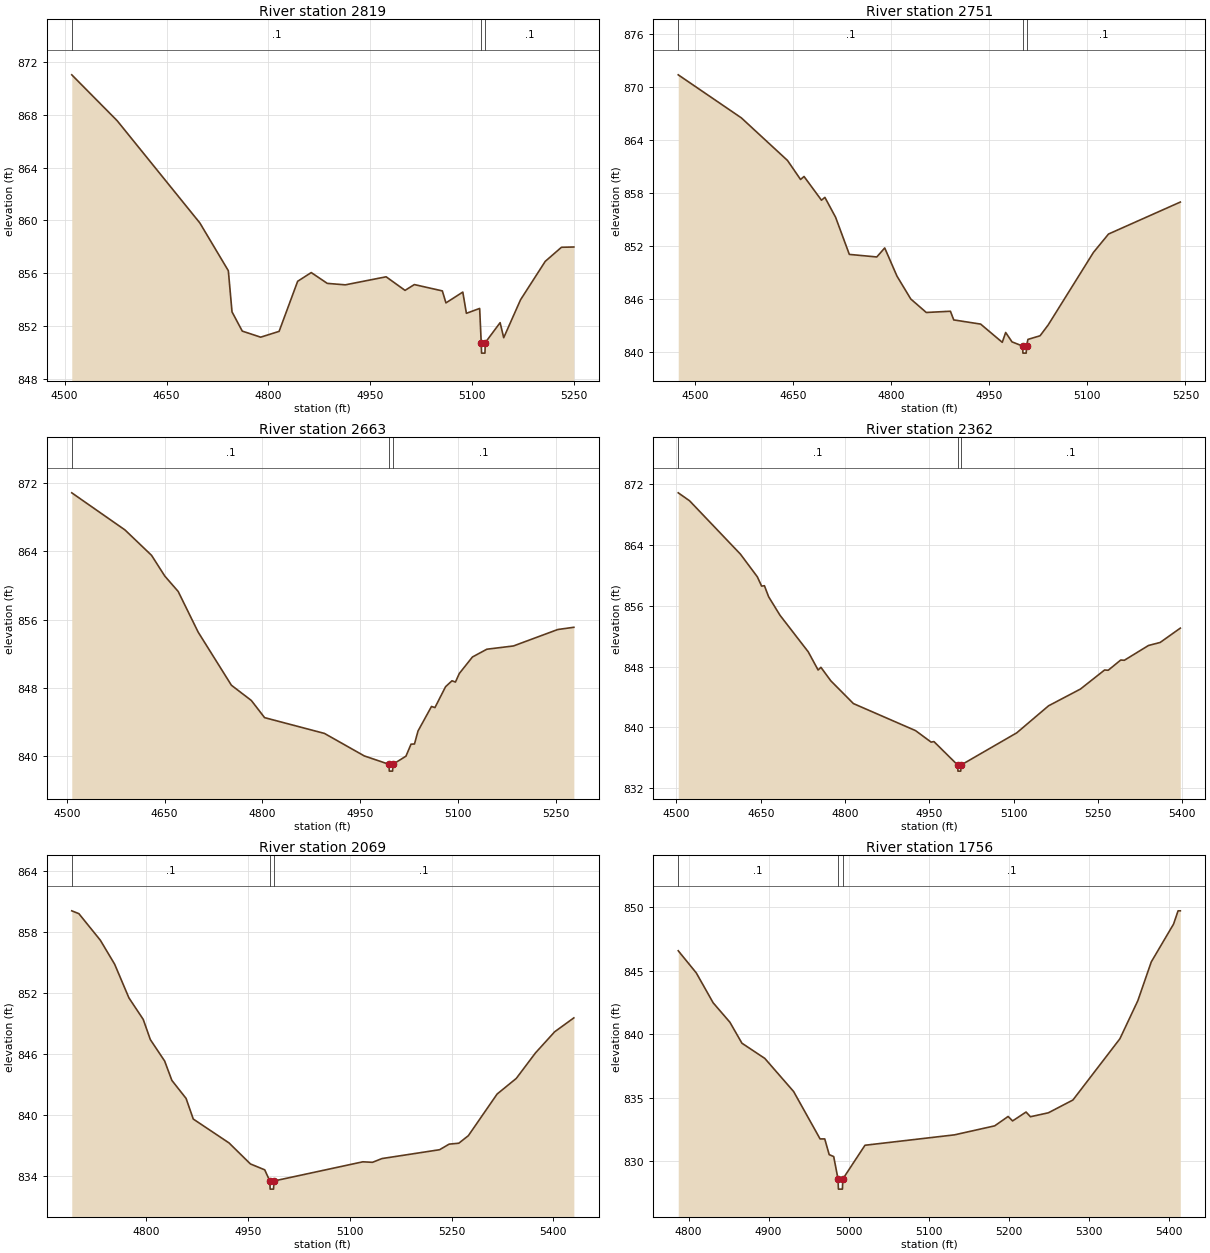
Type RM Length L Ch R = 1,2819,68,68,68
BEGIN DESCRIPTION:
Mapping XS 5b9aeae2
END DESCRIPTION:
XS GIS Cut Line= 4
      1987669.15     13653785.61      1987372.26     13653855.92
      1987195.17     13653866.34      1986955.62     13653957.47
#Sta/Elev= 30
  4510.6  871.04  4577.4  867.56  4699.0  859.81  4741.0  856.18  4746.4  853.06
  4761.5  851.60  4788.6  851.14  4815.7  851.58  4843.0  855.38  4863.0  856.04
  4886.6  855.22  4913.1  855.11  4973.2  855.72  5001.0  854.69  5014.7  855.13
  5055.9  854.65  5061.2  853.74  5086.0  854.56  5091.3  852.95  5110.8  853.32
  5113.1  850.73  5113.6  849.93  5118.6  849.93  5119.1  850.73  5140.9  852.24
  5146.2  851.10  5171.0  853.98  5207.3  856.89  5231.2  857.96  5249.4  857.98
#Mann=3,-1,0
  4510.6     0.1       0  5113.1    0.07       0  5119.1     0.1       0
Bank Sta=5113.1,5119.1
Exp/Cntr=0.3,0.1

Type RM Length L Ch R = 1,2751,88,88,88
BEGIN DESCRIPTION:
Mapping XS 22287838
END DESCRIPTION:
XS GIS Cut Line= 6
      1987663.91     13653730.93      1987367.05     13653827.28
      1987291.53     13653806.44      1987221.22     13653790.82
      1987137.88     13653814.26      1986938.64     13653904.82
#Sta/Elev= 30
  4474.3  871.34  4570.8  866.48  4641.4  861.67  4661.4  859.52  4666.7  859.86
  4693.4  857.18  4698.6  857.50  4715.0  855.25  4736.0  851.06  4778.0  850.77
  4790.1  851.79  4808.9  848.60  4830.0  846.02  4853.7  844.50  4890.6  844.64
  4895.7  843.66  4936.8  843.19  4969.9  841.13  4975.1  842.24  4984.8  841.18
  5001.0  840.71  5001.5  839.91  5006.5  839.91  5007.0  840.71  5009.2  841.46
  5027.7  841.87  5040.1  843.09  5109.3  851.28  5132.4  853.36  5242.2  856.97
#Mann=3,-1,0
  4474.3     0.1       0  5001.0    0.07       0  5007.0     0.1       0
Bank Sta=5001,5007
Exp/Cntr=0.3,0.1

Type RM Length L Ch R = 1,2663,301,301,301
BEGIN DESCRIPTION:
UNT 030 in HW 8.0
END DESCRIPTION:
XS GIS Cut Line= 3
      1987625.01     13653625.00      1987125.00     13653725.00
      1986878.72     13653808.62
#Sta/Elev= 30
  4507.7  870.85  4589.3  866.50  4630.1  863.52  4650.5  861.08  4670.9  859.29
  4701.5  854.53  4752.5  848.30  4783.1  846.51  4803.4  844.50  4895.2  842.65
  4956.4  840.01  4994.2  839.03  4994.7  838.23  4999.7  838.23  5000.2  839.03
  5020.2  839.98  5028.0  841.39  5033.3  841.41  5038.7  842.93  5059.4  845.81
  5064.7  845.68  5081.0  848.13  5090.8  848.82  5096.1  848.67  5102.1  849.68
  5122.2  851.61  5144.3  852.52  5185.0  852.90  5253.1  854.83  5277.7  855.09
#Mann=3,-1,0
  4507.7     0.1       0  4994.2    0.07       0  5000.2     0.1       0
Bank Sta=4994.2,5000.2
Exp/Cntr=0.3,0.1

Type RM Length L Ch R = 1,2362,293,293,293
BEGIN DESCRIPTION:
UNT 030 in HW 7.0
END DESCRIPTION:
XS GIS Cut Line= 3
      1987625.03     13653475.00      1987125.00     13653425.00
      1986875.03     13653724.97
#Sta/Elev= 30
  4503.3  870.81  4523.4  869.77  4613.9  862.76  4644.0  859.78  4651.6  858.56
  4656.6  858.61  4664.1  857.16  4684.2  854.74  4734.5  849.93  4752.1  847.54
  4757.1  847.89  4774.7  846.12  4814.9  843.13  4925.4  839.58  4953.1  838.07
  4958.1  838.14  5000.3  835.06  5000.8  834.26  5005.8  834.26  5006.3  835.06
  5105.4  839.29  5162.0  842.84  5218.7  845.04  5261.6  847.54  5268.1  847.51
  5290.3  848.85  5296.8  848.82  5339.7  850.76  5360.5  851.16  5396.3  853.04
#Mann=3,-1,0
  4503.3     0.1       0  5000.3    0.07       0  5006.3     0.1       0
Bank Sta=5000.3,5006.3
Exp/Cntr=0.3,0.1

Type RM Length L Ch R = 1,2069,313,313,313
BEGIN DESCRIPTION:
UNT 030 in HW 6.0
END DESCRIPTION:
XS GIS Cut Line= 3
      1987324.99     13653075.00      1987025.00     13653175.00
      1986724.98     13653475.02
#Sta/Elev= 30
  4689.9  860.10  4700.4  859.82  4732.0  857.21  4753.1  854.85  4774.2  851.53
  4795.3  849.41  4805.8  847.42  4826.9  845.31  4837.5  843.41  4858.5  841.63
  4869.1  839.60  4921.8  837.25  4953.4  835.18  4974.5  834.60  4982.0  833.50
  4982.5  832.70  4987.5  832.70  4988.0  833.50  5119.2  835.39  5133.4  835.34
  5147.5  835.71  5232.4  836.58  5246.5  837.13  5260.7  837.22  5274.8  837.96
  5317.2  842.06  5345.5  843.60  5373.8  846.11  5402.1  848.19  5430.4  849.56
#Mann=3,-1,0
  4689.9     0.1       0  4982.0    0.07       0  4988.0     0.1       0
Bank Sta=4982,4988
Exp/Cntr=0.3,0.1

Type RM Length L Ch R = 1,1756,286,286,286
BEGIN DESCRIPTION:
UNT 030 in HW 5.0
END DESCRIPTION:
XS GIS Cut Line= 3
      1986975.02     13652874.99      1986825.00     13652975.00
      1986625.01     13653374.99
#Sta/Elev= 30
  4787.1  846.58  4809.7  844.83  4830.7  842.48  4851.7  840.94  4866.7  839.29
  4895.3  838.09  4931.3  835.48  4964.4  831.74  4970.2  831.74  4975.8  830.50
  4981.4  830.35  4986.8  828.58  4987.3  827.78  4992.3  827.78  4992.8  828.58
  5020.5  831.24  5132.3  832.06  5182.6  832.77  5199.4  833.51  5205.0  833.16
  5221.8  833.86  5227.3  833.49  5249.7  833.80  5280.4  834.81  5339.1  839.64
  5361.5  842.64  5378.3  845.70  5406.2  848.69  5411.8  849.73  5414.6  849.73
#Mann=3,-1,0
  4787.1     0.1       0  4986.8    0.07       0  4992.8     0.1       0
Bank Sta=4986.8,4992.8
Exp/Cntr=0.3,0.1

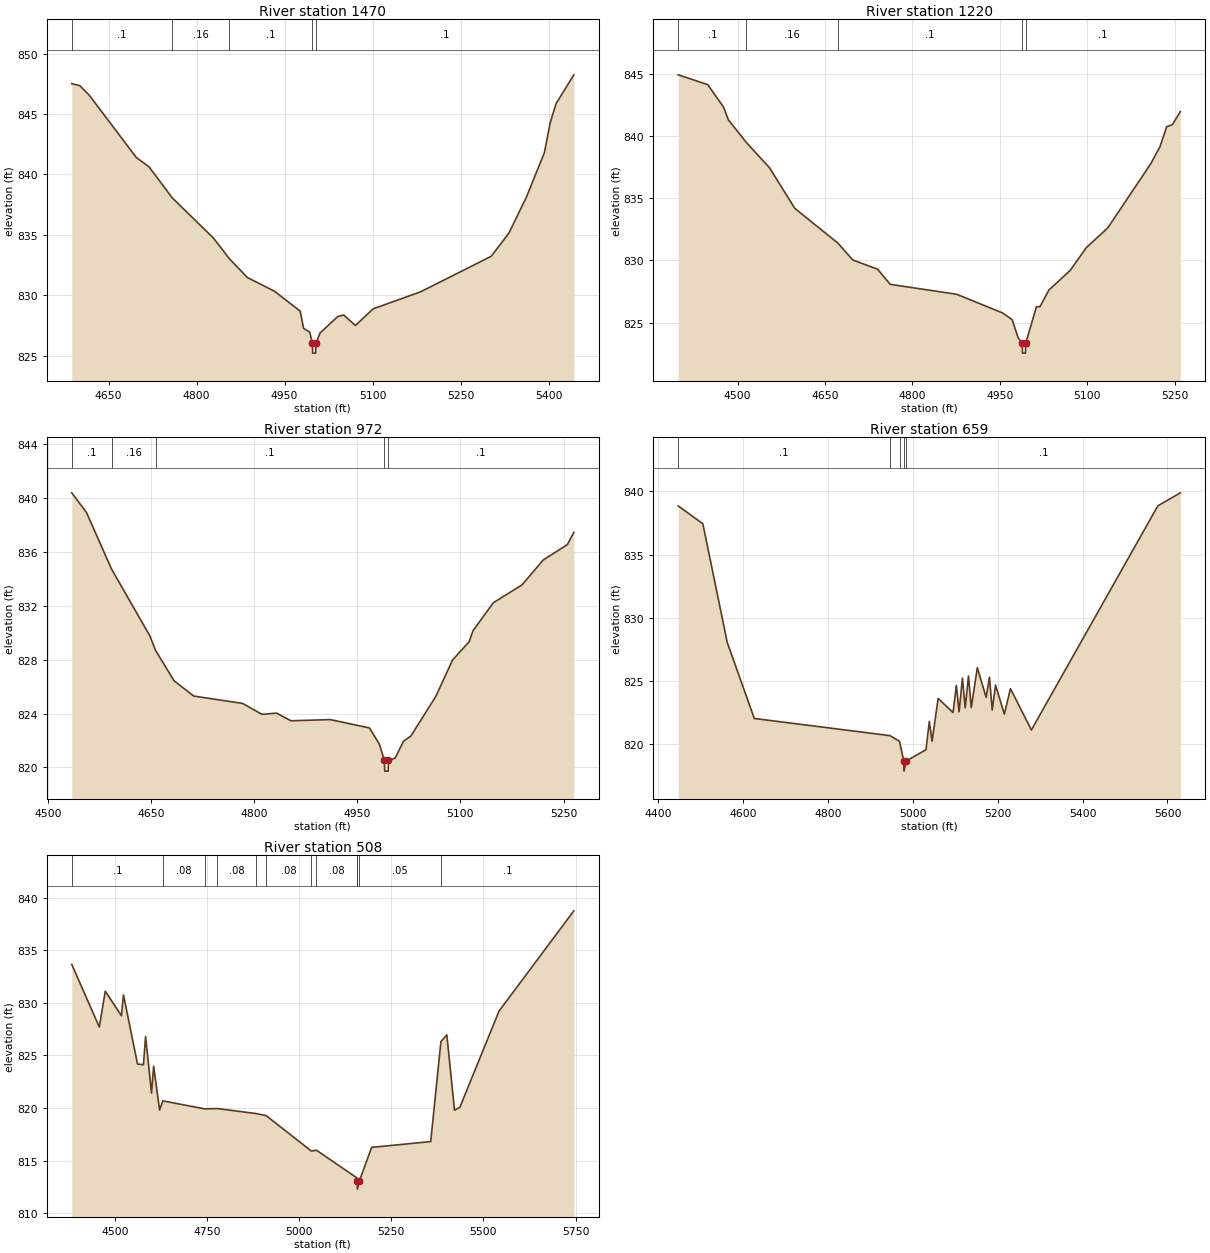
Type RM Length L Ch R = 1,1470,250,250,250
BEGIN DESCRIPTION:
UNT 030 in HW 4.0
END DESCRIPTION:
XS GIS Cut Line= 3
      1986924.99     13652675.00      1986575.00     13652875.00
      1986525.00     13653325.03
#Sta/Elev= 30
  4587.3  847.52  4601.0  847.35  4616.8  846.58  4697.4  841.40  4719.0  840.63
  4758.6  838.06  4829.2  834.71  4855.8  833.03  4886.7  831.46  4932.8  830.33
  4976.7  828.68  4982.5  827.25  4992.9  826.94  4997.5  826.00  4998.0  825.20
  5003.0  825.20  5003.5  826.00  5010.5  826.86  5040.7  828.23  5050.8  828.36
  5070.9  827.49  5101.1  828.87  5181.6  830.27  5302.3  833.22  5332.5  835.14
  5362.7  838.16  5392.9  841.79  5402.9  844.28  5413.0  845.87  5443.2  848.25
#Mann=5,-1,0
  4587.3     0.1       0  4758.6    0.16       0  4855.8     0.1       0
  4997.5    0.07       0  5003.5     0.1       0
Bank Sta=4997.5,5003.5
Exp/Cntr=0.3,0.1

Type RM Length L Ch R = 1,1220,248,248,248
BEGIN DESCRIPTION:
UNT 030 in HW 3.0
END DESCRIPTION:
XS GIS Cut Line= 3
      1986825.03     13652524.98      1986375.00     13652875.00
      1986224.98     13653125.03
#Sta/Elev= 30
  4398.0  844.95  4448.7  844.16  4475.9  842.34  4484.0  841.33  4515.0  839.50
  4554.6  837.47  4598.0  834.20  4672.0  831.40  4697.6  830.04  4740.1  829.30
  4761.8  828.08  4875.8  827.28  4954.5  825.78  4971.0  825.24  4981.7  823.74
  4988.4  823.34  4988.9  822.54  4993.9  822.54  4994.4  823.34  5012.8  826.28
  5018.7  826.27  5034.2  827.62  5071.1  829.22  5098.3  831.03  5135.3  832.63
  5209.1  837.80  5224.7  839.15  5236.3  840.77  5246.1  840.94  5259.7  841.99
#Mann=5,-1,0
  4398.0     0.1       0  4515.0    0.16       0  4672.0     0.1       0
  4988.4    0.07       0  4994.4     0.1       0
Bank Sta=4988.4,4994.4
Exp/Cntr=0.3,0.1

Type RM Length L Ch R = 1,972,313,313,313
BEGIN DESCRIPTION:
UNT 030 in HW 2.0
END DESCRIPTION:
XS GIS Cut Line= 3
      1986525.01     13652374.99      1986225.00     13652725.00
      1986124.98     13652975.04
#Sta/Elev= 30
  4534.7  840.40  4556.1  838.94  4592.6  834.73  4648.3  829.77  4656.5  828.70
  4683.4  826.44  4712.0  825.30  4783.3  824.75  4811.3  823.94  4832.7  824.03
  4853.6  823.46  4910.6  823.55  4967.7  822.93  4982.0  821.74  4989.4  820.52
  4989.9  819.72  4994.9  819.72  4995.4  820.52  5005.1  820.69  5017.2  821.94
  5028.0  822.33  5064.4  825.29  5088.6  827.98  5112.8  829.34  5118.2  830.14
  5147.8  832.23  5189.6  833.56  5220.5  835.41  5255.5  836.55  5265.0  837.46
#Mann=5,-1,0
  4534.7     0.1       0  4592.6    0.16       0  4656.5     0.1       0
  4989.4    0.07       0  4995.4     0.1       0
Bank Sta=4989.4,4995.4
Exp/Cntr=0.3,0.1

Type RM Length L Ch R = 1,659,151,151,151
BEGIN DESCRIPTION:
Mapping XS 44267f56
END DESCRIPTION:
XS GIS Cut Line= 4
      1986398.32     13652236.11      1986137.88     13652449.67
      1985812.36     13652835.09      1985976.44     13653134.60
#Sta/Elev= 30
  4447.4  838.85  4505.4  837.44  4562.8  828.05  4626.6  822.02  4946.4  820.66
  4968.7  820.21  4978.7  818.65  4979.2  817.85  4984.7  818.65  5031.1  819.55
  5038.9  821.79  5045.4  820.22  5059.7  823.61  5094.8  822.49  5102.6  824.64
  5109.1  822.55  5116.9  825.22  5123.4  822.87  5131.2  825.38  5137.7  822.88
  5152.0  826.04  5172.8  823.69  5180.6  825.29  5187.1  822.69  5194.9  824.66
  5215.7  822.36  5230.0  824.38  5279.4  821.11  5577.3  838.86  5630.2  839.89
#Mann=5,-1,0
  4447.4     0.1       0  4946.4    0.05       0  4968.7     0.1       0
  4978.7    0.07       0  4984.7     0.1       0
Bank Sta=4978.7,4984.7
Exp/Cntr=0.3,0.1

Type RM Length L Ch R = 1,508,0,0,0
BEGIN DESCRIPTION:
UNT 030 in HW 1.0
END DESCRIPTION:
XS GIS Cut Line= 4
      1986356.61     13652204.89      1985986.84     13652405.40
      1985687.36     13652783.01      1985962.65     13653150.93
#Sta/Elev= 30
  4383.3  833.66  4458.0  827.70  4474.2  831.11  4517.9  828.78  4523.6  830.76
  4561.7  824.18  4577.8  824.12  4583.5  826.80  4599.7  821.43  4605.4  823.98
  4621.6  819.81  4630.2  820.68  4744.1  819.92  4778.5  819.95  4882.3  819.48
  4910.6  819.28  5033.3  815.91  5047.2  815.99  5155.9  813.38  5157.8  813.09
  5158.3  812.29  5163.8  813.09  5196.9  816.26  5357.1  816.81  5384.8  826.32
  5400.8  826.96  5421.7  819.79  5436.3  820.08  5542.5  829.22  5745.4  838.75
#Mann=12,-1,0
  4383.3     0.1       0  4630.2    0.08       0  4744.1    0.05       0
  4778.5    0.08       0  4882.3     0.1       0  4910.6    0.08       0
  5033.3    0.05       0  5047.2    0.08       0  5155.9    0.05       0
  5157.8    0.07       0  5163.8    0.05       0  5384.8     0.1       0
Bank Sta=5157.8,5163.8
Exp/Cntr=0.3,0.1

Chan Stop Cuts=-1