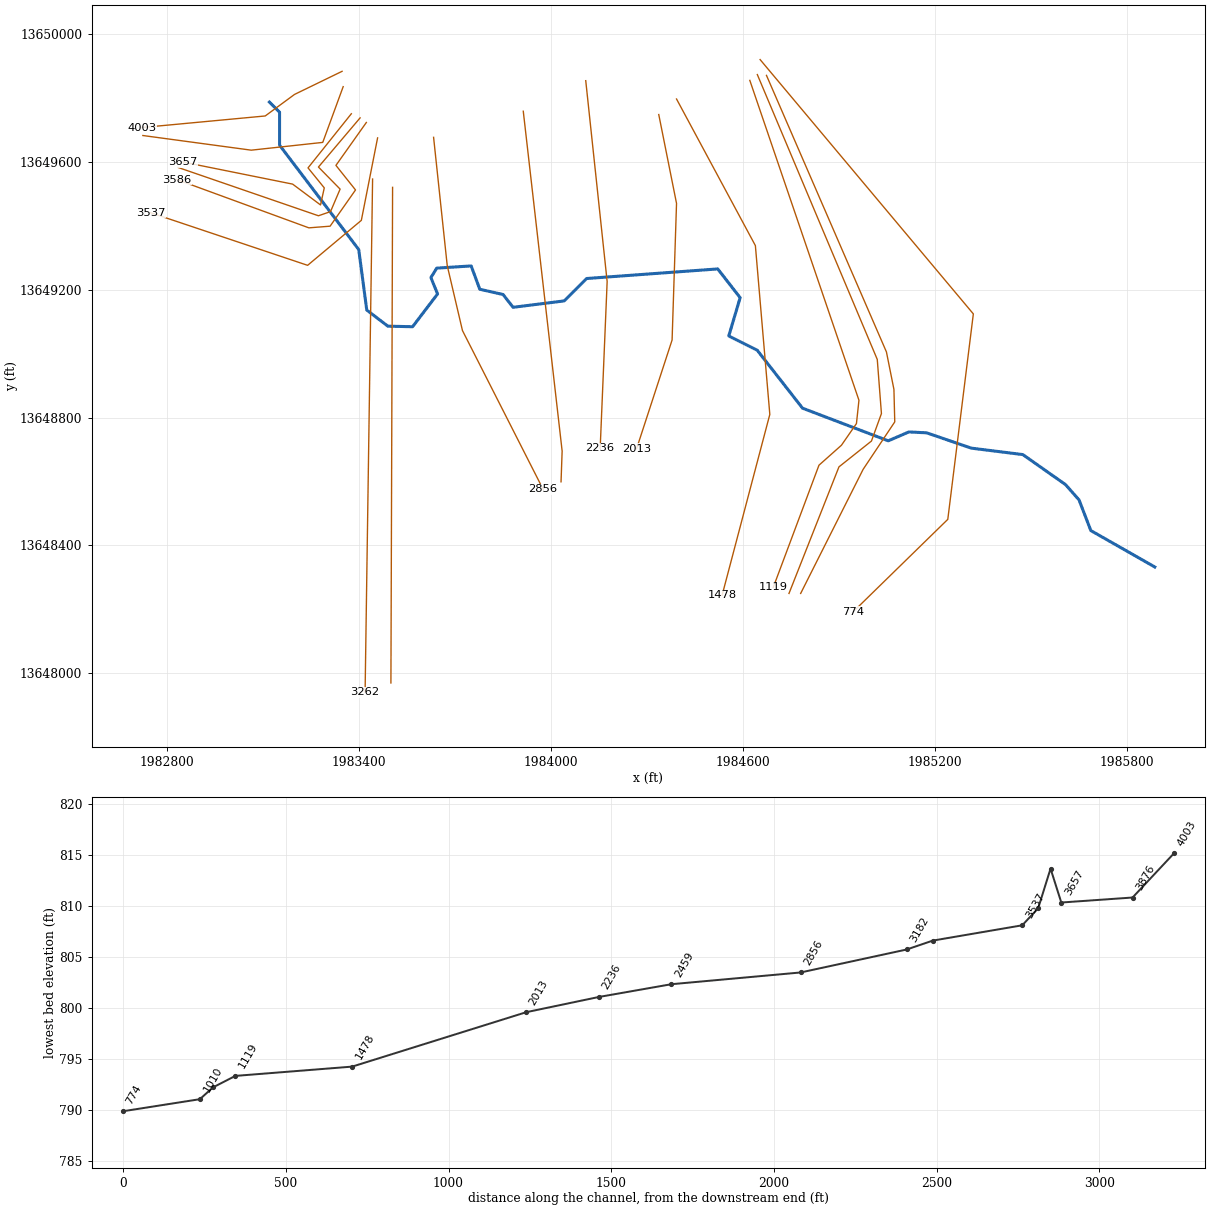
--- UNT 031 in HW.prj (project) ---

Proj Title=UNT 031 in HW Base Level Engineering
Current Plan=p01
Default Exp/Contr=0.3,0.1
English Units
Geom File=g01
Flow File=f01
Plan File=p01
Y Axis Title=Elevation
X Axis Title(PF)=Main Channel Distance
X Axis Title(XS)=Station
BEGIN DESCRIPTION:
UNT 031 in HW
END DESCRIPTION:
DSS Export Rating Curves= 0
DSS Export Rating Curve Sorted= 0
DSS Export Volume Flow Curves= 0
DXF OffsetX= 0
DXF OffsetY= 0
DXF ScaleX= 1
DXF ScaleY= 10

--- UNT 031 in HW.p01 (plan) ---

Plan Title=Multiple Run
Short Identifier=Multiple
Geom File=g01
Flow File=f01
Subcritical Flow
K Sum by GR= 0
Std Step Tol= 0.01
Critical Tol= 0.01
Num of Std Step Trials= 20
Max Error Tol= 0.3
Flow Tol Ratio= 0.001
Split Flow NTrial= 30
Split Flow Tol= 0.02
Split Flow Ratio= 0.02
Log Output Level= 0
Friction Slope Method= 1
Unsteady Friction Slope Method= 2
Unsteady Bridges Friction Slope Method= 1
Parabolic Critical Depth
Global Vel Dist=  1 , 1 , 1
Global Log Level= 0
CheckData=True
Encroach Param= -1, 0, 0, 0
BEGIN DESCRIPTION:
Multiple Run
END DESCRIPTION:

--- UNT 031 in HW.f01 (steady flow) ---

Flow Title=Multiple
Program Version=5.05
Number of Profiles= 7
Profile Names=10-year,25-year,50-year,1pct_min,100-year,1pct_plu,500-year
River Rch & RM=UNT 031 in HW,Reach-1         ,4003
     472     656     808     493     985    1964    1466
River Rch & RM=UNT 031 in HW,Reach-1         ,3262
     692     982    1227     760    1516    3024    2318
River Rch & RM=UNT 031 in HW,Reach-1         ,2459
     692     982    1227     760    1516    3024    2318
Boundary for River Rch & Prof#=UNT 031 in HW,Reach-1         , 1
Up Type= 0
Dn Type= 3
Dn Slope=0.005
Boundary for River Rch & Prof#=UNT 031 in HW,Reach-1         , 2
Up Type= 0
Dn Type= 3
Dn Slope=0.005
Boundary for River Rch & Prof#=UNT 031 in HW,Reach-1         , 3
Up Type= 0
Dn Type= 3
Dn Slope=0.005
Boundary for River Rch & Prof#=UNT 031 in HW,Reach-1         , 4
Up Type= 0
Dn Type= 3
Dn Slope=0.005
Boundary for River Rch & Prof#=UNT 031 in HW,Reach-1         , 5
Up Type= 0
Dn Type= 3
Dn Slope=0.005
Boundary for River Rch & Prof#=UNT 031 in HW,Reach-1         , 6
Up Type= 0
Dn Type= 3
Dn Slope=0.005
Boundary for River Rch & Prof#=UNT 031 in HW,Reach-1         , 7
Up Type= 0
Dn Type= 3
Dn Slope=0.005
DSS Import GetInterval= 0
DSS Import GetPeak= 0
DSS Import FillOption= 0

--- UNT 031 in HW.g01 (geometry) ---

Geom Title=Existing Conditions

River Reach=UNT 031 in HW,Reach-1
Reach XY= 30
      1983119.07     13649786.26      1983150.80     13649754.54
      1983150.80     13649651.52      1983398.28     13649325.13
      1983423.45     13649135.90      1983489.42     13649085.55
      1983566.68     13649083.81      1983644.80     13649186.24
      1983623.97     13649237.46      1983642.20     13649266.97
      1983749.84     13649273.92      1983776.75     13649201.00
      1983849.67     13649184.51      1983880.80     13649144.54
      1984040.80     13649164.54      1984110.80     13649234.54
      1984520.80     13649264.54      1984590.80     13649174.54
      1984555.22     13649054.88      1984644.11     13649010.44
      1984785.78     13648829.19      1985053.83     13648727.10
      1985118.41     13648754.88      1985173.97     13648752.10
      1985313.55     13648704.19      1985474.66     13648684.05
      1985608.00     13648590.30      1985650.36     13648542.38
      1985687.16     13648446.55      1985887.16     13648332.66

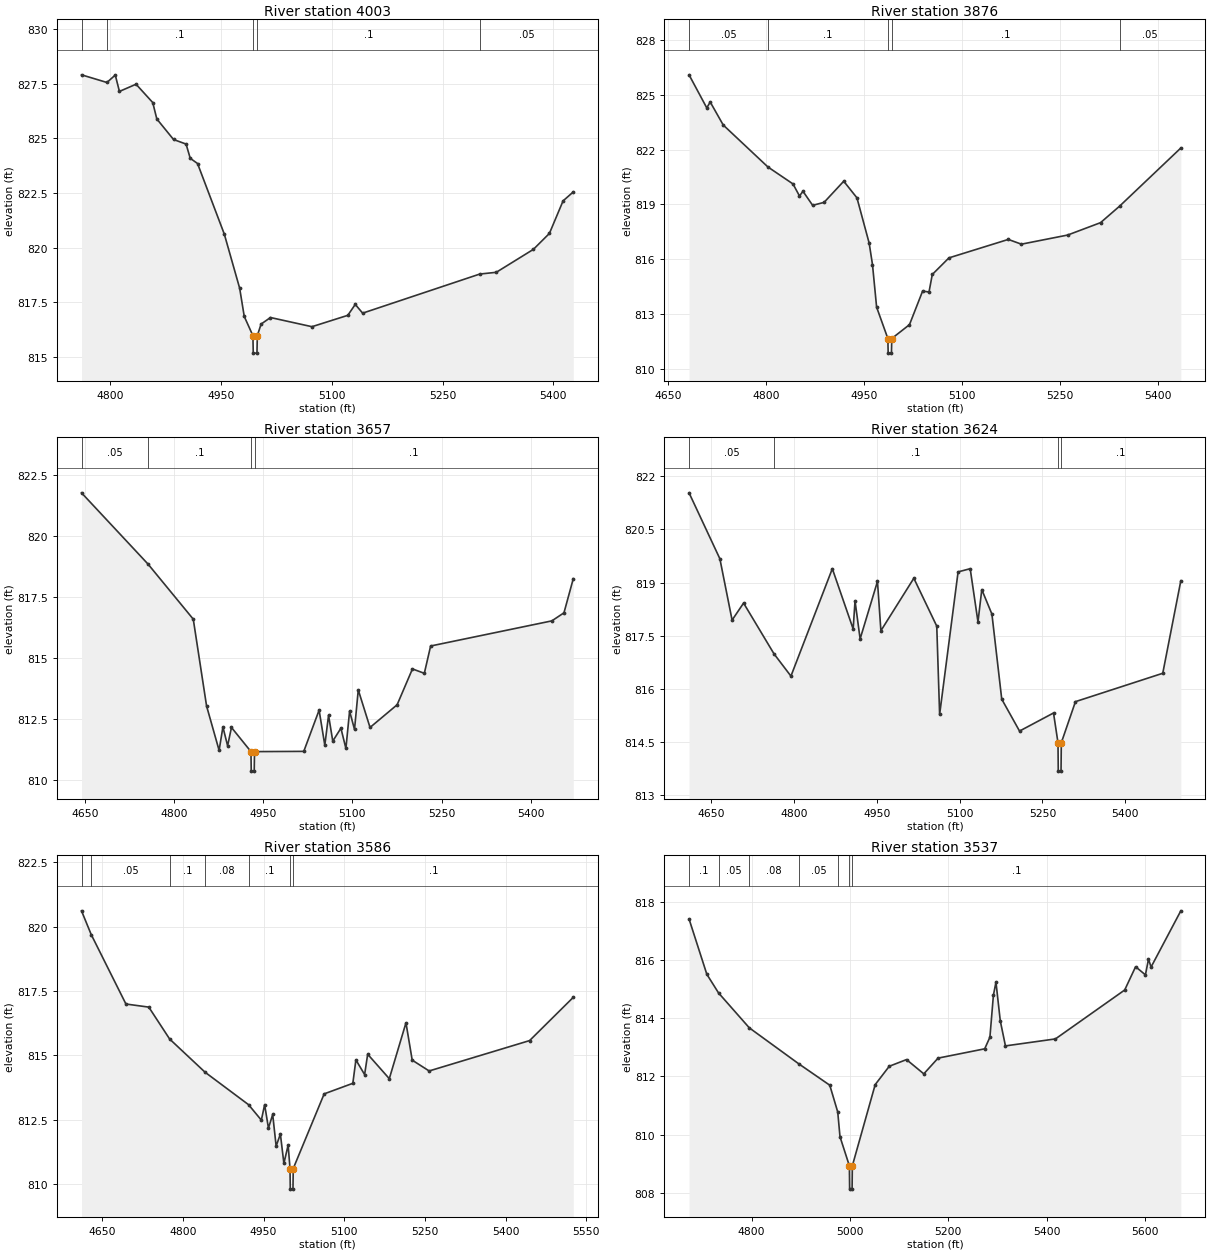
Type RM Length L Ch R = 1,4003,127,127,127
BEGIN DESCRIPTION:
UNT 031 in HW 16.0
END DESCRIPTION:
XS GIS Cut Line= 4
      1983346.25     13649882.35      1983197.65     13649810.13
      1983105.98     13649742.77      1982721.25     13649706.65
#Sta/Elev= 30
  4761.5  827.91  4795.9  827.56  4807.2  827.90  4812.8  827.15  4835.3  827.48
  4857.9  826.64  4863.4  825.89  4886.0  824.95  4903.0  824.74  4908.6  824.09
  4918.5  823.85  4954.7  820.62  4975.5  818.14  4981.7  816.85  4993.4  815.97
  4993.9  815.17  4998.9  815.17  4999.4  815.97  5004.5  816.50  5017.2  816.80
  5073.3  816.38  5121.8  816.90  5131.9  817.40  5141.9  817.00  5300.4  818.79
  5322.7  818.87  5372.9  819.92  5394.6  820.65  5413.1  822.14  5426.9  822.55
#Mann=5,-1,0
  4761.5    0.05       0  4795.9     0.1       0  4993.4    0.07       0
  4999.4     0.1       0  5300.4    0.05       0
Bank Sta=4993.4,4999.4
Exp/Cntr=0.3,0.1

Type RM Length L Ch R = 1,3876,219,219,219
BEGIN DESCRIPTION:
Mapping XS 882c0bf7
END DESCRIPTION:
XS GIS Cut Line= 4
      1983349.71     13649834.39      1983285.84     13649660.13
      1983062.23     13649635.82      1982723.34     13649681.65
#Sta/Elev= 30
  4682.6  826.10  4709.7  824.29  4715.0  824.61  4734.9  823.35  4803.3  821.05
  4841.7  820.12  4851.6  819.46  4856.9  819.72  4871.7  818.95  4889.2  819.11
  4919.3  820.27  4939.5  819.36  4958.2  816.88  4963.3  815.70  4969.6  813.37
  4986.8  811.65  4987.3  810.85  4992.3  810.85  4992.8  811.65  5019.9  812.41
  5040.0  814.25  5049.8  814.20  5054.8  815.16  5080.3  816.07  5171.1  817.08
  5191.2  816.82  5261.9  817.32  5312.3  818.00  5341.3  818.90  5435.1  822.09
#Mann=5,-1,0
  4682.6    0.05       0  4803.3     0.1       0  4986.8    0.07       0
  4992.8     0.1       0  5341.3    0.05       0
Bank Sta=4986.8,4992.8
Exp/Cntr=0.3,0.1

Type RM Length L Ch R = 1,3657,33,33,33
BEGIN DESCRIPTION:
UNT 031 in HW 17.0
END DESCRIPTION:
XS GIS Cut Line= 6
      1983375.23     13649749.72      1983239.82     13649580.47
      1983290.60     13649517.97      1983278.88     13649464.58
      1983191.65     13649529.69      1982849.63     13649598.61
#Sta/Elev= 30
  4644.1  821.77  4756.0  818.85  4832.2  816.59  4854.6  813.03  4875.7  811.21
  4882.1  812.17  4890.0  811.40  4896.5  812.15  4929.3  811.16  4929.8  810.36
  4934.8  810.36  4935.3  811.16  5018.2  811.17  5044.0  812.86  5053.6  811.42
  5059.9  812.65  5067.0  811.59  5080.7  812.12  5089.1  811.29  5095.3  812.82
  5103.6  812.07  5109.9  813.69  5129.7  812.15  5175.3  813.08  5201.1  814.55
  5221.1  814.37  5231.7  815.49  5435.7  816.52  5456.1  816.85  5471.8  818.25
#Mann=4,-1,0
  4644.1    0.05       0  4756.0     0.1       0  4929.3    0.07       0
  4935.3     0.1       0
Bank Sta=4929.3,4935.3
Exp/Cntr=0.3,0.1

Type RM Length L Ch R = 1,3624,38,38,38
BEGIN DESCRIPTION:
UNT 031 in HW 18.0
END DESCRIPTION:
XS GIS Cut Line= 6
      1983402.59     13649736.73      1983272.37     13649583.07
      1983340.08     13649514.06      1983310.13     13649443.75
      1983272.37     13649430.73      1982833.52     13649581.78
#Sta/Elev= 30
  4610.4  821.53  4666.2  819.67  4688.3  817.94  4709.1  818.42  4764.1  816.99
  4794.8  816.36  4869.7  819.39  4907.4  817.69  4910.8  818.48  4920.0  817.41
  4951.4  819.03  4957.6  817.64  5017.2  819.12  5058.7  817.77  5063.9  815.28
  5097.3  819.30  5119.2  819.39  5133.3  817.89  5140.2  818.80  5158.5  818.11
  5176.3  815.71  5208.5  814.81  5270.0  815.32  5278.1  814.48  5278.6  813.68
  5283.6  813.68  5284.1  814.48  5309.7  815.64  5467.7  816.44  5500.4  819.05
#Mann=4,-1,0
  4610.4    0.05       0  4764.1     0.1       0  5278.1    0.07       0
  5284.1     0.1       0
Bank Sta=5278.1,5284.1
Exp/Cntr=0.3,0.1

Type RM Length L Ch R = 1,3586,49,49,49
BEGIN DESCRIPTION:
UNT 031 in HW 19.0
END DESCRIPTION:
XS GIS Cut Line= 6
      1983422.09     13649722.36      1983327.06     13649588.28
      1983388.26     13649511.46      1983308.83     13649398.18
      1983242.43     13649392.97      1982829.85     13649543.95
#Sta/Elev= 30
  4611.5  820.61  4629.5  819.69  4694.1  816.99  4736.6  816.87  4775.4  815.63
  4841.3  814.34  4922.1  813.08  4945.9  812.48  4952.0  813.08  4959.1  812.17
  4967.0  812.70  4973.4  811.47  4981.3  811.94  4987.8  810.80  4995.7  811.51
  4999.2  810.60  4999.7  809.80  5004.7  809.80  5005.2  810.60  5062.7  813.50
  5116.0  813.91  5121.7  814.82  5137.9  814.25  5143.6  815.04  5183.8  814.09
  5214.8  816.26  5226.4  814.81  5257.9  814.39  5444.7  815.57  5525.9  817.25
#Mann=7,-1,0
  4611.5     0.1       0  4629.5    0.05       0  4775.4     0.1       0
  4841.3    0.08       0  4922.1     0.1       0  4999.2    0.07       0
  5005.2     0.1       0
Bank Sta=4999.2,5005.2
Exp/Cntr=0.3,0.1

Type RM Length L Ch R = 1,3537,275,275,275
BEGIN DESCRIPTION:
UNT 031 in HW 20.0
END DESCRIPTION:
XS GIS Cut Line= 4
      1983457.27     13649674.20      1983406.49     13649416.41
      1983238.52     13649275.78      1982746.71     13649440.58
#Sta/Elev= 30
  4672.7  817.41  4708.9  815.51  4732.7  814.87  4795.3  813.67  4896.3  812.43
  4959.0  811.70  4975.2  810.78  4979.8  809.93  4998.9  808.93  4999.4  808.13
  5004.4  808.13  5004.9  808.93  5051.4  811.72  5080.0  812.35  5115.1  812.58
  5150.3  812.09  5179.3  812.63  5274.2  812.95  5284.8  813.35  5291.9  814.79
  5297.1  815.24  5305.9  813.91  5316.4  813.05  5418.1  813.29  5559.0  814.97
  5581.2  815.77  5601.2  815.49  5607.4  816.03  5612.7  815.76  5673.2  817.69
#Mann=7,-1,0
  4672.7     0.1       0  4732.7    0.05       0  4795.3    0.08       0
  4896.3    0.05       0  4975.2     0.1       0  4998.9    0.07       0
  5004.9     0.1       0
Bank Sta=4998.9,5004.9
Exp/Cntr=0.3,0.1

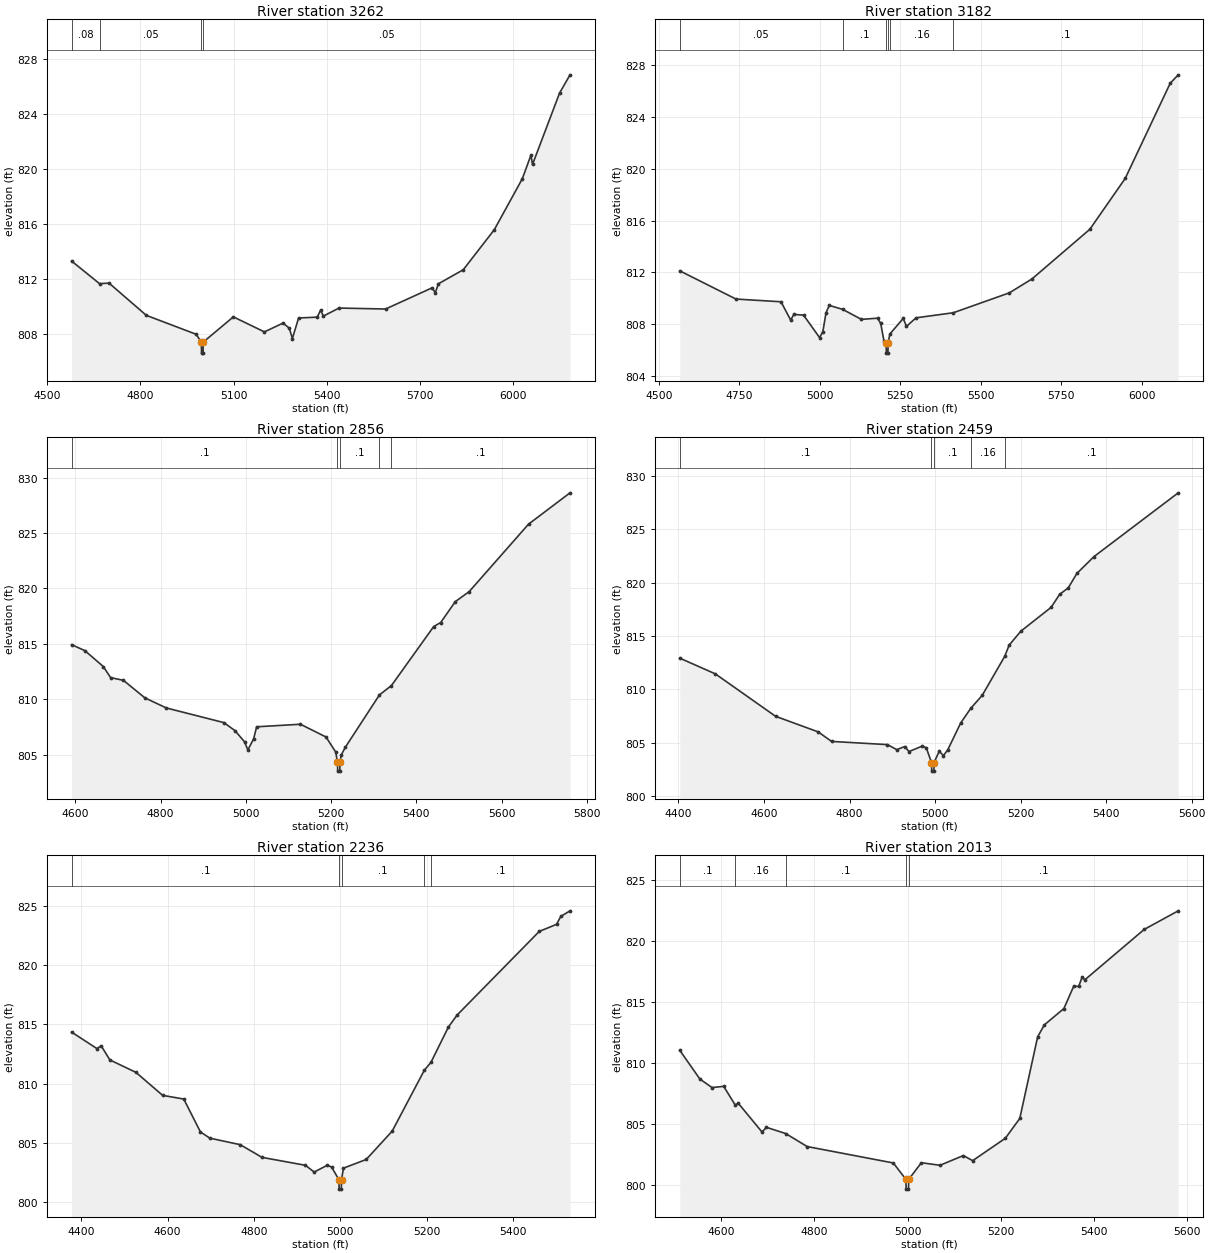
Type RM Length L Ch R = 1,3262,80,80,80
BEGIN DESCRIPTION:
UNT 031 in HW 15.0
END DESCRIPTION:
XS GIS Cut Line= 2
      1983441.65     13649545.62      1983418.21     13647941.39
#Sta/Elev= 30
  4578.2  813.31  4668.2  811.67  4698.8  811.71  4818.8  809.37  4978.9  808.00
  4995.9  807.43  4996.4  806.63  5001.4  806.63  5001.9  807.43  5098.9  809.26
  5198.9  808.17  5258.9  808.81  5278.9  808.44  5288.9  807.69  5308.9  809.18
  5368.9  809.24  5379.6  809.74  5388.9  809.32  5438.9  809.90  5588.9  809.83
  5738.9  811.37  5748.9  811.01  5758.9  811.66  5839.0  812.68  5939.0  815.59
  6029.0  819.28  6056.9  821.00  6061.9  820.32  6149.0  825.50  6182.6  826.82
#Mann=4,-1,0
  4578.2    0.08       0  4668.2    0.05       0  4995.9    0.04       0
  5001.9    0.05       0
Bank Sta=4995.9,5001.9
Exp/Cntr=0.3,0.1

Type RM Length L Ch R = 1,3182,326,326,326
BEGIN DESCRIPTION:
UNT 031 in HW 14.0
END DESCRIPTION:
XS GIS Cut Line= 2
      1983504.15     13649519.57      1983498.94     13647970.08
#Sta/Elev= 30
  4564.5  812.12  4739.1  809.94  4879.1  809.73  4909.1  808.32  4919.1  808.75
  4949.1  808.70  4999.1  806.96  5009.1  807.41  5019.1  808.88  5029.1  809.45
  5071.0  809.14  5129.1  808.37  5179.1  808.46  5189.1  808.06  5199.1  806.71
  5206.1  806.56  5206.6  805.76  5211.6  805.76  5212.1  806.56  5217.6  807.24
  5259.1  808.44  5269.1  807.83  5299.1  808.49  5414.6  808.88  5589.1  810.42
  5659.1  811.49  5839.1  815.33  5949.1  819.26  6089.1  826.62  6114.0  827.27
#Mann=6,-1,0
  4564.5    0.05       0  5071.0     0.1       0  5206.1    0.04       0
  5212.1     0.1       0  5217.6    0.16       0  5414.6     0.1       0
Bank Sta=5206.1,5212.1
Exp/Cntr=0.3,0.1

Type RM Length L Ch R = 1,2856,397,397,397
BEGIN DESCRIPTION:
UNT 031 in HW 4.0
END DESCRIPTION:
XS GIS Cut Line= 4
      1983632.36     13649675.99      1983675.00     13649275.00
      1983722.63     13649071.85      1983975.01     13648574.98
#Sta/Elev= 30
  4591.2  814.92  4622.4  814.38  4665.5  812.95  4682.7  811.95  4712.9  811.70
  4763.1  810.12  4813.4  809.21  4948.2  807.89  4974.3  807.17  4997.0  806.15
  5004.7  805.42  5018.2  806.42  5025.3  807.51  5128.0  807.74  5188.0  806.59
  5210.8  805.23  5214.9  804.31  5215.4  803.51  5220.4  803.51  5220.9  804.31
  5223.5  804.94  5233.2  805.66  5313.4  810.39  5341.5  811.23  5440.5  816.55
  5457.1  816.92  5491.2  818.80  5523.9  819.71  5663.0  825.79  5760.4  828.62
#Mann=5,-1,0
  4591.2     0.1       0  5214.9    0.07       0  5220.9     0.1       0
  5313.4    0.16       0  5341.5     0.1       0
Bank Sta=5214.9,5220.9
Exp/Cntr=0.3,0.1

Type RM Length L Ch R = 1,2459,223,223,223
BEGIN DESCRIPTION:
Mapping XS 16ca6b8e
END DESCRIPTION:
XS GIS Cut Line= 3
      1983912.74     13649757.57      1984034.27     13648695.11
      1984030.83     13648598.96
#Sta/Elev= 30
  4403.1  812.93  4486.2  811.46  4627.1  807.49  4726.8  806.03  4758.0  805.14
  4888.8  804.84  4910.5  804.37  4929.1  804.66  4939.1  804.19  4969.3  804.69
  4979.4  804.56  4991.7  803.16  4992.2  802.36  4997.2  802.36  4997.7  803.16
  5009.6  804.21  5019.7  803.82  5029.7  804.35  5059.9  806.86  5083.6  808.24
  5110.3  809.45  5162.8  813.09  5173.3  814.15  5200.8  815.46  5271.3  817.68
  5291.4  818.90  5311.6  819.51  5331.7  820.86  5371.9  822.44  5568.7  828.40
#Mann=5,-1,0
  4403.1     0.1       0  4991.7    0.07       0  4997.7     0.1       0
  5083.6    0.16       0  5162.8     0.1       0
Bank Sta=4991.7,4997.7
Exp/Cntr=0.3,0.1

Type RM Length L Ch R = 1,2236,223,223,223
BEGIN DESCRIPTION:
UNT 031 in HW 3.0
END DESCRIPTION:
XS GIS Cut Line= 3
      1984108.05     13649853.13      1984175.00     13649225.00
      1984153.19     13648703.75
#Sta/Elev= 30
  4377.9  814.36  4436.4  812.97  4446.4  813.20  4466.5  812.01  4526.9  810.96
  4588.6  809.02  4637.5  808.71  4676.0  805.94  4697.8  805.41  4768.2  804.86
  4818.5  803.79  4919.1  803.12  4939.2  802.55  4969.4  803.12  4979.4  802.98
  4996.5  801.91  4997.0  801.11  5002.0  801.11  5002.5  801.91  5007.1  802.88
  5059.6  803.61  5119.7  806.00  5194.3  811.15  5209.4  811.80  5249.8  814.78
  5269.8  815.79  5460.0  822.85  5500.0  823.45  5510.0  824.12  5531.3  824.59
#Mann=5,-1,0
  4377.9     0.1       0  4996.5    0.07       0  5002.5     0.1       0
  5194.3    0.16       0  5209.4     0.1       0
Bank Sta=4996.5,5002.5
Exp/Cntr=0.3,0.1

Type RM Length L Ch R = 1,2013,535,535,535
BEGIN DESCRIPTION:
Mapping XS be920e74
END DESCRIPTION:
XS GIS Cut Line= 4
      1984336.34     13649747.23      1984391.91     13649469.42
      1984378.02     13649042.33      1984266.90     13648702.04
#Sta/Elev= 30
  4511.7  811.03  4554.8  808.67  4580.8  807.97  4605.8  808.07  4630.6  806.53
  4636.9  806.69  4687.9  804.32  4697.5  804.70  4738.7  804.19  4784.8  803.12
  4969.5  801.77  4996.5  800.42  4997.0  799.62  5002.0  799.62  5002.5  800.42
  5029.6  801.79  5069.6  801.58  5119.6  802.38  5139.6  801.96  5209.6  803.80
  5240.6  805.43  5278.9  812.14  5293.2  813.12  5335.2  814.47  5356.3  816.31
  5366.8  816.28  5374.5  817.07  5379.8  816.82  5507.3  820.97  5580.3  822.50
#Mann=5,-1,0
  4511.7     0.1       0  4630.6    0.16       0  4738.7     0.1       0
  4996.5    0.07       0  5002.5     0.1       0
Bank Sta=4996.5,5002.5
Exp/Cntr=0.3,0.1

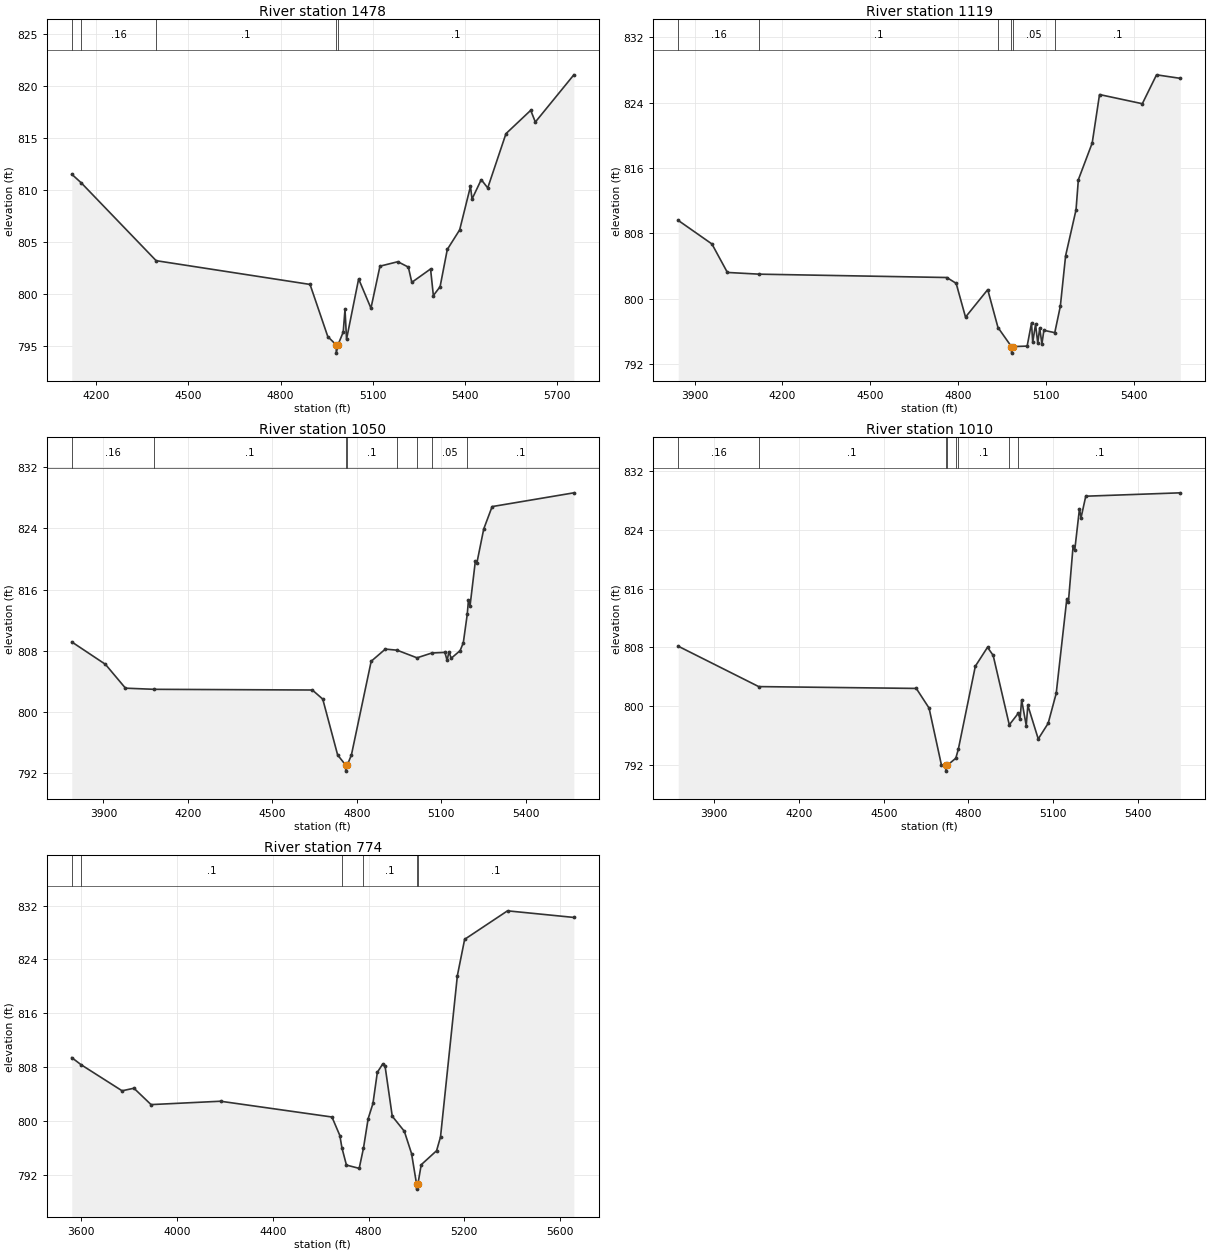
Type RM Length L Ch R = 1,1478,359,359,359
BEGIN DESCRIPTION:
Mapping XS 7850e740
END DESCRIPTION:
XS GIS Cut Line= 4
      1984391.93     13649795.77      1984638.43     13649337.47
      1984683.57     13648809.69      1984534.27     13648243.75
#Sta/Elev= 30
  4119.8  811.53  4150.7  810.70  4394.6  803.20  4895.9  800.91  4953.8  795.88
  4980.9  795.09  4981.4  794.29  4987.0  795.09  5004.0  796.32  5009.8  798.52
  5014.8  795.63  5054.2  801.44  5094.3  798.62  5123.7  802.67  5181.9  803.10
  5216.1  802.58  5227.4  801.11  5288.5  802.40  5297.6  799.84  5319.5  800.69
  5343.0  804.28  5383.3  806.17  5418.5  810.36  5423.6  809.14  5453.6  811.01
  5474.7  810.21  5534.1  815.44  5614.7  817.69  5629.8  816.56  5755.2  821.11
#Mann=5,-1,0
  4119.8     0.1       0  4150.7    0.16       0  4394.6     0.1       0
  4980.9    0.07       0  4987.0     0.1       0
Bank Sta=4980.9,4987
Exp/Cntr=0.3,0.1

Type RM Length L Ch R = 1,1119,69,69,69
BEGIN DESCRIPTION:
Mapping XS 65a23ae3
END DESCRIPTION:
XS GIS Cut Line= 6
      1984621.07     13649853.96      1984962.22     13648853.96
      1984954.41     13648781.05      1984907.53     13648713.34
      1984837.22     13648650.84      1984694.35     13648268.99
#Sta/Elev= 30
  3844.1  809.60  3959.1  806.72  4011.9  803.24  4120.2  803.03  4761.1  802.62
  4792.9  801.91  4824.9  797.78  4900.7  801.14  4935.7  796.51  4981.6  794.18
  4982.1  793.38  4987.7  794.18  5035.3  794.24  5050.2  797.06  5054.3  794.70
  5064.0  796.91  5071.5  794.60  5078.2  796.45  5085.7  794.50  5092.4  796.17
  5129.6  795.88  5148.6  799.11  5166.6  805.28  5202.2  810.89  5210.1  814.57
  5257.4  819.06  5282.4  824.98  5428.5  823.86  5477.0  827.39  5558.2  826.96
#Mann=6,-1,0
  3844.1    0.16       0  4120.2     0.1       0  4935.7    0.05       0
  4981.6   0.033       0  4987.7    0.05       0  5129.6     0.1       0
Bank Sta=4981.6,4987.7
Exp/Cntr=0.3,0.1

Type RM Length L Ch R = 1,1050,40,40,40
BEGIN DESCRIPTION:
Mapping XS 338f8e14
END DESCRIPTION:
XS GIS Cut Line= 6
      1984644.50     13649872.22      1985019.51     13648981.57
      1985032.53     13648812.30      1985001.28     13648726.36
      1984899.72     13648645.63      1984743.50     13648249.88
#Sta/Elev= 30
  3787.6  809.15  3907.1  806.22  3978.3  803.10  4080.3  802.95  4641.8  802.86
  4678.8  801.67  4731.7  794.36  4759.9  793.05  4760.4  792.25  4766.0  793.05
  4780.6  794.37  4850.8  806.62  4901.0  808.21  4942.6  808.07  5013.5  807.07
  5066.1  807.70  5112.6  807.78  5120.4  806.72  5126.8  807.87  5134.9  807.01
  5166.6  808.01  5177.9  809.04  5191.9  812.76  5196.3  814.66  5201.7  813.83
  5220.7  819.73  5226.1  819.48  5250.4  823.92  5280.2  826.85  5570.4  828.65
#Mann=8,-1,0
  3787.6    0.16       0  4080.3     0.1       0  4759.9   0.035       0
  4766.0     0.1       0  4942.6    0.05       0  5013.5     0.1       0
  5066.1    0.05       0  5191.9     0.1       0
Bank Sta=4759.9,4766
Exp/Cntr=0.3,0.1

Type RM Length L Ch R = 1,1010,236,236,236
BEGIN DESCRIPTION:
Mapping XS 0b7dec04
END DESCRIPTION:
XS GIS Cut Line= 6
      1984673.14     13649869.62      1985048.16     13649005.01
      1985071.59     13648887.82      1985074.20     13648786.26
      1984975.24     13648637.82      1984780.02     13648249.98
#Sta/Elev= 30
  3772.6  808.14  4057.5  802.63  4615.3  802.38  4660.5  799.70  4704.1  791.97
  4719.2  791.90  4719.7  791.10  4725.3  791.90  4755.2  792.86  4764.3  794.12
  4824.3  805.41  4867.4  807.99  4887.4  806.89  4944.5  797.41  4976.2  798.99
  4982.5  798.17  4988.2  800.81  5004.5  797.32  5010.2  800.07  5047.0  795.49
  5082.1  797.62  5110.6  801.71  5148.2  814.62  5153.8  814.20  5170.5  821.86
  5176.1  821.21  5192.9  826.88  5198.5  825.66  5215.2  828.60  5549.9  829.06
#Mann=8,-1,0
  3772.6    0.16       0  4057.5     0.1       0  4719.2    0.07       0
  4725.3     0.1       0  4755.2    0.05       0  4764.3     0.1       0
  4944.5    0.05       0  4976.2     0.1       0
Bank Sta=4719.2,4725.3
Exp/Cntr=0.3,0.1

Type RM Length L Ch R = 1,774,0,0,0
BEGIN DESCRIPTION:
UNT 031 in HW 2.0
END DESCRIPTION:
XS GIS Cut Line= 4
      1984653.20     13649919.05      1985319.86     13649123.93
      1985240.00     13648481.57      1984944.88     13648193.39
#Sta/Elev= 30
  3560.3  809.43  3599.2  808.38  3770.5  804.51  3820.0  804.89  3891.5  802.46
  4181.7  802.96  4647.2  800.62  4680.2  797.87  4688.9  796.04  4707.7  793.49
  4761.0  793.00  4778.7  795.96  4798.4  800.37  4818.5  802.63  4836.8  807.25
  4858.8  808.46  4868.9  808.21  4899.1  800.74  4949.5  798.51  4979.8  795.19
  5000.4  790.72  5000.9  789.92  5006.5  790.72  5020.1  793.54  5084.3  795.62
  5100.7  797.66  5171.2  821.61  5201.5  826.98  5380.6  831.21  5657.7  830.23
#Mann=6,-1,0
  3560.3    0.16       0  3599.2     0.1       0  4688.9    0.05       0
  4778.7     0.1       0  5000.4    0.07       0  5006.5     0.1       0
Bank Sta=5000.4,5006.5
Exp/Cntr=0.3,0.1

Chan Stop Cuts=-1