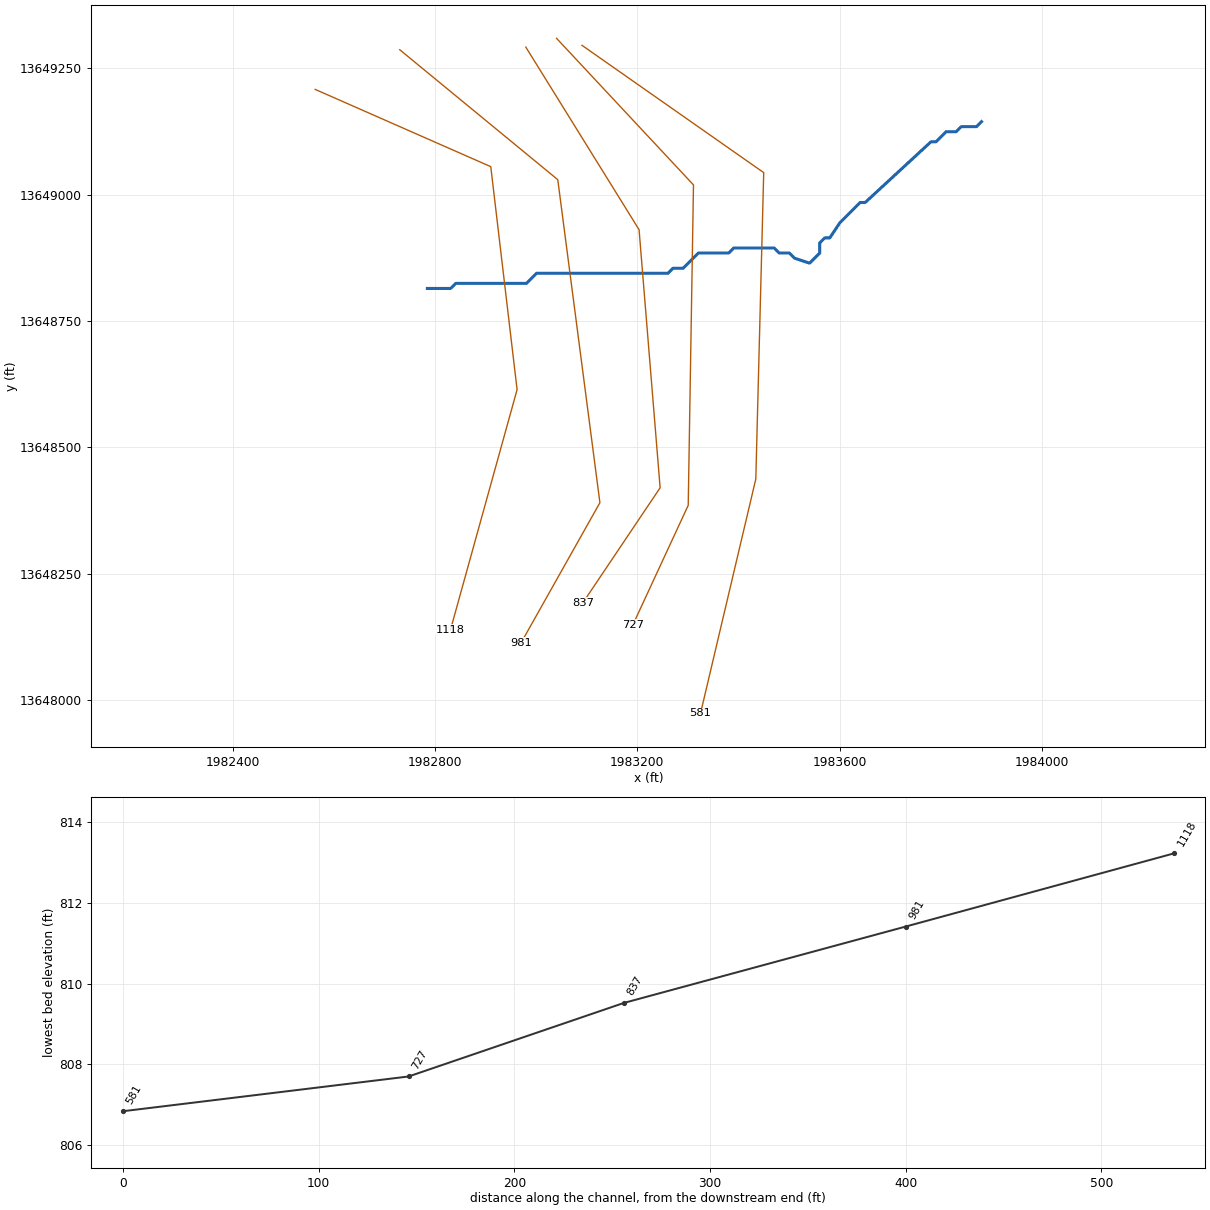
--- UNT 033 in HW.prj (project) ---

Proj Title=UNT 033 in HW Base Level Engineering
Current Plan=p01
Default Exp/Contr=0.3,0.1
English Units
Geom File=g01
Flow File=f01
Plan File=p01
BEGIN DESCRIPTION:
UNT 033 in HW
END DESCRIPTION:

--- UNT 033 in HW.p01 (plan) ---

Plan Title=Multiple Run
Short Identifier=Multiple
Geom File=g01
Flow File=f01
Subcritical Flow
K Sum by GR= 0
Std Step Tol= 0.01
Critical Tol= 0.01
Num of Std Step Trials= 20
Max Error Tol= 0.3
Flow Tol Ratio= 0.001
Split Flow NTrial= 30
Split Flow Tol= 0.02
Split Flow Ratio= 0.02
Log Output Level= 0
Friction Slope Method= 1
Unsteady Friction Slope Method= 2
Unsteady Bridges Friction Slope Method= 1
Parabolic Critical Depth
Global Vel Dist=  1 , 1 , 1
Global Log Level= 0
CheckData=True
Encroach Param= -1, 0, 0, 0
BEGIN DESCRIPTION:
Multiple Run
END DESCRIPTION:

--- UNT 033 in HW.f01 (steady flow) ---

Flow Title=Multiple
Number of Profiles=7
Profile Names=10-year,25-year,50-year,1pct_min,100-year,1pct_plu,500-year
River Rch & RM= UNT 033 in HW,Reach-1,1118
     315     430     524     318     634    1264     927
Boundary for River Rch & Prof#=UNT 033 in HW,Reach-1,1
Up Type=0
Dn Type=3
Dn Slope=0.005
Boundary for River Rch & Prof#=UNT 033 in HW,Reach-1,2
Up Type=0
Dn Type=3
Dn Slope=0.005
Boundary for River Rch & Prof#=UNT 033 in HW,Reach-1,3
Up Type=0
Dn Type=3
Dn Slope=0.005
Boundary for River Rch & Prof#=UNT 033 in HW,Reach-1,4
Up Type=0
Dn Type=3
Dn Slope=0.005
Boundary for River Rch & Prof#=UNT 033 in HW,Reach-1,5
Up Type=0
Dn Type=3
Dn Slope=0.005
Boundary for River Rch & Prof#=UNT 033 in HW,Reach-1,6
Up Type=0
Dn Type=3
Dn Slope=0.005
Boundary for River Rch & Prof#=UNT 033 in HW,Reach-1,7
Up Type=0
Dn Type=3
Dn Slope=0.005

--- UNT 033 in HW.g01 (geometry) ---

Geom Title=Existing Conditions

River Reach=UNT 033 in HW,Reach-1
Reach XY= 30
      1982784.85     13648814.54      1982830.80     13648814.54
      1982840.80     13648824.54      1982980.80     13648824.54
      1983000.80     13648844.54      1983260.80     13648844.54
      1983270.80     13648854.54      1983290.80     13648854.54
      1983320.80     13648884.54      1983380.80     13648884.54
      1983390.80     13648894.54      1983470.80     13648894.54
      1983480.80     13648884.54      1983500.80     13648884.54
      1983510.80     13648874.54      1983540.80     13648864.54
      1983560.80     13648884.54      1983560.80     13648904.54
      1983570.80     13648914.54      1983580.80     13648914.54
      1983600.80     13648944.54      1983640.80     13648984.54
      1983650.80     13648984.54      1983780.80     13649104.54
      1983790.80     13649104.54      1983810.80     13649124.54
      1983830.80     13649124.54      1983840.80     13649134.54
      1983870.80     13649134.54      1983880.80     13649144.54

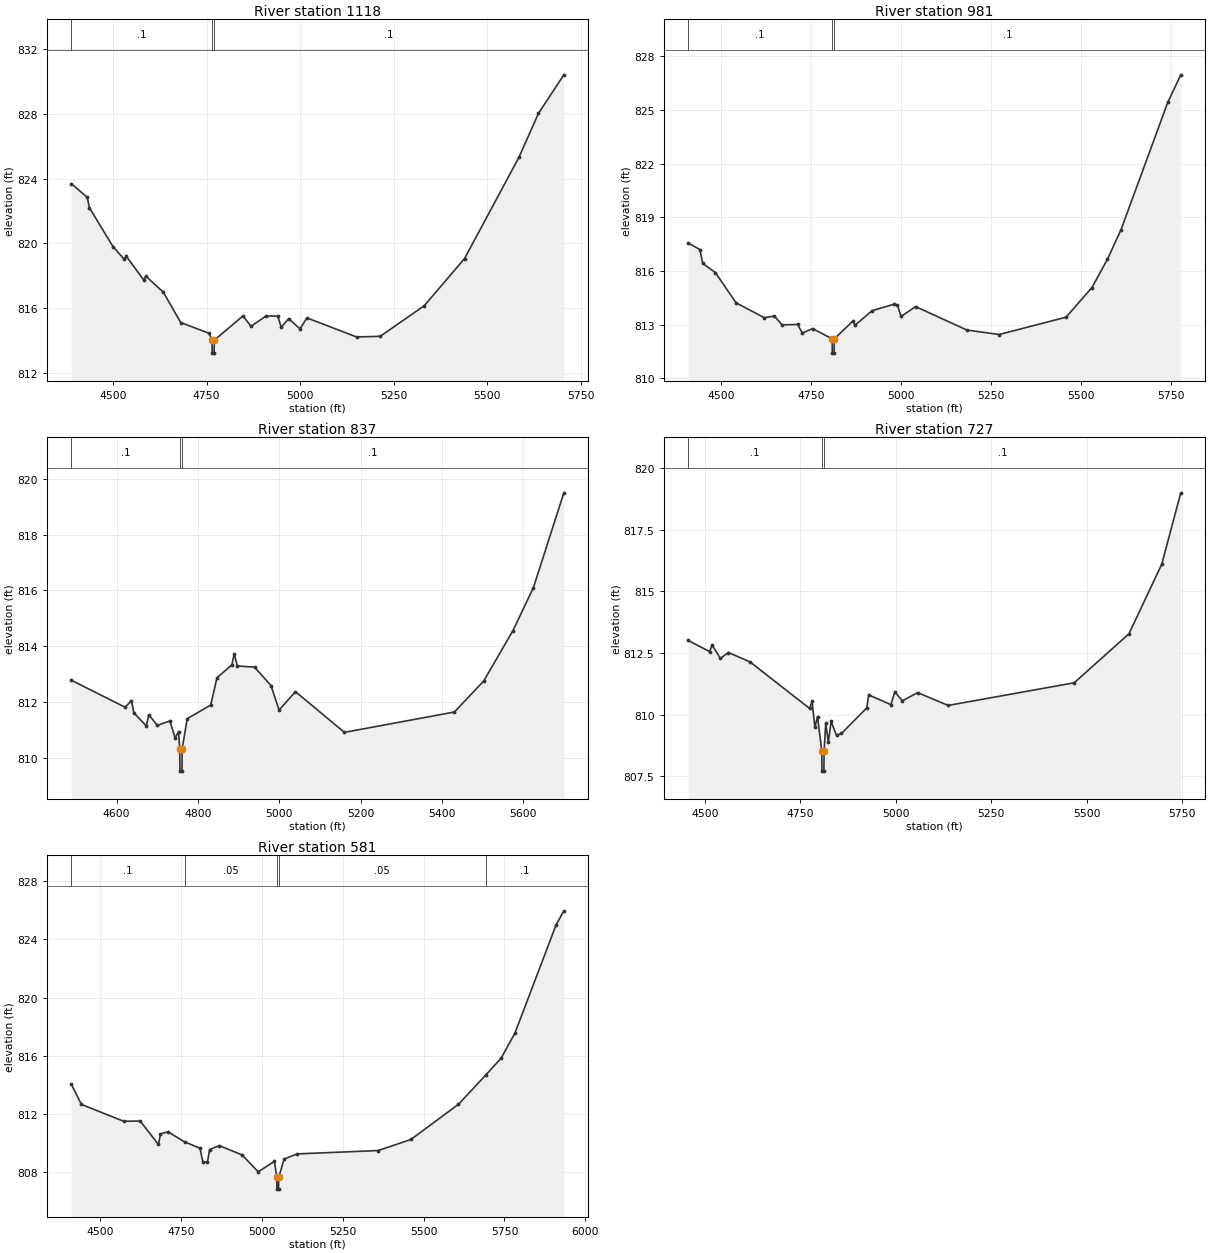
Type RM Length L Ch R = 1,1118,137,137,137
BEGIN DESCRIPTION:
UNT 033 in HW 1.0
END DESCRIPTION:
XS GIS Cut Line= 4
      1982563.05     13649208.18      1982910.25     13649055.41
      1982962.33     13648614.44      1982830.55     13648139.34
#Sta/Elev= 30
  4388.2  823.70  4431.0  822.85  4436.4  822.22  4499.6  819.81  4529.8  819.02
  4535.2  819.21  4581.9  817.74  4587.4  817.98  4634.1  816.99  4680.7  815.11
  4756.2  814.45  4764.4  814.02  4764.9  813.22  4769.9  813.22  4770.4  814.02
  4847.0  815.52  4868.6  814.88  4908.9  815.52  4940.0  815.51  4949.2  814.82
  4969.3  815.35  4999.5  814.72  5017.9  815.40  5150.6  814.22  5213.9  814.26
  5331.4  816.15  5439.3  819.07  5584.6  825.33  5636.7  828.04  5704.6  830.43
#Mann=3,-1,0
  4388.2     0.1       0  4764.4    0.07       0  4770.4     0.1       0
Bank Sta=4764.4,4770.4
Exp/Cntr=0.3,0.1

Type RM Length L Ch R = 1,981,144,144,144
BEGIN DESCRIPTION:
UNT 033 in HW 21.0
END DESCRIPTION:
XS GIS Cut Line= 4
      1982730.26     13649286.64      1983042.77     13649029.69
      1983126.11     13648390.80      1982969.95     13648113.19
#Sta/Elev= 30
  4408.7  817.56  4441.0  817.20  4448.9  816.42  4484.1  815.91  4541.5  814.22
  4619.7  813.39  4647.9  813.48  4669.2  812.99  4712.2  813.01  4725.5  812.53
  4753.9  812.78  4808.2  812.21  4808.7  811.41  4813.7  811.41  4814.2  812.21
  4866.3  813.21  4871.3  812.96  4918.9  813.78  4979.4  814.14  4989.4  814.11
  4999.5  813.46  5039.9  814.01  5182.3  812.70  5271.8  812.45  5457.6  813.42
  5529.3  815.07  5572.6  816.66  5610.2  818.31  5740.3  825.44  5776.1  826.96
#Mann=3,-1,0
  4408.7     0.1       0  4808.2    0.07       0  4814.2     0.1       0
Bank Sta=4808.2,4814.2
Exp/Cntr=0.3,0.1

Type RM Length L Ch R = 1,837,110,110,110
BEGIN DESCRIPTION:
Mapping XS ec56eef7
END DESCRIPTION:
XS GIS Cut Line= 4
      1982979.60     13649291.84      1983203.56     13648930.74
      1983245.22     13648420.33      1983092.45     13648192.90
#Sta/Elev= 30
  4488.6  812.78  4621.2  811.81  4636.6  812.05  4642.4  811.61  4673.2  811.14
  4679.1  811.54  4700.3  811.16  4731.1  811.32  4743.8  810.71  4752.3  810.94
  4755.2  810.32  4755.7  809.52  4760.7  809.52  4761.2  810.32  4773.6  811.40
  4831.4  811.89  4846.8  812.87  4883.4  813.33  4889.3  813.73  4896.7  813.29
  4939.3  813.25  4979.5  812.59  4999.5  811.71  5039.7  812.37  5160.1  810.91
  5430.5  811.64  5502.5  812.75  5574.5  814.56  5624.8  816.10  5699.6  819.50
#Mann=3,-1,0
  4488.6     0.1       0  4755.2    0.07       0  4761.2     0.1       0
Bank Sta=4755.2,4761.2
Exp/Cntr=0.3,0.1

Type RM Length L Ch R = 1,727,146,146,146
BEGIN DESCRIPTION:
Mapping XS 8f1755b1
END DESCRIPTION:
XS GIS Cut Line= 4
      1983040.38     13649309.19      1983311.19     13649019.28
      1983300.78     13648385.60      1983191.53     13648149.76
#Sta/Elev= 30
  4456.5  813.01  4512.3  812.56  4519.2  812.82  4540.7  812.28  4561.7  812.52
  4618.3  812.14  4774.2  810.25  4781.0  810.53  4788.3  809.48  4795.2  809.92
  4806.4  808.50  4806.9  807.70  4811.9  807.70  4812.4  808.50  4816.7  809.65
  4823.5  808.88  4830.8  809.72  4845.0  809.15  4857.9  809.23  4924.2  810.27
  4929.2  810.80  4987.5  810.40  4997.5  810.92  5017.5  810.56  5057.5  810.89
  5137.5  810.37  5467.6  811.29  5611.1  813.28  5697.0  816.11  5746.9  819.01
#Mann=3,-1,0
  4456.5     0.1       0  4806.4    0.07       0  4812.4     0.1       0
Bank Sta=4806.4,4812.4
Exp/Cntr=0.3,0.1

Type RM Length L Ch R = 1,581,0,0,0
BEGIN DESCRIPTION:
UNT 033 in HW 50.0
END DESCRIPTION:
XS GIS Cut Line= 4
      1983090.69     13649295.34      1983450.08     13649043.59
      1983434.46     13648437.69      1983325.08     13647974.12
#Sta/Elev= 30
  4412.1  814.05  4443.4  812.66  4574.1  811.50  4624.7  811.52  4681.4  809.91
  4687.5  810.63  4710.4  810.78  4761.9  810.09  4809.5  809.65  4818.2  808.73
  4832.5  808.68  4839.2  809.56  4869.5  809.83  4939.5  809.19  4989.5  808.03
  5039.6  808.75  5046.6  807.64  5047.1  806.84  5052.1  806.84  5052.6  807.64
  5069.6  808.91  5109.6  809.26  5359.7  809.49  5461.0  810.25  5607.9  812.67
  5691.4  814.66  5740.0  815.85  5782.3  817.56  5909.3  824.99  5933.3  825.96
#Mann=5,-1,0
  4412.1     0.1       0  4761.9    0.05       0  5046.6    0.04       0
  5052.6    0.05       0  5691.4     0.1       0
Bank Sta=5046.6,5052.6
Exp/Cntr=0.3,0.1

Chan Stop Cuts=-1