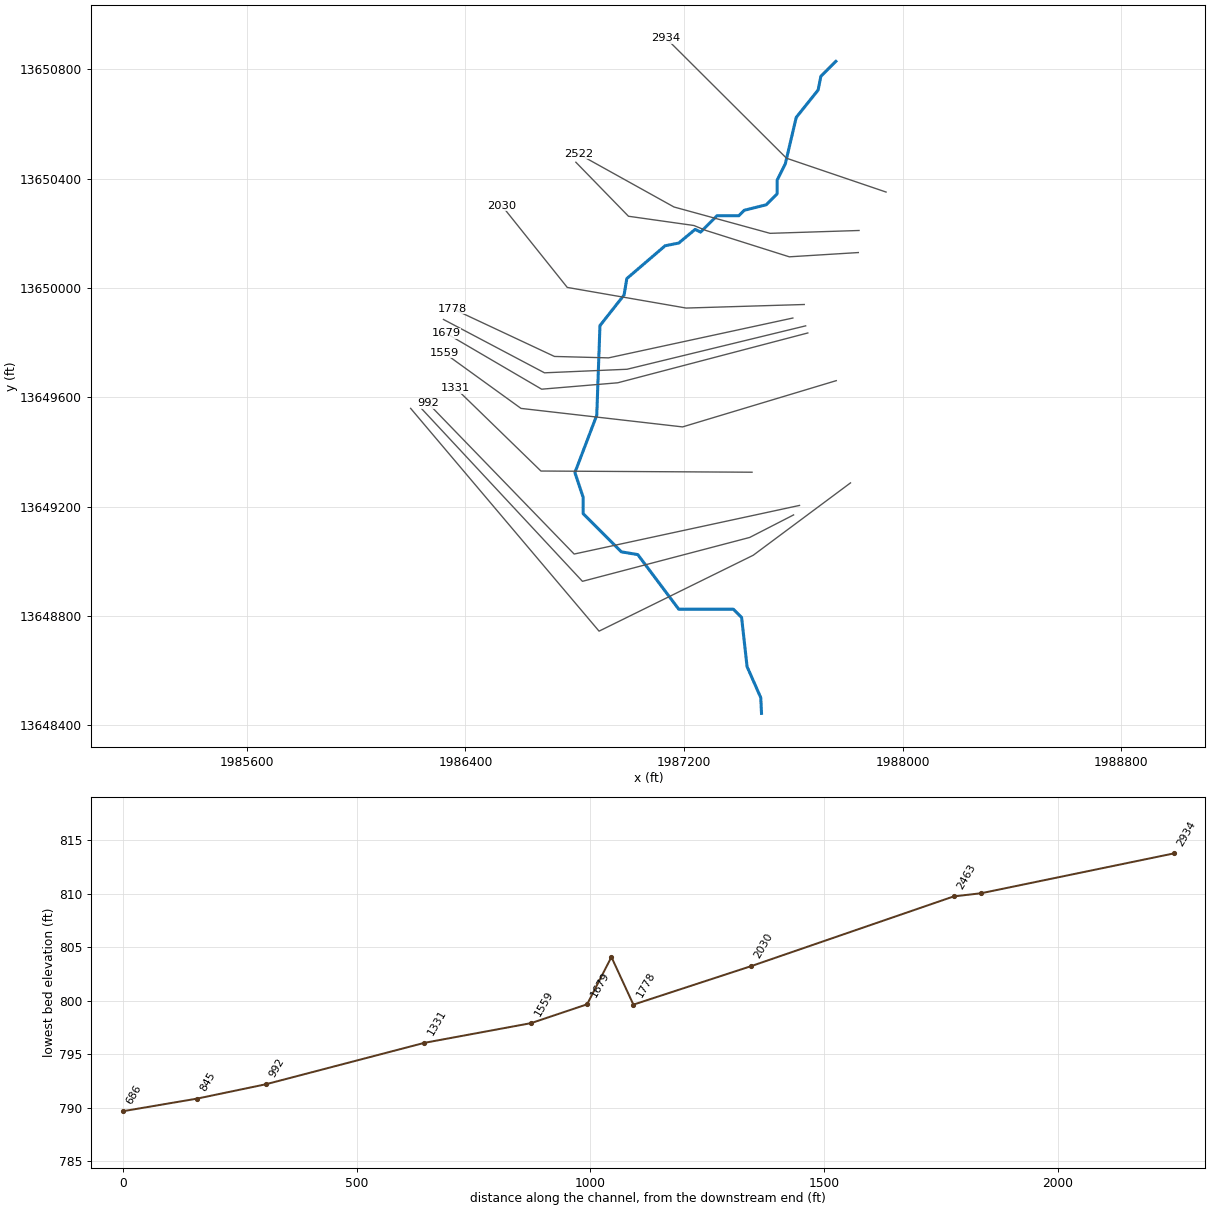
--- UNT 034 in HW.prj (project) ---

Proj Title=UNT 034 in HW Base Level Engineering
Current Plan=p01
Default Exp/Contr=0.3,0.1
English Units
Geom File=g01
Flow File=f01
Plan File=p01
Y Axis Title=Elevation
X Axis Title(PF)=Main Channel Distance
X Axis Title(XS)=Station
BEGIN DESCRIPTION:
UNT 034 in HW
END DESCRIPTION:
DSS Export Rating Curves= 0
DSS Export Rating Curve Sorted= 0
DSS Export Volume Flow Curves= 0
DXF OffsetX= 0
DXF OffsetY= 0
DXF ScaleX= 1
DXF ScaleY= 10

--- UNT 034 in HW.p01 (plan) ---

Plan Title=Multiple Run
Short Identifier=Multiple
Geom File=g01
Flow File=f01
Subcritical Flow
K Sum by GR= 0
Std Step Tol= 0.01
Critical Tol= 0.01
Num of Std Step Trials= 20
Max Error Tol= 0.3
Flow Tol Ratio= 0.001
Split Flow NTrial= 30
Split Flow Tol= 0.02
Split Flow Ratio= 0.02
Log Output Level= 0
Friction Slope Method= 1
Unsteady Friction Slope Method= 2
Unsteady Bridges Friction Slope Method= 1
Parabolic Critical Depth
Global Vel Dist=  1 , 1 , 1
Global Log Level= 0
CheckData=True
Encroach Param= -1, 0, 0, 0
BEGIN DESCRIPTION:
Multiple Run
END DESCRIPTION:

--- UNT 034 in HW.f01 (steady flow) ---

Flow Title=Multiple
Number of Profiles=7
Profile Names=10-year,25-year,50-year,1pct_min,100-year,1pct_plu,500-year
River Rch & RM= UNT 034 in HW,Reach-1,2934
     468     652     804     492     982    1960    1469
Boundary for River Rch & Prof#=UNT 034 in HW,Reach-1,1
Up Type=0
Dn Type=3
Dn Slope=0.005
Boundary for River Rch & Prof#=UNT 034 in HW,Reach-1,2
Up Type=0
Dn Type=3
Dn Slope=0.005
Boundary for River Rch & Prof#=UNT 034 in HW,Reach-1,3
Up Type=0
Dn Type=3
Dn Slope=0.005
Boundary for River Rch & Prof#=UNT 034 in HW,Reach-1,4
Up Type=0
Dn Type=3
Dn Slope=0.005
Boundary for River Rch & Prof#=UNT 034 in HW,Reach-1,5
Up Type=0
Dn Type=3
Dn Slope=0.005
Boundary for River Rch & Prof#=UNT 034 in HW,Reach-1,6
Up Type=0
Dn Type=3
Dn Slope=0.005
Boundary for River Rch & Prof#=UNT 034 in HW,Reach-1,7
Up Type=0
Dn Type=3
Dn Slope=0.005

--- UNT 034 in HW.g01 (geometry) ---

Geom Title=Existing Conditions
Program Version=5.05

River Reach=UNT 034 in HW   ,Reach-1
Reach XY= 30
       1987755.8     13650829.54       1987700.8     13650774.54
       1987690.8     13650724.54       1987610.8     13650624.54
       1987570.8     13650454.54       1987540.8     13650394.54
       1987540.8     13650344.54       1987500.8     13650304.54
       1987420.8     13650284.54       1987400.8     13650264.54
       1987320.8     13650264.54       1987260.8     13650204.54
       1987240.8     13650214.54       1987180.8     13650164.54
       1987130.8     13650154.54       1986990.8     13650034.54
       1986980.8     13649974.54       1986892.5     13649862.47
       1986880.8     13649534.54       1986800.8     13649324.54
       1986830.8     13649234.54       1986830.8     13649174.54
       1986970.8     13649034.54       1987030.8     13649024.54
       1987180.8     13648824.54       1987380.8     13648824.54
       1987410.8     13648794.54       1987430.8     13648614.54
      1987480.91      13648501.1      1987483.69     13648443.46

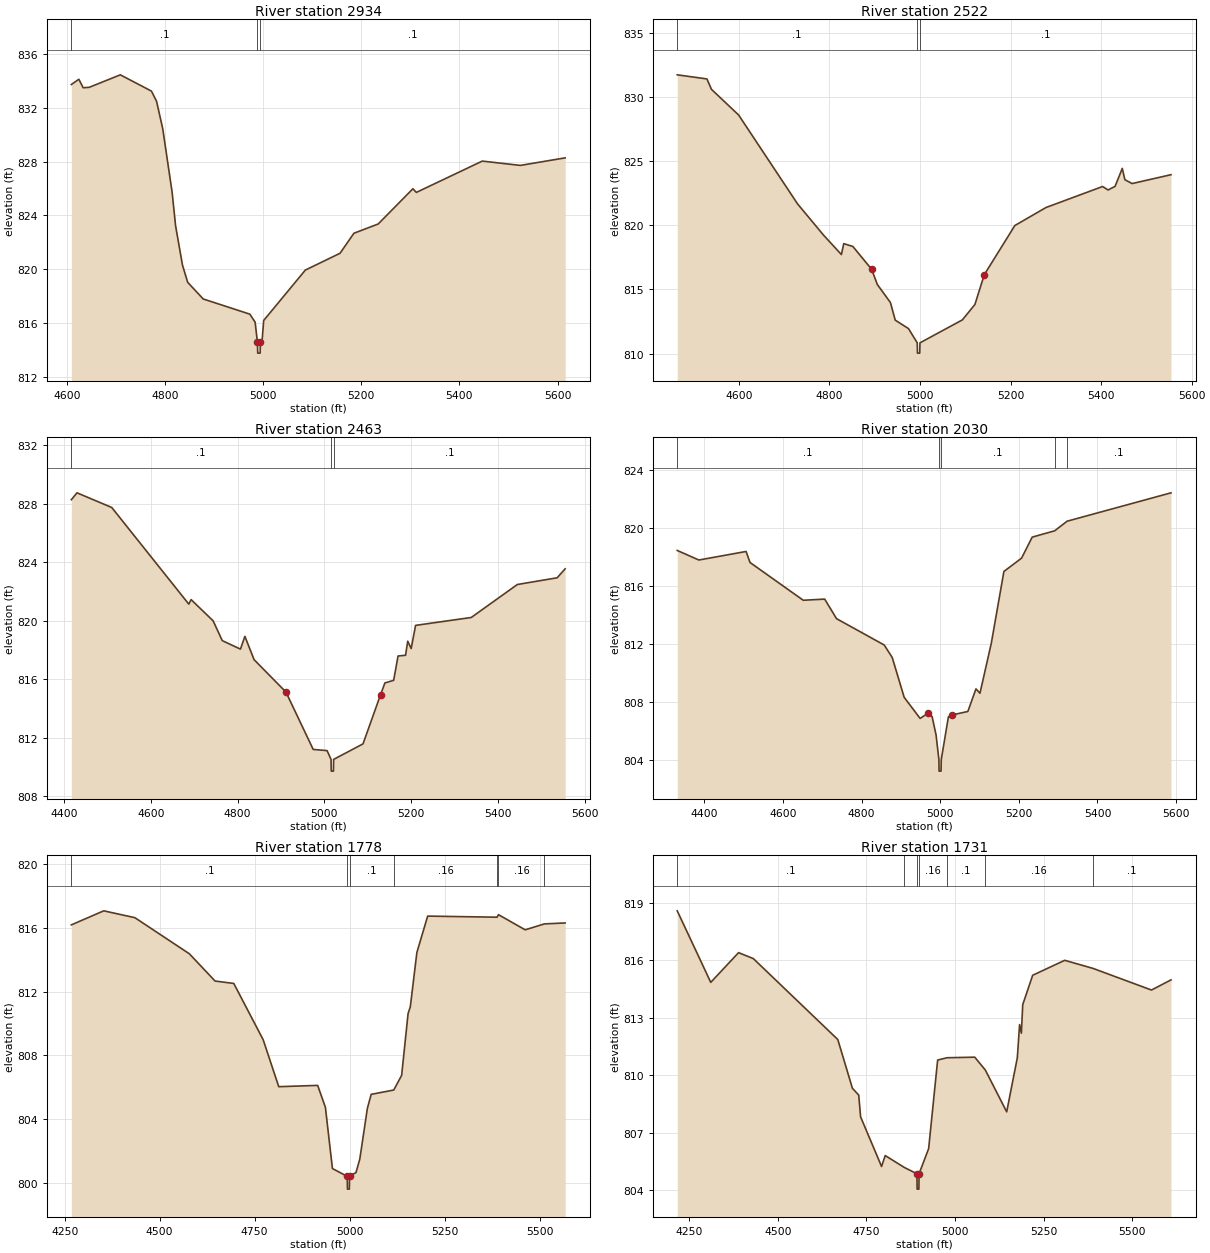
Type RM Length L Ch R = 1 ,2934    ,412,412,412
BEGIN DESCRIPTION:
UNT 034 in HW 5.0
END DESCRIPTION:
XS GIS Cut Line= 3
       1987939.5     13650351.14        1987575.       13650475.
      1987134.81     13650913.65
#Sta/Elev= 30
  4609.1  833.74  4624.4  834.13  4633.2   833.5  4645.5  833.53  4708.9  834.46
  4772.3  833.25  4782.8  832.49  4795.4  830.44  4814.5  825.72  4821.5  823.24
  4835.6   820.3  4846.2  819.02  4877.9  817.78  4972.9  816.65  4983.7  816.05
  4988.4  814.55  4988.9  813.75  4993.9  813.75  4994.4  814.55  4997.6  814.55
  5001.1  816.18    5086  819.93  5156.7  821.18    5185  822.67  5234.5  823.36
  5305.2  825.98  5312.3  825.71  5446.6  828.04  5524.4  827.72  5615.5  828.28
#Mann= 3 ,-1 , 0
  4609.1      .1       0  4988.4     .07       0  4994.4      .1       0
Bank Sta=4988.4,4994.4
XS Rating Curve= 0 ,0
Exp/Cntr=0.3,0.1

Type RM Length L Ch R = 1 ,2522    ,59,59,59
BEGIN DESCRIPTION:
UNT 034 in HW 4.0
END DESCRIPTION:
XS GIS Cut Line= 4
      1987840.54      13650210.5      1987515.04     13650200.09
      1987163.48     13650296.44      1986813.46     13650490.89
#Sta/Elev= 30
  4463.8  831.71  4529.4  831.39  4539.4  830.58  4599.4  828.58  4729.5  821.66
    4787  819.22  4826.4  817.71  4831.6  818.56  4851.7  818.34  4893.2  816.56
  4905.7  815.38  4934.7  813.97  4945.3   812.6  4974.6  811.94  4993.9  810.83
  4994.4  810.03  4999.4  810.03  4999.9  810.83  5093.6  812.62  5121.3  813.82
    5142  816.14  5209.5  819.97  5278.1  821.37  5403.3  823.01  5415.4  822.74
  5430.8  823.02  5446.8  824.42  5452.5  823.54  5468.5  823.24  5554.4  823.93
#Mann= 3 ,-1 , 0
  4463.8      .1       0  4993.9     .07       0  4999.9      .1       0
Bank Sta=4893.2,5142
XS Rating Curve= 0 ,0
Exp/Cntr=0.3,0.1

Type RM Length L Ch R = 1 ,2463    ,433,433,433
BEGIN DESCRIPTION:
Mapping XS 179a0a00
END DESCRIPTION:
XS GIS Cut Line= 6
      1987837.96     13650129.77      1987585.35     13650114.15
      1987280.66      13650210.5      1987236.39     13650228.73
      1986996.81     13650262.59      1986804.33     13650460.27
#Sta/Elev= 30
  4416.7  828.26  4429.7  828.73  4509.8  827.73  4687.5  821.13  4692.8  821.44
  4743.6  819.99  4764.6  818.64  4806.5  818.06  4816.8  818.93    4838  817.34
  4911.4  815.13  4974.3  811.21  5006.3  811.13  5015.4  810.53  5015.9  809.73
  5020.9  809.73  5021.4  810.53  5089.1  811.59  5129.5  814.94  5139.6  815.75
  5159.8  815.93  5169.9  817.59  5187.2  817.64  5192.2   818.6  5200.2   818.1
  5210.3  819.68  5338.7  820.22  5444.9  822.47  5536.7  822.93  5555.1  823.54
#Mann= 3 ,-1 , 0
  4416.7      .1       0  5015.4     .07       0  5021.4      .1       0
Bank Sta=4911.4,5129.5
XS Rating Curve= 0 ,0
Exp/Cntr=0.3,0.1

Type RM Length L Ch R = 1 ,2030    ,252,252,252
BEGIN DESCRIPTION:
UNT 034 in HW 3.0
END DESCRIPTION:
XS GIS Cut Line= 4
      1987640.08     13649939.67      1987207.75     13649926.65
      1986772.85     13650002.17      1986533.93     13650300.83
#Sta/Elev= 30
  4330.7  818.46  4385.8   817.8  4505.9  818.39  4515.9  817.63  4651.4  815.02
  4705.9   815.1    4736  813.75  4857.4  811.93  4877.7  811.07  4908.1  808.32
  4948.7  806.86    4969  807.22  4979.2  806.99  4989.3  805.72  4996.5  804.02
    4997  803.22    5002  803.22  5002.5  804.02  5020.7  806.97  5029.9   807.1
  5070.2  807.34  5090.8   808.9    5101   808.6  5129.9  812.06  5161.9  817.01
  5206.9  817.93  5233.9  819.38  5291.3  819.82  5322.7  820.48  5587.1  822.44
#Mann= 5 ,-1 , 0
  4330.7      .1       0  4996.5     .07       0  5002.5      .1       0
  5291.3     .16       0  5322.7      .1       0
Bank Sta=4969,5029.9
XS Rating Curve= 0 ,0
Exp/Cntr=0.3,0.1

Type RM Length L Ch R = 1 ,1778    ,47,47,47
BEGIN DESCRIPTION:
Mapping XS 711a0fa9
END DESCRIPTION:
XS GIS Cut Line= 4
      1987598.42      13649890.2      1986923.89     13649744.36
      1986725.98     13649749.57      1986353.62     13649924.03
#Sta/Elev= 30
  4267.6  816.18  4352.9  817.06  4434.8  816.63    4578  814.37  4645.8  812.66
    4695  812.51  4772.4  808.98  4813.3  806.04  4915.7  806.12  4936.1  804.75
  4954.6  800.91  4993.6  800.42  4994.1  799.62  4999.1  799.62  4999.6  800.42
  5016.6  800.66  5026.6   801.5  5046.6  804.69  5056.6  805.56    5116  805.83
  5136.7  806.75  5153.7  810.63  5159.5  811.04  5176.8  814.45  5205.2  816.73
  5387.8  816.66  5391.4  816.82  5461.8  815.87  5512.3  816.24  5566.9   816.3
#Mann= 7 ,-1 , 0
  4267.6      .1       0  4993.6     .07       0  4999.6      .1       0
    5116     .16       0  5387.8      .1       0  5391.4     .16       0
  5512.3      .1       0
Bank Sta=4993.6,4999.6
XS Rating Curve= 0 ,0
Exp/Cntr=0.3,0.1

Type RM Length L Ch R = 1 ,1731    ,52,52,52
BEGIN DESCRIPTION:
UNT 034 in HW 2.0
END DESCRIPTION:
XS GIS Cut Line= 4
      1987645.22     13649861.54       1986991.6     13649702.69
      1986689.52     13649689.67      1986319.82     13649884.93
#Sta/Elev= 30
  4216.1  818.58  4310.7  814.85  4389.1   816.4  4430.8  816.09  4669.1  811.87
  4710.3  809.33  4728.2  808.97  4733.4  807.84  4792.6  805.25  4802.9  805.82
  4856.8   805.2  4892.4  804.87  4892.9  804.07  4897.9  804.07  4898.4  804.87
  4925.4  806.18  4950.8   810.8  4977.3  810.92  5055.5  810.95  5085.3  810.28
  5145.6   808.1  5175.6  810.92    5182  812.65    5187   812.2  5190.9  813.69
  5218.9  815.22  5309.3     816  5388.9  815.58  5554.1  814.45  5609.2  814.98
#Mann= 7 ,-1 , 0
  4216.1      .1       0  4856.8     .16       0  4892.4     .07       0
  4898.4     .16       0  4977.3      .1       0  5085.3     .16       0
  5388.9      .1       0
Bank Sta=4892.4,4898.4
XS Rating Curve= 0 ,0
Exp/Cntr=0.3,0.1

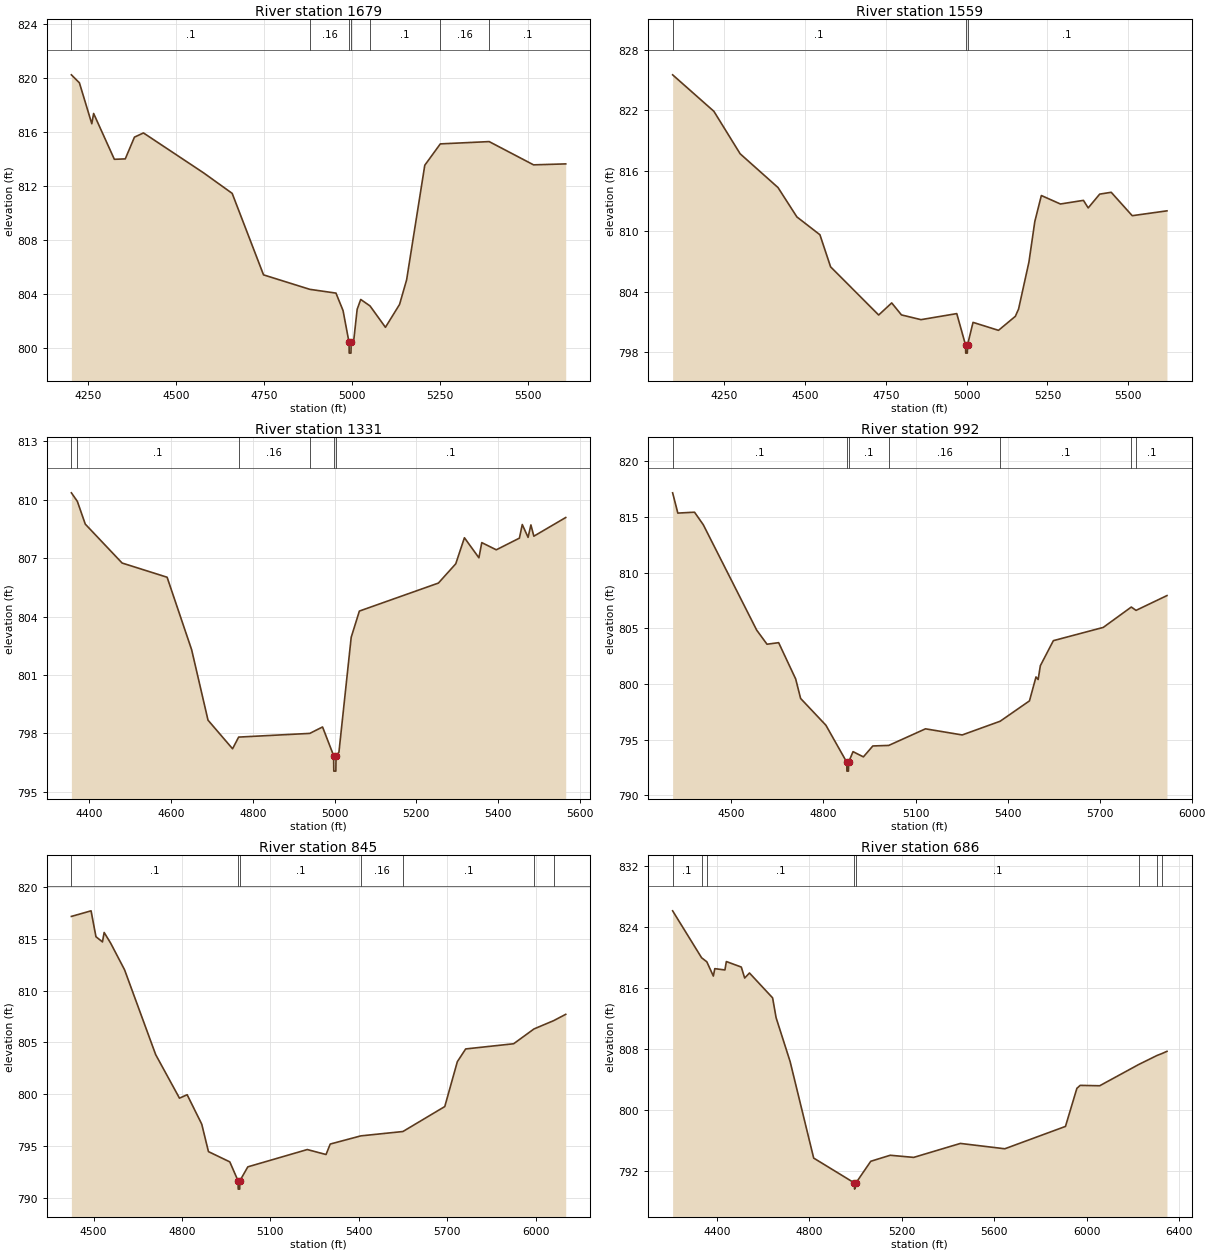
Type RM Length L Ch R = 1 ,1679    ,120,120,120
BEGIN DESCRIPTION:
Mapping XS b8faa07e
END DESCRIPTION:
XS GIS Cut Line= 4
      1987653.09     13649835.51      1986957.75     13649653.21
       1986679.1     13649629.77      1986328.75     13649834.79
#Sta/Elev= 30
  4202.8  820.24  4225.6  819.65  4260.8  816.62    4266  817.38  4324.9  813.99
  4355.9  814.02    4382  815.63  4407.6  815.94  4578.8  812.98  4659.6  811.47
  4748.7  805.44  4880.1  804.37  4954.5  804.09  4974.6   802.8  4991.6  800.45
  4992.1  799.65  4997.1  799.65  4997.6  800.45  5004.7  800.53  5014.7  802.89
  5024.8  803.62  5051.3  803.14    5095  801.56  5135.1  803.25  5155.2  805.07
  5206.8  813.55  5250.9  815.13  5389.7   815.3  5515.8  813.58  5607.2  813.65
#Mann= 7 ,-1 , 0
  4202.8      .1       0  4880.1     .16       0  4991.6     .07       0
  4997.6     .16       0  5051.3      .1       0  5250.9     .16       0
  5389.7      .1       0
Bank Sta=4991.6,4997.6
XS Rating Curve= 0 ,0
Exp/Cntr=0.3,0.1

Type RM Length L Ch R = 1 ,1559    ,228,228,228
BEGIN DESCRIPTION:
Mapping XS 36a6423a
END DESCRIPTION:
XS GIS Cut Line= 4
      1987757.26     13649661.03      1987194.73     13649491.75
      1986603.58     13649559.46      1986322.33     13649762.59
#Sta/Elev= 30
  4090.4  825.49  4218.1  821.87  4299.3  817.66  4416.5  814.31  4474.8   811.4
  4546.1  809.63  4579.1  806.45  4727.9  801.67  4768.2  802.87  4798.4  801.68
  4858.8  801.21  4969.5  801.81  4996.7  798.69  4997.2  797.89  5002.2  797.89
  5002.7  798.69  5019.8  800.94  5098.6  800.15  5150.7  801.54  5160.7  802.26
  5192.8  806.93    5211  810.95  5231.2  813.52  5290.2  812.68  5361.4  813.04
  5376.1  812.29  5411.7  813.66  5447.3  813.84  5512.3  811.52  5619.8     812
#Mann= 3 ,-1 , 0
  4090.4      .1       0  4996.7     .07       0  5002.7      .1       0
Bank Sta=4996.7,5002.7
XS Rating Curve= 0 ,0
Exp/Cntr=0.3,0.1

Type RM Length L Ch R = 1 ,1331    ,339,339,339
BEGIN DESCRIPTION:
Mapping XS 1cff5e98
END DESCRIPTION:
XS GIS Cut Line= 3
      1987449.02     13649325.95       1986676.5     13649330.29
      1986363.98     13649634.13
#Sta/Elev= 30
  4356.8  810.36  4371.4  809.92  4390.8  808.75  4480.8  806.75  4590.8  806.02
  4650.8  802.29  4690.8  798.67  4750.8   797.2  4765.7   797.8  4939.5  797.99
  4970.8  798.32  4997.8  796.85  4998.3  796.05  5003.3  796.05  5003.8  796.85
  5010.8  797.02  5040.8  802.93  5060.8  804.28    5254  805.72  5296.4  806.71
  5317.6  808.05    5353  807.02    5360   807.8  5395.5  807.43    5452  808.03
    5459  808.73  5473.2  808.07  5480.1  808.71  5487.3  808.13  5565.2  809.09
#Mann= 6 ,-1 , 0
  4356.8     .16       0  4371.4      .1       0  4765.7     .16       0
  4939.5      .1       0  4997.8     .07       0  5003.8      .1       0
Bank Sta=4997.8,5003.8
XS Rating Curve= 0 ,0
Exp/Cntr=0.3,0.1

Type RM Length L Ch R = 1 ,992     ,147,147,147
BEGIN DESCRIPTION:
Mapping XS 2b6ece5a
END DESCRIPTION:
XS GIS Cut Line= 3
      1987622.71     13649204.43      1986798.03     13649026.48
      1986264.19     13649577.68
#Sta/Elev= 30
  4308.5  817.18  4325.5  815.36  4379.9  815.44  4408.5  814.31  4582.4  804.85
  4616.1  803.58    4654  803.72  4709.5  800.46  4725.6  798.71  4808.1   796.3
    4876  792.98  4876.5  792.18  4881.5  792.18    4882  792.98  4896.4  793.93
  4930.2  793.46  4960.9  794.44  5012.9  794.49  5132.6  795.98  5252.2  795.43
  5375.8  796.66  5471.4  798.49  5492.7  800.64  5499.7  800.41  5506.9  801.65
  5549.3   803.9  5711.9  805.09  5803.3  806.92  5818.7  806.62  5919.5  807.95
#Mann= 7 ,-1 , 0
  4308.5      .1       0    4876     .07       0    4882      .1       0
  5012.9     .16       0  5375.8      .1       0  5803.3     .16       0
  5818.7      .1       0
Bank Sta=4876,4882
XS Rating Curve= 0 ,0
Exp/Cntr=0.3,0.1

Type RM Length L Ch R = 1 ,845     ,159,159,159
BEGIN DESCRIPTION:
Mapping XS f37499e4
END DESCRIPTION:
XS GIS Cut Line= 4
      1987600.98      13649169.7      1987440.39     13649087.24
      1986828.41     13648926.65      1986239.25     13649559.13
#Sta/Elev= 30
  4424.5  817.16  4491.3   817.7  4507.9   815.2    4530   814.7  4535.7  815.61
  4557.8  814.58    4605  812.01  4710.6  803.82  4791.3  799.62  4817.4  799.95
  4866.9  797.11  4889.7  794.46  4962.1  793.47  4990.2  791.64  4990.7  790.84
  4995.7  790.84  4996.2  791.64  5023.3  792.99  5225.1  794.66  5288.7  794.18
  5302.9  795.19  5406.9  795.98  5549.6   796.4  5691.7  798.81  5734.3  803.14
  5762.6  804.37  5925.3  804.87  5994.4   806.3  6061.1   807.1  6102.1  807.71
#Mann= 7 ,-1 , 0
  4424.5      .1       0  4990.2     .07       0  4996.2      .1       0
  5406.9     .16       0  5549.6      .1       0  5994.4     .16       0
  6061.1      .1       0
Bank Sta=4990.2,4996.2
XS Rating Curve= 0 ,0
Exp/Cntr=0.3,0.1

Type RM Length L Ch R = 1 ,686     ,0,0,0
BEGIN DESCRIPTION:
UNT 034 in HW 1.0
END DESCRIPTION:
XS GIS Cut Line= 4
       1987809.3     13649286.88      1987453.41     13649022.13
      1986889.17     13648744.36      1986199.67     13649559.61
#Sta/Elev= 30
    4208  826.14  4333.4  819.99    4356  819.46  4384.3  817.59  4390.6  818.56
  4434.4  818.39  4440.6  819.49  4505.3  818.77  4519.9  817.33  4540.7  817.99
  4640.9  814.73  4655.9  812.14  4716.7  806.38  4818.7  793.73  4995.4  790.46
  4995.9  789.66  5001.4  790.46  5065.8  793.31  5150.1   794.1  5251.7  793.82
  5453.8  795.65  5646.2  794.95  5908.8  797.88  5958.2  802.87  5972.5  803.26
    6057  803.21  6225.5  805.99  6305.2  807.18  6326.4  807.43  6348.2  807.72
#Mann= 8 ,-1 , 0
    4208      .1       0  4333.4     .16       0    4356      .1       0
  4995.4     .07       0  5001.4      .1       0  6225.5     .16       0
  6305.2      .1       0  6326.4     .16       0
Bank Sta=4995.4,5001.4
XS Rating Curve= 0 ,0
Exp/Cntr=0.3,0.1
LCMann Table=0

Chan Stop Cuts=-1
Use User Specified Reach Order=0
Composite Channel Slope=5