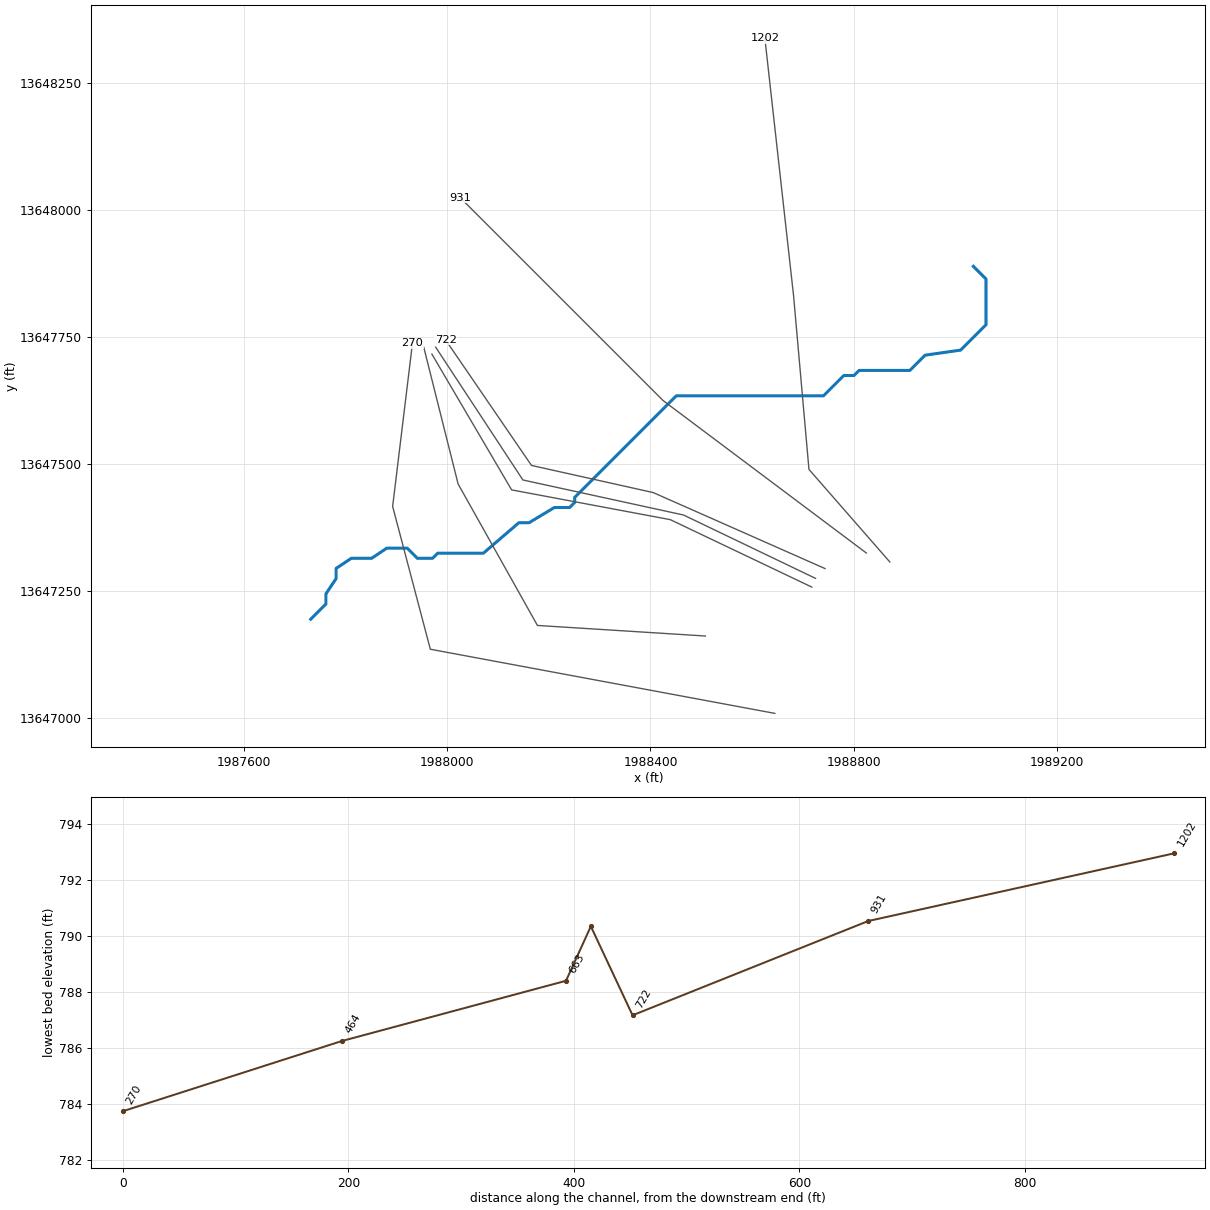
--- UNT 035 in HW.prj (project) ---

Proj Title=UNT 035 in HW Base Level Engineering
Current Plan=p01
Default Exp/Contr=0.3,0.1
English Units
Geom File=g01
Flow File=f01
Plan File=p01
BEGIN DESCRIPTION:
UNT 035 in HW
END DESCRIPTION:

--- UNT 035 in HW.p01 (plan) ---

Plan Title=Multiple Run
Short Identifier=Multiple
Geom File=g01
Flow File=f01
Subcritical Flow
K Sum by GR= 0
Std Step Tol= 0.01
Critical Tol= 0.01
Num of Std Step Trials= 20
Max Error Tol= 0.3
Flow Tol Ratio= 0.001
Split Flow NTrial= 30
Split Flow Tol= 0.02
Split Flow Ratio= 0.02
Log Output Level= 0
Friction Slope Method= 1
Unsteady Friction Slope Method= 2
Unsteady Bridges Friction Slope Method= 1
Parabolic Critical Depth
Global Vel Dist=  1 , 1 , 1
Global Log Level= 0
CheckData=True
Encroach Param= -1, 0, 0, 0
BEGIN DESCRIPTION:
Multiple Run
END DESCRIPTION:

--- UNT 035 in HW.f01 (steady flow) ---

Flow Title=Multiple
Number of Profiles=7
Profile Names=10-year,25-year,50-year,1pct_min,100-year,1pct_plu,500-year
River Rch & RM= UNT 035 in HW,Reach-1,1202
     525     740     920     568    1133    2261    1722
Boundary for River Rch & Prof#=UNT 035 in HW,Reach-1,1
Up Type=0
Dn Type=3
Dn Slope=0.005
Boundary for River Rch & Prof#=UNT 035 in HW,Reach-1,2
Up Type=0
Dn Type=3
Dn Slope=0.005
Boundary for River Rch & Prof#=UNT 035 in HW,Reach-1,3
Up Type=0
Dn Type=3
Dn Slope=0.005
Boundary for River Rch & Prof#=UNT 035 in HW,Reach-1,4
Up Type=0
Dn Type=3
Dn Slope=0.005
Boundary for River Rch & Prof#=UNT 035 in HW,Reach-1,5
Up Type=0
Dn Type=3
Dn Slope=0.005
Boundary for River Rch & Prof#=UNT 035 in HW,Reach-1,6
Up Type=0
Dn Type=3
Dn Slope=0.005
Boundary for River Rch & Prof#=UNT 035 in HW,Reach-1,7
Up Type=0
Dn Type=3
Dn Slope=0.005

--- UNT 035 in HW.g01 (geometry) ---

Geom Title=Existing Conditions

River Reach=UNT 035 in HW,Reach-1
Reach XY= 30
      1989035.80     13647889.54      1989060.80     13647864.54
      1989060.80     13647774.54      1989010.80     13647724.54
      1988940.80     13647714.54      1988910.80     13647684.54
      1988810.80     13647684.54      1988800.80     13647674.54
      1988780.80     13647674.54      1988740.80     13647634.54
      1988450.80     13647634.54      1988250.80     13647434.54
      1988250.80     13647424.54      1988240.80     13647414.54
      1988210.80     13647414.54      1988160.80     13647384.54
      1988140.80     13647384.54      1988070.80     13647324.54
      1987980.80     13647324.54      1987970.80     13647314.54
      1987940.80     13647314.54      1987920.80     13647334.54
      1987880.80     13647334.54      1987850.80     13647314.54
      1987810.80     13647314.54      1987780.80     13647294.54
      1987780.80     13647274.54      1987760.80     13647244.54
      1987760.80     13647224.54      1987730.80     13647194.54

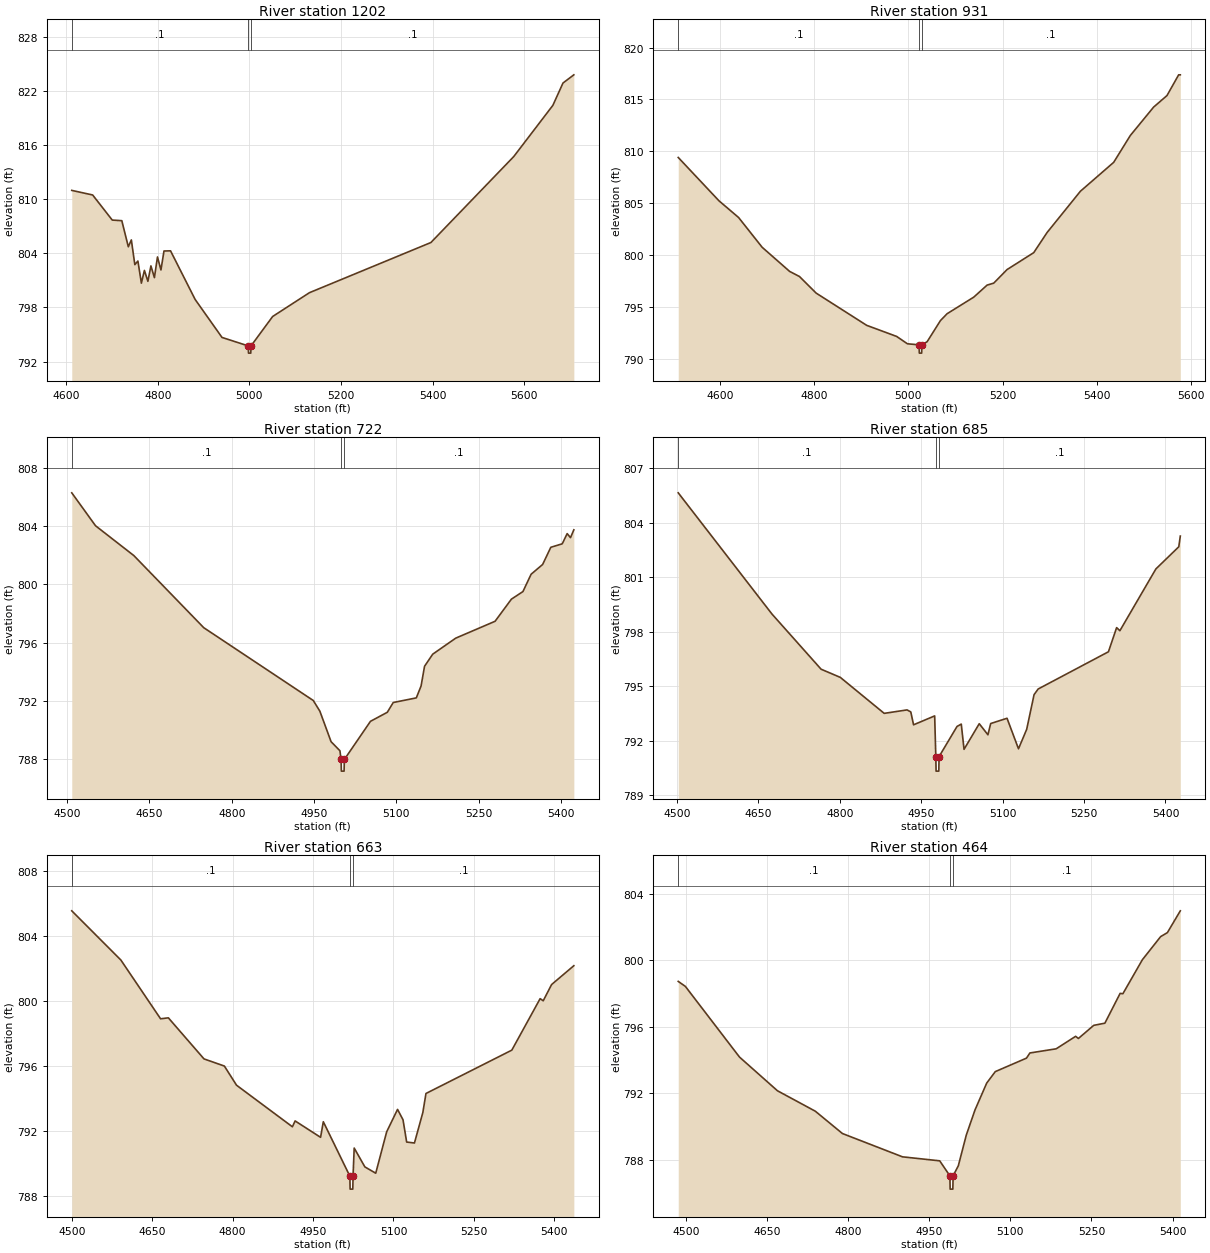
Type RM Length L Ch R = 1,1202,271,271,271
BEGIN DESCRIPTION:
UNT 035 in HW 4.0
END DESCRIPTION:
XS GIS Cut Line= 4
      1988871.37     13647307.29      1988712.09     13647489.58
      1988681.71     13647832.46      1988625.28     13648338.53
#Sta/Elev= 30
  4612.4  810.98  4658.0  810.47  4700.7  807.69  4721.6  807.62  4735.8  804.73
  4742.4  805.49  4750.0  802.75  4756.7  803.15  4764.3  800.70  4770.9  802.11
  4778.5  800.90  4785.1  802.61  4792.7  801.31  4799.4  803.60  4807.0  802.16
  4813.6  804.26  4827.9  804.28  4881.6  798.89  4940.2  794.68  4997.5  793.74
  4998.0  792.94  5003.0  792.94  5003.5  793.74  5050.7  797.00  5131.0  799.64
  5396.0  805.20  5576.8  814.73  5662.2  820.41  5684.2  822.88  5707.9  823.79
#Mann=3,-1,0
  4612.4     0.1       0  4997.5    0.07       0  5003.5     0.1       0
Bank Sta=4997.5,5003.5
Exp/Cntr=0.3,0.1

Type RM Length L Ch R = 1,931,209,209,209
BEGIN DESCRIPTION:
UNT 035 in HW 3.0
END DESCRIPTION:
XS GIS Cut Line= 3
      1988825.01     13647324.99      1988425.00     13647625.00
      1988025.00     13648025.00
#Sta/Elev= 30
  4511.6  809.40  4598.1  805.22  4639.7  803.61  4689.7  800.74  4748.1  798.41
  4768.9  797.92  4804.3  796.32  4911.6  793.21  4975.2  792.14  4998.1  791.43
  5022.8  791.33  5023.3  790.53  5028.3  790.53  5028.8  791.33  5039.9  791.63
  5068.2  793.67  5082.3  794.33  5138.9  795.93  5167.2  797.09  5181.3  797.28
  5209.6  798.59  5266.2  800.22  5294.5  802.16  5365.2  806.14  5435.9  808.93
  5471.2  811.52  5520.7  814.26  5549.0  815.37  5573.8  817.37  5577.3  817.37
#Mann=3,-1,0
  4511.6     0.1       0  5022.8    0.07       0  5028.8     0.1       0
Bank Sta=5022.8,5028.8
Exp/Cntr=0.3,0.1

Type RM Length L Ch R = 1,722,37,37,37
BEGIN DESCRIPTION:
Mapping XS 4c9ee9af
END DESCRIPTION:
XS GIS Cut Line= 4
      1988743.74     13647294.28      1988405.23     13647444.01
      1988165.65     13647497.40      1987996.36     13647744.82
#Sta/Elev= 30
  4508.4  806.28  4551.7  804.02  4621.6  801.97  4749.0  797.02  4948.7  792.02
  4960.7  791.29  4981.2  789.19  4997.3  788.57  4999.4  787.97  4999.9  787.17
  5004.9  787.17  5005.4  787.97  5053.0  790.59  5083.7  791.21  5094.5  791.88
  5136.6  792.20  5145.3  793.02  5151.6  794.37  5166.5  795.20  5208.4  796.30
  5280.2  797.46  5310.0  798.98  5331.0  799.50  5345.9  800.69  5366.9  801.36
  5381.8  802.54  5402.7  802.78  5411.6  803.48  5417.7  803.20  5423.8  803.74
#Mann=3,-1,0
  4508.4     0.1       0  4999.4    0.07       0  5005.4     0.1       0
Bank Sta=4999.4,5005.4
Exp/Cntr=0.3,0.1

Type RM Length L Ch R = 1,685,22,22,22
BEGIN DESCRIPTION:
UNT 035 in HW 2.0
END DESCRIPTION:
XS GIS Cut Line= 4
      1988725.01     13647274.99      1988465.13     13647399.74
      1988148.72     13647468.75      1987977.02     13647730.19
#Sta/Elev= 30
  4502.4  805.66  4675.0  798.99  4765.6  795.95  4801.0  795.50  4881.8  793.52
  4923.9  793.71  4930.8  793.60  4935.9  792.89  4974.8  793.38  4976.9  791.14
  4977.4  790.34  4982.4  790.34  4982.9  791.14  5016.0  792.80  5023.8  792.93
  5028.9  791.54  5056.9  792.95  5072.9  792.34  5078.0  792.96  5108.1  793.25
  5129.2  791.57  5144.3  792.64  5157.9  794.55  5165.4  794.86  5294.9  796.91
  5310.0  798.24  5316.0  798.07  5382.3  801.47  5424.5  802.69  5427.3  803.28
#Mann=3,-1,0
  4502.4     0.1       0  4976.9    0.07       0  4982.9     0.1       0
Bank Sta=4976.9,4982.9
Exp/Cntr=0.3,0.1

Type RM Length L Ch R = 1,663,199,199,199
BEGIN DESCRIPTION:
Mapping XS c92cdc45
END DESCRIPTION:
XS GIS Cut Line= 4
      1988717.69     13647257.83      1988439.08     13647390.62
      1988126.58     13647449.22      1987969.52     13647716.62
#Sta/Elev= 30
  4499.8  805.54  4591.4  802.51  4665.5  798.89  4680.0  798.95  4746.5  796.42
  4784.5  795.98  4807.2  794.80  4911.4  792.24  4916.5  792.60  4964.0  791.59
  4969.1  792.55  5018.6  789.20  5019.1  788.40  5024.1  788.40  5024.6  789.20
  5026.7  790.93  5046.6  789.77  5066.9  789.38  5087.3  791.93  5107.6  793.31
  5117.8  792.67  5124.6  791.30  5139.1  791.24  5154.8  793.12  5160.6  794.29
  5320.8  796.96  5373.6  800.13  5379.4  800.00  5395.0  801.00  5436.5  802.16
#Mann=3,-1,0
  4499.8     0.1       0  5018.6    0.07       0  5024.6     0.1       0
Bank Sta=5018.6,5024.6
Exp/Cntr=0.3,0.1

Type RM Length L Ch R = 1,464,194,194,194
BEGIN DESCRIPTION:
Mapping XS 7a6d1fb9
END DESCRIPTION:
XS GIS Cut Line= 4
      1988508.14     13647161.46      1988177.37     13647182.29
      1988021.12     13647460.94      1987953.46     13647730.28
#Sta/Elev= 30
  4485.8  798.73  4499.0  798.43  4599.2  794.18  4669.3  792.16  4739.4  790.93
  4789.5  789.59  4900.6  788.19  4969.4  787.95  4988.2  787.05  4988.7  786.25
  4993.7  786.25  4994.2  787.05  5003.8  787.65  5018.6  789.50  5034.6  791.00
  5056.3  792.62  5072.2  793.31  5129.9  794.12  5136.2  794.43  5184.8  794.68
  5220.8  795.43  5225.9  795.30  5254.3  796.09  5274.9  796.22  5303.1  798.01
  5308.2  797.99  5344.2  800.03  5378.0  801.42  5390.5  801.66  5414.4  802.97
#Mann=3,-1,0
  4485.8     0.1       0  4988.2    0.07       0  4994.2     0.1       0
Bank Sta=4988.2,4994.2
Exp/Cntr=0.3,0.1

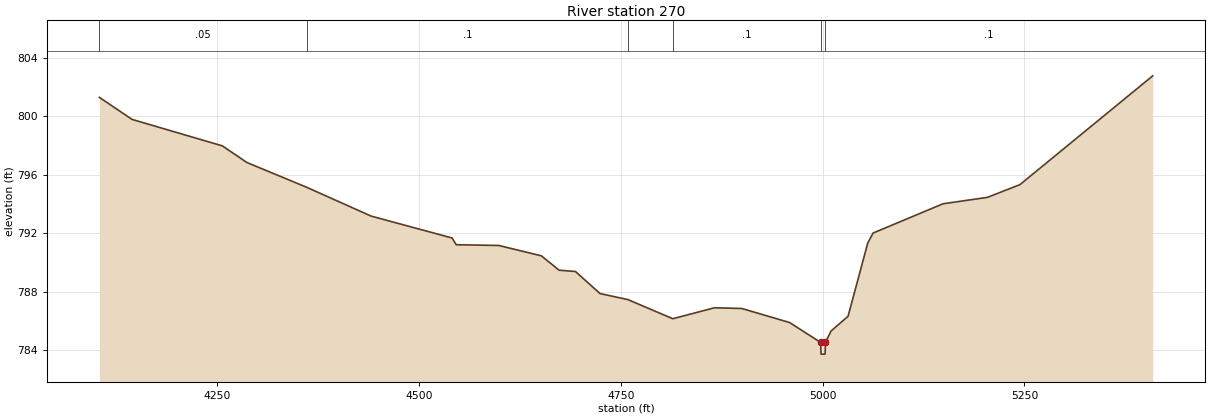
Type RM Length L Ch R = 1,270,0,0,0
BEGIN DESCRIPTION:
UNT 035 in HW 1.0
END DESCRIPTION:
XS GIS Cut Line= 4
      1988644.83     13647009.11      1987966.43     13647135.42
      1987892.21     13647416.67      1987931.27     13647738.26
#Sta/Elev= 30
  4104.0  801.31  4144.5  799.80  4256.4  797.99  4286.9  796.85  4361.2  795.15
  4440.6  793.19  4541.0  791.69  4546.1  791.23  4598.9  791.18  4651.6  790.47
  4673.5  789.49  4693.8  789.40  4724.3  787.89  4758.7  787.48  4814.4  786.17
  4866.0  786.92  4899.9  786.87  4959.1  785.91  4997.5  784.55  4998.0  783.75
  5003.0  783.75  5003.5  784.55  5010.4  785.33  5031.5  786.34  5055.9  791.35
  5062.5  792.03  5149.1  794.03  5204.1  794.47  5244.4  795.34  5408.9  802.78
#Mann=6,-1,0
  4104.0    0.05       0  4361.2     0.1       0  4758.7    0.05       0
  4814.4     0.1       0  4997.5    0.07       0  5003.5     0.1       0
Bank Sta=4997.5,5003.5
Exp/Cntr=0.3,0.1

Chan Stop Cuts=-1