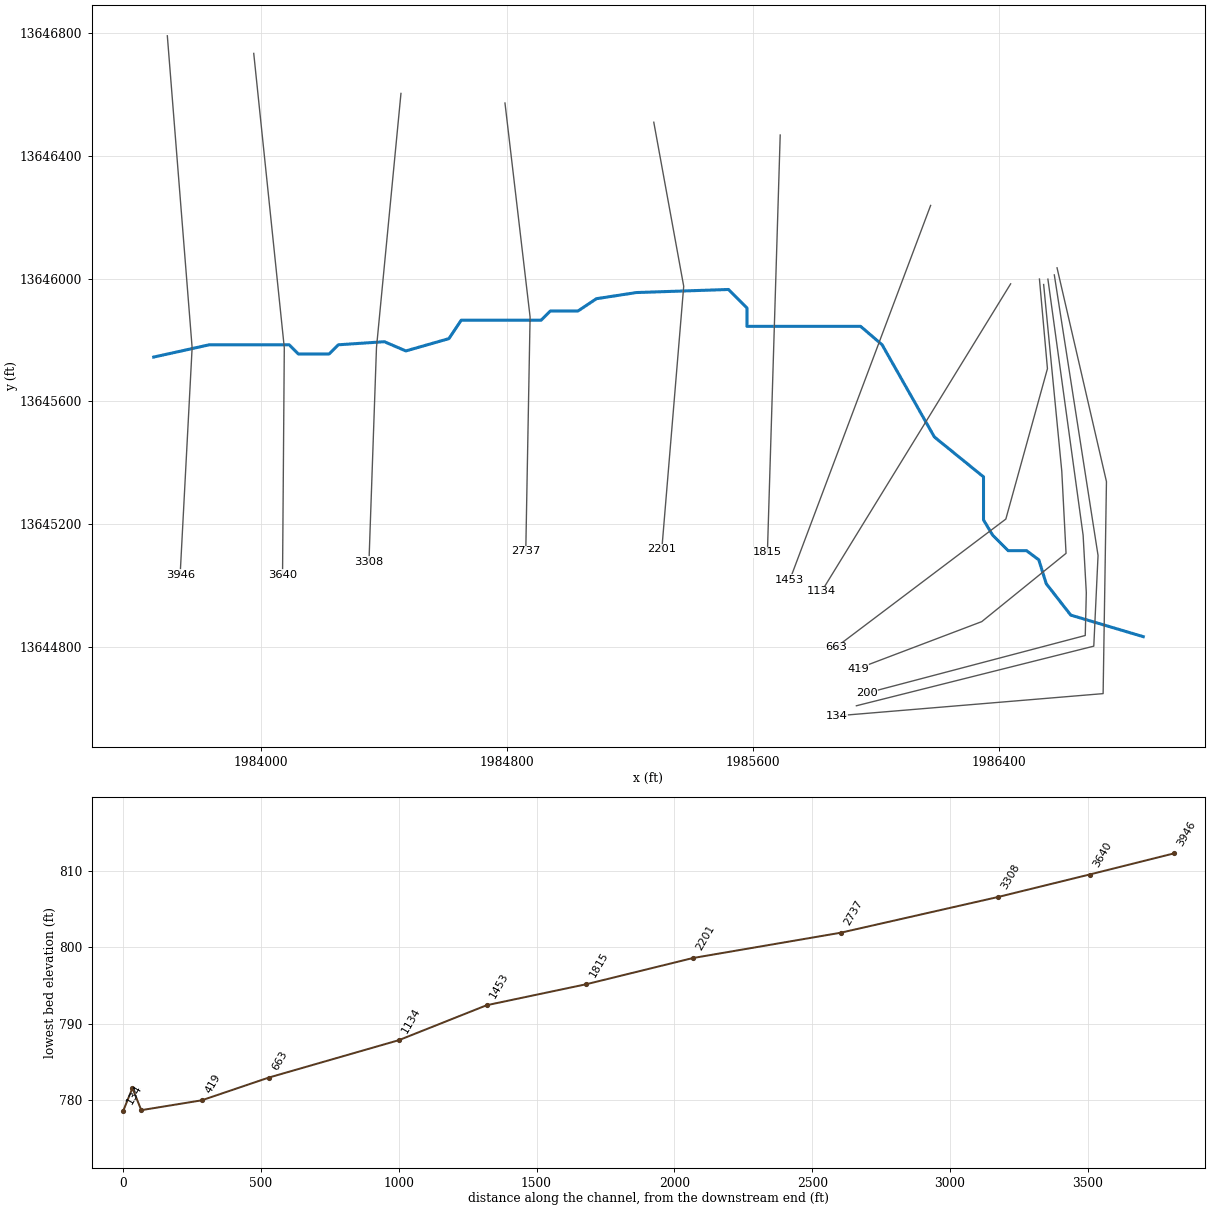
--- UNT 036 in HW.prj (project) ---

Proj Title=UNT 036 in HW Base Level Engineering
Current Plan=p01
Default Exp/Contr=0.3,0.1
English Units
Geom File=g01
Flow File=f01
Plan File=p01
Y Axis Title=Elevation
X Axis Title(PF)=Main Channel Distance
X Axis Title(XS)=Station
BEGIN DESCRIPTION:
UNT 036 in HW
END DESCRIPTION:
DSS Export Rating Curves= 0
DSS Export Rating Curve Sorted= 0
DSS Export Volume Flow Curves= 0
DXF OffsetX= 0
DXF OffsetY= 0
DXF ScaleX= 1
DXF ScaleY= 10

--- UNT 036 in HW.p01 (plan) ---

Plan Title=Multiple Run
Short Identifier=Multiple
Geom File=g01
Flow File=f01
Subcritical Flow
K Sum by GR= 0
Std Step Tol= 0.01
Critical Tol= 0.01
Num of Std Step Trials= 20
Max Error Tol= 0.3
Flow Tol Ratio= 0.001
Split Flow NTrial= 30
Split Flow Tol= 0.02
Split Flow Ratio= 0.02
Log Output Level= 0
Friction Slope Method= 1
Unsteady Friction Slope Method= 2
Unsteady Bridges Friction Slope Method= 1
Parabolic Critical Depth
Global Vel Dist=  1 , 1 , 1
Global Log Level= 0
CheckData=True
Encroach Param= -1, 0, 0, 0
BEGIN DESCRIPTION:
Multiple Run
END DESCRIPTION:

--- UNT 036 in HW.f01 (steady flow) ---

Flow Title=Multiple
Number of Profiles=7
Profile Names=10-year,25-year,50-year,1pct_min,100-year,1pct_plu,500-year
River Rch & RM= UNT 036 in HW,Reach-1,3946
     583     820    1018     627    1250    2495    1891
Boundary for River Rch & Prof#=UNT 036 in HW,Reach-1,1
Up Type=0
Dn Type=3
Dn Slope=0.005
Boundary for River Rch & Prof#=UNT 036 in HW,Reach-1,2
Up Type=0
Dn Type=3
Dn Slope=0.005
Boundary for River Rch & Prof#=UNT 036 in HW,Reach-1,3
Up Type=0
Dn Type=3
Dn Slope=0.005
Boundary for River Rch & Prof#=UNT 036 in HW,Reach-1,4
Up Type=0
Dn Type=3
Dn Slope=0.005
Boundary for River Rch & Prof#=UNT 036 in HW,Reach-1,5
Up Type=0
Dn Type=3
Dn Slope=0.005
Boundary for River Rch & Prof#=UNT 036 in HW,Reach-1,6
Up Type=0
Dn Type=3
Dn Slope=0.005
Boundary for River Rch & Prof#=UNT 036 in HW,Reach-1,7
Up Type=0
Dn Type=3
Dn Slope=0.005

--- UNT 036 in HW.g01 (geometry) ---

Geom Title=Existing Conditions
Program Version=5.05

River Reach=UNT 036 in HW   ,Reach-1
Reach XY= 30
      1983649.87     13645744.54       1983830.8     13645784.54
       1984090.8     13645784.54       1984120.8     13645754.54
       1984220.8     13645754.54       1984250.8     13645784.54
       1984400.8     13645794.54       1984470.8     13645764.54
       1984610.8     13645804.54       1984650.8     13645864.54
       1984910.8     13645864.54       1984940.8     13645894.54
       1985030.8     13645894.54       1985090.8     13645934.54
       1985220.8     13645954.54       1985520.8     13645964.54
       1985580.8     13645904.54       1985580.8     13645844.54
       1985950.8     13645844.54       1986020.8     13645784.54
       1986190.8     13645484.54       1986350.8     13645354.54
       1986350.8     13645214.54       1986380.8     13645164.54
       1986430.8     13645114.54       1986490.8     13645114.54
       1986530.8     13645084.54      1986554.83     13645007.14
      1986634.69     13644904.71       1986870.8     13644834.54

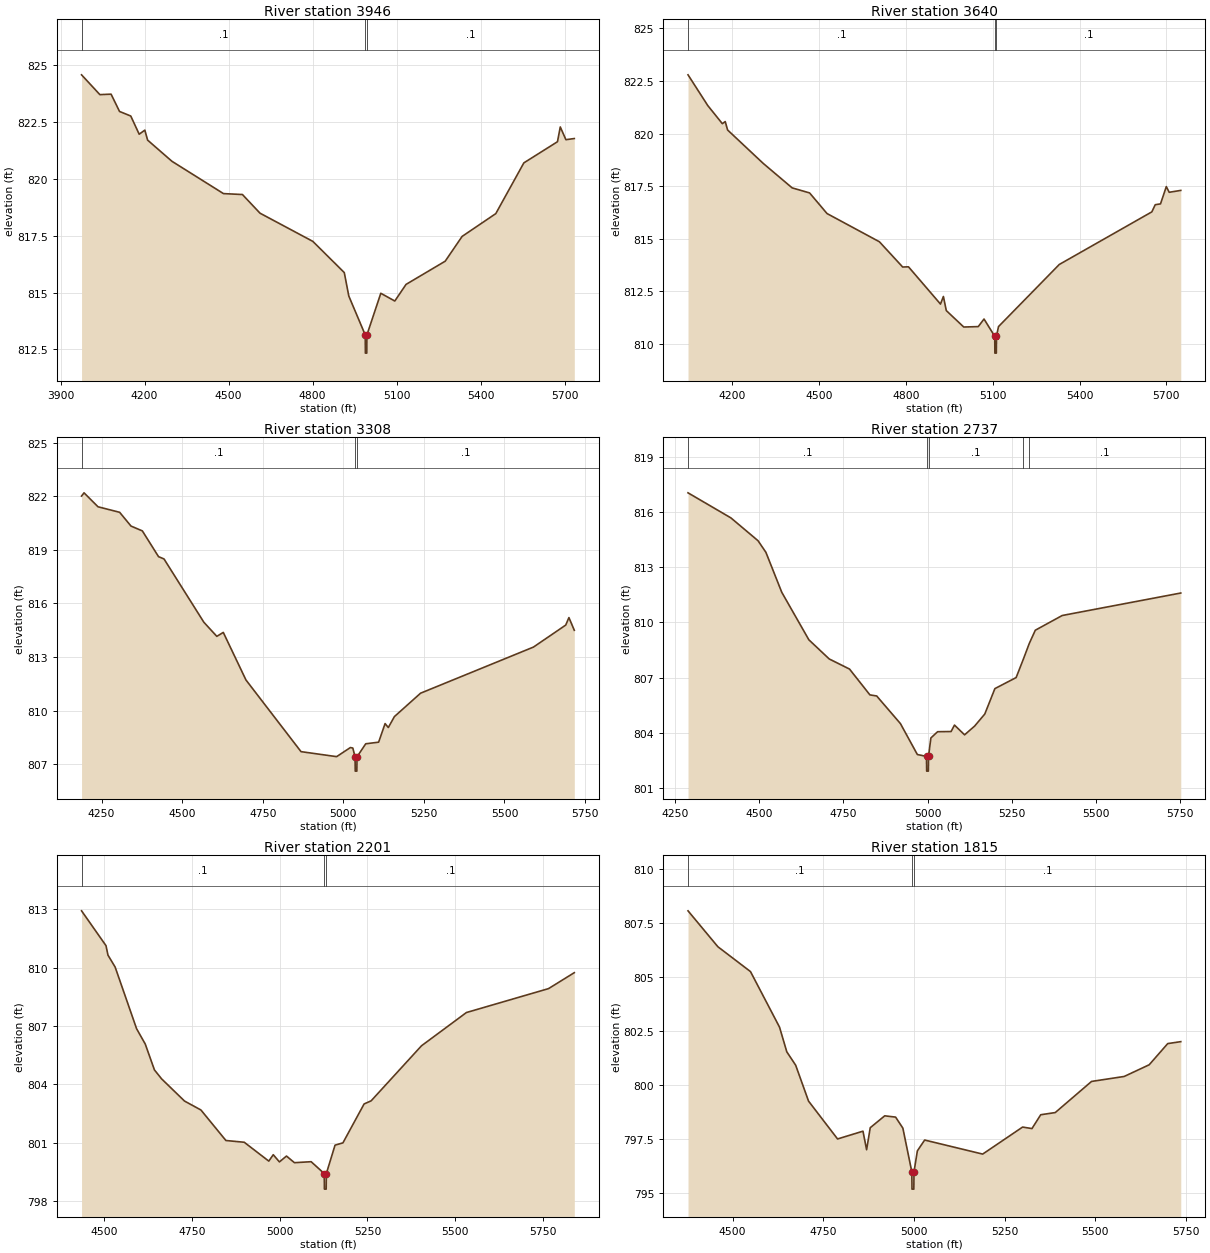
Type RM Length L Ch R = 1 ,3946    ,306,306,306
BEGIN DESCRIPTION:
UNT 036 in HW 6.0
END DESCRIPTION:
XS GIS Cut Line= 3
      1983694.29     13646790.18        1983775.       13645775.
      1983735.96     13645035.01
#Sta/Elev= 30
    3975  824.57  4040.4   823.7  4080.5  823.72  4110.6  822.96  4150.7  822.76
  4180.8  821.96  4200.9  822.14  4210.9   821.7  4297.8  820.77  4481.8  819.35
  4549.4  819.31  4612.2  818.49  4800.9  817.25  4913.1  815.88  4929.2  814.85
  4987.9  813.14  4988.4  812.34  4993.4  812.34  4993.9  813.14  5043.5  814.97
  5093.5  814.63  5133.6  815.36  5273.4  816.38  5333.9  817.47    5454  818.47
  5554.2   820.7  5674.3  821.63  5684.3  822.28  5704.4  821.72  5734.4  821.77
#Mann= 3 ,-1 , 0
    3975      .1       0  4987.9     .07       0  4993.9      .1       0
Bank Sta=4987.9,4993.9
XS Rating Curve= 0 ,0
Exp/Cntr=0.3,0.1

Type RM Length L Ch R = 1 ,3640    ,332,332,332
BEGIN DESCRIPTION:
UNT 036 in HW 5.0
END DESCRIPTION:
XS GIS Cut Line= 3
      1983975.54     13646732.94        1984075.       13645775.
      1984069.29     13645035.01
#Sta/Elev= 30
  4046.5  822.79  4114.8  821.33  4165.1  820.47  4175.1  820.57  4183.3  820.17
  4305.8  818.59  4406.4  817.42  4466.7  817.18    4527   816.2    4708  814.86
  4788.4  813.66  4808.5  813.67  4919.1   811.9  4929.2  812.26  4939.2  811.59
  4999.5  810.81  5049.6  810.83  5069.6  811.19  5106.6  810.37  5107.1  809.57
  5112.1  809.57  5112.6  810.37  5119.6  810.83  5329.6  813.78  5649.6  816.28
  5661.3  816.62  5679.6  816.66  5699.6  817.48  5709.6  817.21  5749.6   817.3
#Mann= 3 ,-1 , 0
  4046.5      .1       0  5106.6     .07       0  5112.6      .1       0
Bank Sta=5106.6,5112.6
XS Rating Curve= 0 ,0
Exp/Cntr=0.3,0.1

Type RM Length L Ch R = 1 ,3308    ,571,571,571
BEGIN DESCRIPTION:
UNT 036 in HW 4.0
END DESCRIPTION:
XS GIS Cut Line= 3
      1984454.71      13646602.7        1984375.       13645775.
       1984350.6     13645078.36
#Sta/Elev= 30
  4188.1  822.01  4195.8  822.19  4239.1  821.41  4306.3   821.1  4341.5  820.33
  4376.7  820.06  4426.9  818.62  4443.9  818.49  4567.5  814.95  4607.7  814.16
  4627.8  814.38  4698.1  811.72  4868.9  807.71  4979.4  807.43  5022.1  807.94
  5029.6  807.91  5036.6  807.42  5037.1  806.62  5042.1  806.62  5042.6  807.42
  5069.7  808.15  5109.7  808.24  5129.7  809.28  5139.7  809.06  5158.6  809.67
  5239.8  810.98    5590  813.56    5690  814.79    5700  815.21  5716.7   814.5
#Mann= 3 ,-1 , 0
  4188.1      .1       0  5036.6     .07       0  5042.6      .1       0
Bank Sta=5036.6,5042.6
XS Rating Curve= 0 ,0
Exp/Cntr=0.3,0.1

Type RM Length L Ch R = 1 ,2737    ,536,536,536
BEGIN DESCRIPTION:
UNT 036 in HW 3.0
END DESCRIPTION:
XS GIS Cut Line= 3
      1984793.25     13646571.45        1984875.       13645875.
      1984860.96     13645113.07
#Sta/Elev= 30
  4288.3  817.04  4415.6  815.68  4496.2  814.44  4519.6  813.81  4566.7  811.64
  4647.2  809.06  4707.6  808.02    4768  807.47  4828.4  806.07  4848.6  806.01
  4919.1  804.51  4969.4  802.83  4996.5  802.73    4997  801.93    5002  801.93
  5002.5  802.73  5009.5  803.73  5029.5  804.07  5069.5  804.08  5079.6  804.43
  5109.6   803.9  5139.6  804.38  5169.6  805.03  5199.6  806.41  5262.7  807.01
  5283.7  807.99  5301.7  808.86  5319.6  809.58  5399.6  810.38  5751.6   811.6
#Mann= 5 ,-1 , 0
  4288.3      .1       0  4996.5     .07       0  5002.5      .1       0
  5283.7     .05       0  5301.7      .1       0
Bank Sta=4996.5,5002.5
XS Rating Curve= 0 ,0
Exp/Cntr=0.3,0.1

Type RM Length L Ch R = 1 ,2201    ,386,386,386
BEGIN DESCRIPTION:
UNT 036 in HW 2.0
END DESCRIPTION:
XS GIS Cut Line= 3
      1985277.62     13646508.96        1985375.       13645975.
      1985303.74     13645119.13
#Sta/Elev= 30
  4436.7  812.92  4506.2  811.13  4511.9  810.64  4532.2  810.03  4593.2  806.86
  4617.9  806.07    4644  804.74  4664.4  804.28  4729.5  803.14  4776.2  802.68
  4847.3  801.11  4899.5  801.02  4969.3  800.05    4982  800.38  4999.5  800.01
  5019.6  800.31  5042.2  799.97  5089.8  800.02    5127  799.41  5127.5  798.61
  5132.5  798.61    5133  799.41  5157.7  800.87  5180.2  800.99  5240.4  802.99
  5260.4  803.15  5403.6  805.98  5531.4  807.69    5765  808.92  5838.3  809.74
#Mann= 3 ,-1 , 0
  4436.7      .1       0    5127     .07       0    5133      .1       0
Bank Sta=5127,5133
XS Rating Curve= 0 ,0
Exp/Cntr=0.3,0.1

Type RM Length L Ch R = 1 ,1815    ,362,362,362
BEGIN DESCRIPTION:
Mapping XS 46e757af
END DESCRIPTION:
XS GIS Cut Line= 2
      1985689.08     13646467.25      1985647.45     13645108.98
#Sta/Elev= 30
    4377  808.05  4459.3  806.39  4549.3  805.24  4629.4  802.67  4649.4  801.53
  4673.9  800.91  4709.4  799.25  4789.4   797.5  4859.5  797.86  4869.5     797
  4879.5  798.02  4919.5  798.57  4949.5  798.51  4969.5     798  4994.2  795.98
  4994.7  795.18  4999.7  795.18  5000.2  795.98  5009.5  796.95  5029.6  797.45
  5189.6   796.8  5299.7  798.05  5325.5  797.98  5349.7  798.62  5389.7  798.72
  5489.8  800.16  5579.8  800.39  5648.8  800.93  5699.9  801.91  5735.9     802
#Mann= 3 ,-1 , 0
    4377      .1       0  4994.2     .07       0  5000.2      .1       0
Bank Sta=4994.2,5000.2
XS Rating Curve= 0 ,0
Exp/Cntr=0.3,0.1

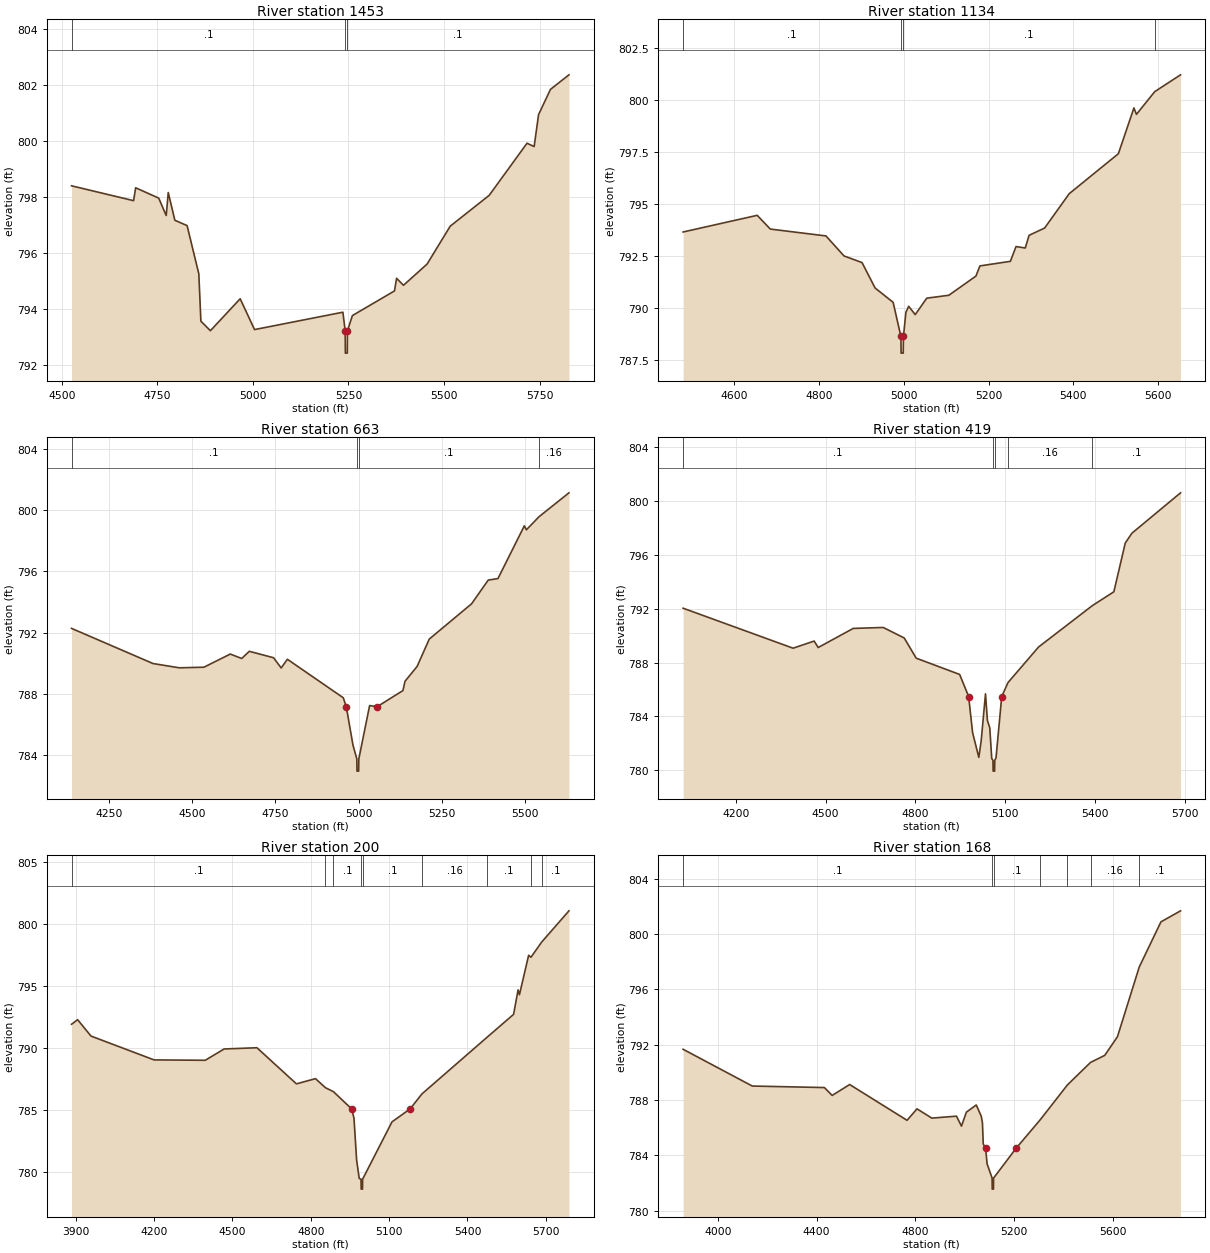
Type RM Length L Ch R = 1 ,1453    ,319,319,319
BEGIN DESCRIPTION:
Mapping XS f77b2fe2
END DESCRIPTION:
XS GIS Cut Line= 2
      1986178.66     13646238.09      1985720.46      13645019.7
#Sta/Elev= 30
  4525.3  798.39  4687.7  797.86  4693.1  798.32  4753.5  797.95  4773.1  797.33
  4778.4  798.15  4795.7  797.16  4827.7  796.97  4858.4  795.25  4863.8  793.56
  4888.7  793.22  4966.6  794.36  5004.2  793.26  5235.4  793.88  5241.4  793.22
  5241.9  792.42  5246.9  792.42  5247.4  793.22  5260.3  793.76  5370.5  794.64
  5375.9  795.09    5394  794.84  5455.9   795.6  5516.3  796.95  5618.3  798.05
  5717.3  799.91  5735.9  799.79  5747.5  800.93  5778.6  801.83    5827  802.35
#Mann= 3 ,-1 , 0
  4525.3      .1       0  5241.4     .07       0  5247.4      .1       0
Bank Sta=5241.4,5247.4
XS Rating Curve= 0 ,0
Exp/Cntr=0.3,0.1

Type RM Length L Ch R = 1 ,1134    ,471,471,471
BEGIN DESCRIPTION:
Mapping XS 0f35e3c4
END DESCRIPTION:
XS GIS Cut Line= 2
      1986439.09     13645982.91      1985824.49     13644982.88
#Sta/Elev= 30
    4479  793.65  4653.8  794.45  4684.7  793.79  4816.1  793.46  4858.6   792.5
  4901.2  792.18    4932  790.96  4974.6  790.27  4992.9  788.63  4993.4  787.83
  4998.4  787.83  4998.9  788.63  5004.7  789.79  5011.3  790.08  5026.7  789.68
  5053.9  790.47    5106  790.61  5169.9  791.53  5179.4  792.02  5251.2  792.24
  5264.6  792.95  5286.4  792.88  5295.4  793.49  5332.1  793.84  5390.1  795.49
  5506.1  797.41  5542.8  799.61  5548.7   799.3  5591.8  800.39  5652.8   801.2
#Mann= 4 ,-1 , 0
    4479      .1       0  4992.9     .07       0  4998.9      .1       0
  5591.8     .16       0
Bank Sta=4992.9,4998.9
XS Rating Curve= 0 ,0
Exp/Cntr=0.3,0.1

Type RM Length L Ch R = 1 ,663     ,244,244,244
BEGIN DESCRIPTION:
Mapping XS 2141e4fa
END DESCRIPTION:
XS GIS Cut Line= 4
      1986532.83     13645998.56      1986558.88     13645706.86
      1986423.46     13645217.27      1985871.37     13644800.61
#Sta/Elev= 30
  4138.2  792.27  4382.7  789.97  4461.6  789.69  4535.5  789.73  4614.5  790.59
  4648.8   790.3  4671.6  790.77  4744.3  790.35  4767.3  789.68  4785.8  790.25
  4953.5  787.73  4962.6787.1409  4982.6  784.64  4994.2  783.73  4994.7  782.93
  4999.7  782.93  5000.2  783.73  5032.6  787.22 5054.88787.1407  5132.5   788.2
  5138.8  788.81  5175.1  789.78  5211.6  791.57  5338.6  793.88  5388.5  795.43
  5417.7  795.53  5496.8  798.98    5503  798.72  5540.6  799.57  5630.7  801.14
#Mann= 4 ,-1 , 0
  4138.2      .1       0  4994.2     .07       0  5000.2      .1       0
  5540.6     .16       0
Bank Sta=4962.6,5054.88
XS Rating Curve= 0 ,0
Exp/Cntr=0.3,0.1

Type RM Length L Ch R = 1 ,419     ,219,219,219
BEGIN DESCRIPTION:
Mapping XS c5aae868
END DESCRIPTION:
XS GIS Cut Line= 5
      1986546.51     13645980.71      1986605.54     13645373.09
      1986619.43     13645105.73      1986345.12     13644883.51
      1985942.34     13644730.73
#Sta/Elev= 30
  4023.9  792.04  4391.3  789.07  4461.7   789.6  4475.2  789.12  4592.3  790.54
  4692.5  790.61  4762.6  789.83  4802.7  788.33  4947.9  787.12 4977.93785.4793
    4991  782.81  5011.9  780.96  5019.8  782.19  5034.2  785.68  5040.6   783.7
  5048.5  783.16    5055  780.88  5059.2  780.74  5059.7  779.94  5064.7  779.94
  5065.2  780.74  5069.4  780.93 5088.41785.4778  5109.5  786.52  5211.6  789.16
  5391.7  792.24  5463.1  793.26  5501.2  796.88  5523.4  797.61  5685.9  800.61
#Mann= 5 ,-1 , 0
  4023.9      .1       0  5059.2     .07       0  5065.2      .1       0
  5109.5     .16       0  5391.7      .1       0
Bank Sta=4977.93,5088.41
XS Rating Curve= 0 ,0
Exp/Cntr=0.3,0.1

Type RM Length L Ch R = 1 ,200     ,32,32,32
BEGIN DESCRIPTION:
Mapping XS 2741e252
END DESCRIPTION:
XS GIS Cut Line= 5
       1986560.4     13645998.07      1986674.98     13645164.76
       1986685.4     13644977.26      1986681.93     13644838.37
      1985970.08     13644650.86
#Sta/Elev= 30
  3884.4  791.93  3907.7   792.3    3959  790.98  4200.4  789.06  4396.3  789.03
  4468.3  789.94  4594.1  790.04  4745.3  787.13  4818.2  787.55  4856.4  786.82
    4887   786.5 4956.66 785.111  4965.6  784.36  4975.6  781.01  4985.6  779.51
  4992.6  779.45  4993.1  778.65  4998.1  778.65  4998.6  779.45  5111.1  784.07
  5180.4785.1111  5225.7  786.32  5474.7  790.88  5576.5  792.73  5593.7   794.7
  5598.9  794.31  5634.1  797.49    5643  797.33  5683.5  798.54  5788.4  801.07
#Mann= 9 ,-1 , 0
  3884.4      .1       0  4856.4     .16       0    4887      .1       0
  4992.6     .07       0  4998.6      .1       0  5225.7     .16       0
  5474.7      .1       0    5643     .16       0  5683.5      .1       0
Bank Sta=4956.66,5180.4
XS Rating Curve= 0 ,0
Exp/Cntr=0.3,0.1

Type RM Length L Ch R = 1 ,168     ,34,34,34
BEGIN DESCRIPTION:
Mapping XS 72733bed
END DESCRIPTION:
XS GIS Cut Line= 4
      1986581.23       13646012.      1986723.59     13645098.79
       1986709.7     13644803.65      1985937.01     13644609.61
#Sta/Elev= 30
  3858.6  791.67  4138.9  789.01  4431.2   788.9  4462.8  788.33  4533.7  789.12
  4766.4  786.53  4806.7  787.36  4866.7  786.69  4966.8  786.83  4986.9  786.11
  5006.9  787.12  5046.9  787.64  5066.9  786.84    5072  786.35  5075.2  784.82
 5084.93 784.507  5090.8  783.38  5111.1  782.35  5111.6  781.55  5116.6  781.55
  5117.1  782.35 5208.44784.5062  5307.1  786.59  5416.4  789.09  5510.2  790.72
  5567.8  791.23  5619.3  792.58  5707.5  797.62  5795.5  800.89    5875  801.69
#Mann= 7 ,-1 , 0
  3858.6      .1       0  5111.1     .07       0  5117.1      .1       0
  5307.1     .16       0  5416.4      .1       0  5510.2     .16       0
  5707.5      .1       0
Bank Sta=5084.93,5208.44
XS Rating Curve= 0 ,0
Exp/Cntr=0.3,0.1

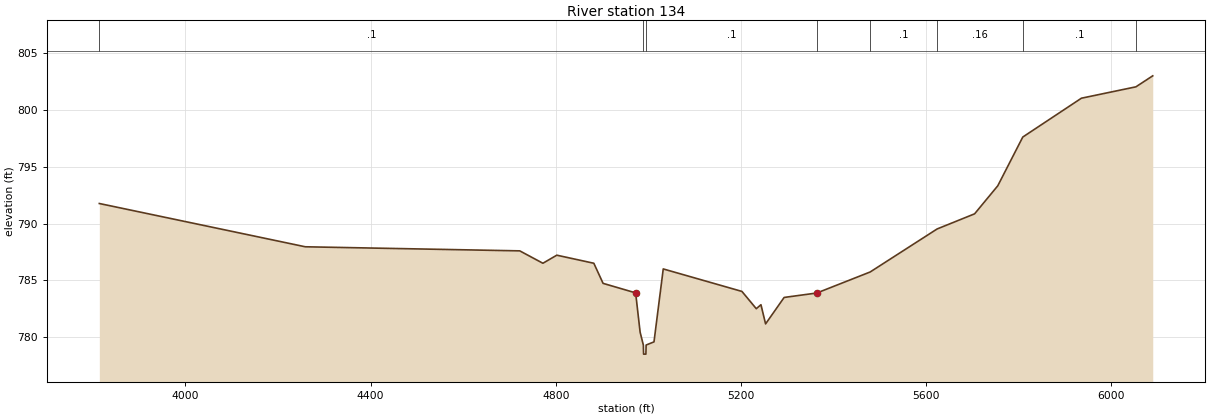
Type RM Length L Ch R = 1 ,134     ,0,0,0
BEGIN DESCRIPTION:
UNT 036 in HW 1.0
END DESCRIPTION:
XS GIS Cut Line= 4
      1986590.12       13646035.      1986750.94     13645339.24
      1986740.09     13644649.13       1985871.4     13644576.65
#Sta/Elev= 30
  3813.9  791.77  4258.9  787.96  4722.3   787.6  4772.3  786.51  4802.3  787.22
  4882.3  786.51  4902.3  784.74 4972.63783.9022  4982.3  780.45  4989.3  779.31
  4989.8  778.51  4994.8  778.51  4995.3  779.31  5012.3  779.59  5032.3  786.01
  5202.3  784.03  5233.3  782.51  5243.4  782.86  5253.4  781.17  5293.5   783.5
    5364  783.89  5364.9783.9038  5479.3  785.74  5624.1  789.53    5705  790.86
  5755.1  793.33  5809.1  797.62  5935.8  801.04  6053.5  802.04  6089.9  803.01
#Mann= 8 ,-1 , 0
  3813.9      .1       0  4989.3     .07       0  4995.3      .1       0
    5364     .16       0  5479.3      .1       0  5624.1     .16       0
  5809.1      .1       0  6053.5     .16       0
Bank Sta=4972.63,5364.9
XS Rating Curve= 0 ,0
Exp/Cntr=0.3,0.1
LCMann Table=0

Chan Stop Cuts=-1
Use User Specified Reach Order=0
Composite Channel Slope=5