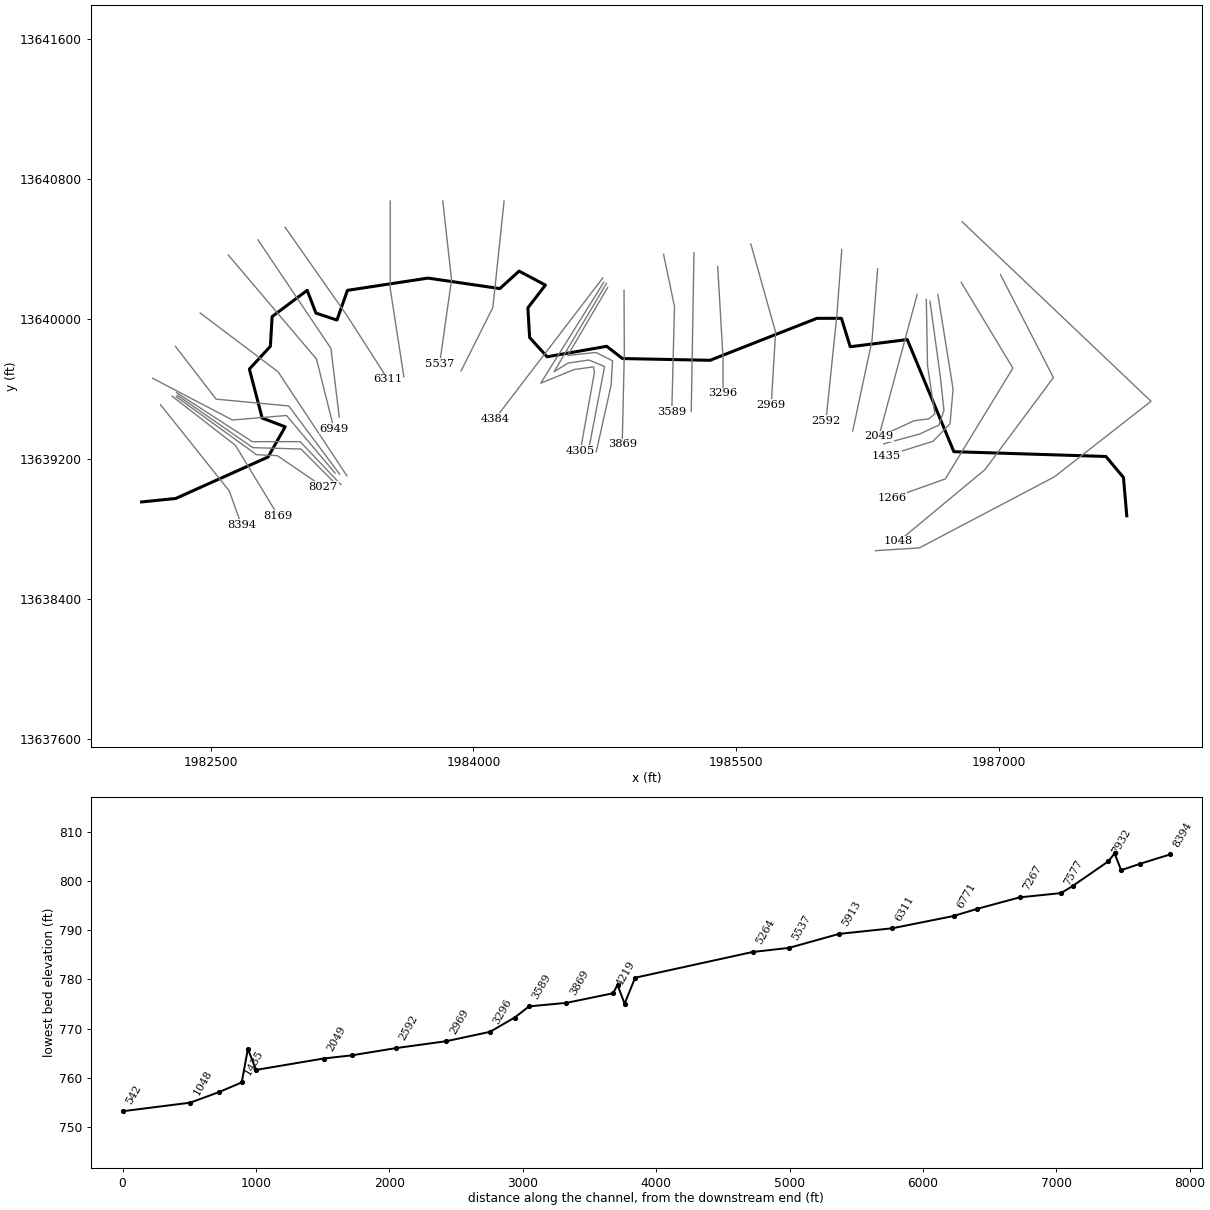
--- UNT 037 in HW.prj (project) ---

Proj Title=UNT 037 in HW Base Level Engineering
Current Plan=p01
Default Exp/Contr=0.3,0.1
English Units
Geom File=g01
Flow File=f01
Plan File=p01
Y Axis Title=Elevation
X Axis Title(PF)=Main Channel Distance
X Axis Title(XS)=Station
BEGIN DESCRIPTION:
UNT 037 in HW
END DESCRIPTION:
DSS Export Rating Curves= 0
DSS Export Rating Curve Sorted= 0
DSS Export Volume Flow Curves= 0
DXF OffsetX= 0
DXF OffsetY= 0
DXF ScaleX= 1
DXF ScaleY= 10

--- UNT 037 in HW.p01 (plan) ---

Plan Title=Multiple Run
Short Identifier=Multiple
Geom File=g01
Flow File=f01
Subcritical Flow
K Sum by GR= 0
Std Step Tol= 0.01
Critical Tol= 0.01
Num of Std Step Trials= 20
Max Error Tol= 0.3
Flow Tol Ratio= 0.001
Split Flow NTrial= 30
Split Flow Tol= 0.02
Split Flow Ratio= 0.02
Log Output Level= 0
Friction Slope Method= 1
Unsteady Friction Slope Method= 2
Unsteady Bridges Friction Slope Method= 1
Parabolic Critical Depth
Global Vel Dist=  1 , 1 , 1
Global Log Level= 0
CheckData=True
Encroach Param= -1, 0, 0, 0
BEGIN DESCRIPTION:
Multiple Run
END DESCRIPTION:

--- UNT 037 in HW.f01 (steady flow) ---

Flow Title=Multiple
Number of Profiles=7
Profile Names=10-year,25-year,50-year,1pct_min,100-year,1pct_plu,500-year
River Rch & RM= UNT 037 in HW,Reach-1,8394
     584     821    1019     627    1251    2496    1891
River Rch & RM= UNT 037 in HW,Reach-1,7267
     844    1210    1522     947    1890    3772    2925
Boundary for River Rch & Prof#=UNT 037 in HW,Reach-1,1
Up Type=0
Dn Type=3
Dn Slope=0.005
Boundary for River Rch & Prof#=UNT 037 in HW,Reach-1,2
Up Type=0
Dn Type=3
Dn Slope=0.005
Boundary for River Rch & Prof#=UNT 037 in HW,Reach-1,3
Up Type=0
Dn Type=3
Dn Slope=0.005
Boundary for River Rch & Prof#=UNT 037 in HW,Reach-1,4
Up Type=0
Dn Type=3
Dn Slope=0.005
Boundary for River Rch & Prof#=UNT 037 in HW,Reach-1,5
Up Type=0
Dn Type=3
Dn Slope=0.005
Boundary for River Rch & Prof#=UNT 037 in HW,Reach-1,6
Up Type=0
Dn Type=3
Dn Slope=0.005
Boundary for River Rch & Prof#=UNT 037 in HW,Reach-1,7
Up Type=0
Dn Type=3
Dn Slope=0.005

--- UNT 037 in HW.g01 (geometry) ---

Geom Title=Existing Conditions
Program Version=5.05

River Reach=UNT 037 in HW   ,Reach-1
Reach XY= 30
       1982105.8     13638954.54       1982300.8     13638974.54
      1982827.35     13639211.28      1982925.26     13639384.19
      1982794.01     13639434.19       1982720.8     13639714.54
       1982840.8     13639844.54       1982850.8     13640014.54
       1983050.8     13640164.54       1983100.8     13640034.54
       1983220.8     13639994.54       1983280.8     13640164.54
       1983740.8     13640234.54       1984150.8     13640174.54
       1984260.8     13640274.54       1984410.8     13640194.54
       1984310.8     13640064.54       1984320.8     13639894.54
       1984420.8     13639784.54       1984760.8     13639844.54
       1984850.8     13639774.54       1985350.8     13639764.54
       1985960.8     13640004.54       1986100.8     13640004.54
      1986151.02       13639842.      1986476.72     13639882.98
      1986742.69       13639242.       1987610.8     13639214.54
       1987710.8     13639094.54      1987729.76     13638875.47

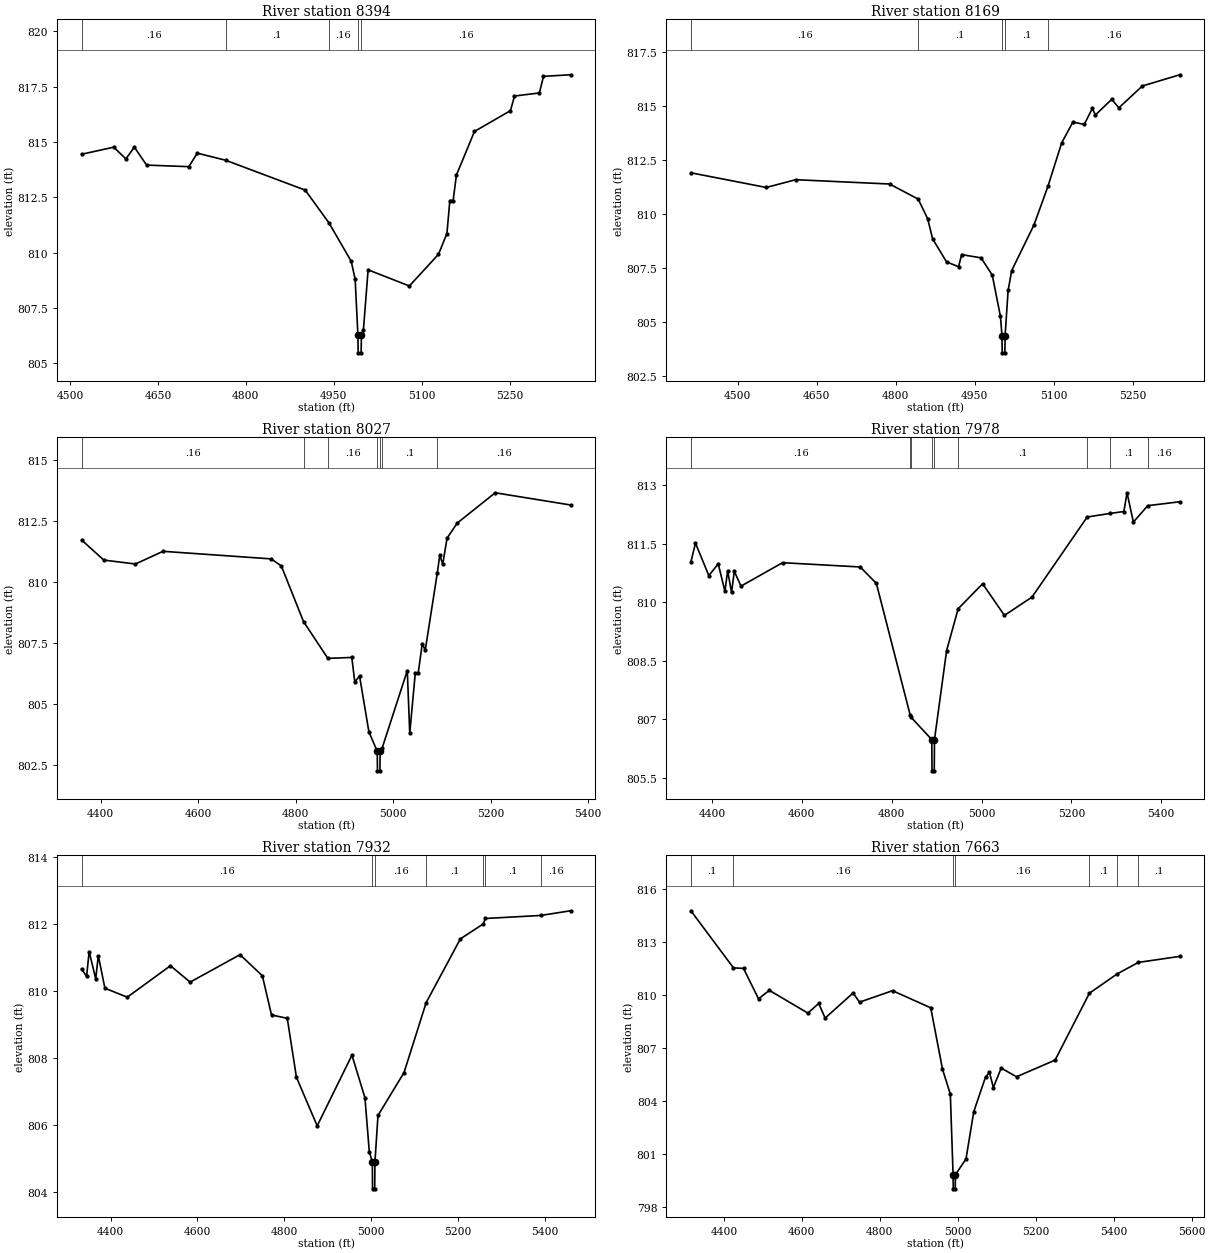
Type RM Length L Ch R = 1 ,8394    ,225,225,225
BEGIN DESCRIPTION:
UNT 037 in HW 15.0
END DESCRIPTION:
XS GIS Cut Line= 3
      1982213.85     13639510.21      1982606.19     13639017.19
        1982675.     13638825.01
#Sta/Elev= 30
  4519.9  814.44  4574.6  814.76  4595.4  814.23  4609.8  814.76  4630.7  813.95
  4702.8  813.88  4717.2  814.49  4765.5  814.17  4901.4  812.82  4941.9  811.34
  4979.8  809.61  4986.6   808.8  4991.3  806.27  4991.8  805.47  4996.8  805.47
  4997.3  806.27  5000.7   806.5  5008.7  809.22  5079.1  808.49  5128.8  809.92
  5143.2  810.86  5148.2  812.35  5153.8  812.35  5159.4   813.5  5190.2  815.47
  5251.7  816.41  5258.5  817.07    5301  817.21    5308  817.96  5354.1  818.03
#Mann= 5 ,-1 , 0
  4519.9     .16       0  4765.5      .1       0  4941.9     .16       0
  4991.3     .07       0  4997.3     .16       0
Bank Sta=4991.3,4997.3
XS Rating Curve= 0 ,0
Exp/Cntr=0.3,0.1

Type RM Length L Ch R = 1 ,8169    ,142,142,142
BEGIN DESCRIPTION:
Mapping XS dd8669e7
END DESCRIPTION:
XS GIS Cut Line= 3
      1982279.38     13639559.71      1982641.78      13639277.6
      1982884.85      13638876.1
#Sta/Elev= 30
  4410.9  811.91    4554  811.23  4610.1  811.59  4788.4  811.39  4842.7  810.69
  4860.7  809.78  4870.1  808.85  4896.6  807.78  4919.4  807.56  4925.2  808.12
  4962.1  807.97  4983.4  807.17  4998.9  805.26  5001.8  804.37  5002.3  803.57
  5007.3  803.57  5007.8  804.37  5013.5  806.46  5020.3  807.38  5062.9  809.51
  5089.1  811.28  5115.3   813.3  5136.6  814.26    5158  814.15  5173.5  814.89
  5179.3  814.59  5210.3  815.31  5223.9  814.92  5268.5  815.93  5339.5  816.45
#Mann= 5 ,-1 , 0
  4410.9     .16       0  4842.7      .1       0  5001.8     .07       0
  5007.8      .1       0  5089.1     .16       0
Bank Sta=5001.8,5007.8
XS Rating Curve= 0 ,0
Exp/Cntr=0.3,0.1

Type RM Length L Ch R = 1 ,8027    ,49,49,49
BEGIN DESCRIPTION:
Mapping XS 6d08ca50
END DESCRIPTION:
XS GIS Cut Line= 4
      1982303.21      13639556.7      1982761.57     13639224.65
      1982880.06     13639219.44      1983143.05     13639039.78
#Sta/Elev= 30
    4361  811.72  4406.5   810.9  4471.4  810.74  4527.9  811.26  4749.8  810.95
  4770.7  810.66  4816.2  808.38  4866.2  806.87  4915.3  806.91  4921.5   805.9
  4931.2  806.15  4950.4  803.86  4967.5  803.06    4968  802.26    4973  802.26
  4973.5  803.06  4977.4  803.18  5029.2  806.37  5034.2   803.8  5045.6  806.27
  5051.6  806.27    5060  807.48    5066   807.2  5090.9  810.39  5095.9  811.11
  5101.9  810.73  5110.8   811.8  5131.8  812.42  5209.6  813.66  5364.1  813.16
#Mann= 7 ,-1 , 0
    4361     .16       0  4816.2      .1       0  4866.2     .16       0
  4967.5     .07       0  4973.5     .16       0  4977.4      .1       0
  5090.9     .16       0
Bank Sta=4967.5,4973.5
XS Rating Curve= 0 ,0
Exp/Cntr=0.3,0.1

Type RM Length L Ch R = 1 ,7978    ,46,46,46
BEGIN DESCRIPTION:
Mapping XS fbf3fd31
END DESCRIPTION:
XS GIS Cut Line= 4
      1982309.73     13639564.51      1982740.73     13639265.02
      1983015.47      13639257.2      1983218.61     13639052.76
#Sta/Elev= 30
  4353.1  811.03  4363.3  811.51    4393  810.68  4413.9  810.98  4428.8  810.28
  4434.9   810.8  4443.6  810.25  4449.7  810.79  4464.6  810.41  4557.1  811.01
    4730   810.9  4765.8  810.48  4841.1  807.11  4842.4  807.06  4889.2  806.48
  4889.7  805.68  4894.7  805.68  4895.2  806.48  4922.2  808.76  4947.9  809.83
  5002.3  810.47  5050.9  809.66  5112.3  810.13  5235.1  812.18  5285.5  812.27
  5316.7  812.32  5323.7   812.8  5337.9  812.05  5369.8  812.47    5441  812.57
#Mann= 9 ,-1 , 0
  4353.1     .16       0  4841.1      .1       0  4842.4     .16       0
  4889.2     .07       0  4895.2     .16       0  4947.9      .1       0
  5235.1     .16       0  5285.5      .1       0  5369.8     .16       0
Bank Sta=4889.2,4895.2
XS Rating Curve= 0 ,0
Exp/Cntr=0.3,0.1

Type RM Length L Ch R = 1 ,7932    ,269,269,269
BEGIN DESCRIPTION:
Mapping XS 8b77cdcb
END DESCRIPTION:
XS GIS Cut Line= 4
      1982305.38     13639579.27      1982737.26     13639299.31
       1983010.7     13639299.31      1983242.87     13639054.11
#Sta/Elev= 30
  4333.3  810.64  4344.6  810.42  4350.5  811.16  4365.7  810.35  4371.6  811.04
  4386.8  810.07  4438.2   809.8  4537.8  810.74  4583.1  810.25    4698  811.07
  4749.4  810.44  4770.5  809.27  4806.8  809.17  4827.9  807.41  4875.7  805.96
  4955.7  808.07  4985.7   806.8  4995.7  805.19  5002.7  804.88  5003.2  804.08
  5008.2  804.08  5008.7  804.88  5015.7  806.27  5075.7  807.55  5126.7  809.64
  5205.4  811.54  5258.4  811.99  5262.9  812.15  5390.2  812.24  5459.1  812.38
#Mann= 7 ,-1 , 0
  4333.3     .16       0  5002.7     .07       0  5008.7     .16       0
  5126.7      .1       0  5258.4     .16       0  5262.9      .1       0
  5390.2     .16       0
Bank Sta=5002.7,5008.7
XS Rating Curve= 0 ,0
Exp/Cntr=0.3,0.1

Type RM Length L Ch R = 1 ,7663    ,86,86,86
BEGIN DESCRIPTION:
Mapping XS b3f8c7dd
END DESCRIPTION:
XS GIS Cut Line= 4
      1982168.66     13639661.73      1982624.41       13639423.
      1982932.57     13639449.04      1983209.84     13639119.79
#Sta/Elev= 30
  4315.3  814.76  4424.5  811.53  4450.3   811.5  4488.8  809.78  4516.5  810.26
  4615.5  808.97  4643.2  809.52  4659.7  808.69  4731.5  810.11  4747.9  809.59
  4832.6  810.24  4930.7  809.27  4960.8   805.8  4980.9  804.39    4988  799.83
  4988.5  799.03  4993.5  799.03    4994  799.83  5021.1  800.72  5041.1   803.4
  5071.2  805.35  5081.3  805.62  5091.3  804.76  5111.4  805.86  5150.7  805.37
  5249.6  806.31  5337.9   810.1  5409.1  811.19  5463.4  811.84  5569.5  812.18
#Mann= 7 ,-1 , 0
  4315.3      .1       0  4424.5     .16       0    4988     .07       0
    4994     .16       0  5337.9      .1       0  5409.1     .16       0
  5463.4      .1       0
Bank Sta=4988,4994
XS Rating Curve= 0 ,0
Exp/Cntr=0.3,0.1

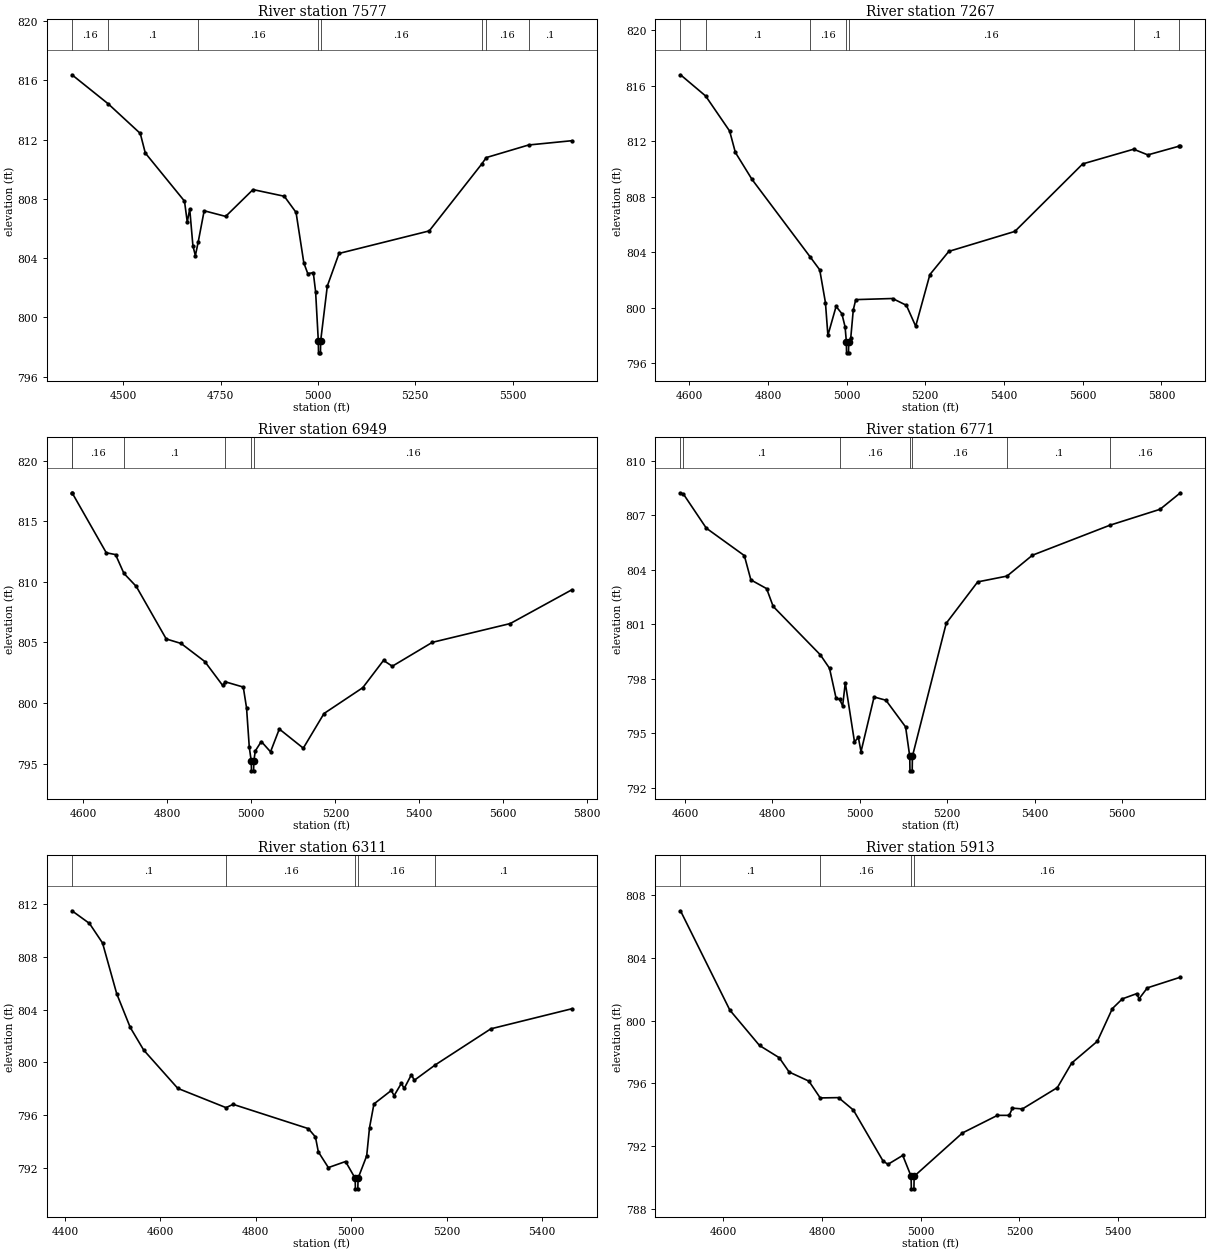
Type RM Length L Ch R = 1 ,7577    ,310,310,310
BEGIN DESCRIPTION:
Mapping XS 016d71f3
END DESCRIPTION:
XS GIS Cut Line= 4
      1982298.88     13639844.03       1982531.1     13639542.36
      1982945.59      13639503.3      1983236.39     13639112.68
#Sta/Elev= 30
  4368.5  816.37  4461.5  814.41  4543.9  812.41  4556.8  811.09  4657.5  807.84
  4664.6  806.43  4670.9  807.31  4679.1  804.83  4685.4  804.16  4692.9  805.11
    4708  807.19  4763.2  806.81  4833.5  808.62  4913.8  808.17    4944  807.08
    4964  803.67  4974.1  802.95  4988.3  803.01  4994.2  801.74  5001.2   798.4
  5001.7   797.6  5006.7   797.6  5007.2   798.4  5024.3  802.11  5054.4  804.31
    5286  805.83  5421.3  810.36  5432.5  810.78  5541.3  811.63  5652.5  811.92
#Mann= 8 ,-1 , 0
  4368.5     .16       0  4461.5      .1       0  4692.9     .16       0
  5001.2     .07       0  5007.2     .16       0  5421.3      .1       0
  5432.5     .16       0  5541.3      .1       0
Bank Sta=5001.2,5007.2
XS Rating Curve= 0 ,0
Exp/Cntr=0.3,0.1

Type RM Length L Ch R = 1 ,7267    ,318,318,318
BEGIN DESCRIPTION:
UNT 037 in HW 14.0
END DESCRIPTION:
XS GIS Cut Line= 3
      1982439.97     13640034.97      1982884.83     13639698.61
      1983277.65     13639103.95
#Sta/Elev= 30
  4577.9  816.79  4641.8  815.26  4702.8  812.73  4717.3  811.19  4759.7  809.24
  4907.7  803.64  4931.7  802.72  4946.2  800.36  4952.5  797.99  4973.3  800.08
  4987.9  799.56  4996.2   798.6  4999.4  797.53  4999.9  796.73  5004.9  796.73
  5005.4  797.53  5010.5  797.78    5017  799.83  5023.3  800.57  5116.9  800.65
  5151.9  800.16  5175.6  798.65  5211.7  802.38  5259.8  804.05  5427.6  805.49
    5600  810.36  5729.4  811.42  5765.5  811.01    5845  811.64  5848.3  811.64
#Mann= 7 ,-1 , 0
  4577.9     .16       0  4641.8      .1       0  4907.7     .16       0
  4999.4     .07       0  5005.4     .16       0  5729.4      .1       0
    5845     .16       0
Bank Sta=4999.4,5005.4
XS Rating Curve= 0 ,0
Exp/Cntr=0.3,0.1

Type RM Length L Ch R = 1 ,6949    ,178,178,178
BEGIN DESCRIPTION:
Mapping XS 91b9751b
END DESCRIPTION:
XS GIS Cut Line= 3
      1982600.54     13640366.36      1983104.01     13639771.74
      1983203.83     13639372.47
#Sta/Elev= 30
  4572.8  817.34  4573.1  817.34  4654.5  812.39  4676.6  812.24  4696.5  810.69
    4726  809.61  4797.3  805.28  4832.6  804.91  4889.1  803.42  4931.4  801.46
  4938.4  801.74  4980.8  801.31  4988.6  799.59  4995.1  796.35  4999.8   795.2
  5000.3   794.4  5005.4   794.4  5005.9   795.2  5009.4  796.04  5023.7  796.82
  5045.7  795.97  5066.6  797.85  5123.7  796.27  5173.1  799.13  5265.4  801.26
  5314.8  803.51  5335.7  803.03    5431     805  5616.6  806.55  5763.5  809.34
#Mann= 6 ,-1 , 0
  4572.8      .1       0  4573.1     .16       0  4696.5      .1       0
  4938.4     .16       0  4999.8     .07       0  5005.9     .16       0
Bank Sta=4999.8,5005.9
XS Rating Curve= 0 ,0
Exp/Cntr=0.3,0.1

Type RM Length L Ch R = 1 ,6771    ,460,460,460
BEGIN DESCRIPTION:
Mapping XS 21178287
END DESCRIPTION:
XS GIS Cut Line= 3
      1982769.81     13640453.17      1983186.48     13639832.51
      1983234.08     13639438.73
#Sta/Elev= 30
  4589.5  808.23  4595.9  808.19  4648.6   806.3  4735.6  804.79  4750.6  803.45
  4786.6  802.97  4801.6  801.99  4909.6  799.32  4930.6  798.58  4945.6  796.93
  4953.7  796.87  4960.6  796.51  4966.7  797.78  4987.7  794.53  4996.6  794.77
  5002.7  793.99  5032.6     797  5059.7  796.82  5104.7  795.35  5114.2  793.73
  5114.7  792.93  5119.8  792.93  5120.3  793.73  5197.7  801.06  5269.7  803.34
  5336.8  803.66    5395  804.81    5572  806.46  5687.1  807.34  5733.7  808.25
#Mann= 7 ,-1 , 0
  4589.5     .16       0  4595.9      .1       0  4953.7     .16       0
  5114.2     .07       0  5120.3     .16       0  5336.8      .1       0
    5572     .16       0
Bank Sta=5114.2,5120.3
XS Rating Curve= 0 ,0
Exp/Cntr=0.3,0.1

Type RM Length L Ch R = 1 ,6311    ,398,398,398
BEGIN DESCRIPTION:
UNT 037 in HW 13.0
END DESCRIPTION:
XS GIS Cut Line= 3
      1982924.98     13640525.03        1983275.       13640025.
      1983511.01      13639656.1
#Sta/Elev= 30
  4414.4  811.49  4451.1  810.53  4478.5  809.05  4508.2  805.21  4536.5  802.66
  4564.8  800.94  4636.3  798.04  4737.4  796.58  4752.3  796.83  4910.1  794.99
  4924.9  794.36    4931  793.23    4952  792.04  4988.1   792.5  5008.2  791.23
  5008.7  790.43  5013.8  790.43  5014.3  791.23  5032.4  792.93  5038.3  795.06
  5047.6  796.86  5083.9  797.88  5089.9  797.49  5105.1  798.42    5111  798.03
  5126.2  799.08  5132.2  798.65  5176.3  799.82  5292.8  802.55  5462.7  804.07
#Mann= 5 ,-1 , 0
  4414.4      .1       0  4737.4     .16       0  5008.2     .07       0
  5014.3     .16       0  5176.3      .1       0
Bank Sta=5008.2,5014.3
XS Rating Curve= 0 ,0
Exp/Cntr=0.3,0.1

Type RM Length L Ch R = 1 ,5913    ,376,376,376
BEGIN DESCRIPTION:
UNT 037 in HW 12.0
END DESCRIPTION:
XS GIS Cut Line= 3
        1983525.     13640675.04        1983525.       13640175.
      1983602.96     13639668.81
#Sta/Elev= 30
  4513.7     807  4613.7  800.67  4673.7  798.42  4713.7  797.64  4733.7  796.73
  4773.7  796.15  4796.6  795.08  4833.7   795.1  4863.7  794.31  4923.7  791.07
  4933.7  790.85  4963.7  791.42  4980.6  790.09  4981.1  789.29  4986.3  789.29
  4986.8  790.09  5084.6  792.85  5155.4  793.97  5179.3  793.97  5185.7  794.43
    5206  794.38  5276.8  795.74  5305.7   797.3  5357.7  798.69  5388.1  800.77
  5408.3  801.39  5437.2  801.72  5442.3   801.4  5458.9  802.09  5525.9  802.77
#Mann= 4 ,-1 , 0
  4513.7      .1       0  4796.6     .16       0  4980.6     .07       0
  4986.8     .16       0
Bank Sta=4980.6,4986.8
XS Rating Curve= 0 ,0
Exp/Cntr=0.3,0.1

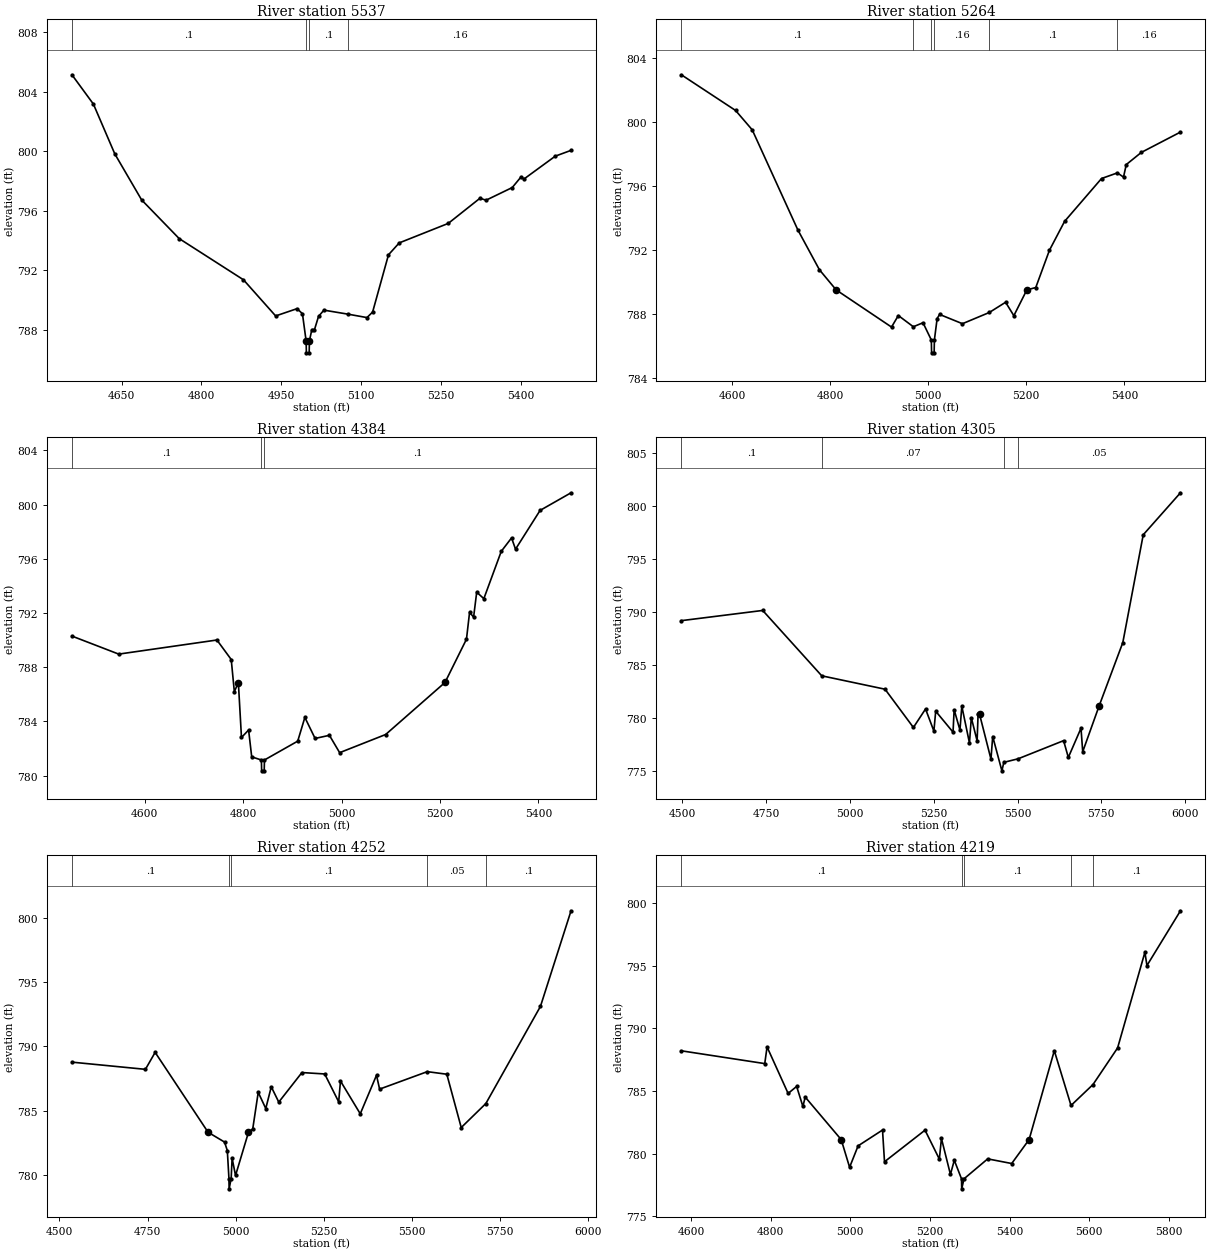
Type RM Length L Ch R = 1 ,5537    ,273,273,273
BEGIN DESCRIPTION:
UNT 037 in HW 11.0
END DESCRIPTION:
XS GIS Cut Line= 3
        1983825.     13640675.03        1983875.       13640225.
      1983807.14     13639745.68
#Sta/Elev= 30
  4556.8  805.13  4597.1  803.16  4637.3  799.81  4687.6  796.72  4758.1  794.12
  4878.8  791.35  4939.2  788.92  4979.4  789.41  4989.5  789.07  4996.4  787.24
  4996.9  786.44  5002.1  786.44  5002.6  787.24  5007.1     788  5012.1     788
  5019.7  788.89  5029.8  789.31  5074.9  789.04  5110.6  788.81  5121.2  789.18
    5151  793.03  5171.2  793.83  5263.2  795.14  5322.7  796.83  5334.2   796.7
  5383.3  797.55  5400.2  798.28  5405.2  798.12  5464.1  799.66  5493.7  800.05
#Mann= 4 ,-1 , 0
  4556.8      .1       0  4996.4     .07       0  5002.6      .1       0
  5074.9     .16       0
Bank Sta=4996.4,5002.6
XS Rating Curve= 0 ,0
Exp/Cntr=0.3,0.1

Type RM Length L Ch R = 1 ,5264    ,880,880,880
BEGIN DESCRIPTION:
UNT 037 in HW 10.0
END DESCRIPTION:
XS GIS Cut Line= 3
        1984175.     13640674.97      1984110.96     13640066.88
      1983929.32     13639703.61
#Sta/Elev= 30
  4496.8  802.97  4607.4  800.74  4641.3  799.53  4734.3  793.28  4778.3  790.79
 4812.48789.5304  4925.3  787.21  4939.2  787.93  4969.8  787.23  4989.5  787.48
  5006.5   786.4    5007   785.6  5012.2   785.6  5012.7   786.4  5018.3  787.74
  5023.3     788  5069.9  787.42  5124.6  788.12  5157.9  788.76  5174.7  787.92
 5201.14789.5302  5219.4  789.68  5247.3  792.01  5278.1  793.81  5353.5  796.49
  5385.7  796.84  5398.3  796.58  5403.9  797.36  5434.6  798.12  5514.4  799.39
#Mann= 6 ,-1 , 0
  4496.8      .1       0  4969.8     .07       0  5006.5      .1       0
  5012.7     .16       0  5124.6      .1       0  5385.7     .16       0
Bank Sta=4812.48,5201.14
XS Rating Curve= 0 ,0
Exp/Cntr=0.3,0.1

Type RM Length L Ch R = 1 ,4384    ,79,79,79
BEGIN DESCRIPTION:
UNT 037 in HW 9.0
END DESCRIPTION:
XS GIS Cut Line= 3
      1984738.12     13640235.05        1984425.       13639825.
      1984122.69     13639428.93
#Sta/Elev= 30
  4452.2   790.3  4547.3  788.97  4746.8  790.01  4775.9  788.57  4782.2   786.2
  4790.4  786.87  4796.7  782.82  4811.2  783.37  4817.5  781.39  4837.2  781.16
  4837.7  780.36  4842.9  780.36  4843.4  781.16    4911  782.55  4925.5   784.3
  4946.3  782.75  4975.4  782.98  4996.2   781.7  5089.7  783.04  5210.3  786.88
  5253.9  790.07  5260.2  792.05  5268.4   791.7  5274.7  793.54  5289.2  793.06
  5324.6  796.55  5345.5  797.54  5353.6  796.71  5403.5  799.57  5466.4  800.87
#Mann= 3 ,-1 , 0
  4452.2      .1       0  4837.2     .07       0  4843.4      .1       0
Bank Sta=4790.4,5210.3
XS Rating Curve= 0 ,0
Exp/Cntr=0.3,0.1

Type RM Length L Ch R = 1 ,4305    ,53,53,53
BEGIN DESCRIPTION:
Mapping XS 0706d966
END DESCRIPTION:
XS GIS Cut Line= 6
       1984744.4     13640210.84      1984384.17     13639633.61
      1984575.14     13639711.73      1984685.82     13639726.92
      1984690.16      13639692.2      1984609.94     13639245.57
#Sta/Elev= 30
  4497.5  789.19  4740.1  790.15  4916.2     784  5104.9  782.74  5189.5  779.14
  5225.7  780.88  5250.6   778.8    5256  780.67  5307.7   778.7    5311  780.81
  5328.3   778.9  5333.9  781.14  5356.7  777.68  5362.2  780.06  5379.5  777.88
  5382.4  780.37  5386.9  780.37  5420.8  776.16    5426  778.29  5453.4  775.06
  5459.2  775.86  5501.5  776.19  5637.4   777.9  5651.5  776.32  5689.3  779.07
  5694.4  776.86  5742.9  781.13    5814  787.13  5874.9  797.27  5985.9  801.22
#Mann= 4 ,-1 , 0
  4497.5      .1       0  4916.2     .07       0  5459.2      .1       0
  5501.5     .05       0
Bank Sta=5386.9,5742.9
XS Rating Curve= 0 ,0
Exp/Cntr=0.3,0.1

Type RM Length L Ch R = 1 ,4252    ,33,33,33
BEGIN DESCRIPTION:
Mapping XS f7c86ced
END DESCRIPTION:
XS GIS Cut Line= 6
      1984759.62     13640204.37      1984460.13     13639698.71
      1984540.42     13639748.62      1984659.78     13639765.99
      1984748.75     13639729.09      1984653.28     13639230.03
#Sta/Elev= 30
  4535.3  788.78  4743.8  788.22  4771.4  789.54 4921.57783.3252  4968.3  782.56
  4976.2   781.9  4980.8  779.72  4981.3  778.92  4987.1  779.72  4989.8   781.3
  4999.5  779.96 5036.28783.3258  5048.3  783.58  5063.9  786.43  5085.3  785.17
  5100.9  786.86  5122.2  785.67  5187.9  787.97  5252.5  787.86  5292.2  785.69
  5297.3  787.31  5353.4  784.76  5399.5  787.76  5408.3  786.68  5543.6  788.04
    5599  787.84  5639.9  783.69  5709.8  785.56  5864.7  793.12  5951.5  800.56
#Mann= 5 ,-1 , 0
  4535.3      .1       0  4980.8     .07       0  4987.1      .1       0
  5543.6     .05       0  5709.8      .1       0
Bank Sta=4921.57,5036.28
XS Rating Curve= 0 ,0
Exp/Cntr=0.3,0.1

Type RM Length L Ch R = 1 ,4219    ,350,350,350
BEGIN DESCRIPTION:
Mapping XS c6edd1c6
END DESCRIPTION:
XS GIS Cut Line= 6
      1984766.14     13640180.52      1984538.25     13639792.03
      1984698.84     13639809.39      1984794.33     13639761.65
      1984785.65     13639620.59      1984701.02     13639240.85
#Sta/Elev= 30
  4575.7  788.21  4785.2  787.19    4791  788.52  4843.9  784.81  4865.3  785.37
    4881  783.77  4886.8  784.52 4977.25 781.127  4998.3  778.92  5019.7  780.63
    5081  781.89    5086  779.36  5187.8  781.88  5223.8  779.57    5229  781.22
  5251.6  778.35  5261.3  779.48  5279.4     778  5279.9   777.2  5285.7     778
  5345.2  779.59  5405.5  779.22 5449.19781.1266  5512.5  788.22  5554.5  783.85
  5609.7  785.52  5671.5  788.44  5740.1  796.07  5745.2  795.01  5829.4  799.38
#Mann= 5 ,-1 , 0
  4575.7      .1       0  5279.4     .07       0  5285.7      .1       0
  5554.5     .05       0  5609.7      .1       0
Bank Sta=4977.25,5449.19
XS Rating Curve= 0 ,0
Exp/Cntr=0.3,0.1

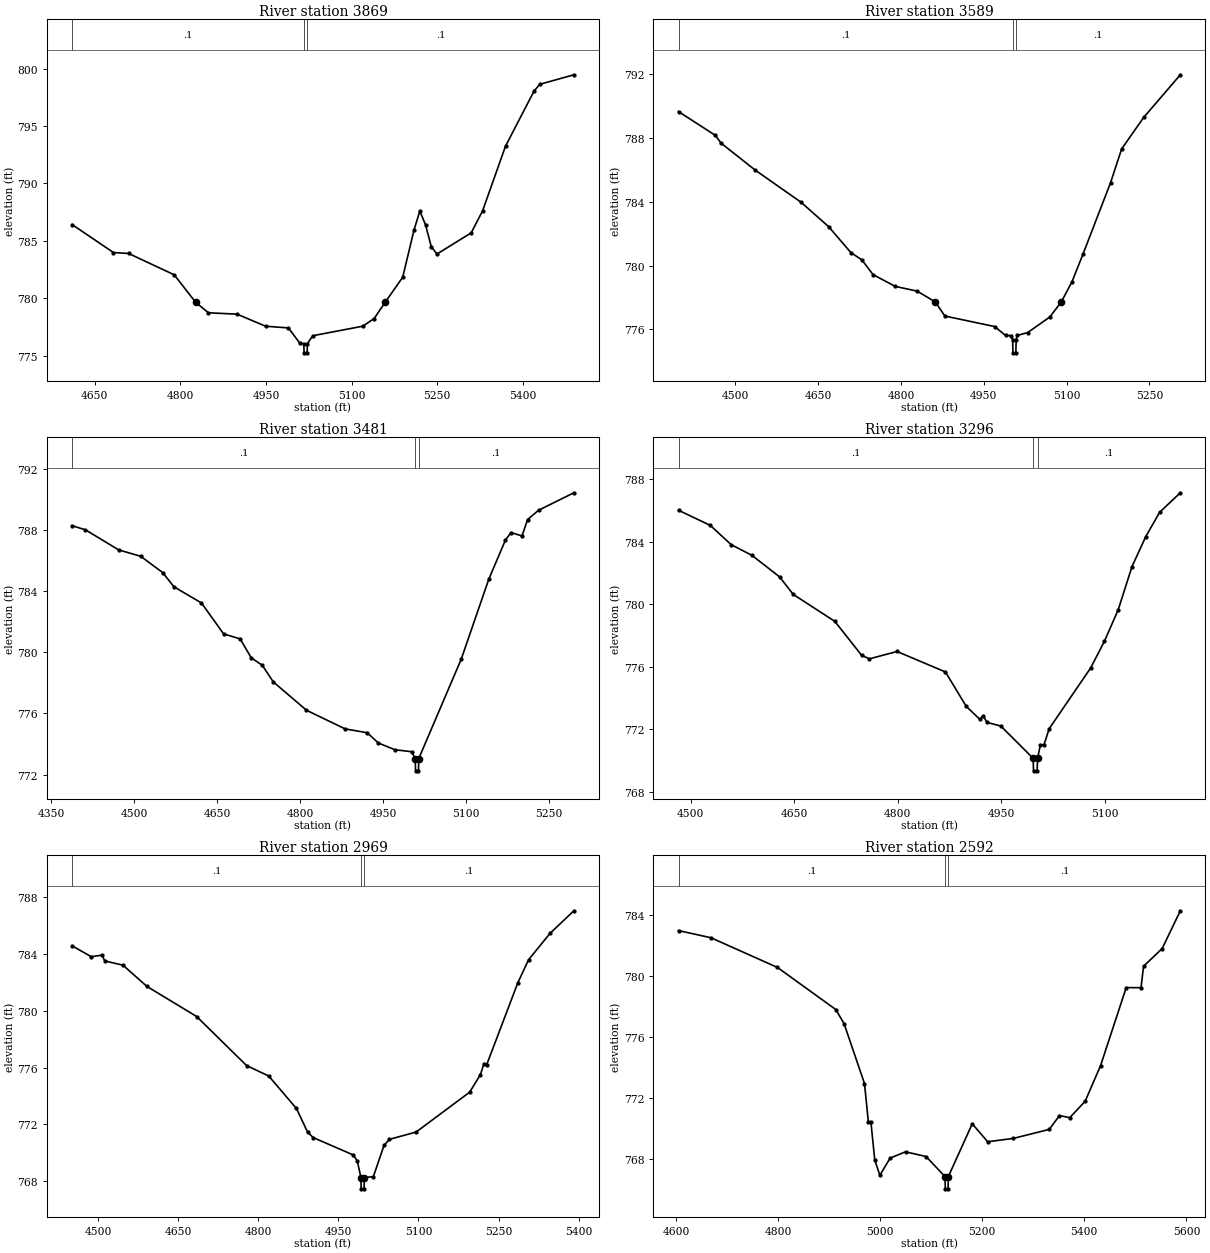
Type RM Length L Ch R = 1 ,3869    ,280,280,280
BEGIN DESCRIPTION:
UNT 037 in HW 8.0
END DESCRIPTION:
XS GIS Cut Line= 3
      1984859.66     13640163.93      1984861.39     13639804.51
      1984849.24     13639285.37
#Sta/Elev= 30
  4610.6  786.42  4683.1  783.98  4709.5   783.9  4789.5  782.04 4826.91779.6465
  4849.5  778.73  4899.5  778.61  4949.5  777.56  4989.5  777.41  5009.5  776.08
  5016.4  776.04  5016.9  775.24  5022.2  775.24  5022.7  776.04    5032  776.73
  5119.6  777.56  5139.6  778.23  5158.9779.6468  5189.6  781.83  5209.6  785.98
  5219.6   787.6  5229.6  786.39  5239.6  784.49  5249.6  783.85  5309.6   785.7
  5329.6  787.63  5369.6  793.25  5419.7  798.06  5429.7  798.64  5489.3  799.47
#Mann= 3 ,-1 , 0
  4610.6      .1       0  5016.4     .07       0  5022.7      .1       0
Bank Sta=4826.91,5158.9
XS Rating Curve= 0 ,0
Exp/Cntr=0.3,0.1

Type RM Length L Ch R = 1 ,3589    ,108,108,108
BEGIN DESCRIPTION:
UNT 037 in HW 7.0
END DESCRIPTION:
XS GIS Cut Line= 3
      1985085.36     13640370.47      1985147.85     13640071.87
      1985132.26     13639468.84
#Sta/Elev= 30
  4397.5  789.66  4464.1  788.17  4474.6  787.68  4535.9     786  4619.1  783.98
    4669  782.45  4709.4  780.82  4729.4  780.36  4749.5  779.44  4789.5   778.7
  4829.5   778.4 4862.45777.7195  4879.5  776.84  4969.5  776.18  4989.5  775.62
  4999.5  775.61  5002.3  775.33  5002.8  774.53  5008.1  774.53  5008.6  775.33
  5010.4  775.62  5029.5   775.8  5069.6  776.78 5090.27777.7195  5109.6  778.98
  5129.6  780.72  5179.6  785.21  5199.6  787.32  5239.6   789.3  5305.8  791.97
#Mann= 3 ,-1 , 0
  4397.5      .1       0  5002.3     .07       0  5008.6      .1       0
Bank Sta=4862.45,5090.27
XS Rating Curve= 0 ,0
Exp/Cntr=0.3,0.1

Type RM Length L Ch R = 1 ,3481    ,185,185,185
BEGIN DESCRIPTION:
Mapping XS 93b2988e
END DESCRIPTION:
XS GIS Cut Line= 2
      1985258.96     13640379.16      1985243.34      13639471.2
#Sta/Elev= 30
  4387.5  788.27  4411.7     788  4471.7  786.69  4511.7  786.27  4551.7   785.2
  4571.7  784.28  4621.7  783.22  4661.7   781.2  4691.7  780.87  4711.7  779.64
  4731.7  779.15  4751.7  778.06  4811.7  776.21  4881.7  774.99  4921.7  774.74
  4941.7  774.07  4971.7  773.63  5001.8   773.5  5008.6  773.05  5009.1  772.25
  5014.4  772.25  5014.9  773.05  5091.8  779.55  5141.8  784.79  5171.8  787.33
  5181.8  787.82  5201.8   787.6  5211.8  788.67  5231.8  789.28  5295.6  790.42
#Mann= 3 ,-1 , 0
  4387.5      .1       0  5008.6     .07       0  5014.9      .1       0
Bank Sta=5008.6,5014.9
XS Rating Curve= 0 ,0
Exp/Cntr=0.3,0.1

Type RM Length L Ch R = 1 ,3296    ,327,327,327
BEGIN DESCRIPTION:
UNT 037 in HW 6.0
END DESCRIPTION:
XS GIS Cut Line= 3
      1985394.38     13640301.06        1985425.       13639775.
        1985425.     13639574.95
#Sta/Elev= 30
  4482.6  786.02  4528.7  785.05  4558.8  783.82  4588.8  783.14  4628.9  781.76
  4648.9  780.63    4709  778.91  4747.8  776.74  4759.1  776.51  4799.2  776.98
  4869.3  775.67  4899.4  773.47    4919  772.64    4924  772.87  4929.4  772.44
  4949.5  772.21  4996.4  770.14  4996.9  769.34  5002.2  769.34  5002.7  770.14
    5007  771.01  5012.1  771.01  5019.6  772.04  5079.6  775.92  5099.6  777.63
  5119.6  779.65  5139.6  782.42  5159.6  784.34  5179.6  785.89  5209.6  787.14
#Mann= 3 ,-1 , 0
  4482.6      .1       0  4996.4     .07       0  5002.7      .1       0
Bank Sta=4996.4,5002.7
XS Rating Curve= 0 ,0
Exp/Cntr=0.3,0.1

Type RM Length L Ch R = 1 ,2969    ,377,377,377
BEGIN DESCRIPTION:
UNT 037 in HW 5.0
END DESCRIPTION:
XS GIS Cut Line= 3
      1985583.61     13640429.55        1985725.       13639925.
      1985699.99     13639510.24
#Sta/Elev= 30
  4451.5  784.59  4487.4  783.82  4507.6  783.93  4512.8  783.52  4546.9  783.22
  4591.4  781.73  4684.7   779.6  4778.2  776.14  4819.7   775.4  4871.6  773.11
  4892.4  771.45  4902.8  771.06    4978  769.83  4985.5  769.41  4992.3  768.24
  4992.8  767.44  4998.2  767.44  4998.7  768.24  5015.6   768.3  5035.6  770.51
  5045.6  770.93  5095.7  771.45  5195.9  774.26  5215.9  775.49  5222.8  776.28
  5227.8   776.2  5286.1  781.98  5306.1   783.6  5346.2  785.46    5391  787.06
#Mann= 3 ,-1 , 0
  4451.5      .1       0  4992.3     .07       0  4998.7      .1       0
Bank Sta=4992.3,4998.7
XS Rating Curve= 0 ,0
Exp/Cntr=0.3,0.1

Type RM Length L Ch R = 1 ,2592    ,333,333,333
BEGIN DESCRIPTION:
UNT 037 in HW 4.0
END DESCRIPTION:
XS GIS Cut Line= 3
      1986102.72      13640398.3        1986075.       13640025.
      1986012.48     13639419.55
#Sta/Elev= 30
  4605.1  782.98  4668.6  782.51  4798.9  780.56  4913.1   777.8  4929.3  776.88
  4969.4  772.94  4976.9  770.44  4981.9  770.44  4989.5  767.92  4999.5  766.92
  5019.6  768.05  5049.8  768.46    5090  768.15  5127.2  766.83  5127.7  766.03
  5133.1  766.03  5133.6  766.83  5180.5   770.3  5210.7  769.12  5260.9  769.34
  5331.3  769.93  5351.4  770.84  5371.5   770.7  5401.7  771.78  5431.8  774.11
  5482.1  779.24  5511.1  779.23  5516.1  780.64  5552.5   781.8  5588.1  784.28
#Mann= 3 ,-1 , 0
  4605.1      .1       0  5127.2     .07       0  5133.6      .1       0
Bank Sta=5127.2,5133.6
XS Rating Curve= 0 ,0
Exp/Cntr=0.3,0.1

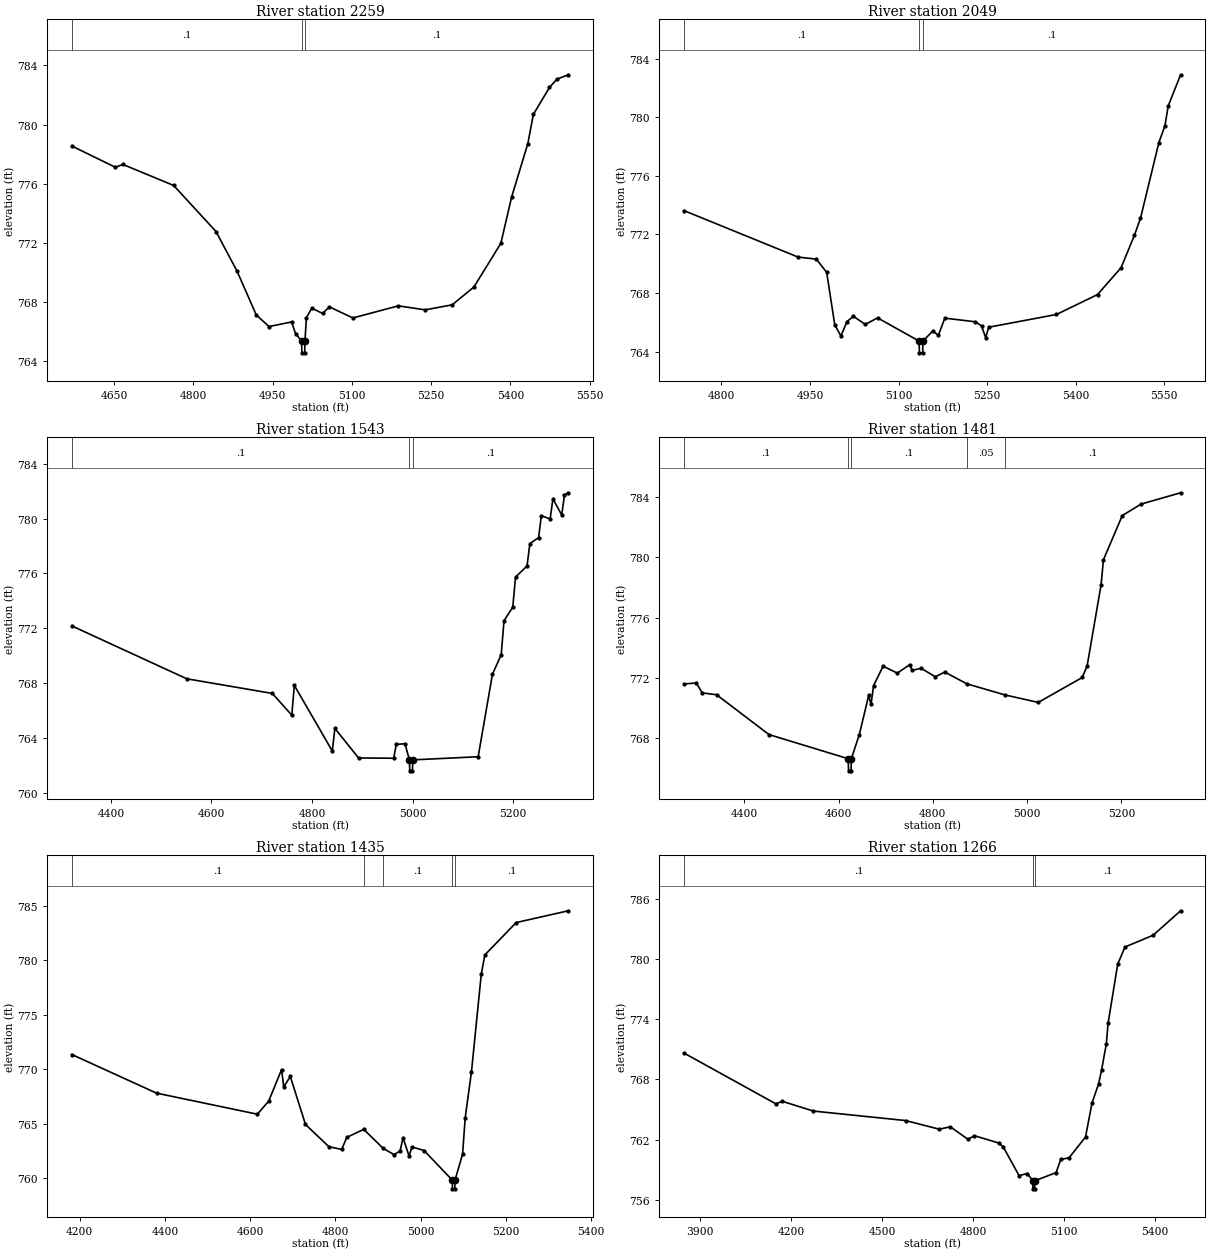
Type RM Length L Ch R = 1 ,2259    ,210,210,210
BEGIN DESCRIPTION:
UNT 037 in HW 3.0
END DESCRIPTION:
XS GIS Cut Line= 3
      1986307.57     13640287.15        1986275.       13639875.
      1986165.22     13639360.11
#Sta/Elev= 30
  4569.8  778.55  4652.2  777.11  4666.6   777.3  4762.6  775.88  4842.8  772.76
  4882.9  770.06  4918.9  767.12  4943.1  766.33  4985.8  766.64  4993.5  765.84
  5004.8  765.35  5005.3  764.55  5010.7  764.55  5011.2  765.35  5013.9  766.93
  5024.1  767.57  5044.6  767.22  5057.5  767.66    5102  766.91  5187.7  767.73
  5238.9  767.46  5289.9   767.8  5330.9     769    5382  771.96  5402.5  775.11
  5433.1  778.71  5443.6  780.69    5474  782.51  5488.1  783.07  5509.7  783.37
#Mann= 3 ,-1 , 0
  4569.8      .1       0  5004.8     .07       0  5011.2      .1       0
Bank Sta=5004.8,5011.2
XS Rating Curve= 0 ,0
Exp/Cntr=0.3,0.1

Type RM Length L Ch R = 1 ,2049    ,506,506,506
BEGIN DESCRIPTION:
Mapping XS 5293676d
END DESCRIPTION:
XS GIS Cut Line= 2
      1986533.27     13640141.34      1986314.69     13639329.45
#Sta/Elev= 30
  4736.8  773.62  4929.8  770.45  4960.8  770.31  4978.3   769.4  4991.9  765.83
  5002.3  765.06  5012.6  766.04  5023.4  766.41  5043.7  765.85  5064.4   766.3
  5134.8  764.71  5135.3  763.91  5140.8  763.91  5141.3  764.71  5157.6  765.39
  5167.6  765.12  5178.3  766.28  5230.1  766.03  5240.5  765.75  5247.5  764.95
  5252.7  765.66  5367.4  766.53  5436.9  767.89  5476.9  769.73  5499.4  771.94
  5509.7   773.1  5540.8  778.27  5551.1  779.42  5556.7  780.78  5577.6   782.9
#Mann= 3 ,-1 , 0
  4736.8      .1       0  5134.8     .07       0  5141.3      .1       0
Bank Sta=5134.8,5141.3
XS Rating Curve= 0 ,0
Exp/Cntr=0.3,0.1

Type RM Length L Ch R = 1 ,1543    ,62,62,62
BEGIN DESCRIPTION:
Mapping XS 55ee9274
END DESCRIPTION:
XS GIS Cut Line= 6
      1986585.35     13640113.59       1986592.3     13639735.07
      1986633.96     13639457.29      1986599.24     13639429.51
      1986515.91      13639419.1      1986335.36     13639335.77
#Sta/Elev= 30
  4322.4  772.17    4551  768.31  4721.2  767.24  4759.8  765.65  4764.8  767.83
  4840.4  763.03  4845.4  764.69  4892.5  762.53  4962.3  762.51  4967.5  763.52
  4984.7  763.57  4993.7  762.39  4994.2  761.59  4999.7  761.59  5000.2  762.39
  5130.3  762.62  5158.7  768.64  5176.1  770.07  5181.7  772.55  5199.1  773.54
  5204.6  775.73  5227.5  776.55  5233.1  778.18  5250.5  778.62    5256  780.23
  5273.4  779.97  5278.9  781.45  5296.4  780.27  5301.9  781.72  5309.5  781.89
#Mann= 3 ,-1 , 0
  4322.4      .1       0  4993.7     .07       0  5000.2      .1       0
Bank Sta=4993.7,5000.2
XS Rating Curve= 0 ,0
Exp/Cntr=0.3,0.1

Type RM Length L Ch R = 1 ,1481    ,46,46,46
BEGIN DESCRIPTION:
Mapping XS aaaa9ed7
END DESCRIPTION:
XS GIS Cut Line= 6
      1986606.18     13640103.17      1986665.21     13639672.57
      1986686.05     13639478.12      1986658.27     13639394.79
      1986547.16     13639342.71      1986342.29     13639287.15
#Sta/Elev= 30
  4272.4   771.6  4298.2  771.67  4310.9  771.01  4341.2  770.89  4452.5  768.25
  4620.6  766.65  4621.1  765.85  4626.6  765.85  4627.1  766.65    4644  768.25
  4663.9  770.84  4668.9  770.25  4674.3   771.5  4694.5  772.78  4724.7  772.32
  4750.9  772.88  4755.9   772.5    4775  772.64  4805.2  772.08  4825.3  772.39
  4872.1  771.61  4952.5  770.88  5023.5  770.38  5116.8  772.03  5127.2   772.8
  5156.7  778.15  5161.8  779.83  5201.7  782.75  5241.5  783.51  5325.4  784.26
#Mann= 5 ,-1 , 0
  4272.4      .1       0  4620.6     .07       0  4627.1      .1       0
  4872.1     .05       0  4952.5      .1       0
Bank Sta=4620.6,4627.1
XS Rating Curve= 0 ,0
Exp/Cntr=0.3,0.1

Type RM Length L Ch R = 1 ,1435    ,169,169,169
BEGIN DESCRIPTION:
Mapping XS 94b10944
END DESCRIPTION:
XS GIS Cut Line= 5
      1986651.33     13640141.29      1986738.13     13639599.65
      1986720.77     13639401.74      1986623.55     13639301.04
      1986358.14     13639218.32
#Sta/Elev= 30
  4181.3  771.35  4380.1  767.81  4616.7  765.88  4643.4  767.08  4673.6  769.97
  4678.7  768.38  4694.1  769.34  4729.7  764.94  4784.7   762.9  4814.8  762.65
  4826.4  763.75  4866.3  764.49  4912.3  762.74  4937.5  762.18  4951.6   762.5
  4958.6  763.72  4972.7  762.06  4979.7  762.88    5008  762.55  5074.2  759.84
  5074.7  759.04  5080.2  759.04  5080.7  759.84  5098.4  762.23  5104.6  765.56
  5119.3  769.78  5142.4  778.76  5150.8  780.48  5224.1  783.44  5346.5  784.52
#Mann= 5 ,-1 , 0
  4181.3      .1       0  4866.3     .05       0  4912.3      .1       0
  5074.2     .07       0  5080.7      .1       0
Bank Sta=5074.2,5080.7
XS Rating Curve= 0 ,0
Exp/Cntr=0.3,0.1

Type RM Length L Ch R = 1 ,1266    ,218,218,218
BEGIN DESCRIPTION:
Mapping XS da55bde3
END DESCRIPTION:
XS GIS Cut Line= 4
      1986784.55     13640210.14      1987079.71     13639719.66
      1986693.42     13639085.98      1986389.78     13638977.54
#Sta/Elev= 30
  3847.8  770.62  4150.3  765.56  4171.7  765.81    4274  764.84  4578.6  763.89
  4688.9  763.03  4725.7  763.27  4783.8  762.02  4805.1  762.38  4884.5  761.66
    4900  761.27  4952.2   758.4  4979.4  758.61  4997.5  757.88    4998  757.08
  5003.5  757.08    5004  757.88  5074.3   758.7  5089.8  760.02  5116.9  760.17
  5171.3  762.25  5192.6  765.62  5214.5  767.56  5224.4  768.95    5240  771.56
  5245.7  773.59  5277.5   779.5  5301.6  781.21  5394.3  782.38  5484.8  784.82
#Mann= 3 ,-1 , 0
  3847.8      .1       0  4997.5     .07       0    5004      .1       0
Bank Sta=4997.5,5004
XS Rating Curve= 0 ,0
Exp/Cntr=0.3,0.1

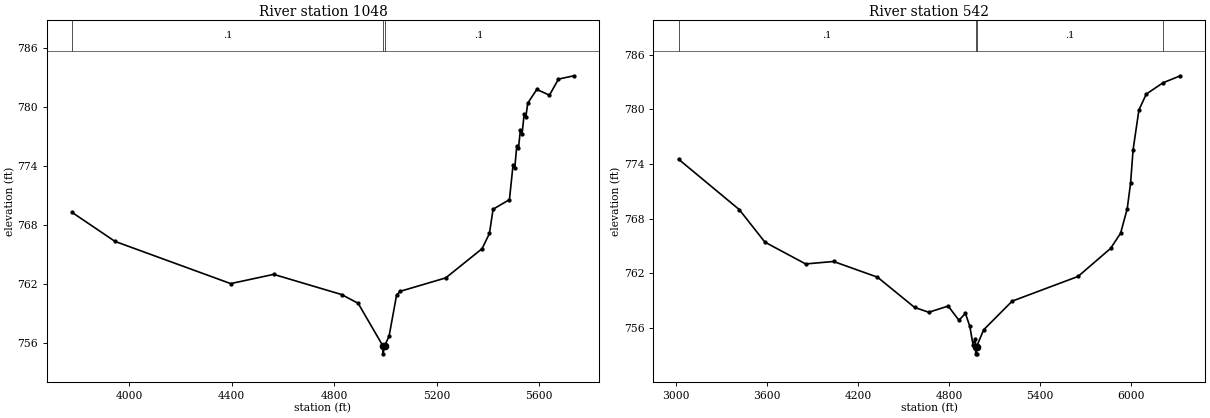
Type RM Length L Ch R = 1 ,1048    ,506,506,506
BEGIN DESCRIPTION:
UNT 037 in HW 1.0
END DESCRIPTION:
XS GIS Cut Line= 4
      1987008.96     13640254.17      1987311.05     13639665.62
      1986920.42     13639139.58      1986426.77     13638729.07
#Sta/Elev= 30
  3776.6  769.29  3944.3  766.34  4395.8  762.05  4563.5  762.99  4828.5  760.94
  4893.2  760.05  4990.1  755.71  4990.6  754.91  4996.6  755.71  5014.2  756.72
  5043.4  760.89    5058  761.27  5235.2  762.63  5377.1   765.6  5405.8  767.15
  5420.1  769.61  5483.9  770.59  5498.2  774.15  5504.7  773.77  5512.5  776.06
    5519  775.79  5526.9   777.7  5533.4   777.3  5541.2  779.25  5547.7  778.97
  5555.5   780.4  5590.7  781.79  5640.1  781.21  5675.3  782.84  5735.4  783.18
#Mann= 3 ,-1 , 0
  3776.6      .1       0  4990.1     .07       0  4996.6      .1       0
Bank Sta=4990.1,4996.6
XS Rating Curve= 0 ,0
Exp/Cntr=0.3,0.1

Type RM Length L Ch R = 1 ,542     ,0,0,0
BEGIN DESCRIPTION:
SF PEREZ CREEK 108.0
END DESCRIPTION:
XS GIS Cut Line= 5
      1986790.24     13640556.23      1987868.34     13639530.21
      1987316.25     13639097.92      1986545.42     13638691.67
      1986295.43     13638676.04
#Sta/Elev= 30
  3015.9  774.52  3416.2     769  3586.1  765.42  3854.7  763.03  4038.7   763.3
  4328.7  761.58  4573.8  758.26    4667  757.73  4795.3  758.41  4865.9  756.86
  4909.3   757.6  4938.2  756.17    4959  754.19  4973.5  754.81  4976.6  753.97
  4977.1  753.17  4982.6  753.17  4983.1  753.97  5029.5  755.81  5217.4  758.95
  5652.3  761.66  5866.9  764.73    5933   766.4  5977.1  769.11  5999.1  771.93
  6015.5  775.55  6053.9  779.92  6102.8  781.67  6212.9   782.9  6327.2  783.67
#Mann= 4 ,-1 , 0
  3015.9      .1       0  4976.6     .07       0  4983.1      .1       0
  6212.9     .05       0
Bank Sta=4976.6,4983.1
XS Rating Curve= 0 ,0
Exp/Cntr=0.3,0.1
LCMann Table=0

Chan Stop Cuts=-1
Use User Specified Reach Order=0
Composite Channel Slope=5