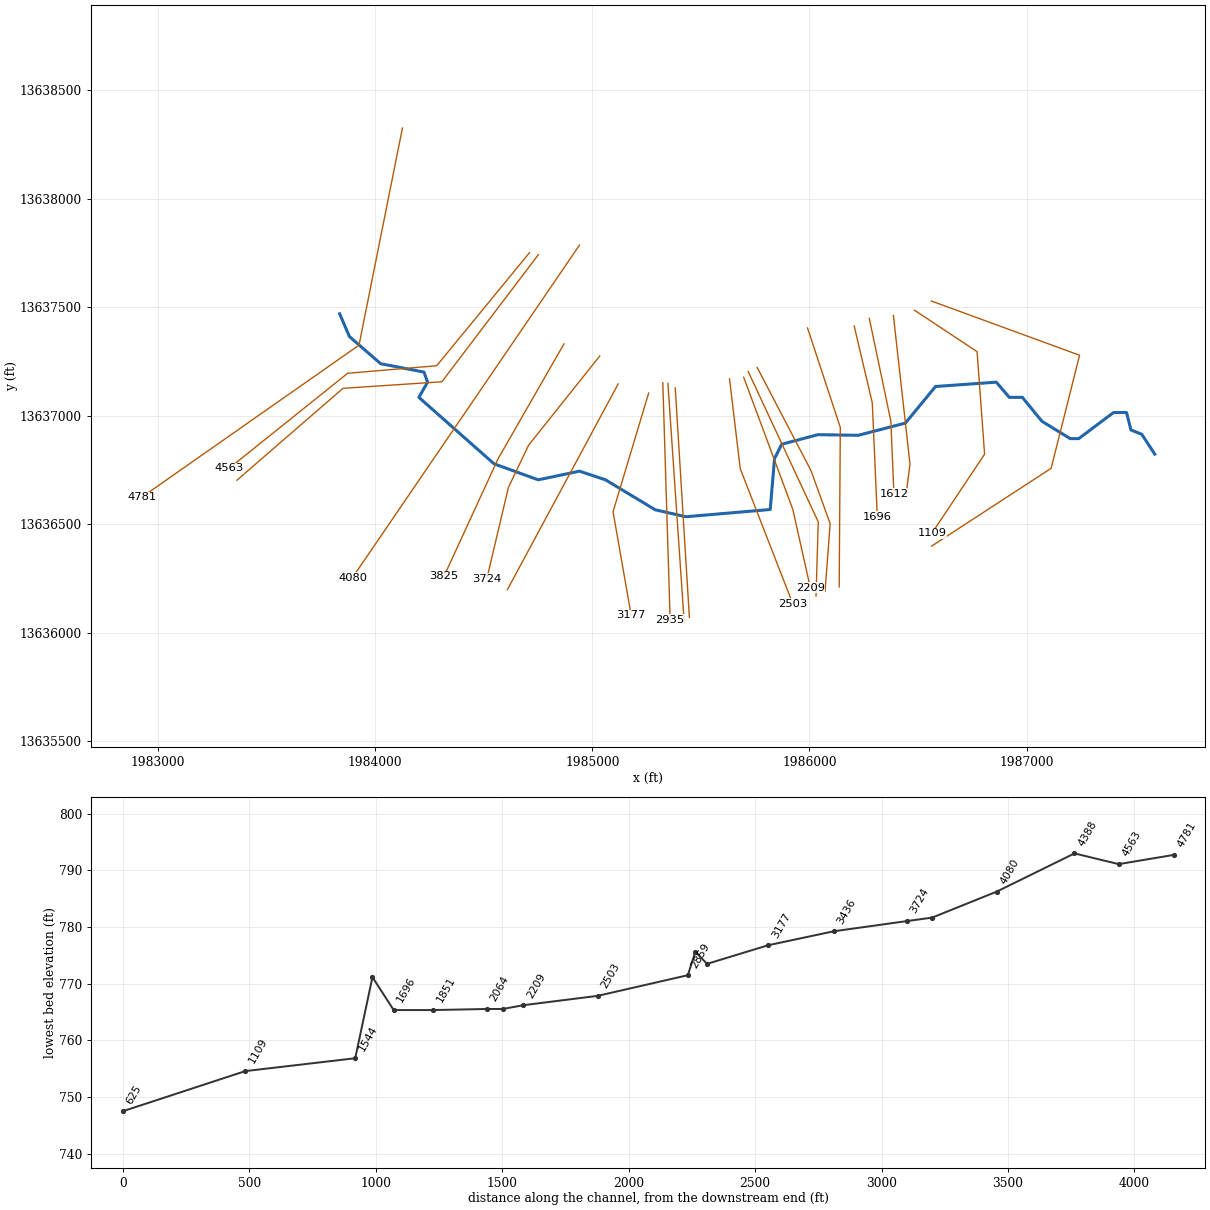
--- UNT 038 in HW.prj (project) ---

Proj Title=UNT 038 in HW Base Level Engineering
Current Plan=p01
Default Exp/Contr=0.3,0.1
English Units
Geom File=g01
Flow File=f01
Plan File=p01
Y Axis Title=Elevation
X Axis Title(PF)=Main Channel Distance
X Axis Title(XS)=Station
BEGIN DESCRIPTION:
UNT 038 in HW
END DESCRIPTION:
DSS Export Rating Curves= 0
DSS Export Rating Curve Sorted= 0
DSS Export Volume Flow Curves= 0
DXF OffsetX= 0
DXF OffsetY= 0
DXF ScaleX= 1
DXF ScaleY= 10

--- UNT 038 in HW.p01 (plan) ---

Plan Title=Multiple Run
Short Identifier=Multiple
Geom File=g01
Flow File=f01
Subcritical Flow
K Sum by GR= 0
Std Step Tol= 0.01
Critical Tol= 0.01
Num of Std Step Trials= 20
Max Error Tol= 0.3
Flow Tol Ratio= 0.001
Split Flow NTrial= 30
Split Flow Tol= 0.02
Split Flow Ratio= 0.02
Log Output Level= 0
Friction Slope Method= 1
Unsteady Friction Slope Method= 2
Unsteady Bridges Friction Slope Method= 1
Parabolic Critical Depth
Global Vel Dist=  1 , 1 , 1
Global Log Level= 0
CheckData=True
Encroach Param= -1, 0, 0, 0
BEGIN DESCRIPTION:
Multiple Run
END DESCRIPTION:

--- UNT 038 in HW.f01 (steady flow) ---

Flow Title=Multiple
Number of Profiles=7
Profile Names=10-year,25-year,50-year,1pct_min,100-year,1pct_plu,500-year
River Rch & RM= UNT 038 in HW,Reach-1,4781
     502     705     874     538    1073    2141    1623
Boundary for River Rch & Prof#=UNT 038 in HW,Reach-1,1
Up Type=0
Dn Type=3
Dn Slope=0.005
Boundary for River Rch & Prof#=UNT 038 in HW,Reach-1,2
Up Type=0
Dn Type=3
Dn Slope=0.005
Boundary for River Rch & Prof#=UNT 038 in HW,Reach-1,3
Up Type=0
Dn Type=3
Dn Slope=0.005
Boundary for River Rch & Prof#=UNT 038 in HW,Reach-1,4
Up Type=0
Dn Type=3
Dn Slope=0.005
Boundary for River Rch & Prof#=UNT 038 in HW,Reach-1,5
Up Type=0
Dn Type=3
Dn Slope=0.005
Boundary for River Rch & Prof#=UNT 038 in HW,Reach-1,6
Up Type=0
Dn Type=3
Dn Slope=0.005
Boundary for River Rch & Prof#=UNT 038 in HW,Reach-1,7
Up Type=0
Dn Type=3
Dn Slope=0.005

--- UNT 038 in HW.g01 (geometry) ---

Geom Title=Existing Conditions
Program Version=5.05

River Reach=UNT 038 in HW   ,Reach-1
Reach XY= 30
       1983835.8     13637469.54       1983880.8     13637364.54
      1984024.83     13637239.55      1984224.41     13637200.93
       1984240.8     13637154.54       1984200.8     13637084.54
      1984546.98     13636778.36       1984750.8     13636704.54
       1984940.8     13636744.54       1985060.8     13636704.54
      1985289.41     13636566.63       1985430.8     13636534.54
      1985819.27     13636567.92      1985839.22     13636802.96
      1985872.44     13636868.48      1986038.84     13636912.58
      1986225.09     13636909.71       1986442.1     13636966.14
       1986580.8     13637134.54       1986860.8     13637154.54
       1986920.8     13637084.54       1986980.8     13637084.54
       1987070.8     13636974.54       1987200.8     13636894.54
       1987240.8     13636894.54       1987400.8     13637014.54
       1987460.8     13637014.54       1987480.8     13636934.54
       1987530.8     13636914.54       1987590.8     13636822.91

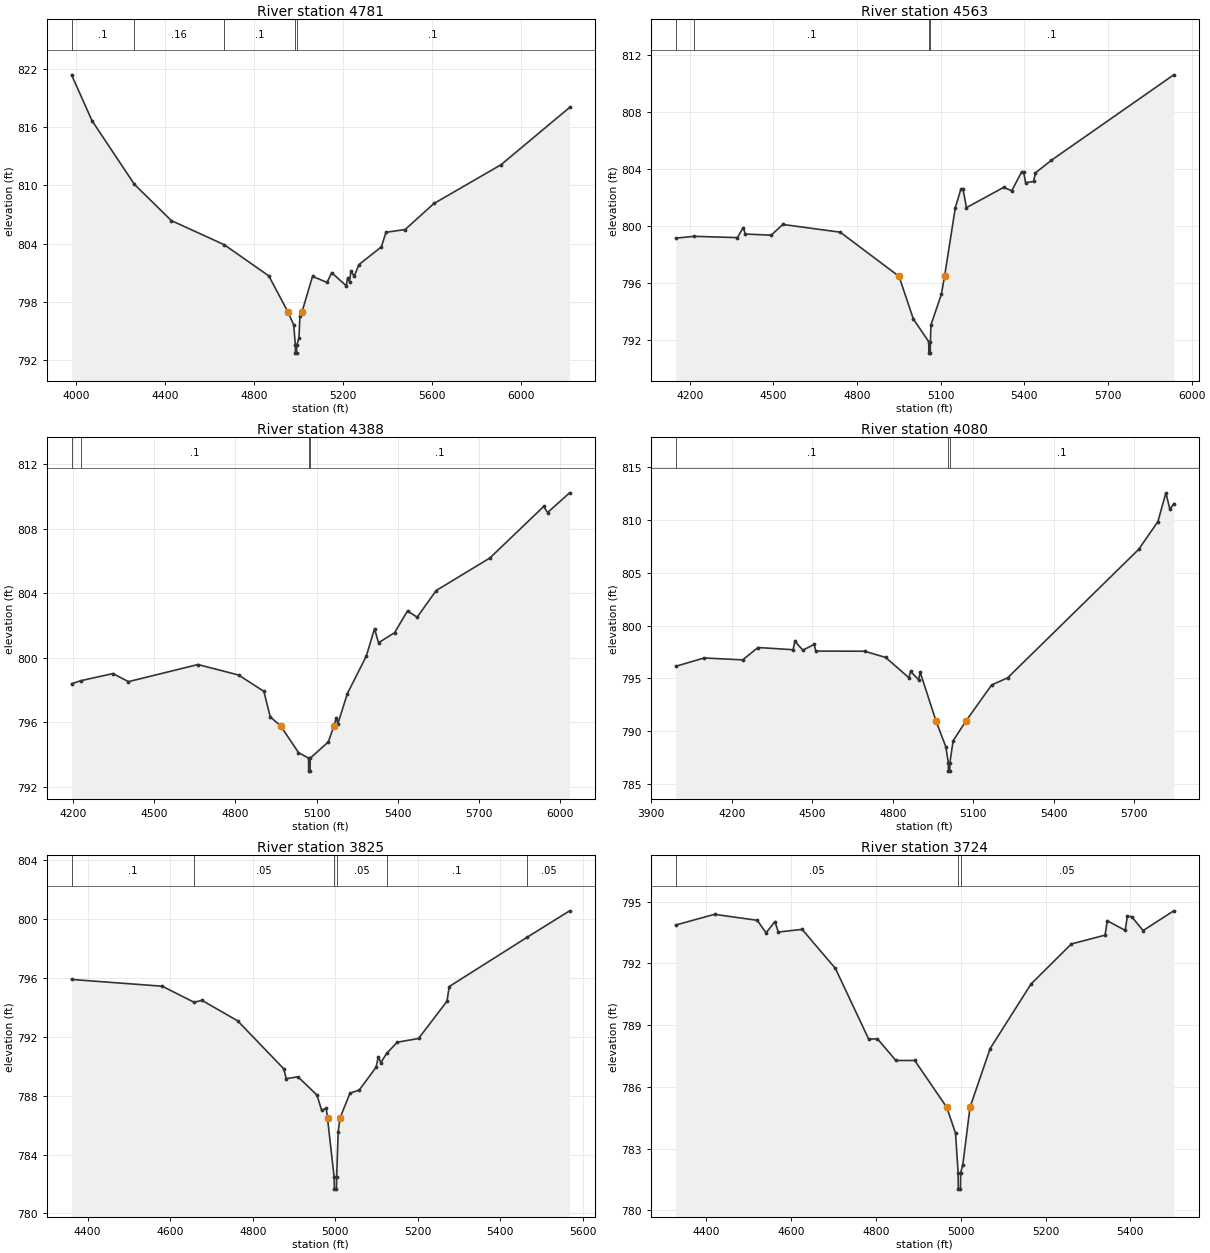
Type RM Length L Ch R = 1 ,4781    ,218,218,218
BEGIN DESCRIPTION:
UNT 038 in HW 11.0
END DESCRIPTION:
XS GIS Cut Line= 3
      1984125.01     13638325.05        1983925.       13637325.
      1982925.01       13636625.
#Sta/Elev= 30
  3979.4   821.4  4071.2  816.68  4261.9  810.12  4428.2  806.38  4666.3  803.89
  4866.7  800.68 4951.77797.0042  4978.9  795.63  4986.1  793.52  4986.6  792.72
  4991.6  792.72  4992.1  793.52  5002.3  794.27  5006.7  796.56 5016.51797.0045
  5063.3  800.63  5128.7  800.01  5149.7  801.01    5215  799.66  5221.1  800.48
  5229.9  800.08    5236  801.18  5250.8  800.64  5271.7  801.83  5372.9  803.67
  5393.8  805.17  5480.1  805.46  5609.6  808.14  5911.7  812.14  6219.9  818.04
#Mann= 5 ,-1 , 0
  3979.4      .1       0  4261.9     .16       0  4666.3      .1       0
  4986.1     .07       0  4992.1      .1       0
Bank Sta=4951.77,5016.51
XS Rating Curve= 0 ,0
Exp/Cntr=0.3,0.1

Type RM Length L Ch R = 1 ,4563    ,175,175,175
BEGIN DESCRIPTION:
Mapping XS 7c08de2a
END DESCRIPTION:
XS GIS Cut Line= 4
      1984710.43     13637751.03      1984282.92     13637230.21
      1983872.77     13637195.49       1983325.9     13636757.13
#Sta/Elev= 30
  4149.5  799.14    4215  799.27  4370.8  799.18  4391.6  799.88  4399.5  799.43
  4492.1  799.35  4533.7   800.1  4739.6  799.56  4950.6796.4658  5001.9  793.48
    5057  791.89  5057.5  791.09  5062.5  791.09    5063  791.89    5065  793.06
  5102.2   795.2 5113.84796.4656  5152.4  801.27  5172.5  802.59  5179.5  802.61
  5192.5  801.28  5325.9   802.7  5354.7  802.46  5389.9  803.77  5397.9  803.77
  5404.3  803.03  5433.1  803.11  5439.5  803.71  5497.2   804.6  5935.8  810.58
#Mann= 4 ,-1 , 0
  4149.5     .16       0    4215      .1       0    5057     .07       0
    5063      .1       0
Bank Sta=4950.6,5113.84
XS Rating Curve= 0 ,0
Exp/Cntr=0.3,0.1

Type RM Length L Ch R = 1 ,4388    ,308,308,308
BEGIN DESCRIPTION:
Mapping XS a667b1c5
END DESCRIPTION:
XS GIS Cut Line= 4
      1984751.65     13637742.34       1984306.8     13637156.42
      1983851.07     13637126.04      1983362.81     13636702.89
#Sta/Elev= 30
  4195.5  798.39  4229.9  798.58  4348.1  799.02  4405.6  798.52  4662.1  799.58
  4811.9  798.93  4905.4  797.92  4928.9  796.34 4967.67795.7705  5033.2  794.13
  5070.3  793.78  5070.8  792.98  5075.8  792.98  5076.3  793.78  5143.4  794.79
 5163.69795.7704  5173.3   796.3  5178.3   795.9  5213.6  797.78  5283.7  800.11
  5313.8   801.8  5328.6  800.93  5387.9  801.55  5435.6   802.9  5471.1  802.51
  5541.5  804.16    5740  806.18  5938.5  809.37  5952.6  808.99    6034  810.21
#Mann= 4 ,-1 , 0
  4195.5     .16       0  4229.9      .1       0  5070.3     .07       0
  5076.3      .1       0
Bank Sta=4967.67,5163.69
XS Rating Curve= 0 ,0
Exp/Cntr=0.3,0.1

Type RM Length L Ch R = 1 ,4080    ,255,255,255
BEGIN DESCRIPTION:
Mapping XS cb6acff0
END DESCRIPTION:
XS GIS Cut Line= 2
      1984940.82     13637786.06      1983894.83     13636253.97
#Sta/Elev= 30
  3991.5  796.15  4097.5  796.94  4241.1  796.76    4298  797.93  4428.7  797.72
  4435.5  798.53    4465  797.68  4507.3  798.22  4513.4  797.59  4695.1  797.58
  4773.5  796.99  4860.3  795.07  4866.3  795.66  4896.2  794.89  4902.2  795.58
 4961.79790.9333  4997.8  788.52  5006.9  787.03  5007.4  786.23  5012.4  786.23
  5012.9  787.03  5024.8   789.1 5071.52790.9337  5168.4  794.39  5227.8  795.06
  5715.7  807.21  5787.5  809.84  5817.4  812.57  5832.3  811.01  5846.6  811.54
#Mann= 3 ,-1 , 0
  3991.5      .1       0  5006.9     .07       0  5012.9      .1       0
Bank Sta=4961.79,5071.52
XS Rating Curve= 0 ,0
Exp/Cntr=0.3,0.1

Type RM Length L Ch R = 1 ,3825    ,101,101,101
BEGIN DESCRIPTION:
UNT 038 in HW 9.0
END DESCRIPTION:
XS GIS Cut Line= 3
      1984869.22      13637330.8      1984565.39     13636801.26
      1984316.11     13636259.36
#Sta/Elev= 30
    4361  795.89  4580.7  795.43  4657.9  794.34  4677.1  794.47  4763.4  793.08
    4875  789.83  4881.3  789.15  4909.6  789.28  4955.7  788.04  4966.9  787.02
  4978.4  787.13 4981.27786.4669  4997.4  782.45  4997.9  781.65  5002.9  781.65
  5003.4  782.45  5007.1  785.54 5011.38786.4659  5035.6  788.16  5058.6  788.39
    5099  789.93  5104.5  790.64  5110.5  790.24  5124.9  790.88  5150.5  791.63
  5201.9  791.88  5270.8  794.41  5276.3  795.41  5465.9  798.77    5568  800.55
#Mann= 6 ,-1 , 0
    4361      .1       0  4657.9     .05       0  4997.4     .04       0
  5003.4     .05       0  5124.9      .1       0  5465.9     .05       0
Bank Sta=4981.27,5011.38
XS Rating Curve= 0 ,0
Exp/Cntr=0.3,0.1

Type RM Length L Ch R = 1 ,3724    ,288,288,288
BEGIN DESCRIPTION:
UNT 038 in HW 8.0
END DESCRIPTION:
XS GIS Cut Line= 4
      1985034.13     13637275.21      1984706.01     13636863.76
      1984613.17     13636669.25      1984513.72     13636248.33
#Sta/Elev= 30
  4327.9  793.86  4419.4  794.38    4520  794.09  4541.1  793.48  4561.9  794.03
  4569.9  793.52    4626  793.65  4704.5  791.75  4782.9  788.32  4803.7  788.33
    4847  787.28  4891.5  787.28 4966.93785.0071  4987.7  783.75  4993.8  781.83
  4994.3  781.03  4999.3  781.03  4999.8  781.83  5004.9  782.22 5021.87 785.007
  5069.3  787.86  5165.9     791  5260.8  792.94  5340.3  793.37  5345.4  794.07
  5387.7   793.6  5392.8  794.28  5402.9  794.27    5430  793.59  5502.2  794.55
#Mann= 3 ,-1 , 0
  4327.9     .05       0  4993.8     .04       0  4999.8     .05       0
Bank Sta=4966.93,5021.87
XS Rating Curve= 0 ,0
Exp/Cntr=0.3,0.1

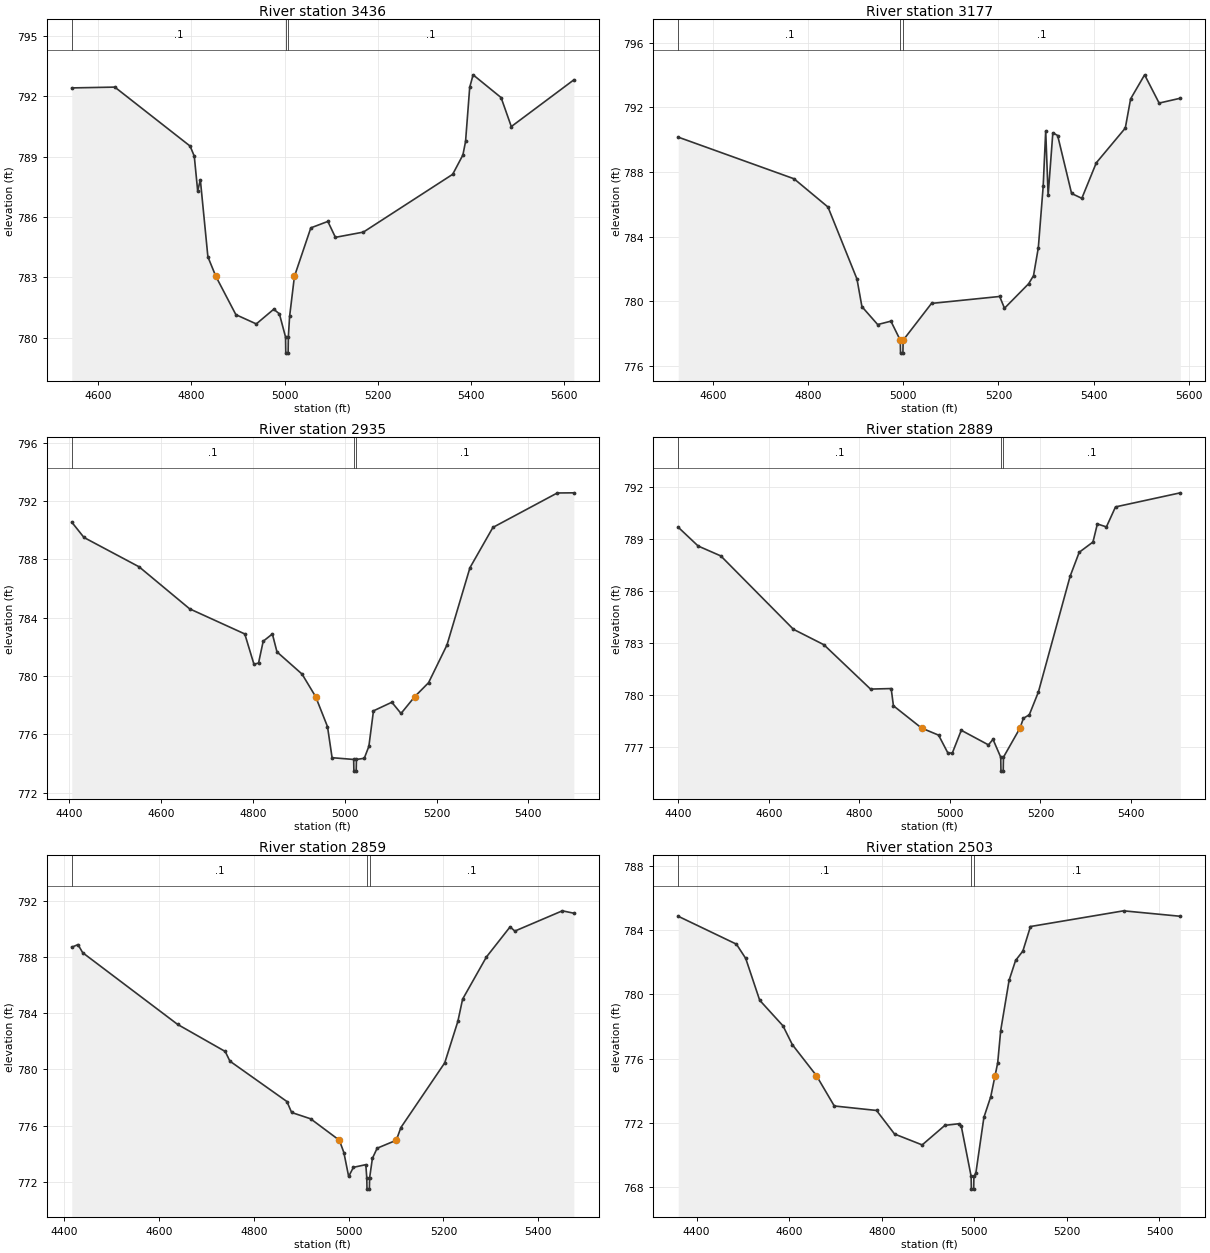
Type RM Length L Ch R = 1 ,3436    ,259,259,259
BEGIN DESCRIPTION:
Mapping XS 8e04e6b1
END DESCRIPTION:
XS GIS Cut Line= 2
      1985118.76      13637146.3      1984608.35     13636198.38
#Sta/Elev= 30
  4543.7  792.41    4636  792.45  4797.5  789.52  4806.4  789.02  4813.7  787.29
  4819.4  787.85  4835.6  784.02 4852.69 783.051  4895.6  781.15  4939.4  780.69
  4976.8  781.42  4988.9  781.19  5002.1  780.04  5002.6  779.24  5007.6  779.24
  5008.1  780.04  5010.8  781.06 5021.15783.0519  5056.3  785.46  5092.8  785.78
    5109  784.99    5169  785.25  5360.5  788.12  5382.4  789.08  5388.1  789.75
    5397  792.44  5404.3  793.06  5464.3  791.93  5486.2  790.49  5620.3  792.81
#Mann= 3 ,-1 , 0
  4543.7      .1       0  5002.1     .07       0  5008.1      .1       0
Bank Sta=4852.69,5021.15
XS Rating Curve= 0 ,0
Exp/Cntr=0.3,0.1

Type RM Length L Ch R = 1 ,3177    ,242,242,242
BEGIN DESCRIPTION:
Mapping XS cfa741f8
END DESCRIPTION:
XS GIS Cut Line= 3
       1985259.4     13637104.65      1985095.33     13636557.77
      1985178.67     13636081.17
#Sta/Elev= 30
  4527.2  790.16  4770.5  787.58  4841.8  785.83  4902.7  781.37  4913.1  779.66
  4946.2  778.55    4974  778.76  4993.7  777.58  4994.2  776.78  4999.2  776.78
  4999.7  777.58  5059.3  779.86  5202.5  780.29  5212.6  779.56  5263.4  781.08
  5273.6  781.58  5283.7  783.31  5293.9  787.11  5299.2  790.55  5304.3  786.55
  5314.2  790.43  5324.3  790.26  5353.6  786.67  5375.1  786.37  5405.5  788.57
  5466.4  790.72  5477.6  792.53    5507  794.02  5537.5  792.27    5582  792.57
#Mann= 3 ,-1 , 0
  4527.2      .1       0  4993.7     .07       0  4999.7      .1       0
Bank Sta=4993.7,4999.7
XS Rating Curve= 0 ,0
Exp/Cntr=0.3,0.1

Type RM Length L Ch R = 1 ,2935    ,46,46,46
BEGIN DESCRIPTION:
Mapping XS 21075328
END DESCRIPTION:
XS GIS Cut Line= 2
       1985324.5     13637151.55      1985358.32     13636058.88
#Sta/Elev= 30
  4405.8  790.55  4432.4   789.5  4552.4  787.49  4662.5  784.61  4782.5  782.89
  4802.5  780.81  4812.5   780.9  4822.6  782.39  4842.6  782.89  4852.6  781.66
  4907.2  780.14 4936.73778.5963  4962.6  776.54  4972.6  774.41  5019.6  774.29
  5020.1  773.49  5025.1  773.49  5025.6  774.29  5042.7  774.37  5052.7  775.19
  5062.7  777.62  5102.7  778.21  5122.7  777.44 5152.64778.5964  5182.7  779.55
  5222.7  782.13  5272.8  787.43  5322.8  790.19  5462.9  792.55    5499  792.56
#Mann= 3 ,-1 , 0
  4405.8      .1       0  5019.6     .07       0  5025.6      .1       0
Bank Sta=4936.73,5152.64
XS Rating Curve= 0 ,0
Exp/Cntr=0.3,0.1

Type RM Length L Ch R = 1 ,2889    ,30,30,30
BEGIN DESCRIPTION:
Mapping XS 66b7cecc
END DESCRIPTION:
XS GIS Cut Line= 2
      1985347.94     13637148.92      1985423.46      13636042.1
#Sta/Elev= 30
  4399.6  789.67  4443.6  788.59  4493.7  788.02  4654.1   783.8  4721.5  782.91
  4824.5  780.36  4870.1  780.39  4875.1   779.4 4937.25778.1183  4974.9  777.71
  4994.9  776.71  5004.9  776.66    5025  777.99  5085.1  777.15  5095.1  777.47
  5112.2  776.44  5112.7  775.64  5117.7  775.64  5118.2  776.44 5154.77778.1183
  5162.3  778.68  5175.3  778.88  5195.4  780.19  5265.5  786.85  5285.6  788.23
    5316  788.82  5325.7  789.86  5345.7  789.69  5365.8  790.84    5509  791.65
#Mann= 3 ,-1 , 0
  4399.6      .1       0  5112.2     .07       0  5118.2      .1       0
Bank Sta=4937.25,5154.77
XS Rating Curve= 0 ,0
Exp/Cntr=0.3,0.1

Type RM Length L Ch R = 1 ,2859    ,356,356,356
BEGIN DESCRIPTION:
Mapping XS 23503baa
END DESCRIPTION:
XS GIS Cut Line= 2
      1985381.79     13637128.06       1985446.9     13636070.76
#Sta/Elev= 30
  4415.9  788.69    4429  788.88    4439   788.3  4639.4   783.2  4739.6  781.28
  4749.6  780.59  4869.8  777.72  4879.8  776.94  4919.9  776.49 4980.47774.9667
    4990  774.09  5000.1  772.39  5010.1  773.04  5036.3  773.23  5038.3  772.29
  5038.8  771.49  5043.8  771.49  5044.3  772.29  5050.2  773.68  5060.2   774.4
 5100.59774.9662  5110.3  775.87  5202.8  780.47  5230.5  783.42  5240.5     785
  5290.6  787.99  5340.7  790.14  5350.7  789.84  5450.9  791.28  5475.2  791.11
#Mann= 3 ,-1 , 0
  4415.9      .1       0  5038.3     .07       0  5044.3      .1       0
Bank Sta=4980.47,5100.59
XS Rating Curve= 0 ,0
Exp/Cntr=0.3,0.1

Type RM Length L Ch R = 1 ,2503    ,294,294,294
BEGIN DESCRIPTION:
Mapping XS 2be0a5ad
END DESCRIPTION:
XS GIS Cut Line= 3
      1985631.79     13637169.77      1985681.27     13636755.69
      1985923.46     13636133.28
#Sta/Elev= 30
  4360.2  784.88  4485.9  783.14    4506  782.25  4536.2  779.64  4586.6  778.04
  4606.7  776.87 4658.71774.9379  4697.4  773.04  4788.7  772.76  4827.6  771.29
  4887.3  770.61  4936.4  771.83  4966.3  771.93  4971.6  771.81  4993.1  768.65
  4993.6  767.85  4998.6  767.85  4999.1  768.65  5003.3  768.85  5020.7  772.33
  5035.5  773.62 5044.87 774.938  5050.5  775.73    5057  777.75  5075.1  780.88
  5089.1  782.12  5104.9  782.71  5121.3  784.24  5322.5  785.22  5445.1  784.88
#Mann= 3 ,-1 , 0
  4360.2      .1       0  4993.1     .07       0  4999.1      .1       0
Bank Sta=4658.71,5044.87
XS Rating Curve= 0 ,0
Exp/Cntr=0.3,0.1

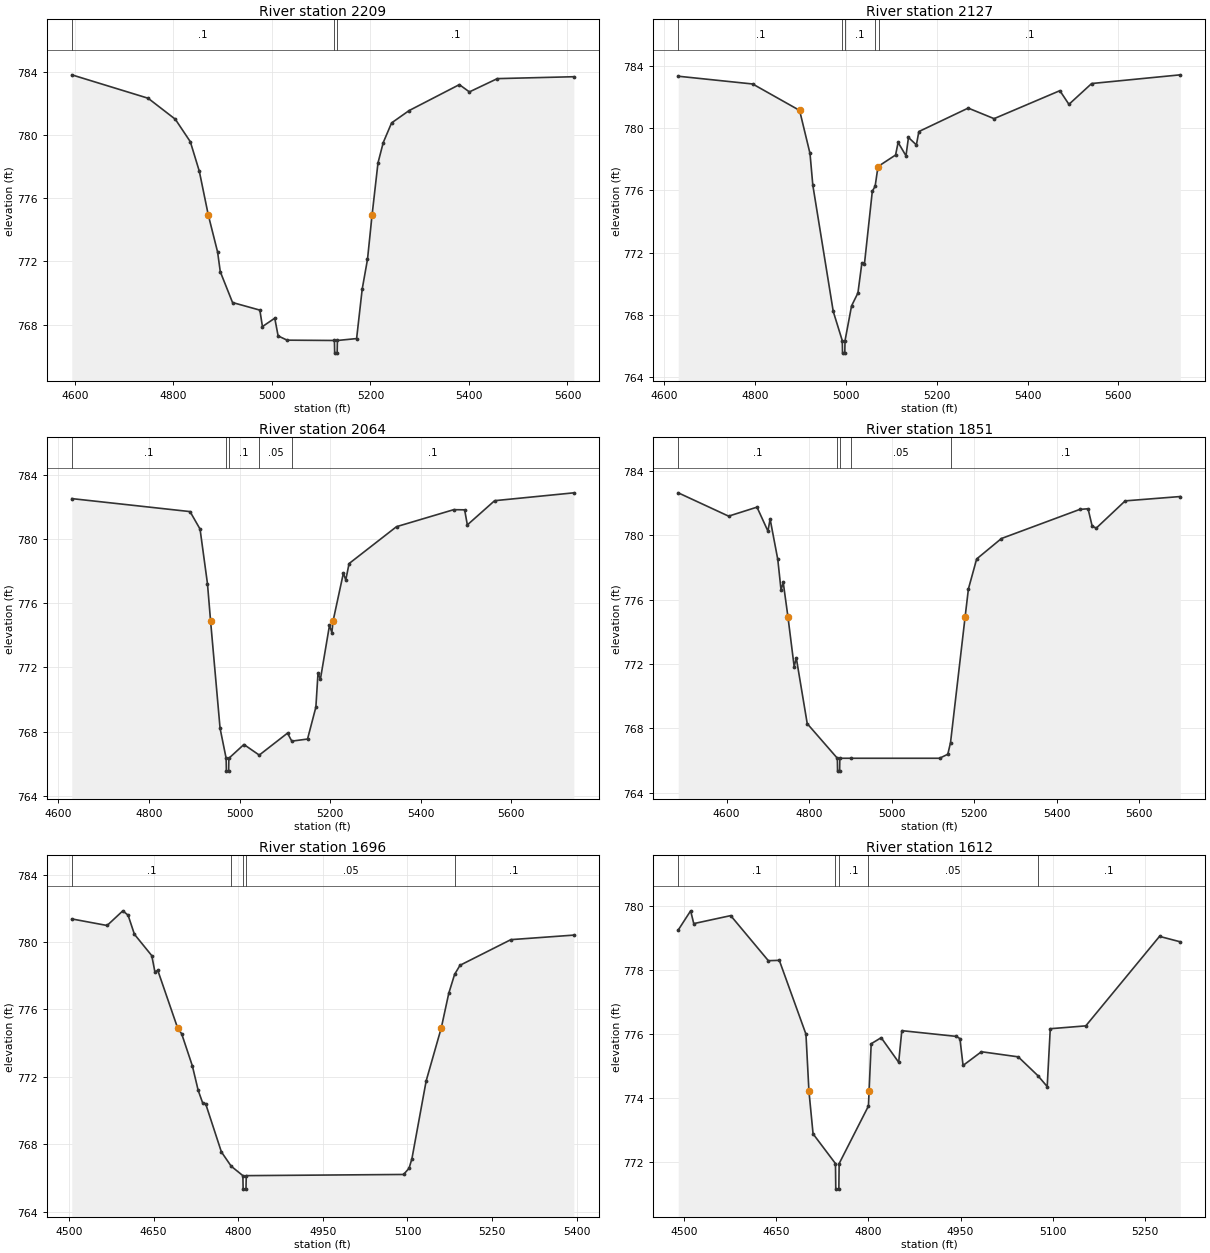
Type RM Length L Ch R = 1 ,2209    ,82,82,82
BEGIN DESCRIPTION:
Mapping XS 3cc23037
END DESCRIPTION:
XS GIS Cut Line= 3
      1985696.91     13637177.53      1985923.46     13636568.19
      1986003.76     13636208.13
#Sta/Elev= 30
  4593.9   783.8  4748.8  782.32  4804.1  780.99  4834.5  779.57  4852.7  777.71
 4871.05774.9252  4889.9  772.59  4895.3  771.35  4920.2   769.4  4975.6  768.92
  4980.9  767.88  5005.9  768.41  5012.7  767.29  5030.9  767.02    5127     767
  5127.5   766.2  5132.5   766.2    5133     767    5172  767.12  5183.4  770.26
  5194.1  772.13 5203.35774.9261  5215.4  778.23  5226.1  779.52    5243  780.76
  5278.6  781.54  5380.5  783.18  5400.9  782.72  5457.6  783.56  5612.9  783.68
#Mann= 3 ,-1 , 0
  4593.9      .1       0    5127     .07       0    5133      .1       0
Bank Sta=4871.05,5203.35
XS Rating Curve= 0 ,0
Exp/Cntr=0.3,0.1

Type RM Length L Ch R = 1 ,2127    ,63,63,63
BEGIN DESCRIPTION:
Mapping XS f6ee332e
END DESCRIPTION:
XS GIS Cut Line= 3
      1985717.74     13637203.58      1986040.65     13636510.89
      1986030.24      13636169.9
#Sta/Elev= 30
    4631  783.35  4794.9  782.85  4898.2  781.15  4921.1  778.38  4927.3  776.34
  4972.3  768.21  4992.2  766.33  4992.7  765.53  4997.7  765.53  4998.2  766.33
  5012.6  768.57  5026.6   769.4  5035.4  771.35  5040.9  771.25  5058.3  775.95
  5064.5  776.27  5070.8  777.53    5073  777.58  5109.5  778.28  5115.1  779.09
  5132.4  778.23  5137.9  779.41  5155.3  778.93  5160.8  779.79  5269.4   781.3
  5326.4  780.62  5471.2  782.42  5491.2  781.54  5541.2  782.88  5736.4  783.44
#Mann= 5 ,-1 , 0
    4631      .1       0  4992.2     .07       0  4998.2      .1       0
  5064.5     .05       0    5073      .1       0
Bank Sta=4898.2,5070.8
XS Rating Curve= 0 ,0
Exp/Cntr=0.3,0.1

Type RM Length L Ch R = 1 ,2064    ,213,213,213
BEGIN DESCRIPTION:
Mapping XS 4394261b
END DESCRIPTION:
XS GIS Cut Line= 4
      1985759.38     13637221.86      1986006.79     13636747.87
      1986095.33     13636503.08      1986071.89     13636190.55
#Sta/Elev= 30
  4629.5  782.52  4890.6  781.71  4912.7  780.62  4929.1  777.21 4935.86774.9124
  4956.9   768.2  4970.3  766.33  4970.8  765.53  4975.8  765.53  4976.3  766.33
  5009.5  767.19  5043.4  766.53  5105.8   767.9  5115.2   767.4    5150  767.53
  5168.4  769.52  5173.1  771.64  5178.4  771.26  5198.4  774.61  5203.7  774.17
 5206.53774.9122  5229.1  777.87  5234.4  777.45  5241.7  778.47  5346.4  780.77
  5472.7  781.83  5496.8  781.82  5502.8  780.88    5563  782.39  5737.9  782.88
#Mann= 5 ,-1 , 0
  4629.5      .1       0  4970.3     .07       0  4976.3      .1       0
  5043.4     .05       0  5115.2      .1       0
Bank Sta=4935.86,5206.53
XS Rating Curve= 0 ,0
Exp/Cntr=0.3,0.1

Type RM Length L Ch R = 1 ,1851    ,155,155,155
BEGIN DESCRIPTION:
Mapping XS bb26a250
END DESCRIPTION:
XS GIS Cut Line= 3
      1985991.16     13637404.15      1986142.21     13636945.79
        1986137.     13636211.41
#Sta/Elev= 30
  4482.6  782.64  4604.7  781.19  4673.5  781.75    4700  780.26  4705.3  781.01
  4723.9   778.5  4731.8   776.6  4737.1  777.07 4748.62774.9137  4763.6  771.84
  4768.8  772.37  4795.3  768.29  4868.3  766.14  4868.8  765.34  4873.8  765.34
  4874.3  766.14  4901.3  766.14    5116  766.14    5136  766.39  5142.6  767.11
  5177.9774.9123    5186  776.67    5206  778.53    5266   779.8    5456  781.61
    5476  781.65    5486  780.56    5496  780.45    5566  782.14  5699.6  782.41
#Mann= 5 ,-1 , 0
  4482.6      .1       0  4868.3    .033       0  4874.3      .1       0
  4901.3     .05       0  5142.6      .1       0
Bank Sta=4748.62,5177.9
XS Rating Curve= 0 ,0
Exp/Cntr=0.3,0.1

Type RM Length L Ch R = 1 ,1696    ,84,84,84
BEGIN DESCRIPTION:
UNT 038 in HW 3.0
END DESCRIPTION:
XS GIS Cut Line= 3
      1986206.19     13637413.06      1986289.52      13637058.9
      1986312.61     13636533.54
#Sta/Elev= 30
  4505.1  781.37  4567.7  780.98  4595.6  781.85  4604.9  781.59  4616.1  780.46
  4646.9  779.19  4652.4  778.23  4657.5  778.32 4692.54774.9125  4699.9  774.55
  4718.8  772.65  4729.1   771.2  4737.2  770.44  4742.3  770.41  4770.2  767.55
  4787.6   766.7  4808.3  766.14  4808.8  765.34  4813.8  765.34  4814.3  766.14
  5093.1  766.21  5102.8  766.58  5107.9  767.15  5133.1  771.76 5159.94774.9128
  5173.1  776.95  5183.5  778.08  5193.1  778.62  5283.2  780.14  5394.8  780.41
#Mann= 5 ,-1 , 0
  4505.1      .1       0  4787.6     .05       0  4808.3    .033       0
  4814.3     .05       0  5183.5      .1       0
Bank Sta=4692.54,5159.94
XS Rating Curve= 0 ,0
Exp/Cntr=0.3,0.1

Type RM Length L Ch R = 1 ,1612    ,68,68,68
BEGIN DESCRIPTION:
UNT 038 in HW 2.0
END DESCRIPTION:
XS GIS Cut Line= 3
      1986275.63     13637448.64        1986375.       13636975.
        1986389.     13636641.14
#Sta/Elev= 30
    4490  779.26  4510.2  779.86  4515.3  779.46  4575.5  779.71  4636.8   778.3
  4654.7  778.31  4698.1     776 4702.98774.2132  4709.7  772.88  4746.2  771.95
  4746.7  771.15  4751.7  771.15  4752.2  771.95  4799.9  773.75 4800.97774.2138
  4804.4   775.7  4820.7  775.89  4849.2  775.12  4854.3  776.11  4943.3  775.93
    4949  775.86  4954.1  775.02    4984  775.45    5044  775.29  5076.1   774.7
  5091.2  774.36  5096.2  776.17  5154.1  776.26  5274.2  779.06  5308.1  778.89
#Mann= 5 ,-1 , 0
    4490      .1       0  4746.2    .033       0  4752.2      .1       0
  4799.9     .05       0  5076.1      .1       0
Bank Sta=4702.98,4800.97
XS Rating Curve= 0 ,0
Exp/Cntr=0.3,0.1

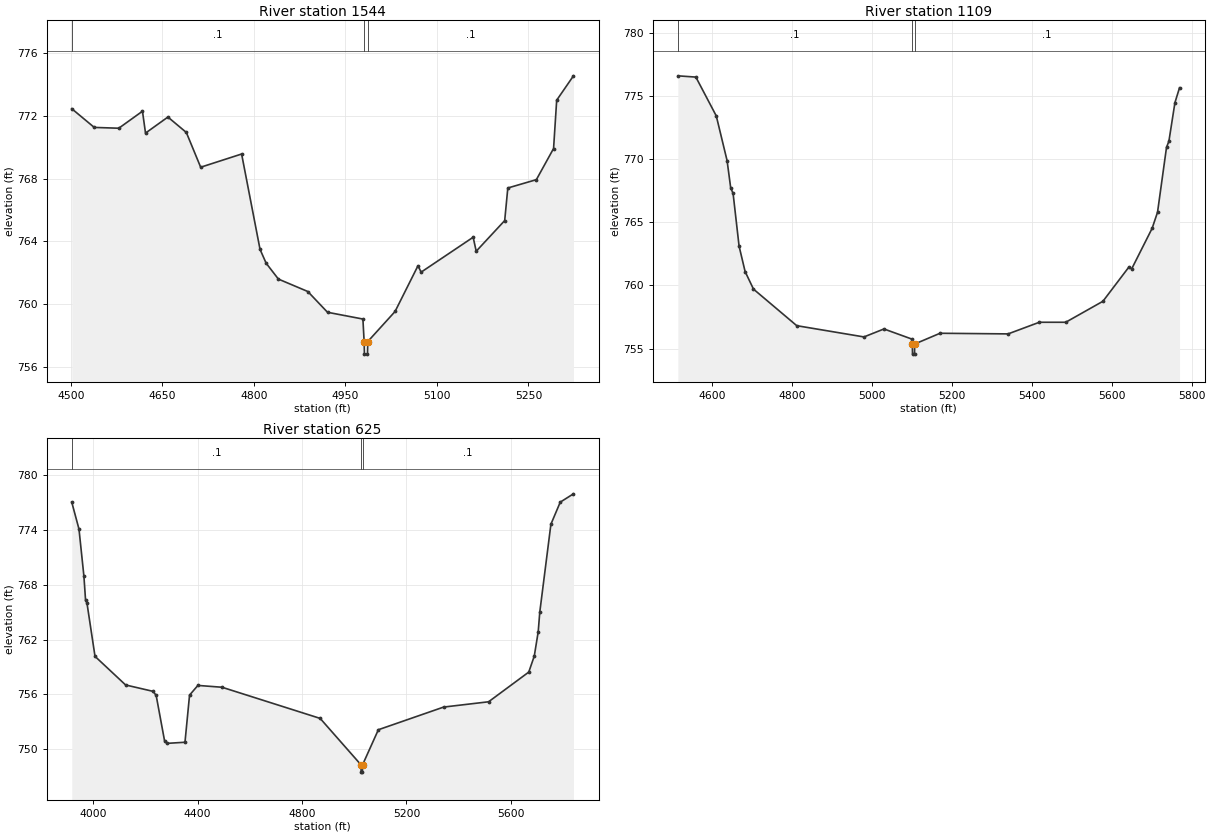
Type RM Length L Ch R = 1 ,1544    ,435,435,435
BEGIN DESCRIPTION:
Mapping XS 6c8c4eed
END DESCRIPTION:
XS GIS Cut Line= 3
      1986386.74     13637461.65      1986463.13     13636777.65
       1986446.3     13636644.66
#Sta/Elev= 30
  4501.4  772.44  4538.3  771.25  4578.5   771.2  4617.3  772.28  4622.3  770.89
    4659  771.91  4689.2  770.93  4712.7  768.72  4779.8  769.56    4810   763.5
    4820  762.62  4840.1  761.61  4888.3  760.82  4920.6   759.5  4978.6  759.07
  4980.6  757.64  4981.1  756.84  4986.1  756.84  4986.6  757.64  5031.3  759.55
  5068.9  762.46    5074  762.05  5159.3  764.27  5164.3  763.38    5211  765.33
  5216.1   767.4  5262.9  767.93  5291.1  769.91  5296.2  772.98  5323.7  774.53
#Mann= 3 ,-1 , 0
  4501.4      .1       0  4980.6     .07       0  4986.6      .1       0
Bank Sta=4980.6,4986.6
XS Rating Curve= 0 ,0
Exp/Cntr=0.3,0.1

Type RM Length L Ch R = 1 ,1109    ,484,484,484
BEGIN DESCRIPTION:
Mapping XS 2b561b4d
END DESCRIPTION:
XS GIS Cut Line= 4
      1986483.94     13637485.99      1986772.16     13637295.01
      1986806.88     13636822.79      1986564.45     13636459.14
#Sta/Elev= 30
  4513.4  776.58  4558.6  776.48  4609.7  773.41  4636.8  769.87  4645.8  767.72
  4651.8  767.28  4666.8  763.11  4681.9   761.1  4702.9  759.71  4811.2  756.82
  4979.5  755.93  5029.6  756.56  5098.6  755.77  5100.6  755.37  5101.1  754.57
  5106.1  754.57  5106.6  755.37    5170  756.22  5340.5  756.17  5418.6  757.09
  5484.7  757.09  5577.9  758.75  5642.5  761.44    5650  761.32  5701.1  764.52
  5714.6  765.79  5737.1  770.92  5743.1  771.41  5758.2  774.46  5769.7  775.64
#Mann= 3 ,-1 , 0
  4513.4      .1       0  5100.6     .07       0  5106.6      .1       0
Bank Sta=5100.6,5106.6
XS Rating Curve= 0 ,0
Exp/Cntr=0.3,0.1

Type RM Length L Ch R = 1 ,625     ,0,0,0
BEGIN DESCRIPTION:
UNT 038 in HW 1.0
END DESCRIPTION:
XS GIS Cut Line= 4
      1986561.28     13637528.52      1987244.38     13637278.52
      1987113.39     13636757.68      1986562.57     13636399.13
#Sta/Elev= 30
  3917.9  777.04  3945.6  774.09  3964.5  768.93  3970.8   766.3  3976.1  766.01
    4007  760.16  4124.2  757.03  4229.5  756.33  4241.3  755.88  4273.3  750.93
  4283.9  750.64  4351.6  750.76  4369.1  755.92  4401.1  756.98  4493.5  756.78
  4869.4  753.37  5025.8  748.29  5026.3  747.49  5031.3  747.49  5031.8  748.29
  5092.3  752.13  5342.3  754.61  5514.5  755.19  5668.4  758.44  5689.5  760.19
  5704.6  762.86  5710.6  765.01  5753.2  774.62    5789  777.04  5839.6  777.95
#Mann= 3 ,-1 , 0
  3917.9      .1       0  5025.8     .07       0  5031.8      .1       0
Bank Sta=5025.8,5031.8
XS Rating Curve= 0 ,0
Exp/Cntr=0.3,0.1
LCMann Table=0

Chan Stop Cuts=-1
Use User Specified Reach Order=0
Composite Channel Slope=5