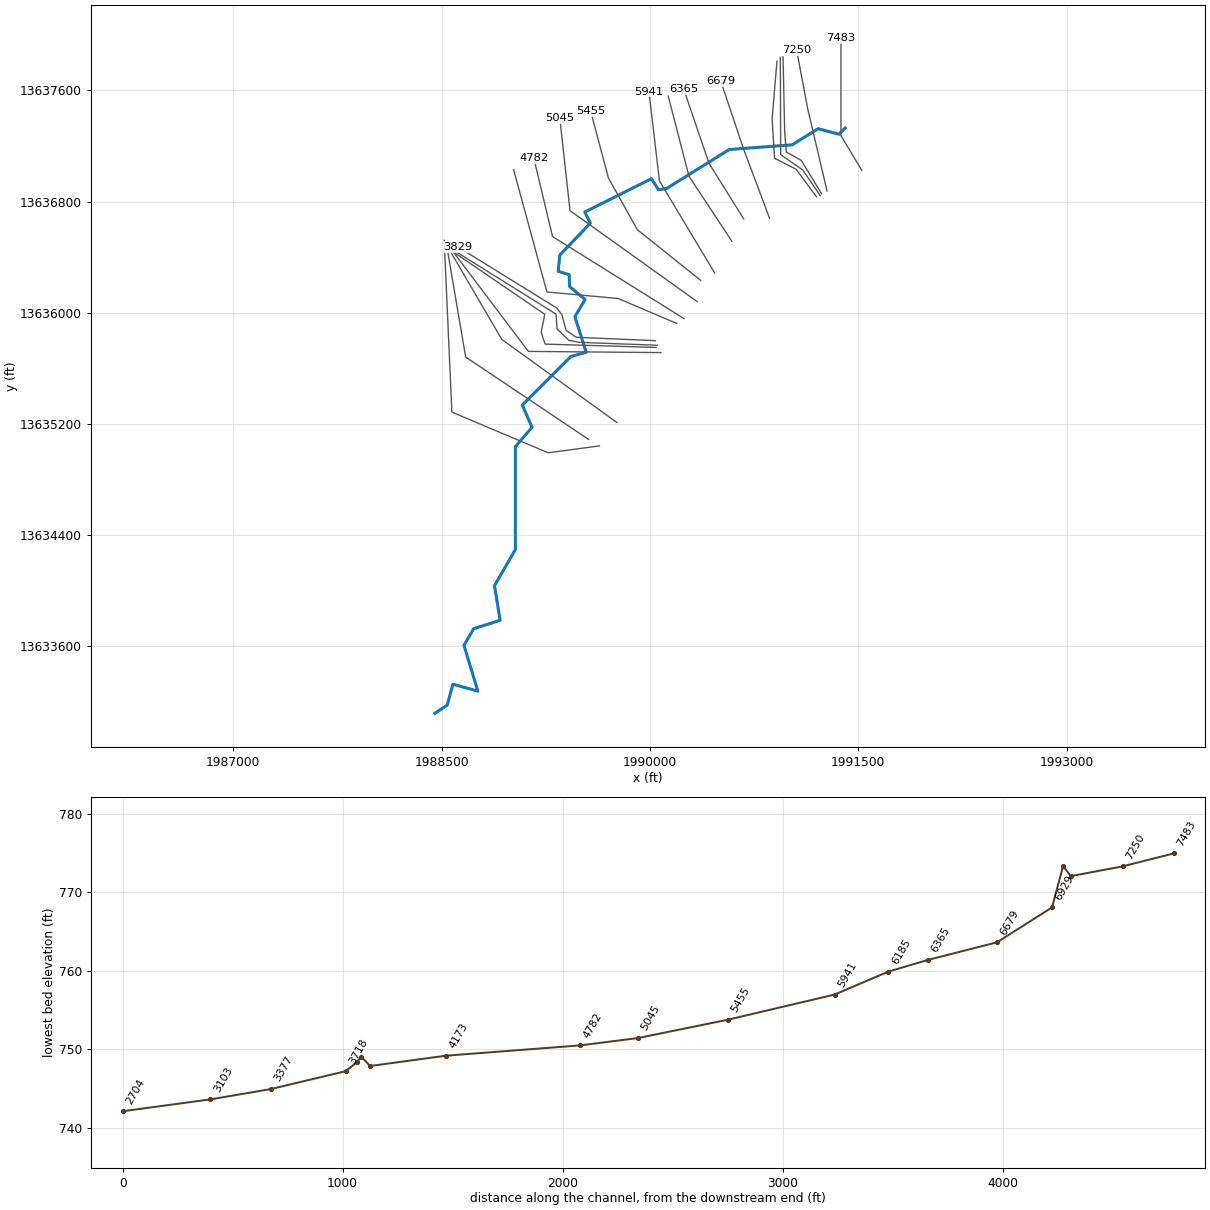
--- UNT 039 in HW.prj (project) ---

Proj Title=UNT 039 in HW Base Level Engineering
Current Plan=p01
Default Exp/Contr=0.3,0.1
English Units
Geom File=g01
Flow File=f01
Plan File=p01
BEGIN DESCRIPTION:
UNT 039 in HW
END DESCRIPTION:

--- UNT 039 in HW.p01 (plan) ---

Plan Title=Multiple Run
Short Identifier=Multiple
Geom File=g01
Flow File=f01
Subcritical Flow
K Sum by GR= 0
Std Step Tol= 0.01
Critical Tol= 0.01
Num of Std Step Trials= 20
Max Error Tol= 0.3
Flow Tol Ratio= 0.001
Split Flow NTrial= 30
Split Flow Tol= 0.02
Split Flow Ratio= 0.02
Log Output Level= 0
Friction Slope Method= 1
Unsteady Friction Slope Method= 2
Unsteady Bridges Friction Slope Method= 1
Parabolic Critical Depth
Global Vel Dist=  1 , 1 , 1
Global Log Level= 0
CheckData=True
Encroach Param= -1, 0, 0, 0
BEGIN DESCRIPTION:
Multiple Run
END DESCRIPTION:

--- UNT 039 in HW.f01 (steady flow) ---

Flow Title=Multiple
Number of Profiles=7
Profile Names=10-year,25-year,50-year,1pct_min,100-year,1pct_plu,500-year
River Rch & RM= UNT 039 in HW,Reach-1,7483
     634     898    1121     693    1383    2760    2114
Boundary for River Rch & Prof#=UNT 039 in HW,Reach-1,1
Up Type=0
Dn Type=3
Dn Slope=0.005
Boundary for River Rch & Prof#=UNT 039 in HW,Reach-1,2
Up Type=0
Dn Type=3
Dn Slope=0.005
Boundary for River Rch & Prof#=UNT 039 in HW,Reach-1,3
Up Type=0
Dn Type=3
Dn Slope=0.005
Boundary for River Rch & Prof#=UNT 039 in HW,Reach-1,4
Up Type=0
Dn Type=3
Dn Slope=0.005
Boundary for River Rch & Prof#=UNT 039 in HW,Reach-1,5
Up Type=0
Dn Type=3
Dn Slope=0.005
Boundary for River Rch & Prof#=UNT 039 in HW,Reach-1,6
Up Type=0
Dn Type=3
Dn Slope=0.005
Boundary for River Rch & Prof#=UNT 039 in HW,Reach-1,7
Up Type=0
Dn Type=3
Dn Slope=0.005

--- UNT 039 in HW.g01 (geometry) ---

Geom Title=Existing Conditions

River Reach=UNT 039 in HW,Reach-1
Reach XY= 30
      1991405.80     13637329.54      1991360.80     13637284.54
      1991210.80     13637324.54      1991024.13     13637208.43
      1990570.80     13637174.54      1990120.80     13636894.54
      1990060.80     13636884.54      1990010.80     13636964.54
      1989530.80     13636724.54      1989570.80     13636644.54
      1989350.80     13636414.54      1989339.23     13636297.49
      1989418.40     13636273.01      1989421.01     13636188.11
      1989532.98     13636094.88      1989459.55     13635970.40
      1989540.80     13635714.54      1989430.80     13635684.54
      1989080.80     13635334.54      1989150.80     13635174.54
      1989030.80     13635034.54      1989030.80     13634294.54
      1988880.80     13634034.54      1988920.80     13633784.54
      1988730.80     13633724.54      1988660.80     13633604.54
      1988760.80     13633274.54      1988580.80     13633324.54
      1988540.80     13633174.54      1988450.80     13633114.54

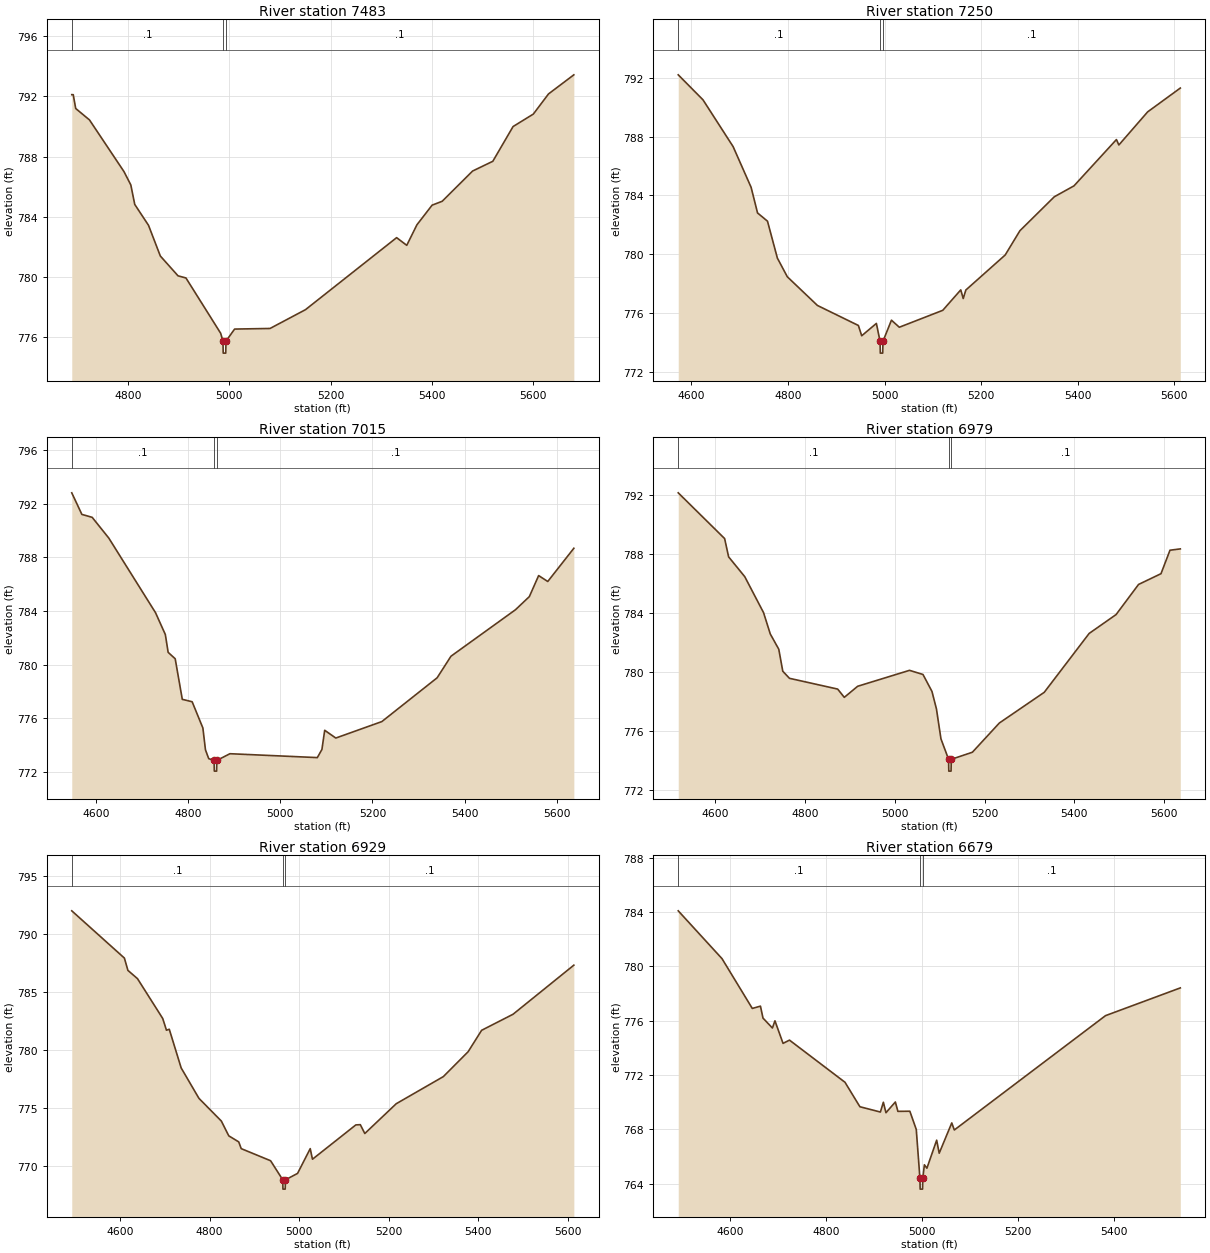
Type RM Length L Ch R = 1,7483,233,233,233
BEGIN DESCRIPTION:
UNT 039 in HW 9.0
END DESCRIPTION:
XS GIS Cut Line= 3
      1991525.01     13637024.99      1991375.00     13637275.00
      1991375.00     13637975.04
#Sta/Elev= 30
  4688.9  792.12  4691.8  792.12  4696.7  791.20  4723.9  790.44  4791.9  787.01
  4805.5  786.12  4813.3  784.82  4840.5  783.43  4863.8  781.39  4898.8  780.07
  4914.4  779.93  4983.0  776.25  4987.5  775.73  4988.0  774.93  4993.0  774.93
  4993.5  775.73  5010.5  776.53  5080.5  776.57  5150.5  777.82  5330.5  782.61
  5350.5  782.10  5370.5  783.46  5400.5  784.77  5420.5  785.03  5480.5  787.04
  5520.5  787.69  5560.5  790.00  5600.5  790.83  5630.5  792.17  5680.5  793.44
#Mann=3,-1,0
  4688.9     0.1       0  4987.5    0.07       0  4993.5     0.1       0
Bank Sta=4987.5,4993.5
Exp/Cntr=0.3,0.1

Type RM Length L Ch R = 1,7250,235,235,235
BEGIN DESCRIPTION:
UNT 039 in HW 8.0
END DESCRIPTION:
XS GIS Cut Line= 3
      1991275.00     13636875.02      1991135.72     13637467.71
      1991055.72     13637891.49
#Sta/Elev= 30
  4572.7  792.20  4624.0  790.50  4686.4  787.32  4723.7  784.55  4737.0  782.81
  4757.6  782.25  4778.1  779.74  4798.7  778.47  4861.1  776.52  4945.9  775.16
  4952.8  774.46  4983.2  775.30  4990.8  774.08  4991.3  773.28  4996.3  773.28
  4996.8  774.08  5014.4  775.52  5030.7  775.04  5120.7  776.19  5158.0  777.58
  5163.1  776.99  5168.5  777.57  5250.0  779.95  5280.5  781.60  5351.8  783.91
  5392.5  784.65  5480.5  787.80  5485.5  787.43  5545.1  789.68  5612.8  791.30
#Mann=3,-1,0
  4572.7     0.1       0  4990.8    0.07       0  4996.8     0.1       0
Bank Sta=4990.8,4996.8
Exp/Cntr=0.3,0.1

Type RM Length L Ch R = 1,7015,36,36,36
BEGIN DESCRIPTION:
Mapping XS f73811ec
END DESCRIPTION:
XS GIS Cut Line= 5
      1991235.52     13636856.31      1991089.71     13637095.85
      1990981.64     13637157.05      1990969.92     13637302.89
      1990958.24     13637841.62
#Sta/Elev= 30
  4547.3  792.82  4569.2  791.21  4591.6  790.99  4627.7  789.44  4729.1  783.87
  4750.4  782.24  4756.5  780.91  4771.8  780.43  4787.2  777.40  4808.6  777.22
  4831.9  775.26  4837.5  773.63  4844.6  772.97  4856.2  772.84  4856.7  772.04
  4861.7  772.04  4862.2  772.84  4890.6  773.34  5080.3  773.05  5090.3  773.66
  5096.3  775.09  5120.4  774.51  5220.4  775.74  5340.4  779.01  5370.4  780.62
  5510.4  784.09  5540.5  785.07  5560.7  786.64  5580.5  786.20  5637.1  788.68
#Mann=3,-1,0
  4547.3     0.1       0  4856.2    0.07       0  4862.2     0.1       0
Bank Sta=4856.2,4862.2
Exp/Cntr=0.3,0.1

Type RM Length L Ch R = 1,6979,50,50,50
BEGIN DESCRIPTION:
UNT 039 in HW 7.0
END DESCRIPTION:
XS GIS Cut Line= 4
      1991226.42     13636841.97      1991100.13     13637026.84
      1990941.28     13637137.52      1990938.67     13637838.02
#Sta/Elev= 30
  4517.8  792.15  4621.1  789.05  4630.0  787.81  4665.9  786.47  4707.8  784.03
  4722.7  782.59  4741.7  781.55  4750.6  780.06  4765.5  779.58  4872.8  778.85
  4887.6  778.29  4917.3  779.04  5032.8  780.12  5062.8  779.84  5082.8  778.69
  5092.8  777.50  5102.8  775.48  5119.8  774.09  5120.3  773.29  5125.3  773.29
  5125.8  774.09  5172.8  774.57  5232.8  776.55  5332.8  778.63  5432.8  782.62
  5492.8  783.90  5542.8  785.94  5592.8  786.67  5612.8  788.26  5635.8  788.35
#Mann=3,-1,0
  4517.8     0.1       0  5119.8    0.07       0  5125.8     0.1       0
Bank Sta=5119.8,5125.8
Exp/Cntr=0.3,0.1

Type RM Length L Ch R = 1,6929,250,250,250
BEGIN DESCRIPTION:
Mapping XS 72169d69
END DESCRIPTION:
XS GIS Cut Line= 5
      1991198.65     13636834.03      1991053.26     13637031.51
      1990897.01     13637111.81      1990879.64     13637396.09
      1990914.34     13637810.32
#Sta/Elev= 30
  4492.2  791.97  4609.7  787.91  4617.6  786.85  4639.0  786.14  4695.3  782.72
  4703.7  781.71  4710.0  781.79  4736.5  778.47  4776.3  775.85  4826.3  773.90
  4842.9  772.63  4865.1  772.11  4870.7  771.53  4936.3  770.49  4963.4  768.85
  4963.9  768.05  4968.9  768.05  4969.4  768.85  4996.5  769.40  5024.8  771.53
  5029.8  770.62  5126.7  773.57  5136.7  773.59  5146.7  772.83  5216.9  775.39
  5322.1  777.72  5377.5  779.86  5407.6  781.70  5477.8  783.08  5613.6  787.30
#Mann=3,-1,0
  4492.2     0.1       0  4963.4    0.07       0  4969.4     0.1       0
Bank Sta=4963.4,4969.4
Exp/Cntr=0.3,0.1

Type RM Length L Ch R = 1,6679,314,314,314
BEGIN DESCRIPTION:
UNT 039 in HW 6.0
END DESCRIPTION:
XS GIS Cut Line= 3
      1990860.55     13636680.47      1990675.00     13637175.00
      1990509.91     13637666.42
#Sta/Elev= 30
  4492.2  784.08  4583.5  780.56  4646.6  776.90  4663.6  777.07  4668.9  776.19
  4688.5  775.46  4693.8  775.99  4710.7  774.33  4724.1  774.57  4839.8  771.47
  4870.9  769.67  4913.6  769.28  4919.8  770.00  4925.2  769.23  4944.8  770.02
  4950.1  769.33  4975.0  769.34  4988.4  768.00  4996.0  764.41  4996.5  763.61
  5001.5  763.61  5002.0  764.41  5005.3  765.40  5010.6  765.15  5030.9  767.21
  5036.2  766.25  5062.4  768.48  5067.7  767.96  5382.9  776.37  5538.8  778.41
#Mann=3,-1,0
  4492.2     0.1       0  4996.0    0.07       0  5002.0     0.1       0
Bank Sta=4996,5002
Exp/Cntr=0.3,0.1

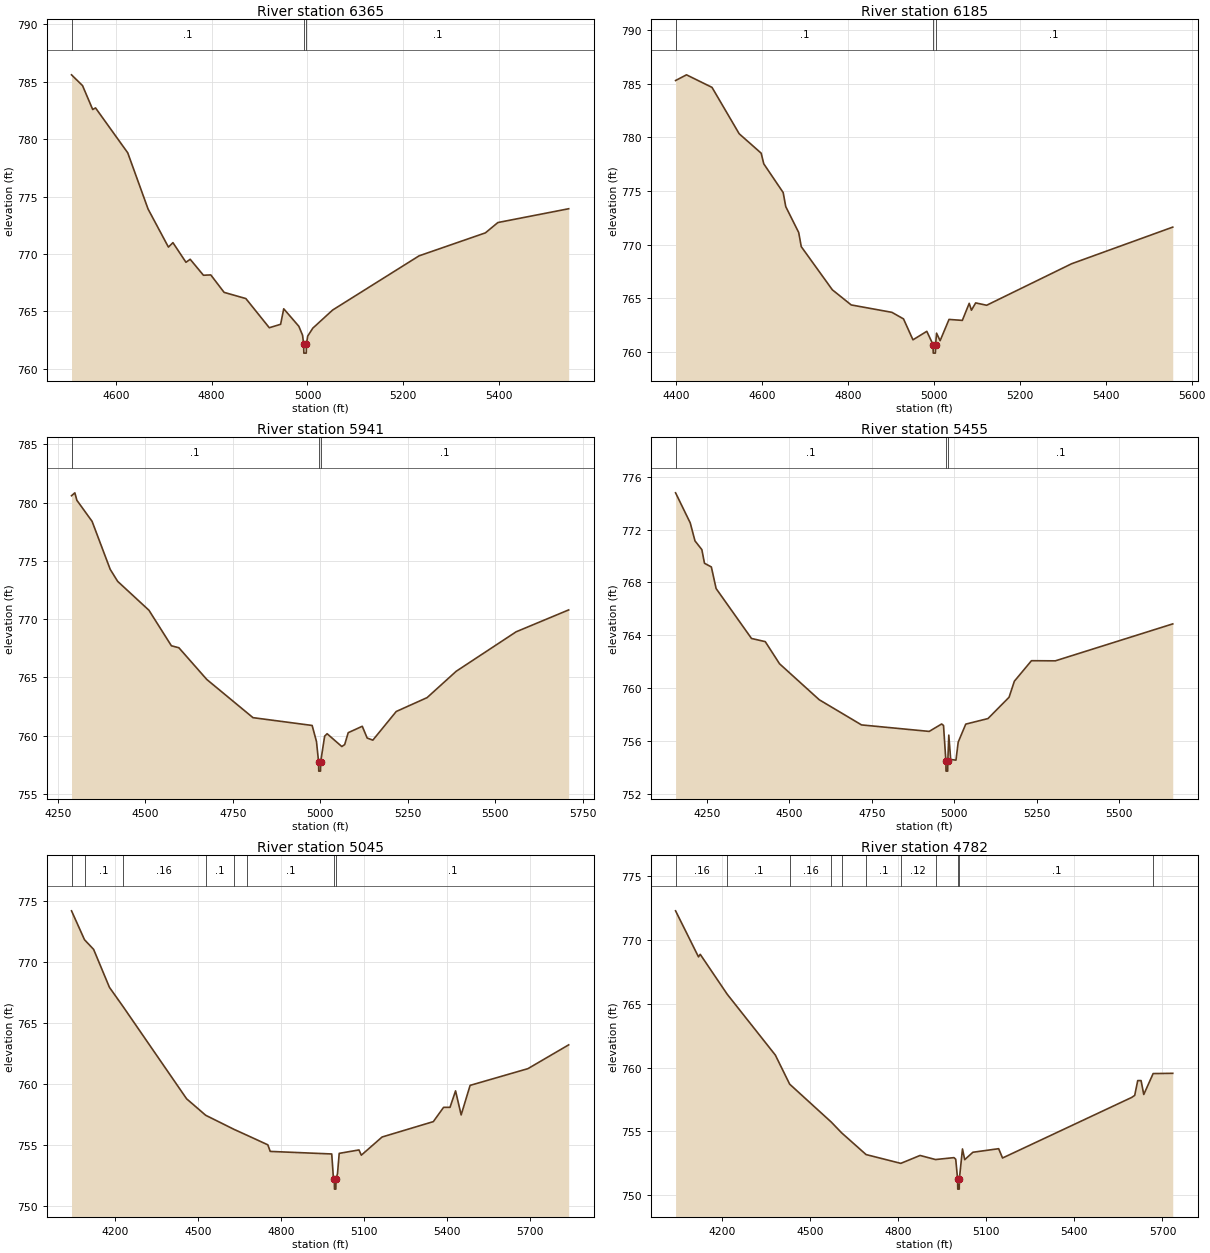
Type RM Length L Ch R = 1,6365,180,180,180
BEGIN DESCRIPTION:
UNT 039 in HW 5.0
END DESCRIPTION:
XS GIS Cut Line= 3
      1990674.98     13636675.03      1990425.00     13637075.00
      1990242.66     13637610.55
#Sta/Elev= 30
  4507.7  785.60  4530.7  784.66  4551.9  782.58  4557.8  782.72  4625.0  778.81
  4667.4  773.92  4709.9  770.60  4719.3  770.99  4746.5  769.28  4755.3  769.54
  4783.0  768.15  4798.3  768.18  4826.1  766.66  4871.5  766.12  4920.4  763.58
  4944.0  763.88  4950.5  765.23  4982.0  763.71  4989.8  762.93  4992.0  762.17
  4992.5  761.37  4997.5  761.37  4998.0  762.17  5000.5  762.85  5011.1  763.54
  5052.5  765.12  5232.9  769.84  5371.3  771.84  5397.4  772.74  5545.1  773.94
#Mann=3,-1,0
  4507.7     0.1       0  4992.0    0.07       0  4998.0     0.1       0
Bank Sta=4992,4998
Exp/Cntr=0.3,0.1

Type RM Length L Ch R = 1,6185,244,244,244
BEGIN DESCRIPTION:
UNT 039 in HW 4.0
END DESCRIPTION:
XS GIS Cut Line= 3
      1990589.73     13636513.81      1990280.69     13636982.57
      1990131.38     13637558.98
#Sta/Elev= 30
  4399.1  785.28  4424.5  785.81  4483.9  784.64  4547.1  780.32  4598.3  778.51
  4604.3  777.52  4649.5  774.84  4655.5  773.53  4685.6  771.12  4691.6  769.80
  4763.9  765.78  4807.8  764.37  4902.5  763.68  4929.5  763.07  4951.5  761.12
  4983.7  761.91  4998.2  760.68  4998.7  759.88  5003.7  759.88  5004.2  760.68
  5006.4  761.74  5014.7  761.04  5035.4  763.02  5066.4  762.93  5082.4  764.52
  5087.6  763.88  5097.4  764.56  5123.0  764.34  5320.8  768.21  5556.0  771.62
#Mann=3,-1,0
  4399.1     0.1       0  4998.2    0.07       0  5004.2     0.1       0
Bank Sta=4998.2,5004.2
Exp/Cntr=0.3,0.1

Type RM Length L Ch R = 1,5941,486,486,486
BEGIN DESCRIPTION:
UNT 039 in HW 3.0
END DESCRIPTION:
XS GIS Cut Line= 3
      1990466.53     13636284.60      1990068.10     13636948.65
      1989992.69     13637590.93
#Sta/Elev= 30
  4288.7  780.60  4298.2  780.85  4304.0  780.21  4347.5  778.40  4399.3  774.28
  4420.6  773.25  4510.0  770.77  4574.2  767.72  4595.6  767.55  4675.3  764.83
  4807.4  761.55  4976.5  760.88  4988.9  759.50  4994.9  757.76  4995.4  756.96
  5000.4  756.96  5000.9  757.76  5012.2  759.96  5019.3  760.17  5061.3  759.07
  5069.5  759.24  5079.6  760.26  5119.8  760.81  5133.8  759.80  5150.0  759.62
  5216.9  762.08  5305.1  763.27  5388.2  765.53  5559.6  768.92  5709.8  770.80
#Mann=3,-1,0
  4288.7     0.1       0  4994.9    0.07       0  5000.9     0.1       0
Bank Sta=4994.9,5000.9
Exp/Cntr=0.3,0.1

Type RM Length L Ch R = 1,5455,410,410,410
BEGIN DESCRIPTION:
UNT 039 in HW 2.0
END DESCRIPTION:
XS GIS Cut Line= 4
      1990364.94     13636232.53      1989909.25     13636597.08
      1989700.91     13636969.48      1989573.32     13637448.60
#Sta/Elev= 30
  4155.8  774.77  4200.2  772.50  4214.6  771.14  4235.4  770.48  4243.4  769.45
  4264.2  769.17  4278.6  767.54  4385.8  763.77  4427.5  763.53  4470.7  761.86
  4591.1  759.14  4719.2  757.24  4924.1  756.75  4961.8  757.31  4967.5  757.20
  4974.6  754.55  4975.1  753.75  4980.1  753.75  4980.6  754.55  4983.5  756.47
  4989.2  754.63  5005.2  754.58  5012.0  755.94  5034.9  757.30  5102.2  757.72
  5166.1  759.33  5182.1  760.54  5233.9  762.09  5306.3  762.08  5661.9  764.87
#Mann=3,-1,0
  4155.8     0.1       0  4974.6    0.07       0  4980.6     0.1       0
Bank Sta=4974.6,4980.6
Exp/Cntr=0.3,0.1

Type RM Length L Ch R = 1,5045,263,263,263
BEGIN DESCRIPTION:
Mapping XS ff8e28b7
END DESCRIPTION:
XS GIS Cut Line= 3
      1990339.99     13636079.10      1989424.22     13636734.45
      1989350.60     13637401.39
#Sta/Elev= 30
  4043.4  774.21  4090.4  771.84  4123.3  771.05  4180.5  767.94  4228.7  766.40
  4459.4  758.81  4528.4  757.46  4630.5  756.31  4679.0  755.81  4753.0  755.04
  4761.6  754.50  4984.0  754.29  4990.1  752.30  4993.4  752.21  4993.9  751.41
  4998.9  751.41  4999.4  752.21  5004.9  752.69  5011.0  754.34  5082.5  754.62
  5090.9  754.19  5166.0  755.68  5351.2  756.94  5388.3  758.11  5411.5  758.11
  5431.6  759.46  5451.8  757.49  5484.2  759.91  5693.2  761.28  5840.5  763.23
#Mann=8,-1,0
  4043.4    0.16       0  4090.4     0.1       0  4228.7    0.16       0
  4528.4     0.1       0  4630.5    0.16       0  4679.0     0.1       0
  4993.4    0.07       0  4999.4     0.1       0
Bank Sta=4993.4,4999.4
Exp/Cntr=0.3,0.1

Type RM Length L Ch R = 1,4782,609,609,609
BEGIN DESCRIPTION:
Mapping XS 5e57cf63
END DESCRIPTION:
XS GIS Cut Line= 3
      1990244.53     13635957.54      1989298.35     13636547.82
      1989164.05     13637111.02
#Sta/Elev= 30
  4040.9  772.30  4119.0  768.69  4124.9  768.89  4216.9  765.76  4380.9  760.99
  4429.7  758.71  4571.8  755.73  4606.9  754.89  4690.1  753.19  4808.4  752.50
  4874.1  753.12  4926.7  752.80  4989.7  752.95  4995.6  752.82  5002.0  751.28
  5002.5  750.48  5007.5  750.48  5008.0  751.28  5018.6  753.63  5026.2  752.79
  5054.0  753.37  5141.9  753.65  5155.1  752.92  5595.3  757.67  5605.5  757.83
  5615.8  758.99  5627.2  758.99  5636.4  757.90  5668.3  759.54  5735.1  759.56
#Mann=11,-1,0
  4040.9    0.16       0  4216.9     0.1       0  4429.7    0.16       0
  4571.8     0.1       0  4606.9    0.16       0  4690.1     0.1       0
  4808.4    0.12       0  4926.7     0.1       0  5002.0    0.07       0
  5008.0     0.1       0  5668.3    0.05       0
Bank Sta=5002,5008
Exp/Cntr=0.3,0.1

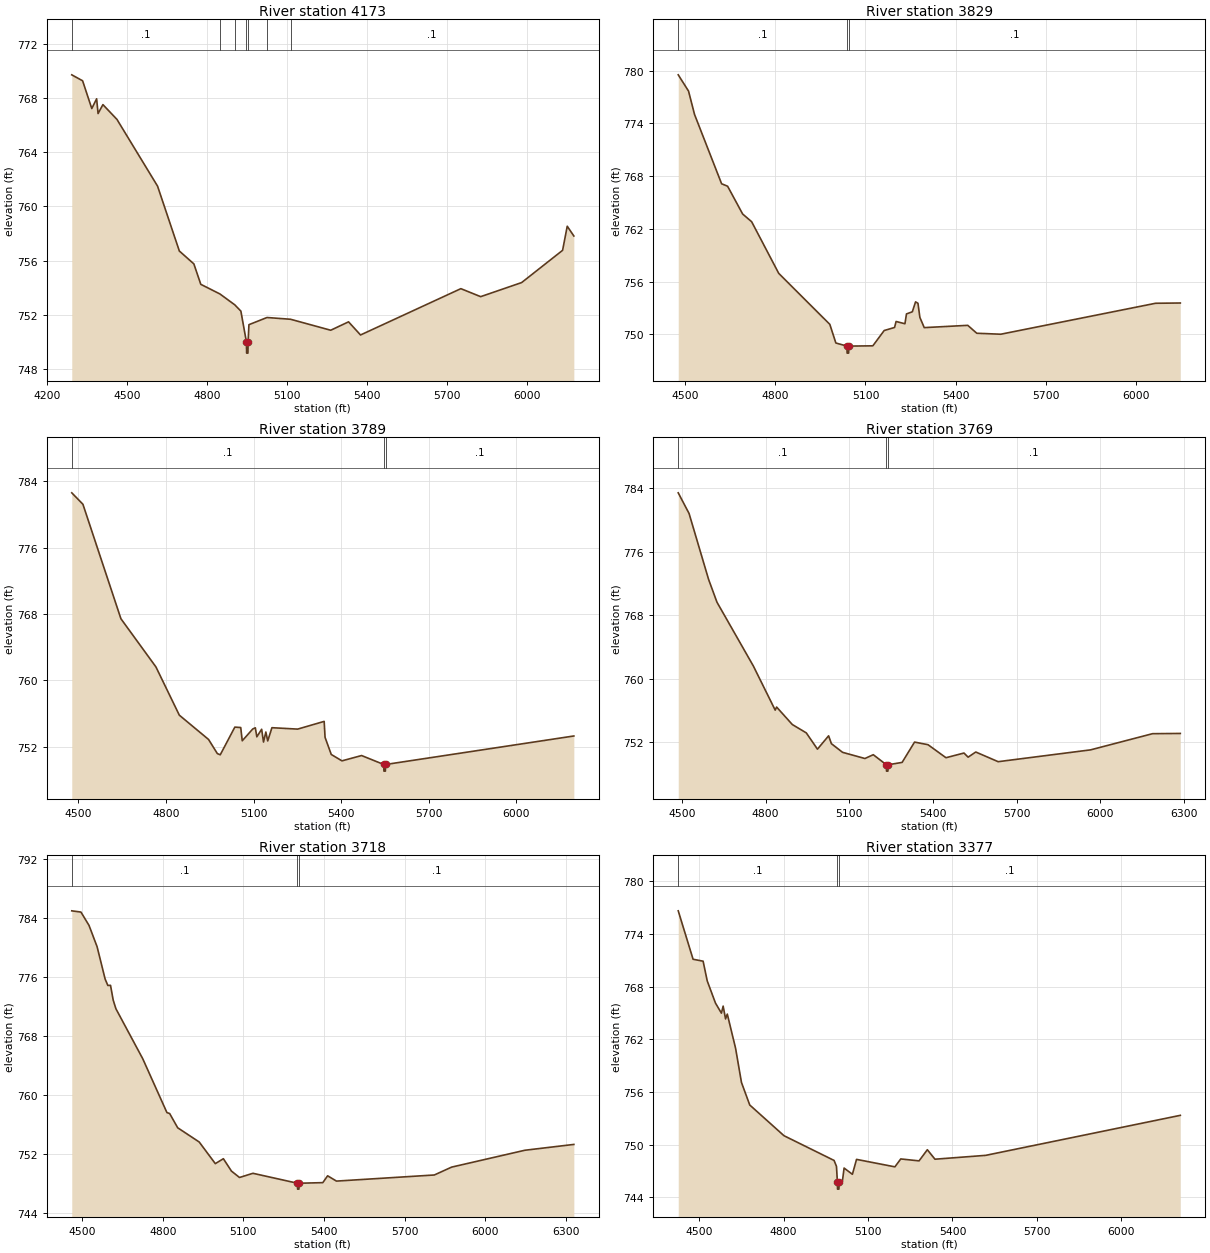
Type RM Length L Ch R = 1,4173,344,344,344
BEGIN DESCRIPTION:
Mapping XS 260122a7
END DESCRIPTION:
XS GIS Cut Line= 4
      1990192.92     13635922.14      1989771.01     13636101.84
      1989257.99     13636148.72      1989018.40     13637028.95
#Sta/Elev= 30
  4291.2  769.72  4331.9  769.28  4366.4  767.23  4384.6  767.95  4390.0  766.86
  4408.2  767.52  4460.9  766.43  4613.5  761.50  4695.3  756.71  4749.8  755.76
  4775.9  754.25  4847.7  753.54  4903.3  752.74  4926.5  752.27  4947.5  749.97
  4948.0  749.17  4953.0  749.17  4953.5  749.97  4956.7  751.27  5024.6  751.80
  5113.2  751.67  5263.9  750.86  5330.9  751.48  5375.9  750.51  5752.8  753.93
  5827.2  753.34  5981.1  754.38  6134.9  756.76  6152.4  758.54  6177.2  757.82
#Mann=7,-1,0
  4291.2     0.1       0  4847.7    0.16       0  4903.3     0.1       0
  4947.5    0.07       0  4953.5     0.1       0  5024.6    0.07       0
  5113.2     0.1       0
Bank Sta=4947.5,4953.5
Exp/Cntr=0.3,0.1

Type RM Length L Ch R = 1,3829,40,40,40
BEGIN DESCRIPTION:
Mapping XS 8f91b62c
END DESCRIPTION:
XS GIS Cut Line= 6
      1990039.28     13635798.24      1989469.79     13635822.55
      1989396.88     13635871.16      1989365.48     13635986.13
      1989327.43     13636034.35      1988618.42     13636472.10
#Sta/Elev= 30
  4476.7  779.51  4511.0  777.66  4531.0  775.00  4621.1  767.12  4641.1  766.84
  4691.2  763.68  4721.2  762.80  4811.3  756.93  4981.4  751.13  5001.5  749.01
  5038.5  748.66  5039.0  747.86  5044.0  747.86  5044.5  748.66  5124.6  748.69
  5162.3  750.43  5196.9  750.78  5202.0  751.46  5231.4  751.20  5236.6  752.32
  5256.0  752.56  5266.8  753.69  5274.8  753.53  5281.2  751.92  5295.7  750.76
  5440.6  751.02  5470.6  750.12  5550.5  750.01  6066.1  753.53  6148.2  753.56
#Mann=3,-1,0
  4476.7     0.1       0  5038.5    0.07       0  5044.5     0.1       0
Bank Sta=5038.5,5044.5
Exp/Cntr=0.3,0.1

Type RM Length L Ch R = 1,3789,20,20,20
BEGIN DESCRIPTION:
Mapping XS 2ddcf1ac
END DESCRIPTION:
XS GIS Cut Line= 6
      1990053.14     13635765.25      1989488.89     13635786.09
      1989414.24     13635801.71      1989330.90     13635883.31
      1989323.96     13635989.21      1988598.54     13636441.87
#Sta/Elev= 30
  4477.3  782.61  4515.5  781.23  4645.6  767.42  4765.6  761.60  4845.7  755.78
  4945.8  752.85  4975.8  751.15  4985.8  751.00  5035.8  754.34  5056.0  754.29
  5061.1  752.69  5097.0  754.11  5106.0  754.26  5111.1  753.17  5127.6  754.08
  5134.0  752.54  5142.0  753.75  5148.4  752.67  5162.8  754.27  5250.9  754.10
  5341.7  755.03  5344.8  753.10  5366.0  751.04  5402.6  750.27  5469.9  750.91
  5545.9  749.83  5546.4  749.03  5551.4  749.03  5551.9  749.83  6196.8  753.27
#Mann=3,-1,0
  4477.3     0.1       0  5545.9    0.07       0  5551.9     0.1       0
Bank Sta=5545.9,5551.9
Exp/Cntr=0.3,0.1

Type RM Length L Ch R = 1,3769,51,51,51
BEGIN DESCRIPTION:
Mapping XS ddb6a6b8
END DESCRIPTION:
XS GIS Cut Line= 5
      1990043.87     13635749.41      1989245.05     13635773.50
      1989216.41     13635858.14      1989242.45     13635988.35
      1988599.24     13636427.07
#Sta/Elev= 30
  4486.7  783.44  4525.6  780.83  4595.6  772.52  4625.6  769.65  4755.7  761.63
  4834.3  756.05  4839.3  756.44  4895.8  754.23  4945.8  753.18  4985.8  751.13
  5025.8  752.81  5035.8  751.82  5075.8  750.73  5155.9  749.95  5185.9  750.43
  5232.9  749.16  5233.4  748.36  5238.4  748.36  5238.9  749.16  5289.3  749.46
  5333.9  752.02  5382.2  751.69  5446.5  750.05  5511.0  750.64  5525.9  750.12
  5553.3  750.77  5633.6  749.55  5964.9  751.04  6187.1  753.08  6286.6  753.11
#Mann=3,-1,0
  4486.7     0.1       0  5232.9    0.07       0  5238.9     0.1       0
Bank Sta=5232.9,5238.9
Exp/Cntr=0.3,0.1

Type RM Length L Ch R = 1,3718,341,341,341
BEGIN DESCRIPTION:
Mapping XS 755eb57e
END DESCRIPTION:
XS GIS Cut Line= 3
      1990079.18     13635712.30      1989124.31     13635720.98
      1988573.88     13636450.02
#Sta/Elev= 30
  4461.6  784.99  4495.8  784.82  4525.8  783.01  4555.8  780.12  4585.8  775.72
  4595.8  774.86  4605.8  774.87  4615.8  772.87  4625.8  771.70  4725.8  764.90
  4815.8  757.59  4825.8  757.47  4855.8  755.53  4935.8  753.60  4995.8  750.66
  5025.8  751.33  5055.8  749.65  5085.8  748.78  5135.8  749.35  5301.5  748.00
  5302.0  747.20  5307.0  747.20  5307.5  748.00  5395.8  748.08  5413.7  749.01
  5446.6  748.29  5810.8  749.12  5875.3  750.19  6148.0  752.48  6330.0  753.27
#Mann=3,-1,0
  4461.6     0.1       0  5301.5    0.07       0  5307.5     0.1       0
Bank Sta=5301.5,5307.5
Exp/Cntr=0.3,0.1

Type RM Length L Ch R = 1,3377,274,274,274
BEGIN DESCRIPTION:
Mapping XS d0a437d7
END DESCRIPTION:
XS GIS Cut Line= 3
      1989762.32     13635208.84      1988933.32     13635806.87
      1988549.76     13636463.56
#Sta/Elev= 30
  4426.2  776.64  4478.9  771.12  4514.5  770.90  4529.2  768.65  4558.5  766.12
  4579.5  764.98  4585.7  765.78  4594.2  764.32  4600.4  764.87  4629.8  760.98
  4650.7  757.08  4680.1  754.51  4801.6  751.01  4979.5  748.19  4988.1  747.51
  4991.3  745.72  4991.8  744.92  4996.8  744.92  4997.3  745.72  5009.0  745.80
  5015.1  747.32  5044.6  746.61  5059.3  748.31  5195.5  747.46  5216.3  748.36
  5281.3  748.14  5310.7  749.41  5337.8  748.33  5518.0  748.77  6208.9  753.33
#Mann=3,-1,0
  4426.2     0.1       0  4991.3    0.07       0  4997.3     0.1       0
Bank Sta=4991.3,4997.3
Exp/Cntr=0.3,0.1

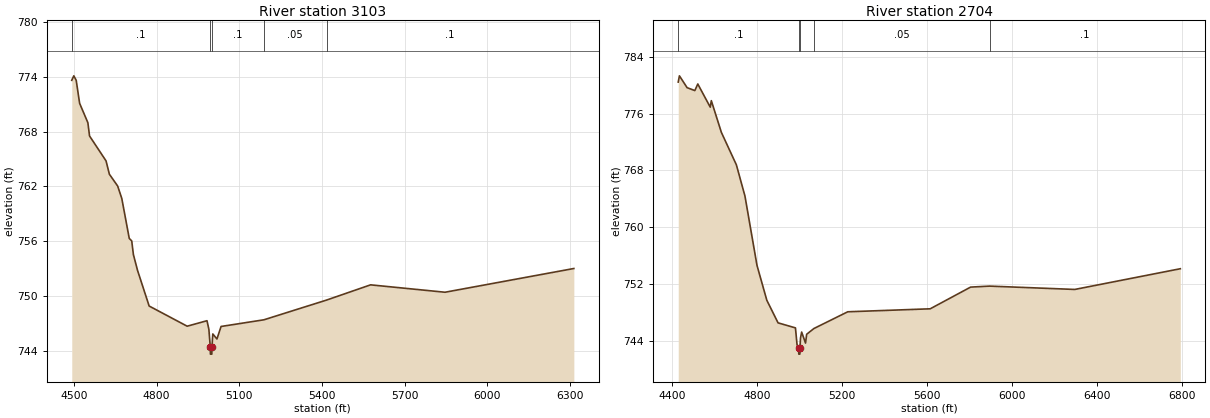
Type RM Length L Ch R = 1,3103,399,399,399
BEGIN DESCRIPTION:
Mapping XS 8aa0bd2b
END DESCRIPTION:
XS GIS Cut Line= 3
      1989558.34     13635087.30      1988672.91     13635680.37
      1988546.02     13636425.85
#Sta/Elev= 30
  4492.0  773.61  4499.4  774.10  4508.1  773.61  4520.5  771.09  4550.5  768.96
  4556.5  767.51  4616.4  764.78  4628.5  763.32  4658.5  762.03  4673.5  760.67
  4700.6  756.29  4709.6  756.01  4715.6  754.52  4730.6  752.79  4772.8  748.88
  4910.7  746.67  4982.7  747.27  4989.5  746.33  4994.7  744.41  4995.2  743.61
  5000.2  743.61  5000.7  744.41  5003.8  745.82  5018.8  745.27  5033.8  746.64
  5189.1  747.37  5416.4  749.53  5576.3  751.20  5846.4  750.39  6313.9  752.99
#Mann=5,-1,0
  4492.0     0.1       0  4994.7    0.07       0  5000.7     0.1       0
  5189.1    0.05       0  5416.4     0.1       0
Bank Sta=4994.7,5000.7
Exp/Cntr=0.3,0.1

Type RM Length L Ch R = 1,2704,0,0,0
BEGIN DESCRIPTION:
UNT 039 in HW 1.0
END DESCRIPTION:
XS GIS Cut Line= 4
      1989636.27     13635040.67      1989267.75     13634990.75
      1988573.74     13635283.72      1988518.32     13636521.48
#Sta/Elev= 30
  4429.1  780.46  4434.7  781.34  4470.8  779.67  4507.3  779.26  4521.2  780.19
  4579.9  776.92  4584.9  777.84  4632.2  773.37  4702.9  768.79  4743.2  764.40
  4799.9  754.62  4846.2  749.70  4899.1  746.51  4981.1  745.80  4988.5  743.43
  4996.3  742.90  4996.8  742.10  5001.8  742.10  5002.3  742.90  5004.8  744.35
  5010.2  745.21  5028.5  743.66  5033.9  744.90  5068.0  745.71  5227.3  748.07
  5615.6  748.49  5805.8  751.55  5895.3  751.69  6296.3  751.22  6793.3  754.14
#Mann=5,-1,0
  4429.1     0.1       0  4996.3    0.07       0  5002.3     0.1       0
  5068.0    0.05       0  5895.3     0.1       0
Bank Sta=4996.3,5002.3
Exp/Cntr=0.3,0.1

Chan Stop Cuts=-1