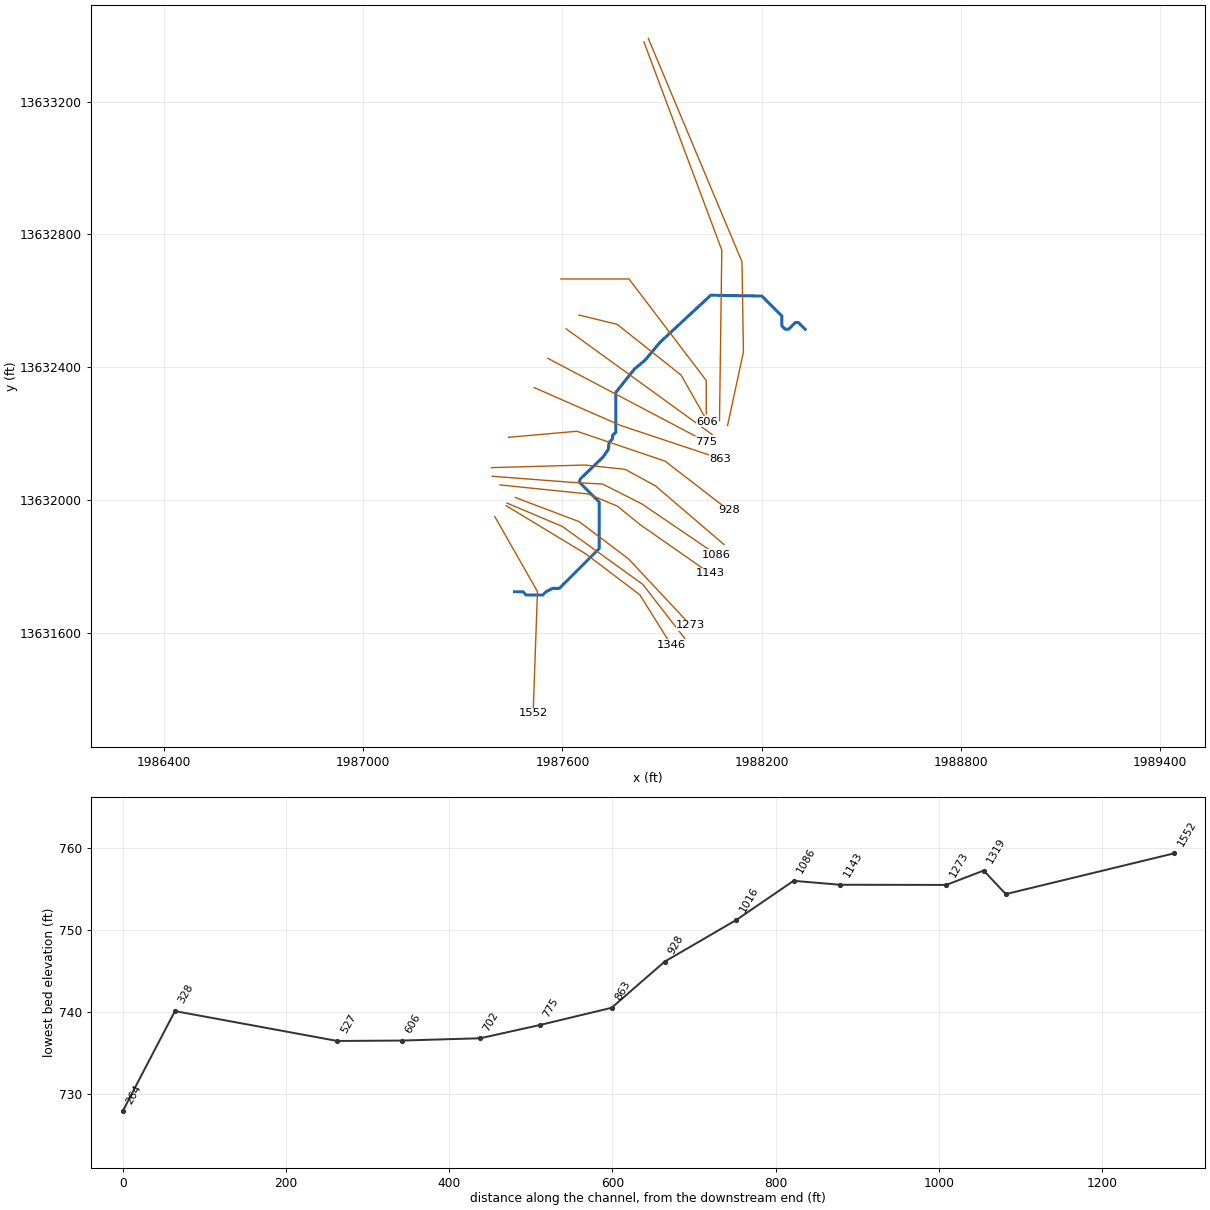
--- UNT 040 in HW.prj (project) ---

Proj Title=UNT 040 in HW Base Level Engineering
Current Plan=p01
Default Exp/Contr=0.3,0.1
English Units
Geom File=g01
Flow File=f01
Plan File=p01
Y Axis Title=Elevation
X Axis Title(PF)=Main Channel Distance
X Axis Title(XS)=Station
BEGIN DESCRIPTION:
UNT 040 in HW
END DESCRIPTION:
DSS Export Rating Curves= 0
DSS Export Rating Curve Sorted= 0
DSS Export Volume Flow Curves= 0
DXF OffsetX= 0
DXF OffsetY= 0
DXF ScaleX= 1
DXF ScaleY= 10

--- UNT 040 in HW.p01 (plan) ---

Plan Title=Multiple Run
Short Identifier=Multiple
Geom File=g01
Flow File=f01
Subcritical Flow
K Sum by GR= 0
Std Step Tol= 0.01
Critical Tol= 0.01
Num of Std Step Trials= 20
Max Error Tol= 0.3
Flow Tol Ratio= 0.001
Split Flow NTrial= 30
Split Flow Tol= 0.02
Split Flow Ratio= 0.02
Log Output Level= 0
Friction Slope Method= 1
Unsteady Friction Slope Method= 2
Unsteady Bridges Friction Slope Method= 1
Parabolic Critical Depth
Global Vel Dist=  1 , 1 , 1
Global Log Level= 0
CheckData=True
Encroach Param= -1, 0, 0, 0
BEGIN DESCRIPTION:
Multiple Run
END DESCRIPTION:

--- UNT 040 in HW.f01 (steady flow) ---

Flow Title=Multiple
Number of Profiles=7
Profile Names=10-year,25-year,50-year,1pct_min,100-year,1pct_plu,500-year
River Rch & RM= UNT 040 in HW,Reach-1,1552
     174     228     270     160     319     637     444
River Rch & RM= UNT 040 in HW,Reach-1,328
     337     465     570     347     693    1383    1028
Boundary for River Rch & Prof#=UNT 040 in HW,Reach-1,1
Up Type=0
Dn Type=3
Dn Slope=0.005
Boundary for River Rch & Prof#=UNT 040 in HW,Reach-1,2
Up Type=0
Dn Type=3
Dn Slope=0.005
Boundary for River Rch & Prof#=UNT 040 in HW,Reach-1,3
Up Type=0
Dn Type=3
Dn Slope=0.005
Boundary for River Rch & Prof#=UNT 040 in HW,Reach-1,4
Up Type=0
Dn Type=3
Dn Slope=0.005
Boundary for River Rch & Prof#=UNT 040 in HW,Reach-1,5
Up Type=0
Dn Type=3
Dn Slope=0.005
Boundary for River Rch & Prof#=UNT 040 in HW,Reach-1,6
Up Type=0
Dn Type=3
Dn Slope=0.005
Boundary for River Rch & Prof#=UNT 040 in HW,Reach-1,7
Up Type=0
Dn Type=3
Dn Slope=0.005

--- UNT 040 in HW.g01 (geometry) ---

Geom Title=Existing Conditions
Program Version=5.05

River Reach=UNT 040 in HW   ,Reach-1
Reach XY= 30
       1987455.8     13631724.54       1987480.8     13631724.54
       1987490.8     13631714.54       1987540.8     13631714.54
       1987550.8     13631724.54       1987570.8     13631734.54
       1987590.8     13631734.54       1987710.8     13631854.54
       1987710.8     13631994.54       1987650.8     13632054.54
      1987654.39     13632064.46      1987721.57     13632129.04
      1987738.24     13632152.48       1987740.8     13632174.54
       1987750.8     13632184.54       1987750.8     13632194.54
       1987760.8     13632204.54       1987760.8     13632324.54
       1987816.8     13632394.75      1987848.74     13632421.14
      1987893.88     13632475.31      1988046.66     13632616.98
       1988200.8     13632614.54       1988260.8     13632554.54
       1988260.8     13632524.54       1988270.8     13632514.54
       1988280.8     13632514.54       1988300.8     13632534.54
       1988310.8     13632534.54       1988330.8     13632514.54

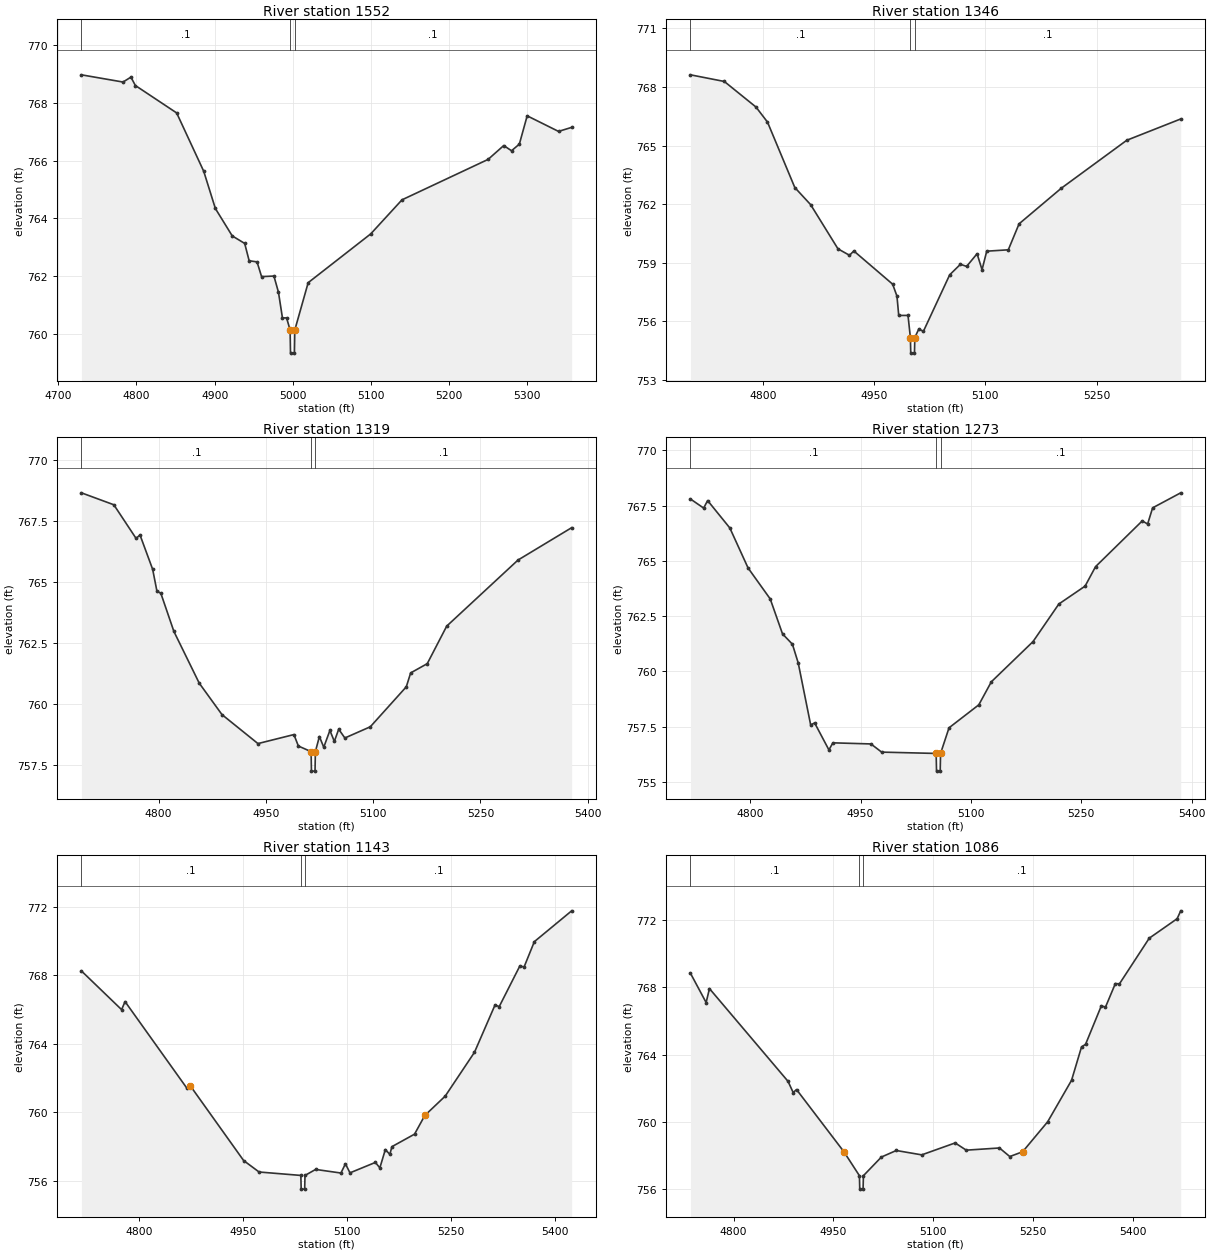
Type RM Length L Ch R = 1 ,1552    ,206,206,206
BEGIN DESCRIPTION:
UNT 040 in HW 5.0
END DESCRIPTION:
XS GIS Cut Line= 3
      1987396.36     13631950.87        1987525.       13631725.
      1987511.87     13631358.17
#Sta/Elev= 30
  4729.6  768.97  4782.8  768.72  4792.9  768.89  4798.6   768.6  4851.4  767.65
    4886  765.63  4900.9  764.34  4922.5  763.39  4938.4  763.13  4944.1  762.53
  4954.2  762.49    4960  761.98  4975.8     762  4981.6  761.44  4986.7  760.55
    4992  760.55  4996.5  760.13    4997  759.33    5002  759.33  5002.5  760.13
  5019.6  761.77  5099.6  763.46  5139.6  764.64  5249.7  766.04  5269.7  766.52
  5279.7  766.34  5289.7  766.57  5299.7  767.55  5339.8  767.01  5356.6  767.15
#Mann= 3 ,-1 , 0
  4729.6      .1       0  4996.5     .07       0  5002.5      .1       0
Bank Sta=4996.5,5002.5
XS Rating Curve= 0 ,0
Exp/Cntr=0.3,0.1

Type RM Length L Ch R = 1 ,1346    ,27,27,27
BEGIN DESCRIPTION:
Mapping XS 736dc455
END DESCRIPTION:
XS GIS Cut Line= 4
      1987430.67     13631983.42      1987671.53      13631837.6
      1987832.99      13631715.2      1987926.72     13631565.49
#Sta/Elev= 30
  4702.5  768.62  4748.1  768.28  4790.8  766.97  4806.3   766.2  4843.1  762.85
  4864.5  761.97  4901.3  759.71  4916.8  759.38  4922.7   759.6    4975   757.9
  4980.8  757.29  4983.2   756.3  4995.7   756.3  4998.9  755.17  4999.4  754.37
  5004.4  754.37  5004.9  755.17  5010.2   755.6  5016.5  755.49  5051.9  758.38
  5066.4  758.92  5074.7  758.81  5088.8  759.46  5095.5  758.64  5101.8  759.59
  5130.9  759.66  5145.4  760.99  5202.2  762.81  5290.6  765.27  5363.3  766.36
#Mann= 3 ,-1 , 0
  4702.5      .1       0  4998.9     .07       0  5004.9      .1       0
Bank Sta=4998.9,5004.9
XS Rating Curve= 0 ,0
Exp/Cntr=0.3,0.1

Type RM Length L Ch R = 1 ,1319    ,46,46,46
BEGIN DESCRIPTION:
Mapping XS b325cd2f
END DESCRIPTION:
XS GIS Cut Line= 4
      1987433.24     13631991.25      1987599.91     13631920.93
       1987842.1     13631746.45       1987968.4      13631583.7
#Sta/Elev= 30
  4692.1  768.66  4737.4  768.17  4768.5  766.79    4774  766.93  4791.7  765.52
  4797.7  764.62  4803.1  764.54  4821.4  762.97  4856.8  760.85  4888.6  759.56
  4938.9  758.37  4989.2  758.74  4995.4  758.27  5013.2  758.04  5013.7  757.24
  5018.7  757.24  5019.2  758.04  5024.8  758.66  5030.9  758.22  5039.5  758.91
  5045.7  758.46  5051.8  758.96  5060.4   758.6    5096  759.06  5146.3   760.7
  5152.4  761.27  5175.6  761.65  5202.8  763.19  5302.4   765.9  5377.5  767.23
#Mann= 3 ,-1 , 0
  4692.1      .1       0  5013.2     .07       0  5019.2      .1       0
Bank Sta=5013.2,5019.2
XS Rating Curve= 0 ,0
Exp/Cntr=0.3,0.1

Type RM Length L Ch R = 1 ,1273    ,130,130,130
BEGIN DESCRIPTION:
Mapping XS 19888763
END DESCRIPTION:
XS GIS Cut Line= 4
      1987458.01     13632008.16      1987650.69     13631935.26
      1987799.13     13631823.28      1987986.65     13631622.74
#Sta/Elev= 30
  4718.7   767.8  4736.6  767.39    4742  767.73  4772.2  766.49    4797  764.68
  4827.1  763.28  4843.8   761.7  4857.3  761.23  4865.2  760.38  4882.1  757.58
  4887.5  757.67  4906.9  756.45  4912.3  756.77    4964  756.72  4978.6  756.35
  5052.7  756.29  5053.2  755.49  5058.2  755.49  5058.7  756.29  5070.2  757.45
  5110.7  758.49  5127.7  759.53  5184.4  761.35  5219.5  763.05  5255.2  763.86
  5269.4  764.74  5332.9  766.81  5340.2  766.67    5347   767.4  5385.2  768.08
#Mann= 3 ,-1 , 0
  4718.7      .1       0  5052.7     .07       0  5058.7      .1       0
Bank Sta=5052.7,5058.7
XS Rating Curve= 0 ,0
Exp/Cntr=0.3,0.1

Type RM Length L Ch R = 1 ,1143    ,57,57,57
BEGIN DESCRIPTION:
Mapping XS 273f3c79
END DESCRIPTION:
XS GIS Cut Line= 5
      1987412.45     13632045.93      1987678.04     13632018.59
      1987765.28     13631982.13      1987834.29     13631926.14
       1988044.5     13631779.52
#Sta/Elev= 30
  4716.8  768.25  4774.7  765.99  4779.7  766.46  4868.7  761.41  4873.8  761.54
  4950.6  757.18  4972.9  756.51  5033.1  756.31  5033.6  755.51  5038.6  755.51
  5039.1  756.31  5054.4  756.66  5090.9  756.45  5097.4  756.99  5103.9  756.46
  5140.6  757.07    5147  756.75  5154.9  757.82  5161.4  757.54  5164.4  757.99
    5197  758.72  5211.8  759.81  5241.2  760.94  5283.4   763.5    5313  766.26
  5319.1  766.17  5348.8  768.54  5354.9  768.48  5369.7  769.96  5423.5  771.76
#Mann= 3 ,-1 , 0
  4716.8      .1       0  5033.1     .07       0  5039.1      .1       0
Bank Sta=4873.8,5211.8
XS Rating Curve= 0 ,0
Exp/Cntr=0.3,0.1

Type RM Length L Ch R = 1 ,1086    ,70,70,70
BEGIN DESCRIPTION:
Mapping XS b4e7d7d3
END DESCRIPTION:
XS GIS Cut Line= 5
      1987388.96     13632071.98      1987627.26     13632053.75
      1987721.01     13632048.54       1987839.5     13631988.64
      1988063.44     13631836.31
#Sta/Elev= 30
  4735.2  768.84  4758.7   767.1  4763.7  767.93  4881.7  762.41  4889.5  761.74
  4894.5  761.92 4965.72758.2148    4989  756.79  4989.5  755.99  4994.5  755.99
    4995  756.79    5022   757.9  5044.4  758.29  5082.6  758.03  5132.8  758.74
  5149.5  758.31  5199.4  758.44  5214.9  757.93  5234.2758.2149  5271.8     760
  5307.7  762.47  5322.7  764.46  5328.7  764.61  5352.5  766.91  5358.6  766.82
  5373.5  768.23  5379.6  768.21  5424.4  770.93  5466.3  772.09  5471.7  772.56
#Mann= 3 ,-1 , 0
  4735.2      .1       0    4989     .07       0    4995      .1       0
Bank Sta=4965.72,5234.2
XS Rating Curve= 0 ,0
Exp/Cntr=0.3,0.1

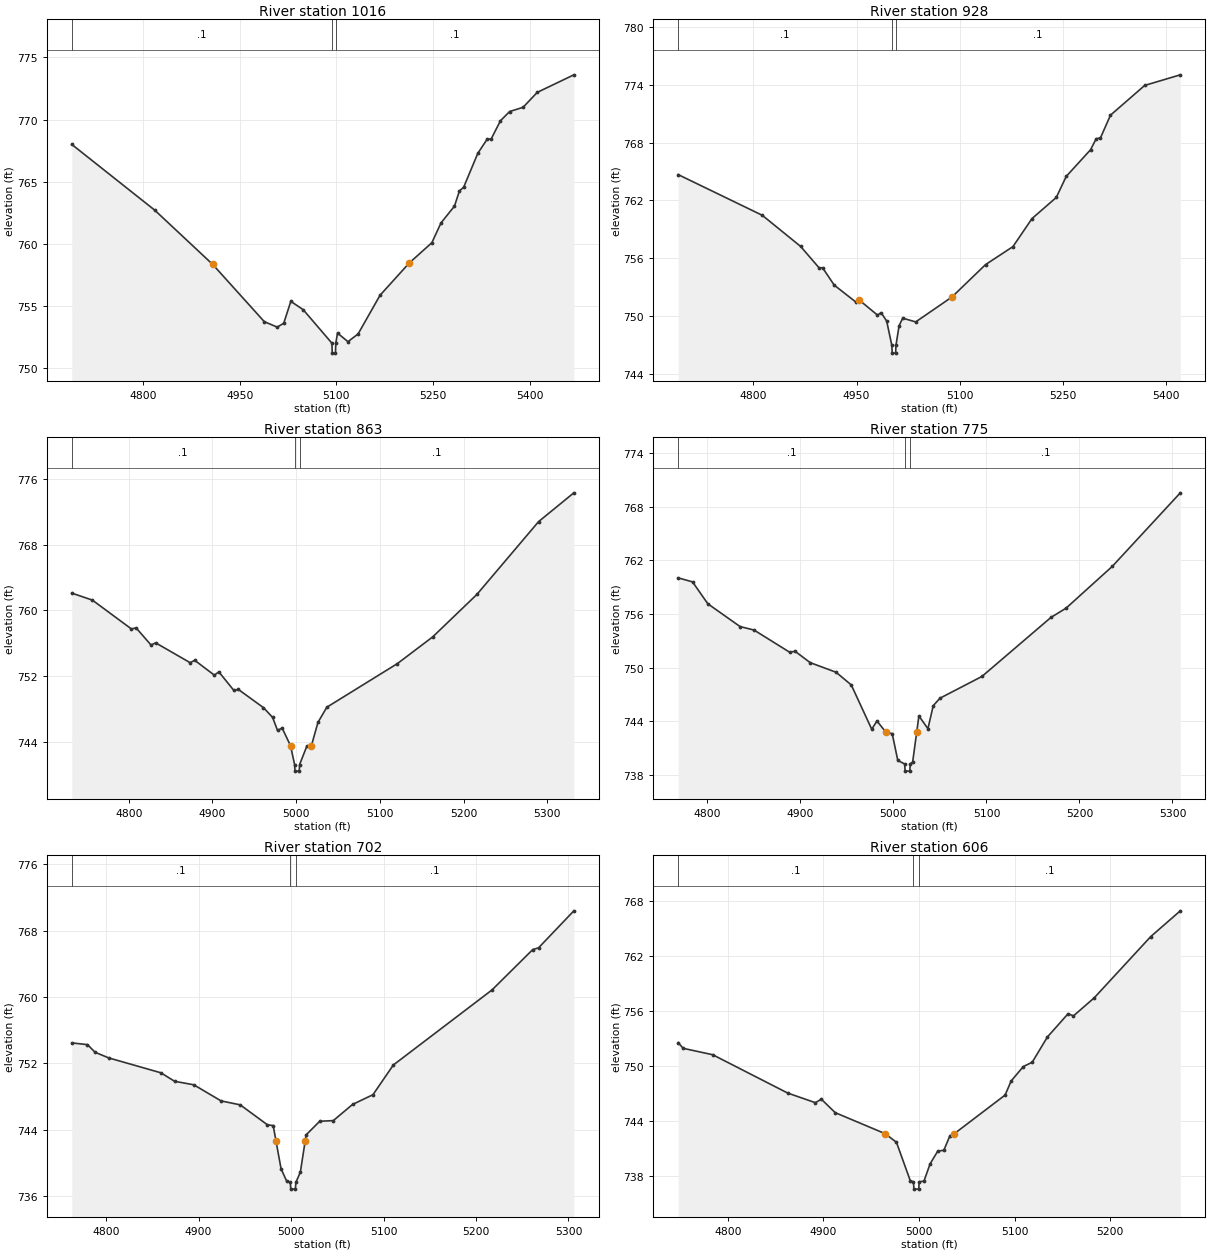
Type RM Length L Ch R = 1 ,1016    ,88,88,88
BEGIN DESCRIPTION:
Mapping XS 03533c85
END DESCRIPTION:
XS GIS Cut Line= 5
       1987386.4     13632098.02      1987667.62     13632105.83
      1987788.72     13632092.81      1987879.86     13632043.33
      1988086.92     13631866.23
#Sta/Elev= 30
  4689.4     768  4818.1  762.72  4908.1  758.36  4988.2  753.76  5008.3  753.32
  5018.4  753.63  5029.4  755.39  5048.6  754.72  5093.2  752.03  5093.7  751.23
  5098.7  751.23  5099.2  752.03  5101.9  752.84  5118.1  752.15  5133.8  752.77
  5167.9  755.88  5213.2  758.47  5248.3   760.1  5262.6   761.7  5283.4  763.04
  5291.1  764.26  5297.7  764.56  5319.6  767.28  5333.9   768.4  5340.5  768.45
  5354.8   769.9    5369  770.64  5389.9  770.98  5411.9  772.18  5468.7  773.59
#Mann= 3 ,-1 , 0
  4689.4      .1       0  5093.2     .07       0  5099.2      .1       0
Bank Sta=4908.1,5213.2
XS Rating Curve= 0 ,0
Exp/Cntr=0.3,0.1

Type RM Length L Ch R = 1 ,928     ,65,65,65
BEGIN DESCRIPTION:
Mapping XS ca1994fd
END DESCRIPTION:
XS GIS Cut Line= 4
      1987437.73     13632189.26      1987643.43     13632207.48
      1987909.05     13632117.64      1988101.73     13631968.93
#Sta/Elev= 30
  4690.7  764.67  4812.9  760.45  4868.7  757.22  4895.5     755  4900.7     755
  4917.6   753.2  4949.1  751.44  4954.3  751.63  4980.5  750.09  4985.8  750.34
  4993.9  749.47  5001.4  746.94  5001.9  746.14  5006.9  746.14  5007.4  746.94
  5011.9  748.97  5017.2  749.77  5036.1  749.38  5088.9  751.97  5137.7  755.33
  5177.6   757.2  5205.3  760.11  5240.6   762.3  5255.1  764.49  5290.4  767.25
  5298.6  768.39  5304.9  768.49  5319.4  770.84  5369.2  773.93    5421  775.03
#Mann= 3 ,-1 , 0
  4690.7      .1       0  5001.4     .07       0  5007.4      .1       0
Bank Sta=4954.3,5088.9
XS Rating Curve= 0 ,0
Exp/Cntr=0.3,0.1

Type RM Length L Ch R = 1 ,863     ,88,88,88
BEGIN DESCRIPTION:
UNT 040 in HW 2.0
END DESCRIPTION:
XS GIS Cut Line= 3
      1987515.27     13632338.91        1987775.       13632225.
      1988074.97     13632125.01
#Sta/Elev= 30
  4731.9  762.11  4756.5  761.26  4803.2  757.76  4808.7   757.9  4826.6  755.81
  4832.1  756.08  4873.3  753.67  4878.8  753.96  4902.2  752.16  4907.6  752.56
  4925.5  750.31    4931  750.42  4960.9  748.22  4971.8  747.04  4977.7  745.46
  4983.2  745.75 4993.24743.5986  4998.1  741.32  4998.6  740.52  5003.6  740.52
  5004.1  741.32  5012.8  743.57 5018.18 743.599    5026  746.43  5036.6  748.27
  5120.9  753.56  5163.1   756.8  5215.8  761.94  5289.6  770.78  5331.7  774.27
#Mann= 3 ,-1 , 0
  4731.9      .1       0  4998.1     .07       0  5004.1      .1       0
Bank Sta=4993.24,5018.18
XS Rating Curve= 0 ,0
Exp/Cntr=0.3,0.1

Type RM Length L Ch R = 1 ,775     ,73,73,73
BEGIN DESCRIPTION:
Mapping XS a60db6b2
END DESCRIPTION:
XS GIS Cut Line= 2
       1987556.2      13632427.1       1988033.6     13632175.38
#Sta/Elev= 30
  4768.7  760.05  4784.1   759.6  4800.5  757.15  4835.2   754.6  4850.2  754.21
  4888.6  751.72  4894.2  751.84  4910.6  750.56  4938.3  749.49  4954.7  748.07
  4976.7  743.11  4982.3  744.03 4992.02  742.77  4998.7  742.62  5004.7  739.62
  5012.1  739.22  5012.6  738.42  5017.6  738.42  5018.1  739.22  5020.7  739.45
 5025.02742.7706  5027.4   744.6  5037.1  743.17  5042.8  745.74    5050  746.58
  5095.2  749.02  5169.3  755.62  5185.6  756.66  5235.3  761.34  5308.4  769.57
#Mann= 3 ,-1 , 0
  4768.7      .1       0  5012.1     .07       0  5018.1      .1       0
Bank Sta=4992.02,5025.02
XS Rating Curve= 0 ,0
Exp/Cntr=0.3,0.1

Type RM Length L Ch R = 1 ,702     ,96,96,96
BEGIN DESCRIPTION:
Mapping XS 32ef6b6c
END DESCRIPTION:
XS GIS Cut Line= 2
      1987611.19     13632515.99      1988050.91     13632197.58
#Sta/Elev= 30
  4762.9  754.46  4779.9  754.25  4788.1  753.33  4802.8  752.65  4859.3  750.85
    4874  749.83  4894.9   749.4  4924.3  747.46  4945.1  746.98  4974.5  744.57
  4980.7  744.48 4983.67742.6597  4989.2  739.27  4995.4  737.74  4999.2  737.61
  4999.7  736.81  5004.7  736.81  5005.2  737.61  5010.1  738.87 5015.34742.6647
  5016.3  743.36    5031     745  5045.7  745.08  5066.5  747.03  5088.6  748.21
  5110.6  751.79  5217.3  760.85  5261.4  765.73  5267.6  765.93  5305.8   770.4
#Mann= 3 ,-1 , 0
  4762.9      .1       0  4999.2     .07       0  5005.2      .1       0
Bank Sta=4983.67,5015.34
XS Rating Curve= 0 ,0
Exp/Cntr=0.3,0.1

Type RM Length L Ch R = 1 ,606     ,79,79,79
BEGIN DESCRIPTION:
Mapping XS be93c880
END DESCRIPTION:
XS GIS Cut Line= 4
      1987649.97      13632557.3      1987764.52     13632529.53
      1987957.23     13632376.75      1988037.08     13632236.14
#Sta/Elev= 30
    4748  752.54  4753.2  751.92  4784.1  751.22  4862.6  747.03  4891.5  745.98
  4897.8  746.36  4912.3  744.89 4964.61742.5901  4976.4  741.65  4990.8  737.47
  4994.2  737.33  4994.7  736.53  4999.7  736.53  5000.2  737.33  5005.2  737.41
  5011.6  739.29  5019.6  740.68    5026  740.78  5032.4  742.37 5036.98742.5905
  5090.1  746.81  5096.5  748.36  5109.2  749.93  5118.5   750.4  5134.4  753.16
    5156   755.7  5161.7  755.47  5183.4  757.44  5242.5  764.13  5273.5  766.95
#Mann= 3 ,-1 , 0
    4748      .1       0  4994.2     .07       0  5000.2      .1       0
Bank Sta=4964.61,5036.98
XS Rating Curve= 0 ,0
Exp/Cntr=0.3,0.1

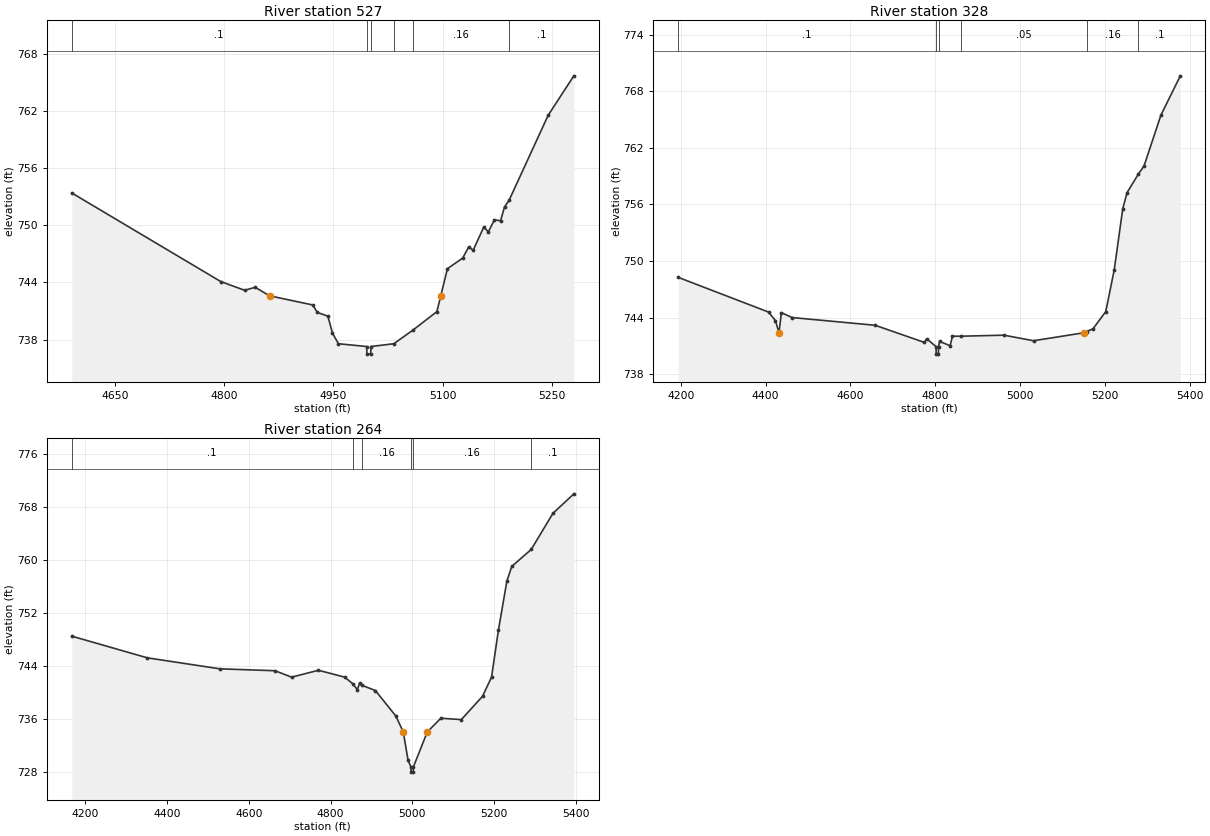
Type RM Length L Ch R = 1 ,527     ,199,199,199
BEGIN DESCRIPTION:
Mapping XS 2ede417c
END DESCRIPTION:
XS GIS Cut Line= 4
      1987595.51     13632665.94      1987800.41     13632665.94
      1988033.04     13632360.39      1988033.04     13632259.82
#Sta/Elev= 30
  4590.8  753.39  4795.5  744.09  4828.2  743.18  4842.7  743.49 4862.52742.5964
  4921.7  741.64    4928  740.86  4942.5  740.46  4948.8  738.69    4957  737.57
  4995.7  737.28  4996.2  736.48  5001.2  736.48  5001.7  737.28    5033  737.57
  5058.8  738.97  5092.2  740.94 5097.58742.5967  5106.7  745.45  5127.6  746.55
  5135.8  747.71  5142.1  747.39  5156.6  749.81  5162.9  749.31  5171.2  750.56
  5179.7  750.48  5185.1  751.93  5191.3  752.61  5245.1  761.55  5280.3  765.68
#Mann= 6 ,-1 , 0
  4590.8      .1       0  4995.7     .07       0  5001.7      .1       0
    5033     .05       0  5058.8     .16       0  5191.3      .1       0
Bank Sta=4862.52,5097.58
XS Rating Curve= 0 ,0
Exp/Cntr=0.3,0.1

Type RM Length L Ch R = 1 ,328     ,64,64,64
BEGIN DESCRIPTION:
Mapping XS 450211e9
END DESCRIPTION:
XS GIS Cut Line= 3
      1987845.55     13633379.46      1988079.92     13632752.75
      1988072.98      13632239.4
#Sta/Elev= 30
  4194.3  748.26    4407  744.58  4423.3  743.67 4431.54742.3819  4437.3  744.52
  4462.3     744  4658.1  743.18  4774.1  741.36  4779.5  741.75  4801.4  740.92
  4801.9  740.12  4806.9  740.12  4807.4  740.92  4809.7  741.47  4834.7  741.01
    4840  742.02    4860  742.02  4961.2  742.13  5031.2  741.54 5149.26742.3824
  5155.9  742.51  5171.2  742.81  5201.2  744.63  5221.2  749.06  5241.2  755.52
  5251.2  757.23  5278.3  759.24  5291.2  760.05  5331.2  765.47  5376.8  769.63
#Mann= 6 ,-1 , 0
  4194.3      .1       0  4801.4    .033       0  4807.4      .1       0
    4860     .05       0  5155.9     .16       0  5278.3      .1       0
Bank Sta=4431.54,5149.26
XS Rating Curve= 0 ,0
Exp/Cntr=0.3,0.1

Type RM Length L Ch R = 1 ,264     ,0,0,0
BEGIN DESCRIPTION:
UNT 040 in HW 1.0
END DESCRIPTION:
XS GIS Cut Line= 4
      1987858.55     13633390.36      1988140.68     13632717.59
      1988145.02     13632446.32      1988097.28     13632224.95
#Sta/Elev= 30
  4167.4  748.48  4352.1   745.2  4529.4  743.54  4664.5  743.25  4704.6  742.28
  4770.5  743.32  4834.7  742.28  4853.8  741.31  4865.5   740.4    4871  741.37
  4876.6  741.05  4909.5  740.26  4959.5  736.41 4977.77733.9926  4989.5   729.7
  4996.5  728.72    4997  727.92    5002  727.92  5002.5  728.72 5036.44733.9926
  5069.5  736.07  5119.6  735.86  5171.5  739.39  5193.6   742.3  5210.5  749.45
    5231   756.8  5242.9  759.02  5290.5  761.59  5343.5  767.04  5394.7     770
#Mann= 6 ,-1 , 0
  4167.4      .1       0  4853.8     .05       0  4876.6     .16       0
  4996.5     .07       0  5002.5     .16       0  5290.5      .1       0
Bank Sta=4977.77,5036.44
XS Rating Curve= 0 ,0
Exp/Cntr=0.3,0.1
LCMann Table=0

Chan Stop Cuts=-1
Use User Specified Reach Order=0
Composite Channel Slope=5