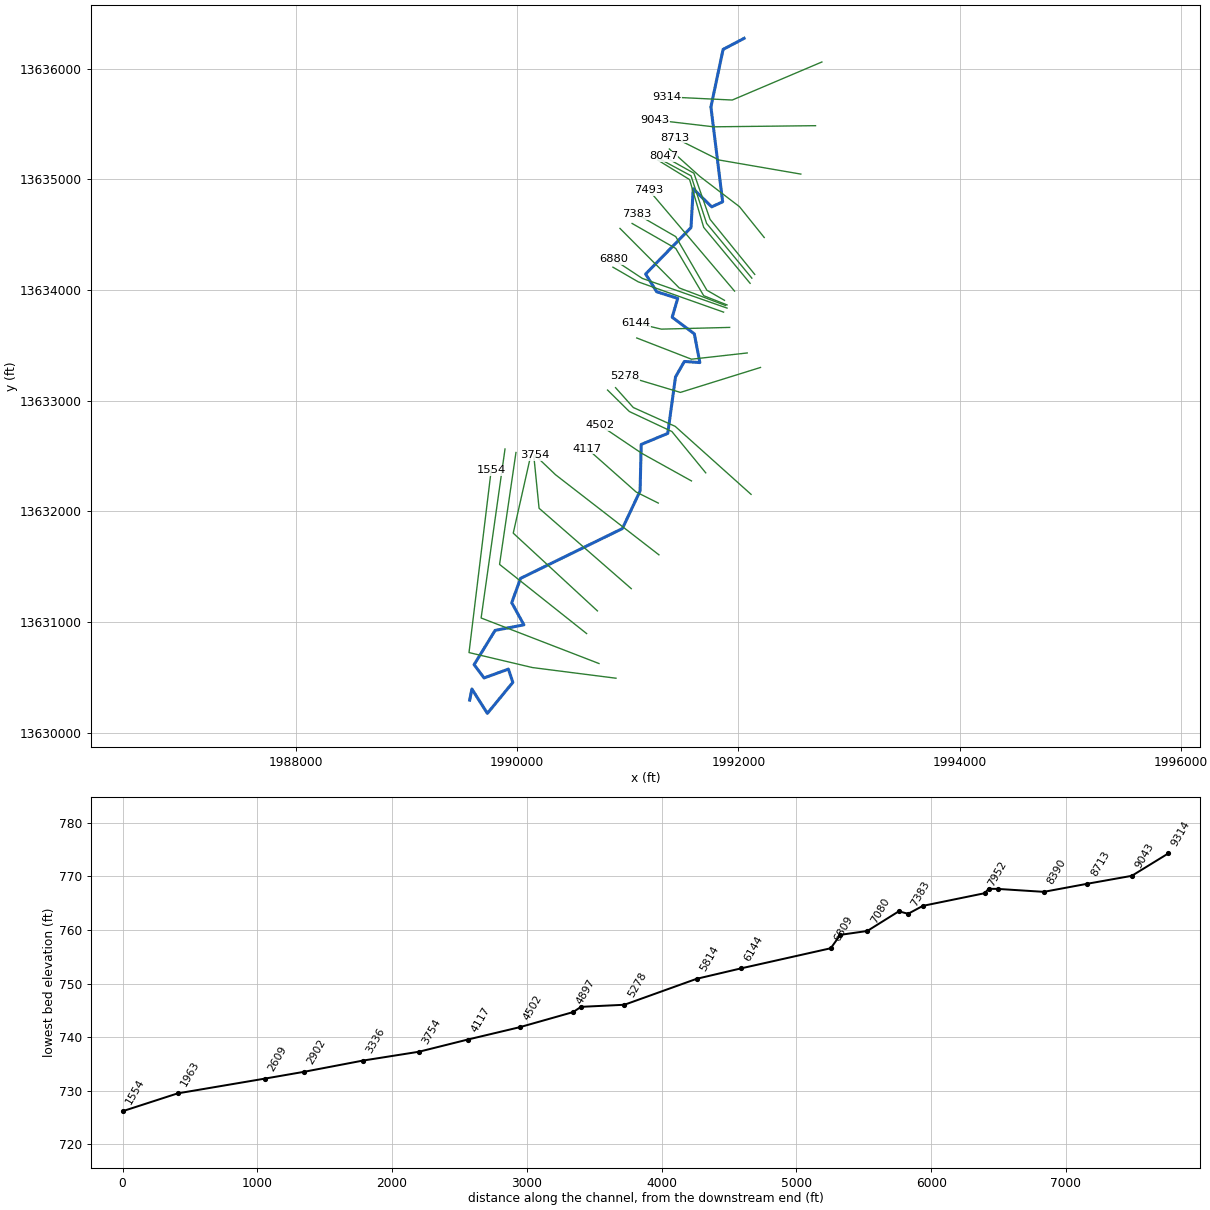
--- UNT 041 in HW.prj (project) ---

Proj Title=UNT 041 in HW Base Level Engineering
Current Plan=p01
Default Exp/Contr=0.3,0.1
English Units
Geom File=g01
Flow File=f01
Plan File=p01
BEGIN DESCRIPTION:
UNT 041 in HW
END DESCRIPTION:

--- UNT 041 in HW.p01 (plan) ---

Plan Title=Multiple Run
Short Identifier=Multiple
Geom File=g01
Flow File=f01
Subcritical Flow
K Sum by GR= 0
Std Step Tol= 0.01
Critical Tol= 0.01
Num of Std Step Trials= 20
Max Error Tol= 0.3
Flow Tol Ratio= 0.001
Split Flow NTrial= 30
Split Flow Tol= 0.02
Split Flow Ratio= 0.02
Log Output Level= 0
Friction Slope Method= 1
Unsteady Friction Slope Method= 2
Unsteady Bridges Friction Slope Method= 1
Parabolic Critical Depth
Global Vel Dist=  1 , 1 , 1
Global Log Level= 0
CheckData=True
Encroach Param= -1, 0, 0, 0
BEGIN DESCRIPTION:
Multiple Run
END DESCRIPTION:

--- UNT 041 in HW.f01 (steady flow) ---

Flow Title=Multiple
Number of Profiles=7
Profile Names=10-year,25-year,50-year,1pct_min,100-year,1pct_plu,500-year
River Rch & RM= UNT 041 in HW,Reach-1,9314
     742    1067    1346     841    1677    3347    2614
River Rch & RM= UNT 041 in HW,Reach-1,8713
     913    1322    1674    1049    2092    4175    3281
Boundary for River Rch & Prof#=UNT 041 in HW,Reach-1,1
Up Type=0
Dn Type=3
Dn Slope=0.005
Boundary for River Rch & Prof#=UNT 041 in HW,Reach-1,2
Up Type=0
Dn Type=3
Dn Slope=0.005
Boundary for River Rch & Prof#=UNT 041 in HW,Reach-1,3
Up Type=0
Dn Type=3
Dn Slope=0.005
Boundary for River Rch & Prof#=UNT 041 in HW,Reach-1,4
Up Type=0
Dn Type=3
Dn Slope=0.005
Boundary for River Rch & Prof#=UNT 041 in HW,Reach-1,5
Up Type=0
Dn Type=3
Dn Slope=0.005
Boundary for River Rch & Prof#=UNT 041 in HW,Reach-1,6
Up Type=0
Dn Type=3
Dn Slope=0.005
Boundary for River Rch & Prof#=UNT 041 in HW,Reach-1,7
Up Type=0
Dn Type=3
Dn Slope=0.005

--- UNT 041 in HW.g01 (geometry) ---

Geom Title=Existing Conditions

River Reach=UNT 041 in HW,Reach-1
Reach XY= 30
      1992050.80     13636274.54      1991860.80     13636174.54
      1991750.80     13635654.54      1991856.78     13634797.53
      1991758.35     13634751.70      1991590.80     13634914.54
      1991570.80     13634564.54      1991160.80     13634144.54
      1991260.80     13633984.54      1991450.80     13633924.54
      1991400.80     13633754.54      1991600.80     13633604.54
      1991650.80     13633344.54      1991510.80     13633354.54
      1991430.80     13633214.54      1991360.80     13632704.54
      1991120.80     13632604.54      1991110.80     13632184.54
      1990950.80     13631844.54      1990030.80     13631394.54
      1989950.80     13631174.54      1990060.80     13630974.54
      1989800.80     13630924.54      1989610.80     13630614.54
      1989700.80     13630494.54      1989920.80     13630574.54
      1989960.80     13630454.54      1989730.80     13630174.54
      1989590.80     13630394.54      1989570.80     13630294.54

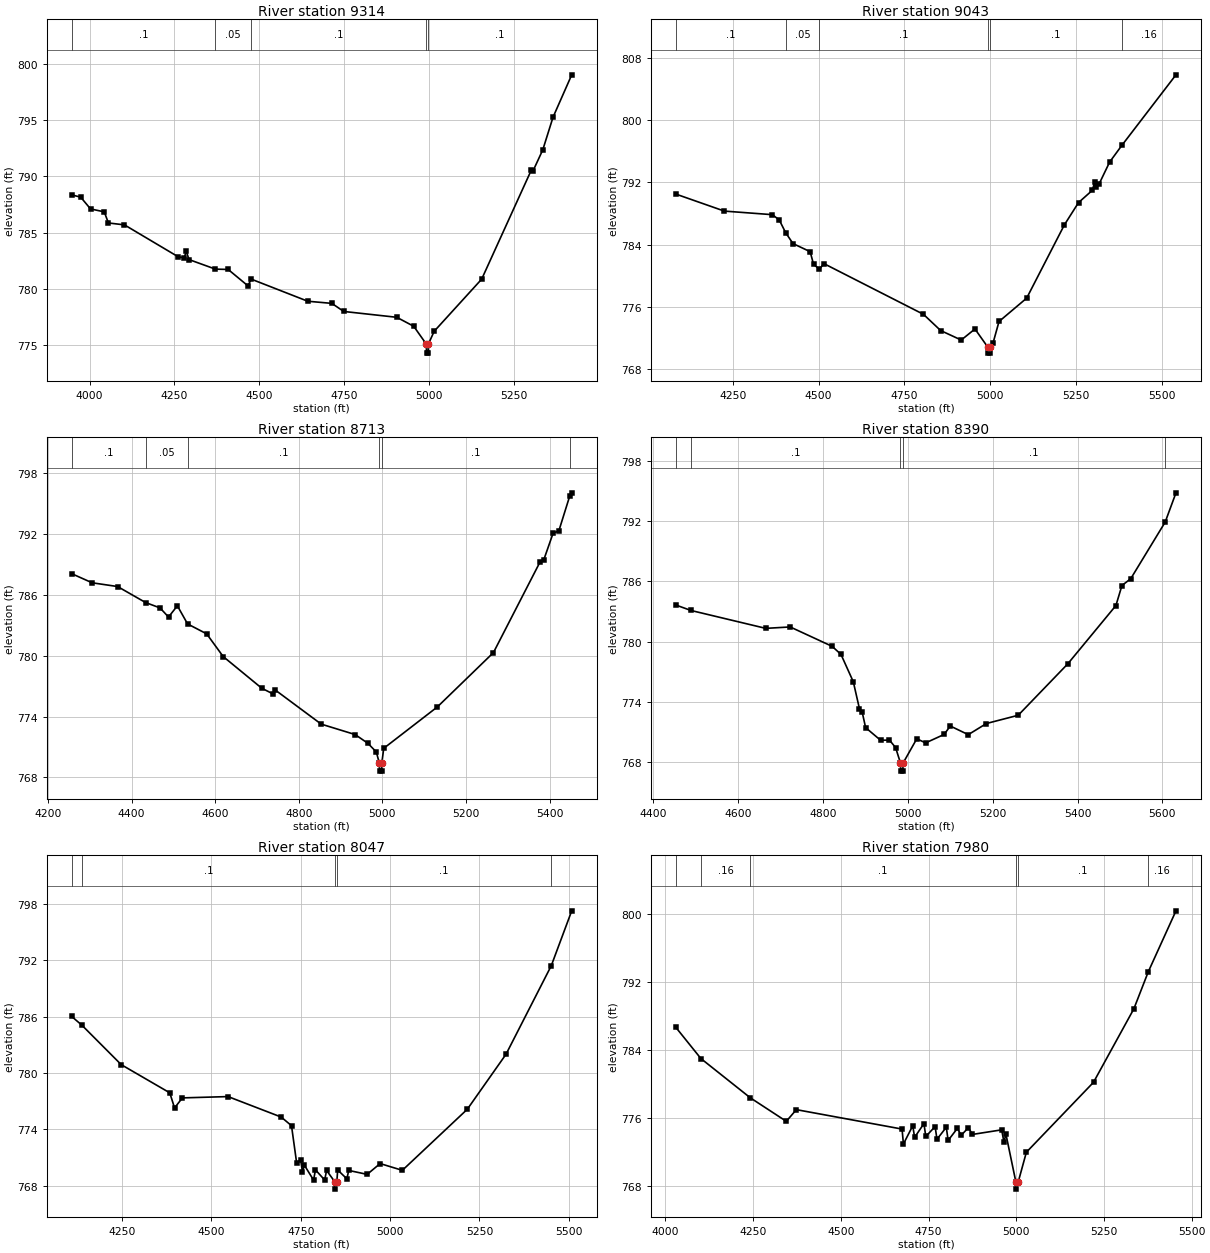
Type RM Length L Ch R = 1,9314,271,271,271
BEGIN DESCRIPTION:
UNT 041 in HW 14.0
END DESCRIPTION:
XS GIS Cut Line= 3
      1992753.37     13636060.76      1991943.49     13635717.01
      1991349.89     13635745.65
#Sta/Elev= 30
  3947.3  788.36  3973.8  788.16  4002.9  787.11  4043.3  786.85  4055.6  785.86
  4102.9  785.69  4261.2  782.85  4279.4  782.75  4284.8  783.36  4293.2  782.60
  4371.0  781.75  4408.6  781.72  4467.0  780.26  4476.5  780.86  4643.3  778.89
  4714.2  778.70  4749.4  777.98  4905.7  777.46  4955.7  776.66  4992.8  775.07
  4993.3  774.27  4998.3  774.27  4998.8  775.07  5015.8  776.21  5156.0  780.86
  5302.6  790.59  5307.6  790.51  5336.2  792.38  5366.2  795.27  5421.4  799.05
#Mann=5,-1,0
  3947.3     0.1       0  4371.0    0.05       0  4476.5     0.1       0
  4992.8    0.07       0  4998.8     0.1       0
Bank Sta=4992.8,4998.8
Exp/Cntr=0.3,0.1

Type RM Length L Ch R = 1,9043,330,330,330
BEGIN DESCRIPTION:
UNT 041 in HW 13.0
END DESCRIPTION:
XS GIS Cut Line= 3
      1992696.12     13635485.24      1991775.00     13635475.00
      1991243.02     13635537.32
#Sta/Elev= 30
  4084.1  790.50  4225.2  788.32  4365.2  787.86  4385.2  787.18  4403.9  785.54
  4425.2  784.15  4475.2  783.11  4485.2  781.47  4502.3  780.87  4515.2  781.58
  4805.3  775.07  4855.3  772.99  4915.3  771.77  4955.3  773.19  4992.2  770.89
  4992.7  770.09  4997.8  770.09  4998.3  770.89  5007.8  771.36  5025.4  774.15
  5106.0  777.15  5215.9  786.56  5257.0  789.41  5297.3  790.99  5304.2  792.07
  5309.2  791.40  5317.4  791.84  5347.6  794.61  5383.0  796.74  5540.9  805.81
#Mann=6,-1,0
  4084.1     0.1       0  4403.9    0.05       0  4502.3     0.1       0
  4992.2    0.07       0  4998.3     0.1       0  5383.0    0.16       0
Bank Sta=4992.2,4998.3
Exp/Cntr=0.3,0.1

Type RM Length L Ch R = 1,8713,323,323,323
BEGIN DESCRIPTION:
UNT 041 in HW 12.0
END DESCRIPTION:
XS GIS Cut Line= 3
      1992563.30     13635047.74      1991825.00     13635175.00
      1991425.00     13635375.00
#Sta/Elev= 30
  4256.7  788.10  4305.7  787.20  4366.6  786.83  4433.6  785.25  4468.1  784.72
  4488.4  783.82  4509.6  784.93  4534.0  783.14  4579.7  782.16  4619.2  779.92
  4711.6  776.79  4739.0  776.22  4744.0  776.61  4853.7  773.25  4934.9  772.22
  4965.3  771.36  4985.6  770.50  4992.7  769.41  4993.2  768.61  4998.3  768.61
  4998.8  769.41  5003.3  770.86  5131.7  774.95  5265.8  780.31  5377.6  789.28
  5386.0  789.44  5408.4  792.08  5422.4  792.34  5448.6  795.80  5453.1  796.08
#Mann=6,-1,0
  4256.7     0.1       0  4433.6    0.05       0  4534.0     0.1       0
  4992.7    0.07       0  4998.8     0.1       0  5448.6    0.16       0
Bank Sta=4992.7,4998.8
Exp/Cntr=0.3,0.1

Type RM Length L Ch R = 1,8390,343,343,343
BEGIN DESCRIPTION:
UNT 041 in HW 11.0
END DESCRIPTION:
XS GIS Cut Line= 4
      1992232.56     13634474.81      1992008.59     13634753.47
      1991651.44     13635026.20      1991375.00     13635275.00
#Sta/Elev= 30
  4453.3  783.63  4488.9  783.09  4665.1  781.31  4722.7  781.45  4821.6  779.52
  4842.4  778.72  4871.5  775.99  4886.0  773.30  4892.3  772.99  4900.5  771.43
  4935.9  770.17  4956.7  770.19  4971.2  769.44  4982.7  767.90  4983.2  767.10
  4988.3  767.10  4988.8  767.90  5021.1  770.32  5041.9  769.91  5085.5  770.75
  5100.1  771.59  5142.5  770.73  5185.3  771.84  5260.2  772.66  5376.9  777.77
  5490.5  783.58  5504.7  785.57  5525.6  786.26  5606.7  791.89  5632.1  794.80
#Mann=5,-1,0
  4453.3    0.05       0  4488.9     0.1       0  4982.7    0.07       0
  4988.8     0.1       0  5606.7    0.16       0
Bank Sta=4982.7,4988.8
Exp/Cntr=0.3,0.1

Type RM Length L Ch R = 1,8047,67,67,67
BEGIN DESCRIPTION:
Mapping XS c11ef7d7
END DESCRIPTION:
XS GIS Cut Line= 4
      1992146.59     13634141.52      1991742.97     13634638.89
      1991597.14     13635055.56      1991320.89     13635210.46
#Sta/Elev= 30
  4109.3  786.03  4138.4  785.08  4247.9  780.90  4383.7  777.90  4397.1  776.29
  4418.9  777.36  4546.7  777.50  4695.4  775.32  4724.2  774.40  4738.5  770.46
  4749.8  770.75  4754.9  769.48  4760.2  770.20  4785.9  768.61  4791.2  769.70
  4817.0  768.62  4822.3  769.64  4844.9  768.45  4845.4  767.65  4851.1  768.45
  4853.3  769.69  4879.0  768.75  4884.3  769.64  4935.8  769.22  4972.1  770.37
  5034.2  769.65  5215.9  776.15  5324.3  782.01  5450.8  791.43  5508.0  797.27
#Mann=5,-1,0
  4109.3    0.16       0  4138.4     0.1       0  4844.9    0.07       0
  4851.1     0.1       0  5450.8    0.16       0
Bank Sta=4844.9,4851.1
Exp/Cntr=0.3,0.1

Type RM Length L Ch R = 1,7980,28,28,28
BEGIN DESCRIPTION:
Mapping XS 7a6661eb
END DESCRIPTION:
XS GIS Cut Line= 4
      1992120.60     13634107.60      1991711.72     13634602.43
      1991571.09     13635032.12      1991279.31     13635189.63
#Sta/Elev= 30
  4029.7  786.65  4100.9  783.00  4241.8  778.39  4344.4  775.63  4373.1  777.00
  4674.4  774.72  4678.3  772.97  4704.9  775.11  4710.2  773.75  4736.8  775.36
  4742.1  773.85  4768.7  775.02  4773.9  773.52  4800.5  774.93  4805.8  773.39
  4832.1  774.80  4842.9  773.99  4863.7  774.89  4874.8  774.09  4958.4  774.63
  4965.1  773.15  4970.3  774.17  4999.1  768.47  4999.6  767.67  5005.3  768.47
  5028.8  772.00  5220.2  780.21  5335.3  788.84  5376.5  793.20  5455.3  800.34
#Mann=6,-1,0
  4029.7     0.1       0  4100.9    0.16       0  4241.8     0.1       0
  4999.1    0.07       0  5005.3     0.1       0  5376.5    0.16       0
Bank Sta=4999.1,5005.3
Exp/Cntr=0.3,0.1

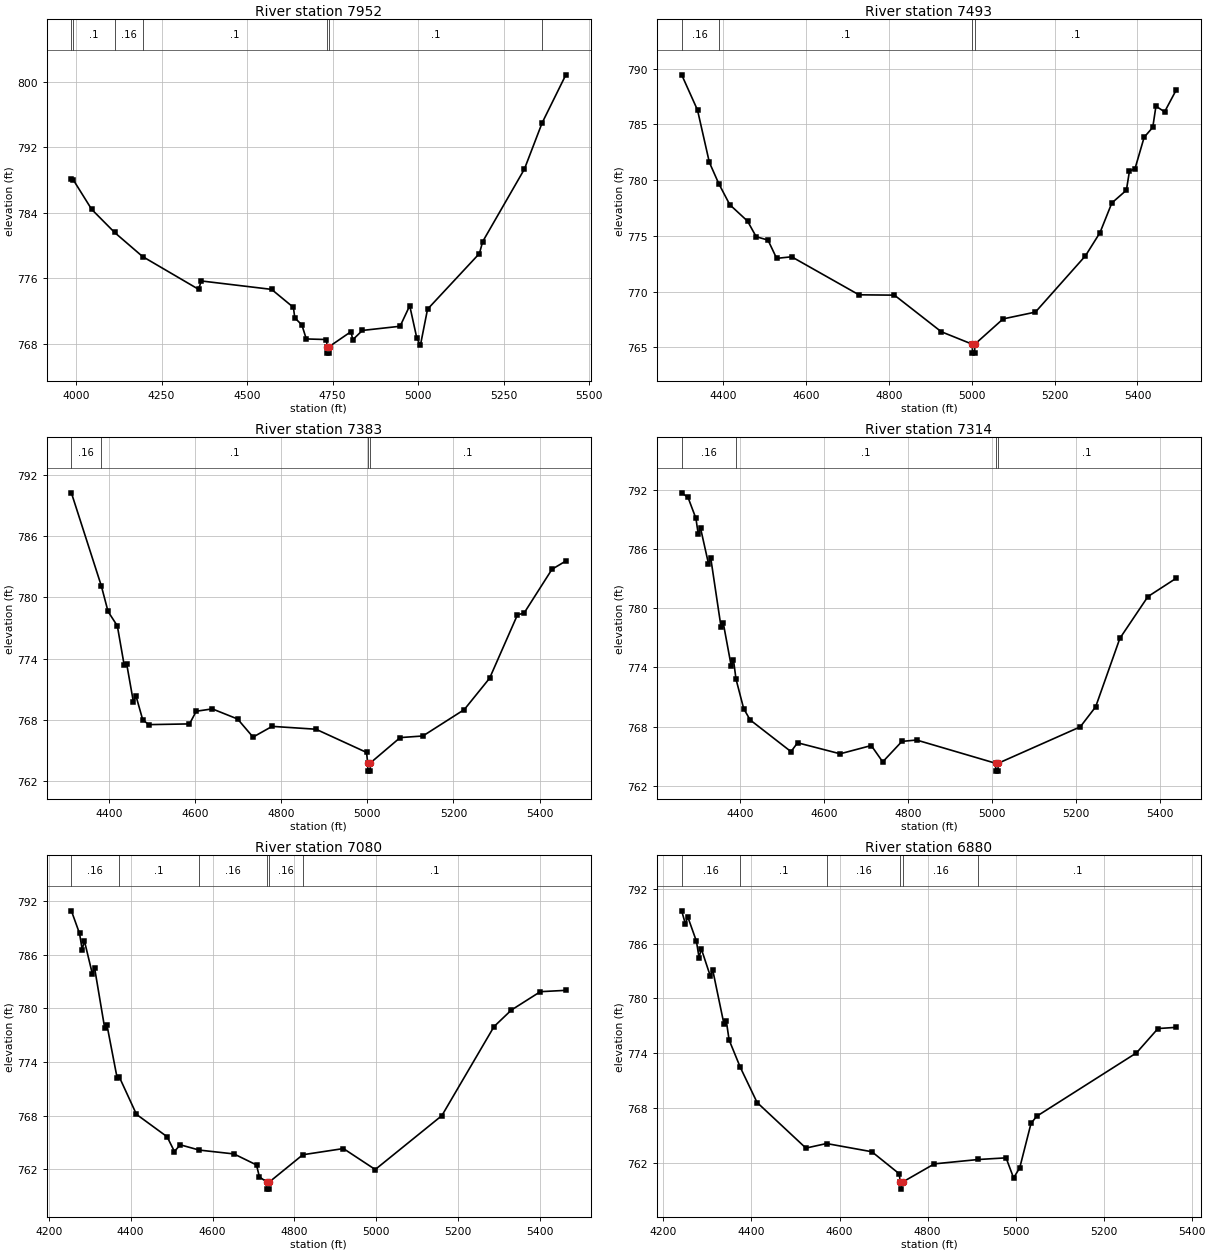
Type RM Length L Ch R = 1,7952,459,459,459
BEGIN DESCRIPTION:
Mapping XS 9c8957d4
END DESCRIPTION:
XS GIS Cut Line= 4
      1992104.94     13634060.77      1991685.68     13634565.97
      1991558.07     13634998.26      1991269.47     13635175.07
#Sta/Elev= 30
  3986.5  788.08  3991.7  788.02  4045.8  784.40  4112.8  781.58  4194.6  778.64
  4358.4  774.64  4366.2  775.66  4571.9  774.63  4635.7  772.43  4639.6  771.16
  4660.4  770.29  4673.3  768.58  4732.2  768.51  4734.3  767.65  4734.8  766.85
  4740.0  766.85  4740.5  767.65  4804.0  769.47  4809.2  768.48  4837.3  769.62
  4947.6  770.13  4975.7  772.64  4996.5  768.68  5006.9  767.79  5027.8  772.21
  5179.5  779.01  5189.0  780.46  5311.0  789.31  5362.9  794.96  5432.2  800.82
#Mann=7,-1,0
  3986.5    0.16       0  3991.7     0.1       0  4112.8    0.16       0
  4194.6     0.1       0  4734.3    0.07       0  4740.5     0.1       0
  5362.9    0.16       0
Bank Sta=4734.3,4740.5
Exp/Cntr=0.3,0.1

Type RM Length L Ch R = 1,7493,110,110,110
BEGIN DESCRIPTION:
Mapping XS 308f55a8
END DESCRIPTION:
XS GIS Cut Line= 2
      1991964.33     13633990.44      1991191.67     13634900.99
#Sta/Elev= 30
  4299.3  789.45  4337.5  786.29  4366.1  781.60  4388.7  779.70  4415.5  777.80
  4458.3  776.33  4479.2  774.93  4507.7  774.63  4528.6  772.99  4564.9  773.13
  4727.4  769.72  4813.1  769.69  4926.2  766.41  5001.1  765.29  5001.6  764.49
  5006.8  764.49  5007.3  765.29  5075.6  767.56  5153.6  768.17  5274.5  773.22
  5309.6  775.30  5338.2  777.96  5373.3  779.10  5380.7  780.81  5394.1  781.03
  5416.2  783.85  5437.0  784.74  5444.7  786.64  5465.6  786.13  5493.5  788.08
#Mann=4,-1,0
  4299.3    0.16       0  4388.7     0.1       0  5001.1    0.07       0
  5007.3     0.1       0
Bank Sta=5001.1,5007.3
Exp/Cntr=0.3,0.1

Type RM Length L Ch R = 1,7383,69,69,69
BEGIN DESCRIPTION:
Mapping XS 4edc6936
END DESCRIPTION:
XS GIS Cut Line= 4
      1991873.14     13633907.14      1991714.32     13633998.26
      1991433.07     13634482.64      1991081.54     13634685.74
#Sta/Elev= 30
  4312.0  790.24  4381.6  781.13  4397.2  778.63  4418.8  777.22  4434.6  773.41
  4440.4  773.53  4456.2  769.76  4462.0  770.39  4477.8  768.03  4491.8  767.56
  4586.5  767.63  4602.2  768.87  4639.5  769.10  4698.3  768.11  4734.2  766.34
  4778.6  767.39  4880.4  767.11  4998.0  764.84  5000.6  763.81  5001.1  763.01
  5006.3  763.01  5006.8  763.81  5076.1  766.29  5129.0  766.45  5225.1  769.03
  5284.0  772.10  5348.6  778.29  5364.4  778.49  5429.0  782.76  5461.2  783.57
#Mann=4,-1,0
  4312.0    0.16       0  4381.6     0.1       0  5000.6    0.07       0
  5006.8     0.1       0
Bank Sta=5000.6,5006.8
Exp/Cntr=0.3,0.1

Type RM Length L Ch R = 1,7314,234,234,234
BEGIN DESCRIPTION:
Mapping XS 431adfda
END DESCRIPTION:
XS GIS Cut Line= 4
      1991896.57     13633865.47      1991685.68     13633948.78
      1991433.07     13634375.87      1991038.66     13634601.62
#Sta/Elev= 30
  4261.7  791.74  4276.8  791.27  4295.6  789.14  4301.1  787.54  4306.5  788.17
  4325.5  784.54  4330.9  785.11  4355.2  778.16  4360.6  778.54  4379.6  774.16
  4385.0  774.78  4391.0  772.82  4409.3  769.82  4424.7  768.67  4522.0  765.45
  4537.6  766.35  4639.0  765.23  4713.1  766.07  4740.4  764.41  4786.1  766.49
  4821.0  766.63  5009.1  764.27  5009.6  763.47  5014.8  763.47  5015.3  764.27
  5210.8  767.97  5247.4  770.00  5305.1  776.96  5371.9  781.20  5439.1  783.06
#Mann=4,-1,0
  4261.7    0.16       0  4391.0     0.1       0  5009.1    0.07       0
  5015.3     0.1       0
Bank Sta=5009.1,5015.3
Exp/Cntr=0.3,0.1

Type RM Length L Ch R = 1,7080,200,200,200
BEGIN DESCRIPTION:
Mapping XS 84442276
END DESCRIPTION:
XS GIS Cut Line= 3
      1991883.58     13633860.25      1991464.32     13634019.10
      1990928.96     13634557.06
#Sta/Elev= 30
  4255.4  790.88  4275.3  788.35  4281.8  786.54  4287.1  787.54  4306.6  783.84
  4311.9  784.54  4336.7  777.79  4342.1  778.16  4366.9  772.26  4372.1  772.35
  4414.3  768.15  4489.1  765.65  4507.0  764.00  4521.2  764.75  4567.7  764.16
  4652.4  763.73  4707.4  762.50  4714.5  761.16  4732.6  760.60  4733.1  759.80
  4738.3  759.80  4738.8  760.60  4820.5  763.64  4919.6  764.33  4997.3  761.99
  5160.0  768.01  5287.3  777.95  5329.7  779.80  5400.4  781.85  5462.7  782.00
#Mann=6,-1,0
  4255.4    0.16       0  4372.1     0.1       0  4567.7    0.16       0
  4732.6    0.07       0  4738.8    0.16       0  4820.5     0.1       0
Bank Sta=4732.6,4738.8
Exp/Cntr=0.3,0.1

Type RM Length L Ch R = 1,6880,71,71,71
BEGIN DESCRIPTION:
Mapping XS c7f74c9a
END DESCRIPTION:
XS GIS Cut Line= 3
      1991896.64     13633836.80      1991130.99     13634105.03
      1990870.57     13634276.91
#Sta/Elev= 30
  4241.5  789.60  4249.9  788.15  4255.2  788.95  4275.0  786.26  4280.9  784.48
  4286.2  785.41  4306.6  782.43  4311.9  783.13  4337.6  777.16  4342.9  777.51
  4349.2  775.44  4374.6  772.44  4412.8  768.58  4523.7  763.58  4570.5  764.08
  4673.5  763.18  4735.5  760.77  4738.1  759.88  4738.6  759.08  4744.3  759.88
  4815.4  761.85  4915.6  762.33  4978.4  762.51  4995.5  760.31  5009.4  761.41
  5035.1  766.29  5048.0  767.07  5274.6  774.02  5323.5  776.69  5364.8  776.82
#Mann=6,-1,0
  4241.5    0.16       0  4374.6     0.1       0  4570.5    0.16       0
  4738.1    0.07       0  4744.3    0.16       0  4915.6     0.1       0
Bank Sta=4738.1,4744.3
Exp/Cntr=0.3,0.1

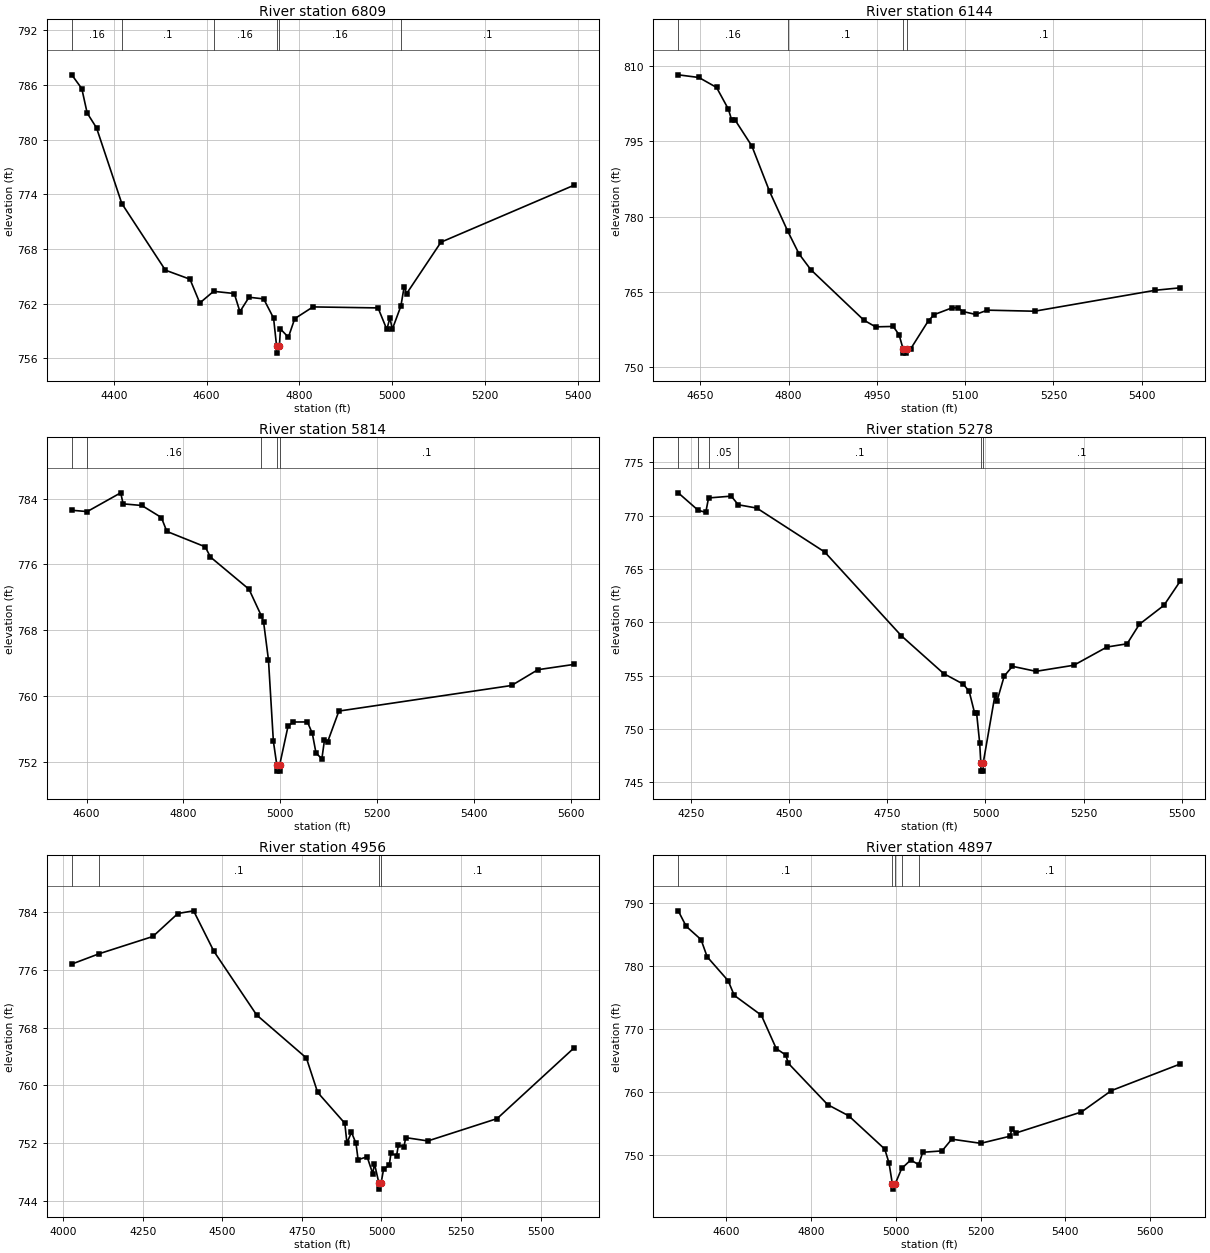
Type RM Length L Ch R = 1,6809,665,665,665
BEGIN DESCRIPTION:
Mapping XS 000b31de
END DESCRIPTION:
XS GIS Cut Line= 4
      1991865.34     13633800.36      1991438.28     13633951.39
      1991094.53     13634073.78      1990865.39     13634206.58
#Sta/Elev= 30
  4309.1  787.11  4330.7  785.60  4342.3  782.92  4362.5  781.29  4417.0  772.99
  4511.0  765.68  4564.0  764.69  4585.2  762.08  4614.9  763.36  4659.5  763.12
  4671.7  761.13  4691.3  762.71  4722.9  762.53  4744.3  760.42  4750.7  757.38
  4751.2  756.58  4756.9  757.38  4759.1  759.23  4776.2  758.32  4789.9  760.36
  4829.2  761.65  4969.6  761.54  4988.5  759.18  4995.1  760.44  5000.4  759.21
  5018.8  761.74  5025.9  763.87  5031.2  763.11  5105.2  768.75  5391.8  774.99
#Mann=6,-1,0
  4309.1    0.16       0  4417.0     0.1       0  4614.9    0.16       0
  4750.7    0.07       0  4756.9    0.16       0  5018.8     0.1       0
Bank Sta=4750.7,4756.9
Exp/Cntr=0.3,0.1

Type RM Length L Ch R = 1,6144,330,330,330
BEGIN DESCRIPTION:
Mapping XS ad8fceb4
END DESCRIPTION:
XS GIS Cut Line= 3
      1991920.09     13633662.33      1991302.86     13633646.70
      1991073.72     13633701.38
#Sta/Elev= 30
  4612.6  808.21  4647.7  807.68  4677.7  805.70  4697.7  801.40  4703.6  799.15
  4708.6  799.32  4737.7  794.04  4767.7  785.03  4798.6  777.11  4817.8  772.58
  4837.8  769.44  4927.8  759.41  4947.8  758.06  4977.8  758.14  4987.8  756.49
  4994.7  753.63  4995.2  752.83  5000.4  752.83  5000.9  753.63  5007.8  753.74
  5037.8  759.31  5047.8  760.51  5077.8  761.84  5087.8  761.86  5096.3  761.11
  5117.9  760.53  5137.9  761.38  5217.9  761.17  5423.2  765.34  5465.6  765.83
#Mann=4,-1,0
  4612.6    0.16       0  4798.6     0.1       0  4994.7    0.07       0
  5000.9     0.1       0
Bank Sta=4994.7,5000.9
Exp/Cntr=0.3,0.1

Type RM Length L Ch R = 1,5814,536,536,536
BEGIN DESCRIPTION:
UNT 041 in HW 6.0
END DESCRIPTION:
XS GIS Cut Line= 3
      1992078.92     13633431.42      1991575.00     13633375.00
      1991080.69     13633566.82
#Sta/Elev= 30
  4569.2  782.59  4601.1  782.43  4670.3  784.71  4675.3  783.37  4714.0  783.17
  4754.3  781.71  4765.6  780.02  4844.8  778.15  4855.8  776.90  4935.4  772.99
  4960.9  769.75  4965.6  768.97  4975.6  764.39  4985.7  754.52  4992.7  751.68
  4993.2  750.88  4998.4  750.88  4998.9  751.68  5015.9  756.31  5026.0  756.85
  5056.1  756.86  5066.2  755.46  5073.8  753.08  5085.9  752.38  5091.2  754.61
  5097.7  754.42  5121.1  758.18  5477.8  761.29  5532.3  763.21  5606.5  763.85
#Mann=5,-1,0
  4569.2     0.1       0  4601.1    0.16       0  4960.9     0.1       0
  4992.7    0.07       0  4998.9     0.1       0
Bank Sta=4992.7,4998.9
Exp/Cntr=0.3,0.1

Type RM Length L Ch R = 1,5278,322,322,322
BEGIN DESCRIPTION:
UNT 041 in HW 5.0
END DESCRIPTION:
XS GIS Cut Line= 3
      1992198.66     13633300.34      1991475.00     13633075.00
      1990975.05     13633224.99
#Sta/Elev= 30
  4216.8  772.14  4267.7  770.50  4287.0  770.31  4294.1  771.66  4352.0  771.83
  4369.7  771.02  4417.1  770.71  4590.2  766.59  4785.4  758.74  4893.4  755.19
  4943.3  754.20  4958.5  753.52  4972.1  751.52  4977.3  751.52  4985.2  748.70
  4988.1  746.84  4988.6  746.04  4993.9  746.04  4994.4  746.84  5024.3  753.18
  5029.5  752.63  5047.8  754.95  5068.7  755.87  5128.7  755.40  5225.3  755.97
  5309.7  757.68  5361.0  757.98  5392.3  759.81  5455.0  761.59  5496.7  763.87
#Mann=6,-1,0
  4216.8    0.05       0  4267.7     0.1       0  4294.1    0.05       0
  4369.7     0.1       0  4988.1    0.07       0  4994.4     0.1       0
Bank Sta=4988.1,4994.4
Exp/Cntr=0.3,0.1

Type RM Length L Ch R = 1,4956,59,59,59
BEGIN DESCRIPTION:
Mapping XS e3586f3f
END DESCRIPTION:
XS GIS Cut Line= 4
      1992113.66     13632153.62      1991427.86     13632768.23
      1991049.39     13632938.37      1990888.98     13633117.75
#Sta/Elev= 30
  4027.5  776.80  4114.1  778.24  4282.2  780.62  4360.7  783.80  4410.0  784.17
  4473.6  778.58  4608.1  769.75  4764.2  763.80  4799.5  759.04  4884.8  754.77
  4891.5  752.04  4905.7  753.52  4919.9  752.00  4926.6  749.72  4954.9  750.13
  4972.5  747.80  4978.0  749.16  4992.1  746.45  4992.6  745.65  4998.6  746.45
  5006.7  748.43  5024.3  748.93  5029.8  750.62  5047.5  750.29  5053.0  751.73
  5070.7  751.54  5076.1  752.78  5145.6  752.32  5363.0  755.41  5604.0  765.17
#Mann=4,-1,0
  4027.5    0.05       0  4114.1     0.1       0  4992.1    0.07       0
  4998.6     0.1       0
Bank Sta=4992.1,4998.6
Exp/Cntr=0.3,0.1

Type RM Length L Ch R = 1,4897,395,395,395
BEGIN DESCRIPTION:
UNT 041 in HW 4.0
END DESCRIPTION:
XS GIS Cut Line= 4
      1991703.91     13632348.09      1991398.35     13632721.35
      1991013.85     13632902.11      1990816.74     13633096.37
#Sta/Elev= 30
  4487.0  788.78  4505.7  786.33  4540.8  784.22  4555.2  781.49  4604.7  777.70
  4619.1  775.38  4683.0  772.23  4718.1  766.95  4740.4  765.93  4746.8  764.60
  4839.4  758.06  4889.0  756.29  4974.0  751.02  4984.1  748.80  4992.0  745.47
  4992.5  744.67  4998.5  745.47  5013.9  747.94  5035.3  749.29  5053.8  748.55
  5063.6  750.51  5109.2  750.73  5132.0  752.59  5200.4  751.93  5268.8  753.05
  5274.4  754.22  5282.5  753.55  5437.9  756.90  5508.6  760.29  5671.0  764.51
#Mann=5,-1,0
  4487.0     0.1       0  4992.0    0.07       0  4998.5     0.1       0
  5013.9    0.07       0  5053.8     0.1       0
Bank Sta=4992,4998.5
Exp/Cntr=0.3,0.1

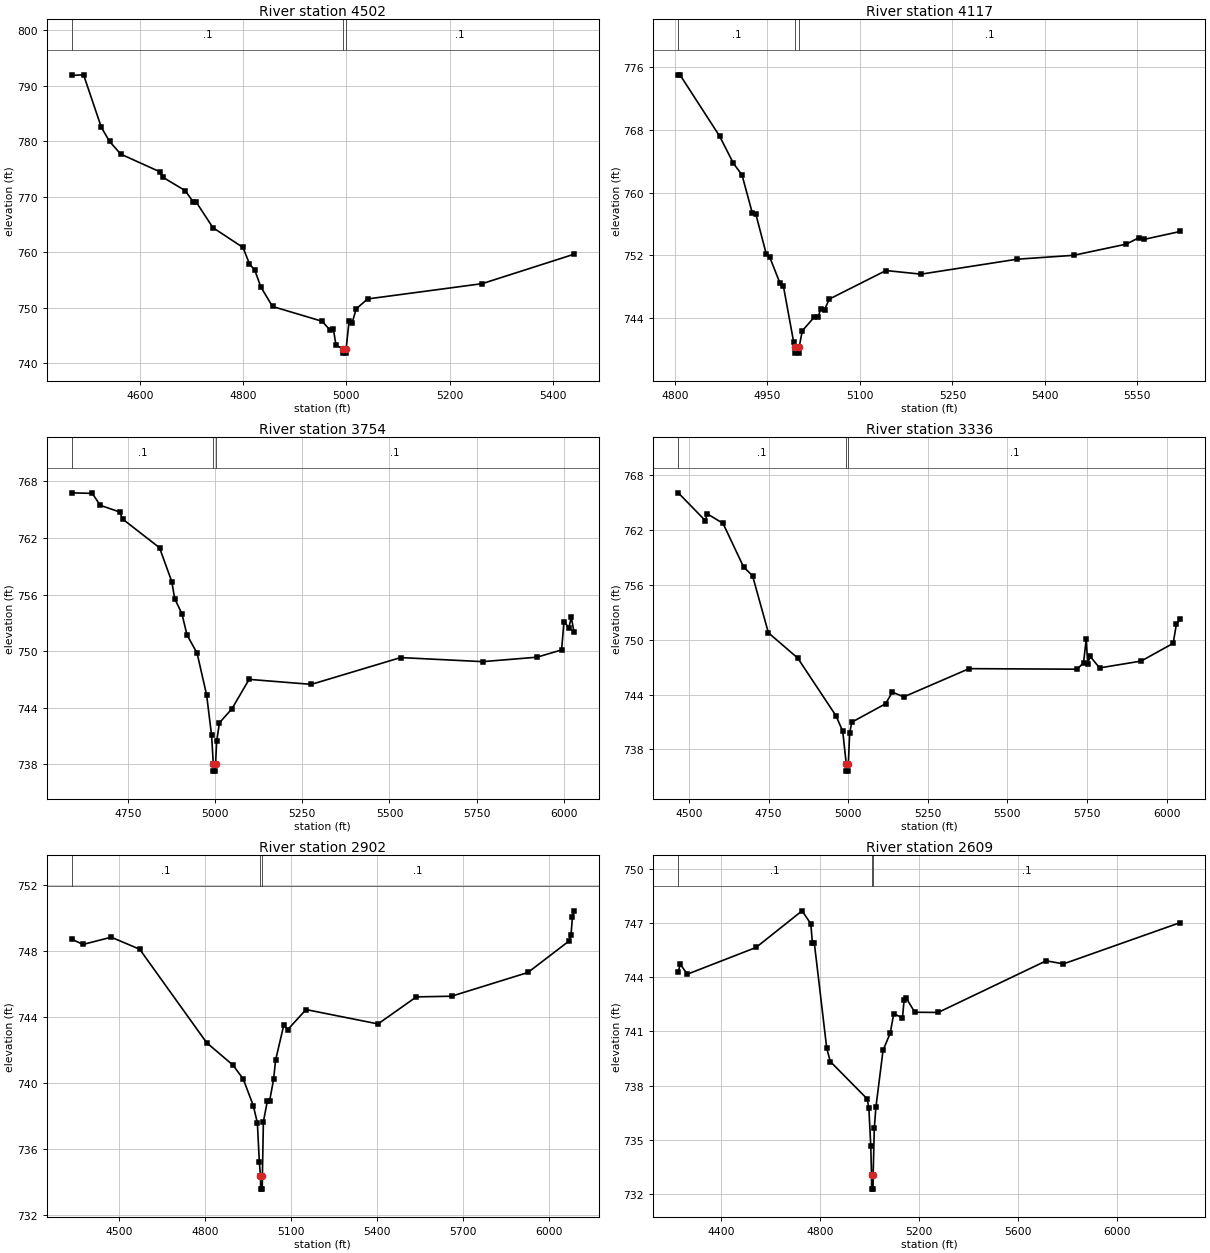
Type RM Length L Ch R = 1,4502,385,385,385
BEGIN DESCRIPTION:
UNT 041 in HW 3.0
END DESCRIPTION:
XS GIS Cut Line= 3
      1991574.99     13632275.01      1991125.00     13632525.00
      1990745.37     13632781.09
#Sta/Elev= 30
  4468.1  791.88  4491.0  791.98  4525.3  782.54  4541.3  779.98  4563.0  777.70
  4638.5  774.53  4644.3  773.55  4687.7  771.13  4703.7  769.07  4709.5  769.02
  4741.5  764.46  4799.8  760.89  4812.4  757.93  4822.7  756.79  4834.2  753.81
  4857.0  750.26  4953.1  747.60  4969.1  745.94  4974.9  746.22  4980.0  743.28
  4993.1  742.66  4993.6  741.86  4999.2  741.86  4999.7  742.66  5005.3  747.60
  5011.4  747.35  5019.1  749.83  5041.3  751.62  5263.2  754.37  5440.8  759.66
#Mann=3,-1,0
  4468.1     0.1       0  4993.1    0.07       0  4999.7     0.1       0
Bank Sta=4993.1,4999.7
Exp/Cntr=0.3,0.1

Type RM Length L Ch R = 1,4117,363,363,363
BEGIN DESCRIPTION:
UNT 041 in HW 2.0
END DESCRIPTION:
XS GIS Cut Line= 3
      1991275.03     13632074.98      1991075.00     13632175.00
      1990632.75     13632566.82
#Sta/Elev= 30
  4805.2  775.01  4808.0  775.01  4872.3  767.20  4894.7  763.74  4908.7  762.24
  4925.4  757.40  4931.0  757.29  4947.8  752.25  4953.4  751.83  4970.1  748.50
  4975.7  748.15  4992.5  740.94  4994.8  740.36  4995.3  739.56  5000.9  739.56
  5001.4  740.36  5006.5  742.41  5026.0  744.16  5032.2  744.16  5036.0  745.13
  5042.6  745.09  5050.2  746.44  5142.2  750.08  5199.1  749.62  5354.6  751.52
  5446.6  752.02  5531.9  753.44  5552.8  754.27  5560.4  754.04  5619.7  755.06
#Mann=3,-1,0
  4805.2     0.1       0  4994.8    0.07       0  5001.4     0.1       0
Bank Sta=4994.8,5001.4
Exp/Cntr=0.3,0.1

Type RM Length L Ch R = 1,3754,418,418,418
BEGIN DESCRIPTION:
Mapping XS 2e39896f
END DESCRIPTION:
XS GIS Cut Line= 3
      1991280.90     13631607.33      1990346.83     13632330.91
      1990159.52     13632509.57
#Sta/Elev= 30
  4588.5  766.79  4647.4  766.73  4670.0  765.47  4726.1  764.76  4734.3  764.01
  4840.2  760.97  4875.5  757.37  4883.7  755.58  4904.5  753.96  4919.0  751.73
  4948.0  749.79  4975.4  745.35  4989.6  741.08  4994.5  738.08  4995.0  737.28
  5000.6  737.28  5001.1  738.08  5004.1  740.44  5012.2  742.41  5047.6  743.87
  5097.3  747.01  5275.7  746.48  5532.0  749.32  5767.3  748.89  5922.9  749.36
  5993.7  750.13  6000.6  753.13  6014.7  752.49  6021.6  753.62  6028.9  752.08
#Mann=3,-1,0
  4588.5     0.1       0  4994.5    0.07       0  5001.1     0.1       0
Bank Sta=4994.5,5001.1
Exp/Cntr=0.3,0.1

Type RM Length L Ch R = 1,3336,434,434,434
BEGIN DESCRIPTION:
Mapping XS 5dd8610e
END DESCRIPTION:
XS GIS Cut Line= 3
      1991030.90     13631301.77      1990197.90     13632028.15
      1990150.81     13632497.37
#Sta/Elev= 30
  4466.4  766.09  4551.1  763.06  4557.7  763.79  4607.1  762.74  4671.7  757.97
  4699.8  757.01  4749.5  750.77  4841.6  748.00  4962.2  741.66  4983.0  739.98
  4994.0  736.42  4994.5  735.62  5000.1  735.62  5000.6  736.42  5004.9  739.83
  5011.5  740.98  5117.8  743.00  5138.7  744.27  5174.8  743.75  5379.9  746.84
  5719.2  746.78  5739.3  747.48  5747.6  750.05  5752.6  747.35  5759.4  748.22
  5789.6  746.92  5920.2  747.67  6020.7  749.61  6030.8  751.69  6043.2  752.27
#Mann=3,-1,0
  4466.4     0.1       0  4994.0    0.07       0  5000.6     0.1       0
Bank Sta=4994,5000.6
Exp/Cntr=0.3,0.1

Type RM Length L Ch R = 1,2902,293,293,293
BEGIN DESCRIPTION:
Mapping XS d8c8f98b
END DESCRIPTION:
XS GIS Cut Line= 3
      1990725.28     13631100.44      1989964.51     13631803.19
      1990121.86     13632501.29
#Sta/Elev= 30
  4335.8  748.70  4374.8  748.38  4473.5  748.82  4572.7  748.09  4806.3  742.42
  4898.2  741.06  4933.9  740.22  4969.0  738.60  4983.2  737.56  4990.0  735.19
  4994.1  734.34  4994.6  733.54  5000.2  733.54  5000.7  734.34  5004.2  737.63
  5018.4  738.91  5025.7  738.87  5039.9  740.21  5046.7  741.36  5075.1  743.47
  5089.3  743.22  5153.0  744.43  5404.1  743.56  5537.7  745.20  5660.4  745.24
  5926.9  746.68  6070.4  748.59  6077.1  748.93  6082.2  750.05  6087.1  750.42
#Mann=3,-1,0
  4335.8     0.1       0  4994.1    0.07       0  5000.7     0.1       0
Bank Sta=4994.1,5000.7
Exp/Cntr=0.3,0.1

Type RM Length L Ch R = 1,2609,646,646,646
BEGIN DESCRIPTION:
Mapping XS 70a7fcd6
END DESCRIPTION:
XS GIS Cut Line= 3
      1990627.37     13630895.85      1989840.91     13631520.85
      1989989.06     13632531.89
#Sta/Elev= 30
  4227.6  744.30  4235.6  744.72  4264.5  744.17  4541.6  745.65  4727.5  747.68
  4762.7  746.96  4769.1  745.89  4777.1  745.87  4826.8  740.08  4841.2  739.33
  4990.2  737.26  4997.0  736.75  5004.6  734.67  5007.7  733.06  5008.2  732.26
  5013.8  732.26  5014.3  733.06  5019.0  735.65  5025.4  736.80  5054.2  739.95
  5083.1  740.90  5097.5  741.98  5132.7  741.75  5139.1  742.74  5147.2  742.86
  5182.4  742.06  5276.8  742.05  5712.6  744.91  5782.4  744.74  6254.0  747.03
#Mann=3,-1,0
  4227.6     0.1       0  5007.7    0.07       0  5014.3     0.1       0
Bank Sta=5007.7,5014.3
Exp/Cntr=0.3,0.1

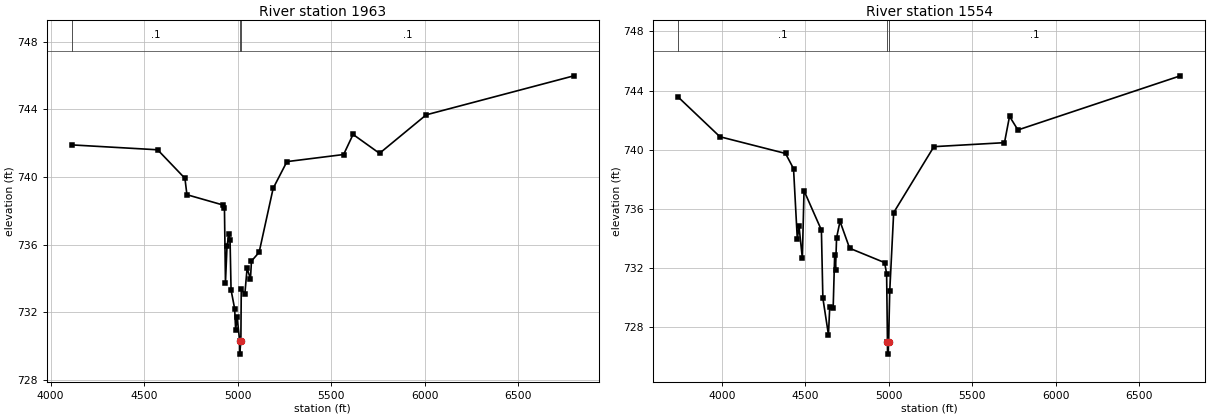
Type RM Length L Ch R = 1,1963,409,409,409
BEGIN DESCRIPTION:
Mapping XS 7f7e9653
END DESCRIPTION:
XS GIS Cut Line= 3
      1990739.37     13630625.01      1989674.24     13631036.48
      1989890.20     13632563.75
#Sta/Elev= 30
  4113.3  741.90  4572.4  741.61  4718.3  739.92  4729.0  738.95  4922.0  738.34
  4929.6  738.15  4935.0  733.73  4943.4  735.93  4954.2  736.64  4959.6  736.26
  4964.9  733.31  4984.2  732.20  4989.5  730.93  4997.0  731.73  5010.8  730.31
  5011.3  729.51  5017.4  730.31  5019.5  733.34  5038.7  733.07  5050.6  734.59
  5068.7  733.97  5074.0  735.02  5115.0  735.54  5190.0  739.33  5263.7  740.91
  5566.7  741.33  5617.2  742.52  5758.6  741.40  6008.3  743.68  6797.6  745.99
#Mann=3,-1,0
  4113.3     0.1       0  5010.8    0.07       0  5017.4     0.1       0
Bank Sta=5010.8,5017.4
Exp/Cntr=0.3,0.1

Type RM Length L Ch R = 1,1554,0,0,0
BEGIN DESCRIPTION:
UNT 041 in HW 1.0
END DESCRIPTION:
XS GIS Cut Line= 4
      1990892.96     13630492.21      1990137.79     13630588.56
      1989564.87     13630723.98      1989765.25     13632371.24
#Sta/Elev= 30
  3738.3  743.56  3988.3  740.88  4381.4  739.75  4429.4  738.72  4452.0  733.96
  4462.1  734.83  4482.2  732.67  4492.3  737.23  4596.4  734.57  4605.2  729.97
  4638.7  727.49  4646.3  729.35  4666.9  729.29  4675.9  732.88  4681.0  731.86
  4687.4  734.05  4708.0  735.16  4765.6  733.34  4975.1  732.37  4987.3  731.63
  4992.4  726.98  4992.9  726.18  4999.0  726.98  5006.0  730.42  5029.6  735.75
  5270.7  740.21  5693.8  740.48  5724.0  742.26  5774.3  741.34  6747.7  745.00
#Mann=3,-1,0
  3738.3     0.1       0  4992.4    0.07       0  4999.0     0.1       0
Bank Sta=4992.4,4999
Exp/Cntr=0.3,0.1

Chan Stop Cuts=-1