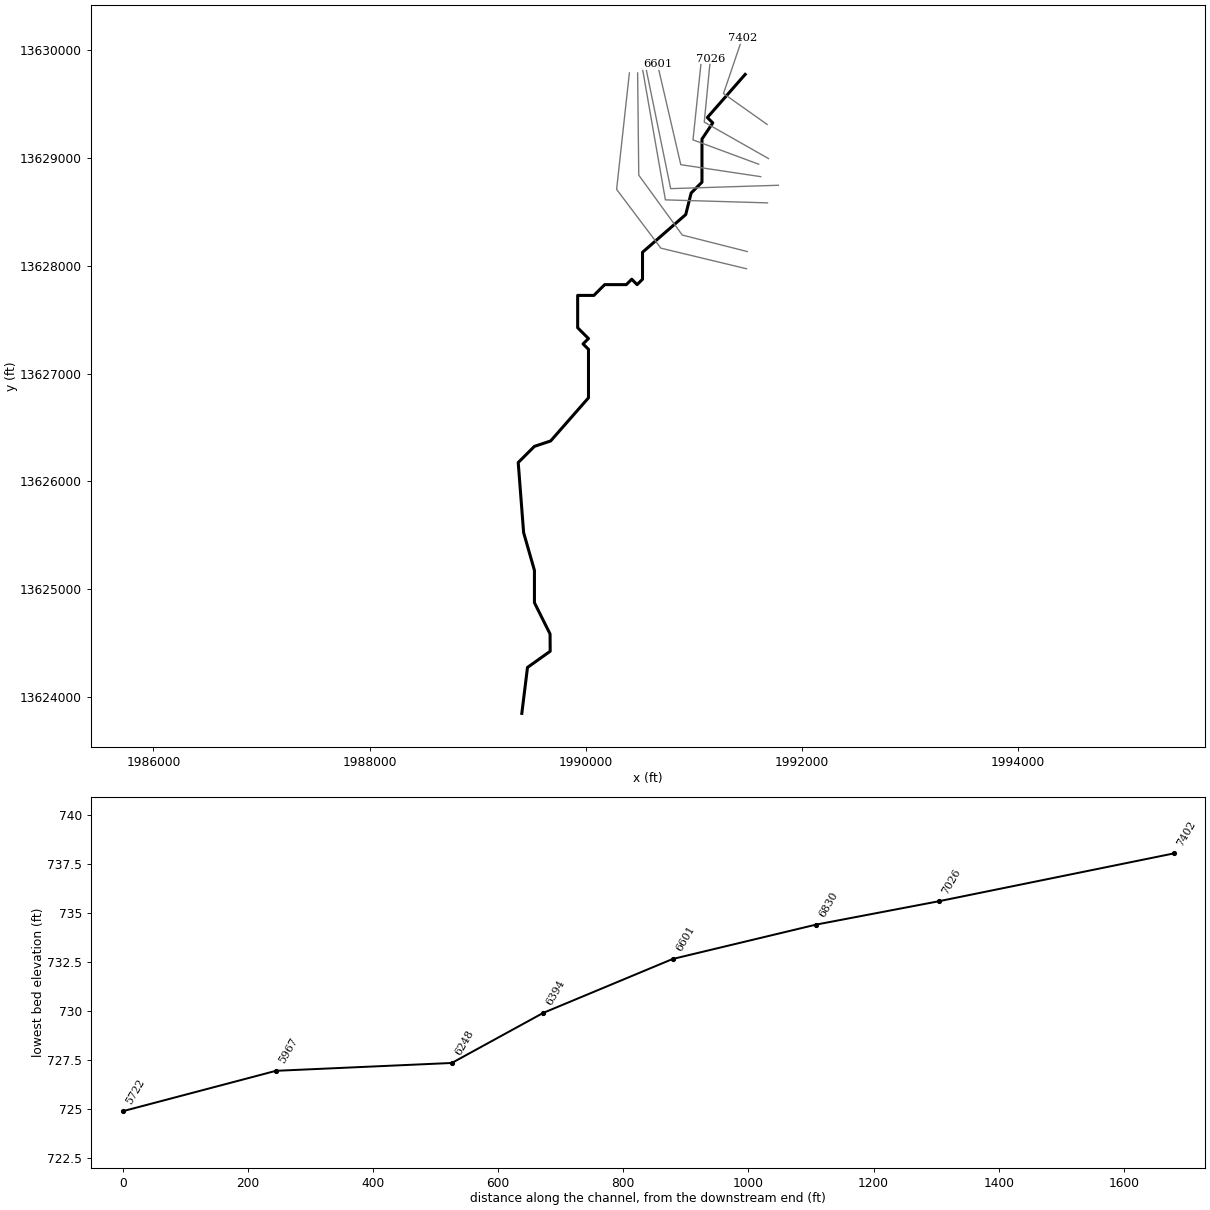
--- UNT 042 in HW.prj (project) ---

Proj Title=UNT 042 in HW Base Level Engineering
Current Plan=p01
Default Exp/Contr=0.3,0.1
English Units
Geom File=g01
Flow File=f01
Plan File=p01
BEGIN DESCRIPTION:
UNT 042 in HW
END DESCRIPTION:

--- UNT 042 in HW.p01 (plan) ---

Plan Title=Multiple Run
Short Identifier=Multiple
Geom File=g01
Flow File=f01
Subcritical Flow
K Sum by GR= 0
Std Step Tol= 0.01
Critical Tol= 0.01
Num of Std Step Trials= 20
Max Error Tol= 0.3
Flow Tol Ratio= 0.001
Split Flow NTrial= 30
Split Flow Tol= 0.02
Split Flow Ratio= 0.02
Log Output Level= 0
Friction Slope Method= 1
Unsteady Friction Slope Method= 2
Unsteady Bridges Friction Slope Method= 1
Parabolic Critical Depth
Global Vel Dist=  1 , 1 , 1
Global Log Level= 0
CheckData=True
Encroach Param= -1, 0, 0, 0
BEGIN DESCRIPTION:
Multiple Run
END DESCRIPTION:

--- UNT 042 in HW.f01 (steady flow) ---

Flow Title=Multiple
Number of Profiles=7
Profile Names=10-year,25-year,50-year,1pct_min,100-year,1pct_plu,500-year
River Rch & RM= UNT 042 in HW,Reach-1,7402
     624     887    1111     689    1374    2742    2112
Boundary for River Rch & Prof#=UNT 042 in HW,Reach-1,1
Up Type=0
Dn Type=3
Dn Slope=0.005
Boundary for River Rch & Prof#=UNT 042 in HW,Reach-1,2
Up Type=0
Dn Type=3
Dn Slope=0.005
Boundary for River Rch & Prof#=UNT 042 in HW,Reach-1,3
Up Type=0
Dn Type=3
Dn Slope=0.005
Boundary for River Rch & Prof#=UNT 042 in HW,Reach-1,4
Up Type=0
Dn Type=3
Dn Slope=0.005
Boundary for River Rch & Prof#=UNT 042 in HW,Reach-1,5
Up Type=0
Dn Type=3
Dn Slope=0.005
Boundary for River Rch & Prof#=UNT 042 in HW,Reach-1,6
Up Type=0
Dn Type=3
Dn Slope=0.005
Boundary for River Rch & Prof#=UNT 042 in HW,Reach-1,7
Up Type=0
Dn Type=3
Dn Slope=0.005

--- UNT 042 in HW.g01 (geometry) ---

Geom Title=Existing Conditions

River Reach=UNT 042 in HW,Reach-1
Reach XY= 30
      1991475.00     13629775.00      1991125.00     13629375.00
      1991175.00     13629325.00      1991075.00     13629175.00
      1991075.00     13628775.00      1990975.00     13628675.00
      1990925.00     13628475.00      1990525.00     13628125.00
      1990525.00     13627875.00      1990475.00     13627825.00
      1990425.00     13627875.00      1990375.00     13627825.00
      1990175.00     13627825.00      1990075.00     13627725.00
      1989925.00     13627725.00      1989925.00     13627425.00
      1990025.00     13627325.00      1989975.00     13627275.00
      1990025.00     13627225.00      1990025.00     13626775.00
      1989675.00     13626375.00      1989525.00     13626325.00
      1989375.00     13626175.00      1989425.00     13625525.00
      1989525.00     13625175.00      1989525.00     13624875.00
      1989669.60     13624584.80      1989670.80     13624424.54
      1989460.80     13624274.54      1989408.32     13623848.40

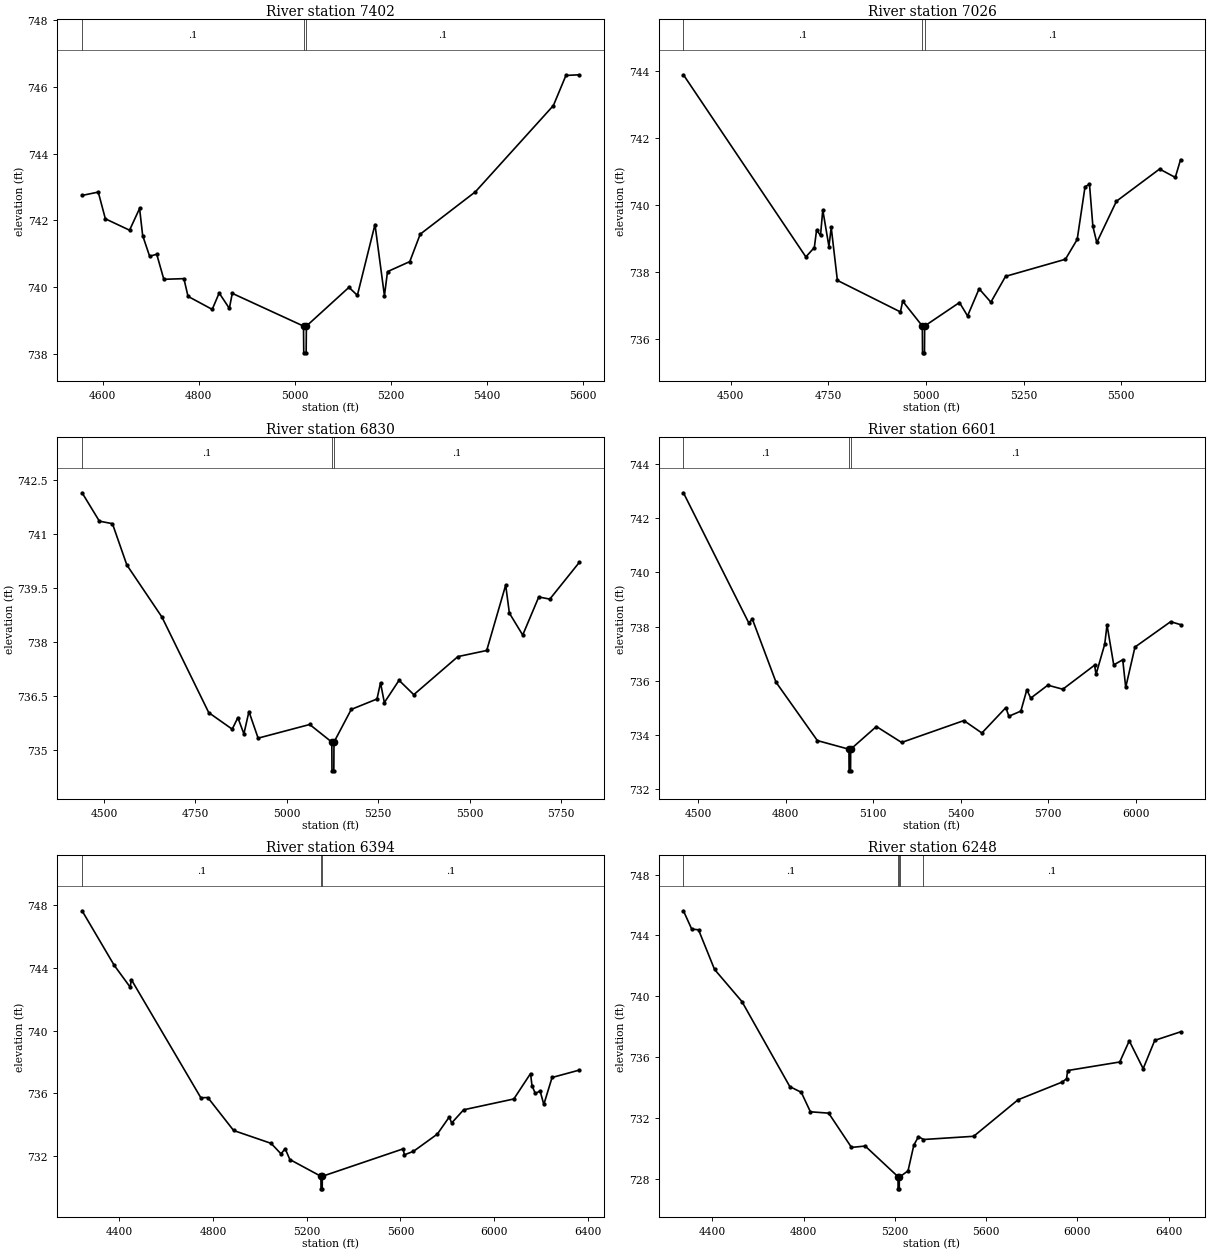
Type RM Length L Ch R = 1,7402,376,376,376
BEGIN DESCRIPTION:
UNT 042 in HW 3.0
END DESCRIPTION:
XS GIS Cut Line= 3
      1991677.88     13629310.78      1991274.23     13629597.24
      1991447.83     13630109.35
#Sta/Elev= 30
  4557.4  742.75  4591.1  742.85  4605.9  742.05  4656.3  741.71  4677.2  742.36
  4683.6  741.55  4698.1  740.93  4712.9  740.99  4727.7  740.24  4769.5  740.26
  4778.1  739.73  4828.5  739.34  4843.0  739.83  4864.2  739.37  4870.3  739.82
  5018.7  738.84  5019.2  738.04  5024.2  738.04  5024.7  738.84  5113.4  740.00
  5130.9  739.76  5167.6  741.88  5187.3  739.75  5193.7  740.47  5240.1  740.77
  5261.8  741.59  5376.9  742.86  5539.3  745.44  5565.4  746.34  5593.1  746.36
#Mann=3,-1,0
  4557.4     0.1       0  5018.7    0.07       0  5024.7     0.1       0
Bank Sta=5018.7,5024.7
Exp/Cntr=0.3,0.1

Type RM Length L Ch R = 1,7026,196,196,196
BEGIN DESCRIPTION:
UNT 042 in HW 2.0
END DESCRIPTION:
XS GIS Cut Line= 3
      1991690.87     13628993.95      1991096.28     13629332.48
      1991152.71     13629918.46
#Sta/Elev= 30
  4379.0  743.89  4692.5  738.46  4714.2  738.74  4719.9  739.26  4730.0  739.10
  4735.8  739.86  4751.6  738.77  4757.4  739.34  4773.2  737.76  4934.6  736.82
  4940.4  737.14  4990.7  736.40  4991.2  735.60  4996.2  735.60  4996.7  736.40
  5085.8  737.10  5106.5  736.70  5136.1  737.51  5166.2  737.11  5203.8  737.88
  5357.1  738.39  5387.2  738.98  5407.3  740.55  5418.7  740.63  5427.4  739.37
  5437.4  738.89  5487.7  740.12  5598.2  741.08  5638.4  740.83  5651.9  741.36
#Mann=3,-1,0
  4379.0     0.1       0  4990.7    0.07       0  4996.7     0.1       0
Bank Sta=4990.7,4996.7
Exp/Cntr=0.3,0.1

Type RM Length L Ch R = 1,6830,229,229,229
BEGIN DESCRIPTION:
UNT 042 in HW 1.0
END DESCRIPTION:
XS GIS Cut Line= 3
      1991599.77     13628941.85      1990992.12     13629167.55
      1991065.90     13629874.99
#Sta/Elev= 30
  4440.2  742.15  4487.5  741.36  4523.2  741.29  4562.6  740.14  4658.6  738.69
  4786.6  736.03  4850.7  735.57  4866.2  735.89  4882.7  735.44  4896.5  736.06
  4921.6  735.32  5062.7  735.70  5123.1  735.21  5123.6  734.41  5128.6  734.41
  5129.1  735.21  5176.3  736.12  5246.7  736.41  5256.3  736.86  5266.8  736.31
  5307.0  736.93  5347.3  736.53  5467.9  737.59  5546.7  737.76  5598.6  739.58
  5608.7  738.80  5645.2  738.19  5689.1  739.25  5719.3  739.19  5799.7  740.21
#Mann=3,-1,0
  4440.2     0.1       0  5123.1    0.07       0  5129.1     0.1       0
Bank Sta=5123.1,5129.1
Exp/Cntr=0.3,0.1

Type RM Length L Ch R = 1,6601,207,207,207
BEGIN DESCRIPTION:
Mapping XS d1925485
END DESCRIPTION:
XS GIS Cut Line= 3
      1991618.70     13628826.41      1990879.10     13628937.52
      1990663.83     13629868.05
#Sta/Elev= 30
  4450.2  742.95  4673.8  738.14  4686.5  738.27  4767.4  735.94  4909.0  733.78
  5017.2  733.46  5017.7  732.66  5022.7  732.66  5023.2  733.46  5111.2  734.30
  5197.6  733.71  5410.9  734.52  5472.6  734.06  5554.8  735.00  5565.0  734.68
  5606.1  734.87  5626.6  735.66  5639.9  735.35  5698.5  735.83  5749.8  735.68
  5858.6  736.57  5863.7  736.23  5893.5  737.35  5901.3  738.06  5924.3  736.58
  5955.1  736.77  5965.3  735.75  5997.0  737.24  6119.3  738.18  6153.2  738.07
#Mann=3,-1,0
  4450.2     0.1       0  5017.2    0.07       0  5023.2     0.1       0
Bank Sta=5017.2,5023.2
Exp/Cntr=0.3,0.1

Type RM Length L Ch R = 1,6394,146,146,146
BEGIN DESCRIPTION:
Mapping XS 82d6be23
END DESCRIPTION:
XS GIS Cut Line= 3
      1991781.87     13628746.55      1990785.35     13628715.30
      1990559.82     13629818.68
#Sta/Elev= 30
  4240.5  747.64  4377.4  744.17  4445.9  742.77  4450.9  743.25  4747.6  735.72
  4777.6  735.73  4887.7  733.63  5047.8  732.81  5090.1  732.14  5107.8  732.47
  5127.8  731.78  5260.5  730.71  5261.0  729.91  5266.0  729.91  5266.5  730.71
  5611.8  732.46  5616.9  732.08  5655.7  732.30  5757.7  733.40  5808.6  734.49
  5819.0  734.11  5870.0  734.95  6084.4  735.64  6155.8  737.26  6162.0  736.49
  6176.2  735.99  6196.6  736.15  6212.5  735.29  6247.7  737.01  6363.7  737.48
#Mann=3,-1,0
  4240.5     0.1       0  5260.5    0.07       0  5266.5     0.1       0
Bank Sta=5260.5,5266.5
Exp/Cntr=0.3,0.1

Type RM Length L Ch R = 1,6248,281,281,281
BEGIN DESCRIPTION:
Mapping XS 88641496
END DESCRIPTION:
XS GIS Cut Line= 3
      1991681.20     13628583.35      1990736.74     13628611.13
      1990524.93     13629826.44
#Sta/Elev= 30
  4273.2  745.62  4309.4  744.42  4339.4  744.37  4409.5  741.77  4529.5  739.66
  4739.6  734.07  4789.6  733.70  4829.6  732.42  4909.7  732.33  5009.7  730.08
  5069.7  730.17  5213.4  728.16  5213.9  727.36  5218.9  727.36  5219.4  728.16
  5222.4  728.16  5257.4  728.54  5282.9  730.23  5303.2  730.79  5325.2  730.60
  5545.1  730.81  5739.7  733.21  5932.6  734.37  5952.0  734.59  5957.1  735.13
  6185.2  735.69  6226.9  737.08  6287.8  735.25  6338.6  737.11  6451.7  737.67
#Mann=5,-1,0
  4273.2     0.1       0  5213.4    0.07       0  5219.4     0.1       0
  5222.4    0.05       0  5325.2     0.1       0
Bank Sta=5213.4,5219.4
Exp/Cntr=0.3,0.1

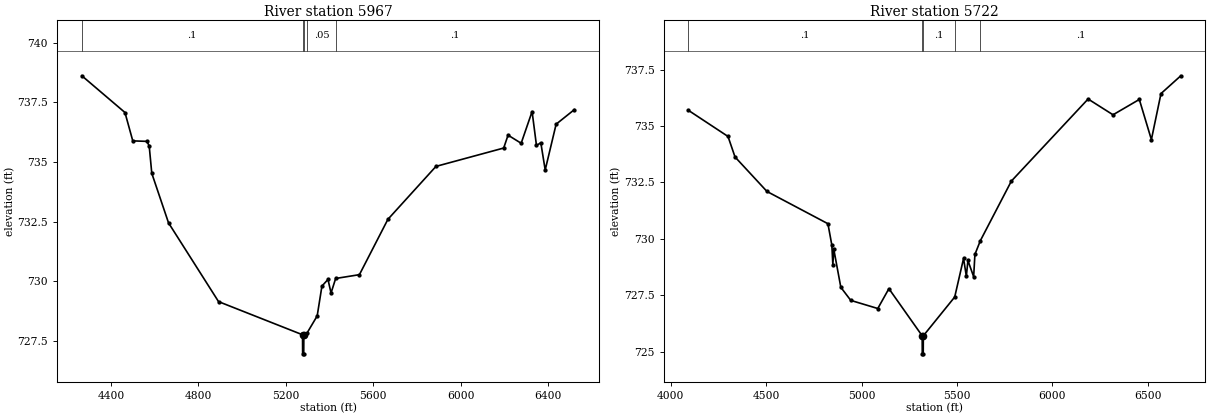
Type RM Length L Ch R = 1,5967,245,245,245
BEGIN DESCRIPTION:
Mapping XS 478472db
END DESCRIPTION:
XS GIS Cut Line= 4
      1991493.66     13628131.97      1990892.99     13628284.74
      1990490.22     13628840.30      1990479.80     13629788.25
#Sta/Elev= 30
  4266.9  738.62  4464.2  737.08  4500.0  735.89  4564.7  735.87  4575.1  735.68
  4587.0  734.53  4663.7  732.45  4892.5  729.15  5276.9  727.76  5277.4  726.96
  5282.4  726.96  5282.9  727.76  5298.7  727.85  5344.0  728.55  5365.7  729.80
  5393.4  730.08  5407.4  729.51  5428.5  730.12  5537.3  730.28  5667.6  732.60
  5887.6  734.82  6197.6  735.59  6217.6  736.13  6277.6  735.79  6327.6  737.12
  6347.6  735.70  6367.6  735.81  6387.6  734.67  6437.6  736.59  6520.9  737.20
#Mann=5,-1,0
  4266.9     0.1       0  5276.9    0.07       0  5282.9     0.1       0
  5298.7    0.05       0  5428.5     0.1       0
Bank Sta=5276.9,5282.9
Exp/Cntr=0.3,0.1

Type RM Length L Ch R = 1,5722,0,0,0
BEGIN DESCRIPTION:
UNT 042 in HW 4.0
END DESCRIPTION:
XS GIS Cut Line= 4
      1991486.69     13627972.25      1990695.08     13628163.21
      1990285.35     13628708.35      1990403.41     13629788.25
#Sta/Elev= 30
  4091.5  735.70  4299.6  734.54  4336.4  733.63  4504.0  732.10  4823.6  730.67
  4844.2  729.72  4849.4  728.86  4854.5  729.53  4891.3  727.85  4943.4  727.27
  5085.1  726.91  5143.4  727.79  5317.9  725.70  5318.4  724.90  5323.4  724.90
  5323.9  725.70  5488.5  727.42  5534.9  729.13  5549.5  728.34  5557.8  729.04
  5587.8  728.32  5594.5  729.31  5623.1  729.92  5785.6  732.56  6188.0  736.20
  6318.7  735.50  6456.6  736.18  6519.9  734.40  6570.2  736.44  6674.1  737.23
#Mann=5,-1,0
  4091.5     0.1       0  5317.9    0.07       0  5323.9     0.1       0
  5488.5    0.05       0  5623.1     0.1       0
Bank Sta=5317.9,5323.9
Exp/Cntr=0.3,0.1

Chan Stop Cuts=-1