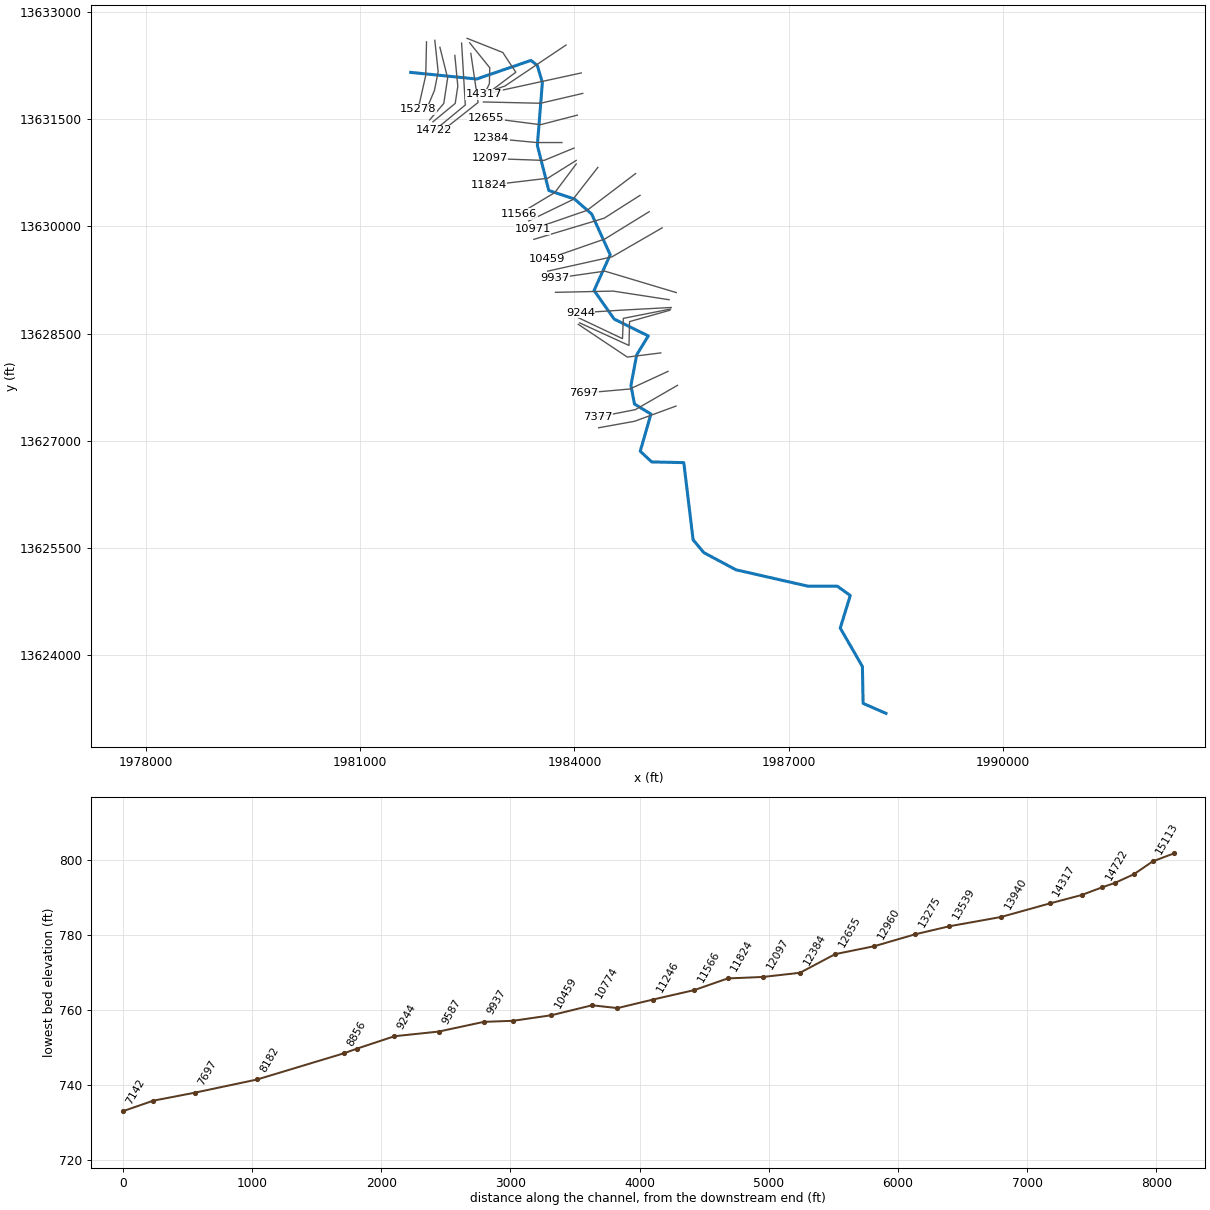
--- UNT 043 in HW.prj (project) ---

Proj Title=UNT 043 in HW Base Level Engineering
Current Plan=p01
Default Exp/Contr=0.3,0.1
English Units
Geom File=g01
Flow File=f01
Plan File=p01
Y Axis Title=Elevation
X Axis Title(PF)=Main Channel Distance
X Axis Title(XS)=Station
BEGIN DESCRIPTION:
UNT 043 in HW
END DESCRIPTION:
DSS Export Rating Curves= 0
DSS Export Rating Curve Sorted= 0
DSS Export Volume Flow Curves= 0
DXF OffsetX= 0
DXF OffsetY= 0
DXF ScaleX= 1
DXF ScaleY= 10

--- UNT 043 in HW.p01 (plan) ---

Plan Title=Multiple Run
Short Identifier=Multiple
Geom File=g01
Flow File=f01
Subcritical Flow
K Sum by GR= 0
Std Step Tol= 0.01
Critical Tol= 0.01
Num of Std Step Trials= 20
Max Error Tol= 0.3
Flow Tol Ratio= 0.001
Split Flow NTrial= 30
Split Flow Tol= 0.02
Split Flow Ratio= 0.02
Log Output Level= 0
Friction Slope Method= 1
Unsteady Friction Slope Method= 2
Unsteady Bridges Friction Slope Method= 1
Parabolic Critical Depth
Global Vel Dist=  1 , 1 , 1
Global Log Level= 0
CheckData=True
Encroach Param= -1, 0, 0, 0
BEGIN DESCRIPTION:
Multiple Run
END DESCRIPTION:

--- UNT 043 in HW.f01 (steady flow) ---

Flow Title=Multiple
Program Version=5.05
Number of Profiles= 7
Profile Names=10-year,25-year,50-year,1pct_min,100-year,1pct_plu,500-year
River Rch & RM=UNT 043 in HW,Reach-1         ,15278
     388     536     658     401     799    1595    1184
River Rch & RM=UNT 043 in HW,Reach-1         ,13539
     699     999    1253     779    1554    3101    2398
River Rch & RM=UNT 043 in HW,Reach-1         ,7697
    1052    1534    1952    1228    2449    4887    3874
River Rch & RM=UNT 043 in HW,Reach-1         ,2848
    1224    1798    2297    1450    2894    5774    4614
River Rch & RM=UNT 043 in HW,Reach-1         ,2427
    1224    1798    2297    1450    2894    5774    4614
Boundary for River Rch & Prof#=UNT 043 in HW,Reach-1         , 1
Up Type= 0
Dn Type= 3
Dn Slope=0.005
Boundary for River Rch & Prof#=UNT 043 in HW,Reach-1         , 2
Up Type= 0
Dn Type= 3
Dn Slope=0.005
Boundary for River Rch & Prof#=UNT 043 in HW,Reach-1         , 3
Up Type= 0
Dn Type= 3
Dn Slope=0.005
Boundary for River Rch & Prof#=UNT 043 in HW,Reach-1         , 4
Up Type= 0
Dn Type= 3
Dn Slope=0.005
Boundary for River Rch & Prof#=UNT 043 in HW,Reach-1         , 5
Up Type= 0
Dn Type= 3
Dn Slope=0.005
Boundary for River Rch & Prof#=UNT 043 in HW,Reach-1         , 6
Up Type= 0
Dn Type= 3
Dn Slope=0.005
Boundary for River Rch & Prof#=UNT 043 in HW,Reach-1         , 7
Up Type= 0
Dn Type= 3
Dn Slope=0.005
DSS Import GetInterval= 0
DSS Import GetPeak= 0
DSS Import FillOption= 0

--- UNT 043 in HW.g01 (geometry) ---

Geom Title=Existing Conditions

River Reach=UNT 043 in HW,Reach-1
Reach XY= 30
      1981708.38     13632156.96      1982630.80     13632064.54
      1983390.80     13632324.54      1983480.80     13632254.54
      1983550.80     13632014.54      1983480.80     13631134.54
      1983640.80     13630504.54      1984000.80     13630384.54
      1984240.80     13630174.54      1984500.80     13629604.54
      1984274.63     13629104.62      1984556.71     13628703.33
      1985033.79     13628467.91      1984871.29     13628203.33
      1984790.80     13627774.54      1984840.80     13627514.54
      1985070.80     13627374.54      1984920.80     13626854.54
      1985080.80     13626704.54      1985530.80     13626694.54
      1985660.80     13625614.54      1985810.80     13625434.54
      1986260.80     13625194.54      1987270.80     13624964.54
      1987680.80     13624964.54      1987860.80     13624834.54
      1987720.80     13624378.53      1988030.93     13623840.34
      1988040.80     13623324.54      1988360.80     13623184.54

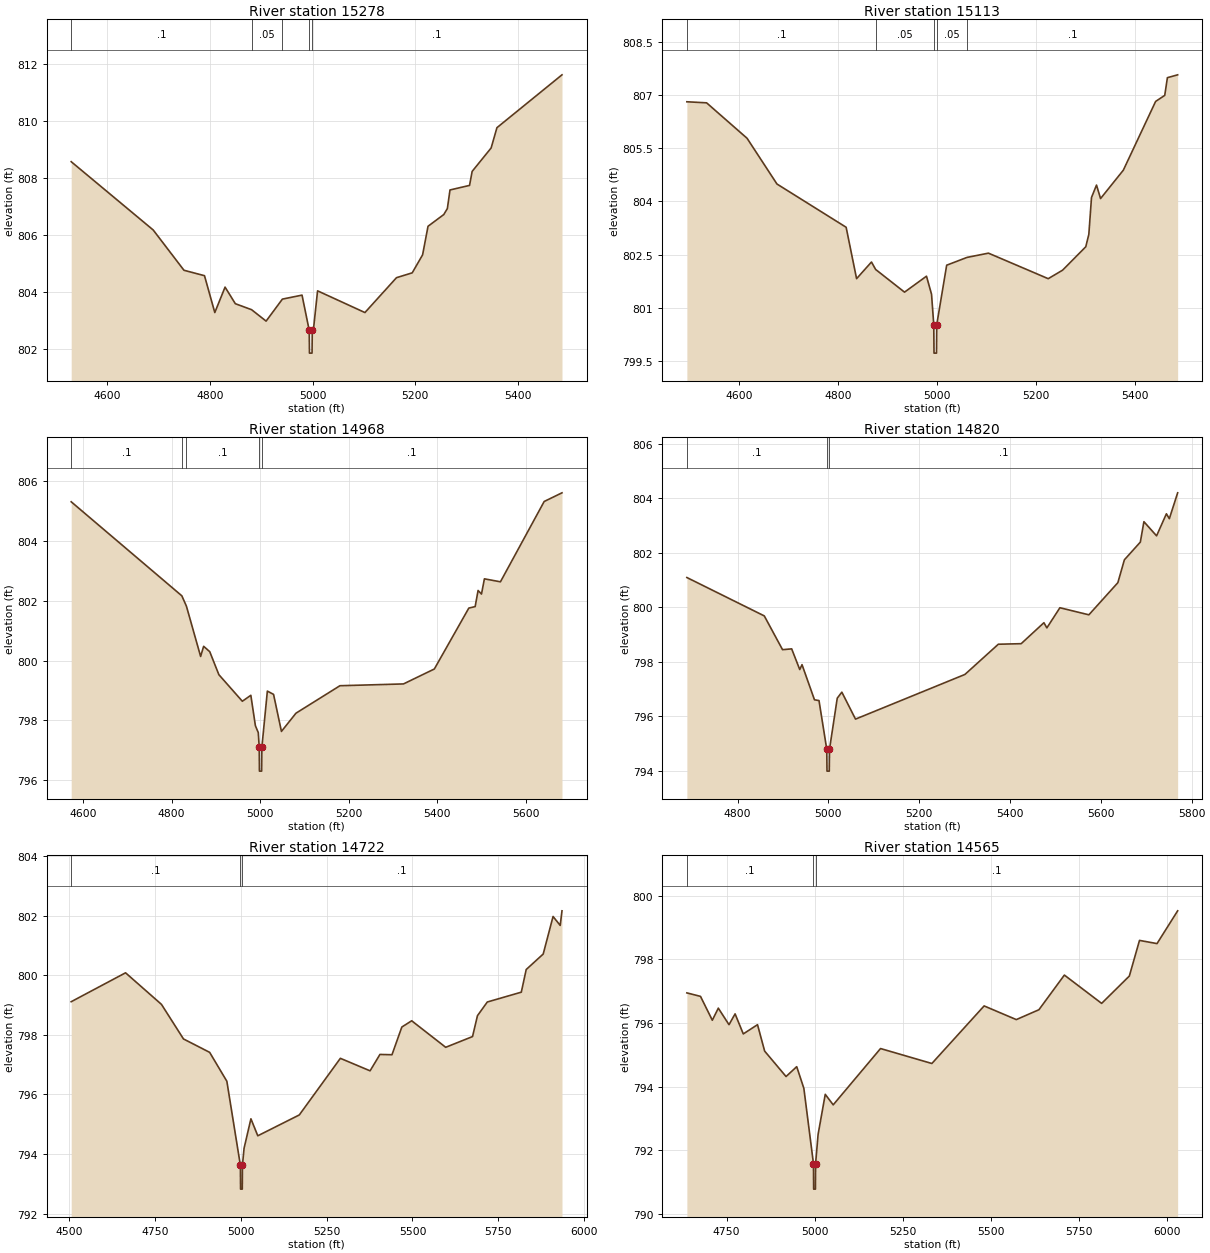
Type RM Length L Ch R = 1,15278,165,165,165
BEGIN DESCRIPTION:
UNT 043 in HW 32.0
END DESCRIPTION:
XS GIS Cut Line= 3
      1981929.17     13632584.78      1981918.75     13632116.04
      1981811.11     13631640.33
#Sta/Elev= 30
  4529.6  808.57  4689.4  806.18  4749.4  804.77  4789.4  804.58  4809.5  803.29
  4829.5  804.18  4849.5  803.60  4881.2  803.39  4909.5  802.99  4941.2  803.76
  4979.5  803.90  4993.5  802.67  4994.0  801.87  4999.0  801.87  4999.5  802.67
  5001.6  802.67  5009.8  804.05  5102.1  803.29  5163.6  804.51  5194.3  804.68
  5214.5  805.31  5225.1  806.31  5255.8  806.72  5262.8  806.93  5267.9  807.58
  5306.0  807.74  5311.1  808.23  5348.1  809.05  5359.4  809.76  5486.2  811.61
#Mann=5,-1,0
  4529.6     0.1       0  4881.2    0.05       0  4941.2     0.1       0
  4993.5    0.07       0  4999.5     0.1       0
Bank Sta=4993.5,4999.5
Exp/Cntr=0.3,0.1

Type RM Length L Ch R = 1,15113,145,145,145
BEGIN DESCRIPTION:
Mapping XS 3ca28b15
END DESCRIPTION:
XS GIS Cut Line= 4
      1982045.36     13632606.02      1982092.24     13632167.21
      1982040.16     13631904.18      1981930.78     13631643.76
#Sta/Elev= 30
  4494.8  806.81  4534.7  806.78  4616.5  805.78  4676.9  804.49  4816.7  803.27
  4837.8  801.82  4867.9  802.29  4876.3  802.08  4934.7  801.44  4979.1  801.89
  4989.3  801.38  4993.8  800.52  4994.3  799.72  4999.3  799.72  4999.8  800.52
  5019.9  802.20  5061.0  802.42  5104.3  802.54  5225.1  801.82  5254.2  802.06
  5301.0  802.72  5307.2  803.07  5312.6  804.11  5322.7  804.46  5330.9  804.08
  5376.9  804.88  5442.2  806.82  5460.6  806.99  5466.0  807.49  5486.7  807.57
#Mann=5,-1,0
  4494.8     0.1       0  4876.3    0.05       0  4993.8   0.035       0
  4999.8    0.05       0  5061.0     0.1       0
Bank Sta=4993.8,4999.8
Exp/Cntr=0.3,0.1

Type RM Length L Ch R = 1,14968,148,148,148
BEGIN DESCRIPTION:
UNT 043 in HW 31.0
END DESCRIPTION:
XS GIS Cut Line= 4
      1982116.66     13632508.45      1982225.00     13632077.60
      1982170.77     13631722.10      1981972.46     13631491.00
#Sta/Elev= 30
  4573.2  805.32  4823.1  802.17  4833.5  801.82  4865.5  800.14  4872.3  800.48
  4886.1  800.30  4906.7  799.53  4959.7  798.64  4978.9  798.84  4989.2  797.82
  4995.7  797.59  4997.8  797.10  4998.3  796.30  5003.3  796.30  5003.8  797.10
  5016.2  798.98  5030.2  798.87  5048.0  797.63  5080.8  798.24  5180.1  799.16
  5323.6  799.22  5393.3  799.72  5471.2  801.76  5485.5  801.81  5492.1  802.35
  5499.8  802.23  5506.4  802.74  5542.6  802.64  5641.4  805.33  5681.6  805.62
#Mann=5,-1,0
  4573.2     0.1       0  4823.1    0.05       0  4833.5     0.1       0
  4997.8    0.07       0  5003.8     0.1       0
Bank Sta=4997.8,5003.8
Exp/Cntr=0.3,0.1

Type RM Length L Ch R = 1,14820,98,98,98
BEGIN DESCRIPTION:
Mapping XS c0220f10
END DESCRIPTION:
XS GIS Cut Line= 4
      1982325.74     13632394.68      1982367.41     13631964.95
      1982330.96     13631722.76      1982019.22     13631465.58
#Sta/Elev= 30
  4688.4  801.09  4858.9  799.68  4899.1  798.44  4919.2  798.47  4937.0  797.71
  4942.0  797.89  4969.4  796.60  4979.4  796.57  4996.5  794.78  4997.0  793.98
  5002.0  793.98  5002.5  794.78  5019.6  796.66  5029.7  796.88  5059.8  795.89
  5300.7  797.53  5374.3  798.64  5424.6  798.66  5474.7  799.43  5481.2  799.24
  5509.9  799.98  5573.7  799.72  5637.5  800.90  5651.9  801.74  5687.0  802.39
  5694.9  803.14  5722.8  802.62  5744.4  803.43  5750.9  803.25  5769.2  804.20
#Mann=3,-1,0
  4688.4     0.1       0  4996.5    0.07       0  5002.5     0.1       0
Bank Sta=4996.5,5002.5
Exp/Cntr=0.3,0.1

Type RM Length L Ch R = 1,14722,157,157,157
BEGIN DESCRIPTION:
Mapping XS a1bd92af
END DESCRIPTION:
XS GIS Cut Line= 3
      1982420.49     13632567.45      1982472.45     13631701.06
      1982039.23     13631344.08
#Sta/Elev= 30
  4506.2  799.11  4664.5  800.08  4769.1  799.02  4833.2  797.86  4909.4  797.41
  4959.5  796.44  4998.9  793.62  4999.4  792.82  5004.4  792.82  5004.9  793.62
  5009.6  794.19  5029.6  795.18  5049.6  794.61  5170.5  795.31  5290.1  797.21
  5376.6  796.79  5405.3  797.34  5440.4  797.33  5469.1  798.26  5497.8  798.47
  5596.8  797.58  5675.0  797.94  5689.3  798.64  5718.0  799.10  5817.0  799.43
  5831.3  800.19  5880.8  800.71  5909.5  801.97  5930.3  801.67  5935.5  802.16
#Mann=3,-1,0
  4506.2     0.1       0  4998.9    0.07       0  5004.9     0.1       0
Bank Sta=4998.9,5004.9
Exp/Cntr=0.3,0.1

Type RM Length L Ch R = 1,14565,248,248,248
BEGIN DESCRIPTION:
Mapping XS 709721d9
END DESCRIPTION:
XS GIS Cut Line= 3
      1982549.71     13632423.24      1982651.27     13631735.78
      1982104.41     13631303.50
#Sta/Elev= 30
  4637.4  796.95  4676.1  796.84  4709.6  796.09  4726.6  796.47  4756.9  795.95
  4774.2  796.29  4797.4  795.66  4837.8  795.95  4858.0  795.12  4918.7  794.32
  4949.0  794.63  4969.2  793.95  4996.5  791.58  4997.0  790.78  5002.0  790.78
  5002.5  791.58  5009.6  792.50  5029.9  793.76  5052.5  793.43  5186.7  795.20
  5332.3  794.73  5480.5  796.54  5571.8  796.11  5635.9  796.42  5708.1  797.51
  5813.8  796.62  5892.4  797.48  5921.2  798.60  5970.9  798.50  6029.4  799.53
#Mann=3,-1,0
  4637.4     0.1       0  4996.5    0.07       0  5002.5     0.1       0
Bank Sta=4996.5,5002.5
Exp/Cntr=0.3,0.1

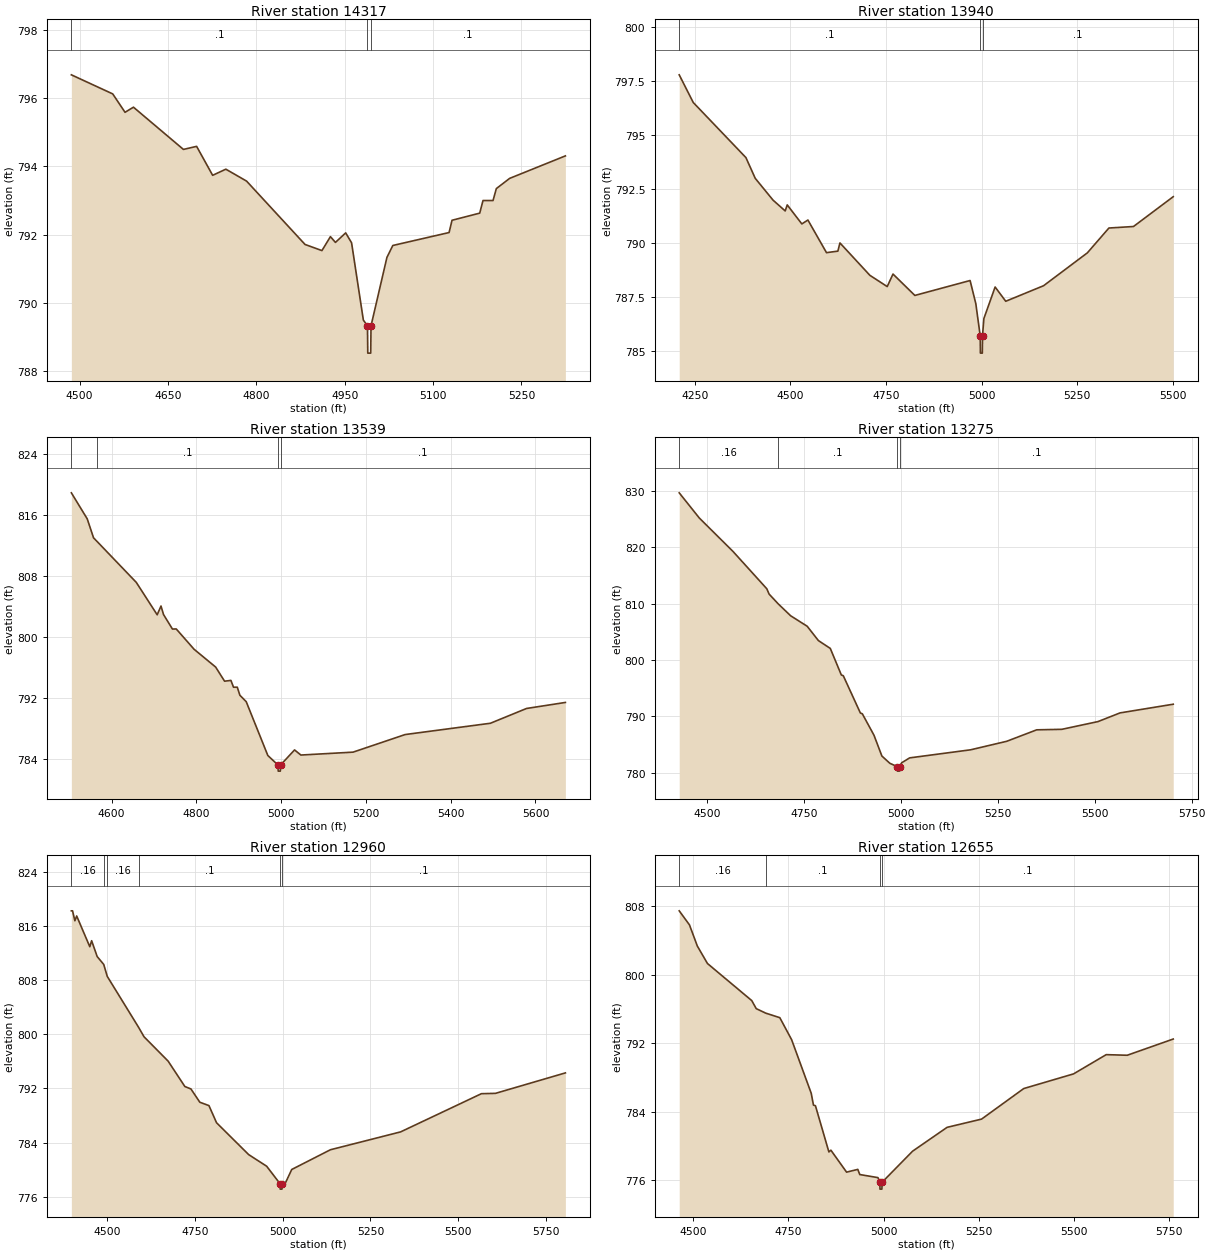
Type RM Length L Ch R = 1,14317,377,377,377
BEGIN DESCRIPTION:
Mapping XS 32008f9f
END DESCRIPTION:
XS GIS Cut Line= 4
      1982533.23     13632571.36      1982814.50     13632222.38
      1982809.29     13631998.42      1982737.00     13631848.69
#Sta/Elev= 30
  4486.1  796.69  4556.3  796.13  4577.2  795.59  4591.5  795.74  4676.3  794.50
  4698.7  794.59  4725.9  793.74  4748.3  793.92  4783.5  793.57  4882.7  791.71
  4911.4  791.53  4925.8  791.94  4934.3  791.77  4951.7  792.05  4961.7  791.76
  4981.7  789.49  4988.7  789.32  4989.2  788.52  4994.2  788.52  4994.7  789.32
  5021.7  791.33  5031.7  791.68  5127.2  792.06  5132.2  792.42  5179.2  792.63
  5184.8  793.00  5201.8  793.00  5207.4  793.35  5230.0  793.65  5324.6  794.31
#Mann=3,-1,0
  4486.1     0.1       0  4988.7    0.07       0  4994.7     0.1       0
Bank Sta=4988.7,4994.7
Exp/Cntr=0.3,0.1

Type RM Length L Ch R = 1,13940,401,401,401
BEGIN DESCRIPTION:
Mapping XS f8991a2d
END DESCRIPTION:
XS GIS Cut Line= 4
      1982496.76     13632633.85      1982996.79     13632435.92
      1983179.08     13632159.88      1982840.57     13631904.70
#Sta/Elev= 30
  4208.9  797.79  4245.6  796.51  4383.4  793.96  4407.8  793.00  4454.4  791.99
  4486.2  791.49  4491.5  791.77  4529.7  790.89  4545.6  791.07  4594.2  789.56
  4624.0  789.63  4629.4  790.01  4707.8  788.51  4753.1  787.99  4768.2  788.57
  4825.4  787.58  4969.9  788.27  4984.9  787.20  4996.4  785.71  4996.9  784.91
  5001.9  784.91  5002.4  785.71  5006.0  786.51  5035.4  787.97  5063.2  787.31
  5162.2  788.03  5276.7  789.55  5333.1  790.70  5397.4  790.77  5501.4  792.15
#Mann=3,-1,0
  4208.9     0.1       0  4996.4    0.07       0  5002.4     0.1       0
Bank Sta=4996.4,5002.4
Exp/Cntr=0.3,0.1

Type RM Length L Ch R = 1,13539,264,264,264
BEGIN DESCRIPTION:
Mapping XS d33ad29c
END DESCRIPTION:
XS GIS Cut Line= 3
      1983882.21     13632540.09      1983028.04     13631967.17
      1982898.96     13631920.71
#Sta/Elev= 30
  4504.9  818.94  4542.3  815.53  4557.3  813.03  4564.5  812.62  4658.1  807.19
  4707.4  802.94  4716.4  804.09  4722.4  802.97  4743.4  801.07  4752.4  801.08
  4794.4  798.42  4845.4  796.08  4866.4  794.23  4881.4  794.33  4887.5  793.44
  4896.4  793.44  4902.5  792.39  4917.5  791.54  4968.5  784.48  4992.5  783.23
  4993.0  782.43  4998.0  782.43  4998.5  783.23  5031.5  785.21  5046.5  784.54
  5169.6  784.92  5292.6  787.23  5493.7  788.71  5579.0  790.65  5670.6  791.44
#Mann=4,-1,0
  4504.9    0.16       0  4564.5     0.1       0  4992.5    0.07       0
  4998.5     0.1       0
Bank Sta=4992.5,4998.5
Exp/Cntr=0.3,0.1

Type RM Length L Ch R = 1,13275,315,315,315
BEGIN DESCRIPTION:
Mapping XS f3e10941
END DESCRIPTION:
XS GIS Cut Line= 2
      1984095.70     13632149.45      1982850.92     13631878.62
#Sta/Elev= 30
  4428.6  829.62  4480.5  825.15  4567.3  819.23  4654.5  812.61  4660.4  811.67
  4683.7  809.95  4715.9  807.83  4758.6  805.97  4787.5  803.43  4818.2  802.04
  4846.6  797.34  4851.7  797.20  4895.7  790.60  4900.8  790.45  4930.8  786.66
  4951.2  782.97  4971.7  781.68  4990.9  781.09  4991.4  780.29  4996.4  780.29
  4996.9  781.09  5002.4  781.78  5022.9  782.64  5180.1  784.07  5273.2  785.58
  5350.4  787.61  5415.3  787.70  5508.4  789.07  5565.3  790.61  5702.5  792.15
#Mann=4,-1,0
  4428.6    0.16       0  4683.7     0.1       0  4990.9    0.07       0
  4996.9     0.1       0
Bank Sta=4990.9,4996.9
Exp/Cntr=0.3,0.1

Type RM Length L Ch R = 1,12960,305,305,305
BEGIN DESCRIPTION:
UNT 043 in HW 30.0
END DESCRIPTION:
XS GIS Cut Line= 3
      1984116.57     13631863.00      1983525.00     13631725.00
      1982725.96     13631743.21
#Sta/Elev= 30
  4398.5  818.22  4401.9  818.22  4408.5  816.75  4413.6  817.46  4451.0  812.92
  4456.2  813.81  4472.0  811.47  4490.7  810.30  4500.7  808.54  4589.7  801.04
  4605.5  799.62  4674.0  796.03  4721.7  792.28  4739.0  791.92  4764.3  789.96
  4790.3  789.46  4811.9  786.93  4903.3  782.23  4954.6  780.51  4992.7  777.93
  4993.2  777.13  4998.2  777.13  4998.7  777.93  5008.5  778.10  5026.0  780.03
  5136.0  782.94  5336.0  785.58  5566.1  791.22  5606.1  791.27  5805.2  794.29
#Mann=6,-1,0
  4398.5    0.16       0  4490.7     0.1       0  4500.7    0.16       0
  4589.7     0.1       0  4992.7    0.07       0  4998.7     0.1       0
Bank Sta=4992.7,4998.7
Exp/Cntr=0.3,0.1

Type RM Length L Ch R = 1,12655,271,271,271
BEGIN DESCRIPTION:
UNT 043 in HW 29.0
END DESCRIPTION:
XS GIS Cut Line= 3
      1984041.09     13631558.85      1983525.00     13631425.00
      1982764.98     13631522.39
#Sta/Elev= 30
  4462.6  807.42  4489.6  805.78  4510.2  803.32  4536.9  801.28  4653.4  796.96
  4665.2  796.02  4690.0  795.50  4727.2  794.97  4758.2  792.41  4809.8  786.16
  4815.7  784.78  4820.9  784.71  4856.3  779.32  4861.5  779.53  4902.8  776.97
  4932.3  777.29  4937.5  776.69  4985.4  776.33  4990.2  775.79  4990.7  774.99
  4995.7  774.99  4996.2  775.79  5076.4  779.41  5167.2  782.19  5257.9  783.15
  5368.8  786.71  5499.9  788.42  5585.7  790.66  5641.0  790.59  5762.0  792.48
#Mann=4,-1,0
  4462.6    0.16       0  4690.0     0.1       0  4990.2    0.07       0
  4996.2     0.1       0
Bank Sta=4990.2,4996.2
Exp/Cntr=0.3,0.1

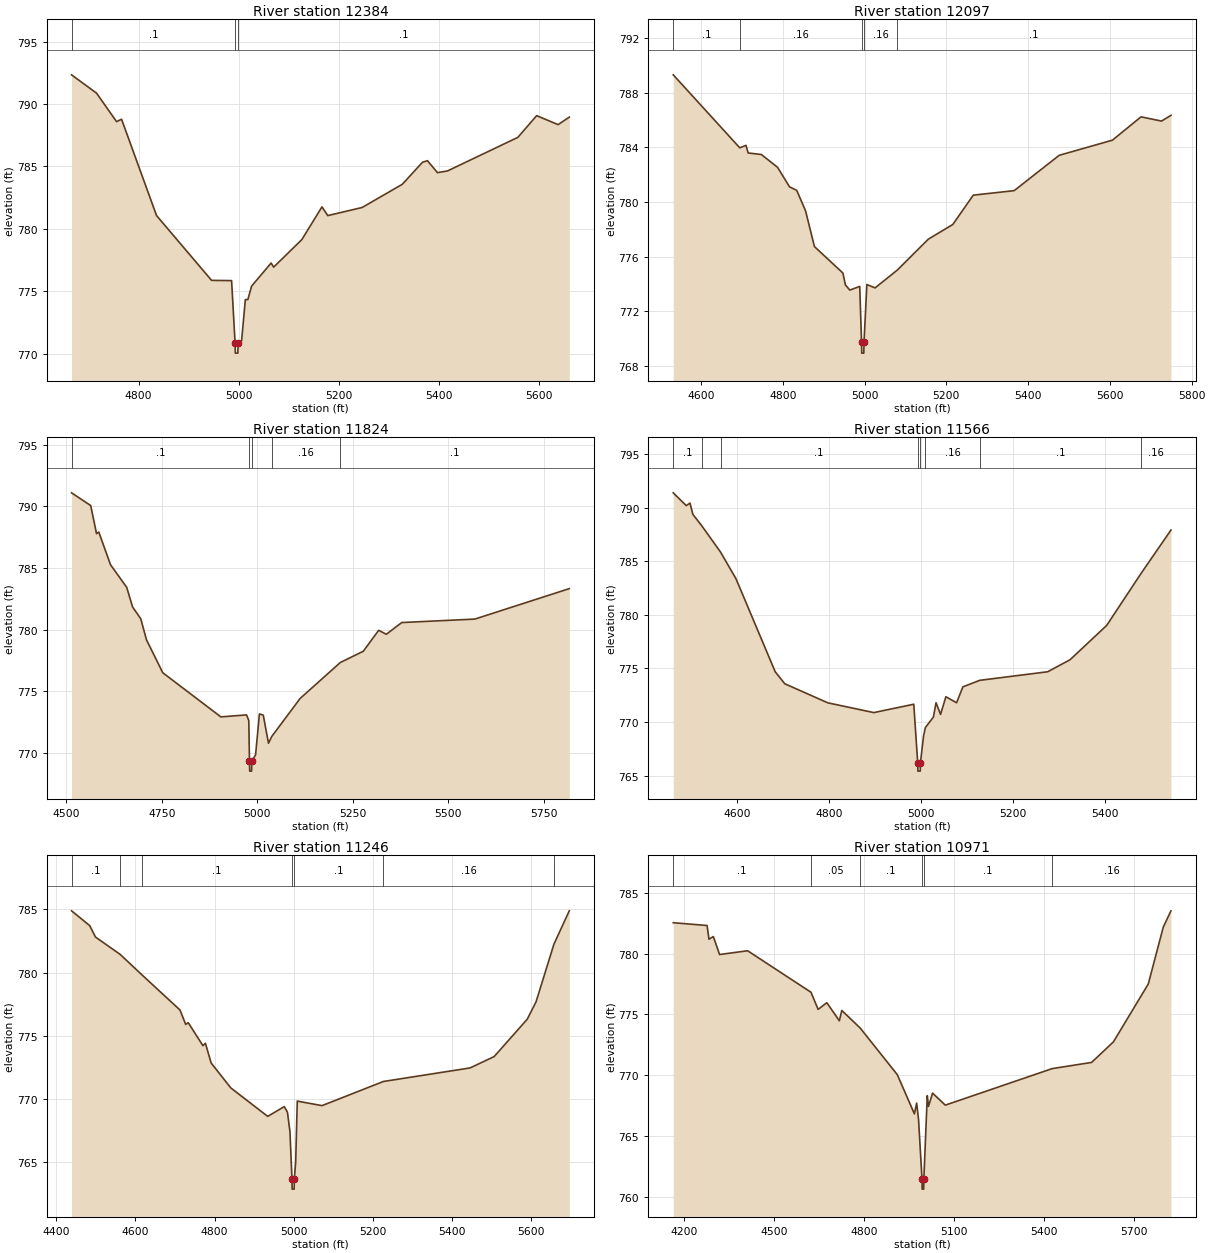
Type RM Length L Ch R = 1,12384,287,287,287
BEGIN DESCRIPTION:
UNT 043 in HW 28.0
END DESCRIPTION:
XS GIS Cut Line= 3
      1983825.00     13631175.00      1983475.00     13631175.00
      1982832.68     13631235.93
#Sta/Elev= 30
  4665.8  792.33  4715.8  790.86  4755.8  788.58  4765.8  788.77  4835.8  781.05
  4945.8  775.86  4985.8  775.84  4992.8  770.83  4993.3  770.03  4998.3  770.03
  4998.8  770.83  5005.8  771.03  5013.3  774.32  5018.3  774.32  5025.8  775.40
  5064.9  777.25  5069.9  776.92  5126.3  779.13  5166.5  781.75  5178.1  781.05
  5246.8  781.70  5327.2  783.56  5367.4  785.32  5377.4  785.45  5397.5  784.49
  5417.6  784.63  5558.2  787.32  5595.8  789.06  5638.6  788.34  5661.0  788.94
#Mann=3,-1,0
  4665.8     0.1       0  4992.8    0.07       0  4998.8     0.1       0
Bank Sta=4992.8,4998.8
Exp/Cntr=0.3,0.1

Type RM Length L Ch R = 1,12097,273,273,273
BEGIN DESCRIPTION:
UNT 043 in HW 27.0
END DESCRIPTION:
XS GIS Cut Line= 3
      1983994.23     13631097.92      1983575.00     13630925.00
      1982811.87     13630952.07
#Sta/Elev= 30
  4532.3  789.32  4695.0  783.97  4710.2  784.15  4715.6  783.59  4747.8  783.48
  4787.4  782.54  4816.7  781.11  4834.3  780.85  4856.0  779.34  4877.6  776.73
  4947.2  774.79  4953.3  773.92  4964.2  773.54  4988.3  773.81  4992.8  769.72
  4993.3  768.92  4998.3  768.92  4998.8  769.72  5005.8  773.95  5025.8  773.70
  5080.3  775.01  5155.9  777.27  5215.9  778.35  5266.0  780.50  5366.0  780.83
  5476.1  783.42  5606.2  784.53  5676.2  786.24  5726.3  785.93  5749.4  786.35
#Mann=5,-1,0
  4532.3     0.1       0  4695.0    0.16       0  4992.8    0.07       0
  4998.8    0.16       0  5080.3     0.1       0
Bank Sta=4992.8,4998.8
Exp/Cntr=0.3,0.1

Type RM Length L Ch R = 1,11824,258,258,258
BEGIN DESCRIPTION:
UNT 043 in HW 26.0
END DESCRIPTION:
XS GIS Cut Line= 3
      1984025.00     13630925.00      1983625.00     13630675.00
      1982799.48     13630577.14
#Sta/Elev= 30
  4514.0  791.09  4564.1  790.06  4579.4  787.78  4585.3  787.91  4616.0  785.26
  4658.5  783.42  4673.8  781.83  4695.0  780.89  4710.3  779.16  4752.8  776.50
  4904.9  772.92  4972.1  773.08  4978.0  772.63  4979.8  769.32  4980.3  768.52
  4985.3  768.52  4985.8  769.32  4995.8  769.84  5005.8  773.16  5015.9  773.06
  5029.6  770.78  5038.1  771.33  5112.3  774.41  5217.6  777.33  5277.7  778.24
  5318.0  779.94  5338.1  779.62  5378.4  780.57  5569.8  780.85  5817.0  783.32
#Mann=5,-1,0
  4514.0     0.1       0  4979.8    0.07       0  4985.8     0.1       0
  5038.1    0.16       0  5217.6     0.1       0
Bank Sta=4979.8,4985.8
Exp/Cntr=0.3,0.1

Type RM Length L Ch R = 1,11566,320,320,320
BEGIN DESCRIPTION:
UNT 043 in HW 25.0
END DESCRIPTION:
XS GIS Cut Line= 3
      1984025.02     13630875.02      1983725.00     13630475.00
      1983225.02     13630175.01
#Sta/Elev= 30
  4460.2  791.38  4488.4  790.19  4496.7  790.42  4502.9  789.37  4522.2  788.31
  4563.2  785.85  4596.7  783.37  4682.1  774.69  4702.9  773.57  4796.7  771.79
  4896.7  770.88  4983.6  771.66  4992.2  766.22  4992.7  765.42  4997.7  765.42
  4998.2  766.22  5004.9  768.70  5008.9  769.49  5026.3  770.46  5032.1  771.80
  5041.9  770.71  5053.5  772.36  5076.8  771.80  5090.5  773.28  5127.3  773.89
  5275.1  774.69  5323.7  775.81  5403.4  779.01  5478.2  783.86  5543.3  787.91
#Mann=8,-1,0
  4460.2     0.1       0  4522.2    0.16       0  4563.2     0.1       0
  4992.2    0.07       0  4998.2     0.1       0  5008.9    0.16       0
  5127.3     0.1       0  5478.2    0.16       0
Bank Sta=4992.2,4998.2
Exp/Cntr=0.3,0.1

Type RM Length L Ch R = 1,11246,275,275,275
BEGIN DESCRIPTION:
UNT 043 in HW 24.0
END DESCRIPTION:
XS GIS Cut Line= 3
      1984327.53     13630827.09      1983975.00     13630375.00
      1983359.37     13630077.36
#Sta/Elev= 30
  4438.8  784.89  4484.7  783.72  4499.2  782.82  4561.8  781.44  4616.9  779.82
  4712.7  777.05  4727.1  775.91  4733.5  776.05  4770.6  774.23  4776.9  774.42
  4791.4  772.86  4841.1  770.89  4934.3  768.64  4975.9  769.41  4984.0  768.98
  4990.4  767.45  4995.5  763.69  4996.0  762.89  5001.0  762.89  5001.5  763.69
  5004.9  765.03  5008.9  769.85  5071.4  769.49  5226.5  771.40  5445.3  772.47
  5506.2  773.37  5589.7  776.32  5611.9  777.69  5657.2  782.26  5695.9  784.89
#Mann=7,-1,0
  4438.8     0.1       0  4561.8    0.16       0  4616.9     0.1       0
  4995.5    0.07       0  5001.5     0.1       0  5226.5    0.16       0
  5657.2     0.1       0
Bank Sta=4995.5,5001.5
Exp/Cntr=0.3,0.1

Type RM Length L Ch R = 1,10971,197,197,197
BEGIN DESCRIPTION:
UNT 043 in HW 23.0
END DESCRIPTION:
XS GIS Cut Line= 3
      1984856.14     13630741.11      1984175.00     13630225.00
      1983413.46     13629962.49
#Sta/Elev= 30
  4163.5  782.56  4276.4  782.33  4282.7  781.20  4297.2  781.42  4318.1  779.94
  4411.6  780.25  4623.0  776.83  4646.7  775.42  4675.8  775.97  4717.5  774.48
  4725.8  775.33  4786.8  773.89  4910.9  770.04  4967.9  766.81  4975.4  767.70
  4981.7  766.34  4993.3  761.41  4993.8  760.61  4998.8  760.61  4999.3  761.41
  5010.8  768.31  5014.9  767.43  5028.4  768.52  5071.0  767.53  5427.5  770.54
  5558.9  771.05  5631.6  772.74  5747.9  777.51  5798.0  782.20  5823.6  783.54
#Mann=6,-1,0
  4163.5     0.1       0  4623.0    0.05       0  4786.8     0.1       0
  4993.3    0.07       0  4999.3     0.1       0  5427.5    0.16       0
Bank Sta=4993.3,4999.3
Exp/Cntr=0.3,0.1

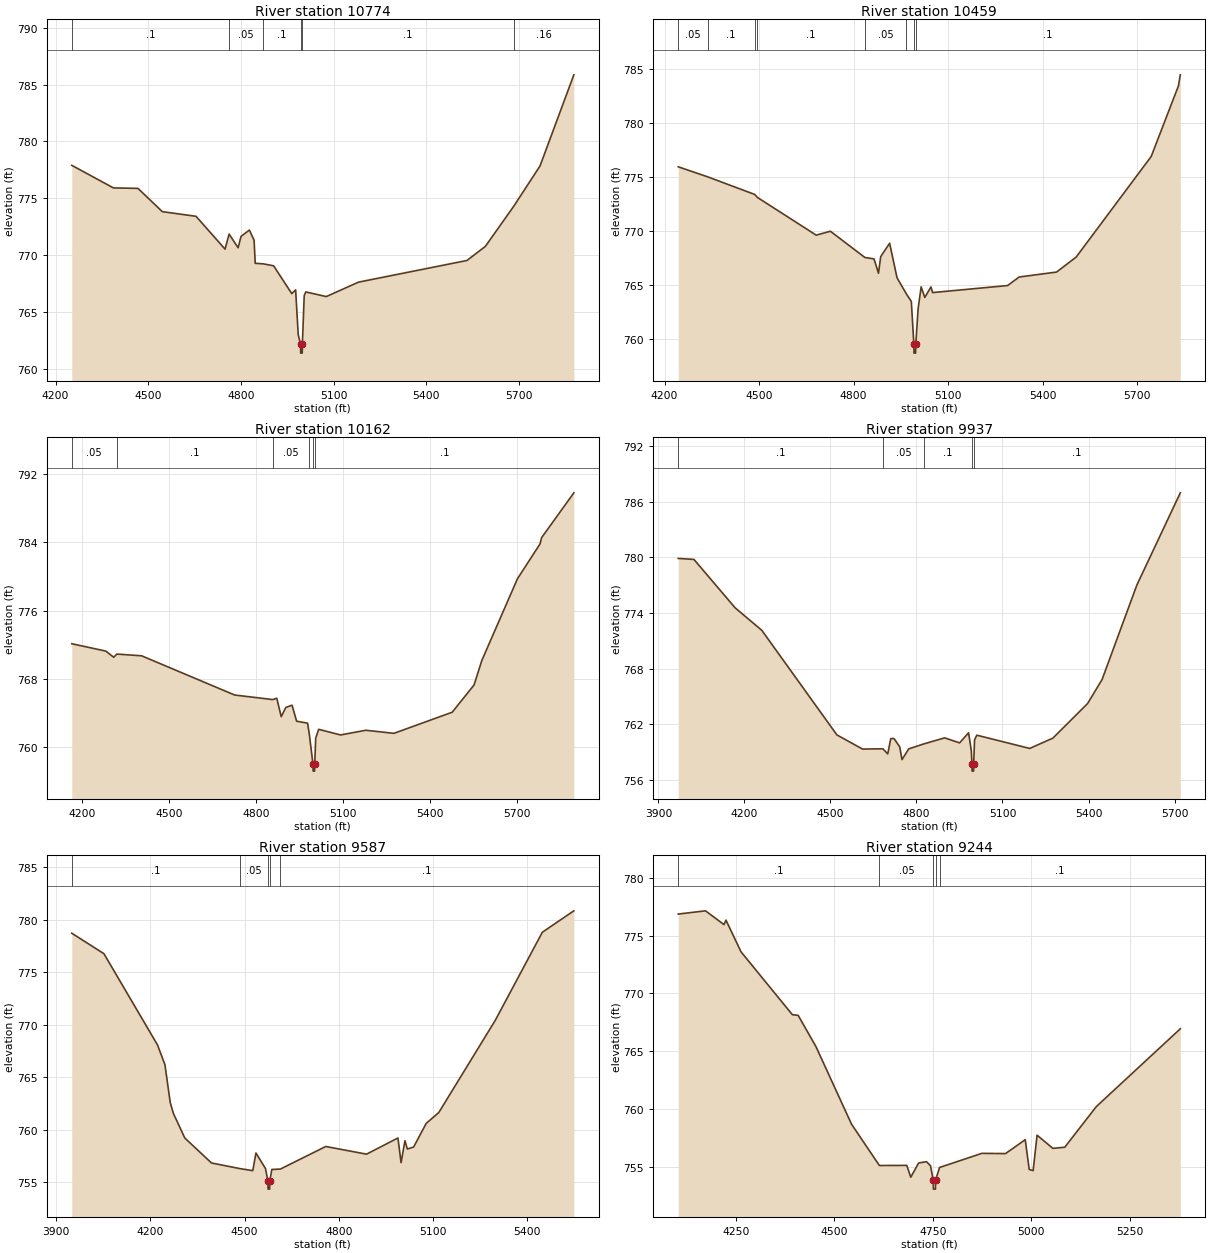
Type RM Length L Ch R = 1,10774,315,315,315
BEGIN DESCRIPTION:
UNT 043 in HW 22.0
END DESCRIPTION:
XS GIS Cut Line= 3
      1984918.68     13630436.45      1984416.06     13630116.13
      1983430.78     13629819.77
#Sta/Elev= 30
  4252.3  777.90  4387.1  775.91  4466.6  775.87  4545.3  773.82  4654.5  773.41
  4748.4  770.52  4761.5  771.84  4790.7  770.64  4800.1  771.64  4827.1  772.20
  4842.4  771.30  4846.0  769.27  4872.7  769.22  4905.6  769.05  4964.3  766.60
  4976.8  766.93  4985.2  762.98  4992.6  762.16  4993.1  761.36  4998.1  761.36
  4998.6  762.16  5004.6  766.43  5009.9  766.75  5075.9  766.34  5180.2  767.61
  5531.3  769.52  5590.8  770.76  5682.3  774.28  5767.7  777.84  5877.2  785.87
#Mann=6,-1,0
  4252.3     0.1       0  4761.5    0.05       0  4872.7     0.1       0
  4992.6    0.07       0  4998.6     0.1       0  5682.3    0.16       0
Bank Sta=4992.6,4998.6
Exp/Cntr=0.3,0.1

Type RM Length L Ch R = 1,10459,297,297,297
BEGIN DESCRIPTION:
UNT 043 in HW 21.0
END DESCRIPTION:
XS GIS Cut Line= 3
      1985046.28     13630207.29      1984425.00     13629825.00
      1983609.37     13629540.82
#Sta/Elev= 30
  4243.3  775.96  4336.8  775.03  4485.9  773.40  4494.7  773.12  4681.1  769.63
  4726.2  769.99  4835.6  767.56  4864.5  767.43  4878.8  766.10  4885.8  767.64
  4914.1  768.88  4937.6  765.68  4967.6  764.17  4983.0  763.48  4991.0  759.50
  4991.5  758.70  4996.5  758.70  4997.0  759.50  5004.5  762.81  5014.1  764.84
  5025.7  763.86  5045.2  764.83  5050.5  764.31  5288.5  764.96  5324.9  765.75
  5443.9  766.21  5506.1  767.60  5744.2  776.92  5830.5  783.45  5836.5  784.48
#Mann=8,-1,0
  4243.3    0.05       0  4336.8     0.1       0  4485.9    0.05       0
  4494.7     0.1       0  4835.6    0.05       0  4967.6     0.1       0
  4991.0    0.07       0  4997.0     0.1       0
Bank Sta=4991,4997
Exp/Cntr=0.3,0.1

Type RM Length L Ch R = 1,10162,225,225,225
BEGIN DESCRIPTION:
UNT 043 in HW 20.0
END DESCRIPTION:
XS GIS Cut Line= 3
      1985227.68     13629981.14      1984525.00     13629575.00
      1983624.96     13629374.99
#Sta/Elev= 30
  4163.6  772.12  4281.1  771.26  4308.4  770.54  4319.2  770.91  4404.6  770.71
  4726.1  766.12  4857.5  765.59  4871.3  765.75  4886.9  763.59  4902.7  764.67
  4924.2  764.93  4940.0  763.06  4977.8  762.83  4983.6  761.60  4996.5  758.02
  4997.0  757.22  5002.0  757.22  5002.5  758.02  5005.9  761.08  5016.2  762.11
  5091.7  761.45  5178.8  762.00  5276.1  761.64  5477.2  764.11  5552.7  767.30
  5579.6  770.17  5702.5  779.72  5780.6  783.80  5785.8  784.52  5897.2  789.77
#Mann=6,-1,0
  4163.6    0.05       0  4319.2     0.1       0  4857.5    0.05       0
  4983.6     0.1       0  4996.5    0.07       0  5002.5     0.1       0
Bank Sta=4996.5,5002.5
Exp/Cntr=0.3,0.1

Type RM Length L Ch R = 1,9937,350,350,350
BEGIN DESCRIPTION:
UNT 043 in HW 19.0
END DESCRIPTION:
XS GIS Cut Line= 3
      1985425.03     13629074.99      1984425.00     13629375.00
      1983724.97     13629275.00
#Sta/Elev= 30
  3969.0  779.90  4023.8  779.79  4167.4  774.57  4260.5  772.14  4522.4  760.85
  4612.0  759.32  4682.8  759.35  4699.8  758.80  4710.3  760.45  4721.6  760.46
  4741.6  759.56  4749.4  758.18  4772.9  759.34  4826.8  759.89  4898.2  760.53
  4950.4  759.99  4981.7  761.08  4991.3  759.13  4993.5  757.74  4994.0  756.94
  4999.0  756.94  4999.5  757.74  5002.6  760.31  5010.4  760.82  5194.9  759.39
  5275.7  760.50  5396.9  764.24  5447.4  766.83  5568.6  777.02  5720.2  786.98
#Mann=5,-1,0
  3969.0     0.1       0  4682.8    0.05       0  4826.8     0.1       0
  4993.5    0.07       0  4999.5     0.1       0
Bank Sta=4993.5,4999.5
Exp/Cntr=0.3,0.1

Type RM Length L Ch R = 1,9587,343,343,343
BEGIN DESCRIPTION:
UNT 043 in HW 18.0
END DESCRIPTION:
XS GIS Cut Line= 3
      1985325.03     13628975.00      1984541.93     13629095.73
      1983734.67     13629078.37
#Sta/Elev= 30
  3949.3  778.72  4051.7  776.77  4222.5  768.08  4246.2  766.20  4263.0  762.60
  4273.1  761.56  4309.4  759.22  4394.5  756.84  4485.8  756.30  4526.1  756.11
  4536.2  757.79  4566.5  756.31  4574.2  755.15  4574.7  754.35  4579.8  754.35
  4580.3  755.15  4586.8  756.22  4614.1  756.26  4758.6  758.41  4888.6  757.68
  4988.6  759.22  4998.6  756.87  5010.9  758.96  5018.6  758.17  5038.6  758.36
  5078.7  760.61  5118.7  761.64  5298.7  770.42  5448.7  778.81  5549.1  780.85
#Mann=5,-1,0
  3949.3     0.1       0  4485.8    0.05       0  4574.2    0.07       0
  4580.3    0.05       0  4614.1     0.1       0
Bank Sta=4574.2,4580.3
Exp/Cntr=0.3,0.1

Type RM Length L Ch R = 1,9244,291,291,291
BEGIN DESCRIPTION:
UNT 043 in HW 17.0
END DESCRIPTION:
XS GIS Cut Line= 3
      1985354.10     13628866.33      1984668.33     13628829.44
      1984082.35     13628792.55
#Sta/Elev= 30
  4104.3  776.86  4173.5  777.14  4220.4  775.95  4225.4  776.34  4263.6  773.60
  4393.8  768.17  4408.6  768.11  4453.9  765.40  4544.0  758.71  4614.7  755.14
  4684.2  755.15  4694.3  754.13  4714.3  755.36  4734.3  755.47  4744.3  755.12
  4751.3  753.90  4751.8  753.10  4756.9  753.10  4757.4  753.90  4767.4  754.97
  4874.6  756.19  4934.7  756.17  4984.8  757.37  4994.8  754.80  5004.8  754.70
  5014.8  757.76  5054.9  756.62  5085.0  756.72  5165.1  760.23  5378.2  766.95
#Mann=5,-1,0
  4104.3     0.1       0  4614.7    0.05       0  4751.3    0.07       0
  4757.4    0.05       0  4767.4     0.1       0
Bank Sta=4751.3,4757.4
Exp/Cntr=0.3,0.1

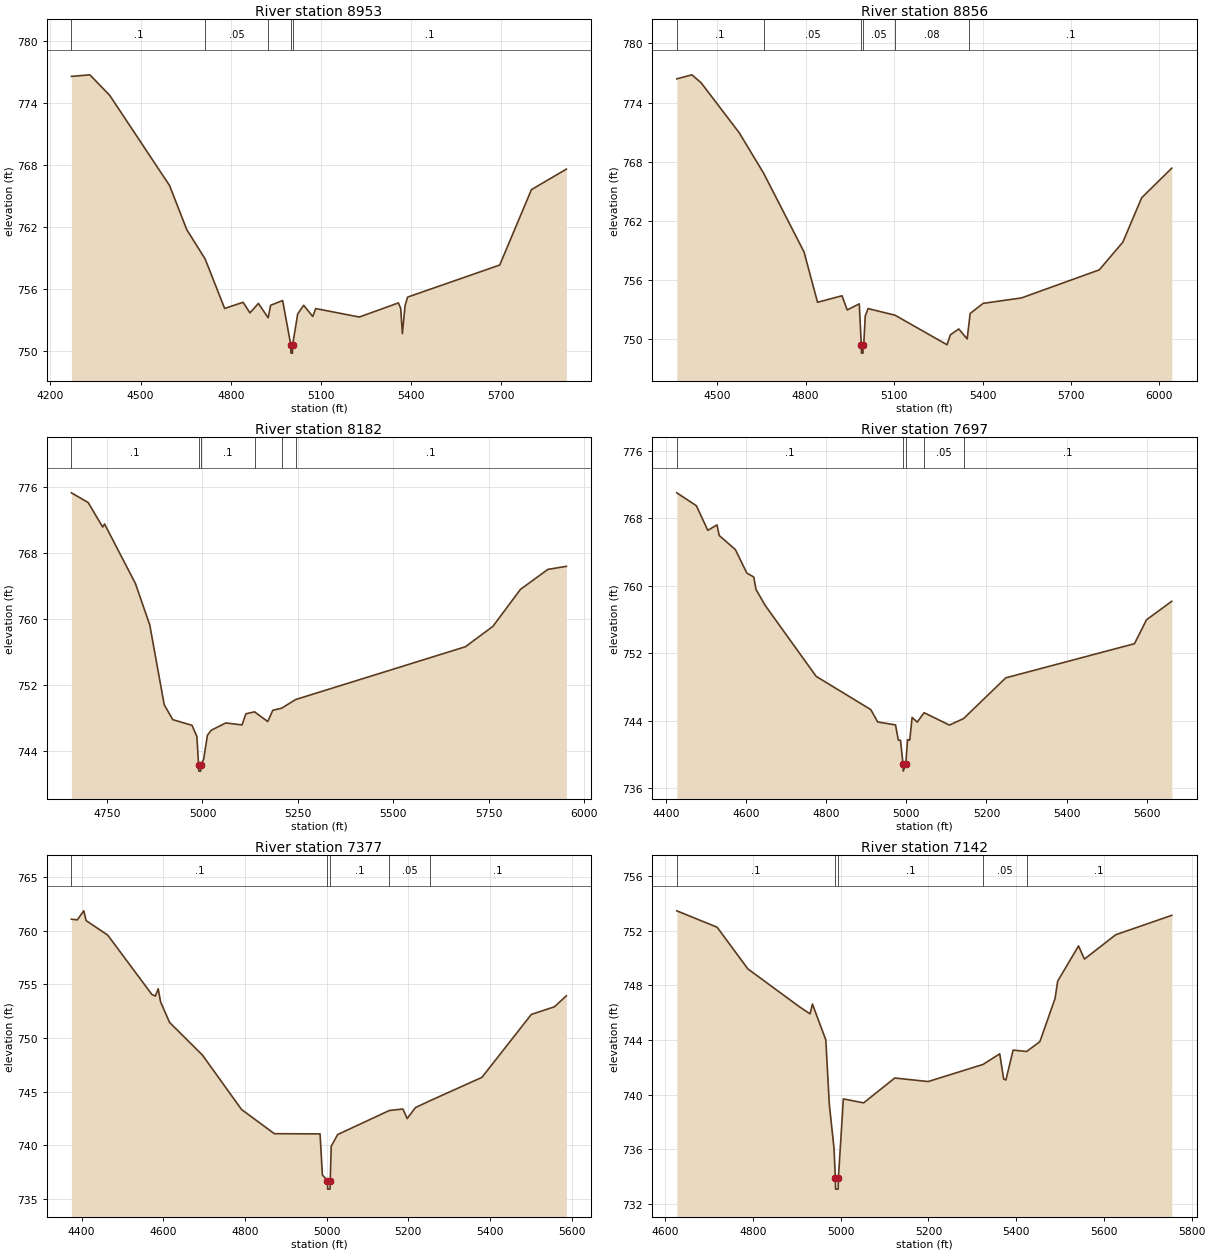
Type RM Length L Ch R = 1,8953,97,97,97
BEGIN DESCRIPTION:
Mapping XS a381d310
END DESCRIPTION:
XS GIS Cut Line= 4
      1985345.37     13628844.62      1984684.25     13628714.08
      1984672.67     13628430.14      1984049.92     13628725.24
#Sta/Elev= 30
  4269.8  776.61  4331.3  776.76  4397.3  774.77  4596.4  766.03  4653.7  761.75
  4714.8  758.91  4779.8  754.11  4841.0  754.71  4864.0  753.68  4892.0  754.60
  4924.5  753.21  4932.7  754.42  4972.8  754.88  4999.8  750.58  5000.3  749.78
  5005.4  749.78  5005.9  750.58  5022.8  753.58  5042.8  754.42  5072.9  753.33
  5082.9  754.10  5227.9  753.28  5358.1  754.65  5365.6  754.12  5371.2  751.67
  5380.2  754.39  5388.4  755.21  5695.1  758.32  5800.7  765.63  5917.0  767.62
#Mann=5,-1,0
  4269.8     0.1       0  4714.8    0.05       0  4924.5     0.1       0
  4999.8    0.07       0  5005.9     0.1       0
Bank Sta=4999.8,5005.9
Exp/Cntr=0.3,0.1

Type RM Length L Ch R = 1,8856,674,674,674
BEGIN DESCRIPTION:
Mapping XS fe096b88
END DESCRIPTION:
XS GIS Cut Line= 4
      1985334.52     13628827.26      1984771.06     13628668.51
      1984763.82     13628334.65      1984073.15     13628650.75
#Sta/Elev= 30
  4363.1  776.41  4414.5  776.82  4445.7  776.01  4574.9  770.94  4657.4  766.85
  4794.6  758.85  4840.5  753.74  4923.6  754.40  4941.1  752.96  4982.0  753.58
  4989.0  749.38  4989.5  748.58  4994.6  748.58  4995.1  749.38  4997.2  749.45
  5002.2  752.34  5012.0  753.10  5103.3  752.43  5279.8  749.43  5291.0  750.44
  5319.5  751.03  5348.0  750.02  5354.6  751.71  5358.1  752.60  5402.1  753.63
  5532.1  754.18  5796.2  757.03  5876.2  759.85  5939.8  764.34  6042.0  767.35
#Mann=6,-1,0
  4363.1     0.1       0  4657.4    0.05       0  4989.0    0.04       0
  4995.1    0.05       0  5103.3    0.08       0  5354.6     0.1       0
Bank Sta=4989,4995.1
Exp/Cntr=0.3,0.1

Type RM Length L Ch R = 1,8182,485,485,485
BEGIN DESCRIPTION:
Mapping XS 6517e613
END DESCRIPTION:
XS GIS Cut Line= 3
      1985208.69     13628230.48      1984739.95     13628171.89
      1984054.17     13628629.80
#Sta/Elev= 30
  4656.6  775.31  4700.6  774.13  4738.5  771.16  4743.5  771.53  4824.2  764.33
  4861.9  759.30  4899.8  749.61  4922.3  747.81  4972.7  747.12  4985.4  745.77
  4989.8  742.37  4990.3  741.57  4995.4  741.57  4995.9  742.37  5003.0  742.98
  5013.0  745.92  5023.1  746.53  5061.0  747.41  5103.7  747.17  5113.8  748.52
  5136.4  748.76  5171.0  747.58  5184.3  748.95  5207.1  749.19  5244.2  750.25
  5689.0  756.65  5761.0  759.12  5833.1  763.60  5905.2  766.03  5953.6  766.40
#Mann=6,-1,0
  4656.6     0.1       0  4989.8    0.07       0  4995.9     0.1       0
  5136.4    0.05       0  5207.1    0.08       0  5244.2     0.1       0
Bank Sta=4989.8,4995.9
Exp/Cntr=0.3,0.1

Type RM Length L Ch R = 1,7697,320,320,320
BEGIN DESCRIPTION:
UNT 043 in HW 16.0
END DESCRIPTION:
XS GIS Cut Line= 3
      1985310.70     13627972.24      1984775.00     13627725.00
      1984132.29     13627668.41
#Sta/Elev= 30
  4427.4  771.03  4476.3  769.50  4504.8  766.58  4527.7  767.23  4533.3  765.97
  4573.6  764.30  4602.1  761.52  4619.5  761.05  4625.0  759.58  4648.0  757.68
  4775.1  749.27  4911.4  745.33  4928.8  743.86  4973.3  743.51  4980.2  741.71
  4985.7  741.69  4992.0  738.83  4992.5  738.03  4998.8  738.83  5003.2  741.77
  5008.7  741.70  5014.6  744.40  5027.4  743.84  5044.5  744.96  5107.7  743.49
  5143.0  744.26  5248.3  749.09  5569.5  753.14  5599.6  755.98  5662.6  758.17
#Mann=5,-1,0
  4427.4     0.1       0  4992.0    0.07       0  4998.8     0.1       0
  5044.5    0.05       0  5143.0     0.1       0
Bank Sta=4992,4998.8
Exp/Cntr=0.3,0.1

Type RM Length L Ch R = 1,7377,235,235,235
BEGIN DESCRIPTION:
UNT 043 in HW 15.0
END DESCRIPTION:
XS GIS Cut Line= 3
      1985443.08     13627776.93      1984852.79     13627436.21
      1984331.95     13627334.21
#Sta/Elev= 30
  4375.1  761.08  4389.6  761.02  4405.4  761.86  4411.1  760.95  4464.2  759.59
  4572.0  754.07  4580.7  753.91  4587.7  754.59  4593.5  753.37  4615.4  751.46
  4696.2  748.40  4791.7  743.34  4872.1  741.08  4984.1  741.06  4989.8  737.23
  5002.2  736.71  5002.7  735.91  5008.5  735.91  5009.0  736.71  5011.4  739.91
  5027.2  741.00  5153.7  743.24  5186.9  743.38  5197.6  742.49  5217.5  743.51
  5253.3  744.15  5380.5  746.33  5501.5  752.20  5558.1  752.91  5587.4  753.94
#Mann=5,-1,0
  4375.1     0.1       0  5002.2    0.07       0  5009.0     0.1       0
  5153.7    0.05       0  5253.3     0.1       0
Bank Sta=5002.2,5009
Exp/Cntr=0.3,0.1

Type RM Length L Ch R = 1,7142,474,474,474
BEGIN DESCRIPTION:
Mapping XS 921622bb
END DESCRIPTION:
XS GIS Cut Line= 3
      1985421.33     13627486.11      1984841.94     13627273.45
      1984339.20     13627182.44
#Sta/Elev= 30
  4626.6  753.46  4718.6  752.26  4788.6  749.21  4905.3  746.46  4930.4  745.92
  4935.7  746.64  4966.2  744.02  4974.2  739.31  4984.9  736.08  4988.0  733.90
  4988.5  733.10  4994.4  733.10  4994.9  733.90  5006.2  739.70  5052.4  739.41
  5123.4  741.23  5199.5  740.97  5324.4  742.22  5362.6  743.00  5371.6  741.15
  5376.7  741.09  5393.1  743.27  5423.9  743.17  5454.1  743.89  5488.7  747.05
  5494.7  748.32  5542.2  750.89  5555.7  749.93  5626.9  751.71  5754.7  753.13
#Mann=5,-1,0
  4626.6     0.1       0  4988.0    0.07       0  4994.9     0.1       0
  5324.4    0.05       0  5423.9     0.1       0
Bank Sta=4988,4994.9
Exp/Cntr=0.3,0.1