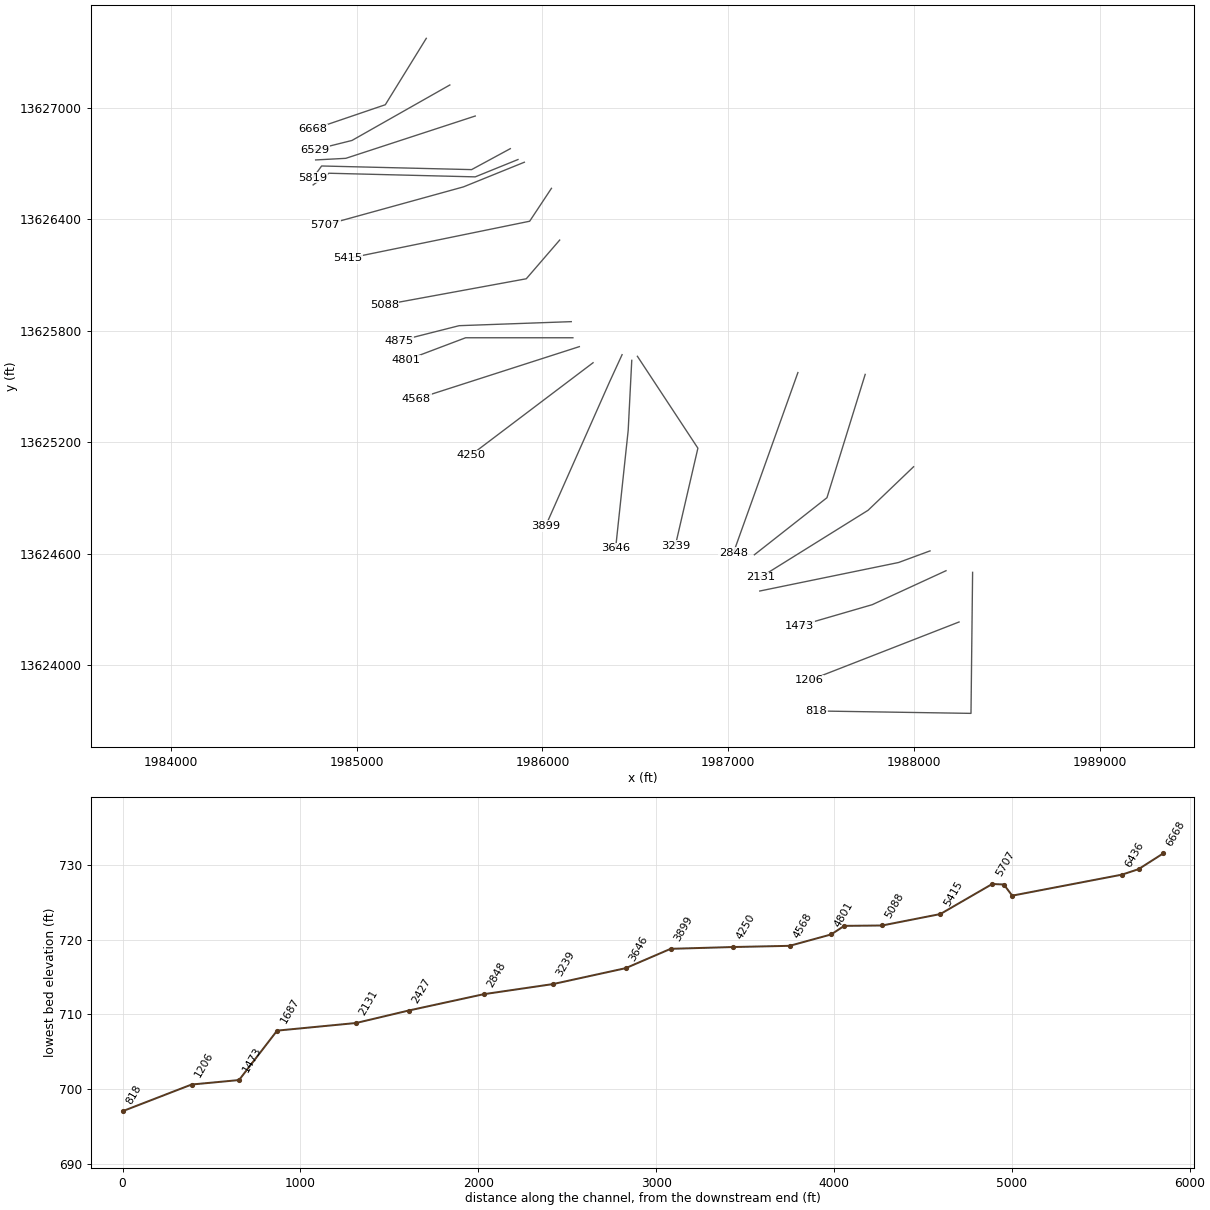
HEC-RAS study UNT 043 in HW.prj: UNT 043 in HW Base Level Engineering

--- UNT 043 in HW.g01 (geometry) --- (continued)

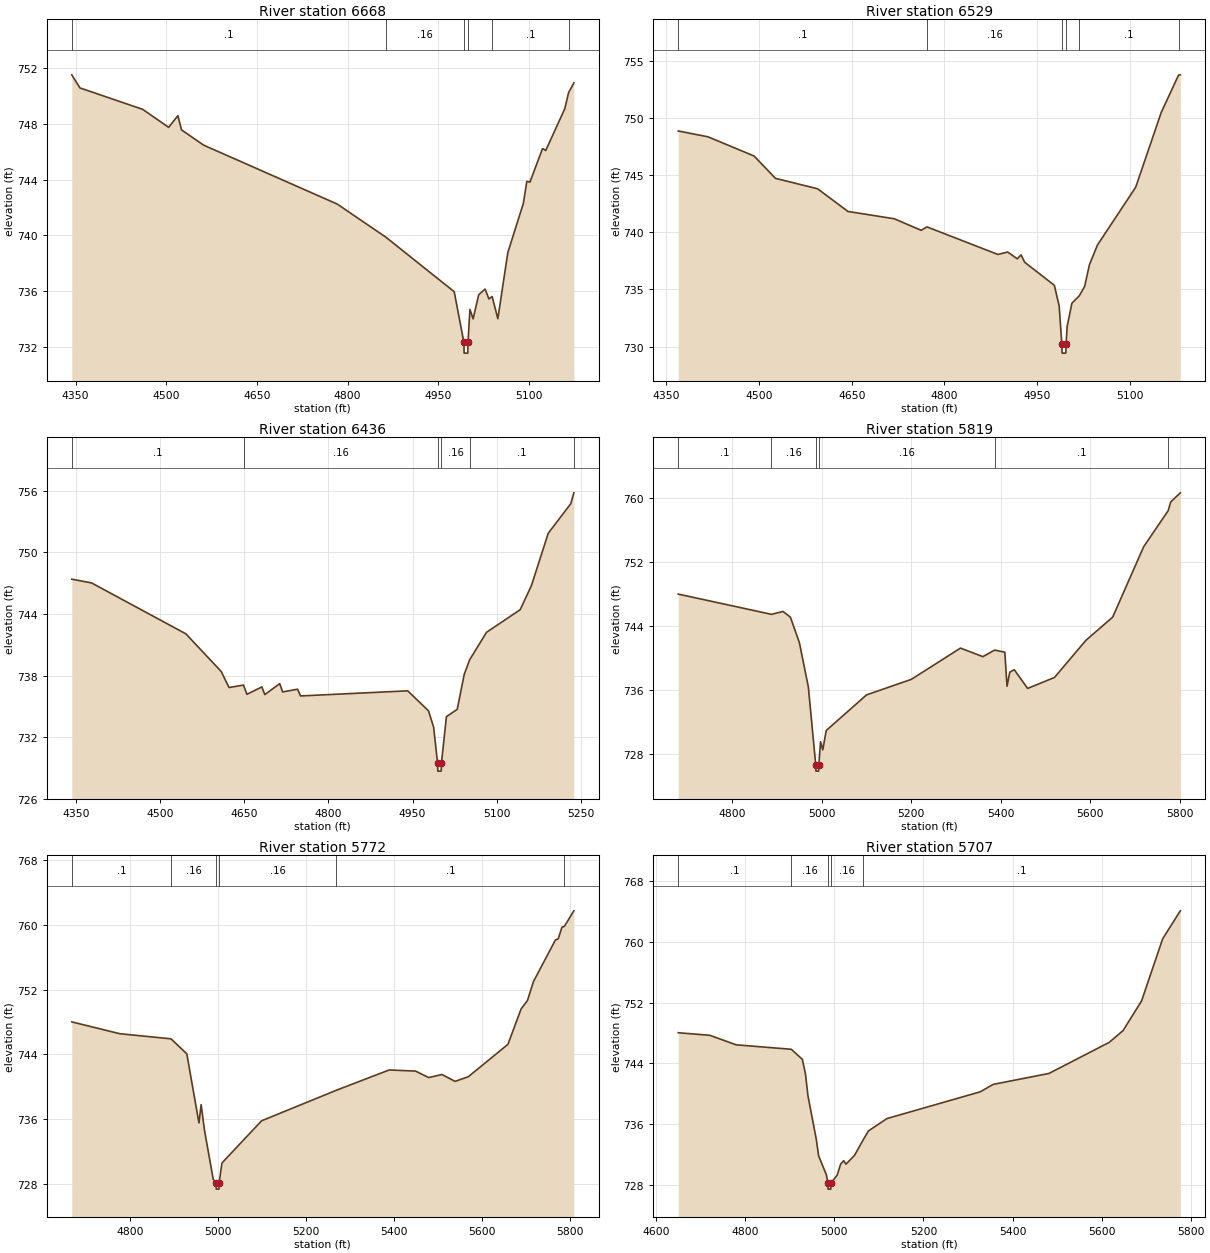
Type RM Length L Ch R = 1,6668,139,139,139
BEGIN DESCRIPTION:
UNT 043 in HW 14.0
END DESCRIPTION:
XS GIS Cut Line= 3
      1985374.98     13627374.96      1985154.44     13627017.38
      1984766.00     13626885.00
#Sta/Elev= 30
  4343.6  751.52  4357.1  750.58  4461.0  749.04  4503.8  747.75  4519.2  748.59
  4525.1  747.57  4561.8  746.47  4782.8  742.24  4863.0  739.87  4976.2  735.95
  4992.1  732.34  4992.6  731.54  4998.6  731.54  4999.1  732.34  5002.2  734.68
  5007.5  734.00  5016.7  735.73  5027.3  736.14  5033.6  735.43  5039.0  735.60
  5048.4  734.01  5064.9  738.76  5090.6  742.29  5096.3  743.87  5101.5  743.82
  5122.3  746.22  5127.6  746.09  5159.0  749.07  5165.4  750.24  5174.1  750.94
#Mann=6,-1,0
  4343.6     0.1       0  4863.0    0.16       0  4992.1    0.07       0
  4999.1    0.16       0  5039.0     0.1       0  5165.4    0.05       0
Bank Sta=4992.1,4999.1
Exp/Cntr=0.3,0.1

Type RM Length L Ch R = 1,6529,93,93,93
BEGIN DESCRIPTION:
UNT 043 in HW 13.0
END DESCRIPTION:
XS GIS Cut Line= 3
      1985501.64     13627123.70      1984975.00     13626825.00
      1984775.01     13626775.00
#Sta/Elev= 30
  4369.6  748.86  4417.6  748.35  4492.2  746.67  4526.7  744.72  4595.0  743.80
  4644.0  741.82  4719.0  741.18  4762.3  740.17  4771.7  740.47  4886.3  738.06
  4902.2  738.27  4917.6  737.68  4923.8  738.02  4929.6  737.38  4977.6  735.36
  4985.4  733.55  4989.6  730.23  4990.1  729.43  4996.1  729.43  4996.6  730.23
  4998.2  731.74  5006.0  733.80  5018.0  734.45  5026.6  735.27  5034.3  737.16
  5047.2  738.88  5109.1  743.94  5150.3  750.47  5178.4  753.75  5181.2  753.77
#Mann=6,-1,0
  4369.6     0.1       0  4771.7    0.16       0  4989.6    0.07       0
  4996.6    0.16       0  5018.0     0.1       0  5178.4    0.05       0
Bank Sta=4989.6,4996.6
Exp/Cntr=0.3,0.1

Type RM Length L Ch R = 1,6436,617,617,617
BEGIN DESCRIPTION:
Mapping XS 644b69ba
END DESCRIPTION:
XS GIS Cut Line= 3
      1985638.42     13626956.62      1984941.77     13626728.75
      1984779.47     13626720.09
#Sta/Elev= 30
  4342.2  747.39  4377.4  747.03  4545.7  742.07  4608.8  738.40  4622.7  736.84
  4648.5  737.08  4654.6  736.18  4681.2  736.90  4686.5  736.15  4713.1  737.22
  4718.3  736.41  4744.9  736.68  4750.2  736.02  4941.4  736.52  4978.5  734.57
  4987.6  732.98  4994.6  729.50  4995.1  728.70  5001.1  728.70  5001.6  729.50
  5010.4  734.00  5029.7  734.72  5042.2  738.12  5051.9  739.55  5082.0  742.22
  5142.0  744.42  5162.1  746.78  5192.1  751.87  5232.2  754.74  5237.7  755.80
#Mann=6,-1,0
  4342.2     0.1       0  4648.5    0.16       0  4994.6    0.07       0
  5001.6    0.16       0  5051.9     0.1       0  5237.7    0.08       0
Bank Sta=4994.6,5001.6
Exp/Cntr=0.3,0.1

Type RM Length L Ch R = 1,5819,47,47,47
BEGIN DESCRIPTION:
Mapping XS 652e3915
END DESCRIPTION:
XS GIS Cut Line= 4
      1985827.21     13626780.84      1985618.85     13626667.98
      1984811.56     13626687.51      1984765.98     13626624.57
#Sta/Elev= 30
  4679.5  748.02  4887.9  745.49  4913.7  745.85  4930.3  745.13  4950.3  741.94
  4970.3  736.42  4986.8  726.69  4987.3  725.89  4993.3  725.89  4993.8  726.69
  4997.6  729.56  5002.6  728.55  5010.3  730.97  5100.4  735.42  5200.4  737.36
  5310.4  741.27  5360.4  740.20  5386.6  741.02  5409.4  740.76  5414.4  736.50
  5420.5  738.25  5430.5  738.57  5460.5  736.23  5520.5  737.60  5590.5  742.23
  5650.5  745.14  5719.8  753.94  5774.7  758.46  5780.2  759.54  5801.7  760.68
#Mann=6,-1,0
  4679.5     0.1       0  4887.9    0.16       0  4986.8    0.07       0
  4993.8    0.16       0  5386.6     0.1       0  5774.7    0.08       0
Bank Sta=4986.8,4993.8
Exp/Cntr=0.3,0.1

Type RM Length L Ch R = 1,5772,65,65,65
BEGIN DESCRIPTION:
Mapping XS 89499871
END DESCRIPTION:
XS GIS Cut Line= 4
      1985868.40     13626722.23      1985638.38     13626628.92
      1984850.62     13626648.45      1984765.98     13626585.51
#Sta/Elev= 30
  4667.7  748.01  4777.0  746.55  4893.4  745.92  4929.3  744.07  4956.9  735.55
  4961.9  737.80  4969.3  734.70  4989.3  728.61  4995.8  728.18  4996.3  727.38
  5002.3  727.38  5002.8  728.18  5009.3  730.61  5099.4  735.81  5269.6  739.58
  5389.5  742.08  5449.5  741.94  5479.5  741.14  5509.5  741.52  5539.5  740.67
  5569.5  741.25  5659.5  745.24  5689.5  749.61  5703.9  750.64  5717.6  752.99
  5767.7  758.13  5773.9  758.25  5782.3  759.68  5787.8  759.79  5809.4  761.71
#Mann=6,-1,0
  4667.7     0.1       0  4893.4    0.16       0  4995.8    0.07       0
  5002.8    0.16       0  5269.6     0.1       0  5787.8    0.08       0
Bank Sta=4995.8,5002.8
Exp/Cntr=0.3,0.1

Type RM Length L Ch R = 1,5707,292,292,292
BEGIN DESCRIPTION:
UNT 043 in HW 12.0
END DESCRIPTION:
XS GIS Cut Line= 3
      1985902.72     13626707.78      1985575.00     13626575.00
      1984831.33     13626369.65
#Sta/Elev= 30
  4650.5  748.04  4721.3  747.70  4780.3  746.45  4903.9  745.86  4928.6  744.54
  4935.7  742.60  4941.1  739.77  4959.8  734.03  4965.2  731.81  4982.5  729.34
  4985.8  728.25  4986.3  727.45  4992.3  727.45  4992.8  728.25  5006.7  729.30
  5014.5  730.76  5021.3  731.19  5026.5  730.74  5045.6  731.90  5065.1  733.95
  5076.7  735.11  5118.2  736.74  5327.2  740.26  5356.3  741.24  5481.3  742.68
  5616.2  746.77  5647.3  748.32  5688.8  752.23  5736.1  760.41  5775.6  764.09
#Mann=5,-1,0
  4650.5     0.1       0  4903.9    0.16       0  4985.8    0.07       0
  4992.8    0.16       0  5065.1     0.1       0
Bank Sta=4985.8,4992.8
Exp/Cntr=0.3,0.1

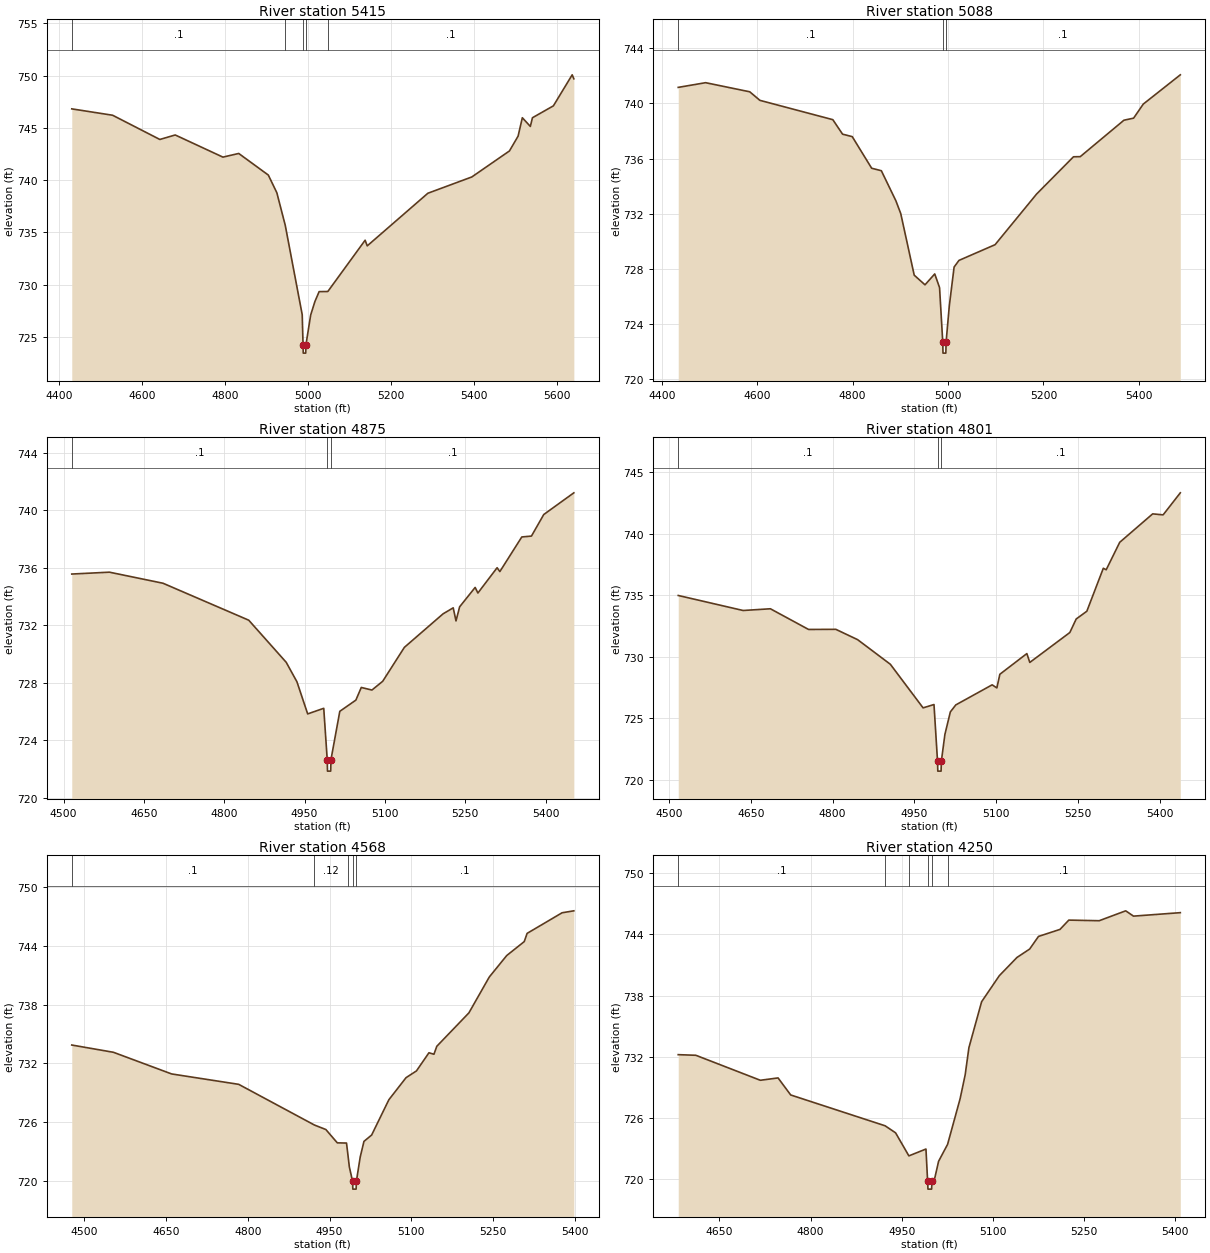
Type RM Length L Ch R = 1,5415,327,327,327
BEGIN DESCRIPTION:
Mapping XS e3a75214
END DESCRIPTION:
XS GIS Cut Line= 3
      1986048.55     13626567.16      1985931.35     13626390.06
      1984953.32     13626189.77
#Sta/Elev= 30
  4429.8  746.82  4528.3  746.21  4642.2  743.89  4679.3  744.32  4794.3  742.20
  4832.4  742.55  4903.8  740.48  4924.3  738.79  4944.6  735.67  4985.5  727.11
  4987.5  724.23  4988.0  723.43  4994.0  723.43  4994.5  724.23  5005.9  727.08
  5016.1  728.37  5026.3  729.32  5047.2  729.33  5137.2  734.24  5142.3  733.70
  5288.5  738.74  5394.5  740.30  5485.2  742.79  5506.1  744.21  5516.3  745.97
  5535.6  745.14  5540.7  745.97  5591.2  747.11  5636.5  750.08  5640.5  749.70
#Mann=5,-1,0
  4429.8     0.1       0  4944.6    0.16       0  4987.5    0.07       0
  4994.5    0.16       0  5047.2     0.1       0
Bank Sta=4987.5,4994.5
Exp/Cntr=0.3,0.1

Type RM Length L Ch R = 1,5088,213,213,213
BEGIN DESCRIPTION:
UNT 043 in HW 11.0
END DESCRIPTION:
XS GIS Cut Line= 3
      1986092.81     13626288.49      1985913.12     13626080.16
      1985148.72     13625939.76
#Sta/Elev= 30
  4434.6  741.16  4492.0  741.50  4584.5  740.84  4605.8  740.22  4758.6  738.82
  4779.0  737.77  4799.3  737.59  4840.0  735.30  4860.3  735.12  4890.8  732.94
  4901.0  732.01  4929.2  727.55  4951.8  726.85  4972.2  727.64  4982.3  726.65
  4989.0  722.70  4989.5  721.90  4995.5  721.90  4996.0  722.70  5002.7  725.31
  5012.8  728.14  5023.0  728.62  5098.7  729.76  5185.7  733.43  5263.0  736.13
  5277.2  736.14  5368.7  738.78  5389.0  738.93  5409.3  739.95  5486.9  742.07
#Mann=3,-1,0
  4434.6     0.1       0  4989.0    0.07       0  4996.0     0.1       0
Bank Sta=4989,4996
Exp/Cntr=0.3,0.1

Type RM Length L Ch R = 1,4875,74,74,74
BEGIN DESCRIPTION:
UNT 043 in HW 10.0
END DESCRIPTION:
XS GIS Cut Line= 3
      1986155.29     13625849.26      1985552.01     13625827.56
      1985228.20     13625745.53
#Sta/Elev= 30
  4515.2  735.56  4585.5  735.69  4685.6  734.92  4845.7  732.35  4915.7  729.42
  4935.8  728.06  4955.8  725.83  4985.8  726.22  4992.3  722.65  4992.8  721.85
  4998.8  721.85  4999.3  722.65  5015.8  726.01  5045.8  726.79  5055.9  727.67
  5075.8  727.49  5095.9  728.10  5136.4  730.46  5208.6  732.79  5227.6  733.21
  5232.8  732.30  5239.6  733.28  5268.6  734.63  5273.7  734.24  5309.6  736.00
  5314.7  735.73  5355.7  738.14  5373.7  738.20  5396.7  739.70  5452.9  741.21
#Mann=3,-1,0
  4515.2     0.1       0  4992.3    0.07       0  4999.3     0.1       0
Bank Sta=4992.3,4999.3
Exp/Cntr=0.3,0.1

Type RM Length L Ch R = 1,4801,233,233,233
BEGIN DESCRIPTION:
Mapping XS 2b626359
END DESCRIPTION:
XS GIS Cut Line= 3
      1986164.00     13625762.46      1985586.73     13625762.46
      1985265.52     13625640.92
#Sta/Elev= 30
  4516.8  734.97  4635.8  733.75  4685.8  733.89  4755.8  732.21  4805.8  732.22
  4845.8  731.38  4905.8  729.38  4965.8  725.84  4985.8  726.11  4992.3  721.50
  4992.8  720.70  4998.8  720.70  4999.3  721.50  5005.8  723.68  5015.8  725.51
  5025.8  726.08  5092.4  727.71  5101.1  727.46  5106.6  728.57  5156.1  730.25
  5161.5  729.53  5234.9  731.96  5246.6  733.06  5266.1  733.69  5296.3  737.18
  5301.6  737.06  5326.4  739.29  5386.8  741.60  5406.0  741.52  5437.5  743.31
#Mann=3,-1,0
  4516.8     0.1       0  4992.3    0.07       0  4999.3     0.1       0
Bank Sta=4992.3,4999.3
Exp/Cntr=0.3,0.1

Type RM Length L Ch R = 1,4568,318,318,318
BEGIN DESCRIPTION:
Mapping XS 22961083
END DESCRIPTION:
XS GIS Cut Line= 2
      1986198.69     13625714.71      1985321.96     13625432.59
#Sta/Elev= 30
  4477.0  733.88  4553.4  733.14  4660.2  730.93  4783.2  729.87  4922.1  725.72
  4943.1  725.26  4964.1  723.90  4981.0  723.88  4983.8  722.57  4986.2  721.44
  4992.1  719.98  4992.6  719.18  4998.6  719.18  4999.1  719.98  5006.1  722.45
  5013.0  724.05  5027.1  724.70  5058.7  728.30  5090.2  730.55  5109.3  731.24
  5132.2  733.09  5141.4  732.94  5146.6  733.75  5205.5  737.16  5242.9  740.82
  5274.9  743.01  5307.0  744.43  5312.3  745.27  5376.4  747.37  5398.0  747.57
#Mann=5,-1,0
  4477.0     0.1       0  4922.1    0.12       0  4983.8     0.1       0
  4992.1    0.07       0  4999.1     0.1       0
Bank Sta=4992.1,4999.1
Exp/Cntr=0.3,0.1

Type RM Length L Ch R = 1,4250,351,351,351
BEGIN DESCRIPTION:
Mapping XS 2e38dab7
END DESCRIPTION:
XS GIS Cut Line= 2
      1986272.53     13625627.93      1985613.58     13625129.38
#Sta/Elev= 30
  4582.3  732.20  4611.3  732.14  4717.4  729.69  4746.6  729.92  4767.4  728.25
  4922.7  725.23  4940.0  724.54  4961.9  722.28  4990.0  722.95  4992.7  719.82
  4993.3  719.02  4999.3  719.02  4999.8  719.82  5004.5  720.10  5010.8  721.75
  5025.6  723.41  5046.2  727.88  5054.5  730.21  5060.7  732.89  5081.6  737.39
  5110.7  739.94  5139.8  741.73  5160.6  742.55  5175.2  743.79  5210.6  744.48
  5225.1  745.39  5275.1  745.33  5318.7  746.30  5331.6  745.78  5408.6  746.12
#Mann=6,-1,0
  4582.3     0.1       0  4922.7    0.12       0  4961.9    0.07       0
  4992.7    0.07       0  4999.8    0.07       0  5025.6     0.1       0
Bank Sta=4992.7,4999.8
Exp/Cntr=0.3,0.1

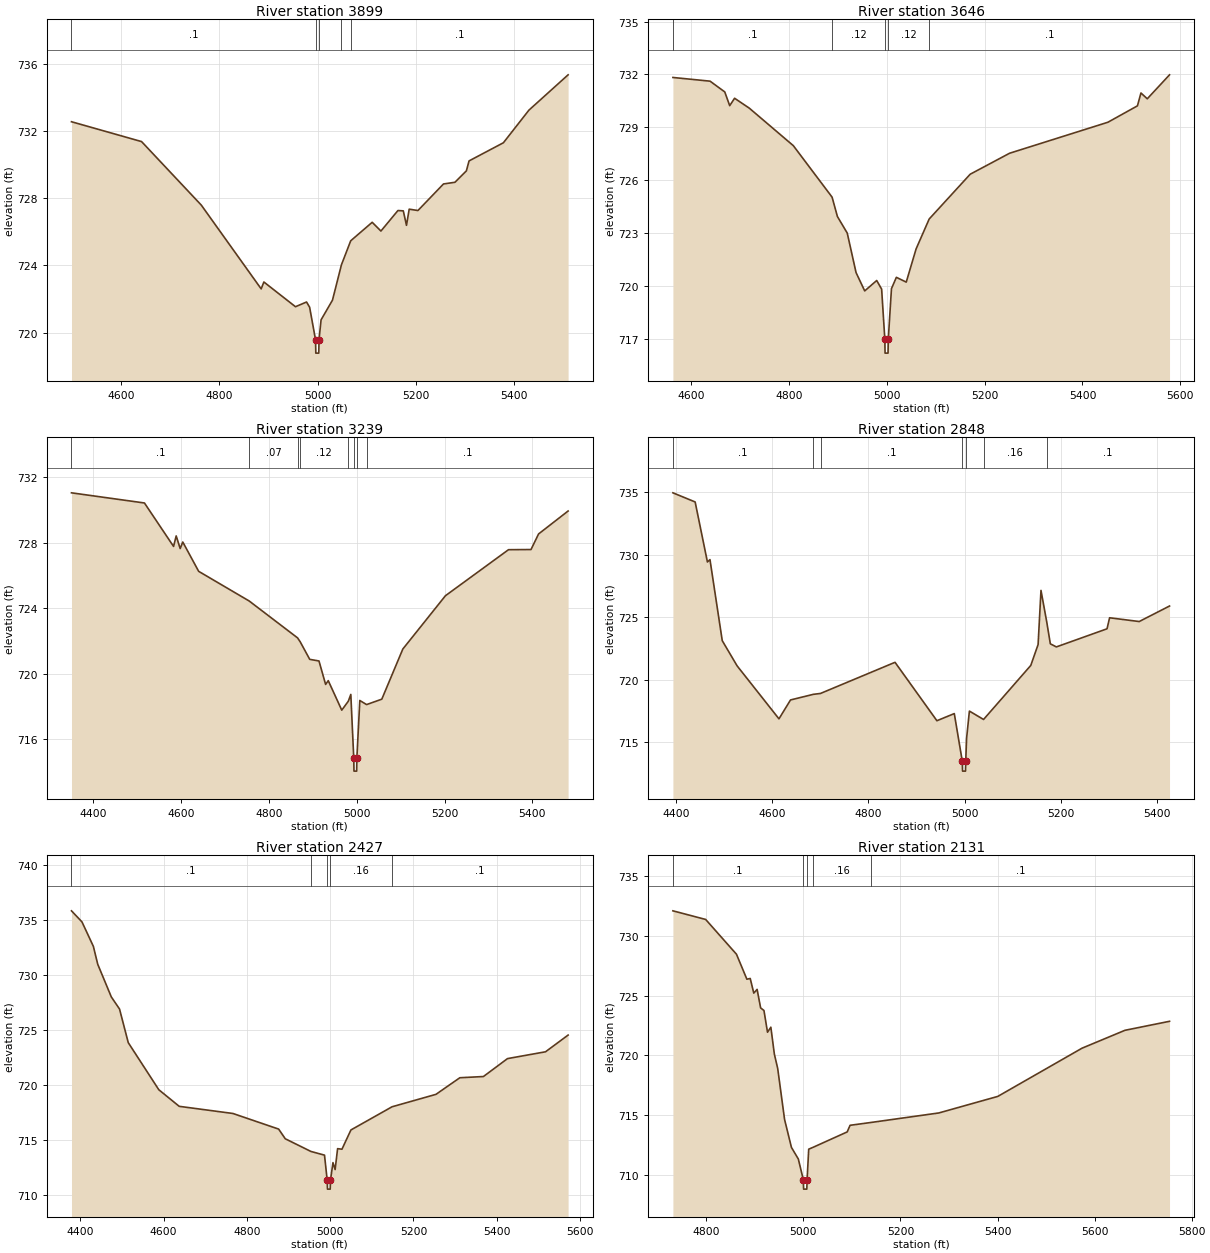
Type RM Length L Ch R = 1,3899,253,253,253
BEGIN DESCRIPTION:
UNT 043 in HW 9.0
END DESCRIPTION:
XS GIS Cut Line= 3
      1986428.76     13625671.35      1986361.28     13625524.65
      1986017.12     13624748.40
#Sta/Elev= 30
  4499.3  732.54  4641.9  731.36  4763.5  727.58  4885.3  722.60  4890.8  723.01
  4955.1  721.54  4977.6  721.82  4983.9  721.51  4995.9  719.58  4996.5  718.78
  5002.5  718.78  5003.0  719.58  5007.2  720.76  5030.4  721.93  5048.6  724.03
  5067.5  725.46  5111.2  726.56  5129.0  726.04  5163.6  727.26  5174.5  727.24
  5181.0  726.38  5186.5  727.34  5204.3  727.26  5256.3  728.84  5279.6  728.94
  5302.9  729.62  5308.3  730.21  5378.2  731.29  5430.2  733.23  5509.9  735.33
#Mann=5,-1,0
  4499.3     0.1       0  4995.9    0.07       0  5003.0     0.1       0
  5048.6    0.07       0  5067.5     0.1       0
Bank Sta=4995.9,5003
Exp/Cntr=0.3,0.1

Type RM Length L Ch R = 1,3646,407,407,407
BEGIN DESCRIPTION:
UNT 043 in HW 8.0
END DESCRIPTION:
XS GIS Cut Line= 3
      1986480.83     13625640.91      1986461.63     13625264.06
      1986394.04     13624629.79
#Sta/Elev= 30
  4562.8  731.83  4638.8  731.62  4668.8  731.01  4678.9  730.23  4688.9  730.65
  4718.9  730.09  4809.0  727.96  4888.2  725.04  4899.1  723.94  4919.2  723.00
  4937.2  720.76  4954.9  719.72  4979.4  720.31  4989.5  719.82  4996.0  716.99
  4996.5  716.19  5002.6  716.19  5003.1  716.99  5009.6  719.85  5019.6  720.49
  5039.8  720.22  5059.9  722.10  5086.7  723.80  5170.5  726.34  5251.0  727.53
  5452.1  729.29  5512.4  730.22  5519.6  730.95  5532.5  730.62  5578.0  731.98
#Mann=5,-1,0
  4562.8     0.1       0  4888.2    0.12       0  4996.0    0.07       0
  5003.1    0.12       0  5086.7     0.1       0
Bank Sta=4996,5003.1
Exp/Cntr=0.3,0.1

Type RM Length L Ch R = 1,3239,391,391,391
BEGIN DESCRIPTION:
UNT 043 in HW 7.0
END DESCRIPTION:
XS GIS Cut Line= 3
      1986511.20     13625662.65      1986836.73     13625167.84
      1986715.21     13624642.70
#Sta/Elev= 30
  4350.0  731.05  4516.2  730.43  4582.5  727.78  4588.5  728.42  4597.6  727.65
  4603.5  728.05  4639.7  726.26  4754.8  724.45  4865.0  722.20  4870.8  721.97
  4892.7  720.89  4913.8  720.79  4928.9  719.36  4934.9  719.59  4965.7  717.79
  4980.7  718.34  4986.3  718.75  4993.0  714.87  4993.5  714.07  4999.6  714.07
  5000.1  714.87  5006.8  718.38  5022.2  718.13  5056.9  718.46  5104.8  721.52
  5201.8  724.77  5345.5  727.58  5396.8  727.59  5414.0  728.54  5481.3  729.94
#Mann=8,-1,0
  4350.0     0.1       0  4754.8    0.07       0  4865.0     0.1       0
  4870.8    0.12       0  4980.7    0.16       0  4993.0    0.07       0
  5000.1    0.16       0  5022.2     0.1       0
Bank Sta=4993,5000.1
Exp/Cntr=0.3,0.1

Type RM Length L Ch R = 1,2848,421,421,421
BEGIN DESCRIPTION:
UNT 043 in HW 6.0
END DESCRIPTION:
XS GIS Cut Line= 3
      1987375.01     13625575.03      1987153.57     13624955.16
      1987027.72     13624603.64
#Sta/Elev= 30
  4394.2  734.96  4440.4  734.23  4465.9  729.43  4471.2  729.62  4496.7  723.14
  4527.5  721.13  4614.5  716.89  4638.5  718.40  4686.0  718.85  4700.8  718.92
  4855.6  721.41  4942.6  716.74  4978.7  717.31  4995.3  713.51  4995.9  712.71
  5002.0  712.71  5002.5  713.51  5004.2  715.31  5010.1  717.51  5039.5  716.84
  5137.6  721.16  5152.8  722.83  5158.8  727.16  5170.7  724.65  5178.2  722.89
  5190.7  722.64  5296.0  724.09  5301.3  724.97  5362.8  724.67  5425.8  725.91
#Mann=7,-1,0
  4394.2     0.1       0  4686.0    0.12       0  4700.8     0.1       0
  4995.3    0.07       0  5002.5     0.1       0  5039.5    0.16       0
  5170.7     0.1       0
Bank Sta=4995.3,5002.5
Exp/Cntr=0.3,0.1

Type RM Length L Ch R = 1,2427,296,296,296
BEGIN DESCRIPTION:
UNT 043 in HW 5.0
END DESCRIPTION:
XS GIS Cut Line= 3
      1987737.12     13625565.17      1987531.39     13624901.13
      1987140.76     13624593.83
#Sta/Elev= 30
  4379.0  735.84  4404.2  734.83  4431.5  732.61  4442.0  730.98  4474.6  728.01
  4494.3  726.91  4515.3  723.85  4588.6  719.57  4637.6  718.06  4766.5  717.41
  4876.3  715.99  4892.2  715.11  4953.6  713.96  4986.4  713.62  4992.9  711.33
  4993.5  710.53  5000.1  710.53  5000.7  711.33  5006.7  712.94  5011.9  712.31
  5017.8  714.21  5028.3  714.16  5049.8  715.91  5148.6  718.02  5254.0  719.15
  5311.3  720.66  5367.9  720.77  5425.7  722.40  5517.0  723.02  5571.2  724.54
#Mann=5,-1,0
  4379.0     0.1       0  4953.6    0.16       0  4992.9    0.07       0
  5000.7    0.16       0  5148.6     0.1       0
Bank Sta=4992.9,5000.7
Exp/Cntr=0.3,0.1

Type RM Length L Ch R = 1,2131,444,444,444
BEGIN DESCRIPTION:
UNT 043 in HW 4.0
END DESCRIPTION:
XS GIS Cut Line= 3
      1987997.57     13625067.82      1987752.75     13624833.42
      1987172.06     13624471.46
#Sta/Elev= 30
  4731.2  732.06  4798.7  731.34  4862.2  728.44  4883.6  726.36  4890.5  726.42
  4897.8  725.20  4904.7  725.51  4911.9  723.97  4918.8  723.75  4926.1  721.94
  4933.0  722.36  4940.2  720.12  4947.1  718.92  4961.3  714.66  4975.4  712.34
  4989.6  711.37  4999.8  709.66  5000.5  708.86  5007.1  708.86  5007.7  709.66
  5011.0  712.19  5020.8  712.36  5090.3  713.63  5096.2  714.18  5139.9  714.42
  5279.1  715.21  5400.6  716.59  5574.2  720.61  5662.6  722.10  5754.4  722.85
#Mann=5,-1,0
  4731.2     0.1       0  4999.8    0.07       0  5007.7     0.1       0
  5020.8    0.16       0  5139.9     0.1       0
Bank Sta=4999.8,5007.7
Exp/Cntr=0.3,0.1

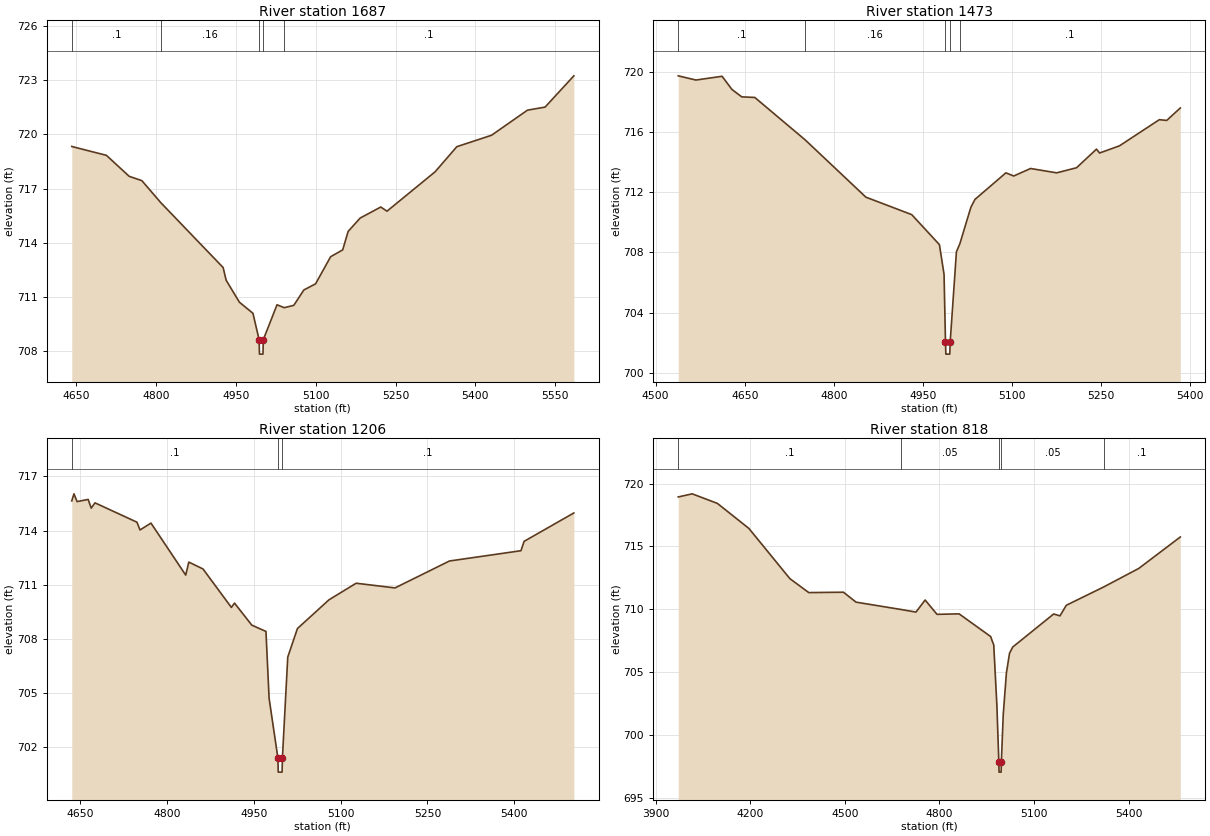
Type RM Length L Ch R = 1,1687,214,214,214
BEGIN DESCRIPTION:
Mapping XS 4b66a389
END DESCRIPTION:
XS GIS Cut Line= 3
      1988086.11     13624614.68      1987916.81     13624552.17
      1987169.70     13624398.58
#Sta/Elev= 30
  4641.7  719.33  4706.8  718.84  4749.5  717.68  4773.4  717.44  4809.0  716.22
  4926.1  712.63  4931.7  711.93  4956.7  710.71  4982.1  710.10  4993.6  708.64
  4994.3  707.84  5000.9  707.84  5001.5  708.64  5027.3  710.57  5040.9  710.41
  5058.8  710.54  5077.7  711.39  5099.7  711.73  5128.0  713.23  5150.7  713.61
  5160.9  714.63  5183.5  715.37  5222.2  715.98  5233.9  715.75  5324.3  717.93
  5365.1  719.32  5430.2  719.95  5497.8  721.34  5530.9  721.51  5584.9  723.24
#Mann=5,-1,0
  4641.7     0.1       0  4809.0    0.16       0  4993.6    0.07       0
  5001.5    0.16       0  5040.9     0.1       0
Bank Sta=4993.6,5001.5
Exp/Cntr=0.3,0.1

Type RM Length L Ch R = 1,1473,267,267,267
BEGIN DESCRIPTION:
UNT 043 in HW 3.0
END DESCRIPTION:
XS GIS Cut Line= 3
      1988172.05     13624507.91      1987775.00     13624325.00
      1987382.99     13624211.03
#Sta/Elev= 30
  4538.1  719.76  4567.9  719.48  4611.9  719.73  4628.6  718.85  4645.0  718.36
  4667.0  718.32  4751.7  715.50  4854.1  711.68  4931.2  710.52  4977.9  708.52
  4985.7  706.53  4988.1  702.03  4988.7  701.23  4995.3  701.23  4996.0  702.03
  5006.5  708.04  5012.3  708.58  5030.8  711.00  5037.7  711.53  5089.8  713.30
  5103.0  713.09  5131.4  713.59  5175.3  713.30  5208.8  713.64  5242.4  714.88
  5247.6  714.62  5281.1  715.10  5348.2  716.84  5360.6  716.79  5383.5  717.62
#Mann=5,-1,0
  4538.1     0.1       0  4751.7    0.16       0  4988.1    0.07       0
  4996.0    0.16       0  5012.3     0.1       0
Bank Sta=4988.1,4996
Exp/Cntr=0.3,0.1

Type RM Length L Ch R = 1,1206,388,388,388
BEGIN DESCRIPTION:
Mapping XS 3e72288c
END DESCRIPTION:
XS GIS Cut Line= 2
      1988242.32     13624231.85      1987435.04     13623916.75
#Sta/Elev= 30
  4636.1  715.65  4639.9  716.04  4645.3  715.61  4664.4  715.73  4669.7  715.25
  4676.2  715.54  4748.6  714.47  4753.9  714.04  4772.8  714.42  4832.8  711.54
  4838.1  712.26  4862.6  711.88  4911.6  709.75  4917.0  709.99  4946.8  708.77
  4971.3  708.42  4976.7  704.72  4991.8  701.43  4992.5  700.63  4999.1  700.63
  4999.7  701.43  5008.9  707.00  5025.6  708.58  5080.0  710.17  5127.0  711.09
  5194.0  710.83  5288.0  712.32  5411.4  712.89  5416.9  713.41  5502.7  714.98
#Mann=3,-1,0
  4636.1     0.1       0  4991.8    0.07       0  4999.7     0.1       0
Bank Sta=4991.8,4999.7
Exp/Cntr=0.3,0.1

Type RM Length L Ch R = 1,818,86,86,86
BEGIN DESCRIPTION:
UNT 043 in HW 2.0
END DESCRIPTION:
XS GIS Cut Line= 3
      1988315.25     13624499.17      1988306.57     13623739.67
      1987473.22     13623752.69
#Sta/Elev= 30
  3971.2  718.93  4015.4  719.18  4095.4  718.42  4195.4  716.43  4325.4  712.44
  4385.4  711.33  4495.4  711.36  4535.4  710.57  4677.4  709.99  4725.4  709.78
  4754.6  710.74  4792.3  709.60  4862.3  709.64  4962.3  707.84  4972.3  707.16
  4982.3  702.34  4988.4  697.86  4989.1  697.06  4995.7  697.06  4996.4  697.86
  5002.4  701.64  5012.4  704.94  5022.4  706.51  5032.4  707.00  5162.4  709.63
  5182.4  709.48  5202.4  710.32  5321.3  711.78  5432.4  713.25  5564.2  715.75
#Mann=5,-1,0
  3971.2     0.1       0  4677.4    0.05       0  4988.4    0.04       0
  4996.4    0.05       0  5321.3     0.1       0
Bank Sta=4988.4,4996.4
Exp/Cntr=0.3,0.1