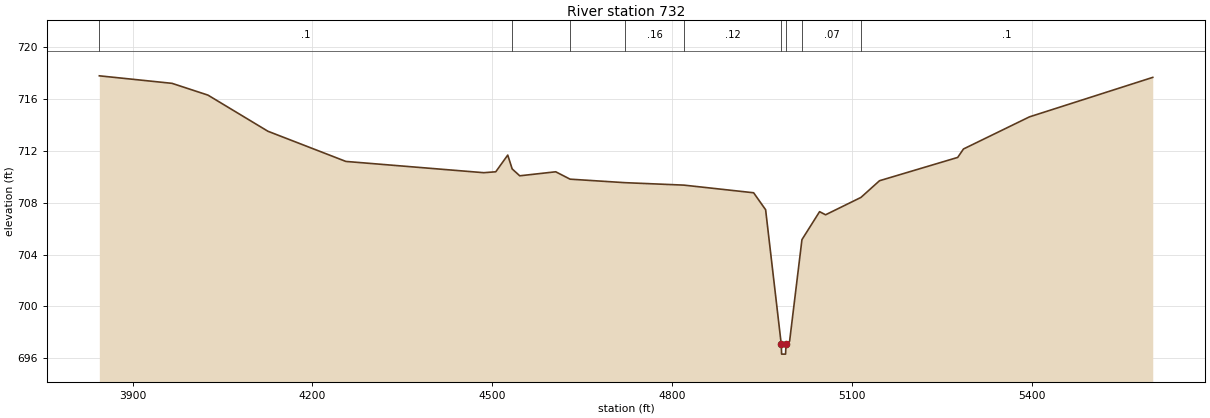
HEC-RAS study UNT 043 in HW.prj: UNT 043 in HW Base Level Engineering

--- UNT 043 in HW.g01 (geometry) --- (continued)

Type RM Length L Ch R = 1,732,0,0,0
BEGIN DESCRIPTION:
UNT 043 in HW 1.0
END DESCRIPTION:
XS GIS Cut Line= 3
      1988367.33     13624486.17      1988367.33     13623657.20
      1987439.30     13623661.54
#Sta/Elev= 30
  3844.5  717.81  3965.7  717.23  4025.7  716.32  4125.7  713.53  4255.7  711.20
  4485.7  710.33  4505.7  710.40  4525.7  711.69  4533.1  710.62  4545.7  710.09
  4605.7  710.40  4629.7  709.83  4721.1  709.56  4819.5  709.37  4935.8  708.78
  4955.8  707.47  4981.8  697.12  4982.5  696.32  4989.1  696.32  4989.8  697.12
  4995.8  697.31  5016.4  705.16  5045.8  707.32  5055.8  707.08  5114.8  708.42
  5145.8  709.71  5276.2  711.51  5285.8  712.16  5395.8  714.64  5601.5  717.69
#Mann=9,-1,0
  3844.5     0.1       0  4533.1    0.05       0  4629.7     0.1       0
  4721.1    0.16       0  4819.5    0.12       0  4981.8    0.07       0
  4989.8    0.12       0  5016.4    0.07       0  5114.8     0.1       0
Bank Sta=4981.8,4989.8
Exp/Cntr=0.3,0.1

Chan Stop Cuts=-1