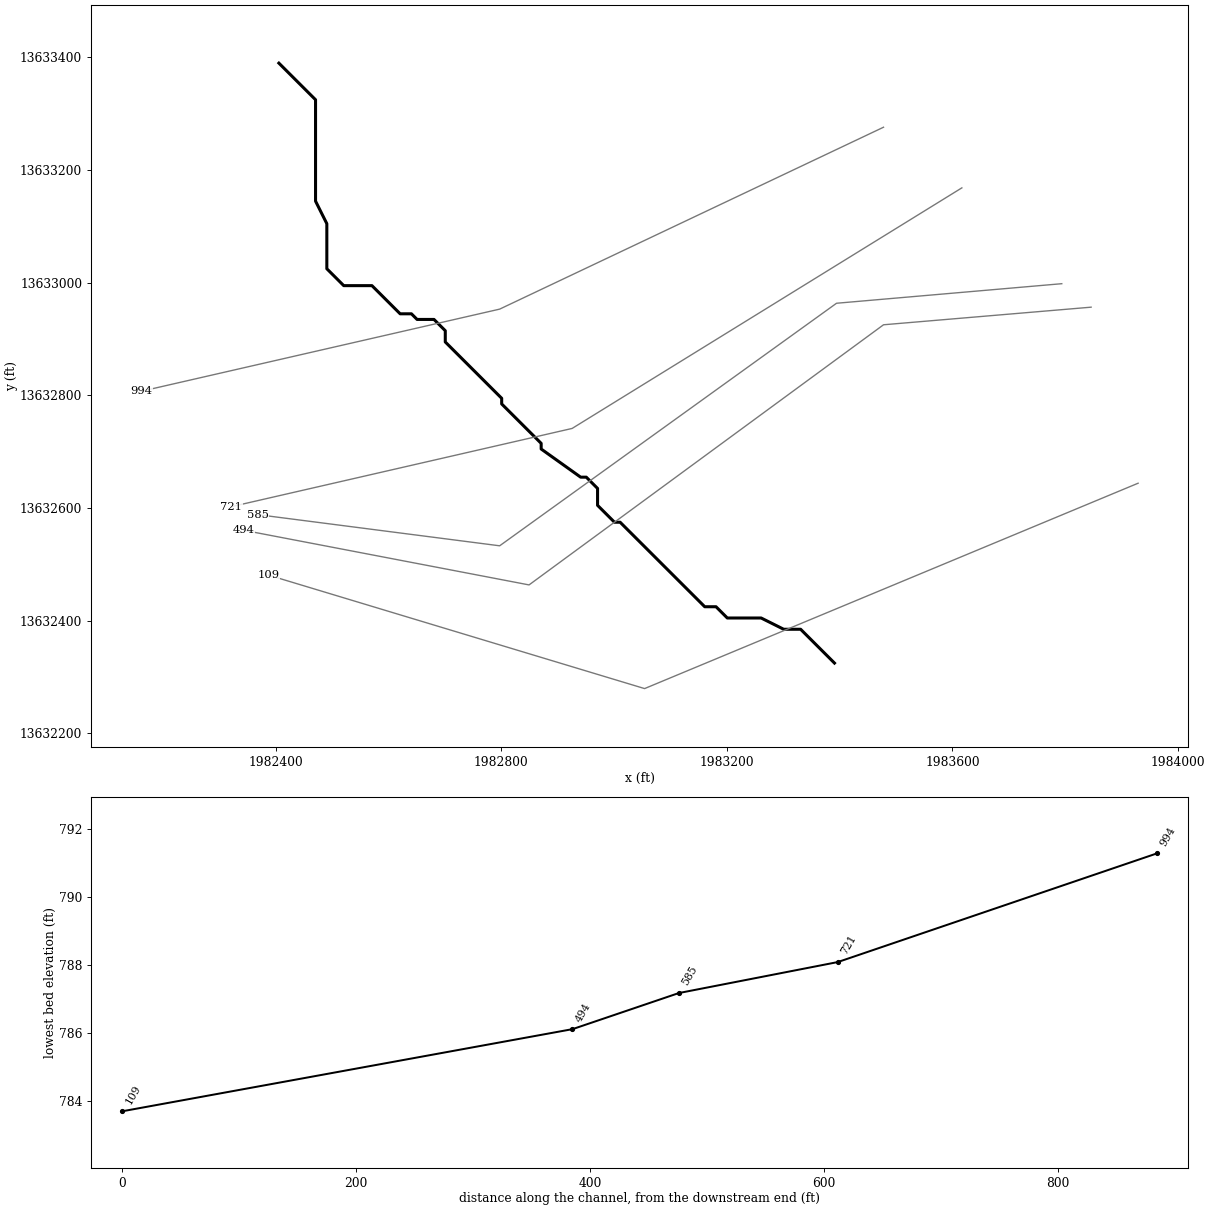
--- UNT 047 in HW.prj (project) ---

Proj Title=UNT 047 in HW Base Level Engineering
Current Plan=p01
Default Exp/Contr=0.3,0.1
English Units
Geom File=g01
Flow File=f01
Plan File=p01
BEGIN DESCRIPTION:
UNT 047 in HW
END DESCRIPTION:

--- UNT 047 in HW.p01 (plan) ---

Plan Title=Multiple Run
Short Identifier=Multiple
Geom File=g01
Flow File=f01
Subcritical Flow
K Sum by GR= 0
Std Step Tol= 0.01
Critical Tol= 0.01
Num of Std Step Trials= 20
Max Error Tol= 0.3
Flow Tol Ratio= 0.001
Split Flow NTrial= 30
Split Flow Tol= 0.02
Split Flow Ratio= 0.02
Log Output Level= 0
Friction Slope Method= 1
Unsteady Friction Slope Method= 2
Unsteady Bridges Friction Slope Method= 1
Parabolic Critical Depth
Global Vel Dist=  1 , 1 , 1
Global Log Level= 0
CheckData=True
Encroach Param= -1, 0, 0, 0
BEGIN DESCRIPTION:
Multiple Run
END DESCRIPTION:

--- UNT 047 in HW.f01 (steady flow) ---

Flow Title=Multiple
Number of Profiles=7
Profile Names=10-year,25-year,50-year,1pct_min,100-year,1pct_plu,500-year
River Rch & RM= UNT 047 in HW,Reach-1,994
     311     424     517     313     624    1246     912
Boundary for River Rch & Prof#=UNT 047 in HW,Reach-1,1
Up Type=0
Dn Type=3
Dn Slope=0.005
Boundary for River Rch & Prof#=UNT 047 in HW,Reach-1,2
Up Type=0
Dn Type=3
Dn Slope=0.005
Boundary for River Rch & Prof#=UNT 047 in HW,Reach-1,3
Up Type=0
Dn Type=3
Dn Slope=0.005
Boundary for River Rch & Prof#=UNT 047 in HW,Reach-1,4
Up Type=0
Dn Type=3
Dn Slope=0.005
Boundary for River Rch & Prof#=UNT 047 in HW,Reach-1,5
Up Type=0
Dn Type=3
Dn Slope=0.005
Boundary for River Rch & Prof#=UNT 047 in HW,Reach-1,6
Up Type=0
Dn Type=3
Dn Slope=0.005
Boundary for River Rch & Prof#=UNT 047 in HW,Reach-1,7
Up Type=0
Dn Type=3
Dn Slope=0.005

--- UNT 047 in HW.g01 (geometry) ---

Geom Title=Existing Conditions

River Reach=UNT 047 in HW,Reach-1
Reach XY= 30
      1982405.80     13633389.54      1982470.80     13633324.54
      1982470.80     13633144.54      1982490.80     13633104.54
      1982490.80     13633024.54      1982520.80     13632994.54
      1982570.80     13632994.54      1982620.80     13632944.54
      1982640.80     13632944.54      1982650.80     13632934.54
      1982680.80     13632934.54      1982700.80     13632914.54
      1982700.80     13632894.54      1982800.80     13632794.54
      1982800.80     13632784.54      1982870.80     13632714.54
      1982870.80     13632704.54      1982940.80     13632654.54
      1982950.80     13632654.54      1982970.80     13632634.54
      1982970.80     13632604.54      1983000.80     13632574.54
      1983010.80     13632574.54      1983160.80     13632424.54
      1983180.80     13632424.54      1983200.80     13632404.54
      1983260.80     13632404.54      1983300.80     13632384.54
      1983330.80     13632384.54      1983390.80     13632324.54

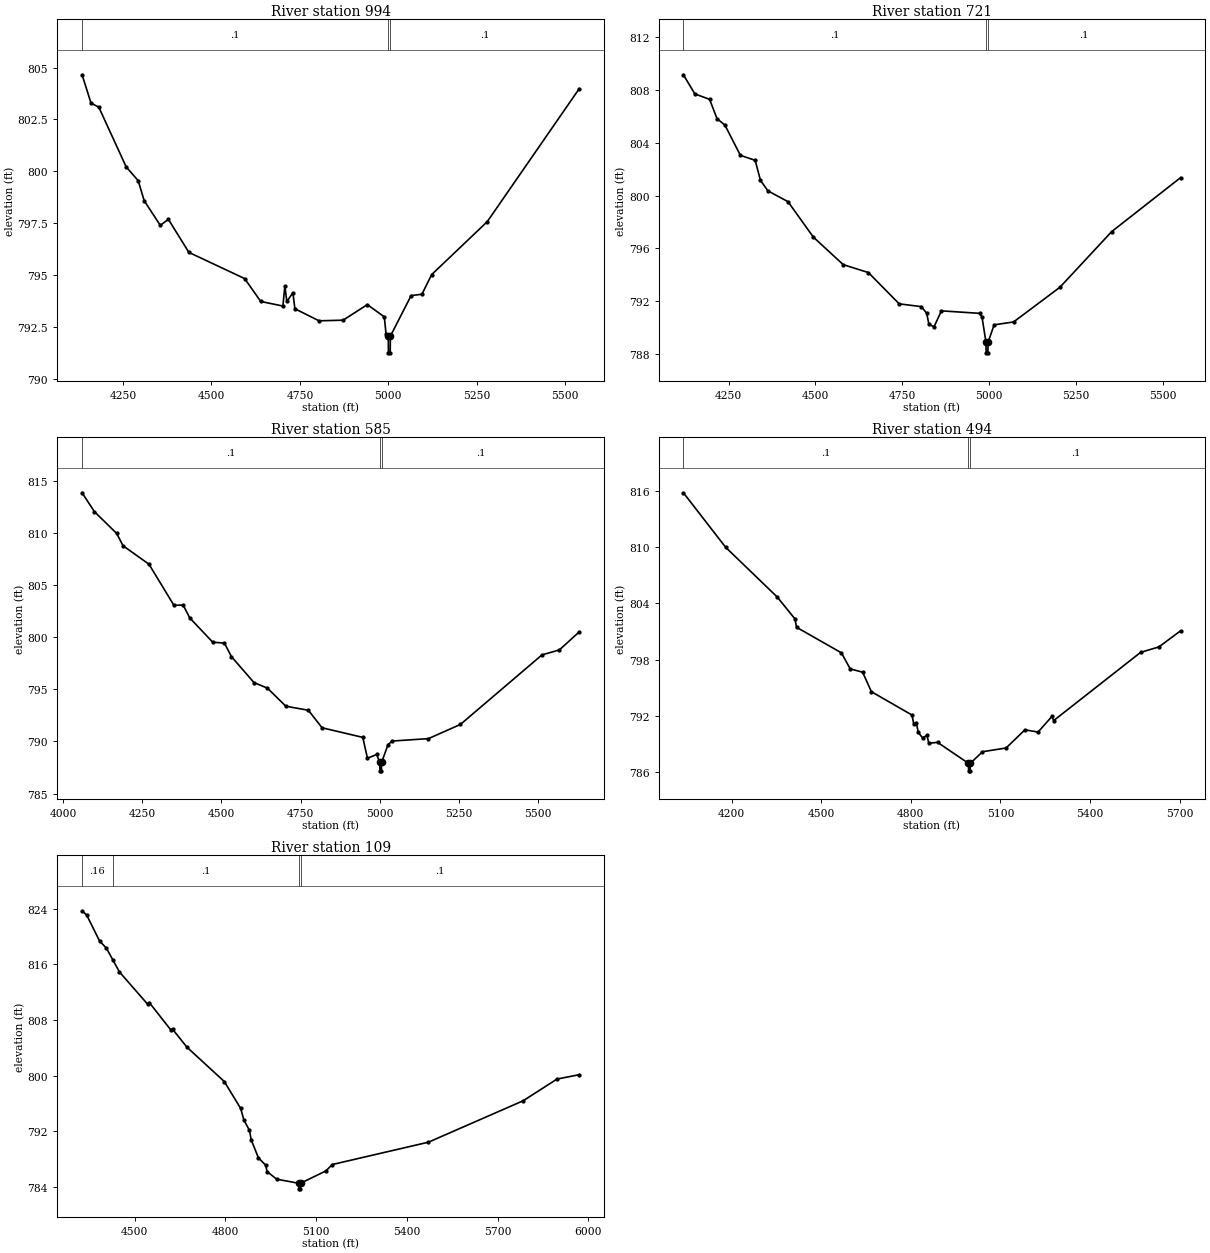
Type RM Length L Ch R = 1,994,273,273,273
BEGIN DESCRIPTION:
UNT 047 in HW 3.0
END DESCRIPTION:
XS GIS Cut Line= 3
      1983477.76     13633275.76      1982797.22     13632952.85
      1982161.81     13632807.02
#Sta/Elev= 30
  4134.3  804.65  4159.5  803.29  4181.6  803.09  4259.0  800.22  4292.8  799.56
  4310.0  798.59  4355.4  797.41  4378.2  797.70  4436.2  796.11  4593.8  794.85
  4639.3  793.75  4701.9  793.53  4707.5  794.49  4713.0  793.75  4730.2  794.17
  4735.8  793.40  4804.0  792.82  4872.2  792.85  4940.5  793.60  4988.5  793.01
  4993.6  792.17  4999.7  792.08  5000.2  791.28  5005.2  791.28  5005.7  792.08
  5064.3  794.03  5095.0  794.10  5122.3  795.04  5279.7  797.59  5539.5  803.98
#Mann=3,-1,0
  4134.3     0.1       0  4999.7    0.07       0  5005.7     0.1       0
Bank Sta=4999.7,5005.7
Exp/Cntr=0.3,0.1

Type RM Length L Ch R = 1,721,136,136,136
BEGIN DESCRIPTION:
UNT 047 in HW 2.0
END DESCRIPTION:
XS GIS Cut Line= 3
      1983616.65     13633168.12      1982925.69     13632741.04
      1982321.54     13632602.16
#Sta/Elev= 30
  4119.8  809.15  4152.7  807.70  4195.2  807.29  4216.5  805.83  4239.3  805.34
  4283.9  803.05  4326.5  802.67  4341.8  801.15  4363.1  800.36  4421.0  799.54
  4494.3  796.85  4580.2  794.77  4652.7  794.17  4741.4  791.80  4805.2  791.59
  4820.6  791.09  4827.1  790.24  4841.9  790.07  4863.1  791.27  4973.8  791.08
  4980.2  790.77  4991.4  788.89  4991.9  788.09  4996.9  788.09  4997.4  788.89
  5014.9  790.21  5071.0  790.43  5204.6  793.06  5353.5  797.27  5552.0  801.36
#Mann=3,-1,0
  4119.8     0.1       0  4991.4    0.07       0  4997.4     0.1       0
Bank Sta=4991.4,4997.4
Exp/Cntr=0.3,0.1

Type RM Length L Ch R = 1,585,91,91,91
BEGIN DESCRIPTION:
Mapping XS dfd1ed07
END DESCRIPTION:
XS GIS Cut Line= 4
      1983793.78     13632997.99      1983394.44     13632963.27
      1982797.22     13632532.71      1982368.36     13632588.05
#Sta/Elev= 30
  4060.2  813.85  4099.1  812.04  4169.4  809.95  4189.5  808.77  4271.3  807.00
  4350.1  803.06  4379.2  803.08  4400.3  801.84  4472.7  799.52  4509.7  799.43
  4531.6  798.14  4602.8  795.65  4645.3  795.11  4703.4  793.38  4774.6  792.99
  4817.9  791.31  4946.4  790.39  4961.1  788.39  4990.5  788.75  4999.8  787.98
  5000.3  787.18  5005.3  787.18  5005.8  787.98  5026.1  789.70  5039.8  790.04
  5153.7  790.27  5254.6  791.63  5512.1  798.30  5567.2  798.78  5629.7  800.51
#Mann=3,-1,0
  4060.2     0.1       0  4999.8    0.07       0  5005.8     0.1       0
Bank Sta=4999.8,5005.8
Exp/Cntr=0.3,0.1

Type RM Length L Ch R = 1,494,385,385,385
BEGIN DESCRIPTION:
Mapping XS 08fa59ac
END DESCRIPTION:
XS GIS Cut Line= 4
      1983845.82     13632956.32      1983477.78     13632925.07
      1982849.31     13632463.27      1982343.68     13632560.24
#Sta/Elev= 30
  4038.7  815.81  4180.0  809.99  4352.7  804.68  4412.3  802.33  4417.2  801.45
  4567.6  798.72  4596.9  797.01  4638.6  796.65  4667.9  794.57  4803.7  792.08
  4809.9  791.09  4818.4  791.28  4824.6  790.23  4839.2  789.64  4853.9  789.90
  4860.1  789.07  4889.4  789.16  4992.9  786.92  4993.4  786.12  4998.4  786.12
  4998.9  786.92  5039.8  788.16  5118.8  788.56  5181.8  790.50  5225.8  790.26
  5272.8  791.95  5277.8  791.48  5569.1  798.77  5630.2  799.35  5702.8  801.07
#Mann=3,-1,0
  4038.7     0.1       0  4992.9    0.07       0  4998.9     0.1       0
Bank Sta=4992.9,4998.9
Exp/Cntr=0.3,0.1

Type RM Length L Ch R = 1,109,0,0,0
BEGIN DESCRIPTION:
UNT 047 in HW 1.0
END DESCRIPTION:
XS GIS Cut Line= 3
      1983929.13     13632643.81      1983054.17     13632279.24
      1982387.50     13632480.63
#Sta/Elev= 30
  4325.9  823.71  4341.2  823.09  4383.5  819.38  4406.2  818.34  4427.4  816.66
  4449.5  814.91  4542.7  810.27  4548.1  810.51  4619.6  806.56  4625.0  806.68
  4672.7  804.09  4796.2  799.15  4850.4  795.28  4861.2  793.60  4879.6  792.11
  4885.0  790.80  4908.9  788.19  4932.7  787.13  4938.1  786.18  4969.5  785.10
  5042.4  784.51  5042.9  783.71  5047.9  783.71  5048.4  784.51  5132.0  786.28
  5153.7  787.21  5471.4  790.42  5784.8  796.38  5896.7  799.50  5970.2  800.13
#Mann=4,-1,0
  4325.9    0.16       0  4427.4     0.1       0  5042.4    0.07       0
  5048.4     0.1       0
Bank Sta=5042.4,5048.4
Exp/Cntr=0.3,0.1

Chan Stop Cuts=-1