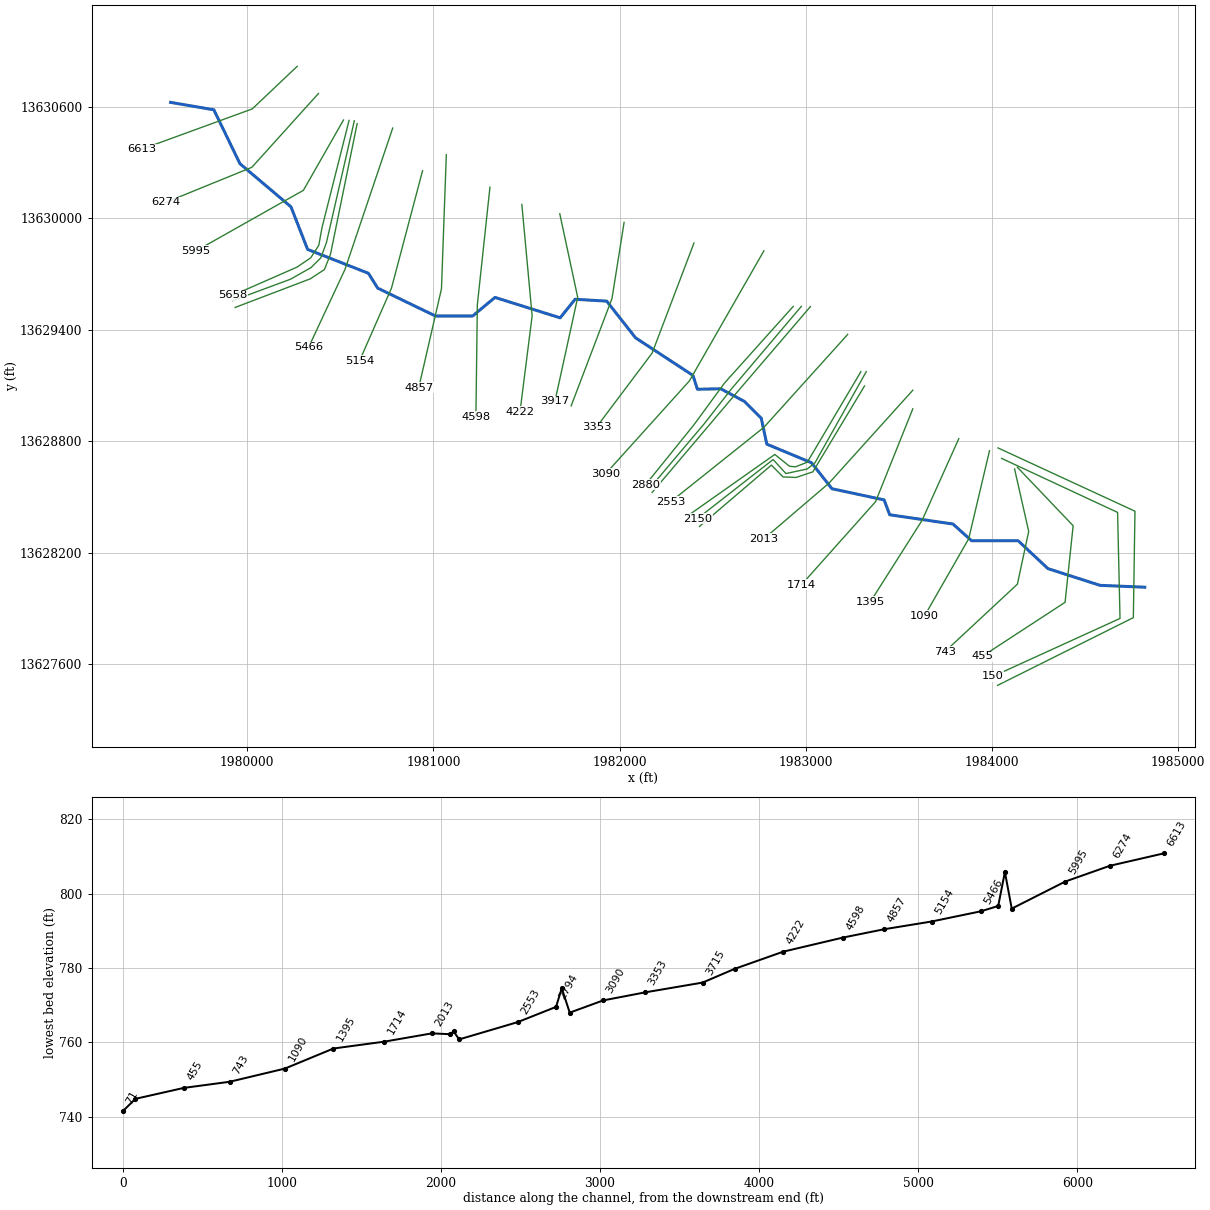
--- UNT 048 in HW.prj (project) ---

Proj Title=UNT 048 in HW Base Level Engineering
Current Plan=p01
Default Exp/Contr=0.3,0.1
English Units
Geom File=g01
Flow File=f01
Plan File=p01
BEGIN DESCRIPTION:
UNT 048 in HW
END DESCRIPTION:

--- UNT 048 in HW.p01 (plan) ---

Plan Title=Multiple Run
Short Identifier=Multiple
Geom File=g01
Flow File=f01
Subcritical Flow
K Sum by GR= 0
Std Step Tol= 0.01
Critical Tol= 0.01
Num of Std Step Trials= 20
Max Error Tol= 0.3
Flow Tol Ratio= 0.001
Split Flow NTrial= 30
Split Flow Tol= 0.02
Split Flow Ratio= 0.02
Log Output Level= 0
Friction Slope Method= 1
Unsteady Friction Slope Method= 2
Unsteady Bridges Friction Slope Method= 1
Parabolic Critical Depth
Global Vel Dist=  1 , 1 , 1
Global Log Level= 0
CheckData=True
Encroach Param= -1, 0, 0, 0
BEGIN DESCRIPTION:
Multiple Run
END DESCRIPTION:

--- UNT 048 in HW.f01 (steady flow) ---

Flow Title=Multiple
Number of Profiles=7
Profile Names=10-year,25-year,50-year,1pct_min,100-year,1pct_plu,500-year
River Rch & RM= UNT 048 in HW,Reach-1,6613
     489     687     852     525    1047    2088    1583
Boundary for River Rch & Prof#=UNT 048 in HW,Reach-1,1
Up Type=0
Dn Type=3
Dn Slope=0.005
Boundary for River Rch & Prof#=UNT 048 in HW,Reach-1,2
Up Type=0
Dn Type=3
Dn Slope=0.005
Boundary for River Rch & Prof#=UNT 048 in HW,Reach-1,3
Up Type=0
Dn Type=3
Dn Slope=0.005
Boundary for River Rch & Prof#=UNT 048 in HW,Reach-1,4
Up Type=0
Dn Type=3
Dn Slope=0.005
Boundary for River Rch & Prof#=UNT 048 in HW,Reach-1,5
Up Type=0
Dn Type=3
Dn Slope=0.005
Boundary for River Rch & Prof#=UNT 048 in HW,Reach-1,6
Up Type=0
Dn Type=3
Dn Slope=0.005
Boundary for River Rch & Prof#=UNT 048 in HW,Reach-1,7
Up Type=0
Dn Type=3
Dn Slope=0.005

--- UNT 048 in HW.g01 (geometry) ---

Geom Title=Existing Conditions

River Reach=UNT 048 in HW,Reach-1
Reach XY= 30
      1979588.53     13630624.54      1979820.80     13630584.54
      1979960.80     13630294.54      1980235.00     13630062.09
      1980324.41     13629832.93      1980650.80     13629704.54
      1980700.80     13629624.54      1981010.80     13629474.54
      1981210.80     13629474.54      1981330.80     13629574.54
      1981680.80     13629464.54      1981760.80     13629564.54
      1981930.80     13629554.54      1982085.69     13629357.06
      1982393.85     13629154.80      1982418.16     13629080.15
      1982543.16     13629082.75      1982670.80     13629014.54
      1982760.80     13628924.54      1982790.80     13628784.54
      1983030.80     13628684.54      1983140.80     13628544.54
      1983420.80     13628484.54      1983450.80     13628404.54
      1983790.80     13628354.54      1983890.80     13628264.54
      1984140.80     13628264.54      1984300.80     13628114.54
      1984580.80     13628024.54      1984820.80     13628014.54

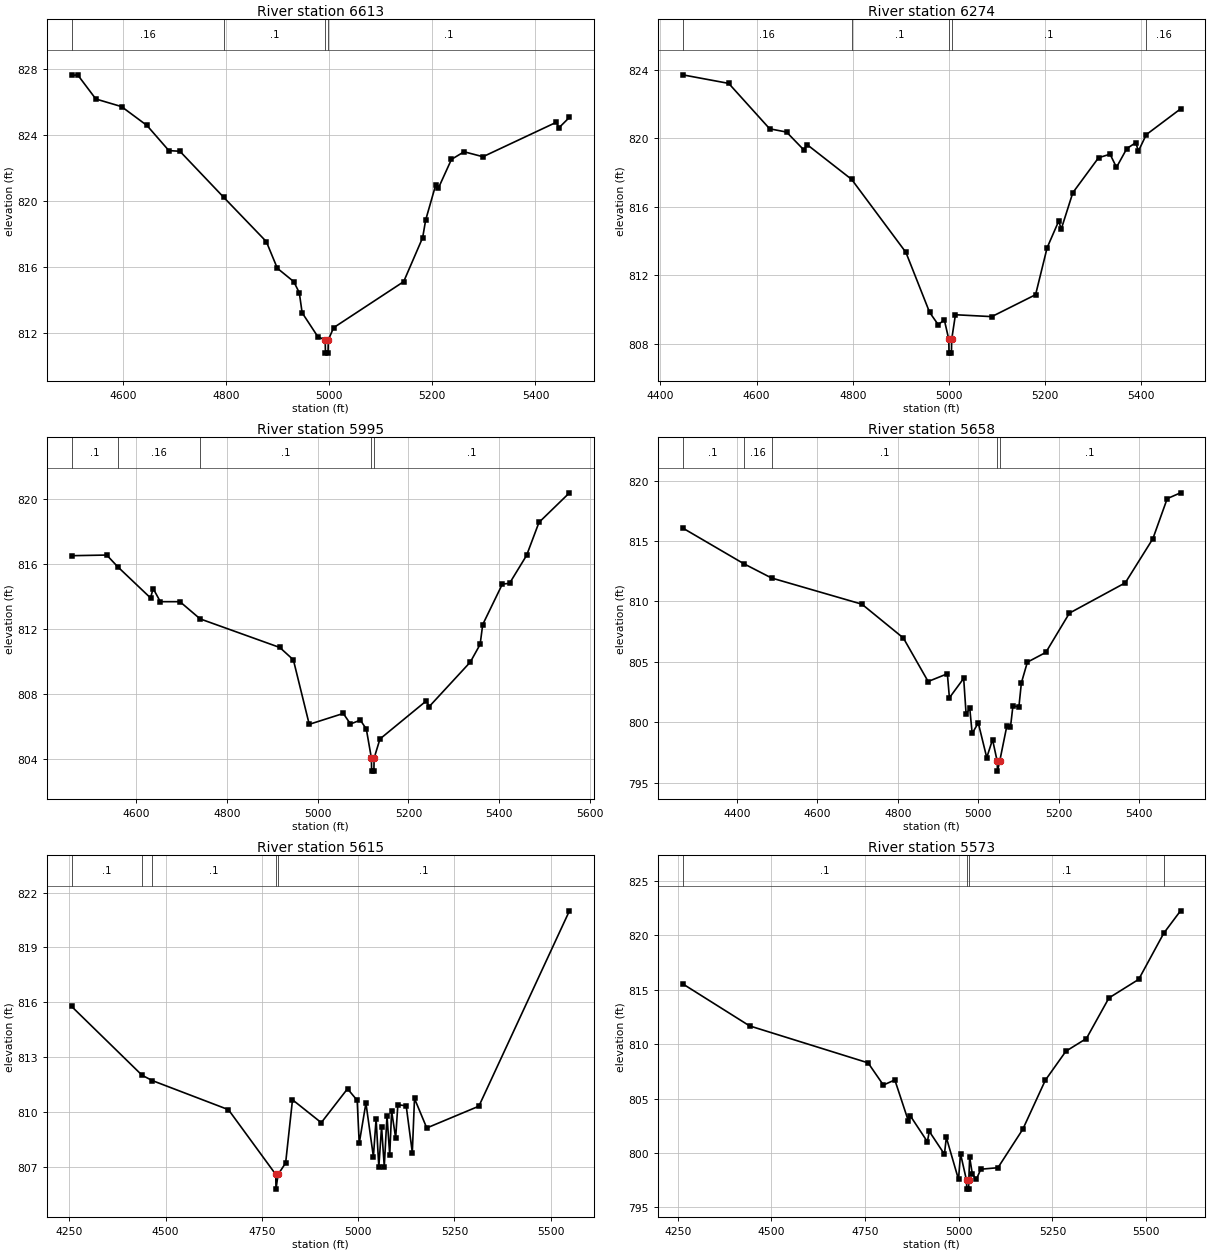
Type RM Length L Ch R = 1,6613,339,339,339
BEGIN DESCRIPTION:
UNT 048 in HW 21.0
END DESCRIPTION:
XS GIS Cut Line= 3
      1980268.31     13630818.42      1980026.95     13630589.22
      1979433.21     13630372.21
#Sta/Elev= 30
  4500.9  827.59  4512.7  827.63  4547.9  826.17  4597.7  825.71  4647.0  824.57
  4689.5  823.05  4710.9  823.01  4795.7  820.23  4878.4  817.55  4899.7  815.94
  4931.6  815.13  4942.3  814.46  4947.8  813.25  4978.3  811.80  4992.5  811.61
  4993.0  810.81  4998.0  810.81  4998.5  811.61  5008.9  812.35  5144.6  815.13
  5181.4  817.79  5187.2  818.85  5206.7  820.98  5212.0  820.79  5237.2  822.52
  5261.7  822.98  5298.3  822.68  5440.3  824.76  5445.6  824.43  5465.9  825.06
#Mann=4,-1,0
  4500.9    0.16       0  4795.7     0.1       0  4992.5    0.07       0
  4998.5     0.1       0
Bank Sta=4992.5,4998.5
Exp/Cntr=0.3,0.1

Type RM Length L Ch R = 1,6274,279,279,279
BEGIN DESCRIPTION:
UNT 048 in HW 20.0
END DESCRIPTION:
XS GIS Cut Line= 3
      1980382.85     13630672.55      1980025.00     13630275.00
      1979561.65     13630085.74
#Sta/Elev= 30
  4446.2  823.71  4542.0  823.21  4627.2  820.56  4662.3  820.37  4698.2  819.33
  4704.9  819.64  4797.6  817.61  4910.5  813.35  4959.8  809.85  4977.7  809.13
  4990.4  809.41  4999.7  808.27  5000.2  807.47  5005.2  807.47  5005.7  808.27
  5013.5  809.71  5089.1  809.60  5180.2  810.88  5204.2  813.62  5228.2  815.17
  5233.6  814.71  5257.6  816.83  5311.1  818.87  5335.1  819.08  5348.4  818.31
  5370.0  819.41  5388.6  819.75  5394.0  819.26  5410.4  820.22  5481.6  821.72
#Mann=5,-1,0
  4446.2    0.16       0  4797.6     0.1       0  4999.7    0.07       0
  5005.7     0.1       0  5410.4    0.16       0
Bank Sta=4999.7,5005.7
Exp/Cntr=0.3,0.1

Type RM Length L Ch R = 1,5995,337,337,337
BEGIN DESCRIPTION:
UNT 048 in HW 19.0
END DESCRIPTION:
XS GIS Cut Line= 3
      1980517.13     13630529.64      1980301.84     13630151.14
      1979725.00     13629825.00
#Sta/Elev= 30
  4457.0  816.51  4534.6  816.55  4558.4  815.84  4631.2  813.91  4636.9  814.49
  4652.8  813.68  4696.0  813.68  4740.6  812.62  4916.3  810.86  4946.2  810.10
  4981.2  806.13  5056.3  806.80  5072.2  806.15  5093.9  806.39  5107.1  805.84
  5118.3  804.05  5118.8  803.25  5123.8  803.25  5124.3  804.05  5137.2  805.23
  5239.7  807.58  5245.4  807.21  5336.4  809.96  5358.1  811.05  5363.8  812.27
  5407.1  814.76  5423.0  814.81  5460.6  816.53  5487.9  818.56  5555.1  820.38
#Mann=5,-1,0
  4457.0     0.1       0  4558.4    0.16       0  4740.6     0.1       0
  5118.3    0.07       0  5124.3     0.1       0
Bank Sta=5118.3,5124.3
Exp/Cntr=0.3,0.1

Type RM Length L Ch R = 1,5658,43,43,43
BEGIN DESCRIPTION:
Mapping XS 54e31606
END DESCRIPTION:
XS GIS Cut Line= 6
      1980547.07     13630527.46      1980401.66     13629950.19
      1980384.30     13629854.70      1980340.90     13629787.43
      1980267.12     13629737.51      1979922.07     13629585.61
#Sta/Elev= 30
  4264.6  816.08  4416.8  813.12  4485.7  811.94  4710.6  809.77  4813.7  806.97
  4875.3  803.37  4923.1  804.01  4928.2  802.02  4963.7  803.63  4969.7  800.68
  4978.9  801.14  4984.8  799.07  5000.0  799.94  5021.1  797.07  5035.5  798.56
  5047.2  796.75  5047.7  795.95  5053.2  796.75  5071.2  799.71  5080.1  799.59
  5086.2  801.34  5101.1  801.28  5107.2  803.25  5122.1  804.97  5168.1  805.78
  5226.7  809.03  5365.7  811.54  5434.3  815.19  5470.0  818.51  5503.1  818.99
#Mann=5,-1,0
  4264.6     0.1       0  4416.8    0.16       0  4485.7     0.1       0
  5047.2    0.07       0  5053.2     0.1       0
Bank Sta=5047.2,5053.2
Exp/Cntr=0.3,0.1

Type RM Length L Ch R = 1,5615,42,42,42
BEGIN DESCRIPTION:
Mapping XS b0358ce5
END DESCRIPTION:
XS GIS Cut Line= 6
      1980575.28     13630525.29      1980425.54     13629869.89
      1980395.15     13629787.43      1980343.07     13629735.34
      1980232.39     13629672.41      1979922.03     13629557.38
#Sta/Elev= 30
  4256.0  815.78  4439.0  812.02  4465.4  811.73  4663.2  810.14  4786.1  806.60
  4786.6  805.80  4792.1  806.60  4811.7  807.23  4829.5  810.68  4904.2  809.43
  4972.3  811.28  4997.4  810.65  5002.7  808.30  5020.1  810.50  5039.5  807.57
  5046.5  809.64  5053.6  807.02  5060.7  809.20  5067.7  807.03  5074.8  809.80
  5081.9  807.66  5086.8  810.06  5097.3  808.60  5103.0  810.41  5124.6  810.35
  5140.5  807.80  5146.2  810.75  5178.0  809.14  5313.3  810.33  5548.4  821.00
#Mann=5,-1,0
  4256.0     0.1       0  4439.0    0.16       0  4465.4     0.1       0
  4786.1    0.07       0  4792.1     0.1       0
Bank Sta=4786.1,4792.1
Exp/Cntr=0.3,0.1

Type RM Length L Ch R = 1,5573,107,107,107
BEGIN DESCRIPTION:
Mapping XS 8f04d765
END DESCRIPTION:
XS GIS Cut Line= 5
      1980590.47     13630510.10      1980447.24     13629806.96
      1980414.68     13629724.49      1980338.73     13629674.58
      1979935.06     13629520.49
#Sta/Elev= 30
  4262.9  815.55  4441.6  811.68  4758.0  808.28  4798.8  806.24  4829.4  806.71
  4865.8  802.91  4870.9  803.40  4916.3  801.03  4921.4  801.98  4961.8  799.88
  4966.9  801.42  4999.4  797.56  5004.8  799.92  5020.8  797.47  5021.3  796.67
  5026.3  796.67  5026.8  797.47  5029.2  799.61  5036.3  798.05  5047.1  797.58
  5058.9  798.50  5104.7  798.64  5171.1  802.18  5231.3  806.69  5286.1  809.35
  5340.9  810.52  5401.0  814.25  5480.5  815.96  5547.5  820.21  5592.1  822.26
#Mann=4,-1,0
  4262.9     0.1       0  5020.8    0.07       0  5026.8     0.1       0
  5547.5    0.16       0
Bank Sta=5020.8,5026.8
Exp/Cntr=0.3,0.1

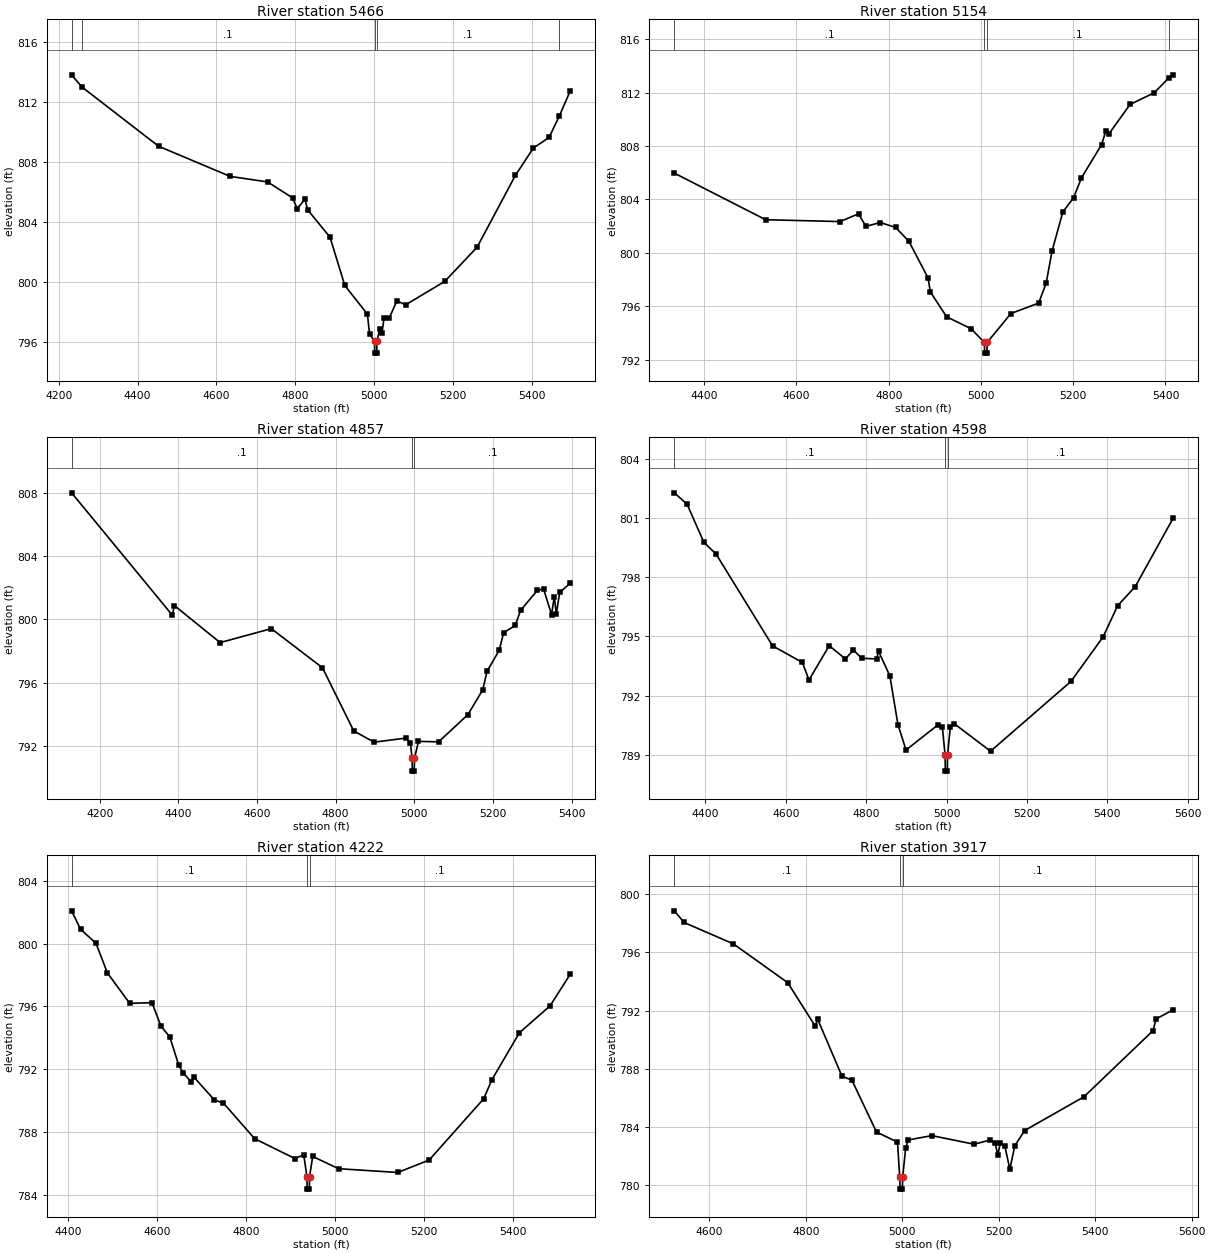
Type RM Length L Ch R = 1,5466,312,312,312
BEGIN DESCRIPTION:
UNT 048 in HW 17.0
END DESCRIPTION:
XS GIS Cut Line= 3
      1980781.45     13630486.25      1980525.00     13629725.00
      1980329.88     13629306.21
#Sta/Elev= 30
  4232.5  813.80  4258.6  812.99  4453.2  809.04  4634.8  807.03  4729.8  806.66
  4793.1  805.60  4804.9  804.87  4824.7  805.52  4831.1  804.81  4888.1  802.98
  4925.6  799.76  4983.0  797.85  4988.5  796.51  5001.1  796.05  5001.6  795.25
  5006.6  795.25  5007.1  796.05  5014.7  796.89  5020.0  796.60  5025.3  797.61
  5038.5  797.59  5057.8  798.74  5079.9  798.47  5179.2  800.03  5261.3  802.31
  5358.3  807.09  5404.1  808.92  5444.0  809.63  5470.2  811.07  5497.8  812.74
#Mann=5,-1,0
  4232.5    0.16       0  4258.6     0.1       0  5001.1    0.07       0
  5007.1     0.1       0  5470.2    0.16       0
Bank Sta=5001.1,5007.1
Exp/Cntr=0.3,0.1

Type RM Length L Ch R = 1,5154,297,297,297
BEGIN DESCRIPTION:
UNT 048 in HW 16.0
END DESCRIPTION:
XS GIS Cut Line= 3
      1980941.77     13630256.53      1980775.00     13629625.00
      1980603.22     13629233.07
#Sta/Elev= 30
  4335.4  805.97  4533.2  802.48  4694.3  802.34  4734.6  802.92  4750.7  801.98
  4781.7  802.27  4815.1  801.90  4843.8  800.86  4885.1  798.13  4890.5  797.06
  4925.6  795.20  4978.2  794.32  5007.4  793.28  5007.9  792.48  5012.9  792.48
  5013.4  793.28  5065.0  795.45  5125.1  796.23  5141.4  797.73  5154.2  800.14
  5177.5  803.06  5200.9  804.13  5217.9  805.62  5261.5  808.11  5271.0  809.16
  5276.5  808.87  5323.2  811.12  5375.4  811.99  5407.9  813.13  5416.5  813.34
#Mann=4,-1,0
  4335.4     0.1       0  5007.4    0.07       0  5013.4     0.1       0
  5407.9    0.16       0
Bank Sta=5007.4,5013.4
Exp/Cntr=0.3,0.1

Type RM Length L Ch R = 1,4857,259,259,259
BEGIN DESCRIPTION:
UNT 048 in HW 15.0
END DESCRIPTION:
XS GIS Cut Line= 3
      1981069.37     13630342.46      1981043.33     13629621.11
      1980921.25     13629088.64
#Sta/Elev= 30
  4128.7  807.99  4384.9  800.26  4389.9  800.87  4506.4  798.53  4636.5  799.41
  4766.6  796.94  4846.1  792.95  4897.8  792.24  4979.9  792.50  4990.2  792.17
  4994.5  791.21  4995.0  790.41  5000.0  790.41  5000.5  791.21  5010.7  792.29
  5062.0  792.26  5136.4  793.98  5174.2  795.55  5185.1  796.72  5215.9  798.04
  5227.3  799.16  5256.9  799.61  5270.2  800.56  5313.1  801.83  5328.7  801.92
  5349.2  800.30  5356.0  801.44  5361.1  800.34  5369.8  801.70  5396.8  802.28
#Mann=3,-1,0
  4128.7     0.1       0  4994.5    0.07       0  5000.5     0.1       0
Bank Sta=4994.5,5000.5
Exp/Cntr=0.3,0.1

Type RM Length L Ch R = 1,4598,376,376,376
BEGIN DESCRIPTION:
UNT 048 in HW 14.0
END DESCRIPTION:
XS GIS Cut Line= 3
      1981303.75     13630168.02      1981236.04     13629535.17
      1981228.23     13628930.98
#Sta/Elev= 30
  4322.9  802.28  4354.6  801.70  4396.3  799.77  4426.5  799.18  4567.3  794.52
  4641.4  793.68  4657.8  792.79  4708.1  794.53  4748.3  793.86  4768.5  794.31
  4788.6  793.89  4826.0  793.86  4831.0  794.24  4859.0  793.00  4879.1  790.53
  4899.2  789.24  4979.5  790.53  4989.5  790.42  4996.5  788.97  4997.0  788.17
  5002.0  788.17  5002.5  788.97  5009.5  790.43  5019.5  790.57  5109.5  789.18
  5309.6  792.72  5389.6  794.98  5425.5  796.55  5469.6  797.53  5563.6  800.99
#Mann=3,-1,0
  4322.9     0.1       0  4996.5    0.07       0  5002.5     0.1       0
Bank Sta=4996.5,5002.5
Exp/Cntr=0.3,0.1

Type RM Length L Ch R = 1,4222,305,305,305
BEGIN DESCRIPTION:
UNT 048 in HW 13.0
END DESCRIPTION:
XS GIS Cut Line= 3
      1981475.00     13630075.03      1981530.31     13629475.27
      1981465.23     13628959.87
#Sta/Elev= 30
  4407.0  802.09  4427.1  800.92  4461.9  800.02  4487.4  798.14  4537.6  796.20
  4587.8  796.24  4607.9  794.76  4628.0  794.05  4648.1  792.25  4658.1  791.77
  4676.2  791.20  4681.2  791.53  4728.4  790.04  4748.5  789.85  4818.8  787.58
  4909.2  786.32  4929.2  786.55  4936.3  785.17  4936.8  784.37  4941.8  784.37
  4942.3  785.17  4949.3  786.45  5007.6  785.67  5140.6  785.43  5211.2  786.22
  5334.1  790.13  5352.3  791.33  5414.4  794.33  5483.3  796.04  5528.8  798.06
#Mann=3,-1,0
  4407.0     0.1       0  4936.3    0.07       0  4942.3     0.1       0
Bank Sta=4936.3,4942.3
Exp/Cntr=0.3,0.1

Type RM Length L Ch R = 1,3917,202,202,202
BEGIN DESCRIPTION:
UNT 048 in HW 12.0
END DESCRIPTION:
XS GIS Cut Line= 3
      1981678.74     13630024.79      1981775.00     13629575.00
      1981652.71     13629014.36
#Sta/Elev= 30
  4527.7  798.84  4547.9  798.04  4650.2  796.57  4762.7  793.91  4819.7  790.93
  4824.8  791.40  4875.2  787.49  4895.6  787.23  4946.8  783.66  4990.2  782.98
  4994.9  780.55  4995.4  779.75  5000.4  779.75  5000.9  780.55  5007.1  782.55
  5012.2  783.12  5061.3  783.42  5149.1  782.83  5182.1  783.12  5192.4  782.93
  5198.2  782.10  5203.3  782.92  5212.9  782.68  5223.1  781.12  5233.3  782.72
  5253.8  783.77  5376.6  786.08  5519.9  790.62  5526.2  791.42  5561.5  792.05
#Mann=3,-1,0
  4527.7     0.1       0  4994.9    0.07       0  5000.9     0.1       0
Bank Sta=4994.9,5000.9
Exp/Cntr=0.3,0.1

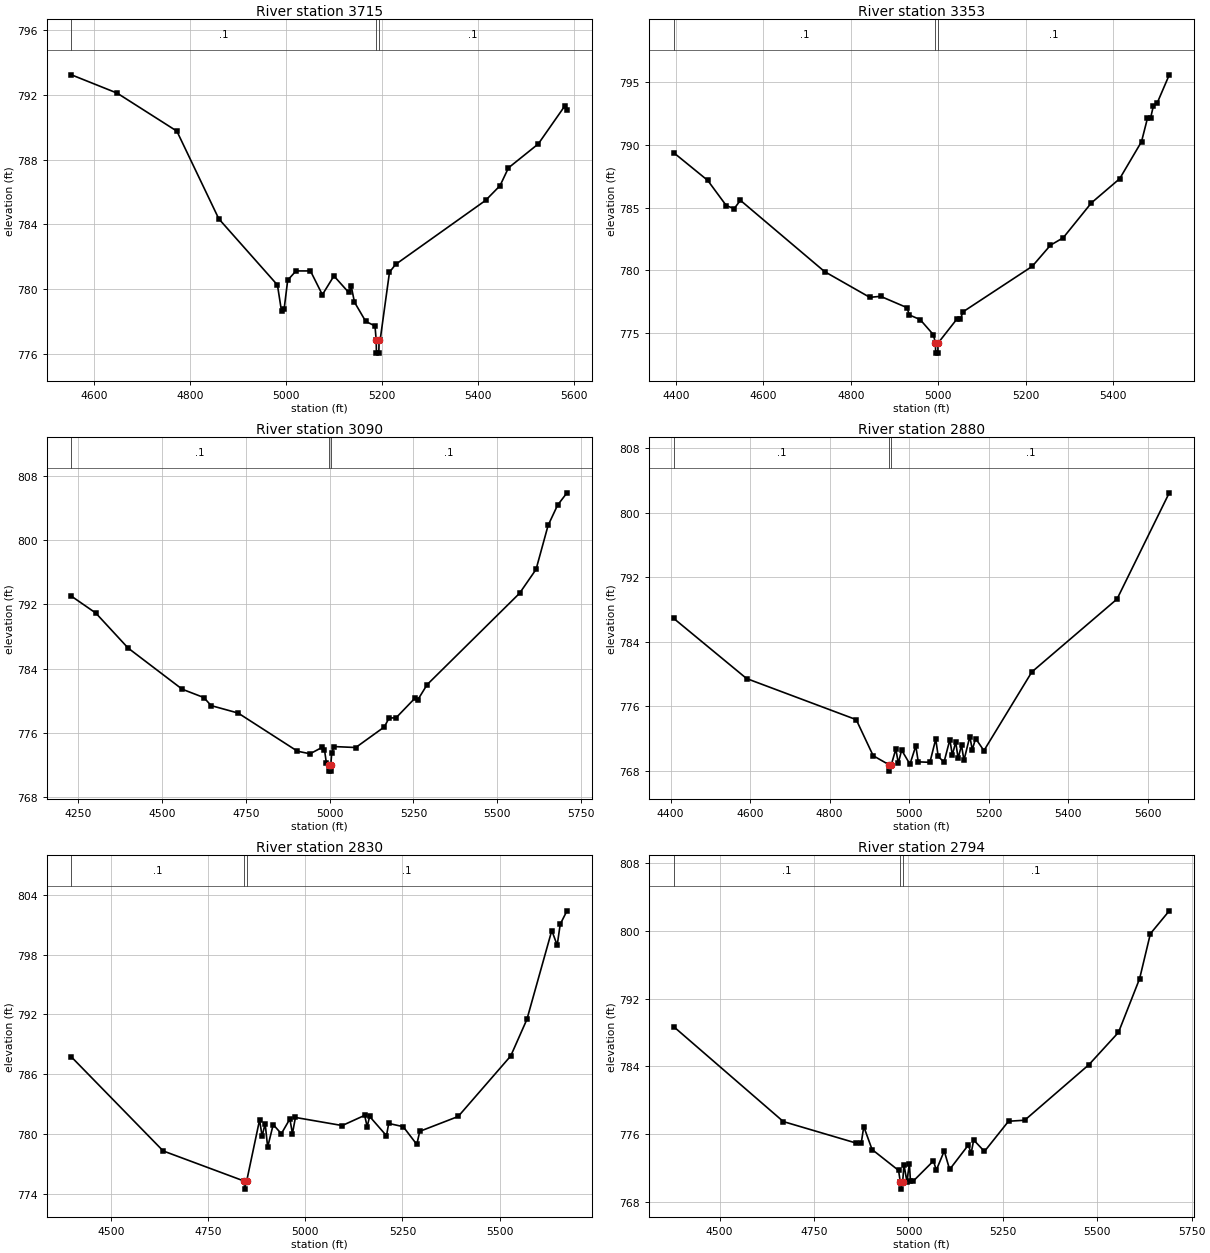
Type RM Length L Ch R = 1,3715,362,362,362
BEGIN DESCRIPTION:
UNT 048 in HW 11.0
END DESCRIPTION:
XS GIS Cut Line= 3
      1982024.23     13629978.30      1981959.13     13629568.16
      1981739.96     13628990.94
#Sta/Elev= 30
  4552.2  793.25  4647.4  792.12  4771.9  789.77  4859.3  784.35  4981.5  780.26
  4990.0  778.64  4995.4  778.77  5002.9  780.56  5020.2  781.13  5050.3  781.13
  5075.1  779.66  5099.2  780.82  5130.0  779.80  5135.4  780.17  5142.0  779.20
  5165.5  778.01  5184.8  777.73  5187.3  776.85  5187.8  776.05  5192.8  776.05
  5193.3  776.85  5195.6  776.87  5215.0  781.05  5227.6  781.53  5415.3  785.49
  5445.4  786.40  5462.9  787.50  5525.1  788.98  5580.0  791.31  5584.9  791.06
#Mann=3,-1,0
  4552.2     0.1       0  5187.3    0.07       0  5193.3     0.1       0
Bank Sta=5187.3,5193.3
Exp/Cntr=0.3,0.1

Type RM Length L Ch R = 1,3353,263,263,263
BEGIN DESCRIPTION:
UNT 048 in HW 10.0
END DESCRIPTION:
XS GIS Cut Line= 3
      1982399.68     13629867.68      1982175.00     13629275.00
      1981875.02     13628875.03
#Sta/Elev= 30
  4394.8  789.36  4472.5  787.16  4515.3  785.14  4533.2  784.92  4547.4  785.57
  4739.9  779.90  4843.4  777.85  4868.2  777.93  4928.5  777.03  4933.8  776.45
  4958.6  776.08  4988.8  774.88  4993.6  774.21  4994.1  773.41  4999.1  773.41
  4999.6  774.21  5042.2  776.10  5050.5  776.11  5056.8  776.70  5215.1  780.32
  5256.8  782.00  5285.9  782.59  5350.5  785.37  5415.1  787.29  5465.1  790.24
  5478.6  792.09  5485.9  792.13  5492.2  793.08  5500.5  793.28  5528.6  795.56
#Mann=3,-1,0
  4394.8     0.1       0  4993.6    0.07       0  4999.6     0.1       0
Bank Sta=4993.6,4999.6
Exp/Cntr=0.3,0.1

Type RM Length L Ch R = 1,3090,210,210,210
BEGIN DESCRIPTION:
UNT 048 in HW 9.0
END DESCRIPTION:
XS GIS Cut Line= 3
      1982775.02     13629825.04      1982375.00     13629125.00
      1981925.03     13628625.04
#Sta/Elev= 30
  4229.3  793.03  4302.0  790.93  4398.5  786.57  4559.8  781.45  4624.5  780.41
  4646.1  779.41  4726.8  778.48  4903.8  773.73  4941.3  773.41  4978.0  774.22
  4984.5  773.92  4990.2  772.22  4997.3  772.05  4997.8  771.25  5002.8  771.25
  5003.3  772.05  5006.1  773.48  5012.5  774.31  5077.8  774.19  5163.0  776.75
  5177.2  777.86  5198.1  777.89  5254.9  780.35  5262.4  780.09  5290.8  782.02
  5566.6  793.39  5615.9  796.37  5651.8  801.84  5680.2  804.37  5708.2  805.90
#Mann=3,-1,0
  4229.3     0.1       0  4997.3    0.07       0  5003.3     0.1       0
Bank Sta=4997.3,5003.3
Exp/Cntr=0.3,0.1

Type RM Length L Ch R = 1,2880,50,50,50
BEGIN DESCRIPTION:
Mapping XS 5bd0f2ac
END DESCRIPTION:
XS GIS Cut Line= 4
      1982932.67     13629526.07      1982563.73     13629113.73
      1982398.80     13628888.03      1982139.21     13628565.71
#Sta/Elev= 30
  4407.8  786.88  4591.1  779.43  4866.9  774.34  4909.6  769.87  4949.2  768.76
  4949.7  767.96  4955.2  768.76  4966.6  770.69  4972.8  768.95  4981.2  770.56
  5002.1  768.82  5016.8  771.08  5023.0  769.11  5052.3  769.05  5067.0  771.93
  5073.2  769.78  5087.8  769.07  5102.5  771.86  5108.7  769.96  5117.2  771.56
  5123.3  769.56  5131.8  771.17  5138.0  769.30  5152.7  772.25  5158.9  770.62
  5167.3  772.00  5188.2  770.50  5308.8  780.25  5523.1  789.28  5654.5  802.44
#Mann=3,-1,0
  4407.8     0.1       0  4949.2    0.07       0  4955.2     0.1       0
Bank Sta=4949.2,4955.2
Exp/Cntr=0.3,0.1

Type RM Length L Ch R = 1,2830,36,36,36
BEGIN DESCRIPTION:
Mapping XS 79cf0173
END DESCRIPTION:
XS GIS Cut Line= 4
      1982976.07     13629526.07      1982598.45     13629079.01
      1982453.05     13628892.38      1982160.08     13628545.15
#Sta/Elev= 30
  4397.5  787.75  4633.7  778.35  4842.7  775.33  4843.2  774.53  4848.7  775.33
  4882.0  781.46  4888.5  779.82  4896.3  781.09  4902.8  778.74  4917.1  780.99
  4938.0  780.07  4960.0  781.55  4966.6  780.08  4974.3  781.70  5094.8  780.89
  5152.6  781.91  5159.0  780.77  5165.4  781.80  5208.8  779.87  5214.5  781.10
  5251.8  780.78  5286.9  779.00  5294.4  780.31  5393.5  781.80  5528.7  787.85
  5570.4  791.51  5634.5  800.40  5648.4  798.93  5656.2  801.03  5673.6  802.37
#Mann=3,-1,0
  4397.5     0.1       0  4842.7    0.07       0  4848.7     0.1       0
Bank Sta=4842.7,4848.7
Exp/Cntr=0.3,0.1

Type RM Length L Ch R = 1,2794,241,241,241
BEGIN DESCRIPTION:
UNT 048 in HW 8.0
END DESCRIPTION:
XS GIS Cut Line= 3
      1983024.99     13629524.99      1982616.25     13629046.89
      1982175.02     13628525.02
#Sta/Elev= 30
  4378.3  788.70  4668.6  777.49  4860.8  774.96  4875.0  774.97  4881.6  776.90
  4903.6  774.19  4973.8  771.72  4978.5  770.31  4979.0  769.51  4984.5  770.31
  4988.1  772.41  4995.8  770.40  5002.4  772.53  5005.3  770.42  5011.8  770.42
  5066.1  772.84  5073.8  771.76  5094.7  774.02  5109.0  771.83  5158.4  774.71
  5166.1  773.76  5172.7  775.32  5201.2  773.96  5265.0  777.53  5307.8  777.65
  5478.1  784.22  5556.2  788.03  5612.2  794.38  5640.7  799.69  5690.7  802.39
#Mann=3,-1,0
  4378.3     0.1       0  4978.5    0.07       0  4984.5     0.1       0
Bank Sta=4978.5,4984.5
Exp/Cntr=0.3,0.1

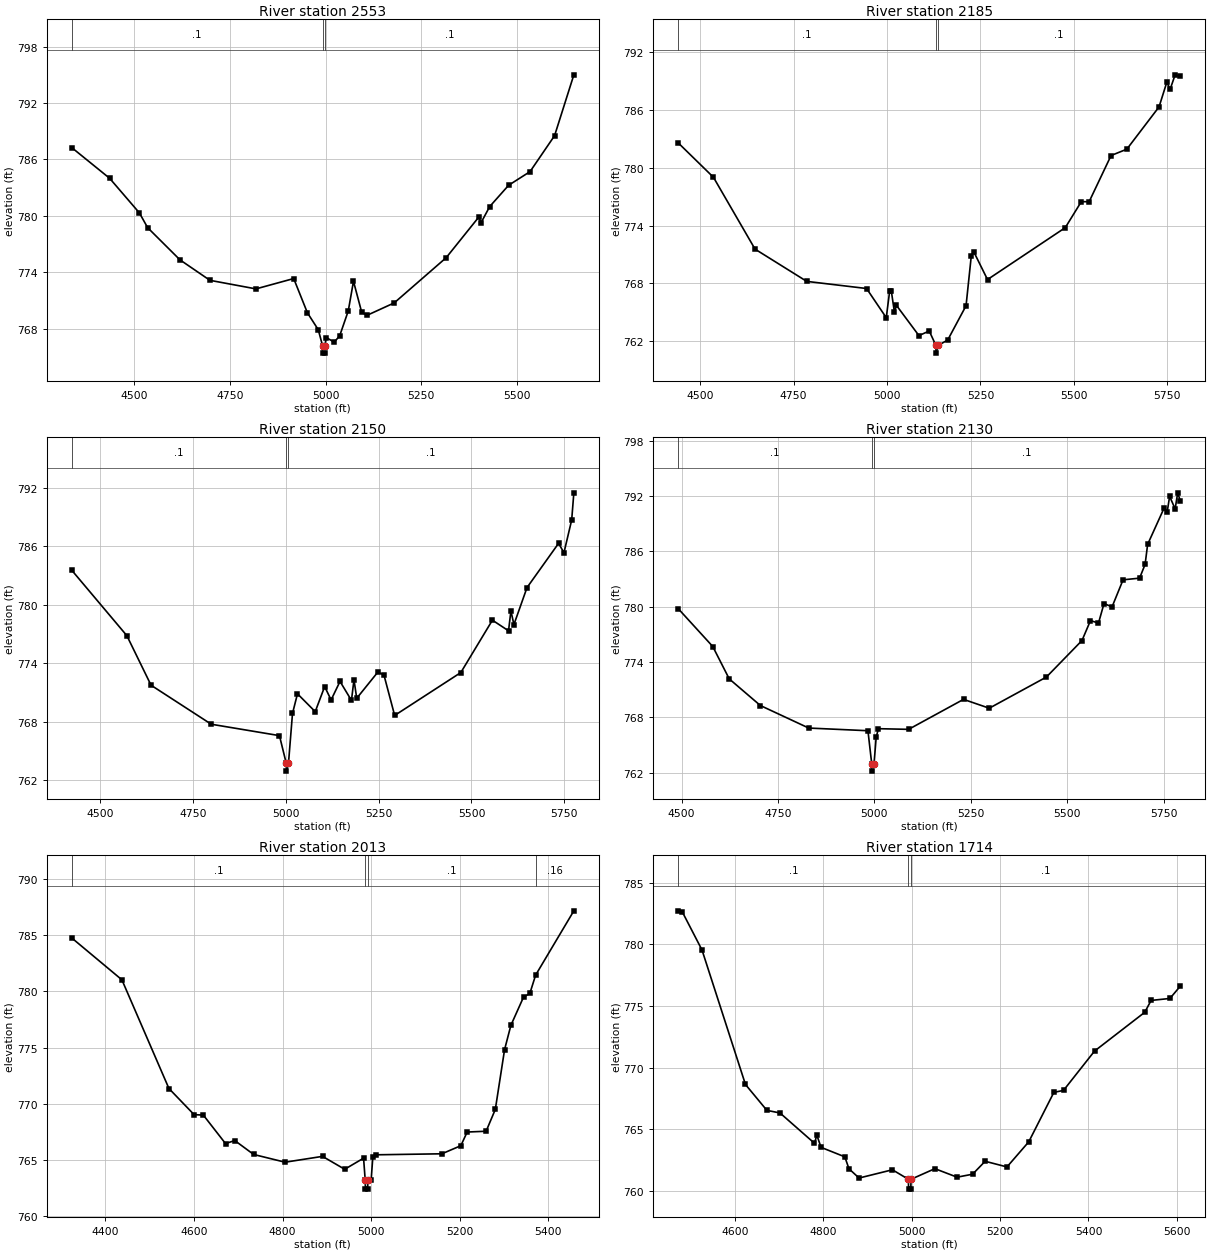
Type RM Length L Ch R = 1,2553,368,368,368
BEGIN DESCRIPTION:
UNT 048 in HW 7.0
END DESCRIPTION:
XS GIS Cut Line= 3
      1983224.99     13629374.99      1982775.00     13628875.00
      1982274.98     13628474.99
#Sta/Elev= 30
  4336.0  787.26  4435.0  784.00  4512.8  780.32  4534.4  778.75  4618.9  775.33
  4697.4  773.15  4817.7  772.24  4916.4  773.34  4952.2  769.70  4980.6  767.90
  4991.8  766.21  4992.3  765.41  4997.3  765.41  4997.8  766.21  5001.6  767.07
  5022.3  766.57  5036.7  767.26  5059.1  769.90  5072.7  773.05  5094.3  769.74
  5108.7  769.44  5179.2  770.75  5315.2  775.56  5400.1  779.86  5406.5  779.29
  5428.9  780.99  5478.5  783.26  5534.5  784.71  5598.6  788.53  5649.0  795.00
#Mann=3,-1,0
  4336.0     0.1       0  4991.8    0.07       0  4997.8     0.1       0
Bank Sta=4991.8,4997.8
Exp/Cntr=0.3,0.1

Type RM Length L Ch R = 1,2185,35,35,35
BEGIN DESCRIPTION:
Mapping XS 6082f129
END DESCRIPTION:
XS GIS Cut Line= 6
      1983295.93     13629174.49      1983008.17     13628687.51
      1982945.67     13628662.77      1982913.12     13628665.38
      1982833.70     13628729.18      1982363.62     13628397.13
#Sta/Elev= 30
  4441.4  782.59  4535.6  779.02  4646.9  771.56  4785.3  768.21  4945.3  767.47
  4998.0  764.44  5007.0  767.17  5011.7  767.17  5019.8  765.03  5025.4  765.71
  5085.4  762.58  5113.0  763.06  5130.8  761.56  5131.3  760.76  5136.8  761.56
  5162.4  762.12  5211.5  765.68  5225.6  770.89  5232.2  771.28  5268.9  768.40
  5477.0  773.79  5519.9  776.49  5540.8  776.48  5599.5  781.28  5641.7  781.94
  5727.9  786.33  5748.8  788.91  5757.5  788.15  5770.9  789.66  5784.8  789.49
#Mann=3,-1,0
  4441.4     0.1       0  5130.8    0.07       0  5136.8     0.1       0
Bank Sta=5130.8,5136.8
Exp/Cntr=0.3,0.1

Type RM Length L Ch R = 1,2150,20,20,20
BEGIN DESCRIPTION:
UNT 048 in HW 6.0
END DESCRIPTION:
XS GIS Cut Line= 6
      1983325.02     13629175.04      1983049.84     13628684.91
      1983008.17     13628651.06      1982893.59     13628626.32
      1982824.58     13628701.84      1982418.54     13628384.01
#Sta/Elev= 30
  4424.1  783.53  4572.4  776.82  4637.5  771.74  4799.5  767.74  4983.1  766.57
  5001.4  763.73  5001.9  762.93  5007.4  763.73  5018.2  768.84  5031.6  770.86
  5079.4  769.03  5104.8  771.60  5122.1  770.23  5146.1  772.13  5176.9  770.18
  5183.7  772.30  5191.1  770.40  5247.8  773.08  5264.3  772.80  5293.2  768.64
  5471.3  773.04  5556.3  778.41  5599.7  777.32  5606.1  779.36  5614.2  777.96
  5649.4  781.75  5734.4  786.29  5748.9  785.33  5769.7  788.69  5775.5  791.47
#Mann=3,-1,0
  4424.1     0.1       0  5001.4    0.07       0  5007.4     0.1       0
Bank Sta=5001.4,5007.4
Exp/Cntr=0.3,0.1

Type RM Length L Ch R = 1,2130,117,117,117
BEGIN DESCRIPTION:
Mapping XS 7bdd5a40
END DESCRIPTION:
XS GIS Cut Line= 6
      1983315.46     13629097.67      1983038.12     13628635.43
      1982948.28     13628605.48      1982877.97     13628608.09
      1982815.47     13628671.89      1982429.37     13628341.69
#Sta/Elev= 30
  4491.4  779.77  4580.9  775.67  4623.6  772.16  4704.4  769.27  4829.7  766.83
  4983.2  766.54  4993.0  762.96  4993.5  762.16  4999.0  762.96  5004.6  765.85
  5010.4  766.76  5088.7  766.69  5231.0  769.94  5297.7  768.98  5445.9  772.36
  5538.1  776.32  5560.1  778.48  5580.9  778.21  5595.2  780.33  5616.0  779.96
  5644.6  782.90  5687.4  783.08  5701.7  784.57  5708.3  786.74  5751.1  790.69
  5758.8  790.21  5765.3  791.95  5779.6  790.58  5786.2  792.33  5793.0  791.45
#Mann=3,-1,0
  4491.4     0.1       0  4993.0    0.07       0  4999.0     0.1       0
Bank Sta=4993,4999
Exp/Cntr=0.3,0.1

Type RM Length L Ch R = 1,2013,299,299,299
BEGIN DESCRIPTION:
UNT 048 in HW 5.0
END DESCRIPTION:
XS GIS Cut Line= 3
      1983575.01     13629075.01      1983125.00     13628575.00
      1982774.98     13628274.98
#Sta/Elev= 30
  4324.0  784.77  4437.2  781.04  4543.4  771.35  4600.2  769.02  4621.1  768.98
  4671.2  766.44  4692.1  766.71  4734.7  765.47  4805.7  764.78  4890.2  765.30
  4940.3  764.15  4982.9  765.14  4986.6  763.18  4987.1  762.38  4992.1  762.38
  4992.6  763.18  5000.0  763.19  5003.8  765.25  5010.4  765.44  5159.7  765.53
  5202.5  766.25  5216.8  767.47  5259.6  767.54  5280.4  769.49  5301.3  774.82
  5315.5  776.98  5344.1  779.50  5358.3  779.82  5371.4  781.46  5457.7  787.19
#Mann=4,-1,0
  4324.0     0.1       0  4986.6    0.07       0  4992.6     0.1       0
  5371.4    0.16       0
Bank Sta=4986.6,4992.6
Exp/Cntr=0.3,0.1

Type RM Length L Ch R = 1,1714,319,319,319
BEGIN DESCRIPTION:
UNT 048 in HW 4.0
END DESCRIPTION:
XS GIS Cut Line= 3
      1983574.98     13628974.96      1983375.00     13628475.00
      1982977.77     13628028.63
#Sta/Elev= 30
  4471.8  782.73  4481.2  782.63  4525.6  779.55  4623.9  768.64  4672.4  766.54
  4702.0  766.33  4780.1  763.87  4785.4  764.53  4794.9  763.54  4848.7  762.77
  4858.1  761.80  4881.0  761.05  4956.4  761.72  4992.5  760.95  4993.0  760.15
  4998.0  760.15  4998.5  760.95  5052.5  761.81  5102.7  761.12  5137.8  761.36
  5166.2  762.41  5215.6  761.95  5264.9  763.99  5321.7  768.00  5343.5  768.16
  5413.7  771.35  5527.4  774.50  5541.7  775.46  5584.3  775.62  5607.8  776.62
#Mann=3,-1,0
  4471.8     0.1       0  4992.5    0.07       0  4998.5     0.1       0
Bank Sta=4992.5,4998.5
Exp/Cntr=0.3,0.1

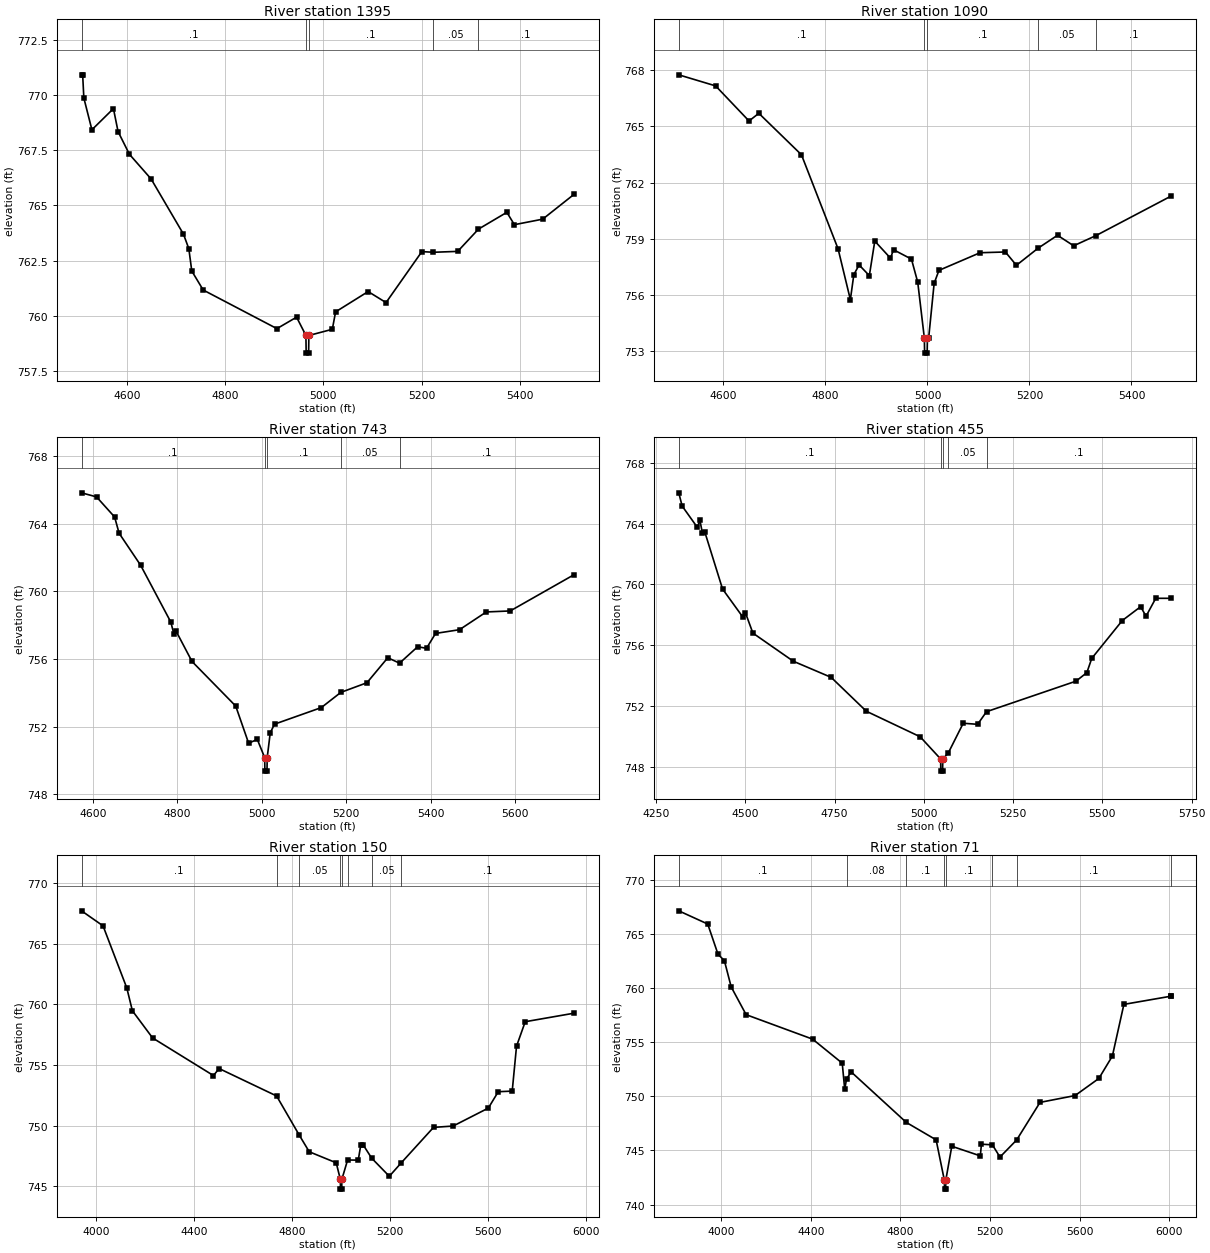
Type RM Length L Ch R = 1,1395,305,305,305
BEGIN DESCRIPTION:
UNT 048 in HW 3.0
END DESCRIPTION:
XS GIS Cut Line= 3
      1983821.97     13628814.23      1983625.00     13628375.00
      1983346.72     13627935.34
#Sta/Elev= 30
  4508.0  770.92  4510.3  770.92  4512.7  769.87  4529.1  768.43  4572.9  769.39
  4582.3  768.35  4605.4  767.32  4649.6  766.20  4715.4  763.70  4726.3  763.04
  4732.3  762.03  4755.5  761.17  4905.5  759.42  4945.5  759.94  4964.5  759.11
  4965.0  758.31  4970.0  758.31  4970.5  759.11  5018.2  759.39  5024.9  760.18
  5091.1  761.10  5127.5  760.60  5200.4  762.91  5224.0  762.88  5273.3  762.92
  5315.6  763.93  5373.3  764.69  5388.6  764.13  5446.2  764.38  5509.7  765.50
#Mann=5,-1,0
  4508.0     0.1       0  4964.5    0.07       0  4970.5     0.1       0
  5224.0    0.05       0  5315.6     0.1       0
Bank Sta=4964.5,4970.5
Exp/Cntr=0.3,0.1

Type RM Length L Ch R = 1,1090,347,347,347
BEGIN DESCRIPTION:
UNT 048 in HW 2.0
END DESCRIPTION:
XS GIS Cut Line= 3
      1983986.91     13628749.14      1983875.00     13628275.00
      1983637.69     13627859.69
#Sta/Elev= 30
  4512.3  767.74  4584.6  767.15  4650.1  765.28  4669.3  765.69  4752.9  763.48
  4824.8  758.46  4848.8  755.76  4855.6  757.09  4865.9  757.61  4886.0  757.04
  4896.7  758.88  4927.5  757.97  4933.4  758.42  4968.6  757.92  4980.9  756.69
  4993.9  753.71  4994.4  752.91  4999.4  752.91  4999.9  753.71  5002.3  753.71
  5013.1  756.63  5022.5  757.32  5103.1  758.26  5152.8  758.30  5174.4  757.59
  5216.8  758.50  5255.0  759.19  5286.7  758.63  5330.2  759.17  5477.8  761.28
#Mann=5,-1,0
  4512.3     0.1       0  4993.9    0.07       0  4999.9     0.1       0
  5216.8    0.05       0  5330.2     0.1       0
Bank Sta=4993.9,4999.9
Exp/Cntr=0.3,0.1

Type RM Length L Ch R = 1,743,288,288,288
BEGIN DESCRIPTION:
Mapping XS 5c4c91f1
END DESCRIPTION:
XS GIS Cut Line= 4
      1984121.46     13628651.45      1984197.41     13628315.12
      1984136.65     13628030.83      1983748.17     13627668.40
#Sta/Elev= 30
  4572.8  765.83  4608.3  765.59  4651.2  764.40  4661.8  763.44  4712.7  761.55
  4784.4  758.18  4791.4  757.50  4796.5  757.66  4834.6  755.85  4938.2  753.21
  4968.8  751.01  4989.3  751.24  5006.8  750.16  5007.3  749.36  5012.3  749.36
  5012.8  750.16  5020.0  751.63  5030.2  752.14  5141.0  753.12  5187.3  754.02
  5249.1  754.59  5298.5  756.07  5326.4  755.75  5369.3  756.72  5390.3  756.63
  5411.8  757.51  5468.5  757.73  5532.0  758.78  5588.7  758.84  5739.6  760.98
#Mann=5,-1,0
  4572.8     0.1       0  5006.8    0.07       0  5012.8     0.1       0
  5187.3    0.05       0  5326.4     0.1       0
Bank Sta=5006.8,5012.8
Exp/Cntr=0.3,0.1

Type RM Length L Ch R = 1,455,305,305,305
BEGIN DESCRIPTION:
Mapping XS a6d3e224
END DESCRIPTION:
XS GIS Cut Line= 4
      1984136.61     13628660.21      1984436.13     13628345.50
      1984392.72     13627933.17      1983948.89     13627643.06
#Sta/Elev= 30
  4313.2  766.02  4322.7  765.15  4365.2  763.75  4372.4  764.21  4379.3  763.39
  4386.6  763.41  4435.9  759.69  4492.6  757.85  4499.8  758.14  4520.9  756.79
  4634.1  754.94  4740.1  753.88  4838.7  751.65  4989.5  749.97  5046.8  748.51
  5047.3  747.71  5052.3  747.71  5052.8  748.51  5067.9  748.89  5110.1  750.86
  5150.4  750.79  5175.3  751.62  5426.1  753.63  5456.4  754.19  5470.2  755.13
  5555.8  757.62  5607.1  758.53  5622.2  757.90  5649.4  759.08  5692.5  759.08
#Mann=5,-1,0
  4313.2     0.1       0  5046.8    0.07       0  5052.8     0.1       0
  5067.9    0.05       0  5175.3     0.1       0
Bank Sta=5046.8,5052.8
Exp/Cntr=0.3,0.1

Type RM Length L Ch R = 1,150,79,79,79
BEGIN DESCRIPTION:
Mapping XS 5d600d9d
END DESCRIPTION:
XS GIS Cut Line= 4
      1984052.03     13628707.90      1984674.84     13628417.11
      1984687.86     13627846.37      1984004.25     13627533.86
#Sta/Elev= 30
  3940.0  767.70  4027.8  766.46  4124.8  761.34  4147.6  759.46  4230.2  757.22
  4478.6  754.12  4501.5  754.70  4736.2  752.44  4829.1  749.20  4869.5  747.84
  4979.6  746.93  4996.6  745.56  4997.1  744.76  5002.1  744.76  5002.6  745.56
  5026.1  747.16  5069.6  747.15  5079.6  748.36  5089.6  748.41  5124.5  747.31
  5196.4  745.82  5243.9  746.90  5376.9  749.85  5456.9  749.96  5600.6  751.44
  5641.1  752.79  5698.1  752.84  5715.7  756.54  5751.2  758.56  5949.9  759.26
#Mann=8,-1,0
  3940.0     0.1       0  4736.2    0.08       0  4829.1    0.05       0
  4996.6    0.04       0  5002.6    0.05       0  5026.1    0.08       0
  5124.5    0.05       0  5243.9     0.1       0
Bank Sta=4996.6,5002.6
Exp/Cntr=0.3,0.1

Type RM Length L Ch R = 1,71,0,0,0
BEGIN DESCRIPTION:
UNT 048 in HW 1.0
END DESCRIPTION:
XS GIS Cut Line= 4
      1984032.45     13628764.35      1984768.16     13628423.63
      1984759.48     13627850.71      1984030.30     13627486.12
#Sta/Elev= 30
  3810.1  767.13  3939.5  765.91  3985.4  763.12  4013.8  762.53  4044.3  760.10
  4111.0  757.54  4408.0  755.28  4540.2  753.06  4551.3  750.65  4559.6  751.62
  4580.4  752.25  4826.4  747.59  4959.5  745.98  4996.5  742.23  4997.0  741.43
  5002.0  741.43  5002.5  742.23  5029.5  745.39  5156.9  744.50  5161.9  745.58
  5210.9  745.52  5244.7  744.39  5319.2  745.97  5423.5  749.44  5580.1  750.07
  5686.3  751.65  5746.7  753.72  5798.1  758.49  6006.6  759.24  6009.1  759.24
#Mann=8,-1,0
  3810.1     0.1       0  4559.6    0.08       0  4826.4     0.1       0
  4996.5    0.07       0  5002.5     0.1       0  5210.9    0.05       0
  5319.2     0.1       0  6006.6    0.05       0
Bank Sta=4996.5,5002.5
Exp/Cntr=0.3,0.1

Chan Stop Cuts=-1