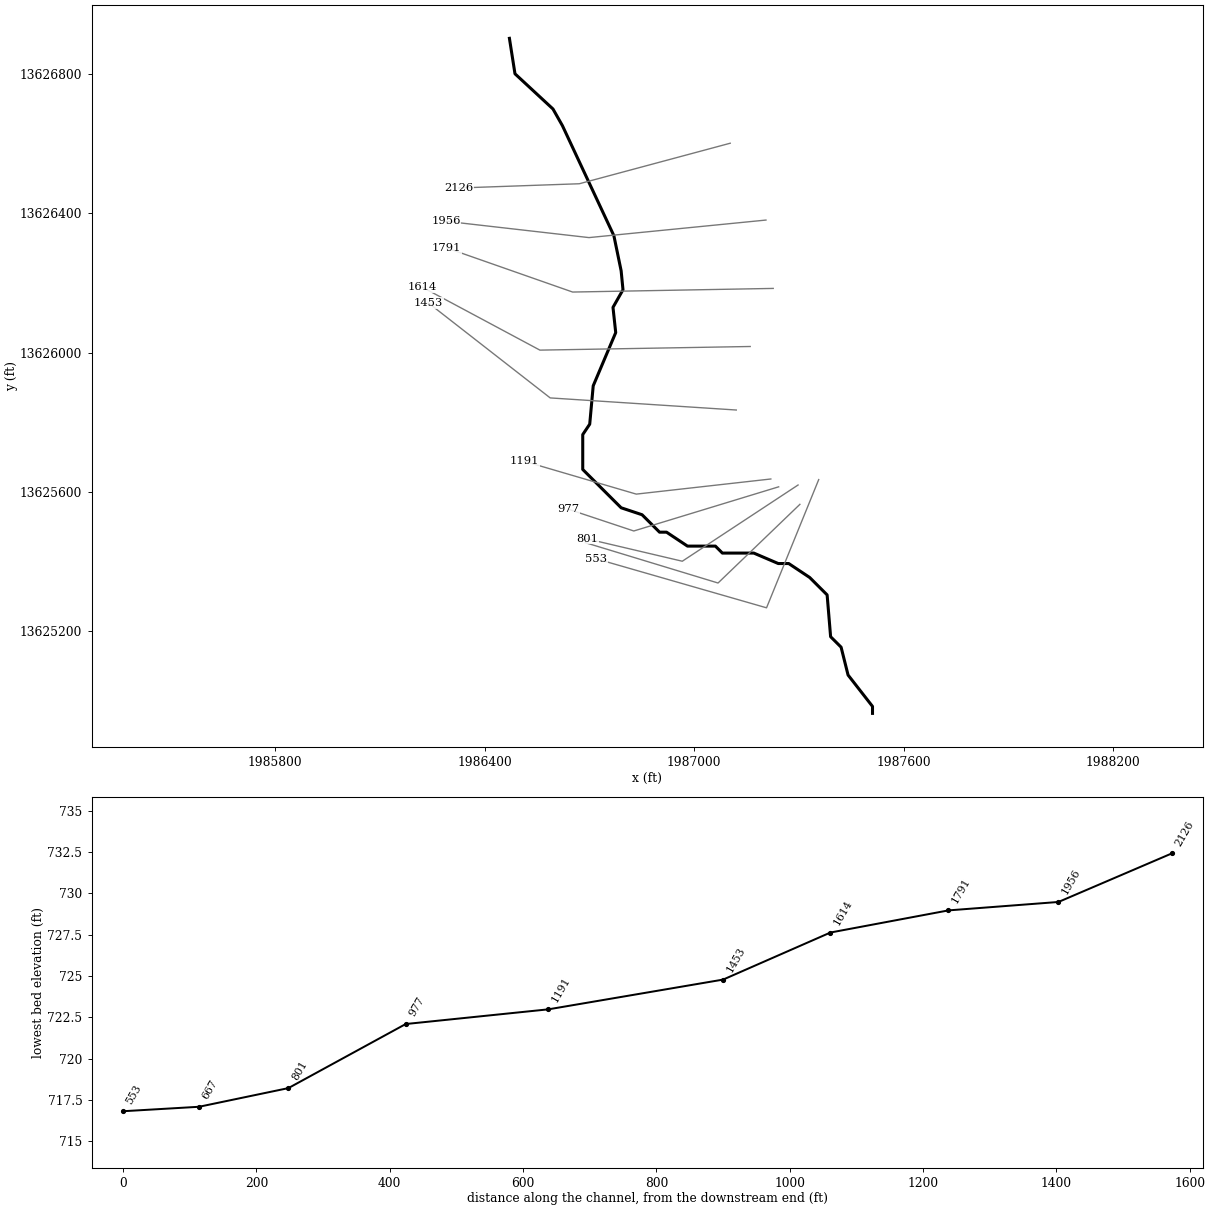
--- UNT 049 in HW.prj (project) ---

Proj Title=UNT 049 in HW Base Level Engineering
Current Plan=p01
Default Exp/Contr=0.3,0.1
English Units
Geom File=g01
Flow File=f01
Plan File=p01
BEGIN DESCRIPTION:
UNT 049 in HW
END DESCRIPTION:

--- UNT 049 in HW.p01 (plan) ---

Plan Title=Multiple Run
Short Identifier=Multiple
Geom File=g01
Flow File=f01
Subcritical Flow
K Sum by GR= 0
Std Step Tol= 0.01
Critical Tol= 0.01
Num of Std Step Trials= 20
Max Error Tol= 0.3
Flow Tol Ratio= 0.001
Split Flow NTrial= 30
Split Flow Tol= 0.02
Split Flow Ratio= 0.02
Log Output Level= 0
Friction Slope Method= 1
Unsteady Friction Slope Method= 2
Unsteady Bridges Friction Slope Method= 1
Parabolic Critical Depth
Global Vel Dist=  1 , 1 , 1
Global Log Level= 0
CheckData=True
Encroach Param= -1, 0, 0, 0
BEGIN DESCRIPTION:
Multiple Run
END DESCRIPTION:

--- UNT 049 in HW.f01 (steady flow) ---

Flow Title=Multiple
Number of Profiles=7
Profile Names=10-year,25-year,50-year,1pct_min,100-year,1pct_plu,500-year
River Rch & RM= UNT 049 in HW,Reach-1,2126
     315     427     518     312     622    1242     900
Boundary for River Rch & Prof#=UNT 049 in HW,Reach-1,1
Up Type=0
Dn Type=3
Dn Slope=0.005
Boundary for River Rch & Prof#=UNT 049 in HW,Reach-1,2
Up Type=0
Dn Type=3
Dn Slope=0.005
Boundary for River Rch & Prof#=UNT 049 in HW,Reach-1,3
Up Type=0
Dn Type=3
Dn Slope=0.005
Boundary for River Rch & Prof#=UNT 049 in HW,Reach-1,4
Up Type=0
Dn Type=3
Dn Slope=0.005
Boundary for River Rch & Prof#=UNT 049 in HW,Reach-1,5
Up Type=0
Dn Type=3
Dn Slope=0.005
Boundary for River Rch & Prof#=UNT 049 in HW,Reach-1,6
Up Type=0
Dn Type=3
Dn Slope=0.005
Boundary for River Rch & Prof#=UNT 049 in HW,Reach-1,7
Up Type=0
Dn Type=3
Dn Slope=0.005

--- UNT 049 in HW.g01 (geometry) ---

Geom Title=Existing Conditions

River Reach=UNT 049 in HW,Reach-1
Reach XY= 30
      1986470.80     13626901.70      1986486.71     13626799.97
      1986595.57     13626698.93      1986622.65     13626651.01
      1986770.00     13626335.34      1986790.80     13626234.54
      1986796.09     13626180.18      1986767.44     13626129.66
      1986775.26     13626057.26      1986710.80     13625904.54
      1986700.80     13625794.54      1986680.80     13625764.54
      1986680.80     13625664.54      1986790.80     13625554.54
      1986850.80     13625534.54      1986900.80     13625484.54
      1986920.80     13625484.54      1986980.80     13625444.54
      1987060.80     13625444.54      1987080.80     13625424.54
      1987170.80     13625424.54      1987240.80     13625394.54
      1987270.80     13625394.54      1987330.80     13625354.54
      1987380.80     13625304.54      1987390.80     13625184.54
      1987420.80     13625154.54      1987440.80     13625074.54
      1987510.80     13624984.54      1987510.80     13624964.54

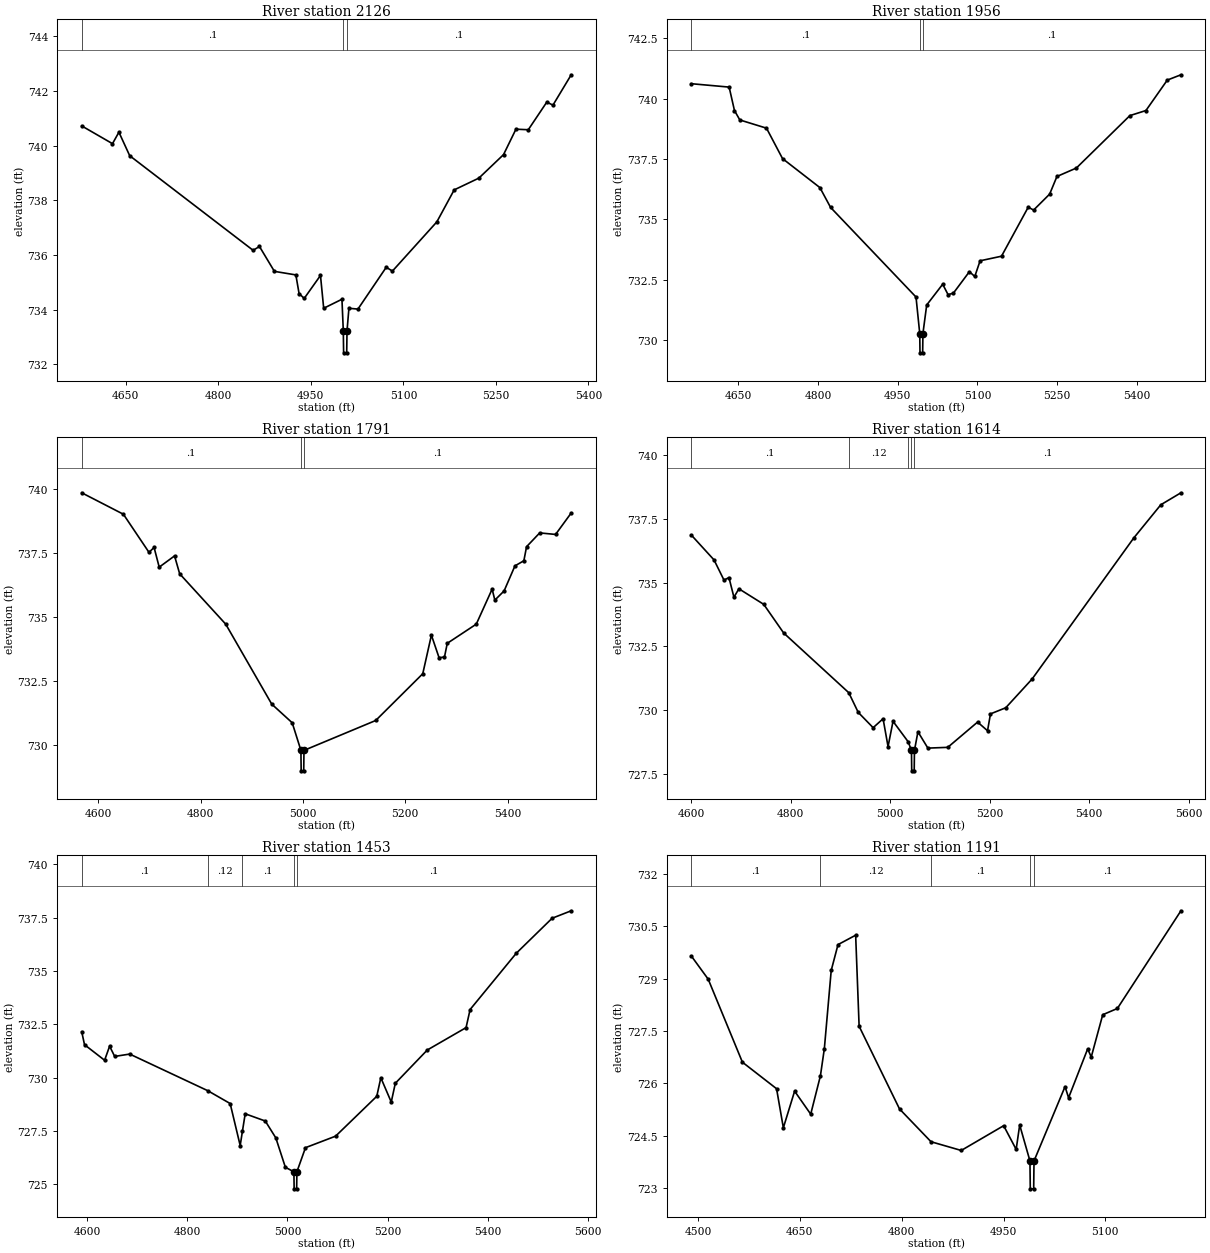
Type RM Length L Ch R = 1,2126,170,170,170
BEGIN DESCRIPTION:
UNT 049 in HW 2.0
END DESCRIPTION:
XS GIS Cut Line= 3
      1987103.22     13626600.71      1986670.93     13626484.39
      1986325.41     13626472.23
#Sta/Elev= 30
  4578.6  740.72  4628.5  740.07  4638.9  740.49  4656.4  739.63  4856.4  736.17
  4866.7  736.31  4890.9  735.40  4925.7  735.27  4930.9  734.59  4939.2  734.41
  4965.6  735.25  4970.8  734.05  5000.4  734.38  5002.6  733.22  5003.1  732.42
  5008.1  732.42  5008.6  733.22  5011.7  734.05  5026.3  734.02  5072.2  735.55
  5082.2  735.41  5154.2  737.21  5182.3  738.38  5222.3  738.81  5262.3  739.67
  5282.4  740.60  5302.4  740.58  5332.4  741.59  5342.4  741.48  5372.0  742.59
#Mann=3,-1,0
  4578.6     0.1       0  5002.6    0.07       0  5008.6     0.1       0
Bank Sta=5002.6,5008.6
Exp/Cntr=0.3,0.1

Type RM Length L Ch R = 1,1956,165,165,165
BEGIN DESCRIPTION:
Mapping XS 409bae42
END DESCRIPTION:
XS GIS Cut Line= 3
      1987205.62     13626380.22      1986698.71     13626329.88
      1986289.48     13626376.69
#Sta/Elev= 30
  4561.6  740.62  4632.6  740.48  4642.6  739.51  4652.7  739.12  4702.9  738.78
  4733.1  737.52  4803.4  736.32  4823.5  735.50  4984.3  731.79  4991.3  730.28
  4991.8  729.48  4996.8  729.48  4997.3  730.28  5004.4  731.46  5034.5  732.32
  5044.6  731.89  5054.6  731.95  5084.8  732.84  5094.9  732.64  5104.9  733.29
  5145.2  733.48  5195.5  735.51  5205.6  735.39  5235.8  736.05  5249.5  736.78
  5286.1  737.13  5386.8  739.30  5417.0  739.51  5457.2  740.77  5482.9  740.99
#Mann=3,-1,0
  4561.6     0.1       0  4991.3    0.07       0  4997.3     0.1       0
Bank Sta=4991.3,4997.3
Exp/Cntr=0.3,0.1

Type RM Length L Ch R = 1,1791,177,177,177
BEGIN DESCRIPTION:
Mapping XS 5ea8c82d
END DESCRIPTION:
XS GIS Cut Line= 3
      1987226.45     13626184.04      1986651.84     13626173.63
      1986291.21     13626300.19
#Sta/Elev= 30
  4567.5  739.85  4649.0  739.01  4699.0  737.52  4709.0  737.71  4719.0  736.94
  4749.0  737.38  4759.0  736.68  4849.0  734.71  4939.0  731.58  4979.0  730.85
  4996.0  729.77  4996.5  728.97  5001.5  728.97  5002.0  729.77  5142.2  730.94
  5234.2  732.77  5251.1  734.28  5266.0  733.40  5276.6  733.42  5282.1  733.96
  5338.8  734.71  5369.8  736.08  5375.1  735.65  5393.2  736.01  5414.4  736.99
  5431.8  737.19  5437.1  737.74  5462.8  738.28  5493.8  738.22  5524.4  739.06
#Mann=3,-1,0
  4567.5     0.1       0  4996.0    0.07       0  5002.0     0.1       0
Bank Sta=4996,5002
Exp/Cntr=0.3,0.1

Type RM Length L Ch R = 1,1614,161,161,161
BEGIN DESCRIPTION:
Mapping XS 989ec155
END DESCRIPTION:
XS GIS Cut Line= 3
      1987160.48     13626017.37      1986558.09     13626006.96
      1986221.31     13626187.50
#Sta/Elev= 30
  4600.1  736.86  4645.6  735.89  4665.6  735.10  4675.6  735.20  4685.6  734.43
  4695.6  734.76  4745.6  734.15  4785.6  733.03  4916.6  730.69  4935.6  729.92
  4965.6  729.32  4985.6  729.67  4995.6  728.58  5005.6  729.57  5036.0  728.77
  5042.7  728.43  5043.2  727.63  5048.2  727.63  5048.7  728.43  5055.7  729.16
  5075.7  728.52  5115.7  728.55  5175.7  729.54  5195.7  729.20  5201.6  729.86
  5232.3  730.10  5285.5  731.23  5489.8  736.75  5544.2  738.05  5584.7  738.52
#Mann=5,-1,0
  4600.1     0.1       0  4916.6    0.12       0  5036.0     0.1       0
  5042.7    0.07       0  5048.7     0.1       0
Bank Sta=5042.7,5048.7
Exp/Cntr=0.3,0.1

Type RM Length L Ch R = 1,1453,262,262,262
BEGIN DESCRIPTION:
Mapping XS 8b9bde80
END DESCRIPTION:
XS GIS Cut Line= 3
      1987120.63     13625835.08      1986587.60     13625869.81
      1986238.60     13626142.40
#Sta/Elev= 30
  4589.3  732.15  4594.9  731.54  4635.0  730.81  4645.0  731.47  4655.1  730.99
  4685.1  731.10  4841.1  729.38  4885.6  728.78  4905.6  726.81  4910.2  727.50
  4915.6  728.30  4955.7  727.96  4976.7  727.17  4995.8  725.79  5012.8  725.58
  5013.3  724.78  5018.3  724.78  5018.8  725.58  5035.9  726.71  5096.0  727.25
  5178.2  729.12  5186.3  729.99  5207.1  728.85  5215.2  729.73  5279.0  731.29
  5356.4  732.34  5364.5  733.19  5456.7  735.83  5528.2  737.47  5566.3  737.82
#Mann=5,-1,0
  4589.3     0.1       0  4841.1    0.12       0  4910.2     0.1       0
  5012.8    0.07       0  5018.8     0.1       0
Bank Sta=5012.8,5018.8
Exp/Cntr=0.3,0.1

Type RM Length L Ch R = 1,1191,214,214,214
BEGIN DESCRIPTION:
Mapping XS 4466690d
END DESCRIPTION:
XS GIS Cut Line= 3
      1987219.58     13625637.17      1986834.13     13625593.76
      1986514.51     13625687.62
#Sta/Elev= 30
  4490.3  729.65  4515.0  728.99  4565.4  726.61  4615.7  725.85  4625.7  724.73
  4642.3  725.78  4666.0  725.12  4680.3  726.22  4686.1  727.00  4696.2  729.24
  4706.2  729.98  4732.2  730.25  4737.3  727.64  4796.8  725.27  4843.2  724.33
  4887.7  724.08  4950.2  724.79  4968.6  724.11  4973.8  724.81  4988.9  723.78
  4989.4  722.98  4994.4  722.98  4994.9  723.78  5040.6  725.91  5045.8  725.59
  5073.9  726.99  5079.2  726.76  5096.1  727.97  5117.7  728.15  5211.3  730.95
#Mann=5,-1,0
  4490.3     0.1       0  4680.3    0.12       0  4843.2     0.1       0
  4988.9    0.07       0  4994.9     0.1       0
Bank Sta=4988.9,4994.9
Exp/Cntr=0.3,0.1

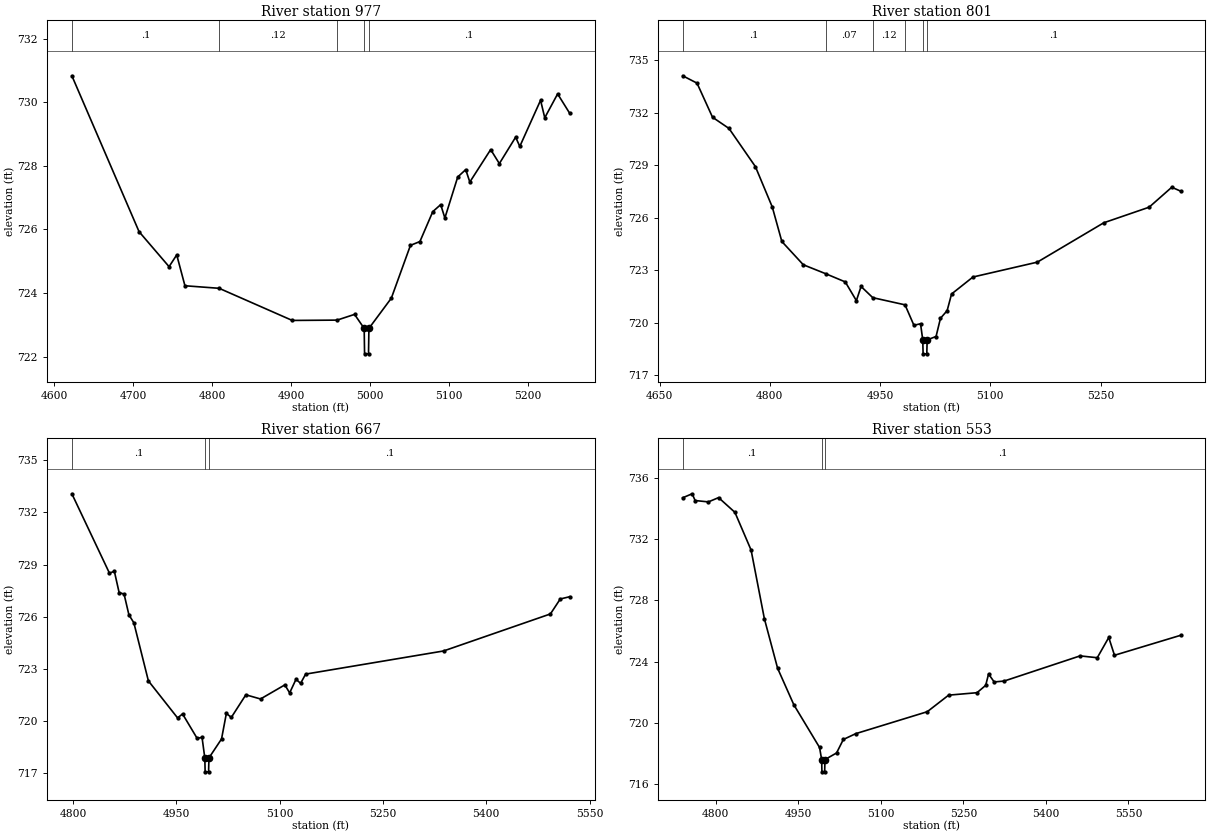
Type RM Length L Ch R = 1,977,176,176,176
BEGIN DESCRIPTION:
Mapping XS 60ade563
END DESCRIPTION:
XS GIS Cut Line= 3
      1987241.96     13625614.68      1986827.05     13625487.95
      1986640.48     13625550.14
#Sta/Elev= 30
  4622.5  730.83  4707.6  725.93  4745.6  724.83  4755.3  725.20  4765.7  724.23
  4809.0  724.15  4901.6  723.14  4958.4  723.15  4980.5  723.33  4992.7  722.89
  4993.2  722.09  4998.2  722.09  4998.7  722.89  5027.1  723.84  5051.3  725.50
  5063.3  725.62  5079.6  726.56  5089.6  726.78  5094.9  726.36  5111.2  727.65
  5121.3  727.88  5126.5  727.49  5152.9  728.51  5163.9  728.07  5184.5  728.90
  5189.8  728.61  5216.1  730.06  5221.4  729.51  5237.7  730.26  5253.0  729.65
#Mann=5,-1,0
  4622.5     0.1       0  4809.0    0.12       0  4958.4     0.1       0
  4992.7    0.07       0  4998.7     0.1       0
Bank Sta=4992.7,4998.7
Exp/Cntr=0.3,0.1

Type RM Length L Ch R = 1,801,134,134,134
BEGIN DESCRIPTION:
Mapping XS 917fb7d1
END DESCRIPTION:
XS GIS Cut Line= 3
      1987297.58     13625619.92      1986965.94     13625401.15
      1986693.40     13625465.37
#Sta/Elev= 30
  4681.5  734.10  4701.0  733.68  4722.1  731.73  4744.5  731.09  4780.4  728.91
  4803.4  726.60  4816.4  724.63  4845.6  723.30  4876.0  722.79  4902.7  722.32
  4917.8  721.25  4924.2  722.06  4940.1  721.42  4984.0  721.01  4996.1  719.84
  5005.1  719.93  5008.1  719.01  5008.6  718.21  5013.6  718.21  5014.1  719.01
  5026.2  719.20  5032.2  720.24  5041.3  720.68  5047.3  721.63  5076.4  722.60
  5164.0  723.45  5254.4  725.70  5316.1  726.59  5346.9  727.73  5358.8  727.51
#Mann=6,-1,0
  4681.5     0.1       0  4876.0    0.07       0  4940.1    0.12       0
  4984.0     0.1       0  5008.1    0.07       0  5014.1     0.1       0
Bank Sta=5008.1,5014.1
Exp/Cntr=0.3,0.1

Type RM Length L Ch R = 1,667,114,114,114
BEGIN DESCRIPTION:
Mapping XS b0dd645e
END DESCRIPTION:
XS GIS Cut Line= 3
      1987302.78     13625564.38      1987068.37     13625338.65
      1986688.23     13625454.42
#Sta/Elev= 30
  4798.4  733.07  4852.9  728.51  4860.1  728.61  4867.0  727.39  4874.2  727.30
  4881.2  726.11  4888.4  725.65  4909.5  722.31  4951.9  720.18  4959.1  720.41
  4980.2  719.01  4987.4  719.06  4991.4  717.88  4991.9  717.08  4996.9  717.08
  4997.4  717.88  5015.7  718.97  5022.7  720.44  5029.9  720.21  5051.0  721.51
  5072.3  721.27  5107.6  722.08  5114.6  721.62  5123.8  722.40  5130.5  722.17
  5137.8  722.70  5338.0  724.03  5493.2  726.16  5507.5  727.02  5521.2  727.15
#Mann=3,-1,0
  4798.4     0.1       0  4991.4    0.07       0  4997.4     0.1       0
Bank Sta=4991.4,4997.4
Exp/Cntr=0.3,0.1

Type RM Length L Ch R = 1,553,0,0,0
BEGIN DESCRIPTION:
UNT 049 in HW 1.0
END DESCRIPTION:
XS GIS Cut Line= 3
      1987356.70     13625635.43      1987207.26     13625267.47
      1986719.66     13625408.02
#Sta/Elev= 30
  4740.0  734.68  4757.2  734.94  4762.6  734.50  4786.7  734.41  4805.2  734.69
  4834.9  733.73  4864.3  731.27  4888.4  726.80  4912.5  723.56  4942.0  721.18
  4988.7  718.40  4992.5  717.61  4993.0  716.81  4998.0  716.81  4998.5  717.61
  5019.6  718.04  5031.9  718.92  5054.5  719.30  5184.4  720.73  5223.2  721.81
  5274.8  721.97  5290.6  722.45  5295.8  723.19  5306.0  722.67  5324.2  722.73
  5462.1  724.37  5493.3  724.25  5514.2  725.57  5524.6  724.41  5644.6  725.71
#Mann=3,-1,0
  4740.0     0.1       0  4992.5    0.07       0  4998.5     0.1       0
Bank Sta=4992.5,4998.5
Exp/Cntr=0.3,0.1

Chan Stop Cuts=-1