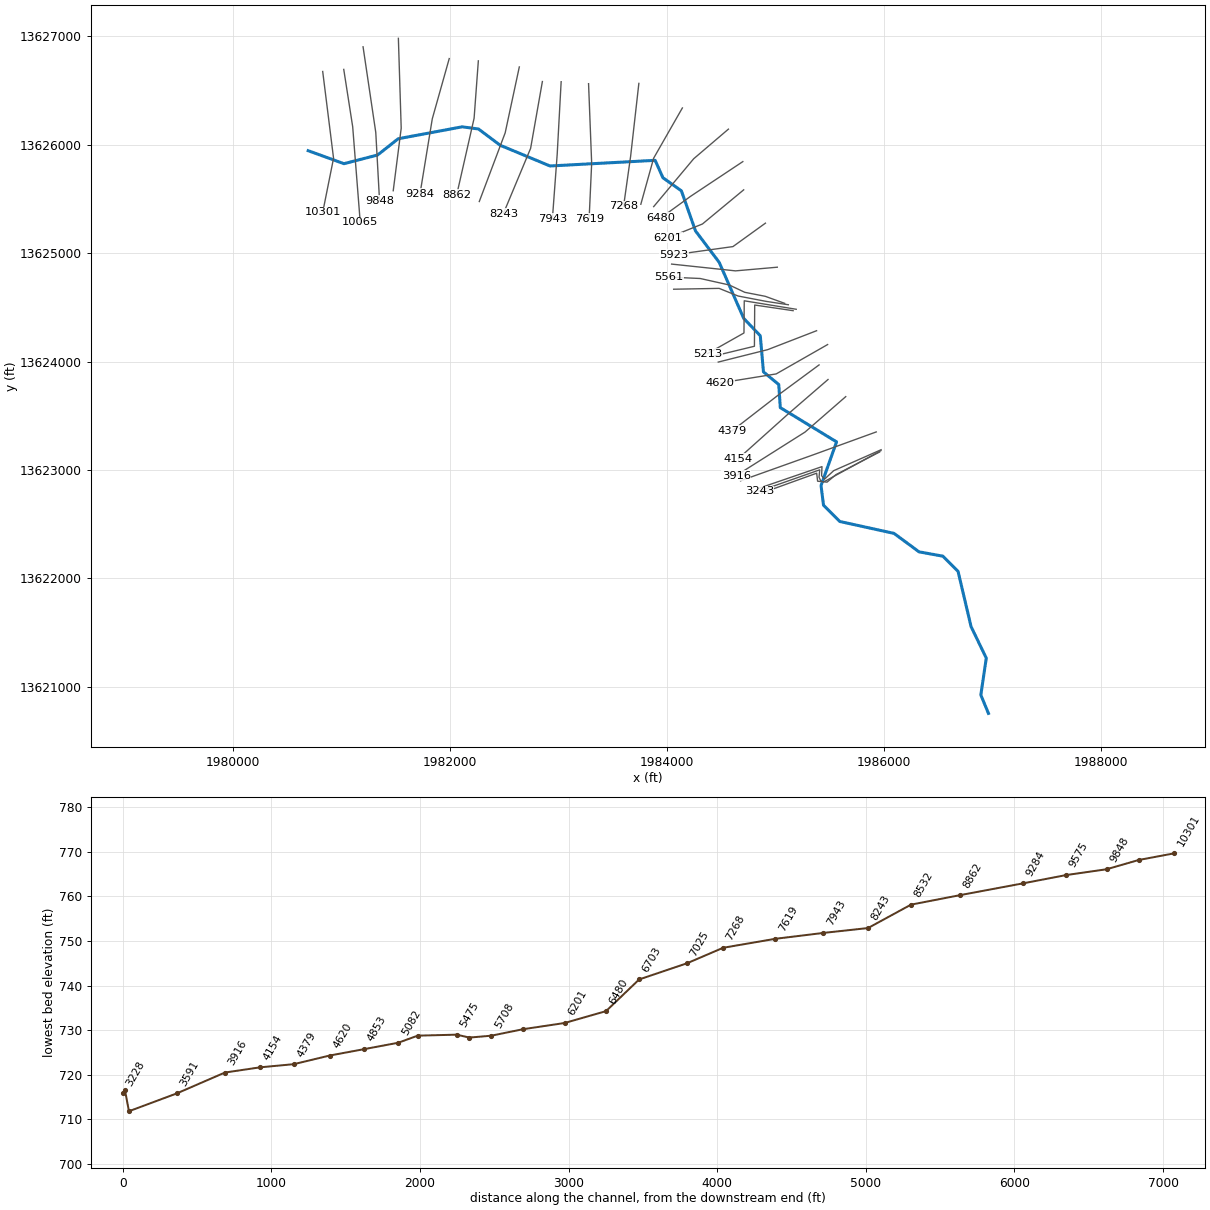
--- UNT 050 in HW.prj (project) ---

Proj Title=UNT 050 in HW Base Level Engineering
Current Plan=p01
Default Exp/Contr=0.3,0.1
English Units
Geom File=g01
Flow File=f01
Plan File=p01
BEGIN DESCRIPTION:
UNT 050 in HW
END DESCRIPTION:

--- UNT 050 in HW.p01 (plan) ---

Plan Title=Multiple Run
Short Identifier=Multiple
Geom File=g01
Flow File=f01
Subcritical Flow
K Sum by GR= 0
Std Step Tol= 0.01
Critical Tol= 0.01
Num of Std Step Trials= 20
Max Error Tol= 0.3
Flow Tol Ratio= 0.001
Split Flow NTrial= 30
Split Flow Tol= 0.02
Split Flow Ratio= 0.02
Log Output Level= 0
Friction Slope Method= 1
Unsteady Friction Slope Method= 2
Unsteady Bridges Friction Slope Method= 1
Parabolic Critical Depth
Global Vel Dist=  1 , 1 , 1
Global Log Level= 0
CheckData=True
Encroach Param= -1, 0, 0, 0
BEGIN DESCRIPTION:
Multiple Run
END DESCRIPTION:

--- UNT 050 in HW.f01 (steady flow) ---

Flow Title=Multiple
Number of Profiles=7
Profile Names=10-year,25-year,50-year,1pct_min,100-year,1pct_plu,500-year
River Rch & RM= UNT 050 in HW,Reach-1,10301
     579     821    1026     635    1267    2529    1941
River Rch & RM= UNT 050 in HW,Reach-1,9848
     910    1319    1671    1047    2090    4170    3282
Boundary for River Rch & Prof#=UNT 050 in HW,Reach-1,1
Up Type=0
Dn Type=3
Dn Slope=0.005
Boundary for River Rch & Prof#=UNT 050 in HW,Reach-1,2
Up Type=0
Dn Type=3
Dn Slope=0.005
Boundary for River Rch & Prof#=UNT 050 in HW,Reach-1,3
Up Type=0
Dn Type=3
Dn Slope=0.005
Boundary for River Rch & Prof#=UNT 050 in HW,Reach-1,4
Up Type=0
Dn Type=3
Dn Slope=0.005
Boundary for River Rch & Prof#=UNT 050 in HW,Reach-1,5
Up Type=0
Dn Type=3
Dn Slope=0.005
Boundary for River Rch & Prof#=UNT 050 in HW,Reach-1,6
Up Type=0
Dn Type=3
Dn Slope=0.005
Boundary for River Rch & Prof#=UNT 050 in HW,Reach-1,7
Up Type=0
Dn Type=3
Dn Slope=0.005

--- UNT 050 in HW.g01 (geometry) ---

Geom Title=Existing Conditions

River Reach=UNT 050 in HW,Reach-1
Reach XY= 30
      1980690.80     13625944.54      1981020.80     13625824.54
      1981330.80     13625904.54      1981520.80     13626054.54
      1982110.80     13626164.54      1982260.80     13626144.54
      1982460.80     13625994.54      1982920.04     13625803.37
      1983889.00     13625855.45      1983960.80     13625694.54
      1984130.80     13625574.54      1984260.80     13625204.54
      1984479.28     13624914.70      1984704.98     13624398.20
      1984857.97     13624237.61      1984887.27     13623904.50
      1985028.33     13623787.31      1985042.43     13623574.64
      1985561.10     13623258.88      1985417.87     13622855.24
      1985440.80     13622674.54      1985590.80     13622524.54
      1986090.80     13622414.54      1986320.80     13622244.54
      1986540.80     13622204.54      1986680.80     13622064.54
      1986800.80     13621554.54      1986940.80     13621264.54
      1986890.80     13620924.54      1986960.80     13620754.54

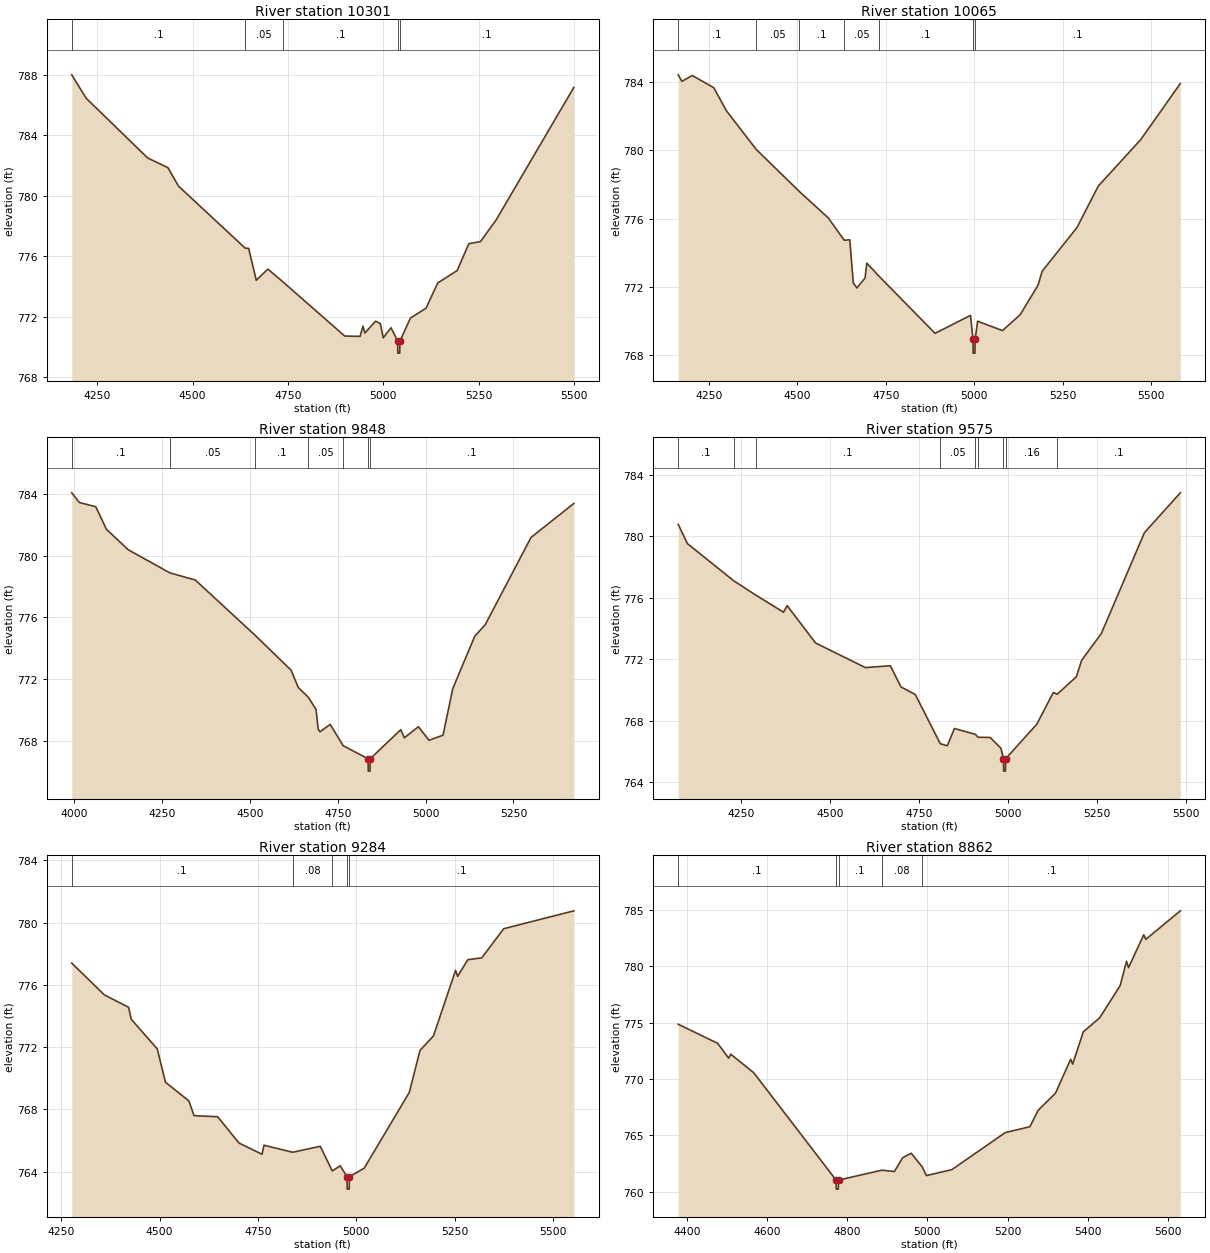
Type RM Length L Ch R = 1,10301,236,236,236
BEGIN DESCRIPTION:
UNT 050 in HW 26.0
END DESCRIPTION:
XS GIS Cut Line= 3
      1980825.00     13626675.00      1980925.00     13625875.00
      1980825.01     13625375.03
#Sta/Elev= 30
  4183.1  788.00  4220.9  786.45  4382.1  782.50  4435.1  781.86  4462.8  780.64
  4637.9  776.53  4646.7  776.52  4666.8  774.41  4697.1  775.15  4736.8  774.30
  4898.6  770.72  4938.9  770.70  4946.5  771.38  4951.5  770.92  4979.3  771.70
  4991.9  771.55  4999.5  770.60  5019.9  771.27  5037.3  770.39  5037.8  769.59
  5042.8  769.59  5043.3  770.39  5070.9  771.91  5111.7  772.56  5142.3  774.23
  5193.3  775.05  5223.9  776.83  5254.5  776.97  5295.3  778.39  5499.2  787.17
#Mann=5,-1,0
  4183.1     0.1       0  4637.9    0.05       0  4736.8     0.1       0
  5037.3    0.07       0  5043.3     0.1       0
Bank Sta=5037.3,5043.3
Exp/Cntr=0.3,0.1

Type RM Length L Ch R = 1,10065,217,217,217
BEGIN DESCRIPTION:
Mapping XS 1159ceb8
END DESCRIPTION:
XS GIS Cut Line= 3
      1981019.00     13626694.22      1981101.46     13626164.76
      1981170.91     13625283.64
#Sta/Elev= 30
  4163.0  784.42  4173.4  784.04  4202.7  784.38  4263.4  783.67  4299.1  782.32
  4383.6  780.05  4505.8  777.58  4587.3  776.04  4632.5  774.73  4648.0  774.76
  4658.1  772.22  4668.2  771.94  4691.4  772.52  4696.2  773.39  4731.5  772.61
  4889.2  769.28  4989.5  770.33  4996.5  768.92  4997.0  768.12  5002.0  768.12
  5002.5  768.92  5009.6  769.99  5079.8  769.44  5129.9  770.37  5180.1  772.09
  5192.2  772.92  5290.4  775.47  5350.6  777.90  5471.0  780.63  5582.7  783.91
#Mann=7,-1,0
  4163.0     0.1       0  4383.6    0.05       0  4505.8     0.1       0
  4632.5    0.05       0  4731.5     0.1       0  4996.5    0.07       0
  5002.5     0.1       0
Bank Sta=4996.5,5002.5
Exp/Cntr=0.3,0.1

Type RM Length L Ch R = 1,9848,273,273,273
BEGIN DESCRIPTION:
UNT 050 in HW 25.0
END DESCRIPTION:
XS GIS Cut Line= 3
      1981196.95     13626902.58      1981314.14     13626112.67
      1981348.85     13625483.38
#Sta/Elev= 30
  3993.0  784.08  4014.8  783.45  4061.3  783.18  4091.6  781.72  4153.7  780.39
  4272.3  778.89  4344.4  778.43  4514.1  774.86  4617.3  772.58  4637.6  771.46
  4666.1  770.83  4688.1  770.04  4694.2  768.78  4699.2  768.59  4728.5  769.07
  4765.2  767.69  4836.3  766.84  4836.8  766.04  4841.8  766.04  4842.3  766.84
  4929.4  768.73  4939.4  768.20  4979.5  768.92  5009.6  768.04  5049.6  768.37
  5077.1  771.38  5139.7  774.78  5169.8  775.54  5300.0  781.19  5421.8  783.39
#Mann=7,-1,0
  3993.0     0.1       0  4272.3    0.05       0  4514.1     0.1       0
  4666.1    0.05       0  4765.2     0.1       0  4836.3    0.07       0
  4842.3     0.1       0
Bank Sta=4836.3,4842.3
Exp/Cntr=0.3,0.1

Type RM Length L Ch R = 1,9575,291,291,291
BEGIN DESCRIPTION:
UNT 050 in HW 24.0
END DESCRIPTION:
XS GIS Cut Line= 3
      1981522.47     13626980.74      1981548.51     13626151.74
      1981475.00     13625575.02
#Sta/Elev= 30
  4072.6  780.77  4098.4  779.52  4228.7  777.10  4291.3  776.16  4368.5  775.06
  4378.5  775.49  4458.5  773.06  4598.6  771.46  4668.6  771.58  4698.7  770.20
  4738.7  769.71  4809.0  766.51  4828.7  766.38  4848.7  767.50  4907.6  767.12
  4915.2  766.93  4949.1  766.92  4979.4  766.22  4986.5  765.53  4987.0  764.73
  4992.0  764.73  4992.5  765.53  5080.2  767.78  5126.5  769.84  5137.5  769.73
  5191.1  770.86  5206.4  771.94  5261.6  773.68  5382.6  780.23  5483.4  782.82
#Mann=9,-1,0
  4072.6     0.1       0  4228.7    0.05       0  4291.3     0.1       0
  4809.0    0.05       0  4907.6     0.1       0  4915.2    0.16       0
  4986.5    0.07       0  4992.5    0.16       0  5137.5     0.1       0
Bank Sta=4986.5,4992.5
Exp/Cntr=0.3,0.1

Type RM Length L Ch R = 1,9284,422,422,422
BEGIN DESCRIPTION:
UNT 050 in HW 23.0
END DESCRIPTION:
XS GIS Cut Line= 3
      1981991.21     13626794.07      1981834.97     13626238.54
      1981722.24     13625549.18
#Sta/Elev= 30
  4277.0  777.39  4359.8  775.35  4421.5  774.55  4427.9  773.79  4494.2  771.88
  4515.0  769.74  4574.5  768.54  4587.7  767.59  4647.8  767.52  4701.9  765.83
  4760.4  765.11  4765.5  765.69  4838.1  765.24  4908.3  765.62  4938.9  764.04
  4959.0  764.37  4976.3  763.67  4976.8  762.87  4981.8  762.87  4982.3  763.67
  5019.8  764.21  5134.5  769.08  5161.7  771.78  5195.9  772.71  5252.2  776.93
  5257.3  776.54  5283.3  777.61  5318.7  777.73  5374.4  779.60  5552.6  780.75
#Mann=5,-1,0
  4277.0     0.1       0  4838.1    0.08       0  4938.9     0.1       0
  4976.3    0.07       0  4982.3     0.1       0
Bank Sta=4976.3,4982.3
Exp/Cntr=0.3,0.1

Type RM Length L Ch R = 1,8862,330,330,330
BEGIN DESCRIPTION:
UNT 050 in HW 22.0
END DESCRIPTION:
XS GIS Cut Line= 3
      1982259.44     13626773.23      1982220.39     13626243.75
      1982060.32     13625538.61
#Sta/Elev= 30
  4377.6  774.85  4476.1  773.16  4503.6  771.84  4508.6  772.20  4566.3  770.55
  4771.9  761.04  4772.4  760.24  4777.4  760.24  4777.9  761.04  4886.2  761.92
  4917.5  761.80  4938.0  763.02  4959.5  763.42  4987.3  762.20  4997.5  761.44
  5061.1  761.97  5194.4  765.25  5255.9  765.77  5276.6  767.23  5319.7  768.73
  5357.7  771.75  5362.8  771.32  5389.2  774.17  5430.2  775.42  5481.5  778.28
  5497.2  780.43  5502.3  779.87  5540.3  782.78  5545.4  782.37  5631.6  784.90
#Mann=5,-1,0
  4377.6     0.1       0  4771.9    0.07       0  4777.9     0.1       0
  4886.2    0.08       0  4987.3     0.1       0
Bank Sta=4771.9,4777.9
Exp/Cntr=0.3,0.1

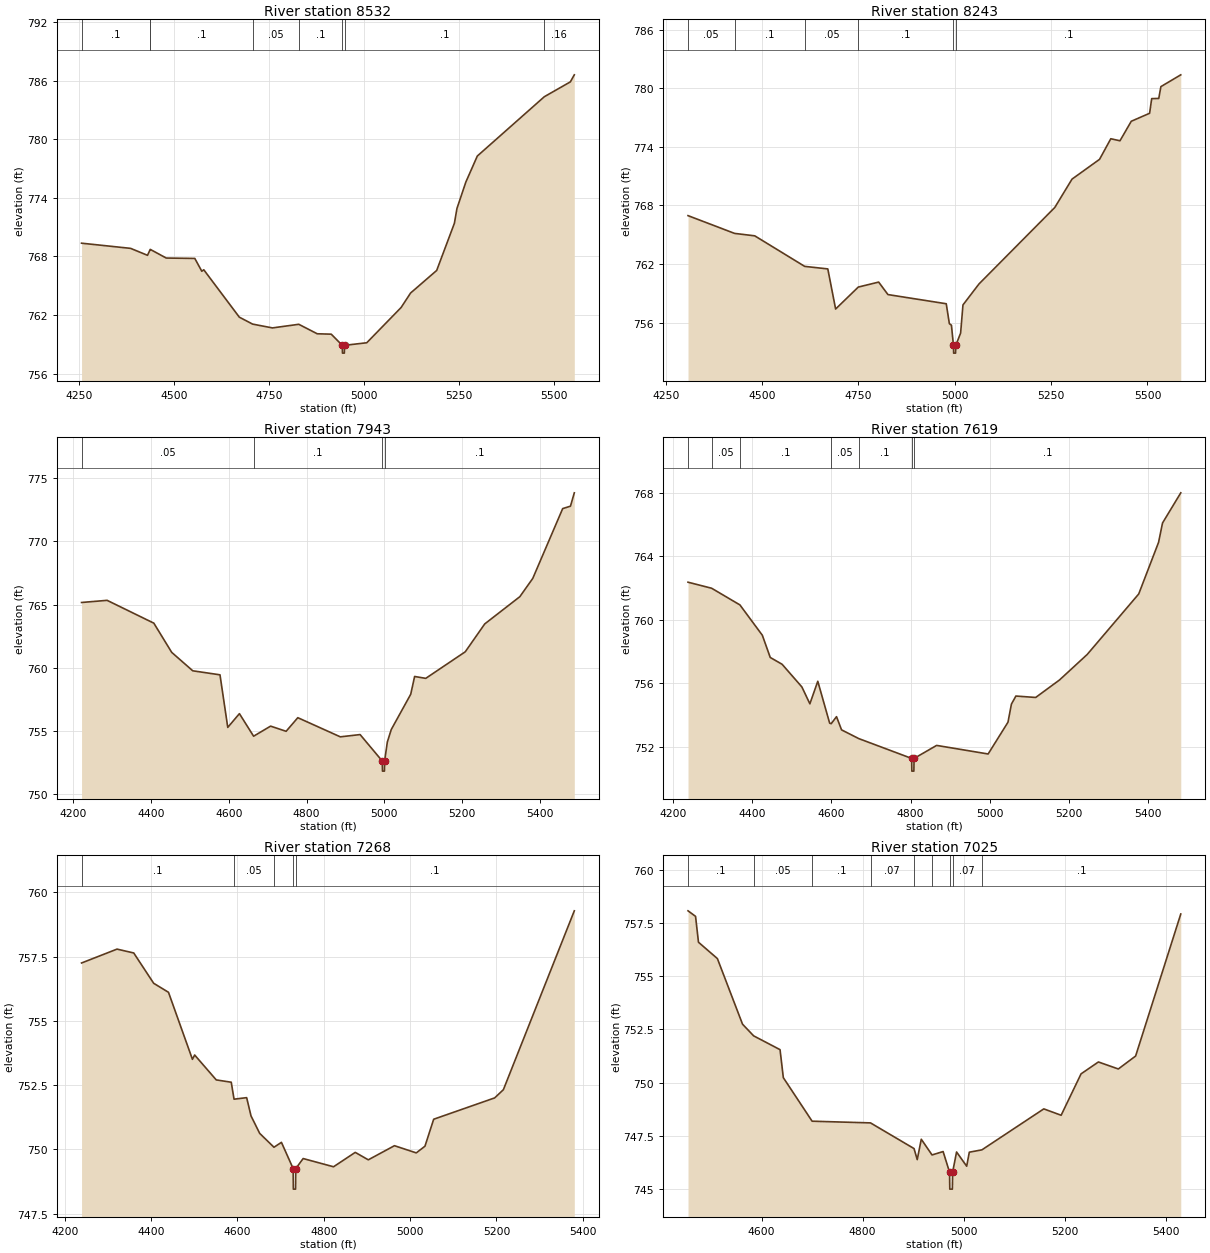
Type RM Length L Ch R = 1,8532,289,289,289
BEGIN DESCRIPTION:
UNT 050 in HW 21.0
END DESCRIPTION:
XS GIS Cut Line= 3
      1982637.06     13626716.88      1982506.84     13626109.20
      1982268.14     13625475.54
#Sta/Elev= 30
  4256.0  769.36  4385.4  768.83  4429.8  768.12  4437.1  768.73  4437.4  768.72
  4479.2  767.84  4554.5  767.80  4572.9  766.49  4578.1  766.64  4671.8  761.79
  4706.8  761.08  4759.0  760.69  4828.5  761.06  4877.1  760.09  4914.0  760.05
  4943.1  758.91  4943.6  758.11  4948.6  758.11  4949.1  758.91  5007.6  759.17
  5098.2  762.78  5123.1  764.26  5191.9  766.57  5238.6  771.40  5245.3  772.91
  5268.8  775.62  5299.0  778.28  5475.6  784.35  5544.2  785.87  5554.6  786.59
#Mann=8,-1,0
  4256.0     0.1       0  4437.1    0.05       0  4437.4     0.1       0
  4706.8    0.05       0  4828.5     0.1       0  4943.1    0.07       0
  4949.1     0.1       0  5475.6    0.16       0
Bank Sta=4943.1,4949.1
Exp/Cntr=0.3,0.1

Type RM Length L Ch R = 1,8243,300,300,300
BEGIN DESCRIPTION:
UNT 050 in HW 20.0
END DESCRIPTION:
XS GIS Cut Line= 3
      1982849.73     13626582.32      1982741.22     13625965.97
      1982489.73     13625363.27
#Sta/Elev= 30
  4307.6  766.96  4428.4  765.14  4480.8  764.89  4610.4  761.76  4670.4  761.50
  4690.7  757.39  4749.5  759.64  4802.4  760.15  4826.5  758.87  4977.8  757.93
  4985.9  755.89  4991.3  755.73  4996.5  753.67  4997.0  752.87  5002.0  752.87
  5002.5  753.67  5015.1  754.92  5021.2  757.81  5062.8  759.96  5259.6  767.80
  5304.2  770.70  5375.7  772.73  5404.9  774.84  5428.7  774.63  5458.0  776.63
  5505.6  777.45  5511.0  778.95  5529.4  778.97  5534.9  780.18  5586.5  781.39
#Mann=6,-1,0
  4307.6    0.05       0  4428.4     0.1       0  4610.4    0.05       0
  4749.5     0.1       0  4996.5    0.07       0  5002.5     0.1       0
Bank Sta=4996.5,5002.5
Exp/Cntr=0.3,0.1

Type RM Length L Ch R = 1,7943,324,324,324
BEGIN DESCRIPTION:
UNT 050 in HW 19.0
END DESCRIPTION:
XS GIS Cut Line= 3
      1983022.68     13626580.73      1982986.23     13625911.50
      1982941.96     13625315.17
#Sta/Elev= 30
  4220.8  765.16  4286.6  765.33  4406.8  763.52  4452.9  761.20  4507.0  759.74
  4577.1  759.42  4597.1  755.25  4627.1  756.34  4663.6  754.55  4707.3  755.35
  4747.3  754.94  4777.4  756.02  4886.8  754.50  4937.7  754.68  4994.8  752.58
  4995.3  751.78  5000.3  751.78  5000.8  752.58  5007.8  754.09  5017.9  755.08
  5068.0  757.88  5078.0  759.29  5106.7  759.14  5208.4  761.25  5258.5  763.46
  5348.8  765.62  5382.1  767.07  5459.1  772.61  5479.1  772.80  5489.0  773.86
#Mann=4,-1,0
  4220.8    0.05       0  4663.6     0.1       0  4994.8    0.07       0
  5000.8     0.1       0
Bank Sta=4994.8,5000.8
Exp/Cntr=0.3,0.1

Type RM Length L Ch R = 1,7619,351,351,351
BEGIN DESCRIPTION:
UNT 050 in HW 18.0
END DESCRIPTION:
XS GIS Cut Line= 3
      1983275.29     13626562.52      1983303.94     13625828.17
      1983280.55     13625318.92
#Sta/Elev= 30
  4238.0  762.36  4297.6  761.98  4369.1  760.93  4425.7  759.02  4445.7  757.62
  4475.7  757.19  4525.7  755.76  4545.8  754.70  4565.8  756.12  4595.8  753.48
  4599.7  753.45  4613.1  753.89  4625.8  753.06  4669.2  752.51  4802.9  751.26
  4803.4  750.46  4808.5  750.46  4809.0  751.26  4866.0  752.08  4996.1  751.54
  5046.2  753.54  5054.9  754.68  5066.2  755.19  5116.2  755.10  5176.3  756.20
  5246.4  757.81  5376.5  761.62  5426.6  764.87  5436.6  766.09  5482.7  767.99
#Mann=7,-1,0
  4238.0     0.1       0  4297.6    0.05       0  4369.1     0.1       0
  4599.7    0.05       0  4669.2     0.1       0  4802.9    0.07       0
  4809.0     0.1       0
Bank Sta=4802.9,4809
Exp/Cntr=0.3,0.1

Type RM Length L Ch R = 1,7268,243,243,243
BEGIN DESCRIPTION:
UNT 050 in HW 17.0
END DESCRIPTION:
XS GIS Cut Line= 3
      1983738.83     13626565.14      1983663.31     13625895.88
      1983598.21     13625432.33
#Sta/Elev= 30
  4238.9  757.25  4321.1  757.79  4359.8  757.64  4406.0  756.46  4440.3  756.11
  4495.8  753.50  4500.9  753.67  4551.0  752.70  4585.7  752.61  4592.2  751.95
  4621.4  752.01  4631.5  751.30  4651.6  750.62  4684.7  750.08  4702.0  750.27
  4729.1  749.25  4729.6  748.45  4734.7  748.45  4735.2  749.25  4752.3  749.64
  4822.7  749.32  4873.0  749.88  4903.2  749.59  4963.8  750.14  5014.3  749.86
  5034.5  750.12  5054.7  751.17  5196.0  752.00  5216.2  752.32  5380.5  759.28
#Mann=5,-1,0
  4238.9     0.1       0  4592.2    0.05       0  4684.7     0.1       0
  4729.1    0.07       0  4735.2     0.1       0
Bank Sta=4729.1,4735.2
Exp/Cntr=0.3,0.1

Type RM Length L Ch R = 1,7025,322,322,322
BEGIN DESCRIPTION:
UNT 050 in HW 16.0
END DESCRIPTION:
XS GIS Cut Line= 3
      1984139.90     13626338.63      1983875.00     13625875.00
      1983757.06     13625450.55
#Sta/Elev= 30
  4454.6  758.09  4469.5  757.83  4475.3  756.61  4512.7  755.84  4562.4  752.75
  4584.4  752.20  4636.6  751.55  4643.1  750.23  4700.0  748.18  4815.5  748.10
  4901.6  746.89  4907.9  746.37  4915.9  747.33  4937.2  746.59  4959.1  746.75
  4971.8  745.78  4972.3  744.98  4977.4  744.98  4977.9  745.78  4985.7  746.73
  5005.7  746.06  5010.9  746.72  5035.8  746.83  5158.2  748.76  5192.5  748.46
  5231.9  750.41  5266.2  750.97  5305.6  750.64  5339.8  751.25  5429.1  757.94
#Mann=9,-1,0
  4454.6     0.1       0  4584.4    0.05       0  4700.0     0.1       0
  4815.5    0.07       0  4901.6     0.1       0  4937.2    0.07       0
  4971.8    0.07       0  4977.9    0.07       0  5035.8     0.1       0
Bank Sta=4971.8,4977.9
Exp/Cntr=0.3,0.1

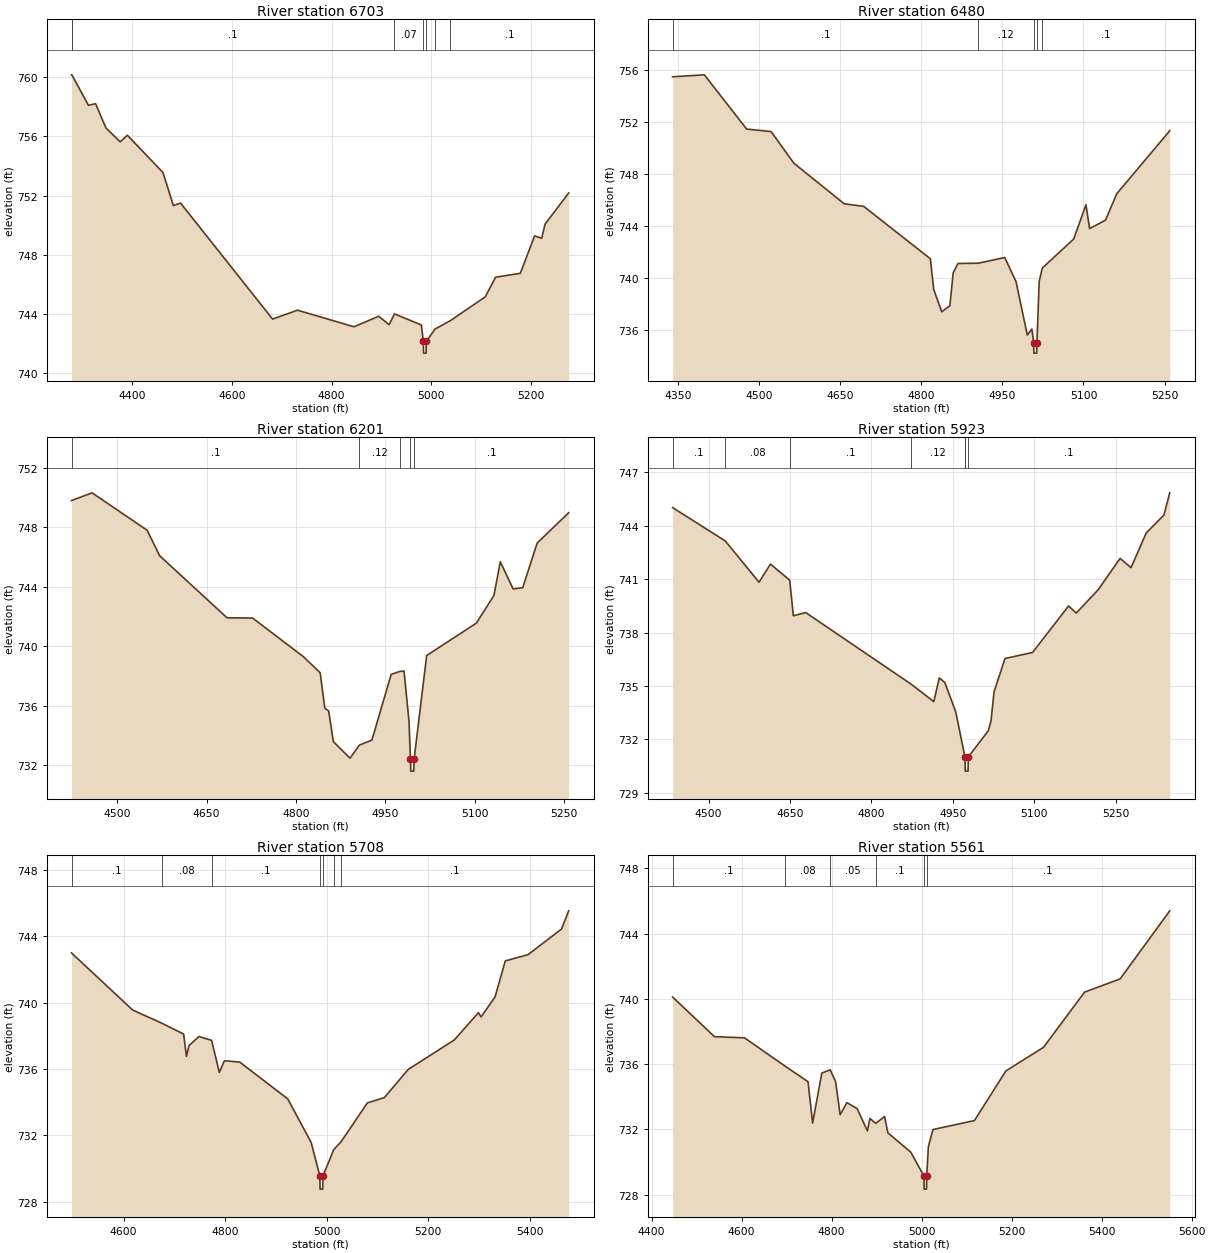
Type RM Length L Ch R = 1,6703,223,223,223
BEGIN DESCRIPTION:
Mapping XS ef522e4e
END DESCRIPTION:
XS GIS Cut Line= 3
      1984564.33     13626143.25      1984244.04     13625869.84
      1983875.44     13625428.55
#Sta/Elev= 30
  4279.1  760.16  4279.8  760.16  4313.0  758.10  4327.3  758.21  4348.1  756.57
  4376.7  755.63  4391.0  756.08  4462.3  753.56  4483.2  751.33  4497.5  751.50
  4681.9  743.66  4731.9  744.26  4845.1  743.14  4894.6  743.85  4915.4  743.28
  4926.2  744.01  4980.1  743.26  4983.9  742.16  4984.4  741.36  4989.5  741.36
  4990.0  742.16  5007.7  742.99  5038.4  743.56  5108.0  745.16  5128.8  746.49
  5178.3  746.75  5206.9  749.28  5221.2  749.12  5227.8  750.07  5275.2  752.18
#Mann=7,-1,0
  4279.1    0.05       0  4279.8     0.1       0  4926.2    0.07       0
  4983.9    0.07       0  4990.0    0.07       0  5007.7    0.12       0
  5038.4     0.1       0
Bank Sta=4983.9,4990
Exp/Cntr=0.3,0.1

Type RM Length L Ch R = 1,6480,279,279,279
BEGIN DESCRIPTION:
UNT 050 in HW 15.0
END DESCRIPTION:
XS GIS Cut Line= 3
      1984697.15     13625843.78      1984215.39     13625523.48
      1983939.68     13625323.20
#Sta/Elev= 30
  4340.2  755.50  4399.0  755.65  4477.2  751.48  4522.3  751.29  4564.4  748.86
  4657.5  745.74  4693.6  745.54  4816.9  741.51  4823.1  739.15  4837.9  737.44
  4852.9  737.90  4859.1  740.44  4868.0  741.15  4905.4  741.17  4954.4  741.61
  4975.3  739.75  4996.1  735.65  5004.6  736.11  5007.8  735.06  5008.3  734.26
  5013.4  734.26  5013.9  735.06  5018.1  739.78  5023.9  740.80  5081.9  743.03
  5104.6  745.66  5111.3  743.83  5140.7  744.48  5161.5  746.51  5259.5  751.35
#Mann=5,-1,0
  4340.2     0.1       0  4905.4    0.12       0  5007.8    0.07       0
  5013.9    0.12       0  5023.9     0.1       0
Bank Sta=5007.8,5013.9
Exp/Cntr=0.3,0.1

Type RM Length L Ch R = 1,6201,278,278,278
BEGIN DESCRIPTION:
UNT 050 in HW 14.0
END DESCRIPTION:
XS GIS Cut Line= 3
      1984704.96     13625583.36      1984324.77     13625268.27
      1984008.51     13625141.25
#Sta/Elev= 30
  4423.4  749.81  4457.9  750.33  4550.4  747.81  4571.2  746.10  4684.5  741.92
  4727.5  741.90  4813.0  739.29  4840.8  738.22  4848.6  735.84  4855.1  735.65
  4863.0  733.58  4890.9  732.47  4906.6  733.35  4927.7  733.69  4960.0  738.11
  4974.6  738.31  4981.6  738.34  4990.0  734.92  4992.4  732.40  4992.9  731.60
  4998.0  731.60  4998.5  732.40  5019.6  739.38  5103.0  741.56  5132.5  743.42
  5143.2  745.69  5164.8  743.86  5180.9  743.95  5205.1  746.95  5258.0  748.99
#Mann=5,-1,0
  4423.4     0.1       0  4906.6    0.12       0  4974.6     0.1       0
  4992.4    0.07       0  4998.5     0.1       0
Bank Sta=4992.4,4998.5
Exp/Cntr=0.3,0.1

Type RM Length L Ch R = 1,5923,215,215,215
BEGIN DESCRIPTION:
UNT 050 in HW 13.0
END DESCRIPTION:
XS GIS Cut Line= 3
      1984905.46     13625276.06      1984606.02     13625059.94
      1984064.35     13624984.42
#Sta/Elev= 30
  4433.6  745.01  4530.7  743.14  4593.0  740.82  4613.9  741.84  4649.4  740.94
  4656.2  738.94  4678.9  739.12  4872.8  735.11  4915.0  734.12  4925.1  735.45
  4935.2  735.20  4955.4  733.55  4971.7  731.12  4972.5  731.02  4973.0  730.22
  4978.1  730.22  4978.6  731.02  5015.3  732.48  5020.4  733.03  5026.0  734.67
  5046.2  736.54  5097.0  736.88  5163.4  739.49  5177.5  739.09  5217.9  740.40
  5258.3  742.16  5278.5  741.64  5306.5  743.59  5339.0  744.59  5349.8  745.84
#Mann=7,-1,0
  4433.6     0.1       0  4530.7    0.08       0  4649.4     0.1       0
  4872.8    0.12       0  4971.7     0.1       0  4972.5    0.07       0
  4978.6     0.1       0
Bank Sta=4972.5,4978.6
Exp/Cntr=0.3,0.1

Type RM Length L Ch R = 1,5708,147,147,147
BEGIN DESCRIPTION:
UNT 050 in HW 12.0
END DESCRIPTION:
XS GIS Cut Line= 3
      1985014.82     13624869.83      1984629.46     13624835.98
      1984040.92     13624898.48
#Sta/Elev= 30
  4497.6  743.00  4617.9  739.56  4674.9  738.77  4718.3  738.11  4723.8  736.76
  4728.8  737.41  4748.4  737.96  4773.4  737.73  4788.5  735.80  4798.6  736.50
  4828.7  736.42  4923.3  734.20  4969.4  731.57  4986.4  729.56  4986.9  728.76
  4992.1  728.76  4992.6  729.56  5013.9  731.15  5028.4  731.62  5080.0  733.96
  5113.5  734.28  5160.5  735.98  5251.0  737.75  5298.7  739.40  5303.8  739.14
  5331.4  740.35  5351.5  742.52  5396.4  742.90  5462.1  744.44  5476.3  745.54
#Mann=7,-1,0
  4497.6     0.1       0  4674.9    0.08       0  4773.4     0.1       0
  4986.4    0.07       0  4992.6     0.1       0  5013.9    0.07       0
  5028.4     0.1       0
Bank Sta=4986.4,4992.6
Exp/Cntr=0.3,0.1

Type RM Length L Ch R = 1,5561,86,86,86
BEGIN DESCRIPTION:
Mapping XS b634e923
END DESCRIPTION:
XS GIS Cut Line= 6
      1985082.58     13624536.50      1984902.89     13624601.61
      1984715.39     13624638.07      1984572.16     13624705.77
      1984303.94     13624765.67      1984014.91     13624778.69
#Sta/Elev= 30
  4446.6  740.11  4539.7  737.68  4606.3  737.61  4695.9  735.89  4747.6  734.92
  4757.8  732.39  4778.2  735.45  4796.8  735.65  4808.8  734.93  4818.9  732.90
  4834.0  733.64  4856.7  733.27  4879.5  731.91  4885.0  732.67  4898.1  732.37
  4917.6  732.79  4925.0  731.79  4976.1  730.60  5005.1  729.14  5005.6  728.34
  5010.8  728.34  5011.3  729.14  5015.0  730.94  5025.2  731.99  5117.4  732.54
  5187.1  735.58  5270.9  737.03  5362.1  740.41  5441.1  741.22  5551.3  745.39
#Mann=6,-1,0
  4446.6     0.1       0  4695.9    0.08       0  4796.8    0.05       0
  4898.1     0.1       0  5005.1    0.07       0  5011.3     0.1       0
Bank Sta=5005.1,5011.3
Exp/Cntr=0.3,0.1

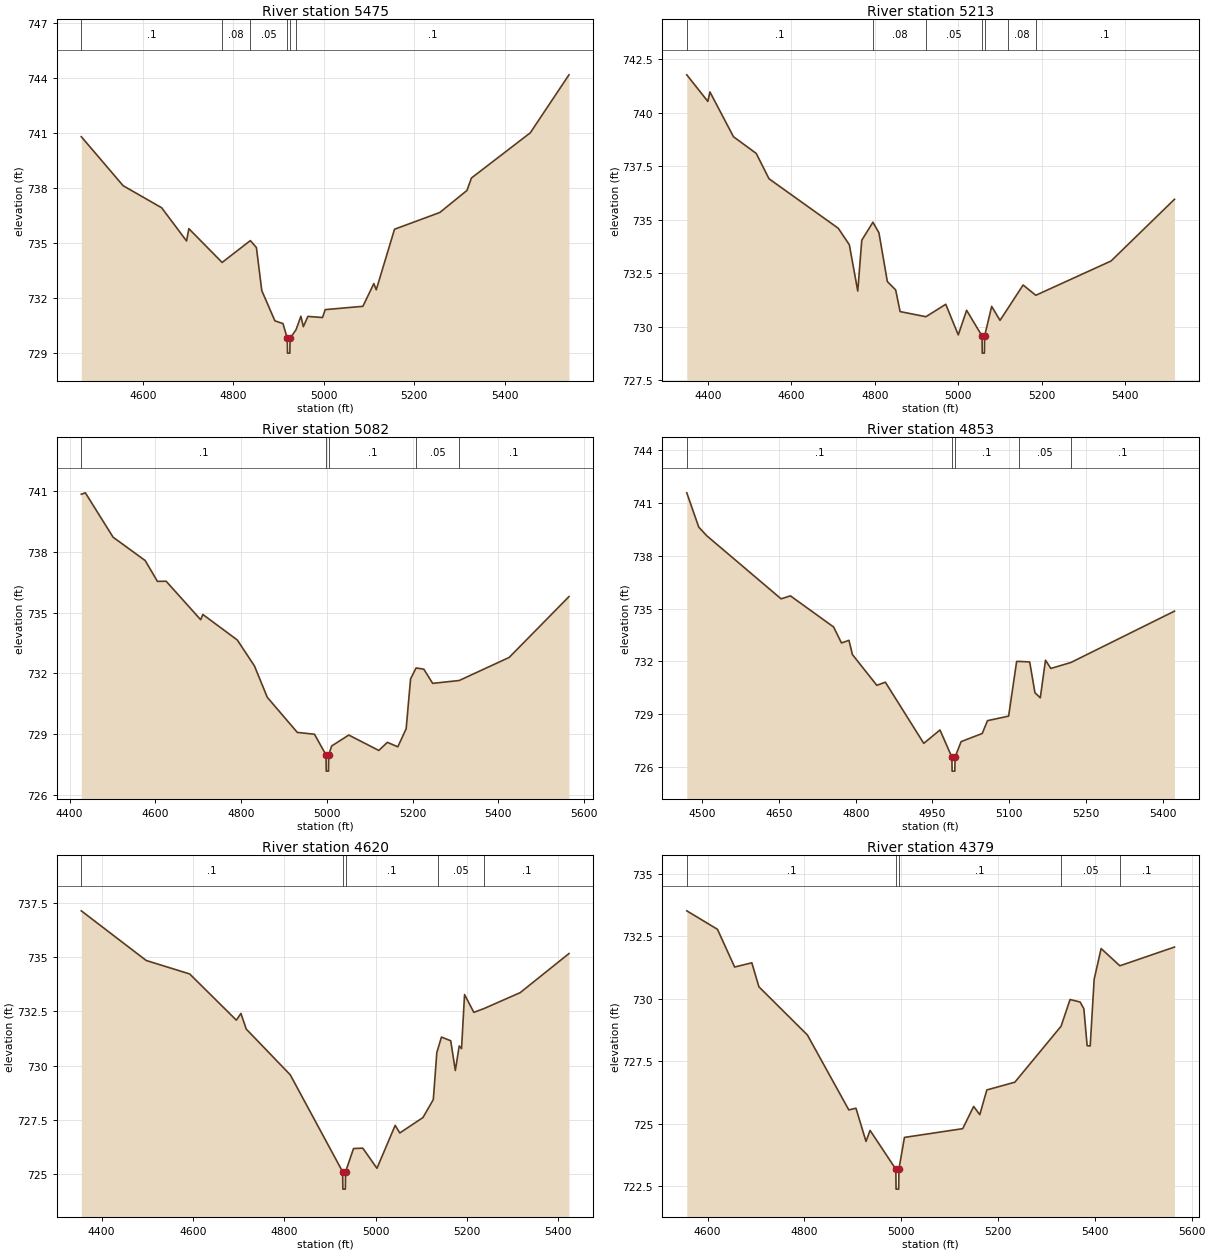
Type RM Length L Ch R = 1,5475,262,262,262
BEGIN DESCRIPTION:
Mapping XS 7fe05a1f
END DESCRIPTION:
XS GIS Cut Line= 5
      1985116.46     13624523.48      1984910.71     13624554.73
      1984652.89     13624604.21      1984478.41     13624674.52
      1984059.54     13624666.72
#Sta/Elev= 30
  4464.2  740.78  4556.7  738.11  4641.7  736.91  4696.8  735.10  4701.9  735.77
  4775.4  733.93  4837.8  735.12  4851.2  734.74  4863.0  732.40  4892.0  730.75
  4909.9  730.60  4919.4  729.79  4919.9  728.99  4925.1  728.99  4925.6  729.79
  4938.8  730.27  4949.5  731.00  4954.9  730.43  4964.9  730.99  4997.3  730.93
  5003.2  731.36  5086.5  731.54  5110.7  732.78  5116.0  732.44  5156.4  735.74
  5256.4  736.65  5316.4  737.85  5326.4  738.53  5456.4  740.99  5541.9  744.15
#Mann=6,-1,0
  4464.2     0.1       0  4775.4    0.08       0  4837.8    0.05       0
  4919.4    0.07       0  4925.6    0.05       0  4938.8     0.1       0
Bank Sta=4919.4,4925.6
Exp/Cntr=0.3,0.1

Type RM Length L Ch R = 1,5213,131,131,131
BEGIN DESCRIPTION:
Mapping XS da4e0d61
END DESCRIPTION:
XS GIS Cut Line= 4
      1985189.31     13624481.82      1984710.19     13624559.94
      1984707.58     13624263.07      1984371.67     13624072.98
#Sta/Elev= 30
  4349.5  741.76  4399.9  740.52  4405.0  740.96  4461.4  738.87  4516.0  738.09
  4546.4  736.91  4712.3  734.60  4738.9  733.83  4759.1  731.67  4768.7  734.04
  4795.4  734.88  4809.8  734.39  4830.0  732.11  4849.9  731.72  4860.5  730.71
  4922.4  730.47  4969.9  731.05  4999.9  729.62  5019.9  730.77  5056.8  729.57
  5057.3  728.77  5062.5  728.77  5063.0  729.57  5079.9  730.95  5099.9  730.30
  5119.5  730.88  5155.2  731.95  5185.6  731.47  5365.9  733.07  5517.8  735.95
#Mann=7,-1,0
  4349.5     0.1       0  4795.4    0.08       0  4922.4    0.05       0
  5056.8    0.04       0  5063.0    0.05       0  5119.5    0.08       0
  5185.6     0.1       0
Bank Sta=5056.8,5063
Exp/Cntr=0.3,0.1

Type RM Length L Ch R = 1,5082,229,229,229
BEGIN DESCRIPTION:
UNT 050 in HW 11.0
END DESCRIPTION:
XS GIS Cut Line= 4
      1985160.67     13624468.80      1984806.54     13624520.88
      1984803.94     13624140.67      1984415.96     13624046.93
#Sta/Elev= 30
  4427.2  740.84  4436.7  740.91  4501.4  738.72  4576.2  737.57  4604.8  736.54
  4625.0  736.55  4705.6  734.65  4710.6  734.91  4791.0  733.65  4831.0  732.37
  4861.0  730.82  4931.0  729.09  4971.0  729.00  4997.9  727.98  4998.4  727.18
  5003.7  727.18  5004.2  727.98  5011.0  728.42  5051.0  728.96  5121.0  728.20
  5141.0  728.60  5165.4  728.38  5184.8  729.27  5195.1  731.73  5208.0  732.27
  5226.0  732.21  5246.6  731.51  5308.4  731.65  5425.1  732.79  5564.5  735.79
#Mann=5,-1,0
  4427.2     0.1       0  4997.9    0.07       0  5004.2     0.1       0
  5208.0    0.05       0  5308.4     0.1       0
Bank Sta=4997.9,5004.2
Exp/Cntr=0.3,0.1

Type RM Length L Ch R = 1,4853,233,233,233
BEGIN DESCRIPTION:
UNT 050 in HW 10.0
END DESCRIPTION:
XS GIS Cut Line= 3
      1985376.86     13624283.90      1984926.33     13624109.42
      1984470.65     13623994.85
#Sta/Elev= 30
  4469.9  741.58  4493.3  739.63  4508.9  739.14  4654.2  735.55  4672.4  735.72
  4756.8  733.95  4772.2  733.04  4786.8  733.19  4793.6  732.38  4841.3  730.63
  4857.9  730.81  4933.0  727.33  4964.7  728.09  4987.9  726.55  4988.4  725.75
  4993.7  725.75  4994.2  726.55  5006.0  727.43  5047.2  727.89  5057.5  728.62
  5098.8  728.88  5114.5  731.99  5119.9  731.99  5140.0  731.96  5150.3  730.21
  5160.7  729.92  5170.9  732.06  5181.3  731.59  5220.6  731.93  5422.9  734.85
#Mann=5,-1,0
  4469.9     0.1       0  4987.9    0.07       0  4994.2     0.1       0
  5119.9    0.05       0  5220.6     0.1       0
Bank Sta=4987.9,4994.2
Exp/Cntr=0.3,0.1

Type RM Length L Ch R = 1,4620,241,241,241
BEGIN DESCRIPTION:
Mapping XS 13cdf61b
END DESCRIPTION:
XS GIS Cut Line= 3
      1985478.46     13624156.32      1985004.46     13623885.46
      1984489.37     13623802.21
#Sta/Elev= 30
  4355.6  737.14  4497.8  734.85  4592.9  734.23  4695.1  732.10  4705.1  732.41
  4716.7  731.69  4813.1  729.58  4927.8  725.11  4928.3  724.31  4933.7  724.31
  4934.2  725.11  4951.6  726.18  4971.9  726.20  5002.9  725.27  5042.8  727.25
  5052.9  726.90  5103.6  727.61  5126.3  728.44  5134.0  730.61  5137.6  730.86
  5144.1  731.32  5164.4  731.15  5174.5  729.78  5183.0  730.91  5188.1  730.79
  5194.7  733.28  5215.0  732.46  5236.8  732.63  5316.6  733.37  5423.3  735.17
#Mann=5,-1,0
  4355.6     0.1       0  4927.8    0.07       0  4934.2     0.1       0
  5137.6    0.05       0  5236.8     0.1       0
Bank Sta=4927.8,4934.2
Exp/Cntr=0.3,0.1

Type RM Length L Ch R = 1,4379,225,225,225
BEGIN DESCRIPTION:
UNT 050 in HW 9.0
END DESCRIPTION:
XS GIS Cut Line= 3
      1985399.86     13623968.51      1985035.27     13623699.41
      1984597.05     13623359.73
#Sta/Elev= 30
  4556.9  733.52  4620.3  732.78  4655.8  731.27  4691.3  731.44  4705.9  730.48
  4806.1  728.55  4891.7  725.55  4906.4  725.62  4927.2  724.29  4935.6  724.73
  4988.8  723.18  4989.3  722.38  4994.7  722.38  4995.2  723.18  5006.6  724.45
  5127.0  724.80  5149.6  725.69  5162.3  725.36  5176.8  726.35  5234.7  726.66
  5330.2  728.90  5348.8  729.97  5369.6  729.87  5377.3  729.60  5384.1  728.12
  5390.4  728.11  5398.6  730.78  5413.0  732.01  5451.7  731.32  5564.5  732.07
#Mann=5,-1,0
  4556.9     0.1       0  4988.8    0.07       0  4995.2     0.1       0
  5330.2    0.05       0  5451.7     0.1       0
Bank Sta=4988.8,4995.2
Exp/Cntr=0.3,0.1

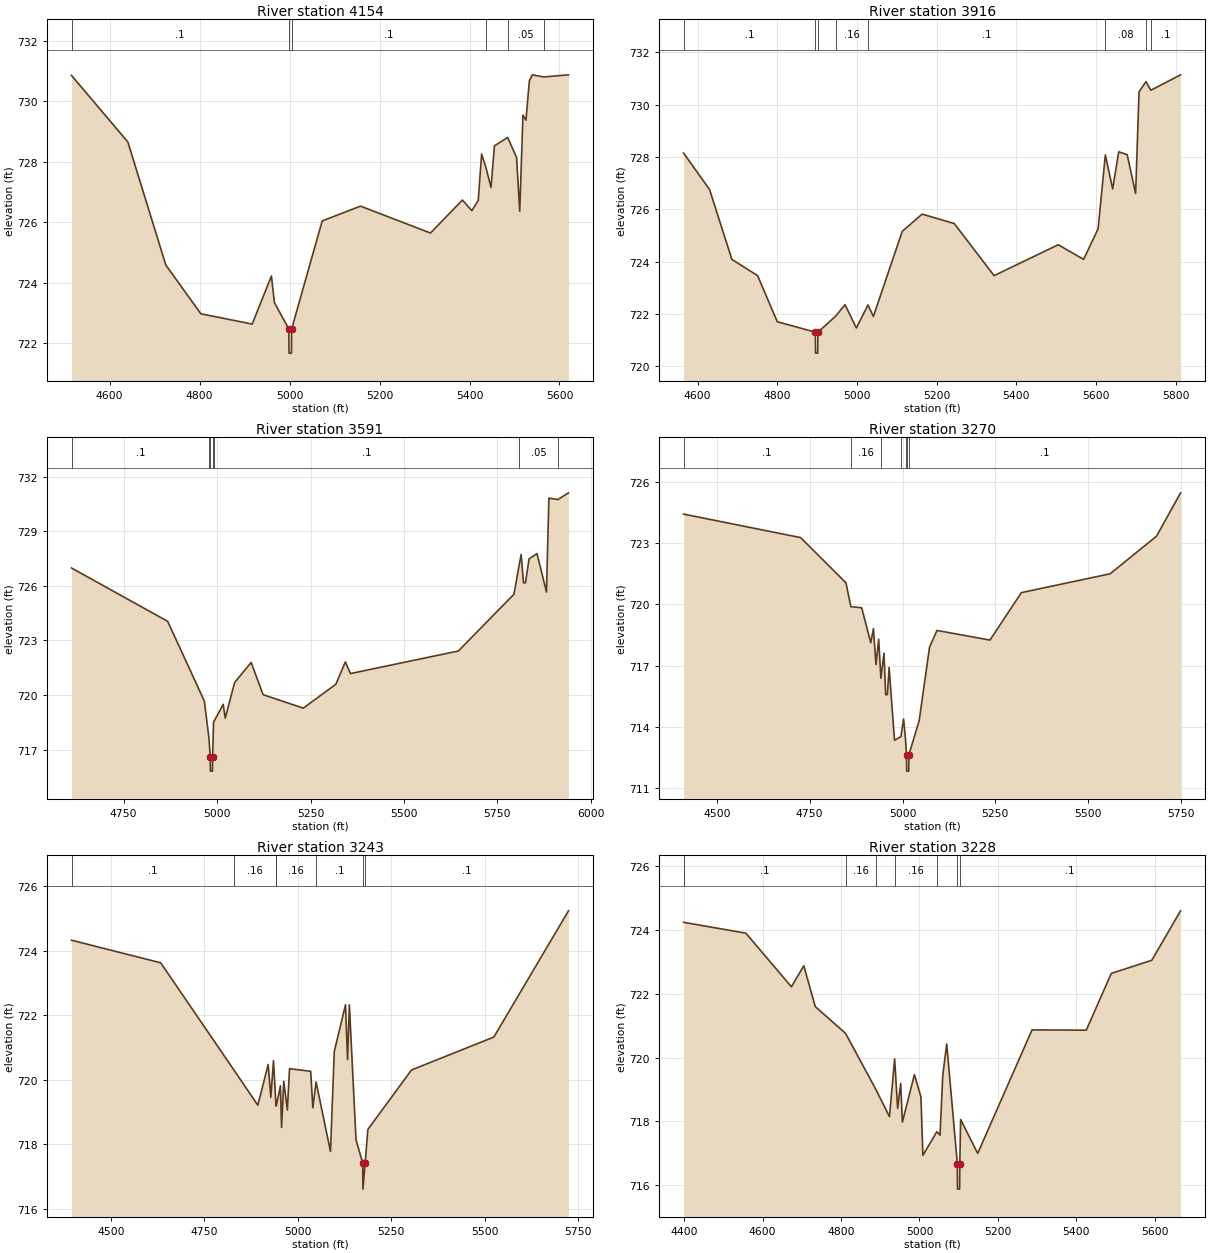
Type RM Length L Ch R = 1,4154,238,238,238
BEGIN DESCRIPTION:
UNT 050 in HW 8.0
END DESCRIPTION:
XS GIS Cut Line= 3
      1985482.32     13623833.96      1985125.00     13623525.00
      1984654.31     13623102.76
#Sta/Elev= 30
  4515.3  730.86  4640.5  728.66  4725.0  724.59  4802.9  722.98  4916.9  722.64
  4959.7  724.23  4966.3  723.35  4998.3  722.48  4998.8  721.68  5004.2  721.68
  5004.7  722.48  5072.5  726.05  5157.7  726.54  5313.2  725.65  5384.2  726.74
  5405.2  726.39  5419.4  726.73  5426.9  728.26  5436.4  727.82  5447.8  727.16
  5455.3  728.53  5484.7  728.81  5504.6  728.15  5511.6  726.37  5518.8  729.55
  5525.5  729.38  5533.0  730.68  5539.7  730.88  5564.9  730.81  5620.0  730.88
#Mann=6,-1,0
  4515.3     0.1       0  4998.3    0.07       0  5004.7     0.1       0
  5436.4    0.08       0  5484.7    0.05       0  5564.9     0.1       0
Bank Sta=4998.3,5004.7
Exp/Cntr=0.3,0.1

Type RM Length L Ch R = 1,3916,325,325,325
BEGIN DESCRIPTION:
UNT 050 in HW 7.0
END DESCRIPTION:
XS GIS Cut Line= 3
      1985645.54     13623675.99      1985270.63     13623349.28
      1984636.96     13622948.24
#Sta/Elev= 30
  4564.7  728.15  4629.9  726.76  4685.9  724.09  4750.5  723.47  4799.8  721.71
  4895.4  721.31  4895.9  720.51  4901.3  720.51  4901.8  721.31  4946.3  721.92
  4969.8  722.36  4998.3  721.47  5027.4  722.35  5041.0  721.91  5113.4  725.16
  5163.3  725.82  5243.9  725.46  5343.9  723.47  5505.0  724.65  5568.6  724.09
  5605.0  725.26  5623.1  728.08  5641.5  726.78  5656.7  728.20  5677.9  728.09
  5699.1  726.61  5707.7  730.49  5725.2  730.88  5737.2  730.55  5811.9  731.14
#Mann=8,-1,0
  4564.7     0.1       0  4895.4    0.07       0  4901.8     0.1       0
  4946.3    0.16       0  5027.4     0.1       0  5623.1    0.08       0
  5725.2    0.05       0  5737.2     0.1       0
Bank Sta=4895.4,4901.8
Exp/Cntr=0.3,0.1

Type RM Length L Ch R = 1,3591,321,321,321
BEGIN DESCRIPTION:
Mapping XS 3cf21ad9
END DESCRIPTION:
XS GIS Cut Line= 3
      1985926.76     13623350.45      1985353.85     13623142.12
      1984675.65     13622899.81
#Sta/Elev= 30
  4610.5  726.98  4867.8  724.05  4965.9  719.67  4978.5  717.60  4981.6  716.62
  4982.1  715.82  4987.5  715.82  4988.0  716.62  4990.6  718.51  5016.4  719.49
  5021.8  718.73  5047.0  720.69  5091.2  721.79  5123.1  720.02  5230.6  719.28
  5317.7  720.59  5343.2  721.82  5356.9  721.18  5645.7  722.42  5794.4  725.54
  5808.4  727.15  5813.6  727.72  5819.9  726.17  5825.2  726.17  5834.8  727.48
  5856.0  727.77  5881.4  725.66  5887.9  730.82  5911.8  730.74  5940.3  731.11
#Mann=7,-1,0
  4610.5     0.1       0  4978.5    0.16       0  4981.6    0.07       0
  4988.0    0.16       0  4990.6     0.1       0  5808.4    0.05       0
  5911.8     0.1       0
Bank Sta=4981.6,4988
Exp/Cntr=0.3,0.1

Type RM Length L Ch R = 1,3270,27,27,27
BEGIN DESCRIPTION:
Mapping XS bf24a601
END DESCRIPTION:
XS GIS Cut Line= 6
      1985971.34     13623186.17      1985534.58     13622993.18
      1985450.46     13622915.31      1985423.12     13622947.00
      1985426.59     13623030.33      1984839.50     13622828.74
#Sta/Elev= 30
  4410.4  724.41  4725.7  723.26  4847.7  721.05  4860.9  719.88  4890.1  719.83
  4914.5  718.12  4921.7  718.81  4928.6  717.05  4935.9  718.29  4941.8  716.38
  4950.1  717.61  4954.7  715.58  4959.3  715.58  4963.9  716.91  4978.5  713.35
  4995.8  713.53  5002.9  714.39  5008.2  713.40  5010.8  712.64  5011.3  711.84
  5016.7  711.84  5017.2  712.64  5044.8  714.30  5072.8  717.90  5092.8  718.72
  5235.6  718.25  5320.2  720.57  5559.2  721.49  5684.2  723.33  5748.9  725.45
#Mann=7,-1,0
  4410.4     0.1       0  4860.9    0.16       0  4941.8     0.1       0
  4995.8    0.16       0  5008.2     0.1       0  5010.8    0.07       0
  5017.2     0.1       0
Bank Sta=5010.8,5017.2
Exp/Cntr=0.3,0.1

Type RM Length L Ch R = 1,3243,15,15,15
BEGIN DESCRIPTION:
Mapping XS 2ce398a3
END DESCRIPTION:
XS GIS Cut Line= 6
      1985969.74     13623177.93      1985451.50     13622894.07
      1985417.65     13622894.07      1985399.42     13622933.13
      1985405.93     13623000.84      1984848.71     13622804.71
#Sta/Elev= 30
  4394.3  724.32  4632.9  723.62  4829.4  720.29  4892.8  719.21  4920.5  720.47
  4927.6  719.45  4934.7  720.59  4941.1  719.26  4942.1  719.18  4953.2  719.81
  4956.3  718.52  4962.1  719.95  4971.8  719.06  4977.6  720.34  5034.2  720.26
  5040.0  719.13  5048.6  719.93  5087.2  717.78  5097.3  720.87  5127.4  722.32
  5132.9  720.62  5137.7  722.32  5155.5  718.14  5173.5  717.41  5174.0  716.61
  5179.9  717.41  5187.3  718.46  5303.9  720.30  5524.3  721.32  5724.0  725.23
#Mann=7,-1,0
  4394.3     0.1       0  4829.4    0.16       0  4941.1     0.1       0
  4942.1    0.16       0  5048.6     0.1       0  5173.5    0.07       0
  5179.9     0.1       0
Bank Sta=5173.5,5179.9
Exp/Cntr=0.3,0.1

Type RM Length L Ch R = 1,3228,133,133,133
BEGIN DESCRIPTION:
Mapping XS 7fe72634
END DESCRIPTION:
XS GIS Cut Line= 6
      1985957.11     13623165.10      1985555.67     13622956.79
      1985473.21     13622887.34      1985386.40     13622896.02
      1985377.72     13622969.81      1984868.89     13622785.76
#Sta/Elev= 30
  4398.5  724.24  4557.3  723.90  4673.5  722.22  4705.1  722.88  4734.2  721.60
  4811.6  720.76  4888.5  719.01  4923.5  718.15  4936.7  719.96  4944.3  718.41
  4952.1  719.19  4956.5  717.98  4987.1  719.47  5003.7  718.77  5008.8  716.94
  5044.3  717.68  5052.4  717.57  5059.5  719.45  5069.5  720.43  5096.5  716.68
  5097.0  715.88  5102.4  715.88  5102.9  716.68  5105.0  718.06  5148.5  717.00
  5287.1  720.87  5425.4  720.86  5489.2  722.64  5592.4  723.05  5665.8  724.60
#Mann=7,-1,0
  4398.5     0.1       0  4811.6    0.16       0  4888.5     0.1       0
  4936.7    0.16       0  5044.3     0.1       0  5096.5    0.07       0
  5102.9     0.1       0
Bank Sta=5096.5,5102.9
Exp/Cntr=0.3,0.1