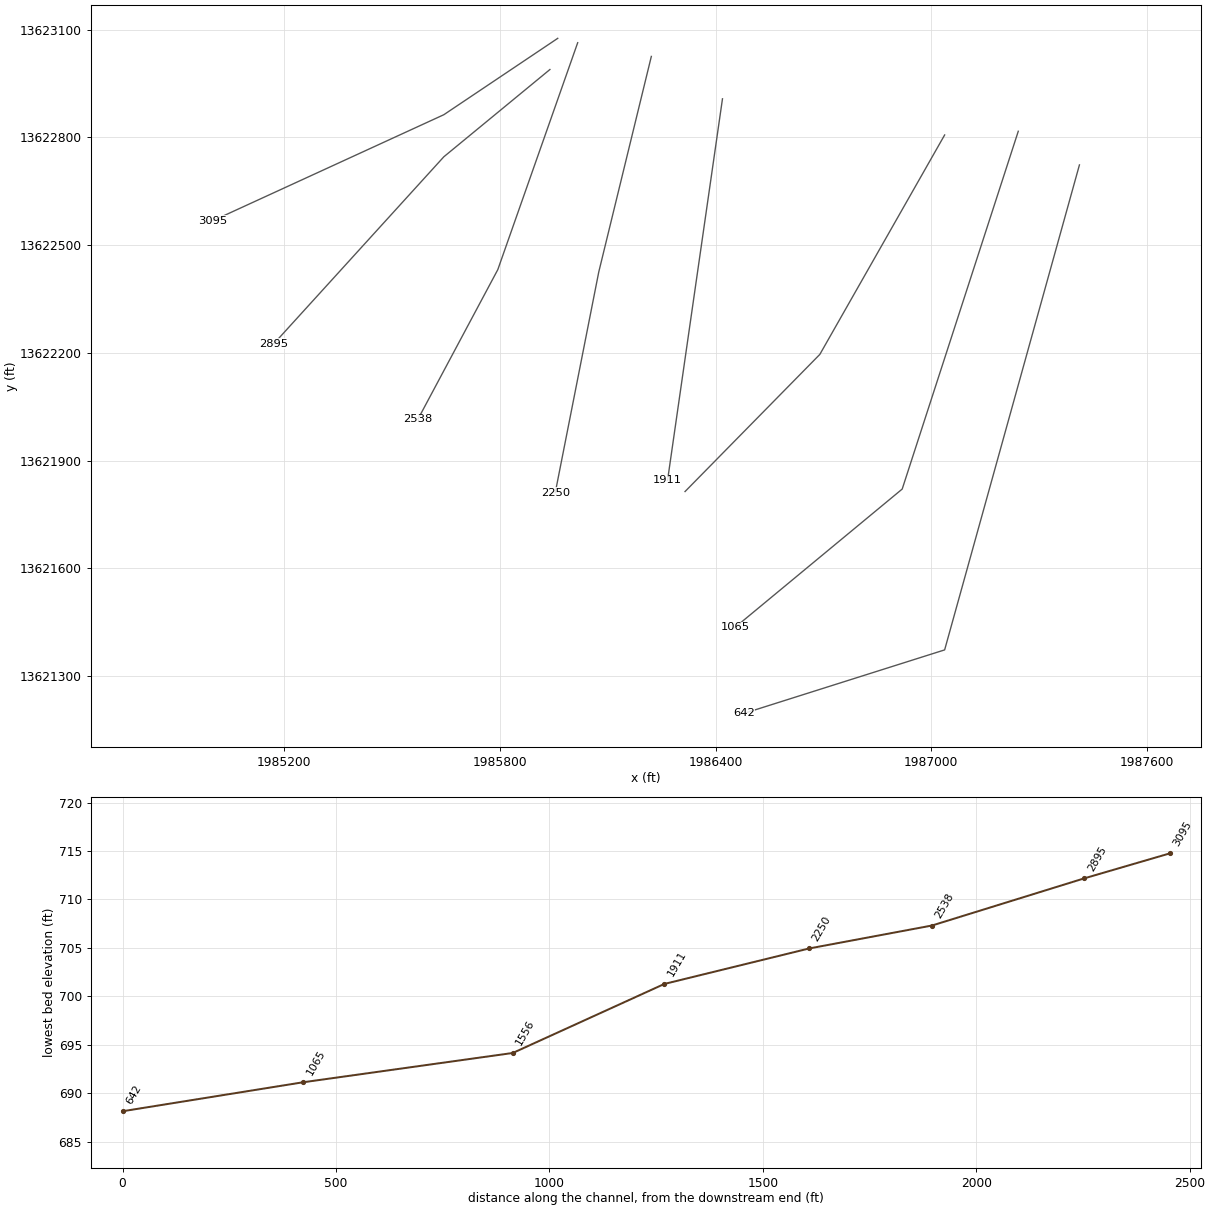
HEC-RAS study UNT 050 in HW.prj: UNT 050 in HW Base Level Engineering

--- UNT 050 in HW.g01 (geometry) --- (continued)

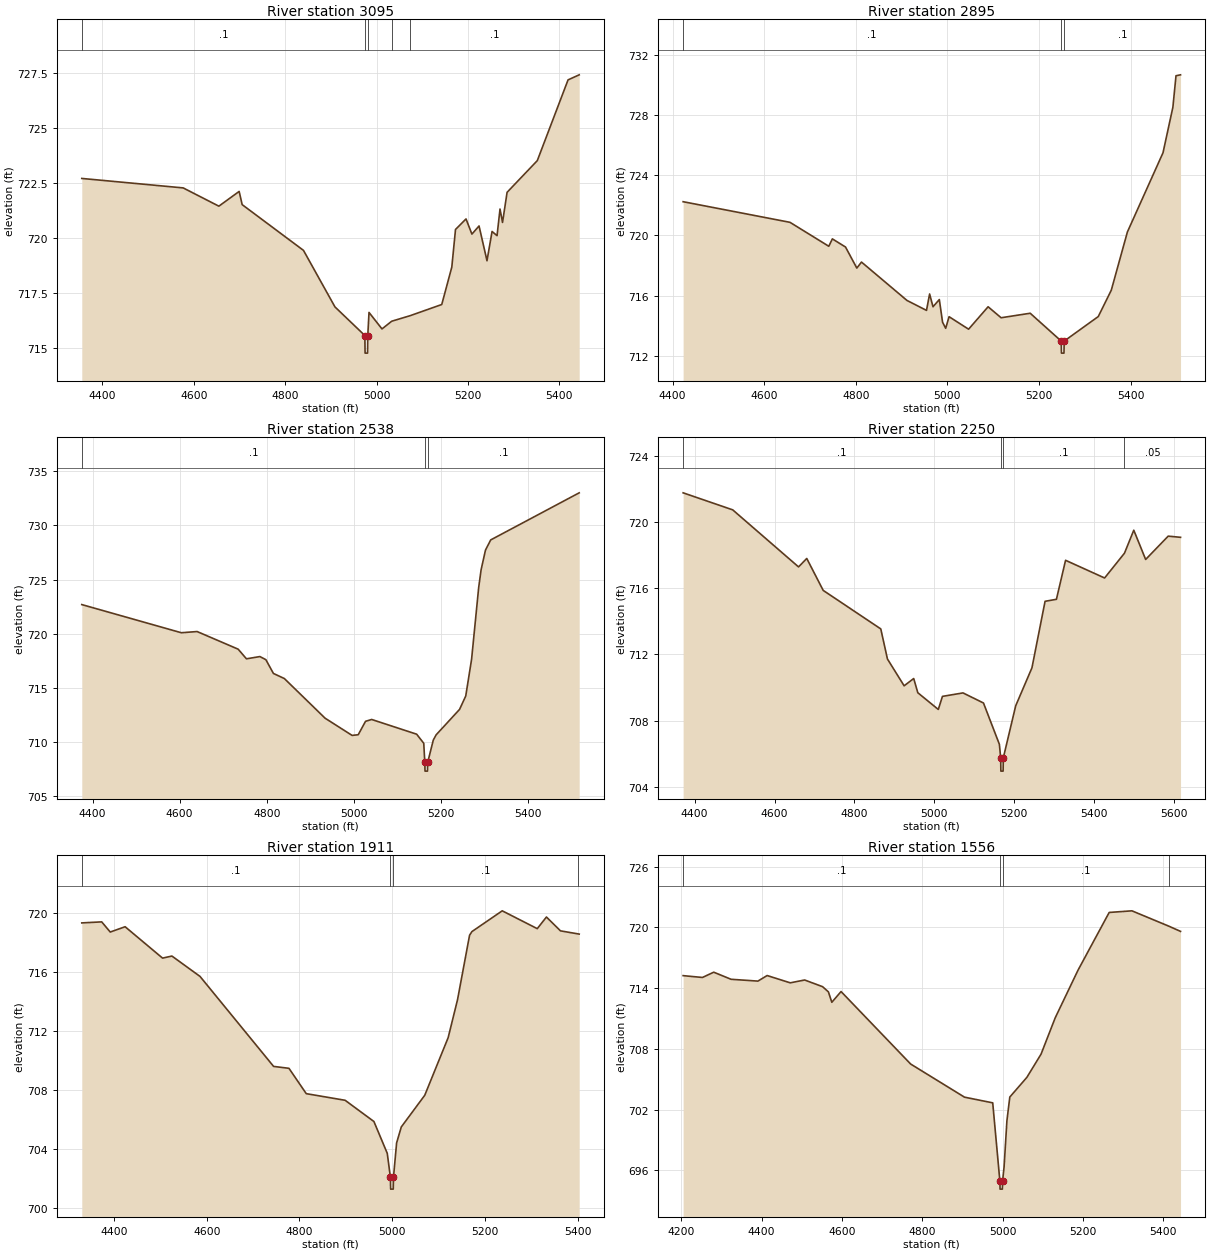
Type RM Length L Ch R = 1,3095,200,200,200
BEGIN DESCRIPTION:
Mapping XS 4b0d0264
END DESCRIPTION:
XS GIS Cut Line= 3
      1985960.92     13623075.93      1985644.04     13622863.23
      1985001.65     13622568.08
#Sta/Elev= 30
  4354.9  722.69  4576.8  722.26  4654.9  721.43  4699.3  722.10  4705.9  721.50
  4840.1  719.42  4909.0  716.85  4974.4  715.55  4974.9  714.75  4980.3  714.75
  4980.8  715.55  4983.5  716.60  5011.9  715.85  5033.2  716.20  5073.2  716.45
  5142.7  716.96  5164.7  718.66  5172.8  720.37  5195.8  720.85  5208.7  720.16
  5224.3  720.53  5241.7  718.95  5252.8  720.28  5263.7  720.09  5270.2  721.30
  5275.7  720.69  5285.7  722.06  5351.8  723.50  5419.1  727.17  5443.5  727.40
#Mann=5,-1,0
  4354.9     0.1       0  4974.4    0.07       0  4980.8     0.1       0
  5033.2    0.16       0  5073.2     0.1       0
Bank Sta=4974.4,4980.8
Exp/Cntr=0.3,0.1

Type RM Length L Ch R = 1,2895,357,357,357
BEGIN DESCRIPTION:
UNT 050 in HW 6.0
END DESCRIPTION:
XS GIS Cut Line= 3
      1985939.15     13622989.07      1985644.04     13622746.04
      1985170.96     13622225.23
#Sta/Elev= 30
  4423.2  722.24  4656.5  720.87  4741.2  719.28  4749.0  719.77  4777.7  719.23
  4802.4  717.83  4812.6  718.23  4911.9  715.68  4954.5  715.02  4961.3  716.11
  4968.7  715.26  4982.5  715.74  4989.6  714.23  4996.4  713.83  5003.8  714.60
  5046.4  713.77  5089.0  715.26  5117.4  714.53  5180.9  714.83  5248.6  712.98
  5249.1  712.18  5254.6  712.18  5255.1  712.98  5329.5  714.61  5357.9  716.36
  5393.1  720.23  5470.8  725.49  5492.4  728.52  5499.2  730.61  5509.1  730.67
#Mann=3,-1,0
  4423.2     0.1       0  5248.6    0.07       0  5255.1     0.1       0
Bank Sta=5248.6,5255.1
Exp/Cntr=0.3,0.1

Type RM Length L Ch R = 1,2538,288,288,288
BEGIN DESCRIPTION:
UNT 050 in HW 5.0
END DESCRIPTION:
XS GIS Cut Line= 3
      1986016.44     13623063.77      1985794.21     13622431.81
      1985572.00     13622015.16
#Sta/Elev= 30
  4375.4  722.69  4603.9  720.09  4640.2  720.20  4734.5  718.57  4753.5  717.68
  4784.4  717.89  4798.1  717.60  4815.4  716.33  4840.5  715.86  4934.0  712.20
  4996.0  710.61  5010.1  710.67  5026.9  711.91  5041.0  712.08  5144.3  710.72
  5160.6  709.88  5163.0  708.11  5163.5  707.31  5169.1  707.31  5169.6  708.11
  5182.5  710.18  5189.0  710.66  5242.8  713.01  5257.0  714.25  5270.4  717.63
  5286.7  724.27  5292.3  725.91  5302.3  727.72  5314.3  728.66  5517.5  733.01
#Mann=3,-1,0
  4375.4     0.1       0  5163.0    0.07       0  5169.6     0.1       0
Bank Sta=5163,5169.6
Exp/Cntr=0.3,0.1

Type RM Length L Ch R = 1,2250,339,339,339
BEGIN DESCRIPTION:
UNT 050 in HW 4.0
END DESCRIPTION:
XS GIS Cut Line= 3
      1986221.30     13623025.57      1986075.00     13622425.00
      1985953.93     13621810.25
#Sta/Elev= 30
  4371.2  721.77  4495.3  720.74  4660.0  717.29  4680.6  717.80  4721.7  715.87
  4865.8  713.54  4882.5  711.72  4924.2  710.10  4948.2  710.54  4958.5  709.68
  5009.7  708.67  5020.1  709.46  5071.5  709.67  5122.8  709.06  5162.6  706.56
  5165.8  705.74  5166.3  704.94  5171.9  704.94  5172.4  705.74  5203.4  708.89
  5244.1  711.19  5276.9  715.21  5305.3  715.33  5328.2  717.69  5425.9  716.62
  5475.6  718.12  5498.9  719.51  5528.6  717.74  5585.0  719.15  5615.9  719.08
#Mann=4,-1,0
  4371.2     0.1       0  5165.8    0.07       0  5172.4     0.1       0
  5475.6    0.05       0
Bank Sta=5165.8,5172.4
Exp/Cntr=0.3,0.1

Type RM Length L Ch R = 1,1911,355,355,355
BEGIN DESCRIPTION:
Mapping XS 87d05445
END DESCRIPTION:
XS GIS Cut Line= 2
      1986419.22     13622907.52      1986266.44     13621845.05
#Sta/Elev= 30
  4330.2  719.35  4373.2  719.42  4391.6  718.73  4423.7  719.09  4504.5  716.96
  4524.7  717.10  4585.3  715.72  4744.1  709.61  4777.3  709.48  4814.6  707.76
  4898.5  707.31  4960.6  705.87  4989.4  703.71  4996.2  702.08  4996.7  701.28
  5002.3  701.28  5002.8  702.08  5009.6  704.42  5019.7  705.50  5070.3  707.65
  5120.8  711.56  5141.0  714.13  5167.0  718.51  5172.1  718.76  5237.5  720.17
  5313.1  718.96  5332.9  719.75  5363.2  718.81  5400.1  718.61  5403.6  718.59
#Mann=4,-1,0
  4330.2     0.1       0  4996.2    0.07       0  5002.8     0.1       0
  5400.1    0.05       0
Bank Sta=4996.2,5002.8
Exp/Cntr=0.3,0.1

Type RM Length L Ch R = 1,1556,491,491,491
BEGIN DESCRIPTION:
UNT 050 in HW 3.0
END DESCRIPTION:
XS GIS Cut Line= 3
      1987037.28     13622806.82      1986690.05     13622195.70
      1986315.08     13621813.79
#Sta/Elev= 30
  4204.9  715.24  4253.0  715.06  4281.1  715.58  4324.3  714.88  4391.0  714.70
  4414.0  715.25  4471.5  714.53  4507.4  714.81  4552.0  714.15  4566.5  713.64
  4575.0  712.61  4598.0  713.67  4771.3  706.51  4905.3  703.24  4975.5  702.68
  4993.3  694.96  4993.8  694.16  4999.5  694.16  5000.0  694.96  5003.8  696.36
  5010.8  700.90  5018.0  703.25  5060.4  705.19  5095.7  707.48  5131.1  711.08
  5187.7  715.77  5265.4  721.48  5322.0  721.64  5414.7  720.11  5443.0  719.61
#Mann=4,-1,0
  4204.9     0.1       0  4993.3    0.07       0  5000.0     0.1       0
  5414.7    0.05       0
Bank Sta=4993.3,5000
Exp/Cntr=0.3,0.1

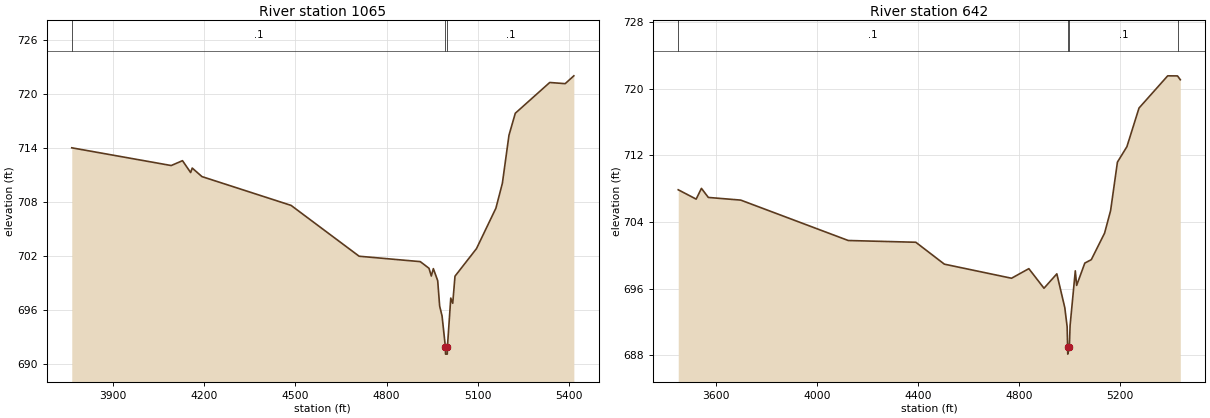
Type RM Length L Ch R = 1,1065,423,423,423
BEGIN DESCRIPTION:
UNT 050 in HW 2.0
END DESCRIPTION:
XS GIS Cut Line= 3
      1987242.12     13622817.18      1986919.21     13621820.70
      1986453.91     13621435.26
#Sta/Elev= 30
  3764.6  714.07  4091.7  712.10  4128.9  712.64  4155.7  711.32  4160.9  711.82
  4192.9  710.87  4486.1  707.67  4710.0  702.02  4911.1  701.42  4939.8  700.68
  4947.4  699.82  4954.1  700.64  4968.4  699.31  4974.9  696.47  4982.8  695.38
  4993.7  691.94  4994.2  691.14  4999.9  691.14  5000.4  691.94  5011.4  697.37
  5017.9  696.79  5025.3  699.80  5096.1  702.87  5159.9  707.36  5181.2  710.13
  5202.9  715.47  5223.7  717.91  5337.0  721.33  5387.8  721.20  5416.3  722.07
#Mann=3,-1,0
  3764.6     0.1       0  4993.7    0.07       0  5000.4     0.1       0
Bank Sta=4993.7,5000.4
Exp/Cntr=0.3,0.1

Type RM Length L Ch R = 1,642,0,0,0
BEGIN DESCRIPTION:
UNT 050 in HW 1.0
END DESCRIPTION:
XS GIS Cut Line= 3
      1987412.26     13622723.44      1987037.27     13621372.78
      1986479.16     13621195.99
#Sta/Elev= 30
  3451.1  707.88  3522.1  706.76  3542.9  708.05  3570.3  706.96  3698.6  706.64
  4124.1  701.79  4391.4  701.58  4504.5  698.95  4770.3  697.26  4838.8  698.41
  4898.8  696.06  4949.6  697.79  4981.1  693.73  4990.4  691.43  4992.3  688.95
  4992.8  688.15  4999.0  688.95  5002.1  691.60  5022.7  698.15  5028.0  696.40
  5060.3  699.08  5086.0  699.49  5138.5  702.67  5162.4  705.38  5189.4  711.20
  5227.0  713.06  5274.8  717.69  5388.4  721.56  5427.2  721.55  5438.3  721.09
#Mann=4,-1,0
  3451.1     0.1       0  4992.3    0.07       0  4999.0     0.1       0
  5427.2    0.05       0
Bank Sta=4992.3,4999
Exp/Cntr=0.3,0.1

Chan Stop Cuts=-1