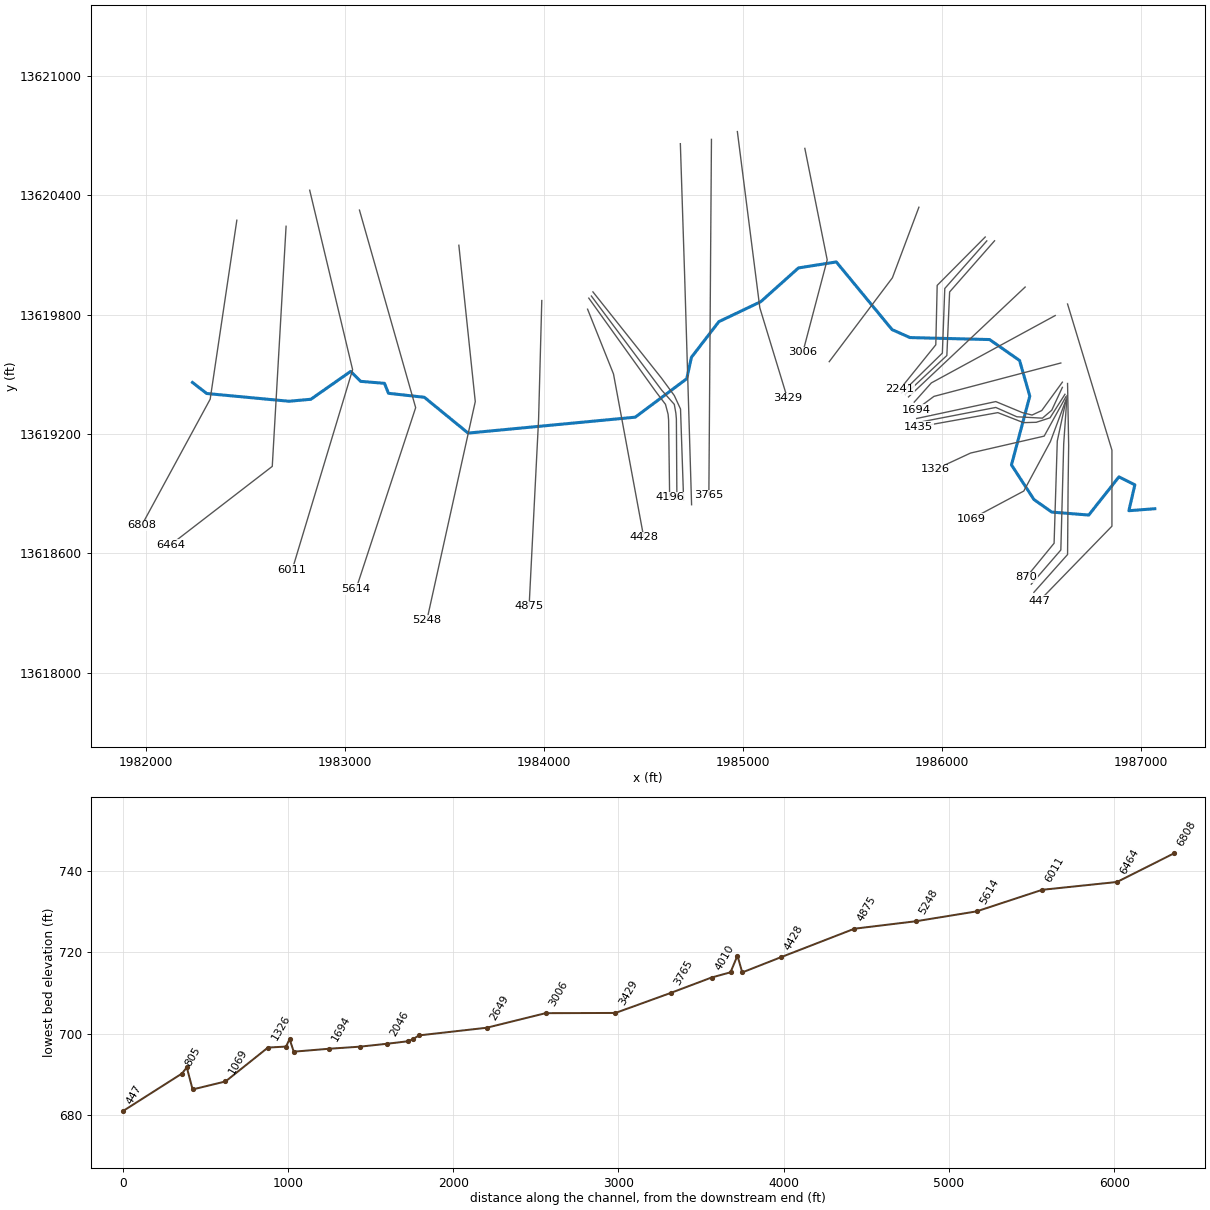
--- UNT 051 in HW.prj (project) ---

Proj Title=UNT 051 in HW Base Level Engineering
Current Plan=p01
Default Exp/Contr=0.3,0.1
English Units
Geom File=g01
Flow File=f01
Plan File=p01
Y Axis Title=Elevation
X Axis Title(PF)=Main Channel Distance
X Axis Title(XS)=Station
BEGIN DESCRIPTION:
UNT 051 in HW
END DESCRIPTION:
DSS Export Rating Curves= 0
DSS Export Rating Curve Sorted= 0
DSS Export Volume Flow Curves= 0
DXF OffsetX= 0
DXF OffsetY= 0
DXF ScaleX= 1
DXF ScaleY= 10

--- UNT 051 in HW.p01 (plan) ---

Plan Title=Multiple Run
Short Identifier=Multiple
Geom File=g01
Flow File=f01
Subcritical Flow
K Sum by GR= 0
Std Step Tol= 0.01
Critical Tol= 0.01
Num of Std Step Trials= 20
Max Error Tol= 0.3
Flow Tol Ratio= 0.001
Split Flow NTrial= 30
Split Flow Tol= 0.02
Split Flow Ratio= 0.02
Log Output Level= 0
Friction Slope Method= 1
Unsteady Friction Slope Method= 2
Unsteady Bridges Friction Slope Method= 1
Parabolic Critical Depth
Global Vel Dist=  1 , 1 , 1
Global Log Level= 0
CheckData=True
Encroach Param= -1, 0, 0, 0
BEGIN DESCRIPTION:
Multiple Run
END DESCRIPTION:

--- UNT 051 in HW.f01 (steady flow) ---

Flow Title=Multiple
Number of Profiles=7
Profile Names=10-year,25-year,50-year,1pct_min,100-year,1pct_plu,500-year
River Rch & RM= UNT 051 in HW,Reach-1,6808
     684     979    1230     765    1527    3047    2363
Boundary for River Rch & Prof#=UNT 051 in HW,Reach-1,1
Up Type=0
Dn Type=3
Dn Slope=0.005
Boundary for River Rch & Prof#=UNT 051 in HW,Reach-1,2
Up Type=0
Dn Type=3
Dn Slope=0.005
Boundary for River Rch & Prof#=UNT 051 in HW,Reach-1,3
Up Type=0
Dn Type=3
Dn Slope=0.005
Boundary for River Rch & Prof#=UNT 051 in HW,Reach-1,4
Up Type=0
Dn Type=3
Dn Slope=0.005
Boundary for River Rch & Prof#=UNT 051 in HW,Reach-1,5
Up Type=0
Dn Type=3
Dn Slope=0.005
Boundary for River Rch & Prof#=UNT 051 in HW,Reach-1,6
Up Type=0
Dn Type=3
Dn Slope=0.005
Boundary for River Rch & Prof#=UNT 051 in HW,Reach-1,7
Up Type=0
Dn Type=3
Dn Slope=0.005

--- UNT 051 in HW.g01 (geometry) ---

Geom Title=Existing Conditions
Program Version=5.05

River Reach=UNT 051 in HW   ,Reach-1
Reach XY= 30
      1982235.97       13619459.      1982307.49     13619403.44
       1982720.8     13619364.54       1982830.8     13619374.54
       1983030.8     13619514.54       1983080.8     13619464.54
       1983200.8     13619454.54       1983220.8     13619404.54
       1983400.8     13619384.54       1983620.8     13619204.54
       1984460.8     13619284.54       1984719.3     13619477.75
      1984742.91     13619585.39       1984880.8     13619764.54
       1985090.8     13619864.54       1985280.8     13620034.54
       1985470.8     13620064.54       1985750.8     13619724.54
       1985840.8     13619684.54       1986240.8     13619674.54
      1986391.52     13619569.41      1986442.91     13619390.25
       1986350.8     13619044.54      1986463.74      13618870.8
      1986553.33     13618807.61      1986739.01     13618792.75
       1986890.8     13618984.54       1986970.8     13618944.54
       1986940.8     13618814.54       1987070.8     13618824.54

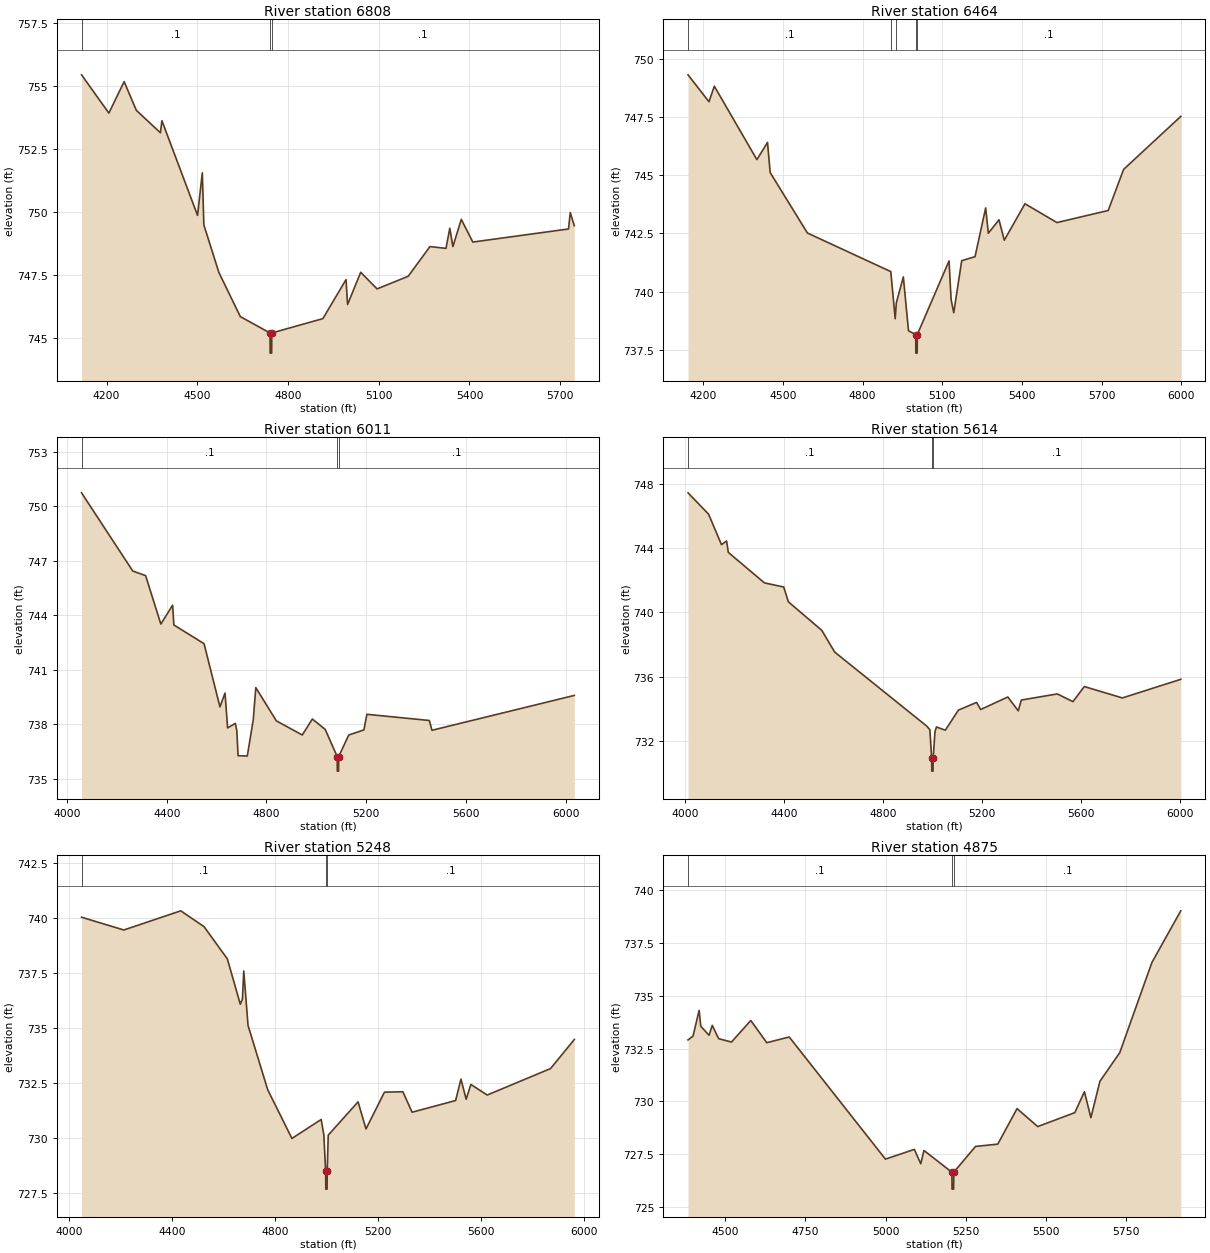
Type RM Length L Ch R = 1 ,6808    ,344,344,344
BEGIN DESCRIPTION:
UNT 051 in HW 12.0
END DESCRIPTION:
XS GIS Cut Line= 3
      1982458.93     13620274.27        1982325.       13619375.
      1981981.48     13618742.11
#Sta/Elev= 30
  4117.4  755.43  4207.7  753.91  4258.2  755.16  4298.6  754.02  4378.1  753.13
  4383.1  753.61  4500.9  749.85  4516.7  751.54  4521.8  749.47  4571.6  747.58
  4642.4  745.83  4740.5  745.18    4741  744.38    4746  744.38  4746.5  745.18
  4915.4  745.75  4991.9   747.3    4997  746.31  5040.4  747.59  5094.6  746.93
  5197.3  747.43  5269.4  748.61  5322.4  748.54    5335  749.34  5345.2  748.61
    5373  749.69  5411.1  748.79  5727.6  749.31  5733.3  749.96  5746.7  749.44
#Mann= 3 ,-1 , 0
  4117.4      .1       0  4740.5     .07       0  4746.5      .1       0
Bank Sta=4740.5,4746.5
XS Rating Curve= 0 ,0
Exp/Cntr=0.3,0.1

Type RM Length L Ch R = 1 ,6464    ,453,453,453
BEGIN DESCRIPTION:
Mapping XS 7bdecf06
END DESCRIPTION:
XS GIS Cut Line= 3
      1982706.32     13620243.84      1982636.88     13619037.28
      1982124.74     13618642.33
#Sta/Elev= 30
    4143  749.33    4222  748.17    4242  748.84  4402.3  745.68  4442.3  746.42
  4452.4  745.12  4592.6  742.52  4906.4  740.86  4923.1  738.83  4927.4  739.52
  4953.7  740.63  4973.2  738.31  5000.3  738.15  5000.8  737.35  5005.8  737.35
  5006.3  738.15  5125.8  741.32  5133.5  739.66  5143.5  739.09  5173.5  741.33
  5223.6   741.5  5263.7   743.6  5273.7  742.51  5313.8  743.09  5333.8  742.21
  5411.7  743.78  5532.1  742.97  5725.1  743.49  5783.1  745.26  5998.3  747.54
#Mann= 5 ,-1 , 0
    4143      .1       0  4906.4     .07       0  4927.4      .1       0
  5000.3     .07       0  5006.3      .1       0
Bank Sta=5000.3,5006.3
XS Rating Curve= 0 ,0
Exp/Cntr=0.3,0.1

Type RM Length L Ch R = 1 ,6011    ,397,397,397
BEGIN DESCRIPTION:
UNT 051 in HW 11.0
END DESCRIPTION:
XS GIS Cut Line= 3
        1982825.     13620424.98      1983040.52      13619523.4
      1982737.24     13618518.24
#Sta/Elev= 30
  4058.1  750.75  4263.7  746.44  4315.1  746.19  4376.2  743.52  4423.4  744.56
  4428.5  743.47  4549.6  742.44  4613.3  738.96  4633.7  739.72  4644.1   737.8
    4675  738.05  4680.9  737.66  4686.1  736.27    4723  736.25    4747  738.25
  4757.2  740.02  4839.5  738.19  4943.6  737.41    4984  738.29  5035.6  737.72
  5083.7  736.22  5084.2  735.42  5089.2  735.42  5089.7  736.22  5130.1  737.41
  5190.9  737.69  5202.8  738.55  5453.4  738.21  5463.9  737.67    6035  739.59
#Mann= 3 ,-1 , 0
  4058.1      .1       0  5083.7     .07       0  5089.7      .1       0
Bank Sta=5083.7,5089.7
XS Rating Curve= 0 ,0
Exp/Cntr=0.3,0.1

Type RM Length L Ch R = 1 ,5614    ,366,366,366
BEGIN DESCRIPTION:
UNT 051 in HW 10.0
END DESCRIPTION:
XS GIS Cut Line= 3
      1983074.99     13620325.03      1983357.36     13619332.42
      1983057.88     13618420.95
#Sta/Elev= 30
  4011.8  747.45    4095  746.12    4147  744.22  4167.8  744.45  4174.6  743.74
  4320.5  741.84  4398.6  741.58  4417.3  740.66  4552.5  738.88  4604.4  737.53
  4976.9  732.91  4989.1  732.69  4996.5  730.91    4997  730.11    5002  730.11
  5002.5  730.91  5009.9  732.57    5016  732.86  5051.6  732.66  5104.5  733.91
  5177.9  734.39  5194.6  733.95  5304.2  734.73  5346.3  733.87  5358.9  734.54
  5504.2  734.92  5567.4  734.44  5613.4  735.38  5767.1  734.67  6003.2  735.83
#Mann= 3 ,-1 , 0
  4011.8      .1       0  4996.5     .07       0  5002.5      .1       0
Bank Sta=4996.5,5002.5
XS Rating Curve= 0 ,0
Exp/Cntr=0.3,0.1

Type RM Length L Ch R = 1 ,5248    ,373,373,373
BEGIN DESCRIPTION:
UNT 051 in HW 9.0
END DESCRIPTION:
XS GIS Cut Line= 3
      1983574.38     13620148.39      1983656.84      13619362.8
      1983413.78     13618264.69
#Sta/Elev= 30
    4048  740.03  4212.3  739.45  4433.5  740.32    4524   739.6  4614.5  738.14
  4664.8  736.08  4673.2  736.32  4678.2  737.59  4694.9  735.12  4771.3   732.2
  4865.4  729.99    4979  730.85  4989.3  730.16  4996.5  728.49    4997  727.69
    5002  727.69  5002.5  728.49  5006.5  730.14  5122.4  731.65  5153.2  730.42
  5224.9  732.09  5296.5  732.11  5332.3  731.18  5501.4  731.71  5522.2  732.68
  5542.4  731.77  5560.7  732.44  5624.3  731.96  5870.1  733.16  5962.6  734.48
#Mann= 3 ,-1 , 0
    4048      .1       0  4996.5     .07       0  5002.5      .1       0
Bank Sta=4996.5,5002.5
XS Rating Curve= 0 ,0
Exp/Cntr=0.3,0.1

Type RM Length L Ch R = 1 ,4875    ,447,447,447
BEGIN DESCRIPTION:
UNT 051 in HW 8.0
END DESCRIPTION:
XS GIS Cut Line= 3
      1983991.04      13619870.6        1983975.       13619275.
       1983927.4     13618334.92
#Sta/Elev= 30
  4383.7  732.91  4399.3  733.09  4418.4  734.31  4423.4  733.56  4449.3  733.13
  4459.3   733.6  4479.3  732.97  4519.3  732.81  4579.4  733.83  4629.4  732.78
  4699.4  733.05  4999.5  727.27  5089.7  727.73  5109.7  727.05  5119.7  727.68
  5206.8  726.65  5207.3  725.85  5212.3  725.85  5212.8  726.65  5280.5  727.87
    5350  727.98  5410.1  729.66  5474.5  728.81  5590.3  729.47  5620.3  730.46
  5640.4  729.23  5668.5  730.95  5730.5  732.31  5830.6  736.57  5920.8  739.02
#Mann= 3 ,-1 , 0
  4383.7      .1       0  5206.8     .07       0  5212.8      .1       0
Bank Sta=5206.8,5212.8
XS Rating Curve= 0 ,0
Exp/Cntr=0.3,0.1

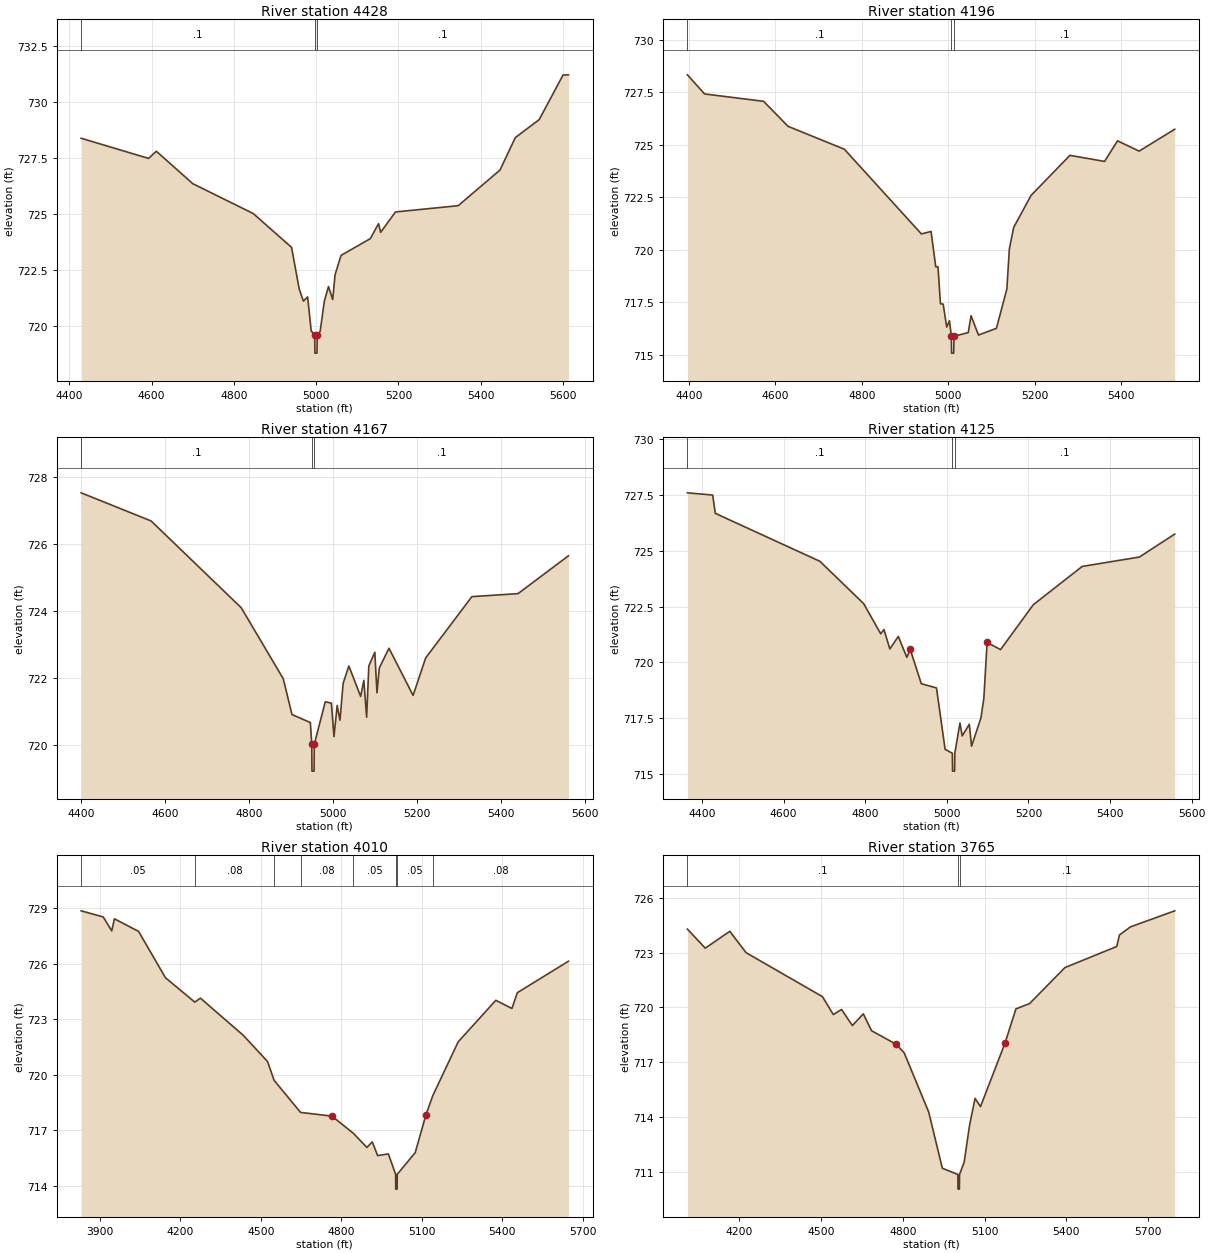
Type RM Length L Ch R = 1 ,4428    ,232,232,232
BEGIN DESCRIPTION:
UNT 051 in HW 7.0
END DESCRIPTION:
XS GIS Cut Line= 3
       1984221.1     13619827.17      1984351.29     13619501.69
       1984503.2     13618681.39
#Sta/Elev= 30
  4428.6  728.39  4592.5  727.49  4611.4  727.81  4700.2  726.36    4847  725.03
  4940.2  723.52  4958.8  721.66    4969  721.12  4979.2  721.31    4988  719.79
  4996.5   719.6    4997   718.8    5002   718.8  5002.5   719.6  5009.7  719.77
  5019.9  721.12    5030  721.77  5040.2  721.19    5046   722.3  5060.5  723.16
  5131.7  723.91  5151.7  724.58  5156.8  724.19  5192.8   725.1  5345.3  725.38
    5447  726.97  5484.3  728.42  5542.3  729.22  5600.2  731.21  5613.4  731.22
#Mann= 3 ,-1 , 0
  4428.6      .1       0  4996.5     .07       0  5002.5      .1       0
Bank Sta=4996.5,5002.5
XS Rating Curve= 0 ,0
Exp/Cntr=0.3,0.1

Type RM Length L Ch R = 1 ,4196    ,29,29,29
BEGIN DESCRIPTION:
Mapping XS 5cf9c1e3
END DESCRIPTION:
XS GIS Cut Line= 6
      1984227.18     13619882.74      1984563.09     13619414.02
      1984612.57     13619348.92      1984625.59     13619299.44
       1984628.2     13619270.79      1984633.41     13618882.79
#Sta/Elev= 30
  4396.8  728.33  4436.5  727.42  4572.9  727.07  4629.4  725.88  4759.6  724.79
  4937.7  720.76    4960  720.88  4970.8   719.2    4976   719.2  4981.7  717.44
    4988  717.42  4996.2  716.33  5002.5  716.63  5006.9  715.89  5007.4  715.09
  5012.4  715.09  5012.9  715.89  5046.1  716.07  5052.4  716.87  5069.6  715.95
  5111.1  716.27  5135.2  718.14    5141  720.05    5151  721.07    5191  722.59
    5281   724.5    5361  724.21    5391  725.19    5441   724.7  5523.2  725.74
#Mann= 3 ,-1 , 0
  4396.8      .1       0  5006.9     .07       0  5012.9      .1       0
Bank Sta=5006.9,5012.9
XS Rating Curve= 0 ,0
Exp/Cntr=0.3,0.1

Type RM Length L Ch R = 1 ,4167    ,42,42,42
BEGIN DESCRIPTION:
Mapping XS 203be81b
END DESCRIPTION:
XS GIS Cut Line= 6
      1984240.15     13619893.22      1984594.34     13619419.23
      1984656.84     13619348.92      1984664.66     13619304.65
      1984667.26       13619276.      1984669.86     13618875.01
#Sta/Elev= 30
  4400.4  727.53    4567  726.69  4781.6   724.1  4881.7  721.98  4902.5  720.91
  4946.3  720.67  4949.6  720.02  4950.1  719.22  4955.1  719.22  4955.6  720.02
  4981.8  721.29  4996.4  721.25  5002.5  720.25  5010.1  721.18  5016.8  720.74
  5024.3  721.84  5037.9  722.36  5066.1  721.45  5073.6  721.93  5080.3  720.83
  5085.5  722.36  5099.8  722.77  5104.9  721.56  5110.5   722.3  5133.5  722.89
  5190.9  721.48  5220.9   722.6  5330.9  724.43  5440.9  724.52  5560.9  725.65
#Mann= 3 ,-1 , 0
  4400.4      .1       0  4949.6     .07       0  4955.6      .1       0
Bank Sta=4949.6,4955.6
XS Rating Curve= 0 ,0
Exp/Cntr=0.3,0.1

Type RM Length L Ch R = 1 ,4125    ,115,115,115
BEGIN DESCRIPTION:
Mapping XS 03d30d15
END DESCRIPTION:
XS GIS Cut Line= 5
      1984247.96     13619914.05      1984591.74     13619481.73
      1984656.84     13619393.19      1984688.09     13619325.48
      1984703.67     13618868.56
#Sta/Elev= 30
  4364.5   727.6  4426.4   727.5  4432.8  726.68  4689.1  724.53  4796.4  722.63
  4838.1  721.28  4846.1  721.47  4860.5   720.6  4881.3  721.16  4902.1  720.22
  4910.2  720.59  4937.6  719.04  4974.8  718.85  4995.9   716.1  5013.7  715.92
  5014.2  715.12  5019.2  715.12  5019.7  715.92  5032.3  717.28  5037.8   716.7
  5055.2  717.22  5060.7  716.24  5083.7  717.51  5090.8  718.38  5098.8  720.89
  5131.8  720.57  5211.9  722.58  5331.9   724.3    5472  724.72  5558.5  725.75
#Mann= 3 ,-1 , 0
  4364.5      .1       0  5013.7     .07       0  5019.7      .1       0
Bank Sta=4910.2,5098.8
XS Rating Curve= 0 ,0
Exp/Cntr=0.3,0.1

Type RM Length L Ch R = 1 ,4010    ,245,245,245
BEGIN DESCRIPTION:
UNT 051 in HW 6.0
END DESCRIPTION:
XS GIS Cut Line= 3
      1984687.23     13620658.81      1984708.93     13619990.41
      1984743.65     13618844.59
#Sta/Elev= 30
  3830.8  728.85    3913  728.52  3944.7  727.77  3954.7  728.42  4044.7  727.74
  4144.8  725.24  4254.2  723.92  4274.8  724.14  4434.9  722.13    4525  720.72
  4549.6   719.7  4648.1  717.97  4765.1  717.77  4845.1  716.84  4895.1  716.08
  4915.2  716.38  4935.2  715.64  4975.2  715.73  5002.2  714.63  5002.7  713.83
  5007.7  713.83  5008.2  714.63  5075.2   715.8  5115.2  717.84  5140.5  718.87
  5235.3  721.78  5375.4  724.02  5435.4  723.58  5455.4  724.43  5645.9  726.13
#Mann= 8 ,-1 , 0
  3830.8     .05       0  4254.2     .08       0  4549.6     .05       0
  4648.1     .08       0  4845.1     .05       0  5002.2     .04       0
  5008.2     .05       0  5140.5     .08       0
Bank Sta=4765.1,5115.2
XS Rating Curve= 0 ,0
Exp/Cntr=0.3,0.1

Type RM Length L Ch R = 1 ,3765    ,336,336,336
BEGIN DESCRIPTION:
Mapping XS 5a93daf7
END DESCRIPTION:
XS GIS Cut Line= 2
      1984843.48     13620680.48      1984830.45     13618892.32
#Sta/Elev= 30
  4009.5  724.28    4075  723.24    4165  724.16    4225  722.99    4505  720.59
    4545  719.61    4575  719.89    4615  719.01    4655  719.65    4685  718.73
    4775  717.99    4805  717.52    4895  714.28    4945  711.21    5002  710.87
  5002.5  710.07  5007.5  710.07    5008  710.87    5025  711.54    5045  713.57
    5065  715.03    5085  714.58    5175  718.05    5215  719.92    5265  720.21
    5395  722.18    5585  723.33    5595  723.96    5635   724.4  5797.7  725.28
#Mann= 3 ,-1 , 0
  4009.5      .1       0    5002     .07       0    5008      .1       0
Bank Sta=4775,5175
XS Rating Curve= 0 ,0
Exp/Cntr=0.3,0.1

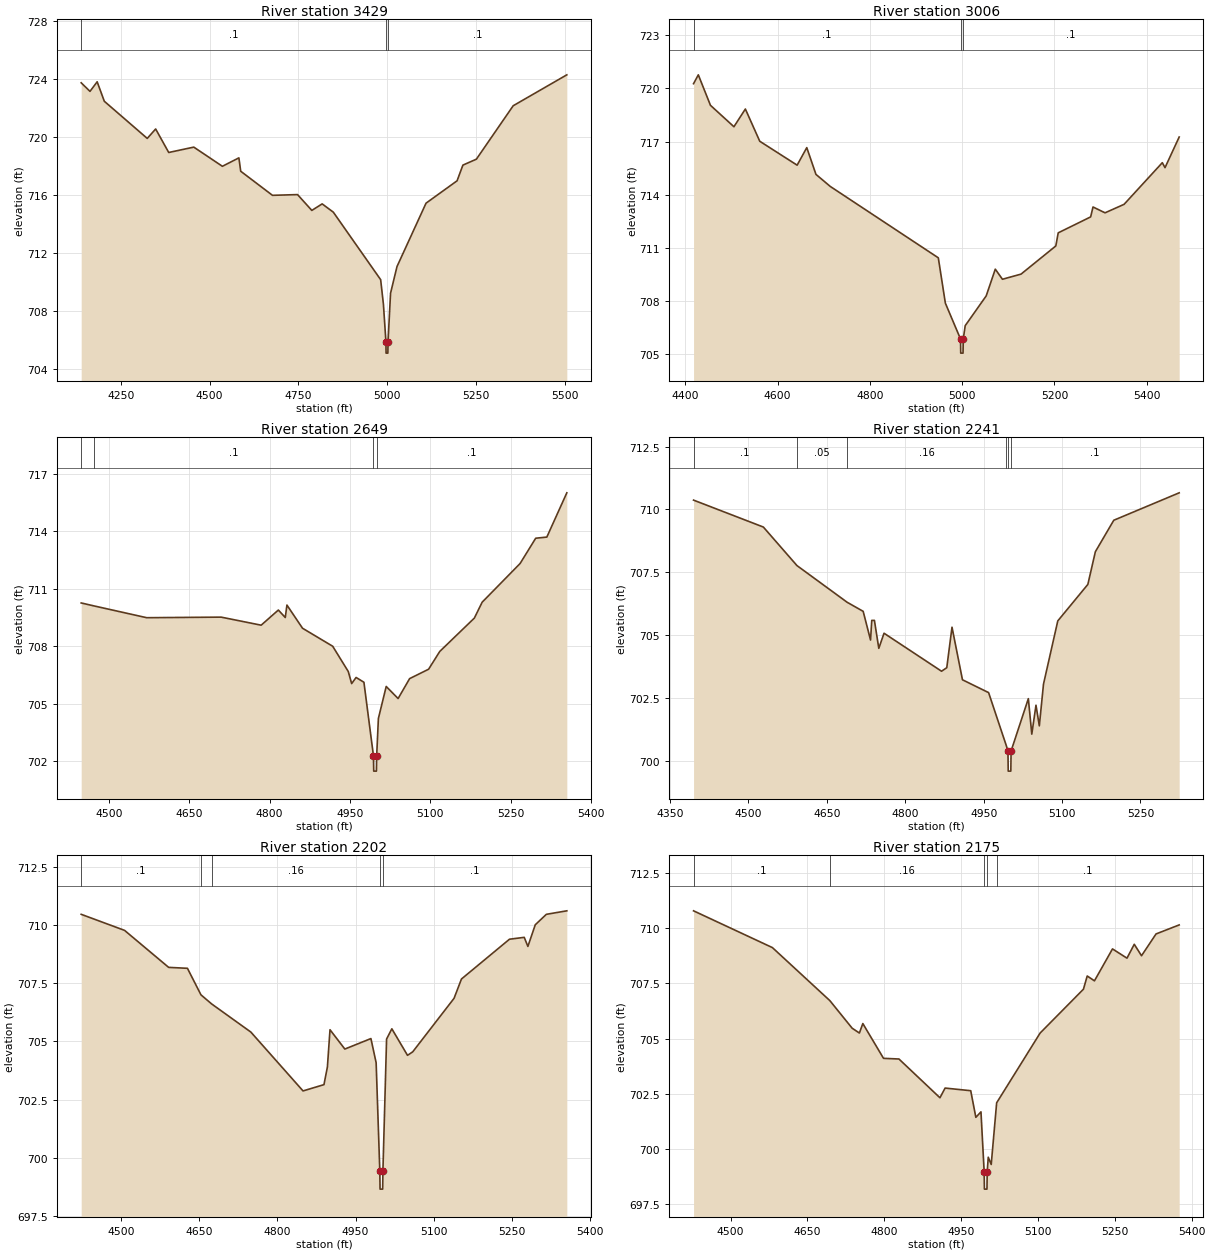
Type RM Length L Ch R = 1 ,3429    ,423,423,423
BEGIN DESCRIPTION:
UNT 051 in HW 5.0
END DESCRIPTION:
XS GIS Cut Line= 3
      1984973.68     13620719.62      1985086.53     13619834.16
      1985225.17     13619379.24
#Sta/Elev= 30
    4138  723.74  4162.8  723.15    4183  723.81  4203.1  722.47  4324.1  719.91
  4347.8  720.56  4384.6  718.94  4455.2  719.31  4535.8  717.99  4582.3  718.57
  4587.4  717.65  4676.9  715.99  4747.5  716.04  4787.8  714.95  4816.9   715.4
  4848.3  714.83  4981.7  710.18  4989.5  708.48  4996.5  705.92    4997  705.12
    5002  705.12  5002.5  705.92  5009.6  709.25  5027.7  711.08  5109.6  715.45
    5197  716.99  5213.4  718.07  5251.4  718.48  5355.1  722.16  5506.2  724.29
#Mann= 3 ,-1 , 0
    4138      .1       0  4996.5     .07       0  5002.5      .1       0
Bank Sta=4996.5,5002.5
XS Rating Curve= 0 ,0
Exp/Cntr=0.3,0.1

Type RM Length L Ch R = 1 ,3006    ,357,357,357
BEGIN DESCRIPTION:
UNT 051 in HW 4.0
END DESCRIPTION:
XS GIS Cut Line= 3
      1985312.67     13620635.13        1985425.       13620075.
      1985302.36     13619609.57
#Sta/Elev= 30
  4417.9  720.27  4428.2  720.77  4454.5  719.05  4505.4  717.84  4530.2  718.84
  4561.4  717.02  4642.4  715.67  4663.3  716.66  4683.2  715.15  4714.2  714.47
  4948.4  710.44  4963.7  707.88  4996.5  705.86    4997  705.06    5002  705.06
  5002.5  705.86  5006.7  706.61  5052.2  708.29  5071.9   709.8  5087.4  709.23
  5127.7  709.52  5203.1  711.11  5208.3  711.85  5278.6  712.75  5283.7  713.31
  5309.8  712.98  5351.1  713.46  5433.9  715.81  5439.8  715.53  5470.5  717.26
#Mann= 3 ,-1 , 0
  4417.9      .1       0  4996.5     .07       0  5002.5      .1       0
Bank Sta=4996.5,5002.5
XS Rating Curve= 0 ,0
Exp/Cntr=0.3,0.1

Type RM Length L Ch R = 1 ,2649    ,408,408,408
BEGIN DESCRIPTION:
UNT 051 in HW 3.0
END DESCRIPTION:
XS GIS Cut Line= 3
      1985885.75      13620339.5       1985752.6      13619984.9
       1985435.2     13619563.42
#Sta/Elev= 30
  4448.3  710.25  4471.5   710.1  4570.6  709.48  4709.5  709.51  4784.2  709.09
  4816.3  709.88  4829.2  709.49  4832.3  710.14  4861.4  708.93  4917.7  707.99
  4946.8  706.67  4953.1  706.04  4961.4  706.36    4976  706.11  4993.8  702.27
  4994.3  701.47  4999.3  701.47  4999.8  702.27    5003  704.22  5017.6  705.89
  5039.8  705.26  5061.3   706.3  5096.7  706.79  5117.6  707.72  5182.1  709.46
  5196.7  710.29  5267.5  712.31  5296.6  713.63  5317.4  713.69  5354.7     716
#Mann= 4 ,-1 , 0
  4448.3     .05       0  4471.5      .1       0  4993.8     .07       0
  4999.8      .1       0
Bank Sta=4993.8,4999.8
XS Rating Curve= 0 ,0
Exp/Cntr=0.3,0.1

Type RM Length L Ch R = 1 ,2241    ,39,39,39
BEGIN DESCRIPTION:
Mapping XS 4e4977eb
END DESCRIPTION:
XS GIS Cut Line= 4
      1986218.89     13620189.82      1985977.59     13619946.79
      1985970.65     13619648.18      1985790.12     13619424.26
#Sta/Elev= 30
  4395.2  710.37  4528.7   709.3  4592.9  707.77    4689  706.31  4719.6  705.95
  4733.7  704.81    4736  705.59  4741.1  705.59  4749.5  704.48  4759.5  705.08
  4869.5  703.57  4879.5  703.71  4889.5  705.32  4909.5  703.23  4959.5  702.72
  4993.4  700.61  4996.5   700.4    4997   699.6    5002   699.6  5002.5   700.4
  5035.5  702.48  5042.1  701.07  5050.1  702.22  5056.5   701.4  5064.5  703.06
  5091.8  705.57  5149.3  707.02  5163.7  708.32  5198.9  709.57    5324  710.66
#Mann= 6 ,-1 , 0
  4395.2      .1       0  4592.9     .05       0    4689     .16       0
  4993.4      .1       0  4996.5     .07       0  5002.5      .1       0
Bank Sta=4996.5,5002.5
XS Rating Curve= 0 ,0
Exp/Cntr=0.3,0.1

Type RM Length L Ch R = 1 ,2202    ,27,27,27
BEGIN DESCRIPTION:
Mapping XS 02056ea3
END DESCRIPTION:
XS GIS Cut Line= 4
      1986226.87      13620170.2      1986015.78     13619931.16
      1986003.63     13619606.51      1985798.59     13619405.95
#Sta/Elev= 30
  4424.3  710.46  4507.4  709.77  4591.9  708.18  4627.9  708.14  4653.8     707
  4674.2  706.61  4749.4   705.4  4849.4  702.87  4889.5  703.14  4896.1   703.9
  4901.1   705.5  4929.5  704.67  4979.5  705.12  4989.5  704.08  4996.5  699.45
    4997  698.65    5002  698.65  5002.5  699.45  5009.5   705.1  5019.6  705.54
  5049.6   704.4  5059.6  704.55  5138.8  706.85    5153  707.68    5245  709.39
  5273.3  709.47  5280.3  709.08  5294.4  710.01  5315.7  710.46  5354.9  710.61
#Mann= 5 ,-1 , 0
  4424.3      .1       0  4653.8     .05       0  4674.2     .16       0
  4996.5     .07       0  5002.5      .1       0
Bank Sta=4996.5,5002.5
XS Rating Curve= 0 ,0
Exp/Cntr=0.3,0.1

Type RM Length L Ch R = 1 ,2175    ,129,129,129
BEGIN DESCRIPTION:
Mapping XS 3103f13c
END DESCRIPTION:
XS GIS Cut Line= 4
       1986265.8     13620170.76      1986040.09      13619913.8
       1986026.2     13619594.36      1985817.07     13619399.06
#Sta/Elev= 30
  4427.8   710.8  4581.7  709.13  4693.9  706.72  4737.3  705.47  4751.5  705.25
  4758.2  705.68  4798.6   704.1  4828.7  704.07  4908.7  702.31  4918.8  702.75
  4968.8  702.63  4978.8  701.42  4988.8  701.67    4995  698.96  4995.5  698.16
  5000.5  698.16    5001  698.96    5003  699.61  5008.8  699.28  5019.4  702.08
  5104.3  705.25  5188.8  707.24  5196.2  707.84  5210.3  707.62  5245.5  709.07
  5273.8  708.65    5288  709.28  5302.2  708.76  5330.5  709.75  5375.7  710.16
#Mann= 5 ,-1 , 0
  4427.8      .1       0  4693.9     .16       0    4995     .07       0
    5001     .16       0  5019.4      .1       0
Bank Sta=4995,5001
XS Rating Curve= 0 ,0
Exp/Cntr=0.3,0.1

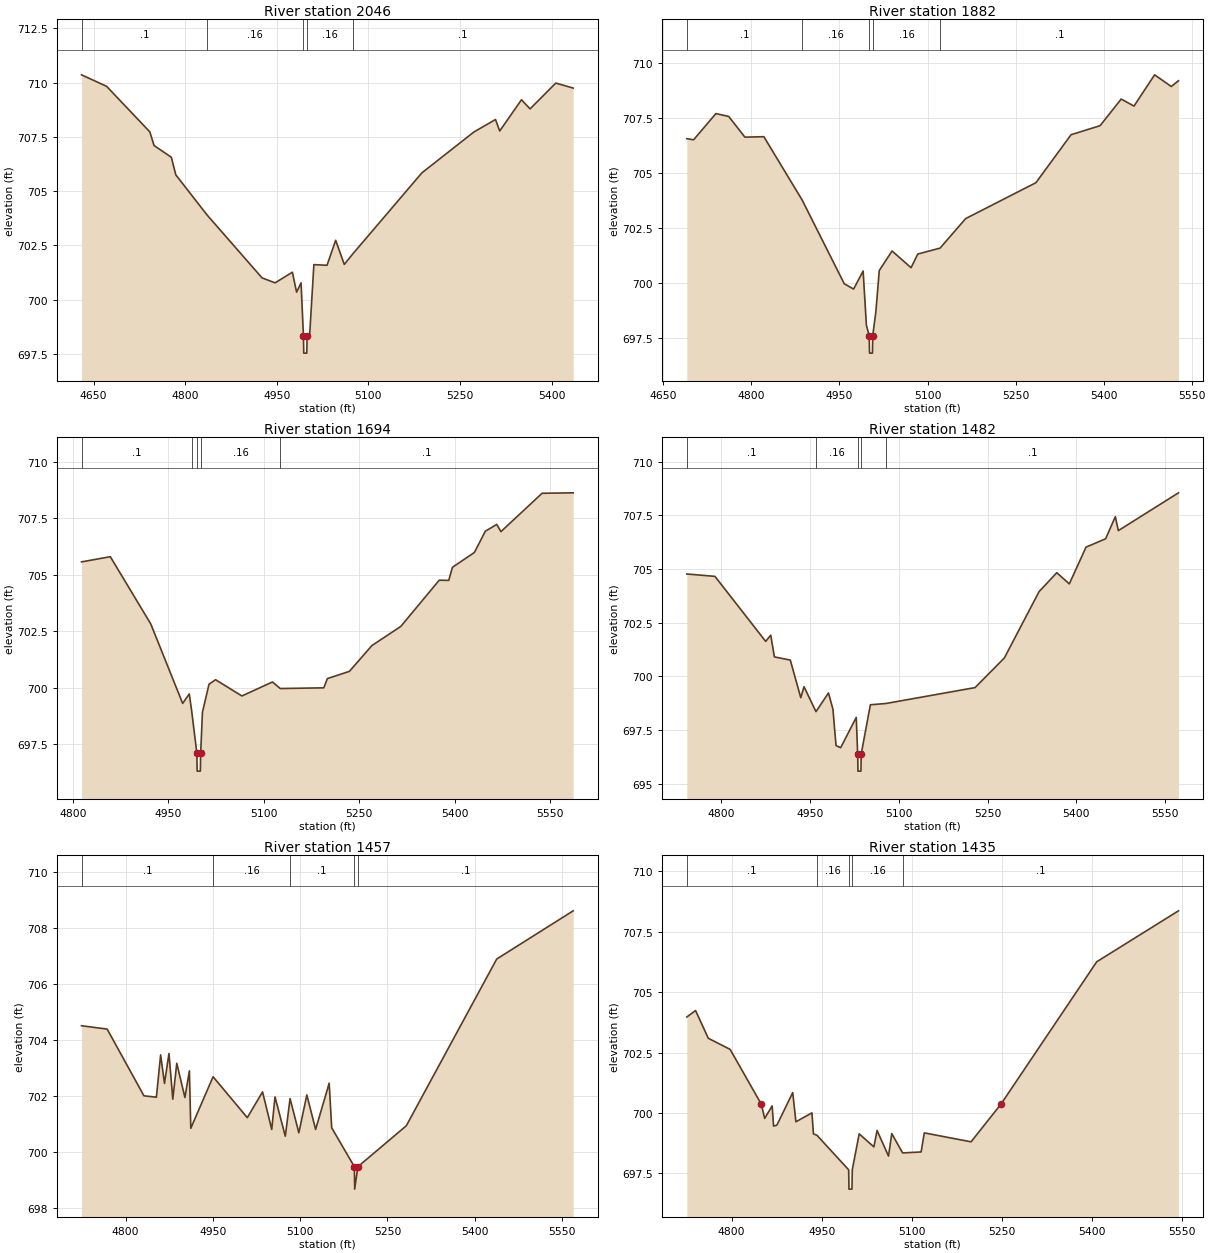
Type RM Length L Ch R = 1 ,2046    ,164,164,164
BEGIN DESCRIPTION:
Mapping XS 2e2408c9
END DESCRIPTION:
XS GIS Cut Line= 2
      1986419.61     13619938.47      1985833.65     13619386.35
#Sta/Elev= 30
  4630.2  710.36  4671.3  709.83  4742.1  707.73    4749   707.1  4777.3  706.56
  4784.6  705.75  4835.8   703.9  4925.8     701  4947.2  700.77  4975.5  701.26
  4982.4  700.34  4989.7  700.77  4993.6  698.33  4994.1  697.53  4999.1  697.53
  4999.6  698.33  5003.9  698.42  5010.7  701.61  5032.2  701.58  5046.4  702.73
  5060.5  701.62  5074.9  702.12  5187.5  705.84  5272.5  707.72  5308.1   708.3
    5315  707.77  5350.6  709.21  5364.7  708.79  5406.8  709.98  5435.3  709.75
#Mann= 5 ,-1 , 0
  4630.2      .1       0  4835.8     .16       0  4993.6     .07       0
  4999.6     .16       0  5074.9      .1       0
Bank Sta=4993.6,4999.6
XS Rating Curve= 0 ,0
Exp/Cntr=0.3,0.1

Type RM Length L Ch R = 1 ,1882    ,188,188,188
BEGIN DESCRIPTION:
Mapping XS 6f671d83
END DESCRIPTION:
XS GIS Cut Line= 3
      1986570.68     13619795.24      1985948.25     13619456.69
      1985862.28      13619360.3
#Sta/Elev= 30
  4689.9  706.56  4701.5  706.51  4739.5   707.7  4761.3  707.57  4788.9  706.63
  4821.2  706.65  4886.5  703.77  4958.2  699.97  4974.1  699.73  4990.3  700.55
  4995.9  698.08  5000.7  697.62  5001.2  696.82  5006.2  696.82  5006.7  697.62
  5012.1  698.72  5017.8  700.57  5039.6  701.46    5072   700.7  5083.4  701.32
  5121.4  701.59    5165  702.93  5284.7  704.56  5344.6  706.74    5394  707.15
    5430  708.36  5451.8  708.04  5486.9  709.46  5515.3  708.93  5527.6  709.19
#Mann= 5 ,-1 , 0
  4689.9      .1       0  4886.5     .16       0  5000.7     .07       0
  5006.7     .16       0  5121.4      .1       0
Bank Sta=5000.7,5006.7
XS Rating Curve= 0 ,0
Exp/Cntr=0.3,0.1

Type RM Length L Ch R = 1 ,1694    ,212,212,212
BEGIN DESCRIPTION:
Mapping XS 3effd046
END DESCRIPTION:
XS GIS Cut Line= 3
      1986598.79     13619556.78      1985961.27     13619388.98
      1985870.11     13619321.26
#Sta/Elev= 30
  4813.7  705.57    4859   705.8  4922.6  702.82  4972.7   699.3  4983.1  699.72
  4986.8  698.98    4995   697.1  4995.5   696.3  5000.5   696.3    5001   697.1
  5003.8  698.91  5014.1  700.15  5024.4  700.35  5065.8  699.63  5113.8  700.25
  5126.1  699.96  5194.5  699.99  5200.2   700.4  5234.8  700.72    5270  701.86
  5315.5  702.71    5376  704.76  5390.9  704.75  5396.7  705.33  5431.3  705.99
  5448.4  706.93  5466.4  707.23  5472.9  706.91  5537.6  708.61  5586.5  708.63
#Mann= 5 ,-1 , 0
  4813.7      .1       0  4986.8     .16       0    4995     .07       0
    5001     .16       0  5126.1      .1       0
Bank Sta=4995,5001
XS Rating Curve= 0 ,0
Exp/Cntr=0.3,0.1

Type RM Length L Ch R = 1 ,1482    ,25,25,25
BEGIN DESCRIPTION:
Mapping XS b91235be
END DESCRIPTION:
XS GIS Cut Line= 6
      1986606.59     13619460.43      1986502.94      13619317.8
      1986454.33     13619295.23      1986405.71     13619307.38
      1986272.03     13619362.94      1985874.51     13619277.88
#Sta/Elev= 30
  4741.5  704.77  4789.1  704.66  4874.9  701.63  4883.4  701.92  4889.6  700.91
  4916.5  700.76  4934.2  699.01  4939.7  699.52  4959.9  698.36    4981  699.23
  4988.6  698.47  4993.8  696.78  5001.6  696.68    5028  698.09  5030.4  696.39
  5030.9  695.59  5035.9  695.59  5036.4  696.39  5051.9  698.68  5078.3  698.74
  5228.9  699.48  5278.4  700.86  5337.1  703.95  5367.1  704.83  5388.2  704.31
  5416.5  706.02  5449.6  706.41    5466  707.44  5471.1  706.79  5572.8  708.55
#Mann= 5 ,-1 , 0
  4741.5      .1       0  4959.9     .16       0  5030.4     .07       0
  5036.4     .16       0  5078.3      .1       0
Bank Sta=5030.4,5036.4
XS Rating Curve= 0 ,0
Exp/Cntr=0.3,0.1

Type RM Length L Ch R = 1 ,1457    ,22,22,22
BEGIN DESCRIPTION:
Mapping XS 6c7b53ec
END DESCRIPTION:
XS GIS Cut Line= 6
      1986606.54     13619434.31      1986553.28     13619319.53
      1986506.41      13619279.6      1986377.94     13619286.55
      1986272.03     13619333.42      1985868.74     13619255.53
#Sta/Elev= 30
  4724.2   704.5  4768.3  704.38  4831.5     702  4852.9  701.95  4860.2  703.46
  4866.8  702.44  4874.5  703.51  4881.1  701.88  4887.9  703.16  4901.9  701.94
  4909.6  702.89    4912  700.84  4950.3  702.68  5009.1  701.22  5035.3  702.14
  5051.1   700.8  5056.7  701.96  5074.4  700.56  5082.6   701.9  5097.7  700.68
  5111.4  702.03  5126.5   700.8  5149.8  702.45  5154.1  700.86  5193.1  699.47
  5193.6  698.67  5199.1  699.47  5282.3  700.93  5437.7  706.88  5569.1   708.6
#Mann= 5 ,-1 , 0
  4724.2      .1       0  4950.3     .16       0  5082.6      .1       0
  5193.1     .07       0  5199.1      .1       0
Bank Sta=5193.1,5199.1
XS Rating Curve= 0 ,0
Exp/Cntr=0.3,0.1

Type RM Length L Ch R = 1 ,1435    ,109,109,109
BEGIN DESCRIPTION:
Mapping XS 6152f1d3
END DESCRIPTION:
XS GIS Cut Line= 6
      1986619.56     13619399.59       1986544.6     13619281.34
      1986475.16     13619258.77      1986410.92     13619257.03
      1986282.45     13619307.38      1985884.84     13619236.19
#Sta/Elev= 30
  4725.3  703.97  4739.9  704.24  4761.1  703.09  4797.5  702.63 4849.38700.3611
  4855.1  699.77  4867.5  700.29  4869.9  699.45  4875.4  699.49  4901.8  700.84
  4907.1  699.63  4933.8     700  4936.3  699.13  4942.2  699.07    4995  697.64
  4995.5  696.84  5000.5  696.84    5001  697.64  5012.5  699.13    5037  698.59
  5042.3  699.27  5061.4  698.21  5066.8  699.14  5084.9  698.34  5115.7  698.38
    5121  699.17  5198.9   698.8 5248.69700.3604  5408.3  706.26  5544.5  708.37
#Mann= 5 ,-1 , 0
  4725.3      .1       0  4942.2     .16       0    4995     .07       0
    5001     .16       0  5084.9      .1       0
Bank Sta=4849.38,5248.69
XS Rating Curve= 0 ,0
Exp/Cntr=0.3,0.1

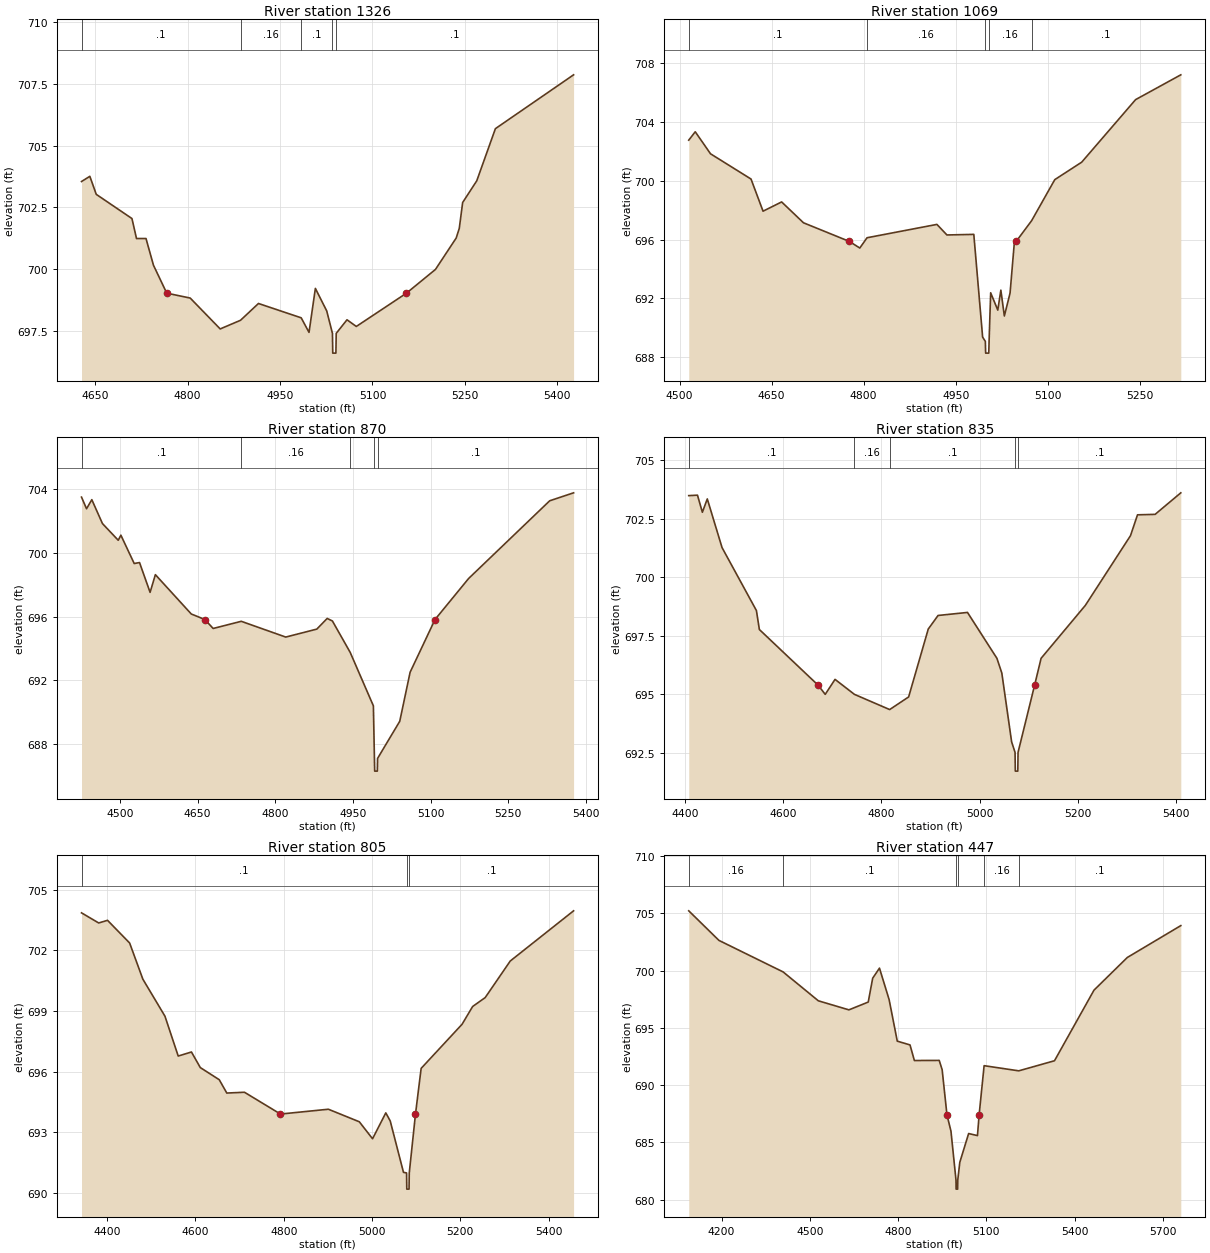
Type RM Length L Ch R = 1 ,1326    ,257,257,257
BEGIN DESCRIPTION:
Mapping XS ccd8d057
END DESCRIPTION:
XS GIS Cut Line= 4
      1986623.92     13619386.59      1986515.09     13619189.32
       1986145.3     13619104.25        1985970.     13619022.68
#Sta/Elev= 30
  4628.1  703.55  4641.6  703.76    4652  703.03  4709.9  702.05  4717.3  701.24
  4732.7  701.24  4744.8  700.16 4766.35699.0283  4804.4  698.83    4853  697.58
    4886  697.93  4915.1  698.61  4984.4  698.03  4997.1  697.44  5007.4  699.22
  5025.8  698.31  5035.1   697.4  5035.6   696.6  5040.7   696.6  5041.2   697.4
  5058.7  697.95  5073.8  697.68 5155.16699.0283  5202.2  699.99  5235.8  701.26
  5240.8  701.65  5246.3   702.7  5269.2  703.58  5299.4  705.69  5426.2  707.87
#Mann= 5 ,-1 , 0
  4628.1      .1       0    4886     .16       0  4984.4      .1       0
  5035.1     .07       0  5041.2      .1       0
Bank Sta=4766.35,5155.16
XS Rating Curve= 0 ,0
Exp/Cntr=0.3,0.1

Type RM Length L Ch R = 1 ,1069    ,199,199,199
BEGIN DESCRIPTION:
Mapping XS 83df534c
END DESCRIPTION:
XS GIS Cut Line= 4
      1986623.93     13619369.26      1986546.34     13619161.55
      1986412.66     13618913.28      1986149.41       13618773.
#Sta/Elev= 30
  4514.9  702.77  4525.5  703.34  4550.4  701.84  4616.4  700.12    4636  697.93
  4666.3  698.56  4701.9  697.14 4776.87695.8666  4793.7  695.42  4805.5  696.12
  4919.4  697.03  4935.7  696.31  4979.5  696.35  4993.9  689.35  4998.3  689.06
  4998.8  688.26  5003.9  688.26  5004.4  689.06    5007  692.37  5018.6  691.19
  5023.6  692.55  5029.3  690.79  5038.6  692.35  5045.6  695.81 5048.51695.8671
  5073.7  697.28  5111.5  700.08  5155.4  701.27  5243.2  705.53  5316.9  707.22
#Mann= 5 ,-1 , 0
  4514.9      .1       0  4805.5     .16       0  4998.3     .07       0
  5004.4     .16       0  5073.7      .1       0
Bank Sta=4776.87,5048.51
XS Rating Curve= 0 ,0
Exp/Cntr=0.3,0.1

Type RM Length L Ch R = 1 ,870     ,35,35,35
BEGIN DESCRIPTION:
Mapping XS 7159286f
END DESCRIPTION:
XS GIS Cut Line= 4
      1986625.84     13619374.48      1986580.97     13619164.52
        1986565.     13618651.04      1986424.69     13618479.55
#Sta/Elev= 30
  4425.9   703.5  4435.6  702.77  4445.8  703.34  4466.3  701.84  4496.8  700.79
  4501.9  701.11  4527.6  699.33  4537.9  699.39  4558.3  697.52  4568.5  698.63
  4637.8  696.16 4664.01695.8134  4680.1  695.25  4734.3   695.7  4820.2  694.71
  4880.2  695.21  4900.2  695.88  4910.3  695.72  4944.6  693.75  4989.4  690.39
  4991.4  687.09  4991.9  686.29    4997  686.29  4997.5  687.09  5040.3  689.42
  5060.3   692.5 5108.43695.8134  5173.3  698.39  5329.8  703.27  5375.9  703.77
#Mann= 5 ,-1 , 0
  4425.9      .1       0  4734.3     .16       0  4944.6      .1       0
  4991.4     .07       0  4997.5      .1       0
Bank Sta=4664.01,5108.43
XS Rating Curve= 0 ,0
Exp/Cntr=0.3,0.1

Type RM Length L Ch R = 1 ,835     ,30,30,30
BEGIN DESCRIPTION:
Mapping XS 55cf80c0
END DESCRIPTION:
XS GIS Cut Line= 4
        1986630.     13619392.71      1986613.28      13619150.8
      1986598.86     13618617.19      1986450.42     13618445.31
#Sta/Elev= 30
  4407.1  703.48  4424.9   703.5  4434.9  702.77  4444.9  703.34    4475  701.26
  4545.1  698.57  4551.1  697.76 4670.86695.3824  4685.4  694.99  4705.4  695.63
  4744.9  694.99  4816.8  694.34  4855.5  694.88  4895.5  697.78  4915.5  698.36
  4975.5  698.49  5035.5  696.53  5045.5   695.9  5065.5  692.96  5072.5  692.51
    5073  691.71  5078.1  691.71  5078.6  692.51 5112.37695.3821  5125.6  696.53
  5215.8  698.79  5307.9  701.77  5322.2  702.66  5358.1  702.68  5410.5   703.6
#Mann= 5 ,-1 , 0
  4407.1      .1       0  4744.9     .16       0  4816.8      .1       0
  5072.5     .07       0  5078.6      .1       0
Bank Sta=4670.86,5112.37
XS Rating Curve= 0 ,0
Exp/Cntr=0.3,0.1

Type RM Length L Ch R = 1 ,805     ,358,358,358
BEGIN DESCRIPTION:
UNT 051 in HW 2.0
END DESCRIPTION:
XS GIS Cut Line= 5
      1986632.61     13619453.87       1986638.2     13619142.08
      1986635.32     13618932.99      1986632.71     13618594.45
      1986463.47     13618404.37
#Sta/Elev= 30
  4342.3  703.85  4381.2  703.35  4401.2  703.48  4451.2  702.36  4481.2  700.57
  4531.2  698.74  4561.2  696.77  4591.2  696.97  4611.2   696.2  4654.1   695.6
  4671.2  694.94  4711.2  694.98 4792.72693.9017  4901.2  694.14  4971.2  693.52
  5001.2  692.68  5031.2  693.96  5041.2  693.56  5071.2  691.02  5078.2  690.99
  5078.7  690.19  5083.8  690.19  5084.3  690.99  5098.4693.9016  5111.2  696.16
  5203.8  698.34  5227.8  699.22  5256.2  699.66    5313  701.47  5456.3  703.95
#Mann= 3 ,-1 , 0
  4342.3      .1       0  5078.2     .07       0  5084.3      .1       0
Bank Sta=4792.72,5098.4
XS Rating Curve= 0 ,0
Exp/Cntr=0.3,0.1

Type RM Length L Ch R = 1 ,447     ,0,0,0
BEGIN DESCRIPTION:
UNT 051 in HW 1.0
END DESCRIPTION:
XS GIS Cut Line= 4
      1986632.62     13619853.15      1986855.56     13619118.75
      1986855.56     13618736.81       1986491.2     13618361.79
#Sta/Elev= 30
  4088.3  705.21  4190.9  702.63    4409  699.88  4528.7  697.36  4632.6  696.57
  4698.3  697.25  4713.4  699.33  4736.5  700.21  4769.3  697.46    4797  693.84
  4840.3  693.51  4855.1  692.15  4939.5  692.16  4949.5  691.35 4965.84687.4117
  4979.5  685.98  4996.5  681.73    4997  680.93  5002.1  680.93  5002.6  681.73
  5009.5  683.27  5039.5  685.78  5069.5   685.6 5075.16687.4113  5092.1   691.7
  5209.9  691.25  5331.3  692.13  5465.6  698.29  5578.8  701.14  5760.6  703.92
#Mann= 6 ,-1 , 0
  4088.3     .16       0    4409      .1       0  4996.5     .07       0
  5002.6      .1       0  5092.1     .16       0  5209.9      .1       0
Bank Sta=4965.84,5075.16
XS Rating Curve= 0 ,0
Exp/Cntr=0.3,0.1
LCMann Table=0

Chan Stop Cuts=-1
Use User Specified Reach Order=0
Composite Channel Slope=5