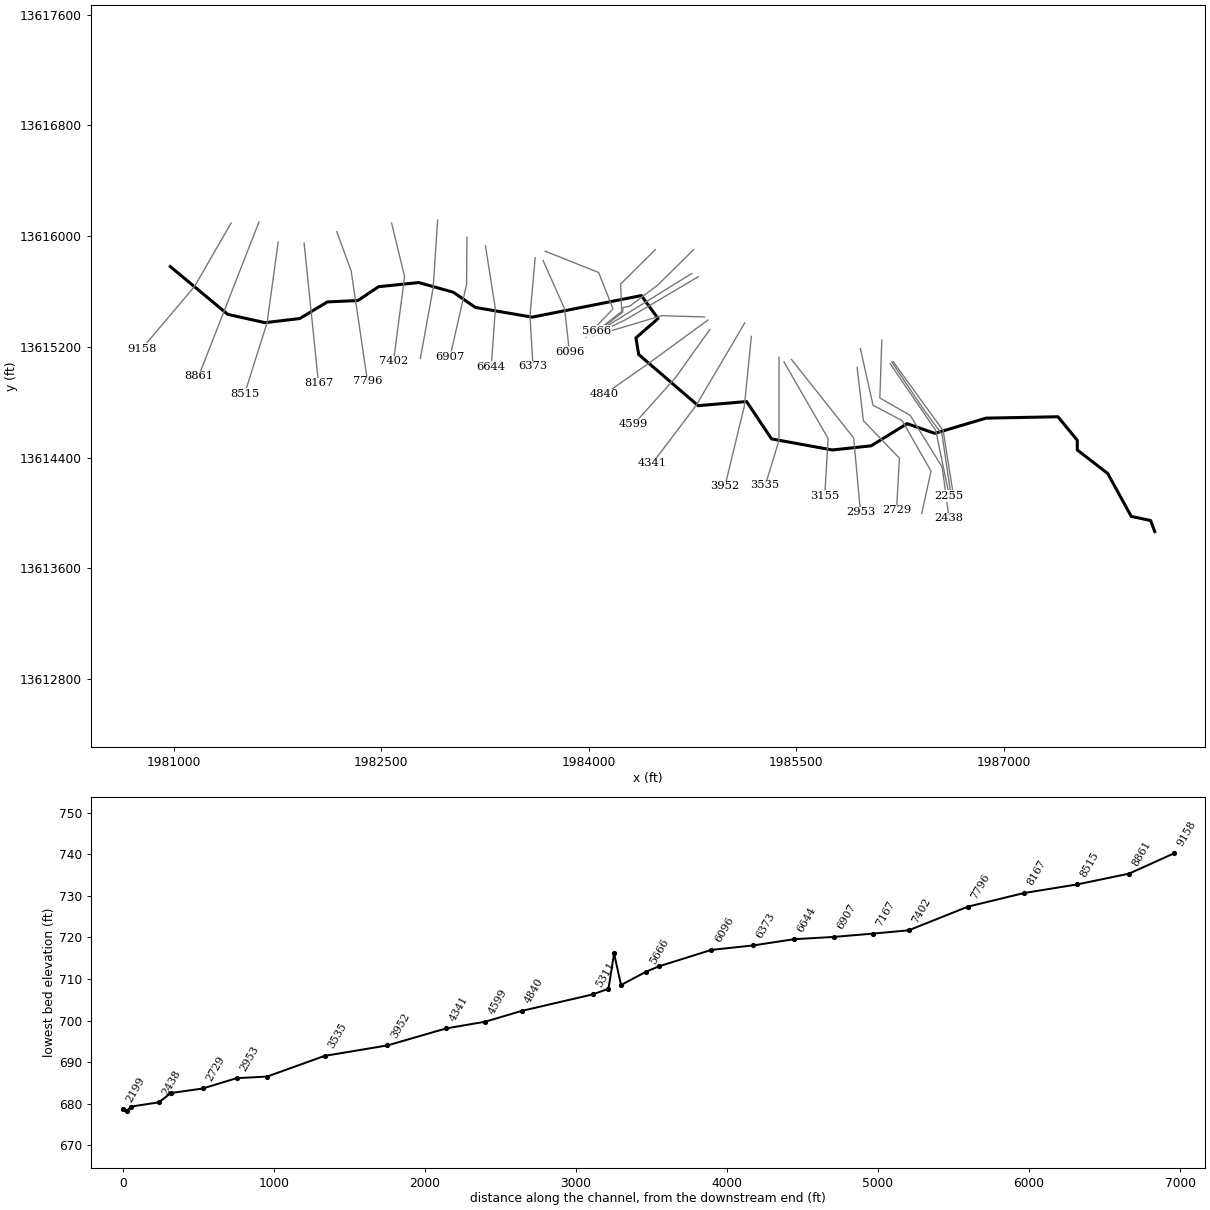
--- UNT 052 in HW.prj (project) ---

Proj Title=UNT 052 in HW Base Level Engineering
Current Plan=p01
Default Exp/Contr=0.3,0.1
English Units
Geom File=g01
Flow File=f01
Plan File=p01
Y Axis Title=Elevation
X Axis Title(PF)=Main Channel Distance
X Axis Title(XS)=Station
BEGIN DESCRIPTION:
UNT 052 in HW
END DESCRIPTION:
DSS Export Rating Curves= 0
DSS Export Rating Curve Sorted= 0
DSS Export Volume Flow Curves= 0
DXF OffsetX= 0
DXF OffsetY= 0
DXF ScaleX= 1
DXF ScaleY= 10

--- UNT 052 in HW.p01 (plan) ---

Plan Title=Multiple Run
Short Identifier=Multiple
Geom File=g01
Flow File=f01
Subcritical Flow
K Sum by GR= 0
Std Step Tol= 0.01
Critical Tol= 0.01
Num of Std Step Trials= 20
Max Error Tol= 0.3
Flow Tol Ratio= 0.001
Split Flow NTrial= 30
Split Flow Tol= 0.02
Split Flow Ratio= 0.02
Log Output Level= 0
Friction Slope Method= 1
Unsteady Friction Slope Method= 2
Unsteady Bridges Friction Slope Method= 1
Parabolic Critical Depth
Global Vel Dist=  1 , 1 , 1
Global Log Level= 0
CheckData=True
Encroach Param= -1, 0, 0, 0
BEGIN DESCRIPTION:
Multiple Run
END DESCRIPTION:

--- UNT 052 in HW.f01 (steady flow) ---

Flow Title=Multiple
Number of Profiles=7
Profile Names=10-year,25-year,50-year,1pct_min,100-year,1pct_plu,500-year
River Rch & RM= UNT 052 in HW,Reach-1,9158
     463     644     794     485     967    1930    1441
River Rch & RM= UNT 052 in HW,Reach-1,5666
     668     949    1186     733    1463    2918    2235
Boundary for River Rch & Prof#=UNT 052 in HW,Reach-1,1
Up Type=0
Dn Type=3
Dn Slope=0.005
Boundary for River Rch & Prof#=UNT 052 in HW,Reach-1,2
Up Type=0
Dn Type=3
Dn Slope=0.005
Boundary for River Rch & Prof#=UNT 052 in HW,Reach-1,3
Up Type=0
Dn Type=3
Dn Slope=0.005
Boundary for River Rch & Prof#=UNT 052 in HW,Reach-1,4
Up Type=0
Dn Type=3
Dn Slope=0.005
Boundary for River Rch & Prof#=UNT 052 in HW,Reach-1,5
Up Type=0
Dn Type=3
Dn Slope=0.005
Boundary for River Rch & Prof#=UNT 052 in HW,Reach-1,6
Up Type=0
Dn Type=3
Dn Slope=0.005
Boundary for River Rch & Prof#=UNT 052 in HW,Reach-1,7
Up Type=0
Dn Type=3
Dn Slope=0.005

--- UNT 052 in HW.g01 (geometry) ---

Geom Title=Existing Conditions
Program Version=5.05

River Reach=UNT 052 in HW   ,Reach-1
Reach XY= 30
       1980975.8     13615779.54       1981390.8     13615434.54
       1981660.8     13615374.54       1981910.8     13615404.54
       1982110.8     13615524.54       1982330.8     13615534.54
       1982480.8     13615634.54       1982770.8     13615664.54
       1983020.8     13615594.54       1983180.8     13615484.54
       1983590.8     13615414.54      1984379.98     13615570.42
       1984500.8     13615404.54       1984340.8     13615264.54
       1984360.8     13615144.54       1984790.8     13614774.54
       1985140.8     13614804.54       1985320.8     13614534.54
       1985760.8     13614454.54       1986040.8     13614484.54
       1986300.8     13614644.54       1986500.8     13614574.54
       1986870.8     13614684.54       1987390.8     13614694.54
       1987530.8     13614524.54       1987530.8     13614454.54
       1987750.8     13614284.54       1987920.8     13613974.54
       1988060.8     13613944.54       1988090.8     13613864.54

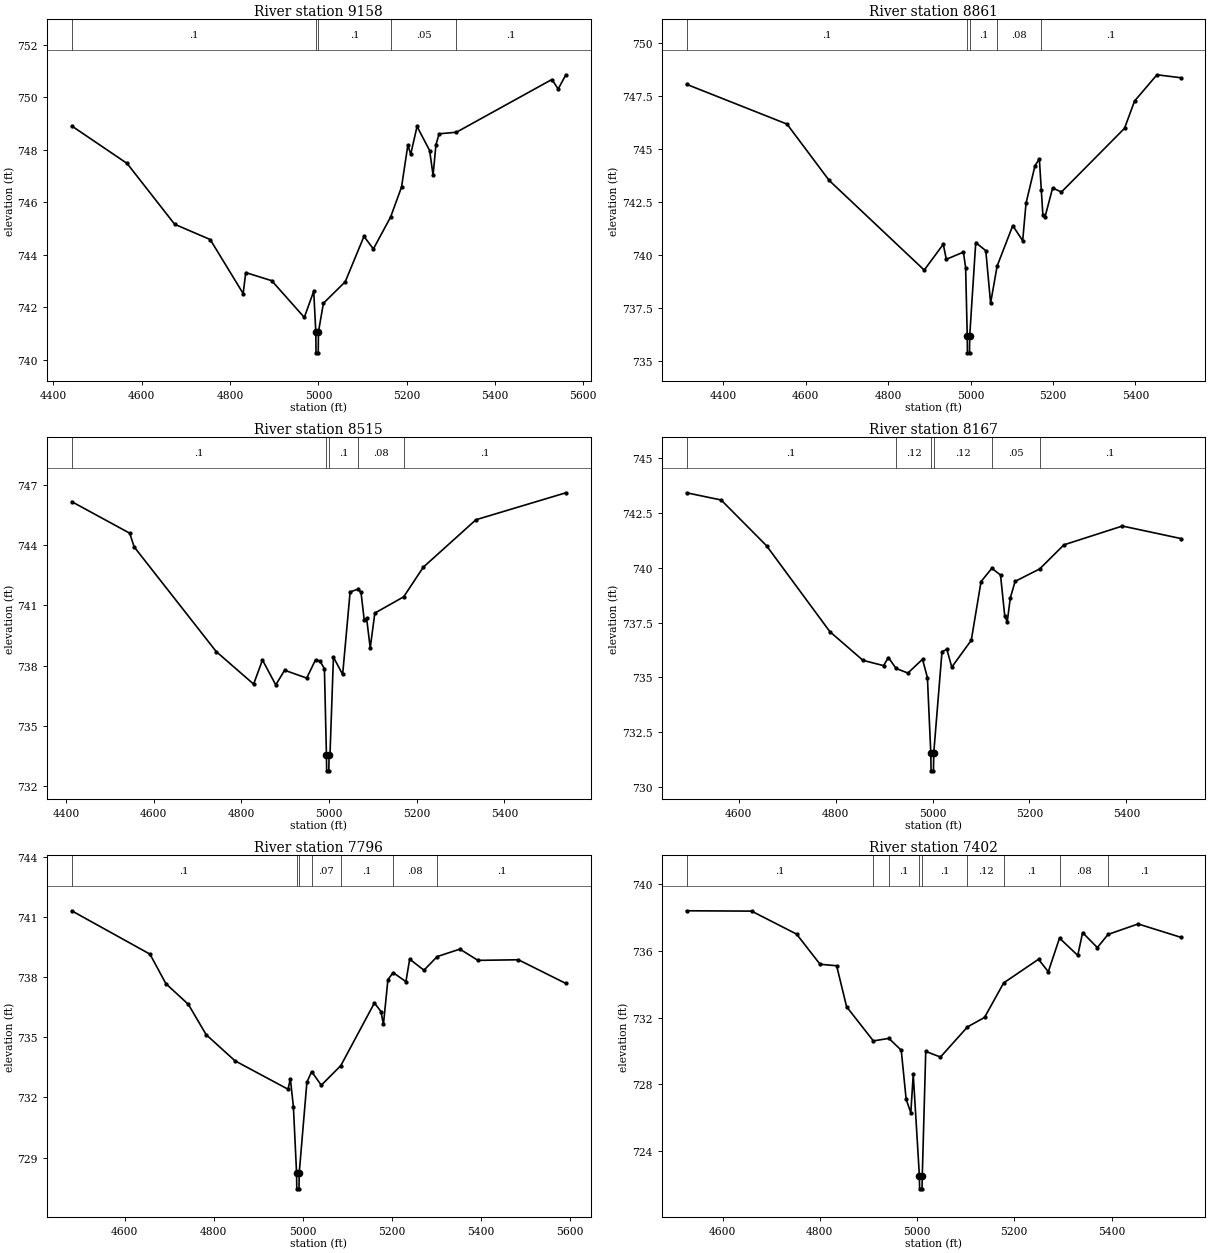
Type RM Length L Ch R = 1 ,9158    ,297,297,297
BEGIN DESCRIPTION:
UNT 052 in HW 19.0
END DESCRIPTION:
XS GIS Cut Line= 3
      1981414.74     13616094.99      1981150.85     13615636.66
      1980769.47     13615185.94
#Sta/Elev= 30
  4441.2  748.91  4566.7  747.48  4674.5  745.16  4754.9  744.58  4829.6  742.52
  4835.4  743.32  4894.3  743.01  4968.1  741.61  4989.4  742.61  4994.1  741.06
  4994.6  740.26  4999.6  740.26  5000.1  741.06  5011.4  742.15  5060.8  742.97
  5103.2   744.7  5124.5  744.22  5163.6  745.44  5188.3  746.58  5202.6  748.18
  5209.1  747.83  5223.4  748.89    5252  747.97  5259.7  747.03  5266.3   748.2
  5273.5  748.61  5312.6  748.67  5528.8  750.68  5543.1  750.32  5560.5  750.86
#Mann= 5 ,-1 , 0
  4441.2      .1       0  4994.1     .07       0  5000.1      .1       0
  5163.6     .05       0  5312.6      .1       0
Bank Sta=4994.1,5000.1
XS Rating Curve= 0 ,0
Exp/Cntr=0.3,0.1

Type RM Length L Ch R = 1 ,8861    ,346,346,346
BEGIN DESCRIPTION:
Mapping XS 9b84bd63
END DESCRIPTION:
XS GIS Cut Line= 2
      1981616.12     13616101.91      1981179.32     13614985.63
#Sta/Elev= 30
    4311  748.07  4554.7  746.19  4656.9  743.53  4887.6  739.29  4933.7  740.51
  4941.2   739.8  4982.6  740.14    4988  739.41  4991.9  736.18  4992.4  735.38
  4997.4  735.38  4997.9  736.18  5012.5  740.59  5036.9  740.21  5048.6  737.73
  5064.4  739.48  5102.3  741.39  5126.4  740.68  5134.5  742.45  5156.2  744.22
  5166.8  744.55  5171.5  743.09  5175.3  741.91  5180.7  741.81    5199  743.17
  5220.4  742.98  5373.4  745.99  5397.8  747.28  5452.1  748.52  5509.7  748.38
#Mann= 5 ,-1 , 0
    4311      .1       0  4991.9     .07       0  4997.9      .1       0
  5064.4     .08       0  5171.5      .1       0
Bank Sta=4991.9,4997.9
XS Rating Curve= 0 ,0
Exp/Cntr=0.3,0.1

Type RM Length L Ch R = 1 ,8515    ,348,348,348
BEGIN DESCRIPTION:
UNT 052 in HW 18.0
END DESCRIPTION:
XS GIS Cut Line= 3
      1981755.02     13615956.13        1981675.       13615375.
      1981512.14     13614859.43
#Sta/Elev= 30
  4412.9  746.15  4545.3  744.58  4555.4   743.9  4742.5   738.7  4827.9  737.08
  4848.1  738.28  4878.4  737.04  4898.6  737.77    4949  737.38  4969.2  738.29
  4979.3  738.22  4989.4  737.85    4994  733.57  4994.5  732.77  4999.5  732.77
    5000  733.57  5002.1  733.57    5010  738.42    5031  737.56    5048  741.66
  5065.9   741.8  5072.9  741.64  5080.3  740.25  5085.6  740.36  5093.9  738.88
  5104.4  740.61  5170.3  741.42  5214.9  742.89  5335.1  745.25  5540.2  746.59
#Mann= 5 ,-1 , 0
  4412.9      .1       0    4994     .07       0    5000      .1       0
  5065.9     .08       0  5170.3      .1       0
Bank Sta=4994,5000
XS Rating Curve= 0 ,0
Exp/Cntr=0.3,0.1

Type RM Length L Ch R = 1 ,8167    ,371,371,371
BEGIN DESCRIPTION:
Mapping XS 809cb4e2
END DESCRIPTION:
XS GIS Cut Line= 2
      1981942.52     13615949.18      1982046.68     13614935.32
#Sta/Elev= 30
  4492.7  743.43  4564.1   743.1  4657.7  741.01  4788.4  737.08  4856.6  735.77
    4899  735.53  4909.1   735.9  4924.9   735.4  4949.3  735.19  4979.4  735.82
  4989.5  734.98  4996.5  731.52    4997  730.72    5002  730.72  5002.5  731.52
  5019.6  736.17  5029.7  736.27  5039.7  735.46    5080  736.69  5100.1  739.37
  5122.4  739.98  5140.3  739.67  5149.1  737.78  5154.2  737.53  5160.4  738.62
  5170.4  739.38  5221.1  739.95    5271  741.05  5391.6  741.91  5511.9  741.34
#Mann= 6 ,-1 , 0
  4492.7      .1       0  4924.9     .12       0  4996.5     .07       0
  5002.5     .12       0  5122.4     .05       0  5221.1      .1       0
Bank Sta=4996.5,5002.5
XS Rating Curve= 0 ,0
Exp/Cntr=0.3,0.1

Type RM Length L Ch R = 1 ,7796    ,394,394,394
BEGIN DESCRIPTION:
UNT 052 in HW 17.0
END DESCRIPTION:
XS GIS Cut Line= 3
      1982178.64     13616032.47       1982282.8     13615747.77
      1982400.79     13614949.59
#Sta/Elev= 30
  4481.3   741.3  4657.1  739.14  4692.9  737.67  4743.3  736.64  4783.3  735.13
  4847.9  733.83  4967.3  732.41  4972.4  732.94  4979.3  731.54  4986.4  728.25
  4986.9  727.45  4991.9  727.45  4992.4  728.25  5009.6  732.76  5020.3  733.29
  5041.9  732.61  5085.9  733.59  5161.3  736.71    5176  736.28  5181.5  735.64
  5191.6  737.87  5203.3  738.22    5232  737.77  5240.5  738.89  5272.5  738.34
  5302.4  739.02  5353.3  739.39  5393.8  738.83  5484.7  738.86  5591.3  737.68
#Mann= 7 ,-1 , 0
  4481.3      .1       0  4986.4     .07       0  4992.4      .1       0
  5020.3     .07       0  5085.9      .1       0  5203.3     .08       0
  5302.4      .1       0
Bank Sta=4986.4,4992.4
XS Rating Curve= 0 ,0
Exp/Cntr=0.3,0.1

Type RM Length L Ch R = 1 ,7402    ,235,235,235
BEGIN DESCRIPTION:
Mapping XS d17b722e
END DESCRIPTION:
XS GIS Cut Line= 3
      1982574.47     13616094.98      1982668.79     13615707.96
      1982588.35     13615094.96
#Sta/Elev= 30
  4525.7  738.42  4659.5   738.4  4752.1  737.02  4800.4  735.21  4834.5  735.12
    4855  732.66    4910  730.61    4942  730.76  4967.4  730.05  4977.5   727.1
  4987.1   726.3  4992.1   728.6  5004.7  722.53  5005.2  721.73  5010.2  721.73
  5010.7  722.53  5017.8  729.98  5048.1  729.64  5103.7  731.45  5138.8  732.02
  5178.1  734.09  5249.8  735.51  5269.9  734.76    5293  736.78  5330.5  735.74
  5340.5  737.11  5370.8  736.21  5392.8     737  5454.6  737.63  5542.3  736.83
#Mann= 9 ,-1 , 0
  4525.7      .1       0    4910     .12       0    4942      .1       0
  5004.7     .07       0  5010.7      .1       0  5103.7     .12       0
  5178.1      .1       0    5293     .08       0  5392.8      .1       0
Bank Sta=5004.7,5010.7
XS Rating Curve= 0 ,0
Exp/Cntr=0.3,0.1

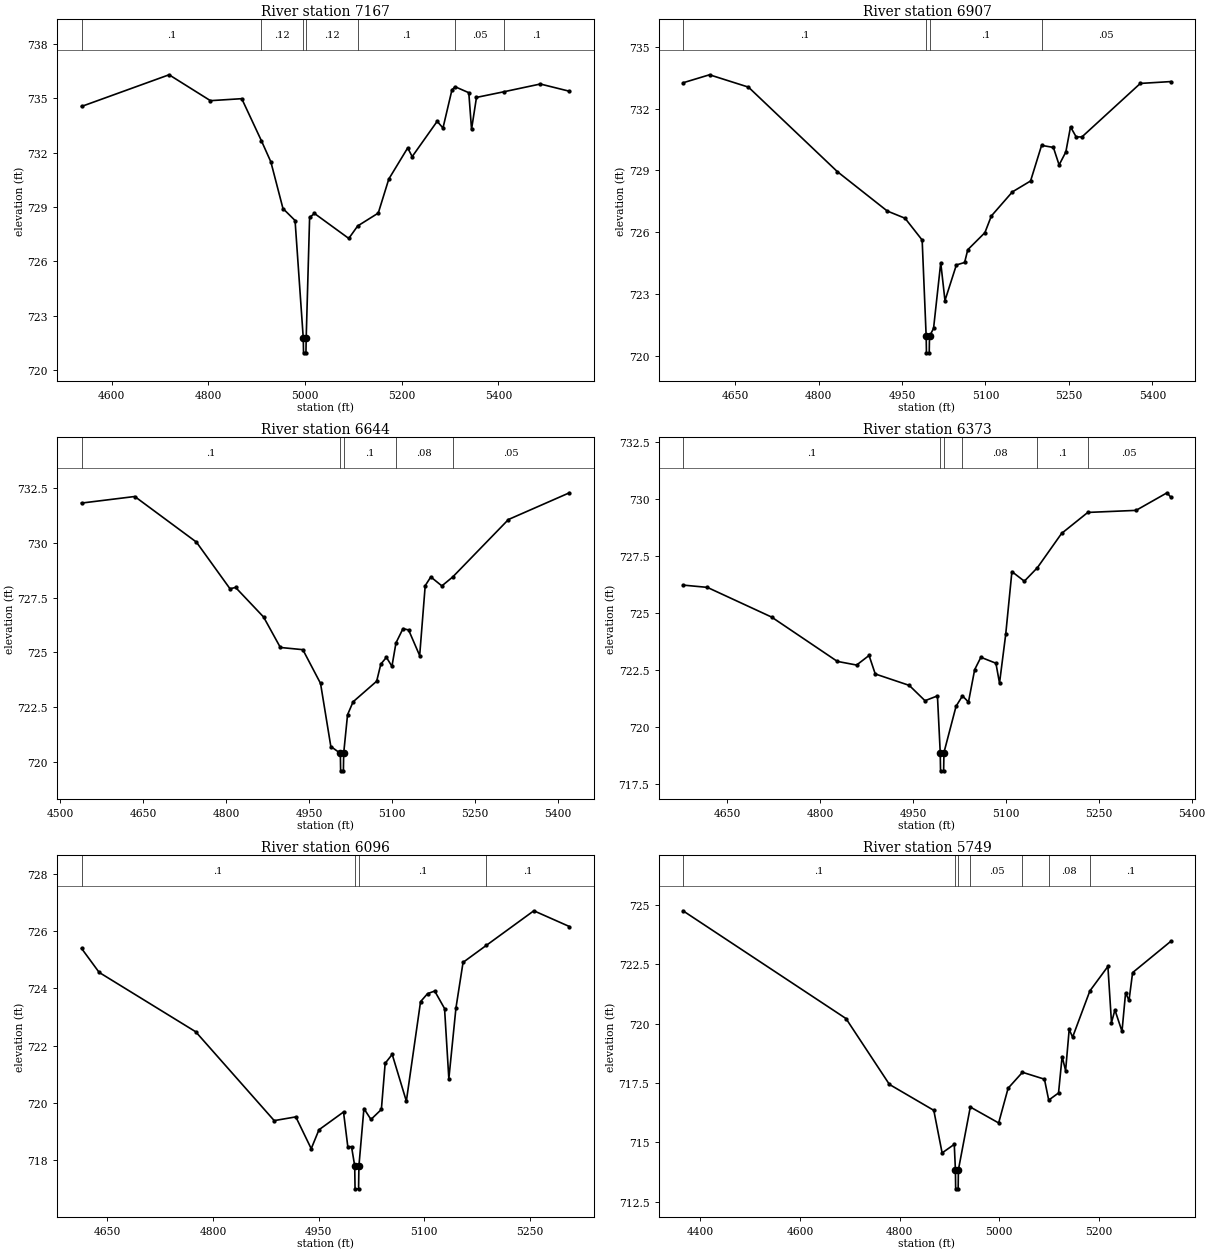
Type RM Length L Ch R = 1 ,7167    ,260,260,260
BEGIN DESCRIPTION:
UNT 052 in HW 16.0
END DESCRIPTION:
XS GIS Cut Line= 3
       1982907.8     13616115.81        1982875.       13615625.
      1982782.79     13615115.78
#Sta/Elev= 30
  4537.7  734.55  4718.9   736.3  4804.4  734.87  4869.2  734.98  4909.8  732.66
  4929.4  731.49  4954.5  728.91  4979.5  728.25  4996.5  721.74    4997  720.94
    5002  720.94  5002.5  721.74  5009.6  728.42  5019.6  728.64  5090.6  727.26
  5109.1  727.95  5151.6  728.66  5173.4  730.54  5212.5  732.26  5221.8  731.78
  5273.5  733.73  5285.5  733.36    5304  735.46  5310.5  735.64  5338.9  735.31
  5344.6  733.29  5354.8  735.05  5411.2  735.36  5486.9  735.79  5547.1  735.39
#Mann= 7 ,-1 , 0
  4537.7      .1       0  4909.8     .12       0  4996.5     .07       0
  5002.5     .12       0  5109.1      .1       0  5310.5     .05       0
  5411.2      .1       0
Bank Sta=4996.5,5002.5
XS Rating Curve= 0 ,0
Exp/Cntr=0.3,0.1

Type RM Length L Ch R = 1 ,6907    ,263,263,263
BEGIN DESCRIPTION:
Mapping XS 68cb8bb1
END DESCRIPTION:
XS GIS Cut Line= 3
      1983119.31     13615992.72      1983116.71     13615651.53
      1982997.13     13615129.04
#Sta/Elev= 30
  4556.2  733.26  4603.9  733.65  4673.9  733.05  4833.9  728.94  4923.5  727.03
  4955.4  726.68  4986.2  725.62  4993.4  720.94  4993.9  720.14  4998.9  720.14
  4999.4  720.94  5006.7  721.33  5019.6  724.52  5027.2  722.68  5047.7  724.41
  5062.5  724.53  5068.2  725.15    5099  725.98  5110.6  726.79  5148.4  727.96
  5181.1  728.49  5200.9  730.22  5222.1  730.12  5232.4  729.27  5244.5   729.9
  5252.9  731.12  5263.1  730.63  5273.4  730.63  5378.4  733.23  5433.4  733.32
#Mann= 4 ,-1 , 0
  4556.2      .1       0  4993.4     .07       0  4999.4      .1       0
  5200.9     .05       0
Bank Sta=4993.4,4999.4
XS Rating Curve= 0 ,0
Exp/Cntr=0.3,0.1

Type RM Length L Ch R = 1 ,6644    ,271,271,271
BEGIN DESCRIPTION:
UNT 052 in HW 15.0
END DESCRIPTION:
XS GIS Cut Line= 3
      1983253.29     13615930.02        1983325.       13615475.
      1983294.95     13615055.11
#Sta/Elev= 30
  4538.9  731.81  4635.1  732.11  4746.5  730.03  4807.2   727.9  4817.3  727.96
  4867.9  726.61  4898.2  725.22  4938.8  725.12  4970.8  723.58  4989.4   720.7
  5006.6  720.39  5007.1  719.59  5012.1  719.59  5012.6  720.39  5019.6  722.15
  5029.6  722.74  5072.2  723.68  5079.7  724.46  5089.8  724.77  5099.8  724.36
  5107.1  725.43  5119.8  726.08  5129.9  726.02  5149.9  724.85  5159.9  728.04
    5170  728.44    5190  728.03  5209.7  728.44  5310.3  731.06  5420.5  732.28
#Mann= 5 ,-1 , 0
  4538.9      .1       0  5006.6     .07       0  5012.6      .1       0
  5107.1     .08       0  5209.7     .05       0
Bank Sta=5006.6,5012.6
XS Rating Curve= 0 ,0
Exp/Cntr=0.3,0.1

Type RM Length L Ch R = 1 ,6373    ,277,277,277
BEGIN DESCRIPTION:
UNT 052 in HW 14.0
END DESCRIPTION:
XS GIS Cut Line= 3
      1983612.66     13615844.15        1983575.       13615425.
      1983596.97      13615058.8
#Sta/Elev= 30
  4578.7  726.22    4618  726.12  4721.8  724.82  4827.9  722.88    4859  722.72
  4879.1  723.14  4889.1  722.33    4944  721.83  4969.4  721.16  4989.5  721.37
    4994  718.89  4994.5  718.09  4999.5  718.09    5000  718.89  5019.6  720.92
  5029.9  721.37  5039.6   721.1  5049.6  722.52  5059.6  723.06  5083.9   722.8
  5089.7  721.93  5099.7  724.06  5109.7  726.81  5129.8  726.39  5150.8  726.98
  5189.9  728.48  5232.2   729.4  5310.1  729.49  5360.2  730.26  5366.4  730.06
#Mann= 6 ,-1 , 0
  4578.7      .1       0    4994     .07       0    5000      .1       0
  5029.9     .08       0  5150.8      .1       0  5232.2     .05       0
Bank Sta=4994,5000
XS Rating Curve= 0 ,0
Exp/Cntr=0.3,0.1

Type RM Length L Ch R = 1 ,6096    ,347,347,347
BEGIN DESCRIPTION:
UNT 052 in HW 13.0
END DESCRIPTION:
XS GIS Cut Line= 3
      1983669.95     13615823.29        1983825.       13615475.
      1983860.02     13615164.71
#Sta/Elev= 30
  4613.1   725.4  4638.2  724.56  4775.4  722.49    4887  719.39  4917.7  719.52
  4939.6  718.41  4950.6  719.07  4985.5  719.69  4991.6  718.48  4996.9  718.48
  5001.4  717.81  5001.9  717.01  5006.9  717.01  5007.4  717.81  5014.5  719.81
  5024.5  719.43  5039.3  719.78  5044.7  721.39  5054.7   721.7  5074.8  720.07
    5095  723.54    5105  723.82  5115.1  723.91  5129.1   723.3  5135.2  720.85
  5145.3  723.32  5155.4  724.91  5188.3   725.5    5256  726.71  5306.6  726.16
#Mann= 4 ,-1 , 0
  4613.1      .1       0  5001.4     .07       0  5007.4      .1       0
  5188.3      .1       0
Bank Sta=5001.4,5007.4
XS Rating Curve= 0 ,0
Exp/Cntr=0.3,0.1

Type RM Length L Ch R = 1 ,5749    ,83,83,83
BEGIN DESCRIPTION:
UNT 052 in HW 12.0
END DESCRIPTION:
XS GIS Cut Line= 4
      1983685.58       13615891.      1984070.99     13615737.36
      1984175.16     13615474.34      1983979.92     13615271.28
#Sta/Elev= 30
  4365.1  724.74  4692.3  720.21  4779.5  717.44  4868.6  716.35  4885.3  714.56
  4909.7  714.92    4912  713.85  4912.5  713.05  4917.5  713.05    4918  713.85
  4941.9  716.49  4998.8  715.82  5017.8  717.28  5046.6  717.95  5090.7  717.66
  5099.3  716.78    5119  717.08  5126.2  718.61  5133.2  718.02  5140.4  719.75
  5147.3  719.43  5181.9  721.37  5218.1   722.4  5225.3  720.04  5232.2  720.57
  5246.4  719.67  5253.6  721.29  5260.5  720.97  5267.7  722.14  5344.6  723.46
#Mann= 7 ,-1 , 0
  4365.1      .1       0    4912     .04       0    4918      .1       0
  4941.9     .05       0  5046.6      .1       0  5099.3     .08       0
  5181.9      .1       0
Bank Sta=4912,4918
XS Rating Curve= 0 ,0
Exp/Cntr=0.3,0.1

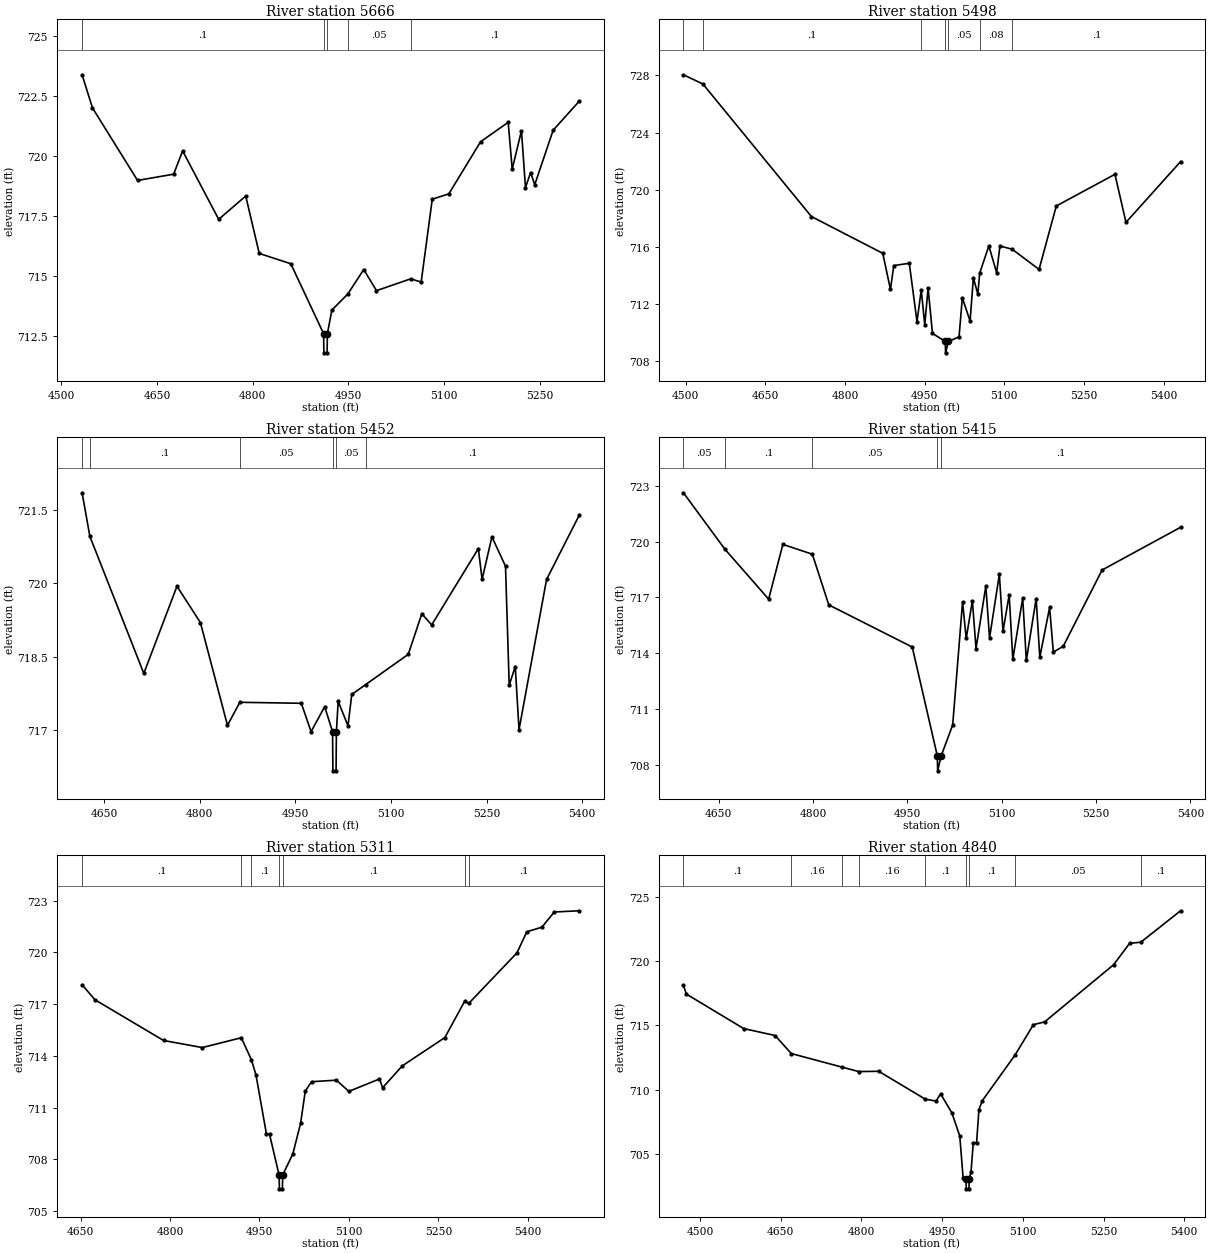
Type RM Length L Ch R = 1 ,5666    ,168,168,168
BEGIN DESCRIPTION:
Mapping XS 775b1a5a
END DESCRIPTION:
XS GIS Cut Line= 4
       1984480.8      13615902.2      1984230.46     13615654.85
      1984237.73     13615455.14      1984058.42     13615314.25
#Sta/Elev= 30
  4532.3  723.38  4548.6     722  4619.3  718.98  4675.9  719.24    4690  720.21
  4746.6  717.36    4789  718.33  4810.2  715.94  4859.7  715.51  4911.1   712.6
  4911.6   711.8  4916.6   711.8  4917.1   712.6  4924.1  713.58  4949.1  714.25
  4974.1  715.27  4994.1  714.39  5047.6  714.88  5064.2  714.75  5081.6   718.2
  5107.6  718.42  5157.3  720.59  5200.7   721.4    5207  719.45  5221.5  721.05
  5227.8  718.68  5235.9  719.31  5242.3   718.8  5271.2  721.07  5312.1  722.28
#Mann= 5 ,-1 , 0
  4532.3      .1       0  4911.1     .04       0  4917.1      .1       0
  4949.1     .05       0  5047.6      .1       0
Bank Sta=4911.1,4917.1
XS Rating Curve= 0 ,0
Exp/Cntr=0.3,0.1

Type RM Length L Ch R = 1 ,5498    ,46,46,46
BEGIN DESCRIPTION:
Mapping XS b91332e5
END DESCRIPTION:
XS GIS Cut Line= 6
      1984758.14      13615902.6      1984497.71     13615645.63
      1984294.58     13615492.86      1984247.71     13615484.18
      1984244.24     13615449.45      1984058.93     13615307.05
#Sta/Elev= 30
  4495.6  728.05  4532.4   727.4  4736.6  718.11    4871  715.53  4885.5     713
  4891.8  714.67    4921  714.83  4935.5  710.74  4943.5  712.96  4950.1  710.53
  4956.4  713.08  4964.7  709.91  4988.8  709.35  4989.3  708.55  4994.8  709.35
  5014.7  709.67  5020.9  712.41  5035.5  710.78  5041.7  713.82  5050.1  712.66
  5053.6  714.14  5070.9  716.05  5085.5  714.16  5091.7  716.04  5114.6  715.82
  5165.4   714.4  5197.9  718.85  5308.3  721.07  5329.1   717.7  5431.9  721.96
#Mann= 7 ,-1 , 0
  4495.6     .05       0  4532.4      .1       0  4943.5     .05       0
  4988.8     .04       0  4994.8     .05       0  5053.6     .08       0
  5114.6      .1       0
Bank Sta=4988.8,4994.8
XS Rating Curve= 0 ,0
Exp/Cntr=0.3,0.1

Type RM Length L Ch R = 1 ,5452    ,37,37,37
BEGIN DESCRIPTION:
Mapping XS 50f70d02
END DESCRIPTION:
XS GIS Cut Line= 2
      1984744.21     13615729.82      1984081.51      13615319.2
#Sta/Elev= 30
  4615.6  721.85  4627.8  720.96  4712.4  718.16  4764.4  719.94  4801.1   719.2
  4843.6   717.1    4863  717.57  4959.4  717.55  4974.7  716.97    4996  717.48
  5008.4  716.97  5008.9  716.17  5013.9  716.17  5014.4  716.97  5017.2  717.59
  5032.6  717.09  5038.5  717.73  5060.1  717.93  5127.1  718.55  5148.4  719.38
  5163.8  719.15    5237  720.71  5242.9  720.08  5258.3  720.95  5279.6  720.35
  5285.4  717.92  5294.9   718.3  5300.8  717.01    5344  720.08  5395.2  721.39
#Mann= 6 ,-1 , 0
  4615.6     .05       0  4627.8      .1       0    4863     .05       0
  5008.4     .04       0  5014.4     .05       0  5060.1      .1       0
Bank Sta=5008.4,5014.4
XS Rating Curve= 0 ,0
Exp/Cntr=0.3,0.1

Type RM Length L Ch R = 1 ,5415    ,104,104,104
BEGIN DESCRIPTION:
Mapping XS 6f4bf6ea
END DESCRIPTION:
XS GIS Cut Line= 3
      1984791.08     13615706.38      1984262.47      13615393.9
      1984102.74     13615319.19
#Sta/Elev= 30
  4593.9  722.64  4659.6  719.61  4729.4  716.91    4752  719.86  4798.9  719.33
    4825   716.6  4957.7  714.33  4997.6  708.46  4998.1  707.66  5003.6  708.46
    5022  710.13  5037.7  716.76  5043.5  714.79  5053.3  716.82  5059.1  714.25
  5074.7  717.61  5080.6  714.82  5096.2  718.24    5102  715.18  5111.8  717.14
  5117.6  713.67  5133.3  716.97  5139.1  713.61  5154.7  716.94  5160.5  713.78
  5176.1  716.46    5182  714.06  5197.6  714.36  5259.6  718.48  5384.3  720.78
#Mann= 5 ,-1 , 0
  4593.9     .05       0  4659.6      .1       0  4798.9     .05       0
  4997.6     .04       0  5003.6      .1       0
Bank Sta=4997.6,5003.6
XS Rating Curve= 0 ,0
Exp/Cntr=0.3,0.1

Type RM Length L Ch R = 1 ,5311    ,471,471,471
BEGIN DESCRIPTION:
UNT 052 in HW 11.0
END DESCRIPTION:
XS GIS Cut Line= 3
      1984836.57     13615416.09        1984525.       13615425.
      1984025.01       13615275.
#Sta/Elev= 30
  4652.6  718.12  4674.2  717.25  4789.3  714.89  4854.2  714.48  4919.6  715.05
  4936.6  713.77  4944.3  712.88  4961.8  709.46  4966.9  709.46    4983  707.09
  4983.5  706.29  4988.5  706.29    4989  707.09  5006.1  708.32  5019.1   710.1
  5026.9  711.96  5037.4   712.5  5079.1  712.59    5100  711.94  5151.3  712.66
  5156.6  712.15  5189.6  713.42    5261  715.06  5294.1  717.16    5301  717.04
  5381.9  719.97  5398.4  721.19  5423.7  721.46  5444.5  722.34  5486.3  722.41
#Mann= 7 ,-1 , 0
  4652.6      .1       0  4919.6     .16       0  4936.6      .1       0
    4983     .07       0    4989      .1       0  5294.1     .05       0
    5301      .1       0
Bank Sta=4983,4989
XS Rating Curve= 0 ,0
Exp/Cntr=0.3,0.1

Type RM Length L Ch R = 1 ,4840    ,241,241,241
BEGIN DESCRIPTION:
UNT 052 in HW 10.0
END DESCRIPTION:
XS GIS Cut Line= 3
       1984862.6     13615394.41        1984425.       13615075.
      1984111.72      13614856.2
#Sta/Elev= 30
  4469.2  718.12  4474.6  717.44  4581.2  714.76  4639.6  714.22  4669.6  712.82
  4763.4  711.77    4795  711.42  4832.2  711.44  4918.9  709.27  4938.8  709.13
  4947.2  709.69  4968.1  708.21  4982.8  706.41    4989  703.16  4994.4  703.11
  4994.9  702.31  4999.9  702.31  5000.4  703.11  5003.6   703.6  5007.9  705.89
    5014  705.89  5018.4  708.46  5024.5  709.15  5085.6  712.71  5119.6  715.06
  5140.5  715.28  5268.7  719.72  5298.4  721.38  5319.3  721.47  5393.1  723.91
#Mann= 9 ,-1 , 0
  4469.2      .1       0  4669.6     .16       0  4763.4      .1       0
    4795     .16       0  4918.9      .1       0  4994.4     .07       0
  5000.4      .1       0  5085.6     .05       0  5319.3      .1       0
Bank Sta=4994.4,5000.4
XS Rating Curve= 0 ,0
Exp/Cntr=0.3,0.1

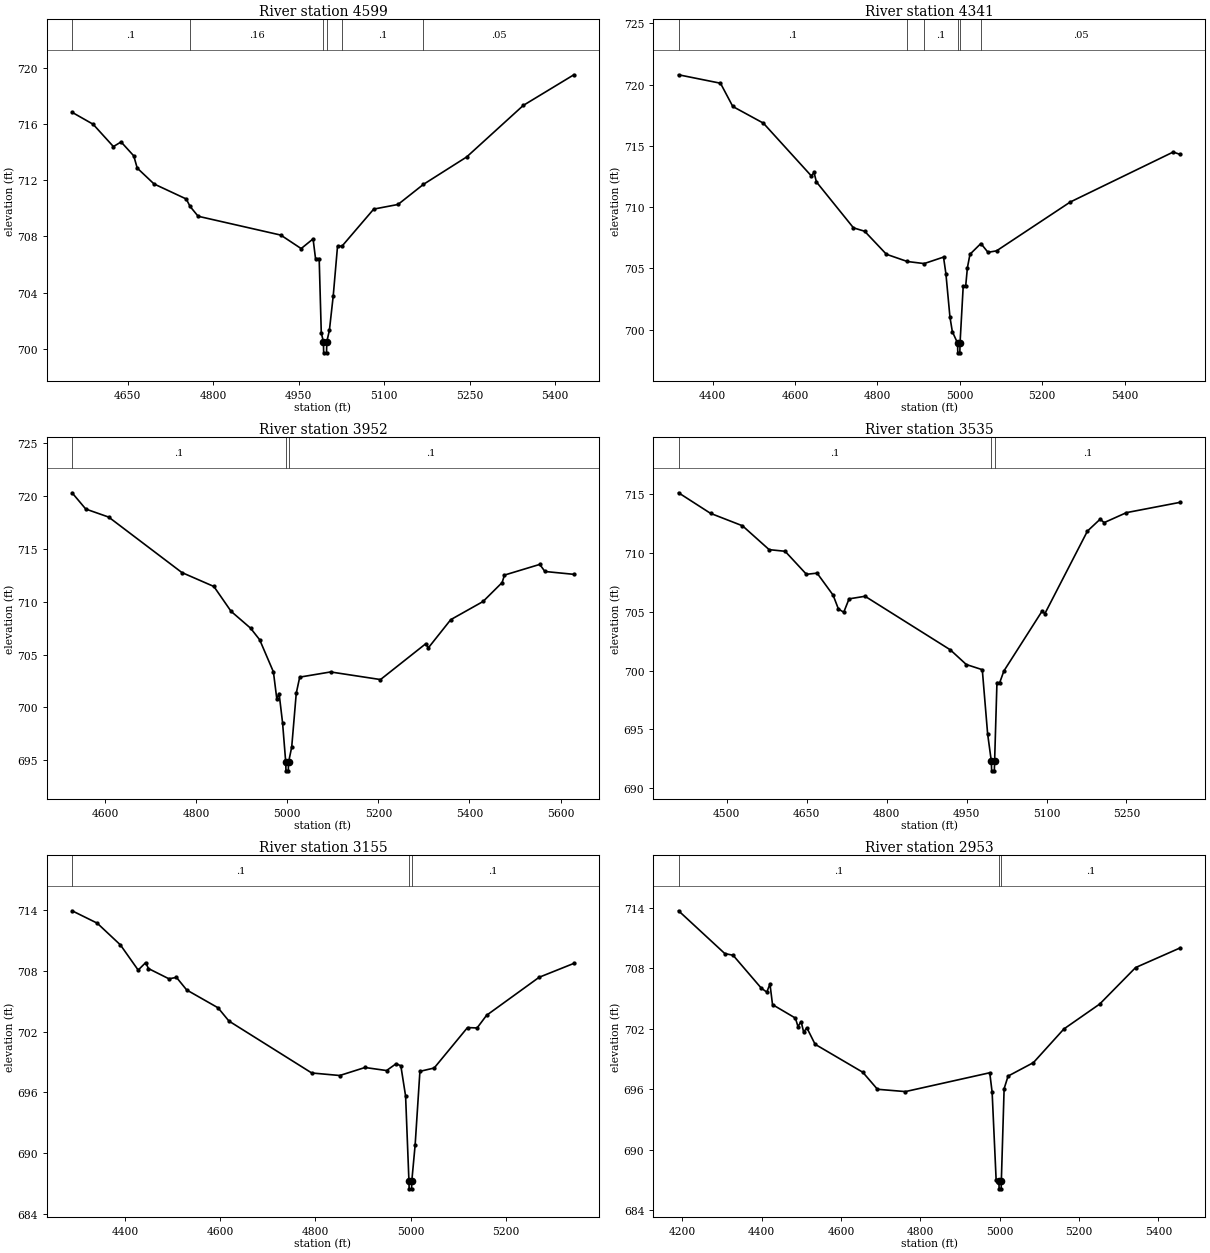
Type RM Length L Ch R = 1 ,4599    ,258,258,258
BEGIN DESCRIPTION:
UNT 052 in HW 9.0
END DESCRIPTION:
XS GIS Cut Line= 3
      1984875.01     13615325.01        1984625.       13614975.
      1984324.75     13614639.59
#Sta/Elev= 30
  4552.4  716.83  4589.3  715.98  4624.9  714.39  4638.4  714.72  4660.6  713.73
  4666.7  712.86  4696.2  711.73  4752.7  710.66  4759.4  710.13  4773.6  709.43
  4918.6  708.09  4954.3  707.13  4975.2  707.82  4979.5  706.42  4985.9  706.42
  4989.6  701.13  4993.3  700.51  4993.8  699.71  4998.8  699.71  4999.3  700.51
  5003.8   701.3  5010.6  703.78  5018.1   707.3  5026.1  707.31  5081.6  709.94
  5124.2  710.27  5168.8   711.7  5244.6  713.65    5344  717.32  5432.7   719.5
#Mann= 6 ,-1 , 0
  4552.4      .1       0  4759.4     .16       0  4993.3     .07       0
  4999.3     .16       0  5026.1      .1       0  5168.8     .05       0
Bank Sta=4993.3,4999.3
XS Rating Curve= 0 ,0
Exp/Cntr=0.3,0.1

Type RM Length L Ch R = 1 ,4341    ,389,389,389
BEGIN DESCRIPTION:
UNT 052 in HW 8.0
END DESCRIPTION:
XS GIS Cut Line= 3
      1985127.33     13615372.68        1984775.       13614775.
      1984458.93     13614357.06
#Sta/Elev= 30
  4317.4  720.81  4419.2  720.12  4449.1  718.22  4523.3  716.86  4639.7  712.55
  4646.2  712.83    4652  712.06  4741.9  708.31  4769.1  708.03  4821.9  706.15
  4872.6  705.56  4913.5  705.39  4960.5  705.92  4966.3  704.56  4976.1  701.02
  4981.9  699.83  4994.6   698.9  4995.1   698.1  5000.1   698.1  5000.6   698.9
  5008.3  703.56  5014.3  703.56  5018.5  705.06  5024.7  706.15  5051.2  707.03
  5068.4  706.31  5089.2  706.43  5268.2  710.42  5517.9   714.5  5535.2   714.3
#Mann= 6 ,-1 , 0
  4317.4      .1       0  4872.6     .16       0  4913.5      .1       0
  4994.6     .07       0  5000.6      .1       0  5051.2     .05       0
Bank Sta=4994.6,5000.6
XS Rating Curve= 0 ,0
Exp/Cntr=0.3,0.1

Type RM Length L Ch R = 1 ,3952    ,417,417,417
BEGIN DESCRIPTION:
UNT 052 in HW 7.0
END DESCRIPTION:
XS GIS Cut Line= 3
        1985175.     13615274.99        1985125.       13614775.
      1984984.11     13614192.17
#Sta/Elev= 30
  4527.2  720.32  4557.3  718.78  4607.6  718.02  4768.4  712.77  4838.7  711.45
  4876.4   709.1  4919.1  707.51  4939.2  706.41  4969.4  703.37  4976.9   700.8
  4981.9  701.32  4989.5  698.56  4996.5   694.8    4997     694  5002.1     694
  5002.6   694.8  5009.6  696.25  5019.6  701.35  5027.2  702.87    5095  703.36
  5204.6  702.64  5304.3  706.04  5309.5  705.63  5358.9  708.31  5429.9  710.03
  5471.7  711.82  5476.9  712.53  5554.4  713.54  5565.7  712.87  5629.3   712.6
#Mann= 3 ,-1 , 0
  4527.2      .1       0  4996.5     .07       0  5002.6      .1       0
Bank Sta=4996.5,5002.6
XS Rating Curve= 0 ,0
Exp/Cntr=0.3,0.1

Type RM Length L Ch R = 1 ,3535    ,380,380,380
BEGIN DESCRIPTION:
UNT 052 in HW 6.0
END DESCRIPTION:
XS GIS Cut Line= 3
        1985375.     13615125.04        1985375.       13614525.
      1985275.45     13614198.27
#Sta/Elev= 30
  4409.5  715.14  4469.5  713.39  4529.5  712.33  4579.5   710.3  4609.5  710.16
  4649.5   708.2  4669.5   708.3  4699.5  706.43  4709.5  705.25  4719.5  704.97
  4729.5  706.11  4759.5  706.33  4919.5  701.77  4949.5  700.52  4979.5  700.08
  4989.5  694.62  4996.5  692.27    4997  691.47  5002.1  691.47  5002.6  692.27
    5007  698.98  5012.2  698.98    5020  699.97  5091.6  705.06  5096.9  704.85
  5176.8  711.88  5200.6  712.89  5208.2   712.6    5250  713.45  5351.1  714.33
#Mann= 3 ,-1 , 0
  4409.5      .1       0  4996.5     .07       0  5002.6      .1       0
Bank Sta=4996.5,5002.6
XS Rating Curve= 0 ,0
Exp/Cntr=0.3,0.1

Type RM Length L Ch R = 1 ,3155    ,202,202,202
BEGIN DESCRIPTION:
UNT 052 in HW 5.0
END DESCRIPTION:
XS GIS Cut Line= 3
      1985410.81     13615090.85       1985729.8      13614537.5
      1985705.45     13614121.82
#Sta/Elev= 30
  4288.2  713.92    4341   712.7  4389.9  710.55  4427.2  708.07    4443  708.81
  4448.8  708.22  4491.9  707.21  4507.7  707.35  4529.2  706.11  4595.1  704.35
  4618.1  703.04  4792.1  697.92    4851  697.67  4904.1  698.46  4949.5  698.16
  4969.5  698.83  4979.5  698.63  4989.5  695.64  4996.5  687.29    4997  686.49
  5002.1  686.49  5002.6  687.29  5009.6  690.84  5019.6  698.08  5049.6  698.41
  5119.7   702.4  5139.8  702.36  5159.8  703.61  5270.3  707.36  5343.3  708.73
#Mann= 3 ,-1 , 0
  4288.2      .1       0  4996.5     .07       0  5002.6      .1       0
Bank Sta=4996.5,5002.6
XS Rating Curve= 0 ,0
Exp/Cntr=0.3,0.1

Type RM Length L Ch R = 1 ,2953    ,224,224,224
BEGIN DESCRIPTION:
Mapping XS 0e6dbbce
END DESCRIPTION:
XS GIS Cut Line= 3
      1985465.03     13615108.27      1985914.53     13614541.87
      1985963.86     13614002.81
#Sta/Elev= 30
  4190.8  713.73  4307.4  709.48  4328.3  709.31  4399.2  706.05  4413.2  705.65
  4421.2  706.46  4427.6  704.41  4485.3  703.07  4491.7  702.23  4499.7  702.72
  4506.1  701.67  4514.1  702.11  4534.9  700.47  4655.1  697.69    4692     696
  4762.5  695.77    4975  697.64    4981   695.7  4991.1  686.98  4998.1  686.91
  4998.6  686.11  5003.7  686.11  5004.2  686.91  5011.2  696.06  5021.2  697.31
  5085.1  698.65  5161.8  701.99  5252.2  704.47  5342.5  708.09  5455.2  710.05
#Mann= 3 ,-1 , 0
  4190.8      .1       0  4998.1     .07       0  5004.2      .1       0
Bank Sta=4998.1,5004.2
XS Rating Curve= 0 ,0
Exp/Cntr=0.3,0.1

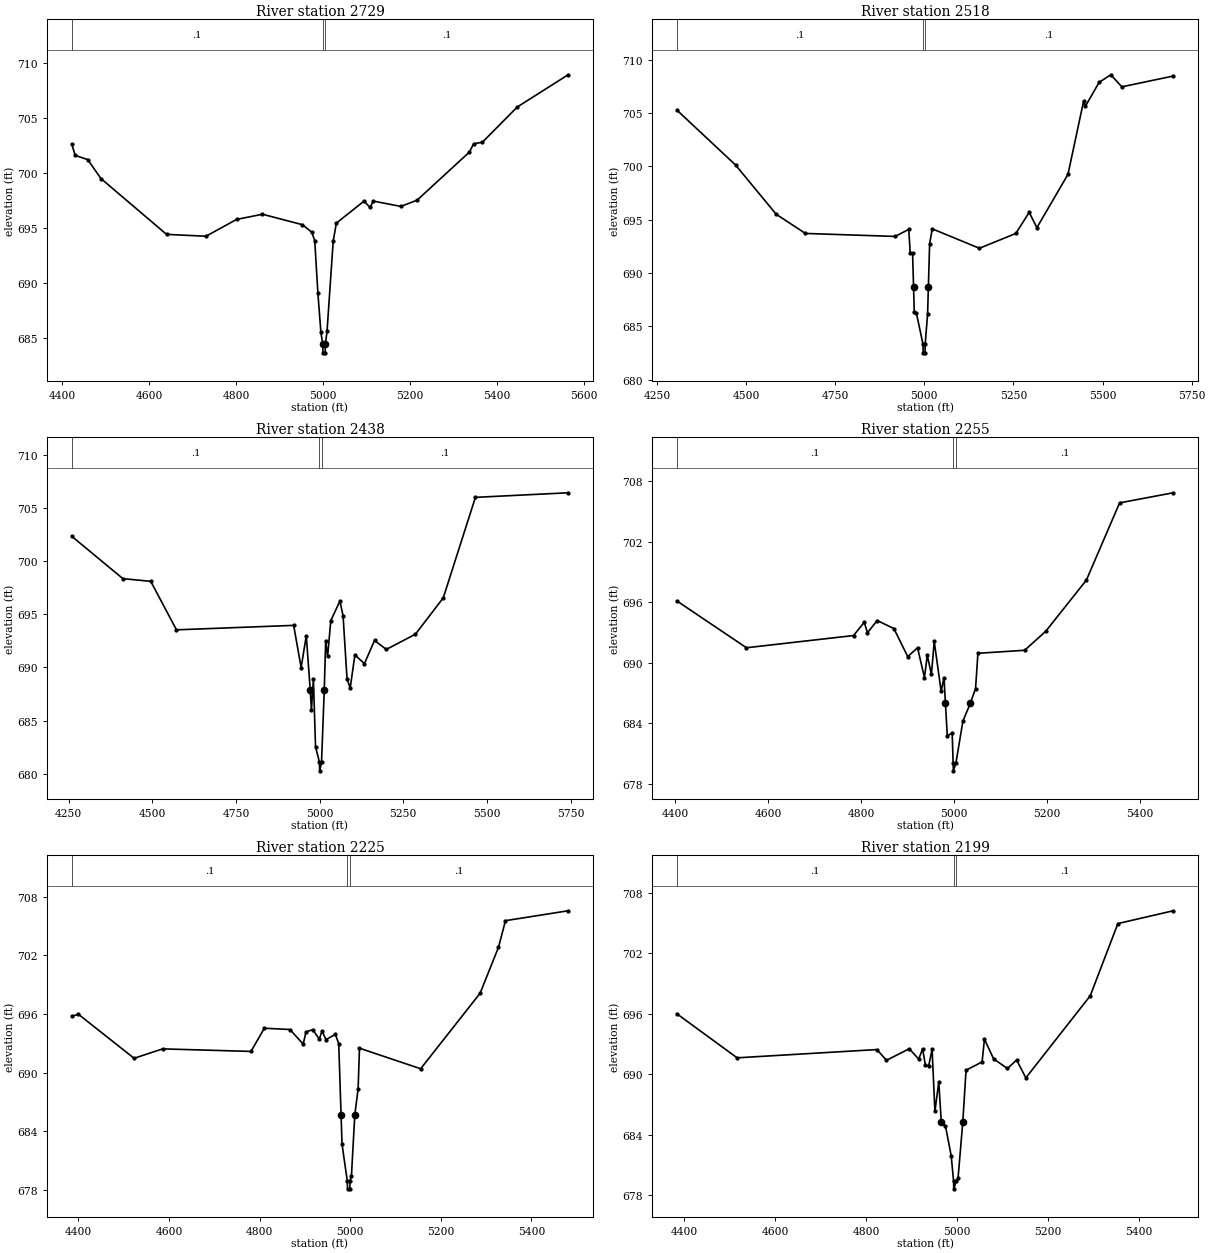
Type RM Length L Ch R = 1 ,2729    ,211,211,211
BEGIN DESCRIPTION:
Mapping XS b18bd8b8
END DESCRIPTION:
XS GIS Cut Line= 4
      1985939.55     13615051.43      1985984.69       13614666.
      1986245.11     13614395.17      1986224.36     13614018.32
#Sta/Elev= 30
  4422.7   702.6  4430.4  701.57  4459.4  701.19  4489.6  699.47  4640.6  694.39
  4731.2  694.22  4801.7  695.75  4861.2  696.22    4953  695.27  4974.4  694.59
  4981.3  693.83  4988.6  689.05  4995.5  685.48  4999.7  684.42  5000.2  683.62
  5005.3  683.62  5005.8  684.42  5009.6  685.57  5023.8  693.78    5031  695.41
  5094.5  697.41  5108.7  696.84  5115.9  697.42  5179.4  696.93  5216.7   697.5
  5336.9  701.87  5346.9  702.63  5366.9  702.77    5447  705.97  5563.9   708.9
#Mann= 3 ,-1 , 0
  4422.7      .1       0  4999.7     .07       0  5005.8      .1       0
Bank Sta=4999.7,5005.8
XS Rating Curve= 0 ,0
Exp/Cntr=0.3,0.1

Type RM Length L Ch R = 1 ,2518    ,80,80,80
BEGIN DESCRIPTION:
UNT 052 in HW 4.0
END DESCRIPTION:
XS GIS Cut Line= 5
      1985963.28     13615186.88      1986054.41     13614778.07
      1986265.35     13614666.09      1986473.68     13614301.51
      1986405.98     13613994.25
#Sta/Elev= 30
    4306  705.27  4470.7  700.12  4584.5  695.51  4666.5  693.71  4918.2  693.43
  4956.5  694.09  4960.6  691.84  4967.2  691.84 4969.93688.6451  4971.9  686.34
  4977.6  686.29  4996.4  683.32  4996.9  682.52    5002  682.52  5002.5  683.32
  5009.3  686.17 5011.44688.6442    5015  692.76  5022.5  694.14  5154.7  692.32
  5256.9  693.71  5294.3  695.69  5315.9  694.25  5403.1  699.25  5446.9  706.11
    5452  705.63  5490.6  707.88  5523.4  708.58  5554.1  707.45  5698.2  708.46
#Mann= 3 ,-1 , 0
    4306      .1       0  4996.4     .07       0  5002.5      .1       0
Bank Sta=4969.93,5011.44
XS Rating Curve= 0 ,0
Exp/Cntr=0.3,0.1

Type RM Length L Ch R = 1 ,2438    ,183,183,183
BEGIN DESCRIPTION:
UNT 052 in HW 3.0
END DESCRIPTION:
XS GIS Cut Line= 5
      1986117.78     13615247.72      1986103.89     13614830.15
      1986322.64     13614705.15      1986554.41     13614330.15
       1986603.9     13613960.33
#Sta/Elev= 30
    4259  702.32  4411.8  698.34    4495  698.09  4571.9  693.53  4922.3  693.95
  4944.6  689.98    4960  692.98 4971.75 687.918  4975.4  686.02  4981.3  688.88
  4987.7  682.52  4999.5  681.08    5000  680.28  5005.6  681.08 5013.81687.9171
    5018  692.52  5023.8  691.04  5033.3   694.4  5060.5  696.23    5070  694.86
  5081.8  688.94  5091.3  688.05  5105.3  691.18  5133.8  690.35    5164  692.53
  5199.3  691.69  5286.3  693.12  5369.6  696.54  5465.6  705.98  5742.7  706.41
#Mann= 3 ,-1 , 0
    4259      .1       0  4999.5     .07       0  5005.6      .1       0
Bank Sta=4971.75,5013.81
XS Rating Curve= 0 ,0
Exp/Cntr=0.3,0.1

Type RM Length L Ch R = 1 ,2255    ,30,30,30
BEGIN DESCRIPTION:
Mapping XS 55d9eac5
END DESCRIPTION:
XS GIS Cut Line= 3
      1986178.61     13615077.83      1986508.01     13614594.79
      1986605.67     13614122.14
#Sta/Elev= 30
  4404.3  696.11  4553.9  691.47  4784.2  692.68  4807.2     694  4814.1  692.96
  4835.1  694.17    4871  693.37  4900.8  690.59  4921.8  691.47  4936.7  688.52
  4942.8  690.72  4951.7  688.82  4957.7   692.1  4972.6  687.16  4978.7  688.51
 4981.85685.9456  4985.8  682.73  4996.3  683.03  4998.4  680.07  4998.9  679.27
  5004.5  680.07  5019.4   684.2 5035.25685.9447  5046.6  687.43  5051.7  690.92
  5152.1  691.22  5197.3  693.09  5284.9  698.17  5356.4  705.83  5471.6  706.83
#Mann= 3 ,-1 , 0
  4404.3      .1       0  4998.4     .07       0  5004.5      .1       0
Bank Sta=4981.85,5035.25
XS Rating Curve= 0 ,0
Exp/Cntr=0.3,0.1

Type RM Length L Ch R = 1 ,2225    ,26,26,26
BEGIN DESCRIPTION:
Mapping XS 8b427832
END DESCRIPTION:
XS GIS Cut Line= 4
      1986190.28     13615089.62      1986420.77     13614747.14
      1986553.59     13614566.15        1986620.       13614113.
#Sta/Elev= 30
  4385.5  695.77    4400  695.98    4523  691.48    4586  692.44  4780.9  692.18
  4810.5  694.55  4866.9  694.42  4896.2  692.93  4902.4  694.18  4917.1   694.4
  4931.7  693.45  4937.9  694.27  4946.4  693.38  4967.2  693.93  4974.6  692.97
 4979.78685.6827  4981.9   682.7  4993.5  678.94    4994  678.14  4999.1  678.14
  4999.6  678.94  5002.7  679.49 5010.04685.6813  5017.4  688.37  5020.4  692.51
  5155.4  690.41  5286.7  698.13  5327.2  702.82  5342.6  705.54  5480.8  706.55
#Mann= 3 ,-1 , 0
  4385.5      .1       0  4993.5     .07       0  4999.6      .1       0
Bank Sta=4979.78,5010.04
XS Rating Curve= 0 ,0
Exp/Cntr=0.3,0.1

Type RM Length L Ch R = 1 ,2199    ,56,56,56
BEGIN DESCRIPTION:
Mapping XS 716cd6a3
END DESCRIPTION:
XS GIS Cut Line= 3
      1986199.41     13615093.51       1986561.4     13614594.79
      1986635.61     13614124.76
#Sta/Elev= 30
  4383.5     696    4516  691.63  4823.7  692.45  4844.6  691.38  4894.8  692.53
  4915.7   691.5  4924.2  692.52  4930.4  690.88  4937.7  690.86  4945.1  692.46
  4951.3  686.32  4959.8  689.22 4965.36685.2384  4974.5  684.86  4987.1  681.91
  4992.3  679.42  4992.8  678.62  4998.4  679.42  5002.2  679.68 5012.62 685.239
  5019.8   690.4  5055.1  691.22  5060.3  693.48  5080.5  691.52  5110.9  690.57
  5131.1  691.41  5151.4  689.64  5293.1  697.79  5353.9  704.96  5475.6  706.23
#Mann= 3 ,-1 , 0
  4383.5      .1       0  4992.3     .07       0  4998.4      .1       0
Bank Sta=4965.36,5012.62
XS Rating Curve= 0 ,0
Exp/Cntr=0.3,0.1