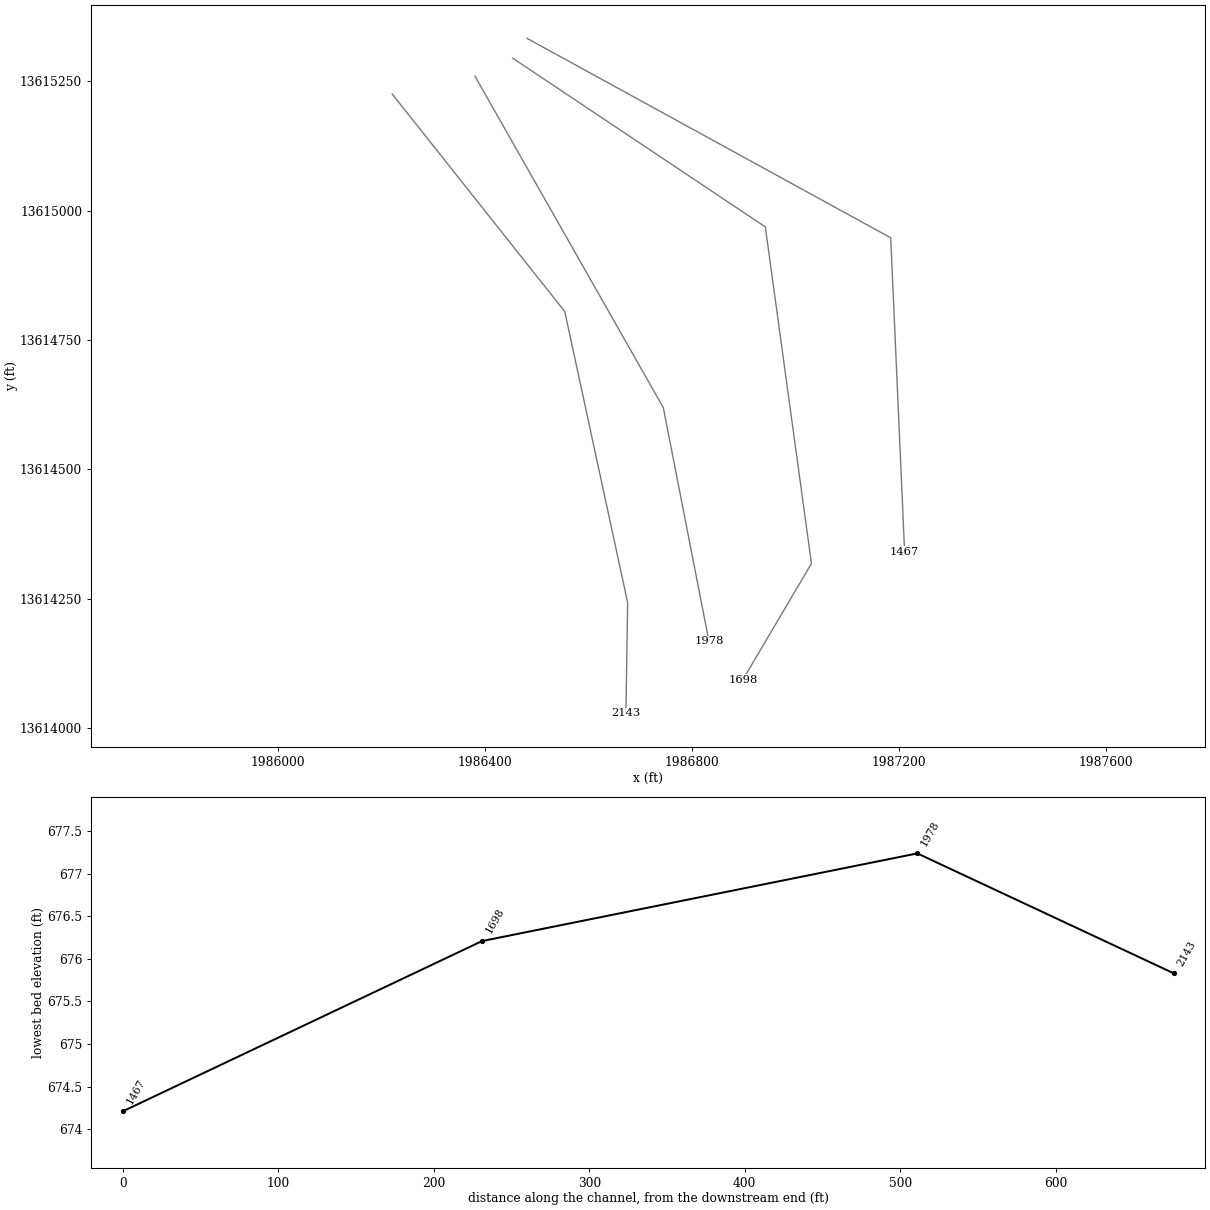
HEC-RAS study UNT 052 in HW.prj: UNT 052 in HW Base Level Engineering

--- UNT 052 in HW.g01 (geometry) --- (continued)

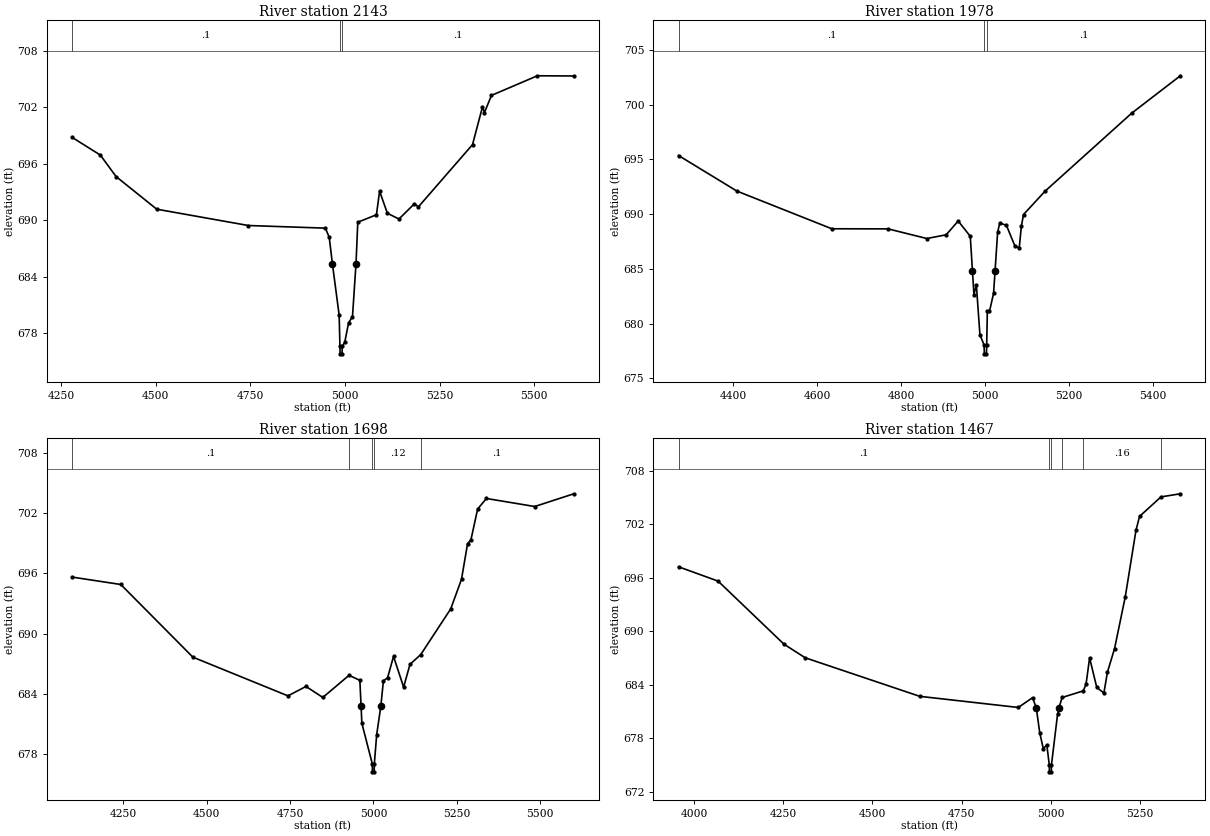
Type RM Length L Ch R = 1 ,2143    ,165,165,165
BEGIN DESCRIPTION:
Mapping XS 3167391a
END DESCRIPTION:
XS GIS Cut Line= 4
      1986220.82     13615225.01      1986554.13     13614804.89
      1986675.66     13614242.39      1986672.21     13614028.58
#Sta/Elev= 30
  4279.2  698.79  4353.9  696.91  4395.5  694.63  4502.9  691.17  4744.8  689.44
  4948.4  689.16  4958.6  688.18  4966.9 685.397  4984.8  679.92  4986.8  676.63
  4987.3  675.83  4992.4  675.83  4992.9  676.63  4999.5  677.05  5009.8  679.14
    5020  679.77 5029.28685.3938    5034  689.79  5083.3  690.58  5091.6  693.09
  5112.1  690.74  5142.8  690.13  5183.7  691.75  5193.9  691.41  5337.1  698.02
  5363.4  702.02  5368.6  701.41  5387.1  703.24  5508.4  705.32  5604.8   705.3
#Mann= 3 ,-1 , 0
  4279.2      .1       0  4986.8     .07       0  4992.9      .1       0
Bank Sta=4966.9,5029.28
XS Rating Curve= 0 ,0
Exp/Cntr=0.3,0.1

Type RM Length L Ch R = 1 ,1978    ,280,280,280
BEGIN DESCRIPTION:
UNT 052 in HW 2.0
END DESCRIPTION:
XS GIS Cut Line= 3
      1986380.53     13615259.74      1986744.52     13614619.21
      1986832.67     13614168.07
#Sta/Elev= 30
  4269.4  695.35  4408.6   692.1  4634.9  688.66    4769  688.65  4861.4  687.77
  4907.5  688.11  4936.2  689.37    4965  687.97 4970.23 684.772  4973.7  682.65
  4979.5  683.53    4988  678.98    4998  678.04  4998.5  677.24  5003.6  677.24
  5004.1  678.04  5005.7  681.11  5010.8  681.11  5020.6  682.79 5024.03684.7728
  5030.2  688.34  5035.3  689.19  5051.2  688.97  5071.6  687.07  5081.7  686.91
  5086.8  688.89  5091.9  689.96  5143.5   692.1  5349.7  699.21  5465.8  702.63
#Mann= 3 ,-1 , 0
  4269.4      .1       0    4998     .07       0  5004.1      .1       0
Bank Sta=4970.23,5024.03
XS Rating Curve= 0 ,0
Exp/Cntr=0.3,0.1

Type RM Length L Ch R = 1 ,1698    ,231,231,231
BEGIN DESCRIPTION:
Mapping XS 5dd2e174
END DESCRIPTION:
XS GIS Cut Line= 4
      1986453.48     13615294.45      1986941.62     13614968.37
      1987030.69     13614317.95      1986897.87     13614093.07
#Sta/Elev= 30
  4096.2  695.64  4242.3   694.9  4458.5  687.65  4743.6  683.79  4797.7  684.73
  4848.1  683.63  4926.7  685.84  4959.2  685.34 4962.78682.7866  4965.2  681.06
  4996.4  677.01  4996.9  676.21  5002.1  676.21  5002.6  677.01  5009.6  679.91
 5022.17682.7818  5029.8  685.29  5042.4   685.6  5060.1  687.73  5090.4  684.66
  5109.5  686.93  5141.8  687.91  5231.7  692.47    5264  695.42  5282.1  698.97
  5292.2  699.35  5312.4  702.43  5338.7  703.48  5483.5  702.68  5600.9  703.95
#Mann= 5 ,-1 , 0
  4096.2      .1       0  4926.7     .12       0  4996.4     .07       0
  5002.6     .12       0  5141.8      .1       0
Bank Sta=4962.78,5022.17
XS Rating Curve= 0 ,0
Exp/Cntr=0.3,0.1

Type RM Length L Ch R = 1 ,1467    ,0,0,0
BEGIN DESCRIPTION:
Mapping XS cd692d3f
END DESCRIPTION:
XS GIS Cut Line= 3
      1986481.21     13615332.68      1987183.86     13614947.31
      1987210.66     13614340.59
#Sta/Elev= 30
  3955.6  697.24  4066.7  695.63  4251.5  688.55  4311.2  687.02  4632.8  682.69
  4909.4  681.44  4949.5  682.54 4960.07681.3736  4969.5  678.62  4979.5  676.83
  4989.5  677.22  4996.4  675.01  4996.9  674.21  5002.1  674.21  5002.6  675.01
  5019.6  680.66 5023.63681.3732  5032.2  682.56  5091.7   683.3  5099.6  684.04
  5109.6  687.01  5129.7  683.69  5149.7  683.06  5159.7  685.41  5179.7  688.06
  5209.7  693.86  5239.8  701.33  5249.8   702.9    5310  705.09  5364.3  705.44
#Mann= 6 ,-1 , 0
  3955.6      .1       0  4996.4     .07       0  5002.6      .1       0
  5032.2     .12       0  5091.7     .16       0    5310      .1       0
Bank Sta=4960.07,5023.63
XS Rating Curve= 0 ,0
Exp/Cntr=0.3,0.1
LCMann Table=0

Chan Stop Cuts=-1
Use User Specified Reach Order=0
Composite Channel Slope=5