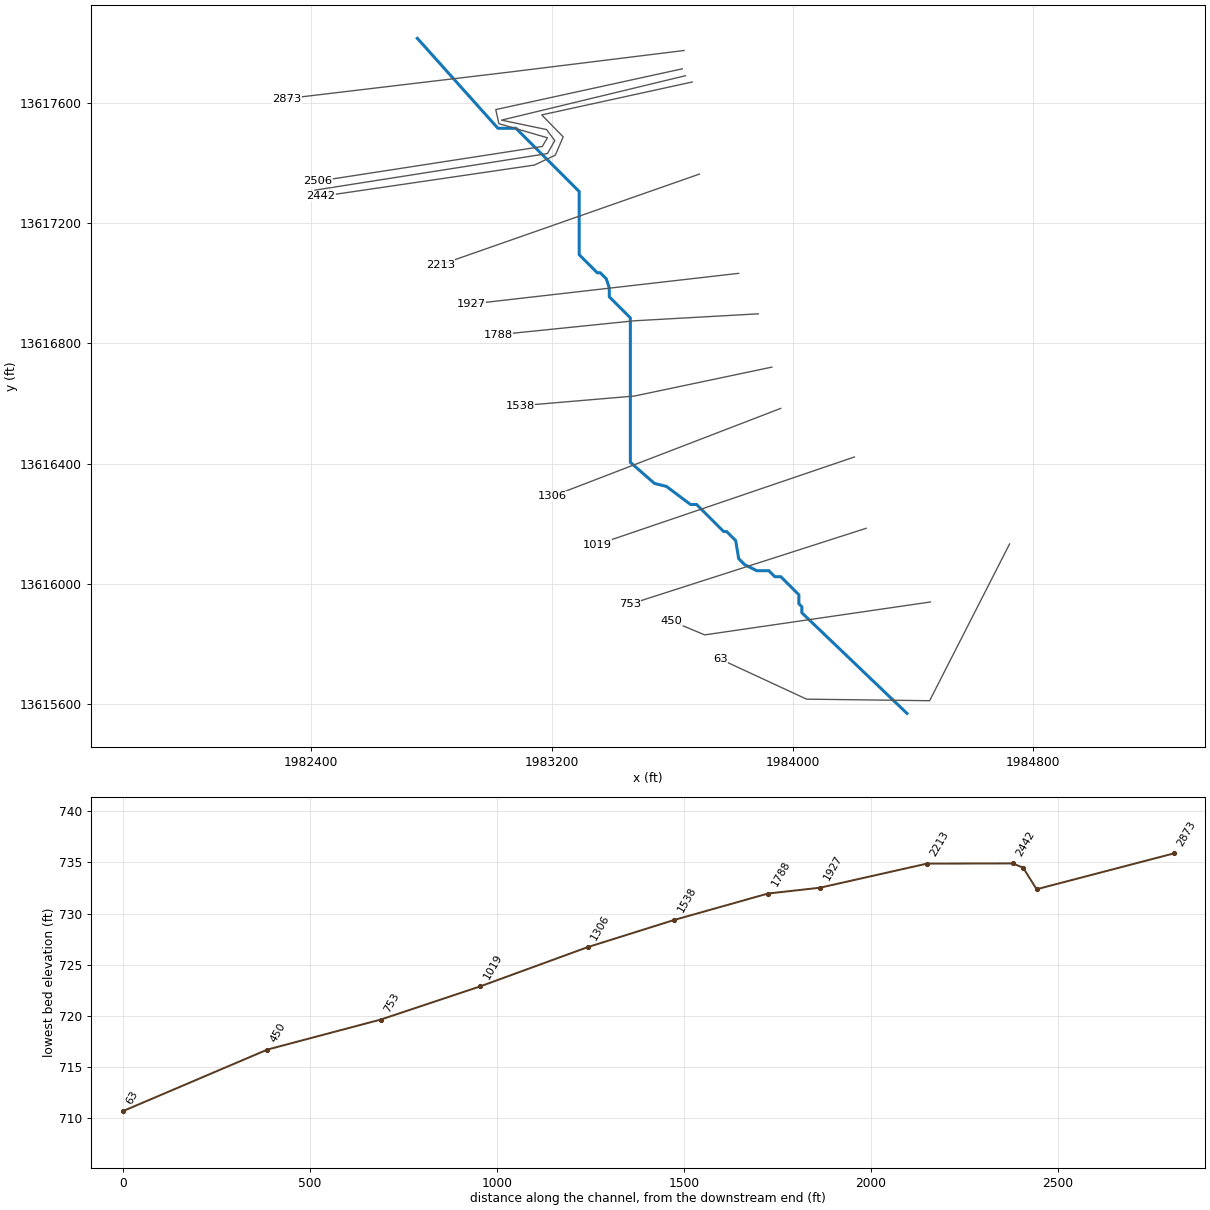
--- UNT 054 in HW.prj (project) ---

Proj Title=UNT 054 in HW Base Level Engineering
Current Plan=p01
Default Exp/Contr=0.3,0.1
English Units
Geom File=g01
Flow File=f01
Plan File=p01
BEGIN DESCRIPTION:
UNT 054 in HW
END DESCRIPTION:

--- UNT 054 in HW.p01 (plan) ---

Plan Title=Multiple Run
Short Identifier=Multiple
Geom File=g01
Flow File=f01
Subcritical Flow
K Sum by GR= 0
Std Step Tol= 0.01
Critical Tol= 0.01
Num of Std Step Trials= 20
Max Error Tol= 0.3
Flow Tol Ratio= 0.001
Split Flow NTrial= 30
Split Flow Tol= 0.02
Split Flow Ratio= 0.02
Log Output Level= 0
Friction Slope Method= 1
Unsteady Friction Slope Method= 2
Unsteady Bridges Friction Slope Method= 1
Parabolic Critical Depth
Global Vel Dist=  1 , 1 , 1
Global Log Level= 0
CheckData=True
Encroach Param= -1, 0, 0, 0
BEGIN DESCRIPTION:
Multiple Run
END DESCRIPTION:

--- UNT 054 in HW.f01 (steady flow) ---

Flow Title=Multiple
Number of Profiles=7
Profile Names=10-year,25-year,50-year,1pct_min,100-year,1pct_plu,500-year
River Rch & RM= UNT 054 in HW,Reach-1,2873
     149     192     225     131     261     521     352
River Rch & RM= UNT 054 in HW,Reach-1,63
     668     949    1186     733    1463    2918    2235
Boundary for River Rch & Prof#=UNT 054 in HW,Reach-1,1
Up Type=0
Dn Type=3
Dn Slope=0.005
Boundary for River Rch & Prof#=UNT 054 in HW,Reach-1,2
Up Type=0
Dn Type=3
Dn Slope=0.005
Boundary for River Rch & Prof#=UNT 054 in HW,Reach-1,3
Up Type=0
Dn Type=3
Dn Slope=0.005
Boundary for River Rch & Prof#=UNT 054 in HW,Reach-1,4
Up Type=0
Dn Type=3
Dn Slope=0.005
Boundary for River Rch & Prof#=UNT 054 in HW,Reach-1,5
Up Type=0
Dn Type=3
Dn Slope=0.005
Boundary for River Rch & Prof#=UNT 054 in HW,Reach-1,6
Up Type=0
Dn Type=3
Dn Slope=0.005
Boundary for River Rch & Prof#=UNT 054 in HW,Reach-1,7
Up Type=0
Dn Type=3
Dn Slope=0.005

--- UNT 054 in HW.g01 (geometry) ---

Geom Title=Existing Conditions

River Reach=UNT 054 in HW,Reach-1
Reach XY= 30
      1982753.07     13617813.50      1983020.80     13617514.54
      1983080.80     13617514.54      1983290.80     13617304.54
      1983290.80     13617094.54      1983350.80     13617034.54
      1983360.80     13617034.54      1983380.80     13617014.54
      1983390.80     13616984.54      1983390.80     13616954.54
      1983460.80     13616884.54      1983460.80     13616404.54
      1983540.80     13616334.54      1983580.80     13616324.54
      1983660.80     13616264.54      1983680.80     13616264.54
      1983770.80     13616174.54      1983780.80     13616174.54
      1983810.80     13616144.54      1983820.80     13616084.54
      1983840.80     13616064.54      1983880.80     13616044.54
      1983920.80     13616044.54      1983940.80     13616024.54
      1983960.80     13616024.54      1984020.80     13615964.54
      1984020.80     13615934.54      1984030.80     13615924.54
      1984030.80     13615904.54      1984379.98     13615570.42

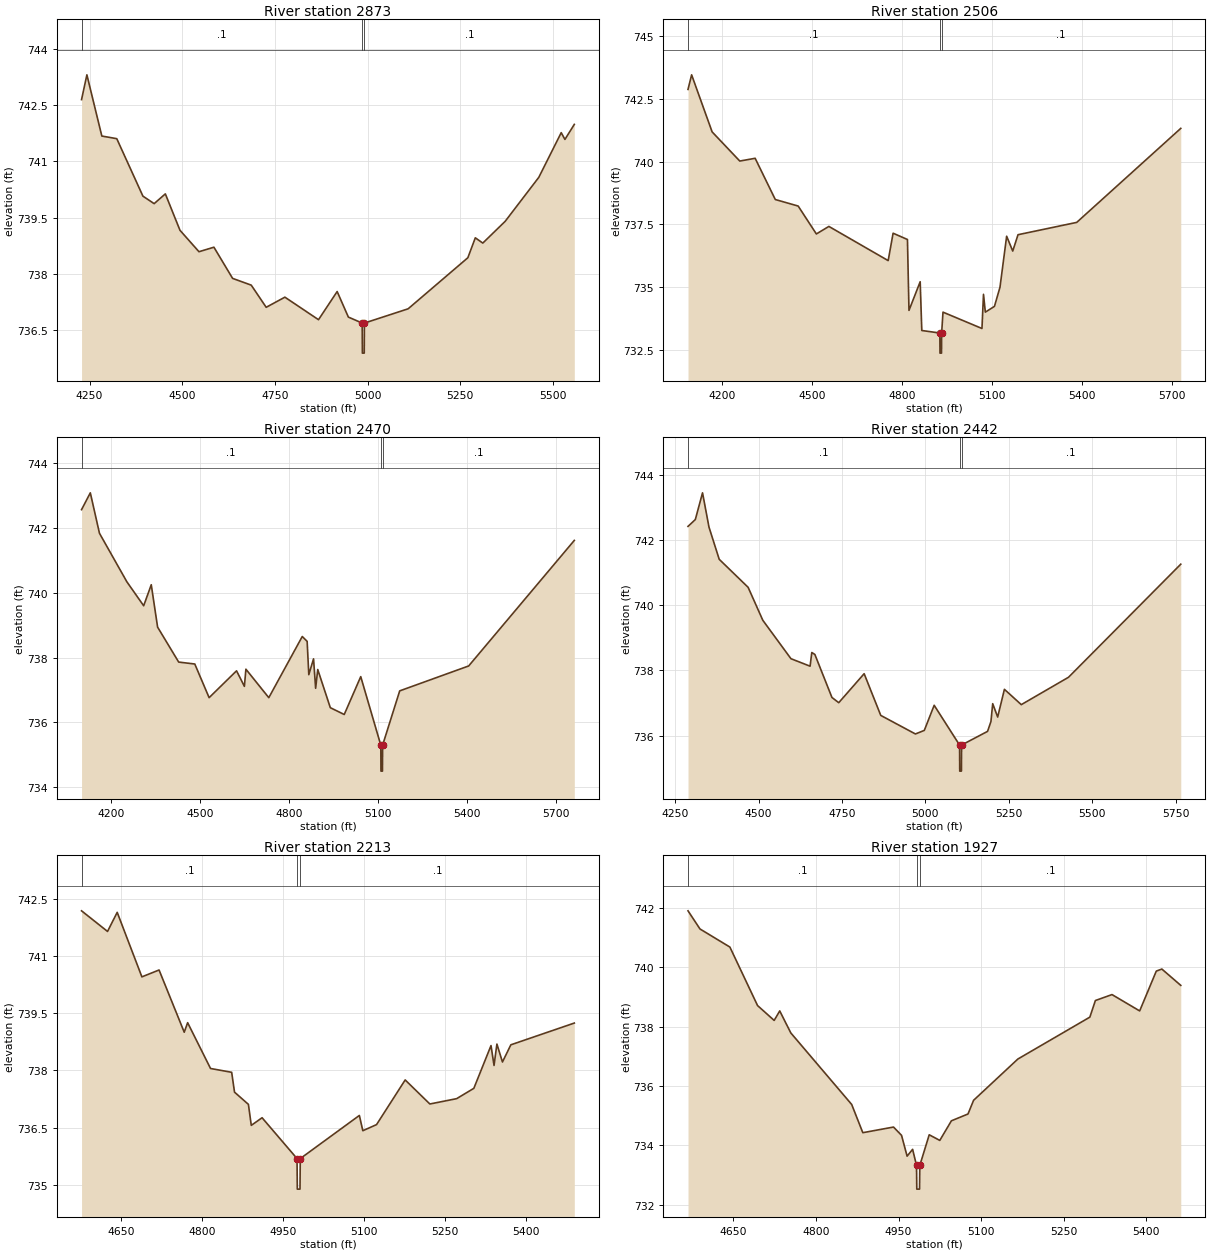
Type RM Length L Ch R = 1,2873,367,367,367
BEGIN DESCRIPTION:
UNT 054 in HW 4.0
END DESCRIPTION:
XS GIS Cut Line= 3
      1983639.28     13617773.06      1983049.00     13617700.15
      1982319.92     13617613.35
#Sta/Elev= 30
  4228.3  742.64  4242.7  743.30  4283.0  741.67  4323.3  741.60  4393.8  740.07
  4424.1  739.87  4454.3  740.13  4493.8  739.16  4545.0  738.59  4585.3  738.71
  4635.7  737.88  4686.0  737.70  4726.3  737.11  4776.7  737.38  4867.4  736.78
  4917.7  737.53  4947.9  736.85  4985.2  736.69  4985.7  735.89  4990.7  735.89
  4991.2  736.69  5109.1  737.07  5270.2  738.43  5290.3  738.96  5310.5  738.82
  5370.9  739.40  5461.5  740.57  5522.0  741.76  5532.0  741.58  5557.3  741.98
#Mann=3,-1,0
  4228.3     0.1       0  4985.2    0.07       0  4991.2     0.1       0
Bank Sta=4985.2,4991.2
Exp/Cntr=0.3,0.1

Type RM Length L Ch R = 1,2506,36,36,36
BEGIN DESCRIPTION:
UNT 054 in HW 7.0
END DESCRIPTION:
XS GIS Cut Line= 6
      1983633.40     13617712.18      1983013.59     13617576.76
      1983024.01     13617529.88      1983185.47     13617483.01
      1983168.11     13617454.07      1982423.34     13617338.92
#Sta/Elev= 30
  4086.9  742.87  4098.9  743.45  4167.2  741.18  4259.3  740.02  4310.5  740.13
  4377.6  738.49  4453.8  738.23  4514.4  737.12  4556.1  737.42  4753.6  736.06
  4770.0  737.15  4817.8  736.90  4822.9  734.08  4860.2  735.22  4865.6  733.28
  4925.7  733.18  4926.2  732.38  4931.2  732.38  4931.7  733.18  4936.2  734.01
  5066.0  733.36  5071.1  734.72  5077.2  734.01  5107.6  734.24  5126.0  735.00
  5148.2  737.03  5168.5  736.44  5186.1  737.09  5381.6  737.58  5728.2  741.32
#Mann=3,-1,0
  4086.9     0.1       0  4925.7    0.07       0  4931.7     0.1       0
Bank Sta=4925.7,4931.7
Exp/Cntr=0.3,0.1

Type RM Length L Ch R = 1,2470,28,28,28
BEGIN DESCRIPTION:
UNT 054 in HW 5.0
END DESCRIPTION:
XS GIS Cut Line= 6
      1983643.80     13617689.26      1983032.69     13617541.69
      1983182.00     13617510.44      1983209.77     13617473.98
      1983185.47     13617430.58      1982412.89     13617309.05
#Sta/Elev= 30
  4099.5  742.57  4129.1  743.09  4160.0  741.84  4252.6  740.34  4309.3  739.60
  4334.9  740.25  4356.3  738.94  4427.5  737.86  4481.9  737.80  4530.3  736.76
  4622.9  737.59  4649.4  737.11  4654.5  737.64  4731.8  736.76  4844.8  738.65
  4861.3  738.50  4866.9  737.47  4882.9  737.96  4890.0  737.05  4897.1  737.63
  4939.6  736.45  4986.6  736.24  5042.3  737.41  5110.1  735.29  5110.6  734.49
  5115.6  734.49  5116.1  735.29  5173.9  736.97  5406.8  737.74  5763.5  741.62
#Mann=3,-1,0
  4099.5     0.1       0  5110.1    0.07       0  5116.1     0.1       0
Bank Sta=5110.1,5116.1
Exp/Cntr=0.3,0.1

Type RM Length L Ch R = 1,2442,229,229,229
BEGIN DESCRIPTION:
UNT 054 in HW 6.0
END DESCRIPTION:
XS GIS Cut Line= 6
      1983666.39     13617668.43      1983166.37     13617559.05
      1983237.55     13617486.13      1983211.51     13617425.37
      1983142.06     13617392.38      1982432.02     13617288.22
#Sta/Elev= 30
  4288.5  742.42  4310.4  742.63  4332.0  743.45  4351.3  742.40  4382.0  741.41
  4468.7  740.55  4512.6  739.54  4597.0  738.36  4654.4  738.13  4659.5  738.55
  4668.7  738.49  4719.9  737.17  4740.3  737.01  4816.4  737.90  4866.2  736.62
  4970.1  736.05  4996.7  736.16  5026.3  736.93  5102.4  735.71  5102.9  734.91
  5107.9  734.91  5108.4  735.71  5186.3  736.13  5196.4  736.43  5201.7  736.98
  5216.6  736.57  5236.8  737.42  5287.4  736.95  5428.9  737.79  5765.4  741.26
#Mann=3,-1,0
  4288.5     0.1       0  5102.4    0.07       0  5108.4     0.1       0
Bank Sta=5102.4,5108.4
Exp/Cntr=0.3,0.1

Type RM Length L Ch R = 1,2213,286,286,286
BEGIN DESCRIPTION:
UNT 054 in HW 8.0
END DESCRIPTION:
XS GIS Cut Line= 2
      1983690.41     13617362.46      1982829.46     13617061.02
#Sta/Elev= 30
  4576.6  742.18  4624.7  741.64  4642.6  742.14  4688.3  740.45  4720.1  740.63
  4766.7  739.00  4773.0  739.25  4815.4  738.05  4854.5  737.95  4859.8  737.43
  4885.5  737.11  4890.8  736.56  4910.8  736.76  4975.5  735.69  4976.0  734.89
  4981.0  734.89  4981.5  735.69  5090.9  736.82  5097.3  736.42  5122.7  736.58
  5175.7  737.75  5221.4  737.12  5271.0  737.26  5302.8  737.53  5334.6  738.65
  5340.2  738.13  5345.5  738.69  5355.8  738.22  5371.3  738.67  5488.8  739.24
#Mann=3,-1,0
  4576.6     0.1       0  4975.5    0.07       0  4981.5     0.1       0
Bank Sta=4975.5,4981.5
Exp/Cntr=0.3,0.1

Type RM Length L Ch R = 1,1927,139,139,139
BEGIN DESCRIPTION:
UNT 054 in HW 9.0
END DESCRIPTION:
XS GIS Cut Line= 2
      1983820.58     13617032.59      1982930.81     13616930.59
#Sta/Elev= 30
  4567.4  741.90  4589.1  741.29  4643.5  740.68  4693.8  738.71  4724.0  738.21
  4734.1  738.53  4754.2  737.79  4864.9  735.38  4885.1  734.43  4940.9  734.62
  4955.5  734.34  4965.6  733.64  4975.6  733.87  4982.7  733.33  4983.2  732.53
  4988.2  732.53  4988.7  733.33  5005.8  734.36  5025.0  734.17  5046.1  734.83
  5076.3  735.06  5086.4  735.52  5166.9  736.91  5297.7  738.32  5307.8  738.88
  5338.0  739.08  5388.3  738.53  5418.5  739.87  5428.6  739.94  5463.0  739.39
#Mann=3,-1,0
  4567.4     0.1       0  4982.7    0.07       0  4988.7     0.1       0
Bank Sta=4982.7,4988.7
Exp/Cntr=0.3,0.1

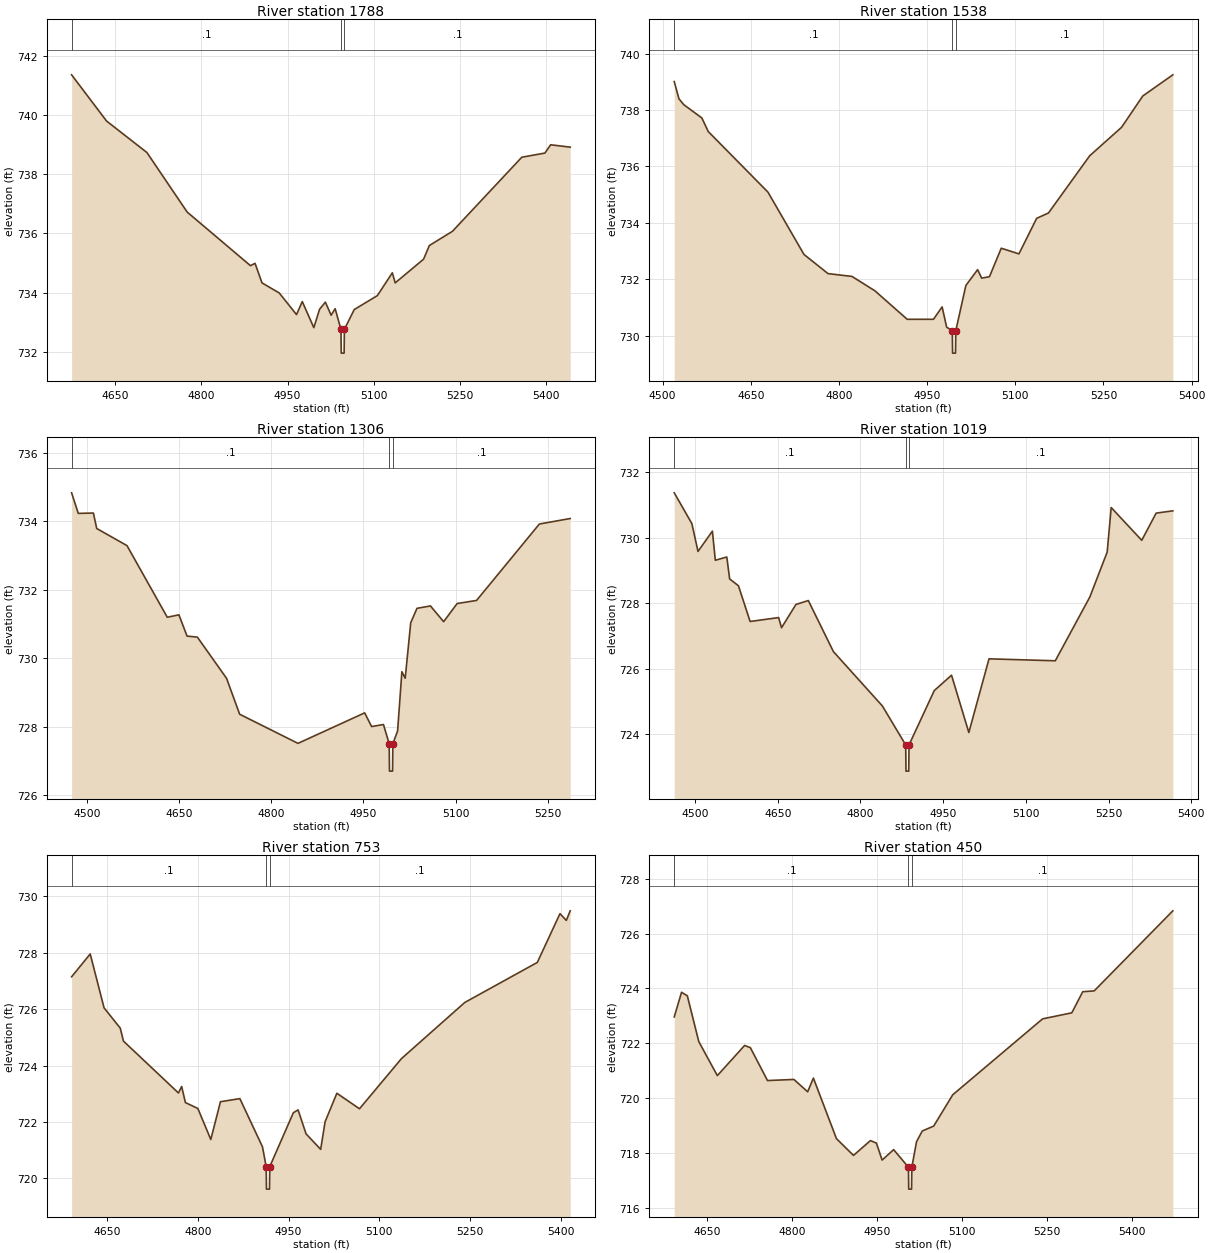
Type RM Length L Ch R = 1,1788,250,250,250
BEGIN DESCRIPTION:
UNT 054 in HW 3.0
END DESCRIPTION:
XS GIS Cut Line= 3
      1983885.78     13616898.06      1983475.00     13616875.00
      1983021.19     13616828.61
#Sta/Elev= 30
  4574.3  741.35  4635.2  739.79  4705.3  738.73  4775.4  736.72  4885.6  734.91
  4893.5  734.99  4905.6  734.33  4935.6  733.99  4965.7  733.26  4975.7  733.70
  4995.8  732.82  5005.8  733.44  5015.9  733.68  5025.9  733.24  5032.9  733.46
  5043.0  732.76  5043.5  731.96  5048.5  731.96  5049.0  732.76  5066.1  733.43
  5106.3  733.90  5132.4  734.67  5137.4  734.33  5186.8  735.13  5196.8  735.59
  5237.0  736.07  5357.7  738.57  5397.9  738.71  5407.9  738.99  5441.9  738.91
#Mann=3,-1,0
  4574.3     0.1       0  5043.0    0.07       0  5049.0     0.1       0
Bank Sta=5043,5049
Exp/Cntr=0.3,0.1

Type RM Length L Ch R = 1,1538,232,232,232
BEGIN DESCRIPTION:
UNT 054 in HW 2.0
END DESCRIPTION:
XS GIS Cut Line= 3
      1983930.95     13616720.98      1983475.00     13616625.00
      1983094.13     13616592.51
#Sta/Elev= 30
  4519.8  739.01  4527.8  738.40  4536.1  738.19  4566.8  737.72  4577.6  737.24
  4679.2  735.09  4740.5  732.88  4781.4  732.20  4822.2  732.10  4861.2  731.59
  4916.1  730.58  4960.8  730.58  4975.5  731.02  4983.2  730.30  4992.8  730.18
  4993.3  729.38  4998.3  729.38  4998.8  730.18  5015.9  731.78  5035.9  732.34
  5042.8  732.04  5056.0  732.09  5076.1  733.10  5106.2  732.90  5136.3  734.16
  5156.4  734.35  5226.6  736.38  5280.8  737.39  5316.9  738.50  5368.0  739.25
#Mann=3,-1,0
  4519.8     0.1       0  4992.8    0.07       0  4998.8     0.1       0
Bank Sta=4992.8,4998.8
Exp/Cntr=0.3,0.1

Type RM Length L Ch R = 1,1306,287,287,287
BEGIN DESCRIPTION:
Mapping XS ead3bfe6
END DESCRIPTION:
XS GIS Cut Line= 2
      1983960.44     13616583.82      1983202.63     13616292.15
#Sta/Elev= 30
  4474.7  734.83  4485.6  734.23  4510.2  734.24  4515.6  733.79  4564.9  733.29
  4630.5  731.20  4649.5  731.27  4662.7  730.65  4679.5  730.62  4727.0  729.42
  4748.4  728.37  4843.4  727.52  4952.0  728.41  4963.3  728.01  4982.6  728.07
  4991.9  727.51  4992.4  726.71  4997.4  726.71  4997.9  727.51  5005.6  727.88
  5012.6  729.61  5018.0  729.42  5027.0  731.04  5037.2  731.46  5059.1  731.53
  5080.6  731.07  5102.6  731.60  5134.2  731.69  5236.5  733.92  5286.7  734.08
#Mann=3,-1,0
  4474.7     0.1       0  4991.9    0.07       0  4997.9     0.1       0
Bank Sta=4991.9,4997.9
Exp/Cntr=0.3,0.1

Type RM Length L Ch R = 1,1019,266,266,266
BEGIN DESCRIPTION:
Mapping XS 36d4c1b0
END DESCRIPTION:
XS GIS Cut Line= 2
      1984205.26     13616422.37      1983349.20     13616130.95
#Sta/Elev= 30
  4462.3  731.37  4494.3  730.43  4505.4  729.58  4531.5  730.20  4536.8  729.31
  4557.6  729.41  4562.8  728.74  4578.8  728.53  4599.9  727.44  4651.6  727.56
  4656.9  727.25  4683.0  727.96  4705.5  728.08  4751.0  726.52  4839.8  724.86
  4882.1  723.67  4882.6  722.87  4887.6  722.87  4888.1  723.67  4933.9  725.33
  4965.2  725.80  4996.6  724.05  5033.2  726.30  5153.4  726.24  5216.1  728.19
  5247.5  729.56  5254.8  730.92  5310.2  729.92  5336.3  730.75  5366.6  730.82
#Mann=3,-1,0
  4462.3     0.1       0  4882.1    0.07       0  4888.1     0.1       0
Bank Sta=4882.1,4888.1
Exp/Cntr=0.3,0.1

Type RM Length L Ch R = 1,753,303,303,303
BEGIN DESCRIPTION:
Mapping XS f43d9826
END DESCRIPTION:
XS GIS Cut Line= 2
      1984244.31     13616185.39      1983458.92     13615933.13
#Sta/Elev= 30
  4591.1  727.15  4621.9  727.96  4644.8  726.05  4671.6  725.33  4676.9  724.87
  4767.9  723.03  4773.2  723.26  4779.4  722.69  4800.0  722.48  4821.4  721.38
  4837.4  722.72  4869.5  722.83  4906.9  721.12  4913.0  720.42  4913.5  719.62
  4918.5  719.62  4919.0  720.42  4958.0  722.33  4965.8  722.43  4979.0  721.58
  5003.2  721.03  5010.5  722.01  5030.0  723.02  5067.4  722.47  5136.9  724.25
  5241.6  726.24  5361.6  727.66  5399.1  729.39  5409.6  729.15  5416.0  729.49
#Mann=3,-1,0
  4591.1     0.1       0  4913.0    0.07       0  4919.0     0.1       0
Bank Sta=4913,4919
Exp/Cntr=0.3,0.1

Type RM Length L Ch R = 1,450,387,387,387
BEGIN DESCRIPTION:
Mapping XS 870f6707
END DESCRIPTION:
XS GIS Cut Line= 3
      1984457.81     13615940.59      1983707.86     13615831.22
      1983595.86     13615878.10
#Sta/Elev= 30
  4592.5  722.96  4605.4  723.86  4615.6  723.73  4635.8  722.06  4668.5  720.82
  4716.6  721.92  4726.7  721.84  4757.0  720.64  4803.5  720.68  4827.8  720.23
  4837.9  720.73  4878.6  718.52  4908.6  717.91  4938.5  718.45  4949.0  718.36
  4959.1  717.74  4979.4  718.12  5005.5  717.48  5006.0  716.68  5011.0  716.68
  5011.5  717.48  5019.8  718.41  5029.9  718.80  5050.1  718.98  5083.6  720.12
  5242.1  722.89  5293.6  723.11  5312.9  723.88  5333.1  723.91  5471.8  726.83
#Mann=3,-1,0
  4592.5     0.1       0  5005.5    0.07       0  5011.5     0.1       0
Bank Sta=5005.5,5011.5
Exp/Cntr=0.3,0.1

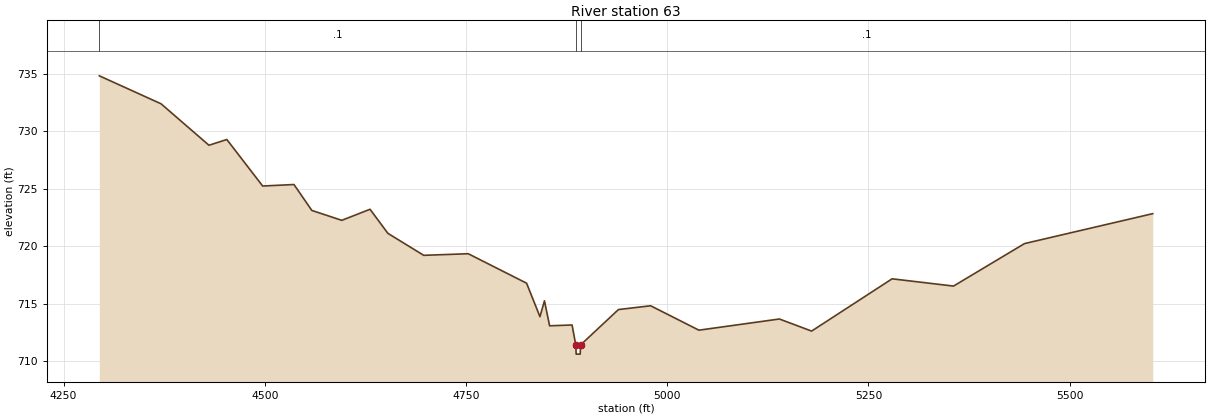
Type RM Length L Ch R = 1,63,0,0,0
BEGIN DESCRIPTION:
UNT 054 in HW 1.0
END DESCRIPTION:
XS GIS Cut Line= 4
      1984720.88     13616133.31      1984455.25     13615612.47
      1984046.40     13615617.68      1983760.48     13615750.24
#Sta/Elev= 30
  4294.5  734.81  4371.2  732.38  4430.7  728.78  4452.9  729.28  4497.4  725.24
  4536.3  725.37  4558.5  723.12  4595.7  722.26  4630.8  723.22  4653.0  721.13
  4697.5  719.22  4752.8  719.36  4825.3  716.80  4841.9  713.89  4847.5  715.27
  4853.9  713.10  4881.8  713.17  4886.4  711.44  4886.9  710.64  4891.9  710.64
  4892.4  711.44  4939.4  714.51  4979.4  714.84  5039.4  712.72  5139.4  713.69
  5179.4  712.64  5279.4  717.18  5355.7  716.55  5443.9  720.24  5603.2  722.84
#Mann=3,-1,0
  4294.5     0.1       0  4886.4    0.07       0  4892.4     0.1       0
Bank Sta=4886.4,4892.4
Exp/Cntr=0.3,0.1

Chan Stop Cuts=-1