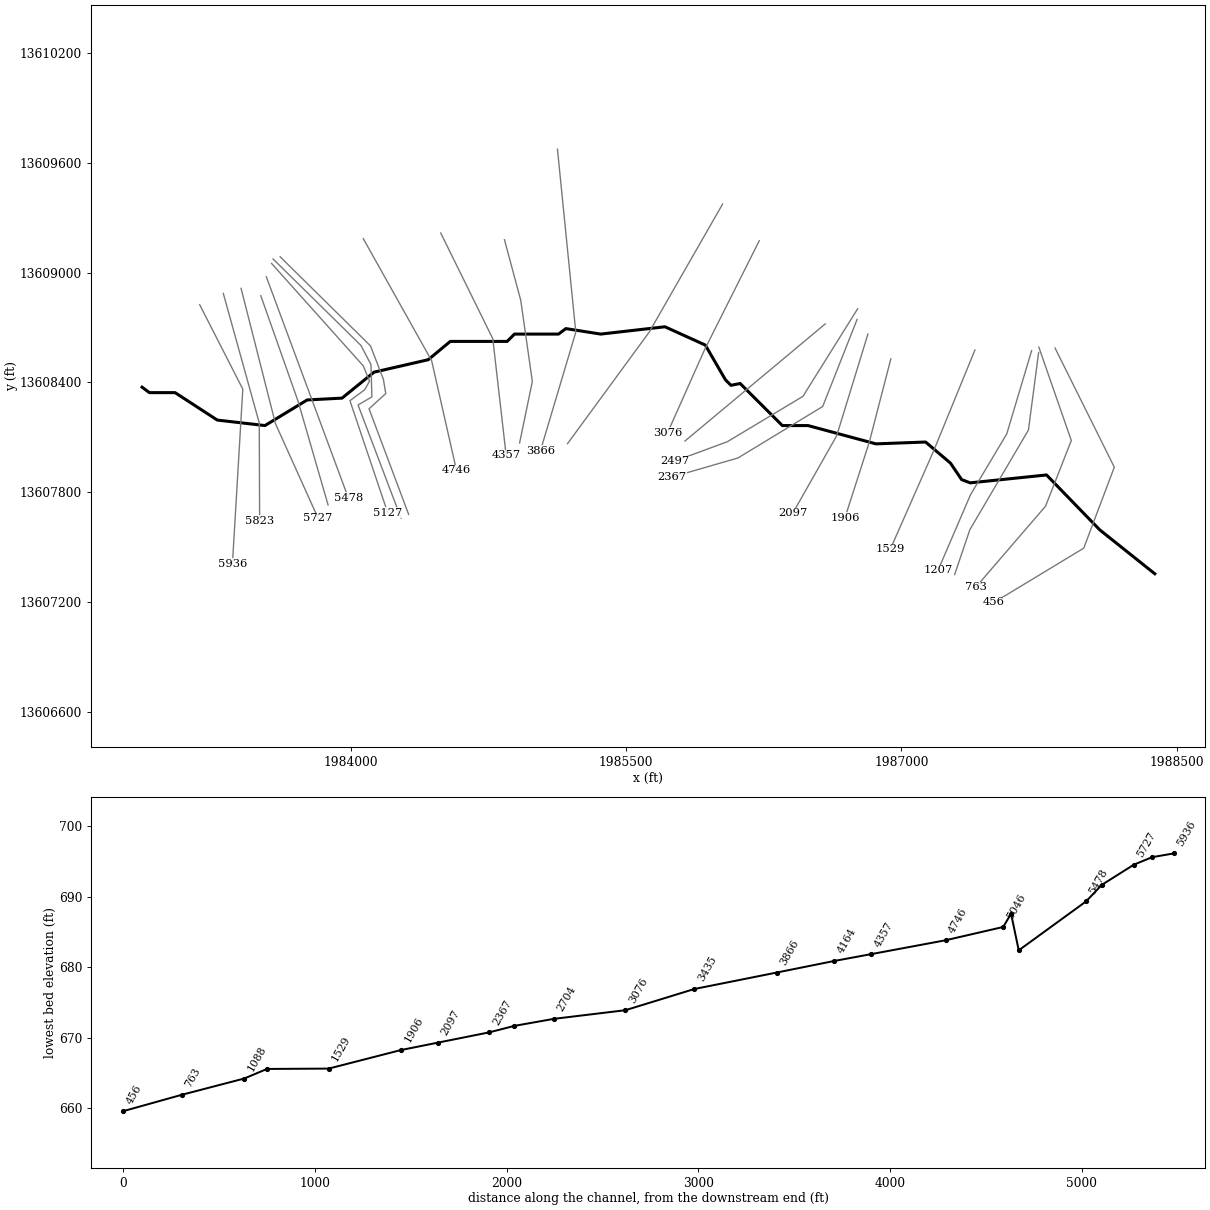
--- UNT 055 in HW.prj (project) ---

Proj Title=UNT 055 in HW Base Level Engineering
Current Plan=p01
Default Exp/Contr=0.3,0.1
English Units
Geom File=g01
Flow File=f01
Plan File=p01
Y Axis Title=Elevation
X Axis Title(PF)=Main Channel Distance
X Axis Title(XS)=Station
BEGIN DESCRIPTION:
UNT 055 in HW
END DESCRIPTION:
DSS Export Rating Curves= 0
DSS Export Rating Curve Sorted= 0
DSS Export Volume Flow Curves= 0
DXF OffsetX= 0
DXF OffsetY= 0
DXF ScaleX= 1
DXF ScaleY= 10

--- UNT 055 in HW.p01 (plan) ---

Plan Title=Multiple Run
Short Identifier=Multiple
Geom File=g01
Flow File=f01
Subcritical Flow
K Sum by GR= 0
Std Step Tol= 0.01
Critical Tol= 0.01
Num of Std Step Trials= 20
Max Error Tol= 0.3
Flow Tol Ratio= 0.001
Split Flow NTrial= 30
Split Flow Tol= 0.02
Split Flow Ratio= 0.02
Log Output Level= 0
Friction Slope Method= 1
Unsteady Friction Slope Method= 2
Unsteady Bridges Friction Slope Method= 1
Parabolic Critical Depth
Global Vel Dist=  1 , 1 , 1
Global Log Level= 0
CheckData=True
Encroach Param= -1, 0, 0, 0
BEGIN DESCRIPTION:
Multiple Run
END DESCRIPTION:

--- UNT 055 in HW.f01 (steady flow) ---

Flow Title=Multiple
Number of Profiles=7
Profile Names=10-year,25-year,50-year,1pct_min,100-year,1pct_plu,500-year
River Rch & RM= UNT 055 in HW,Reach-1,5936
     355     487     595     361     720    1436    1056
River Rch & RM= UNT 055 in HW,Reach-1,3866
     773    1110    1396     870    1736    3463    2692
Boundary for River Rch & Prof#=UNT 055 in HW,Reach-1,1
Up Type=0
Dn Type=3
Dn Slope=0.005
Boundary for River Rch & Prof#=UNT 055 in HW,Reach-1,2
Up Type=0
Dn Type=3
Dn Slope=0.005
Boundary for River Rch & Prof#=UNT 055 in HW,Reach-1,3
Up Type=0
Dn Type=3
Dn Slope=0.005
Boundary for River Rch & Prof#=UNT 055 in HW,Reach-1,4
Up Type=0
Dn Type=3
Dn Slope=0.005
Boundary for River Rch & Prof#=UNT 055 in HW,Reach-1,5
Up Type=0
Dn Type=3
Dn Slope=0.005
Boundary for River Rch & Prof#=UNT 055 in HW,Reach-1,6
Up Type=0
Dn Type=3
Dn Slope=0.005
Boundary for River Rch & Prof#=UNT 055 in HW,Reach-1,7
Up Type=0
Dn Type=3
Dn Slope=0.005

--- UNT 055 in HW.g01 (geometry) ---

Geom Title=Existing Conditions
Program Version=5.05

River Reach=UNT 055 in HW   ,Reach-1
Reach XY= 30
       1982860.8     13608374.54       1982900.8     13608344.54
       1983040.8     13608344.54       1983270.8     13608194.54
       1983530.8     13608164.54       1983760.8     13608304.54
       1983950.8     13608314.54      1984125.08     13608456.36
       1984420.8     13608524.54       1984540.8     13608624.54
       1984850.8     13608624.54       1984890.8     13608664.54
       1985130.8     13608664.54       1985170.8     13608694.54
       1985360.8     13608664.54       1985710.8     13608704.54
       1985930.8     13608604.54       1986040.8     13608414.54
       1986070.8     13608384.54       1986120.8     13608394.54
       1986350.8     13608164.54       1986490.8     13608164.54
       1986860.8     13608064.54      1987131.68     13608074.54
      1987267.09     13607959.49      1987327.86     13607869.21
      1987374.73     13607851.42       1987790.8     13607894.54
       1988080.8     13607594.54       1988380.8     13607354.54

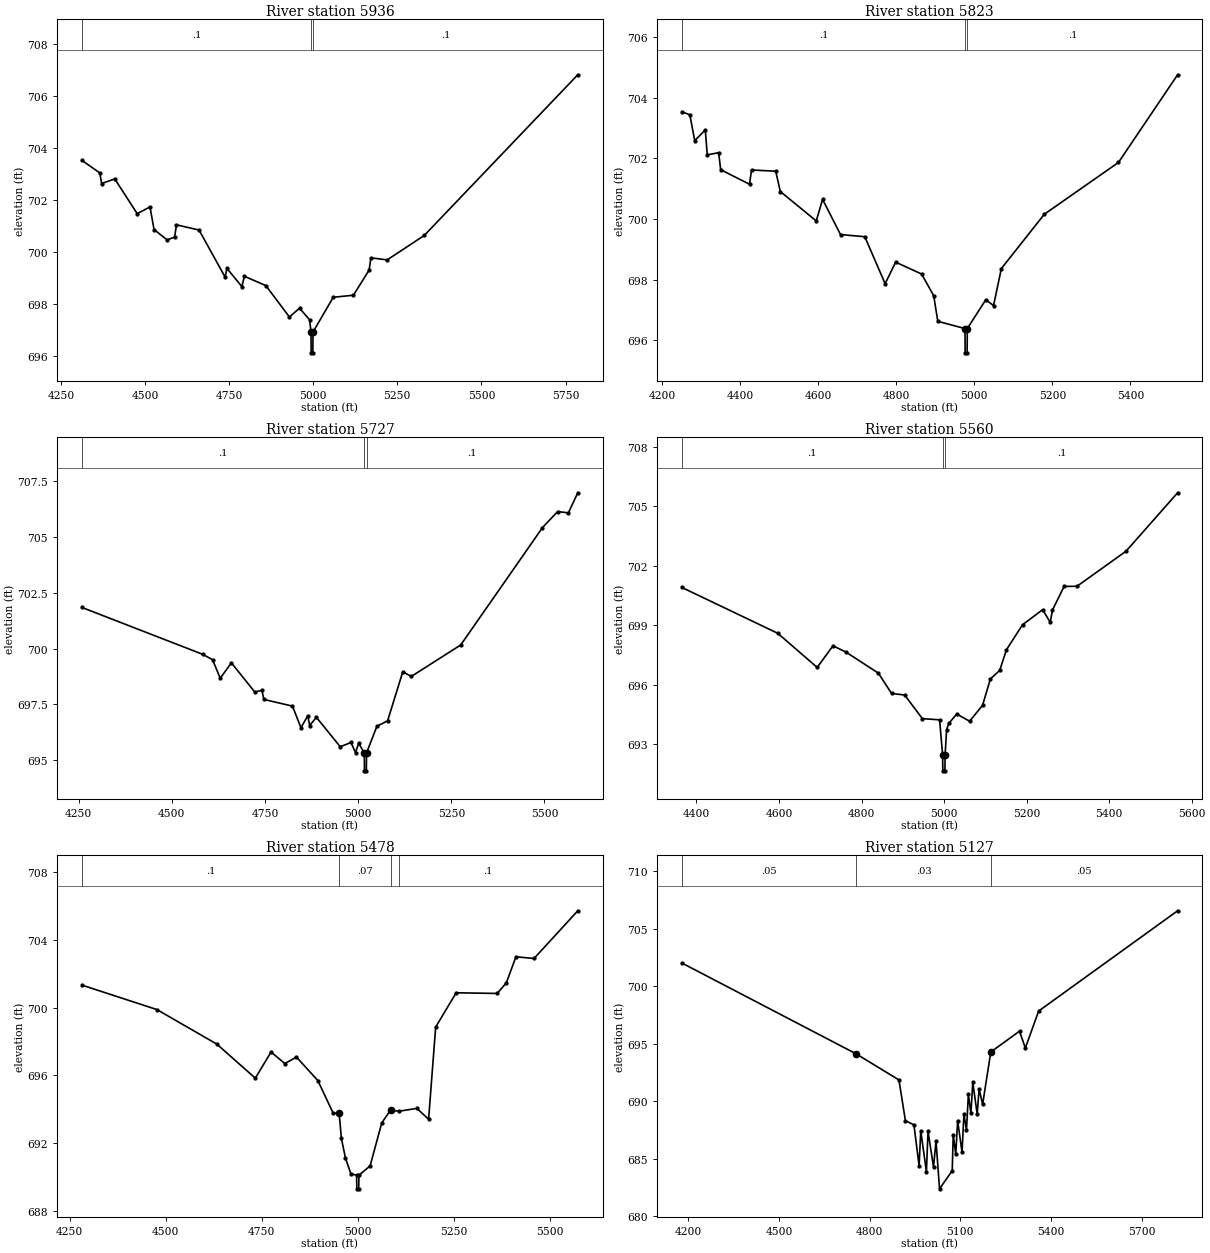
Type RM Length L Ch R = 1 ,5936    ,113,113,113
BEGIN DESCRIPTION:
UNT 055 in HW 14.0
END DESCRIPTION:
XS GIS Cut Line= 3
      1983175.01     13608824.98       1983409.9     13608363.71
      1983353.51     13607409.41
#Sta/Elev= 30
  4312.9  703.53  4365.7  703.05  4371.3  702.64  4410.2  702.82  4476.9  701.48
  4514.9  701.74    4527  700.87  4565.8  700.47  4588.1  700.58  4593.7  701.05
  4660.8  700.85  4738.1  699.04  4743.8  699.37  4788.2  698.67  4795.4  699.07
  4859.3  698.71  4929.4   697.5  4959.5  697.84  4989.5  697.39  4993.5  696.92
    4994  696.12    4999  696.12  4999.5  696.92  5059.6  698.26  5119.7  698.34
  5166.4  699.31  5171.4  699.78  5219.9   699.7  5330.1  700.64  5786.5  706.83
#Mann= 3 ,-1 , 0
  4312.9      .1       0  4993.5     .07       0  4999.5      .1       0
Bank Sta=4993.5,4999.5
XS Rating Curve= 0 ,0
Exp/Cntr=0.3,0.1

Type RM Length L Ch R = 1 ,5823    ,96,96,96
BEGIN DESCRIPTION:
UNT 055 in HW 16.0
END DESCRIPTION:
XS GIS Cut Line= 3
      1983303.71     13608886.71      1983499.74     13608178.47
      1983501.63     13607643.64
#Sta/Elev= 30
  4251.2  703.54  4271.7  703.44  4284.1  702.59  4311.2  702.94  4316.3  702.12
  4345.5  702.19  4350.6  701.63  4424.5  701.15  4429.6  701.62  4491.6  701.58
  4503.4  700.91  4595.4  699.94  4611.6  700.65  4657.6  699.49  4719.7  699.42
  4771.8  697.87  4798.7  698.58  4865.2  698.19  4896.3  697.47  4906.7  696.63
  4976.3  696.39  4976.8  695.59  4981.8  695.59  4982.3  696.39  5029.5  697.34
  5049.5  697.15  5069.5  698.37  5179.5  700.16  5369.5  701.87  5520.9  704.76
#Mann= 3 ,-1 , 0
  4251.2      .1       0  4976.3     .07       0  4982.3      .1       0
Bank Sta=4976.3,4982.3
XS Rating Curve= 0 ,0
Exp/Cntr=0.3,0.1

Type RM Length L Ch R = 1 ,5727    ,167,167,167
BEGIN DESCRIPTION:
UNT 055 in HW 15.0
END DESCRIPTION:
XS GIS Cut Line= 3
       1983400.5     13608914.49        1983588.      13608174.9
      1983820.62     13607657.58
#Sta/Elev= 30
  4259.1  701.84  4583.1  699.74  4609.3   699.5    4630  698.67  4659.9  699.36
  4722.8  698.05  4741.8  698.13    4747  697.72  4823.8  697.42  4846.6  696.45
  4864.8  696.99  4869.9  696.55  4887.9  696.92  4951.9   695.6  4980.7  695.79
  4992.9  695.34  5001.4  695.76  5016.5  695.32    5017  694.52    5022  694.52
  5022.5  695.32  5050.4  696.52    5079  696.76  5119.8  698.96  5142.6  698.75
  5275.2  700.16  5494.6  705.42  5535.4  706.14  5564.1  706.08  5589.3  706.98
#Mann= 3 ,-1 , 0
  4259.1      .1       0  5016.5     .07       0  5022.5      .1       0
Bank Sta=5016.5,5022.5
XS Rating Curve= 0 ,0
Exp/Cntr=0.3,0.1

Type RM Length L Ch R = 1 ,5560    ,82,82,82
BEGIN DESCRIPTION:
Mapping XS f8634359
END DESCRIPTION:
XS GIS Cut Line= 3
      1983508.01     13608874.35        1983712.     13608294.91
      1983874.75     13607730.71
#Sta/Elev= 30
  4364.5   700.9    4597  698.59  4692.5  696.87  4730.7  697.96  4761.7  697.65
  4840.9  696.58  4872.7  695.56  4904.5  695.48  4947.4  694.29  4989.1  694.23
  4996.5  692.46    4997  691.66    5002  691.66  5002.5  692.46  5006.2  693.74
  5011.4  694.05  5030.7  694.52    5062  694.16  5093.2  694.96  5112.3  696.29
  5134.8  696.72  5151.2  697.76  5190.1  699.02  5238.9  699.78  5257.4  699.14
  5262.6  699.76  5290.9  700.95  5322.2  700.96  5441.2  702.73    5566  705.67
#Mann= 3 ,-1 , 0
  4364.5      .1       0  4996.5     .07       0  5002.5      .1       0
Bank Sta=4996.5,5002.5
XS Rating Curve= 0 ,0
Exp/Cntr=0.3,0.1

Type RM Length L Ch R = 1 ,5478    ,351,351,351
BEGIN DESCRIPTION:
Mapping XS b8873c67
END DESCRIPTION:
XS GIS Cut Line= 2
      1983538.15     13608977.66      1983985.47     13607768.34
#Sta/Elev= 30
  4282.3  701.32  4477.1  699.88  4632.6  697.85    4733  695.84    4774  697.38
  4809.7   696.7  4840.1  697.08  4895.6   695.7  4935.5  693.78  4951.1  693.76
  4956.9  692.29  4967.5  691.13  4981.5  690.21  4996.5  690.12    4997  689.32
    5002  689.32  5002.5  690.12  5031.5  690.67    5062  693.21  5084.8  693.96
  5106.1  693.89  5153.2  694.06  5183.7  693.42  5202.1  698.85  5255.4  700.87
    5362  700.83  5385.8  701.45  5410.9  702.99    5458  702.89  5571.7   705.7
#Mann= 4 ,-1 , 0
  4282.3      .1       0  4951.1     .07       0  5084.8      .1       0
  5106.1      .1       0
Bank Sta=4951.1,5084.8
XS Rating Curve= 0 ,0
Exp/Cntr=0.3,0.1

Type RM Length L Ch R = 1 ,5127    ,40,40,40
BEGIN DESCRIPTION:
Mapping XS 2a3f99b9
END DESCRIPTION:
XS GIS Cut Line= 6
       1983566.8     13609050.56       1984066.8     13608490.66
      1984100.66     13608407.33      1984074.62     13608360.45
      1983993.89     13608300.55      1984199.36     13607689.33
#Sta/Elev= 30
  4178.9  702.03  4755.2  694.13  4896.9  691.86  4918.2  688.32  4946.5  687.95
  4963.6  684.38    4969  687.44  4987.7  683.88  4993.1  687.39  5011.2  684.29
  5019.5  686.54  5031.1  682.39  5073.1  683.97  5076.4  687.11  5084.8  685.38
    5091  688.33  5105.6  685.56  5111.8  688.92  5120.2   687.5  5126.5   690.6
  5134.9  688.96  5141.1  691.65  5155.7  688.88  5161.9  691.07  5173.7  689.74
  5200.6  694.29  5295.6   696.1  5314.9  694.63  5358.9  697.85  5818.5  706.57
#Mann= 3 , 0 , 0
  4178.9     .05       0  4755.2     .03       0  5200.6     .05       0
Bank Sta=4755.2,5200.6
XS Rating Curve= 0 ,0
Exp/Cntr=0.3,0.1

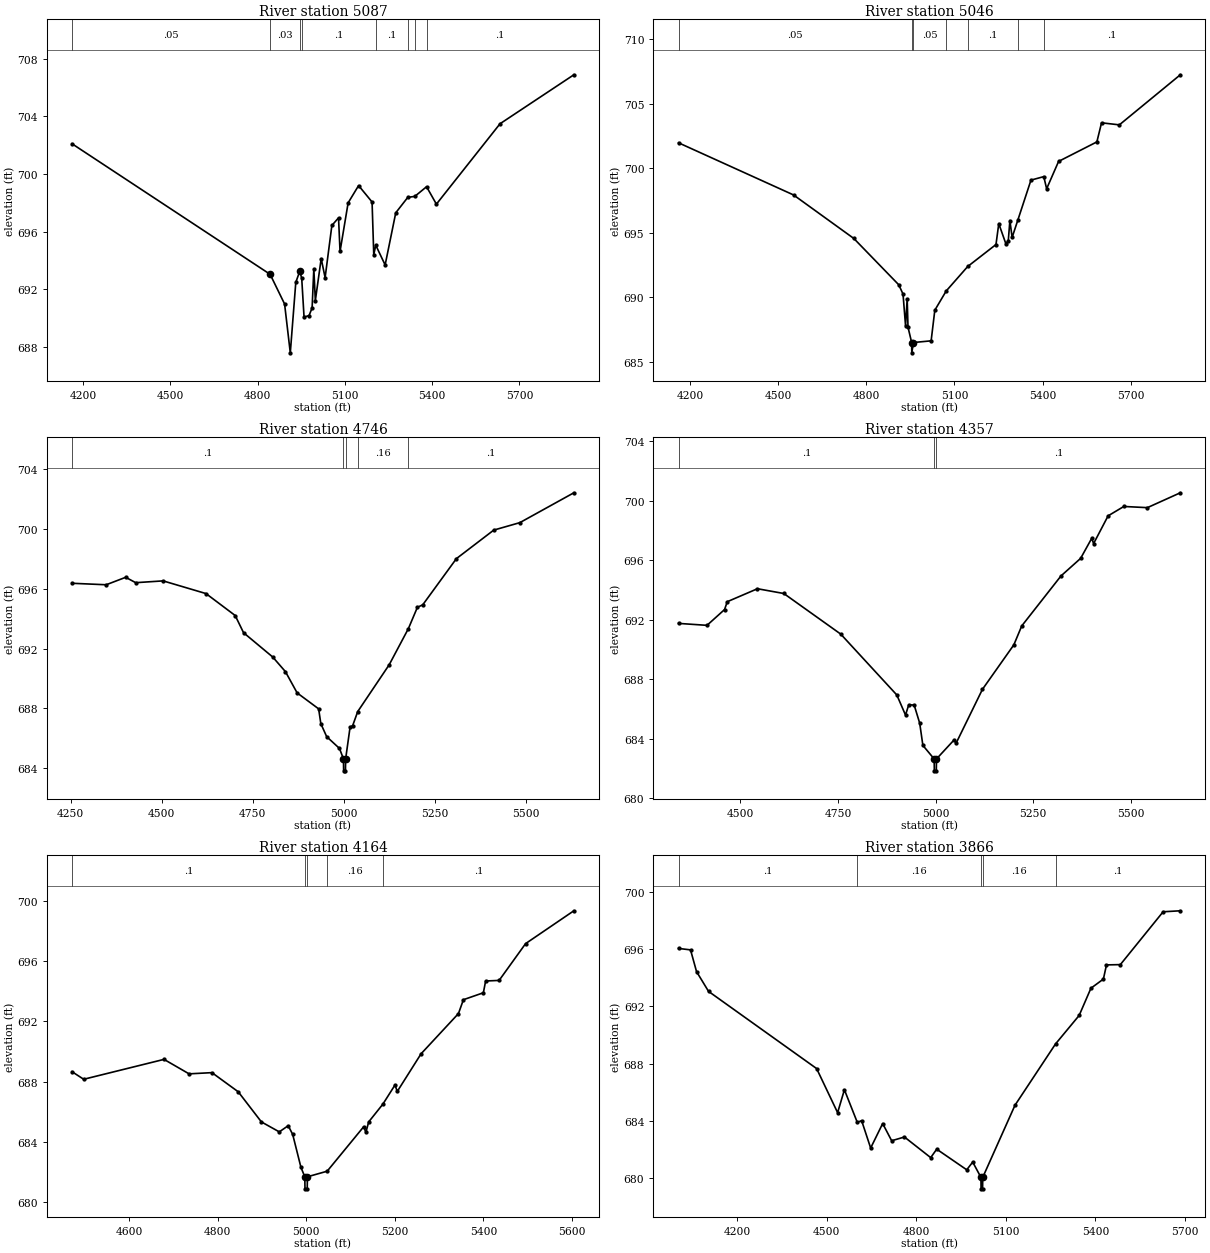
Type RM Length L Ch R = 1 ,5087    ,41,41,41
BEGIN DESCRIPTION:
UNT 055 in HW 13.0
END DESCRIPTION:
XS GIS Cut Line= 6
      1983574.97     13609075.03      1984053.78     13608602.64
      1984108.47     13608498.47      1984113.68     13608321.39
      1984038.16     13608277.12      1984272.07     13607658.67
#Sta/Elev= 30
  4162.4  702.09  4843.2  693.03  4892.9  690.97  4912.5  687.58  4931.4  692.47
  4945.3  693.26  4951.8  692.74  4959.8  690.06  4977.1  690.17  4987.5   690.7
  4993.4  693.41  4998.6  691.21  5018.7  694.12  5032.2   692.8  5055.4  696.42
  5078.3  696.95  5083.5  694.62  5111.3  697.99  5147.3  699.19  5193.6  698.05
  5199.4   694.4  5206.3  695.05  5238.5  693.68    5275   697.3  5316.3  698.37
  5340.5  698.44  5380.9  699.11  5414.7   697.9  5633.4  703.48  5887.2  706.88
#Mann= 8 ,-1 , 0
  4162.4     .05       0  4843.2     .03       0  4945.3     .05       0
  4951.8      .1       0  5206.3      .1       0  5316.3      .1       0
  5340.5     .16       0  5380.9      .1       0
Bank Sta=4843.2,4945.3
XS Rating Curve= 0 ,0
Exp/Cntr=0.3,0.1

Type RM Length L Ch R = 1 ,5046    ,300,300,300
BEGIN DESCRIPTION:
UNT 055 in HW 12.0
END DESCRIPTION:
XS GIS Cut Line= 6
      1983613.68     13609087.02      1984105.87     13608600.03
      1984176.18     13608417.74       1984189.2     13608339.62
      1984098.05     13608256.28      1984313.87     13607679.04
#Sta/Elev= 30
  4161.3  701.97  4552.6  697.93  4757.6  694.56  4910.5  690.97    4925  690.25
  4933.6  687.79  4939.1  689.89  4941.9  687.69  4954.3   686.5  4954.8   685.7
  4960.3   686.5  5020.6  686.63  5033.1     689  5071.8  690.49  5145.1  692.39
  5241.2  694.09  5250.7  695.71  5274.8  694.15  5283.1   694.4  5288.5  695.95
  5296.1  694.64  5315.8     696  5360.2  699.08  5403.8  699.35  5413.5  698.41
  5454.2  700.53  5584.4  702.04  5600.3  703.52  5660.9  703.36  5868.3  707.24
#Mann= 7 ,-1 , 0
  4161.3     .05       0  4954.3     .03       0  4960.3     .05       0
  5071.8     .16       0  5145.1      .1       0  5315.8     .16       0
  5403.8      .1       0
Bank Sta=4954.3,4960.3
XS Rating Curve= 0 ,0
Exp/Cntr=0.3,0.1

Type RM Length L Ch R = 1 ,4746    ,389,389,389
BEGIN DESCRIPTION:
UNT 055 in HW 11.0
END DESCRIPTION:
XS GIS Cut Line= 3
      1984066.78     13609186.01       1984439.2      13608519.3
      1984574.61     13607920.39
#Sta/Elev= 30
  4253.7  696.38  4347.3  696.28  4400.9  696.78  4428.4  696.42  4503.7  696.54
  4621.4  695.69  4701.6  694.22  4724.5  693.07  4804.7  691.44  4839.6  690.46
  4871.6  689.04  4930.7  687.97  4936.7  686.98  4952.7  686.11  4987.9  685.32
  4998.8  684.62  4999.3  683.82  5004.3  683.82  5004.8  684.62    5017  686.75
    5024  686.84    5038  687.79  5124.3  690.92  5177.2  693.35  5201.8  694.77
  5216.6  694.94  5308.9  698.03  5411.4  699.94  5483.1  700.44  5631.4  702.44
#Mann= 5 ,-1 , 0
  4253.7      .1       0  4998.8     .03       0  5004.8      .1       0
    5038     .16       0  5177.2      .1       0
Bank Sta=4998.8,5004.8
XS Rating Curve= 0 ,0
Exp/Cntr=0.3,0.1

Type RM Length L Ch R = 1 ,4357    ,193,193,193
BEGIN DESCRIPTION:
UNT 055 in HW 10.0
END DESCRIPTION:
XS GIS Cut Line= 3
      1984488.68     13609217.22      1984772.53      13608639.1
      1984845.45      13608001.1
#Sta/Elev= 30
  4341.3  691.76  4414.3  691.63  4459.2  692.69  4466.3  693.22  4543.6  694.09
  4611.1  693.77  4757.1  691.04  4900.8  686.95  4923.1   685.6  4931.4  686.29
  4945.3  686.27  4959.5  685.05  4967.6  683.56  4996.5  682.65    4997  681.85
    5002  681.85  5002.5  682.65    5048  683.94    5053  683.72  5120.3  687.33
  5200.8  690.32    5221  691.59  5321.6  694.95  5371.9  696.13  5400.2  697.47
  5405.3  697.13  5442.4  698.99  5482.7  699.62    5543  699.54  5627.5  700.54
#Mann= 3 ,-1 , 0
  4341.3      .1       0  4996.5     .07       0  5002.5      .1       0
Bank Sta=4996.5,5002.5
XS Rating Curve= 0 ,0
Exp/Cntr=0.3,0.1

Type RM Length L Ch R = 1 ,4164    ,298,298,298
BEGIN DESCRIPTION:
Mapping XS ffce10c8
END DESCRIPTION:
XS GIS Cut Line= 4
      1984836.12     13609180.37      1984925.11      13608848.3
      1984988.05     13608405.59      1984918.69     13608069.63
#Sta/Elev= 30
  4470.6  688.65  4496.9  688.15  4678.4  689.47    4735  688.51  4786.7  688.59
  4846.1  687.32  4898.5  685.32  4938.9  684.66  4959.1  685.07  4969.2  684.49
  4987.8  682.31  4996.5  681.68    4997  680.88    5002  680.88  5002.5  681.68
  5047.1  682.05  5129.6     685  5134.6  684.63  5140.9  685.32    5173   686.5
  5200.4  687.77  5205.5  687.34  5259.3  689.84  5343.8  692.51    5355  693.43
  5400.1  693.89  5405.2  694.67  5435.7  694.71  5495.5  697.15  5604.6  699.33
#Mann= 5 ,-1 , 0
  4470.6      .1       0  4996.5     .07       0  5002.5      .1       0
  5047.1     .16       0    5173      .1       0
Bank Sta=4996.5,5002.5
XS Rating Curve= 0 ,0
Exp/Cntr=0.3,0.1

Type RM Length L Ch R = 1 ,3866    ,431,431,431
BEGIN DESCRIPTION:
UNT 055 in HW 9.0
END DESCRIPTION:
XS GIS Cut Line= 3
        1985125.       13609675.        1985225.       13608675.
      1985032.63     13608028.08
#Sta/Elev= 30
  4004.6  696.04  4044.8  695.94  4064.9  694.42  4105.1  693.04  4466.9  687.65
  4537.2  684.57  4559.9  686.17  4602.9   683.9  4617.6  684.01  4647.8   682.1
    4688  683.81  4718.1  682.61  4760.9  682.87  4848.8  681.43  4868.9  682.02
  4969.4  680.58  4989.5  681.12    5017  680.05  5017.5  679.25  5022.5  679.25
    5023  680.05    5131  685.09  5266.7  689.37  5345.8  691.36  5385.2  693.26
  5426.9   693.9  5437.3  694.89  5483.7  694.91  5626.9   698.6  5684.5  698.67
#Mann= 5 ,-1 , 0
  4004.6      .1       0  4602.9     .16       0    5017     .07       0
    5023     .16       0  5266.7      .1       0
Bank Sta=5017,5023
XS Rating Curve= 0 ,0
Exp/Cntr=0.3,0.1

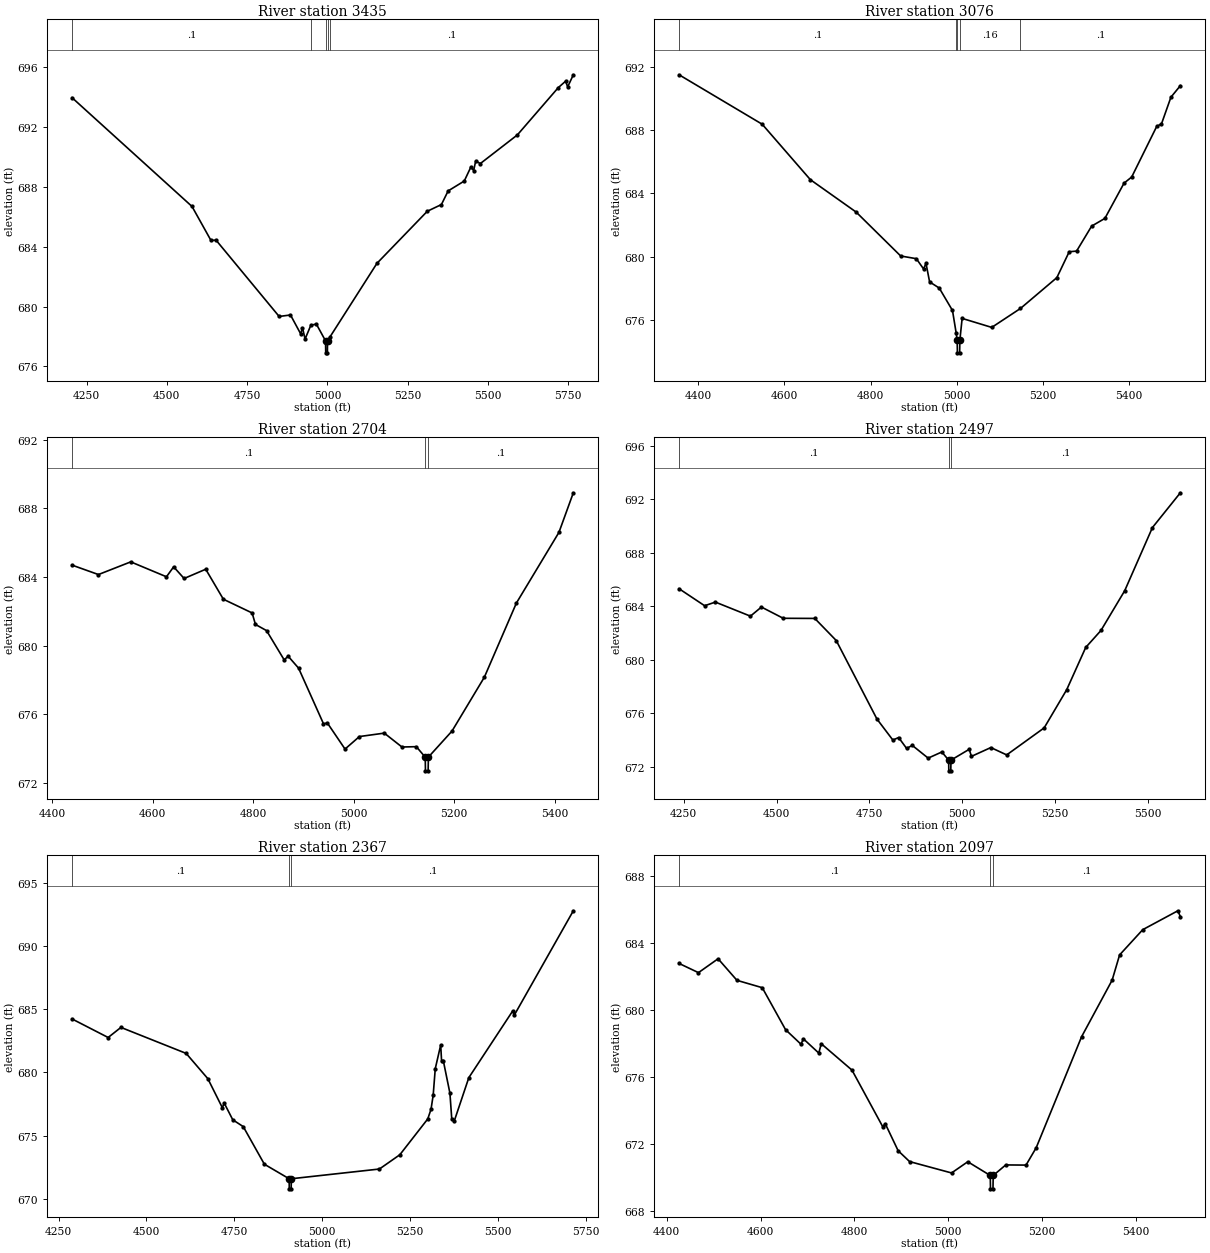
Type RM Length L Ch R = 1 ,3435    ,359,359,359
BEGIN DESCRIPTION:
UNT 055 in HW 8.0
END DESCRIPTION:
XS GIS Cut Line= 3
      1986024.98     13609374.96        1985625.       13608675.
      1985179.83     13608065.56
#Sta/Elev= 30
  4204.8  693.96  4578.4  686.69  4637.4  684.42  4653.2  684.44  4849.7  679.34
    4885  679.44  4916.7  678.18  4922.4  678.59  4930.4  677.83  4948.5  678.76
  4965.6  678.83  4994.2  677.71  4994.7  676.91  4999.9  676.91  5000.4  677.71
  5007.9  677.97  5154.2  682.89    5311  686.37    5355  686.82  5375.9  687.73
  5426.1  688.39    5447  689.34  5455.4  689.09  5461.6  689.72  5476.3  689.56
  5591.4  691.47  5718.8  694.63  5741.6  695.06  5748.1  694.68  5765.7  695.49
#Mann= 5 ,-1 , 0
  4204.8      .1       0  4948.5     .16       0  4994.2     .07       0
  5000.4     .16       0  5007.9      .1       0
Bank Sta=4994.2,5000.4
XS Rating Curve= 0 ,0
Exp/Cntr=0.3,0.1

Type RM Length L Ch R = 1 ,3076    ,372,372,372
BEGIN DESCRIPTION:
UNT 055 in HW 7.0
END DESCRIPTION:
XS GIS Cut Line= 3
      1986225.01     13609175.02        1985925.       13608575.
      1985724.99     13608124.98
#Sta/Elev= 30
  4355.5  691.51  4548.4  688.38  4660.2  684.87  4766.4  682.82  4869.8  680.04
  4906.1  679.87  4922.9  679.22  4928.5  679.58  4936.9   678.4  4959.3  678.01
    4990  676.59  4998.4  675.19  5000.9  674.71  5001.4  673.91  5006.6  673.91
  5007.1  674.71  5012.4  676.09  5081.1  675.52  5147.8  676.72  5232.2  678.67
  5260.9  680.31    5278  680.35  5312.9  681.93  5343.7  682.42  5388.1  684.65
  5405.9  685.04  5464.1  688.25    5475   688.4  5496.9  690.09  5518.8  690.82
#Mann= 5 ,-1 , 0
  4355.5      .1       0  4998.4     .16       0  5000.9     .07       0
  5007.1     .16       0  5147.8      .1       0
Bank Sta=5000.9,5007.1
XS Rating Curve= 0 ,0
Exp/Cntr=0.3,0.1

Type RM Length L Ch R = 1 ,2704    ,207,207,207
BEGIN DESCRIPTION:
Mapping XS 9d8f5f4d
END DESCRIPTION:
XS GIS Cut Line= 2
      1986584.56     13608720.07      1985819.98     13608080.04
#Sta/Elev= 30
  4439.7  684.69  4492.2  684.14  4556.5  684.88  4627.5  684.01  4641.8  684.59
  4662.6  683.91  4705.6  684.45  4740.7   682.7  4797.9   681.9  4804.5  681.23
  4826.6  680.87  4861.7  679.16  4869.5  679.38  4890.3  678.68  4939.8  675.44
  4947.6  675.48  4982.7  673.96  5011.3  674.69  5060.8  674.89  5095.9  674.08
  5124.5   674.1  5142.2  673.49  5142.7  672.69    5148  672.69  5148.5  673.49
  5195.5  675.01  5259.8  678.15  5323.6  682.48  5408.2   686.6  5436.8  688.91
#Mann= 3 ,-1 , 0
  4439.7      .1       0  5142.2     .07       0  5148.5      .1       0
Bank Sta=5142.2,5148.5
XS Rating Curve= 0 ,0
Exp/Cntr=0.3,0.1

Type RM Length L Ch R = 1 ,2497    ,130,130,130
BEGIN DESCRIPTION:
UNT 055 in HW 6.0
END DESCRIPTION:
XS GIS Cut Line= 4
      1986761.62     13608803.39        1986463.     13608324.21
      1986051.63     13608076.53      1985764.37     13607969.93
#Sta/Elev= 30
  4237.3   685.3  4306.1  684.03  4335.2   684.3  4429.6  683.25  4459.3  683.93
  4518.1  683.09  4603.1  683.08  4660.9  681.43  4770.7  675.56  4813.6  673.99
  4829.1  674.18  4850.5  673.37    4866  673.59  4908.7  672.64  4945.6   673.1
  4963.9  672.49  4964.4  671.69  4969.7  671.69  4970.2  672.49  5019.4   673.3
  5025.3  672.77  5077.7  673.43  5120.4  672.88  5221.4   674.9  5282.1  677.75
  5333.4  680.91  5374.5  682.18  5438.5  685.15  5513.2  689.87  5588.5  692.47
#Mann= 3 ,-1 , 0
  4237.3      .1       0  4963.9     .07       0  4970.2      .1       0
Bank Sta=4963.9,4970.2
XS Rating Curve= 0 ,0
Exp/Cntr=0.3,0.1

Type RM Length L Ch R = 1 ,2367    ,270,270,270
BEGIN DESCRIPTION:
Mapping XS 85e87515
END DESCRIPTION:
XS GIS Cut Line= 4
      1986758.15     13608744.37      1986570.64     13608268.65
      1986108.83      13607987.4      1985749.48     13607883.19
#Sta/Elev= 30
  4288.5  684.24  4391.2  682.77  4427.6  683.57  4613.2  681.51  4674.8  679.51
  4716.1  677.21  4721.5  677.57  4745.8  676.25  4775.6  675.71  4835.7  672.73
  4906.1  671.58  4906.6  670.78  4911.9  670.78  4912.4  671.58    5163  672.35
  5221.1  673.48  5300.6  676.32  5309.9  677.09    5316   678.2  5321.9   680.3
  5337.4  682.18  5339.9  680.89  5345.1  680.89  5363.6  678.36  5368.8  676.33
  5375.8  676.14  5417.4  679.59  5541.9  684.86  5547.1  684.56  5714.7  692.81
#Mann= 3 ,-1 , 0
  4288.5      .1       0  4906.1     .07       0  4912.4      .1       0
Bank Sta=4906.1,4912.4
XS Rating Curve= 0 ,0
Exp/Cntr=0.3,0.1

Type RM Length L Ch R = 1 ,2097    ,191,191,191
BEGIN DESCRIPTION:
UNT 055 in HW 5.0
END DESCRIPTION:
XS GIS Cut Line= 3
      1986817.16     13608664.47      1986647.03     13608108.93
      1986407.43      13607685.3
#Sta/Elev= 30
  4426.5  682.79  4467.8  682.24  4509.6  683.07  4549.8  681.78  4603.7  681.34
  4653.3  678.83  4686.1  677.96  4691.3  678.28  4724.1  677.43  4729.3  677.99
  4794.8  676.41  4860.4  673.02  4865.6  673.21  4893.1  671.59  4917.5  670.94
  5006.9  670.26  5041.4  670.93  5089.3  670.11  5089.8  669.31  5095.1  669.31
  5095.6  670.11  5122.3  670.74  5165.5  670.73  5187.2  671.77  5283.9  678.41
  5348.9  681.79  5364.8   683.3  5414.1  684.81  5488.9  685.94  5494.2  685.59
#Mann= 3 ,-1 , 0
  4426.5      .1       0  5089.3     .07       0  5095.6      .1       0
Bank Sta=5089.3,5095.6
XS Rating Curve= 0 ,0
Exp/Cntr=0.3,0.1

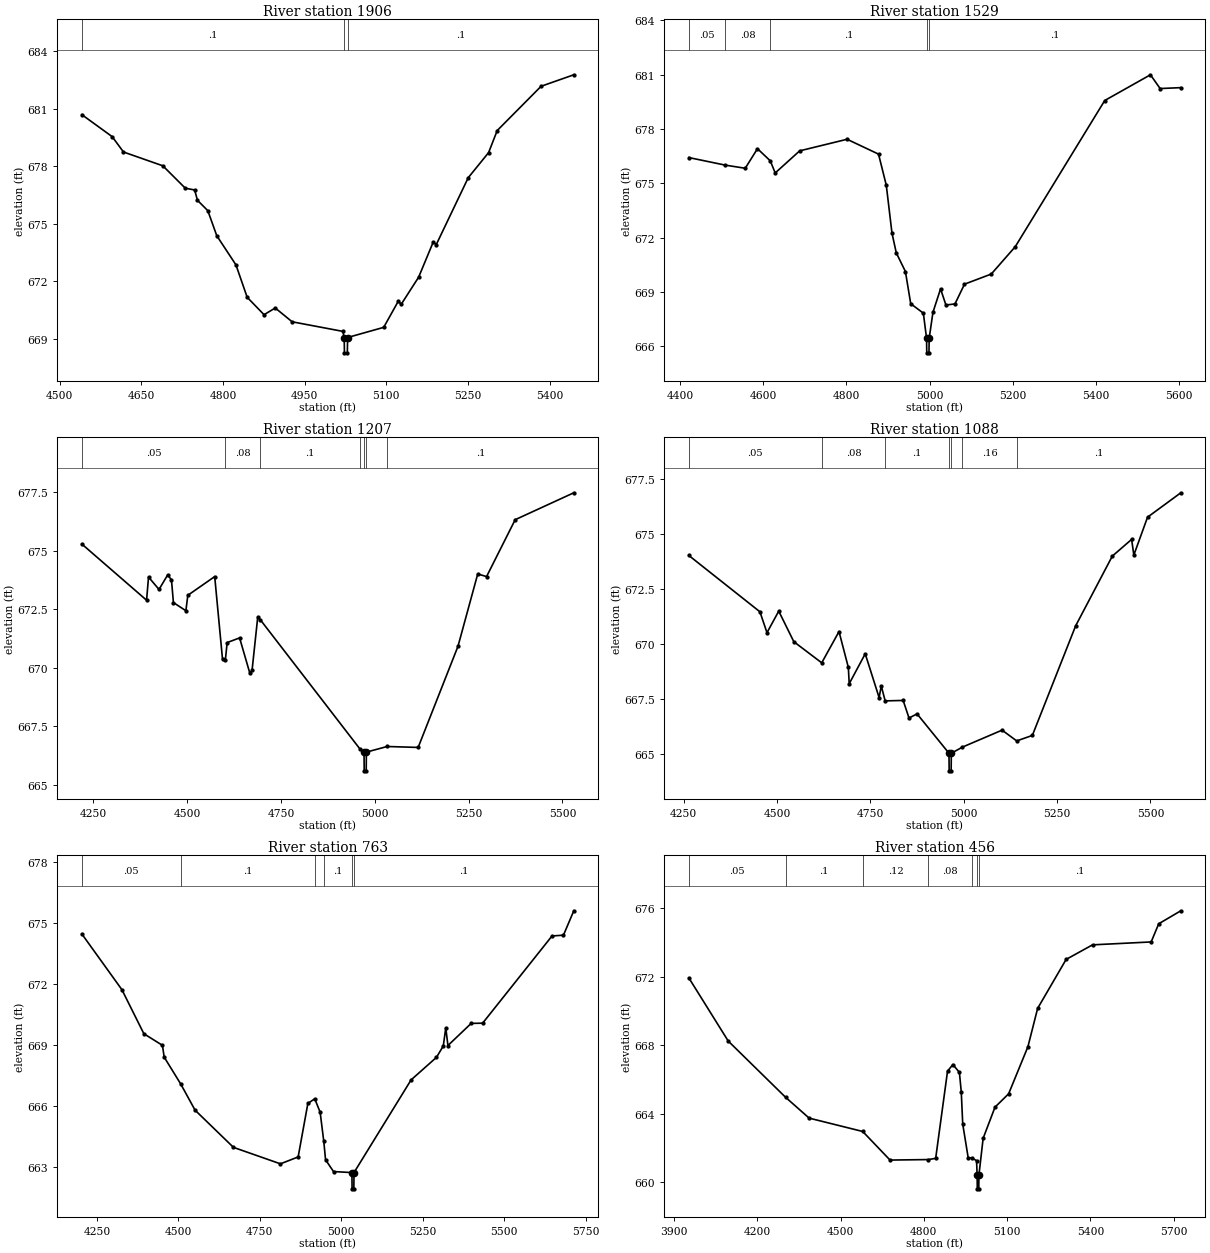
Type RM Length L Ch R = 1 ,1906    ,377,377,377
BEGIN DESCRIPTION:
UNT 055 in HW 4.0
END DESCRIPTION:
XS GIS Cut Line= 3
      1986942.17     13608529.08        1986825.       13608075.
      1986692.17     13607661.04
#Sta/Elev= 30
  4540.9   680.7  4596.7  679.55  4617.4  678.75  4689.7  678.03    4731  676.86
  4748.1  676.77  4753.3  676.23  4772.3  675.69  4788.8  674.38    4824  672.86
  4844.6  671.17  4875.6  670.26  4896.2  670.61  4927.2  669.89  5020.4  669.39
  5022.8  669.07  5023.3  668.27  5028.6  668.27  5029.1  669.07  5095.4   669.6
  5122.3  670.97  5127.5   670.8  5159.6  672.22  5186.5  674.06  5191.8  673.91
  5250.7  677.41  5288.1  678.72  5303.9  679.87  5384.5  682.18  5444.6  682.78
#Mann= 3 ,-1 , 0
  4540.9      .1       0  5022.8     .07       0  5029.1      .1       0
Bank Sta=5022.8,5029.1
XS Rating Curve= 0 ,0
Exp/Cntr=0.3,0.1

Type RM Length L Ch R = 1 ,1529    ,322,322,322
BEGIN DESCRIPTION:
UNT 055 in HW 3.0
END DESCRIPTION:
XS GIS Cut Line= 3
       1987400.5     13608577.68        1987175.       13608025.
      1986938.67     13607487.36
#Sta/Elev= 30
  4420.6  676.42  4508.8     676  4556.4  675.83  4585.8  676.91  4616.6  676.24
  4628.5  675.57  4687.4  676.79  4801.5  677.43  4877.2  676.61  4895.9  674.89
  4909.5  672.26  4919.9  671.16  4941.9  670.13  4954.7  668.35  4985.1  667.83
  4992.8  666.44  4993.3  665.64  4998.6  665.64  4999.1  666.44  5008.2  667.88
  5026.5  669.17  5039.4  668.28  5061.2  668.34  5084.1  669.43  5148.6  669.99
  5206.3   671.5  5421.7  679.57  5531.7  680.99    5555  680.23  5604.8  680.28
#Mann= 5 ,-1 , 0
  4420.6     .05       0  4508.8     .08       0  4616.6      .1       0
  4992.8     .07       0  4999.1      .1       0
Bank Sta=4992.8,4999.1
XS Rating Curve= 0 ,0
Exp/Cntr=0.3,0.1

Type RM Length L Ch R = 1 ,1207    ,119,119,119
BEGIN DESCRIPTION:
Mapping XS c501173a
END DESCRIPTION:
XS GIS Cut Line= 4
      1987709.53     13608574.22      1987574.11     13608119.35
      1987376.19     13607786.01      1987199.55     13607373.84
#Sta/Elev= 30
  4219.6  675.28  4392.1  672.88  4397.3  673.87  4425.2  673.34  4448.3  673.96
  4458.4  673.75  4463.6  672.78  4496.8  672.43    4502  673.09  4573.6  673.89
  4594.4  670.36    4602  670.33  4606.8  671.07  4639.9  671.27  4667.4  669.75
  4673.1  669.88  4688.3  672.17  4695.4  672.04  4960.7  666.52  4971.4  666.39
  4971.9  665.59  4977.2  665.59  4977.7  666.39  5033.1  666.63  5115.6  666.59
  5221.7  670.91  5274.3     674  5297.9  673.89  5374.1  676.32  5530.3  677.47
#Mann= 7 ,-1 , 0
  4219.6     .05       0    4602     .08       0  4695.4      .1       0
  4960.7     .16       0  4971.4     .07       0  4977.7     .16       0
  5033.1      .1       0
Bank Sta=4971.4,4977.7
XS Rating Curve= 0 ,0
Exp/Cntr=0.3,0.1

Type RM Length L Ch R = 1 ,1088    ,325,325,325
BEGIN DESCRIPTION:
Mapping XS 90fc1f6f
END DESCRIPTION:
XS GIS Cut Line= 4
      1987747.72     13608563.77      1987692.17     13608140.18
      1987372.72     13607595.04      1987289.93     13607350.12
#Sta/Elev= 30
  4263.9  674.02  4454.3  671.46  4473.2  670.51  4504.7  671.49  4545.1   670.1
  4619.8  669.14  4666.1  670.56  4691.1  668.93  4693.4  668.19  4736.3  669.55
  4773.5  667.56  4779.3  668.09  4789.7  667.41  4837.9  667.43  4853.6  666.63
  4875.1  666.82  4960.6  665.03  4961.1  664.23  4966.4  664.23  4966.9  665.03
  4996.8  665.31  5102.8  666.08    5142  665.59  5183.9  665.84  5299.8  670.82
    5398  673.99  5449.7  674.75  5455.7  674.04  5492.4  675.76  5581.5  676.87
#Mann= 7 ,-1 , 0
  4263.9     .05       0  4619.8     .08       0  4789.7      .1       0
  4960.6     .07       0  4966.9      .1       0  4996.8     .16       0
    5142      .1       0
Bank Sta=4960.6,4966.9
XS Rating Curve= 0 ,0
Exp/Cntr=0.3,0.1

Type RM Length L Ch R = 1 ,763     ,307,307,307
BEGIN DESCRIPTION:
UNT 055 in HW 2.0
END DESCRIPTION:
XS GIS Cut Line= 4
      1987748.77     13608593.29      1987925.85     13608082.89
      1987785.22     13607723.51      1987405.03     13607280.82
#Sta/Elev= 30
  4203.8  674.47  4326.7  671.73  4394.2  669.56  4451.2  668.99  4456.5  668.41
  4507.2  667.09  4551.3   665.8  4669.1  663.97  4813.3  663.16  4867.6   663.5
  4897.4  666.13  4918.5  666.36  4935.1   665.7  4946.3  664.26  4951.7  663.36
  4976.1  662.78  5032.6  662.73  5033.1  661.93  5038.5  661.93    5039  662.73
  5214.2  667.29  5292.1   668.4    5313  668.96  5320.6  669.85  5327.2  668.98
  5398.6  670.07  5433.7  670.08  5646.6  674.37  5681.7  674.41  5713.5  675.61
#Mann= 6 ,-1 , 0
  4203.8     .05       0  4507.2      .1       0  4918.5     .08       0
  4946.3      .1       0  5032.6     .07       0    5039      .1       0
Bank Sta=5032.6,5039
XS Rating Curve= 0 ,0
Exp/Cntr=0.3,0.1

Type RM Length L Ch R = 1 ,456     ,0,0,0
BEGIN DESCRIPTION:
UNT 055 in HW 1.0
END DESCRIPTION:
XS GIS Cut Line= 4
      1987837.31     13608588.09      1988160.22     13607937.06
      1987993.56     13607494.35      1987503.99     13607197.48
#Sta/Elev= 30
  3953.5  671.92  4095.5  668.23  4301.8  664.95  4386.9  663.73  4579.9  662.95
  4678.3  661.28  4816.5  661.31  4842.7  661.38  4885.4  666.47  4904.7  666.86
  4928.2   666.4  4934.9  665.26  4940.2  663.38  4959.8  661.42  4972.7   661.4
    4990  661.25  4992.1   660.4  4992.6   659.6    4998   659.6  4998.5   660.4
  5013.7  662.55  5056.4  664.37  5105.5  665.15    5175   667.9    5210  670.14
  5312.7     673  5407.7  673.85    5619  674.02  5646.2  675.08  5725.8  675.84
#Mann= 7 ,-1 , 0
  3953.5     .05       0  4301.8      .1       0  4579.9     .12       0
  4816.5     .08       0  4972.7      .1       0  4992.1     .07       0
  4998.5      .1       0
Bank Sta=4992.1,4998.5
XS Rating Curve= 0 ,0
Exp/Cntr=0.3,0.1
LCMann Table=0

Chan Stop Cuts=-1
Use User Specified Reach Order=0
Composite Channel Slope=5