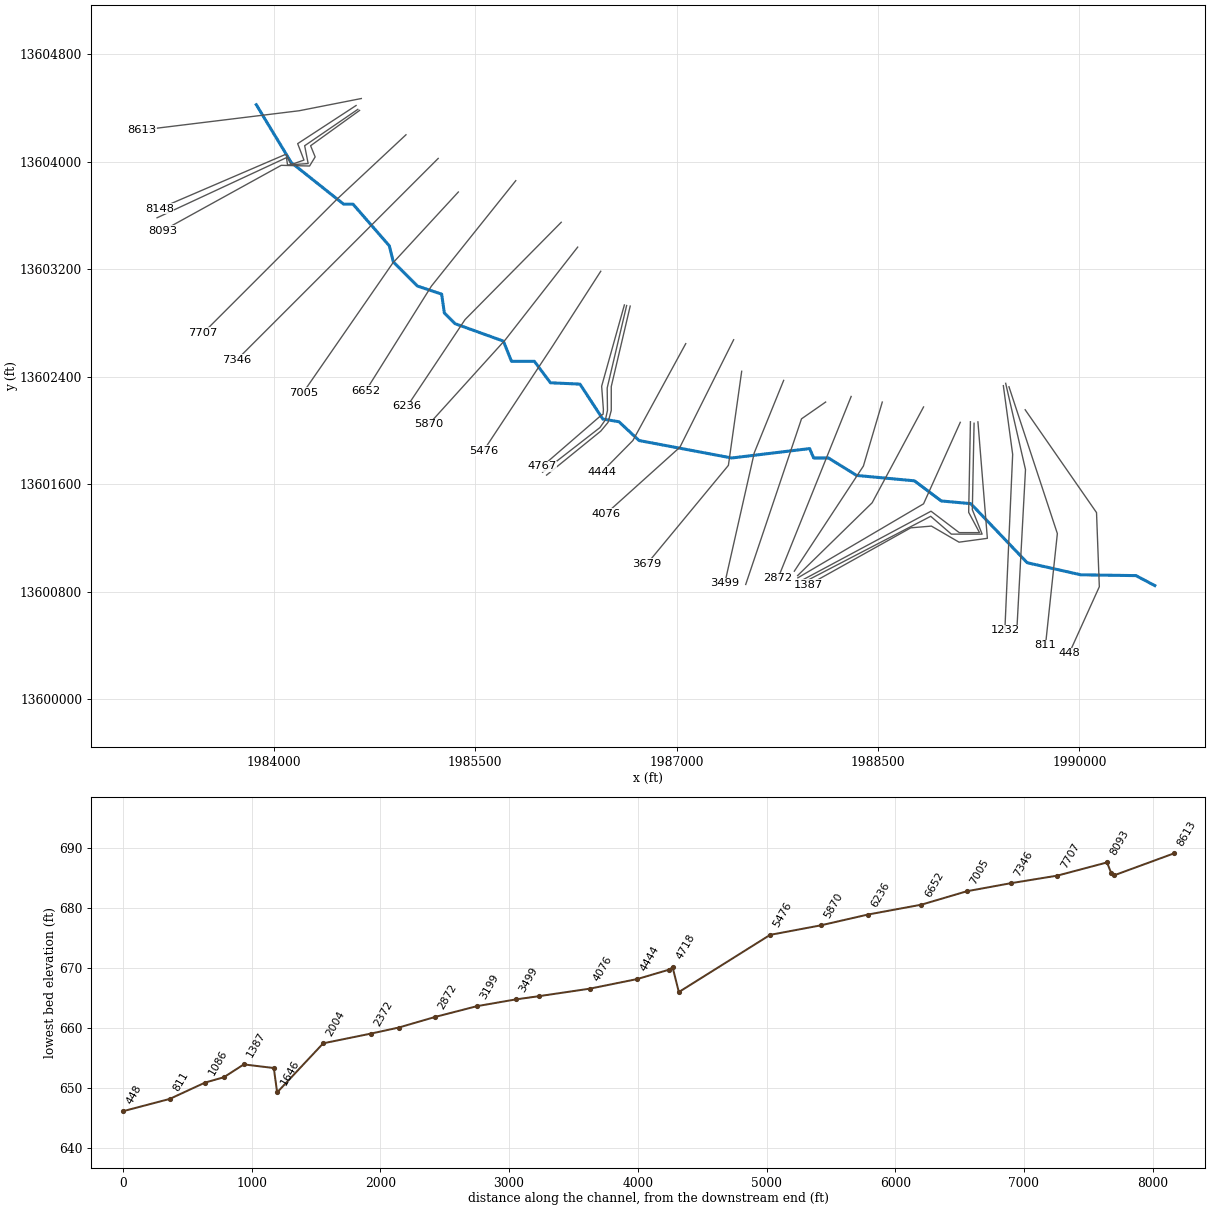
--- UNT 056 in HW.prj (project) ---

Proj Title=UNT 056 in HW Base Level Engineering
Current Plan=p01
Default Exp/Contr=0.3,0.1
English Units
Geom File=g01
Flow File=f01
Plan File=p01
Y Axis Title=Elevation
X Axis Title(PF)=Main Channel Distance
X Axis Title(XS)=Station
BEGIN DESCRIPTION:
UNT 056 in HW
END DESCRIPTION:
DSS Export Rating Curves= 0
DSS Export Rating Curve Sorted= 0
DSS Export Volume Flow Curves= 0
DXF OffsetX= 0
DXF OffsetY= 0
DXF ScaleX= 1
DXF ScaleY= 10

--- UNT 056 in HW.p01 (plan) ---

Plan Title=Multiple Run
Short Identifier=Multiple
Geom File=g01
Flow File=f01
Subcritical Flow
K Sum by GR= 0
Std Step Tol= 0.01
Critical Tol= 0.01
Num of Std Step Trials= 20
Max Error Tol= 0.3
Flow Tol Ratio= 0.001
Split Flow NTrial= 30
Split Flow Tol= 0.02
Split Flow Ratio= 0.02
Log Output Level= 0
Friction Slope Method= 1
Unsteady Friction Slope Method= 2
Unsteady Bridges Friction Slope Method= 1
Parabolic Critical Depth
Global Vel Dist=  1 , 1 , 1
Global Log Level= 0
CheckData=True
Encroach Param= -1, 0, 0, 0
BEGIN DESCRIPTION:
Multiple Run
END DESCRIPTION:

--- UNT 056 in HW.f01 (steady flow) ---

Flow Title=Multiple
Number of Profiles=7
Profile Names=10-year,25-year,50-year,1pct_min,100-year,1pct_plu,500-year
River Rch & RM= UNT 056 in HW,Reach-1,8613
     506     707     874     536    1069    2132    1603
River Rch & RM= UNT 056 in HW,Reach-1,8148
     729    1038    1298     803    1601    3195    2449
River Rch & RM= UNT 056 in HW,Reach-1,1232
    1250    1831    2335    1470    2934    5854    4654
Boundary for River Rch & Prof#=UNT 056 in HW,Reach-1,1
Up Type=0
Dn Type=3
Dn Slope=0.005
Boundary for River Rch & Prof#=UNT 056 in HW,Reach-1,2
Up Type=0
Dn Type=3
Dn Slope=0.005
Boundary for River Rch & Prof#=UNT 056 in HW,Reach-1,3
Up Type=0
Dn Type=3
Dn Slope=0.005
Boundary for River Rch & Prof#=UNT 056 in HW,Reach-1,4
Up Type=0
Dn Type=3
Dn Slope=0.005
Boundary for River Rch & Prof#=UNT 056 in HW,Reach-1,5
Up Type=0
Dn Type=3
Dn Slope=0.005
Boundary for River Rch & Prof#=UNT 056 in HW,Reach-1,6
Up Type=0
Dn Type=3
Dn Slope=0.005
Boundary for River Rch & Prof#=UNT 056 in HW,Reach-1,7
Up Type=0
Dn Type=3
Dn Slope=0.005

--- UNT 056 in HW.g01 (geometry) ---

Geom Title=Existing Conditions

River Reach=UNT 056 in HW,Reach-1
Reach XY= 30
      1983870.80     13604424.54      1984130.80     13603994.54
      1984520.80     13603684.54      1984590.80     13603684.54
      1984860.80     13603374.54      1984890.80     13603254.54
      1985070.80     13603074.54      1985250.80     13603014.54
      1985270.80     13602874.54      1985350.80     13602794.54
      1985710.80     13602664.54      1985770.80     13602514.54
      1985940.80     13602514.54      1986060.80     13602354.54
      1986280.80     13602344.54      1986450.80     13602084.54
      1986570.80     13602064.54      1986720.80     13601924.54
      1987410.80     13601794.54      1987990.80     13601864.54
      1988020.80     13601794.54      1988130.80     13601794.54
      1988340.80     13601664.54      1988770.80     13601624.54
      1988970.80     13601474.54      1989190.80     13601454.54
      1989610.80     13601014.54      1990010.80     13600924.54
      1990420.56     13600918.66      1990560.80     13600844.54

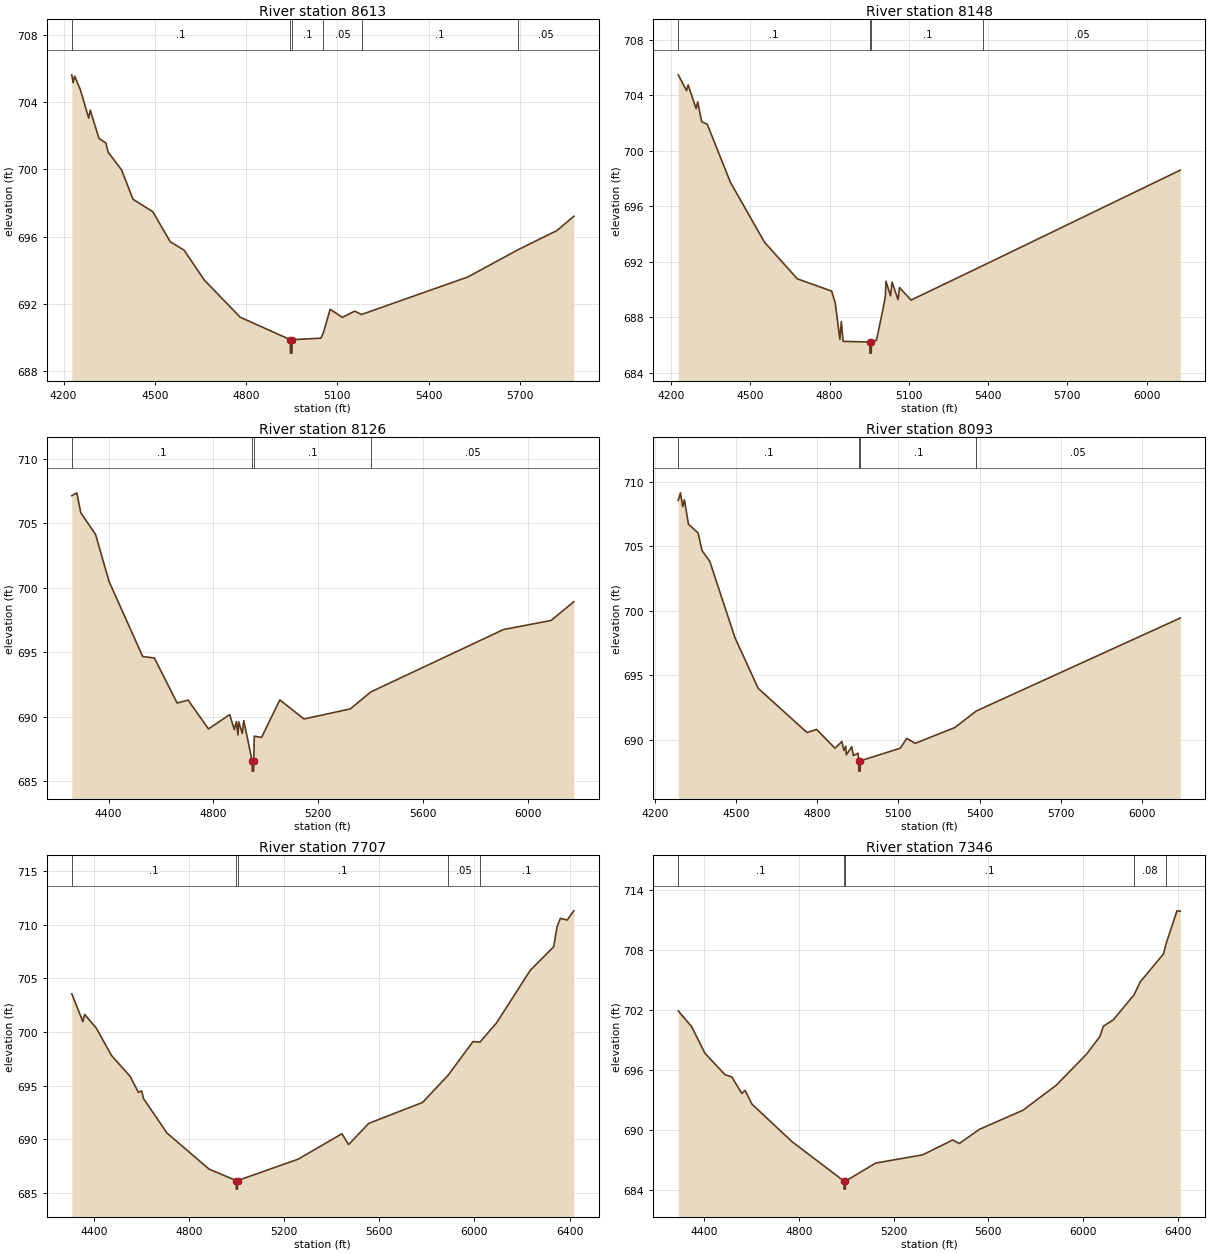
Type RM Length L Ch R = 1,8613,465,465,465
BEGIN DESCRIPTION:
UNT 056 in HW 18.0
END DESCRIPTION:
XS GIS Cut Line= 3
      1984652.59     13604471.15      1984189.07     13604380.01
      1983019.91     13604236.79
#Sta/Elev= 30
  4227.1  705.63  4231.4  705.16  4236.5  705.55  4255.2  704.75  4282.8  703.05
  4287.9  703.53  4316.4  701.85  4339.3  701.57  4346.9  701.02  4390.7  699.97
  4428.5  698.22  4493.5  697.48  4550.8  695.69  4596.3  695.19  4662.9  693.41
  4780.5  691.20  4945.4  689.86  4945.9  689.06  4950.9  689.06  4951.4  689.86
  5046.1  689.95  5054.3  690.28  5076.4  691.67  5116.7  691.19  5157.0  691.56
  5179.5  691.36  5529.7  693.60  5694.4  695.22  5821.9  696.36  5877.4  697.21
#Mann=6,-1,0
  4227.1     0.1       0  4945.4    0.07       0  4951.4     0.1       0
  5054.3    0.05       0  5179.5     0.1       0  5694.4    0.05       0
Bank Sta=4945.4,4951.4
Exp/Cntr=0.3,0.1

Type RM Length L Ch R = 1,8148,22,22,22
BEGIN DESCRIPTION:
Mapping XS 528b61f3
END DESCRIPTION:
XS GIS Cut Line= 6
      1984613.58     13604419.10      1984178.65     13604135.22
      1984225.53     13604012.82      1984129.17     13603978.97
      1984092.72     13604057.09      1983148.66     13603651.38
#Sta/Elev= 30
  4227.3  705.49  4258.9  704.35  4264.8  704.76  4295.1  703.05  4301.0  703.54
  4316.1  702.10  4337.2  701.92  4424.8  697.73  4554.5  693.39  4678.2  690.76
  4808.0  689.88  4821.7  689.02  4839.2  686.39  4844.7  687.68  4851.5  686.25
  4952.5  686.20  4953.0  685.40  4958.0  685.40  4958.5  686.20  4977.9  686.34
  5006.4  688.97  5011.6  689.59  5013.6  690.59  5031.0  689.53  5036.5  690.53
  5059.4  689.26  5064.9  690.13  5108.7  689.23  5381.8  691.73  6127.8  698.61
#Mann=4,-1,0
  4227.3     0.1       0  4952.5    0.07       0  4958.5     0.1       0
  5381.8    0.05       0
Bank Sta=4952.5,4958.5
Exp/Cntr=0.3,0.1

Type RM Length L Ch R = 1,8126,33,33,33
BEGIN DESCRIPTION:
Mapping XS abfd7715
END DESCRIPTION:
XS GIS Cut Line= 6
      1984626.61     13604390.45      1984230.74     13604119.59
      1984256.78     13603986.78      1984103.13     13603976.36
      1984095.32     13604031.05      1983131.74     13603583.12
#Sta/Elev= 30
  4259.5  707.14  4278.8  707.36  4293.7  705.83  4350.6  704.12  4401.4  700.51
  4530.0  694.68  4574.7  694.56  4661.3  691.08  4703.4  691.30  4781.0  689.07
  4861.9  690.18  4879.3  689.02  4886.8  689.63  4893.5  688.60  4896.0  689.63
  4909.9  688.72  4915.5  689.71  4947.5  686.60  4948.0  685.80  4953.1  685.80
  4953.6  686.60  4955.6  688.51  4983.4  688.41  5053.1  691.32  5145.3  689.84
  5321.8  690.62  5400.3  691.94  5906.2  696.77  6087.6  697.47  6174.5  698.93
#Mann=4,-1,0
  4259.5     0.1       0  4947.5    0.07       0  4953.6     0.1       0
  5400.3    0.05       0
Bank Sta=4947.5,4953.6
Exp/Cntr=0.3,0.1

Type RM Length L Ch R = 1,8093,386,386,386
BEGIN DESCRIPTION:
Mapping XS d77214ff
END DESCRIPTION:
XS GIS Cut Line= 6
      1984639.63     13604382.64      1984275.01     13604119.59
      1984308.86     13604036.26      1984267.20     13603968.55
      1984056.26     13603973.76      1983173.45     13603486.78
#Sta/Elev= 30
  4287.1  708.57  4295.3  709.16  4303.8  708.09  4310.0  708.62  4324.7  706.73
  4360.3  706.05  4375.0  704.68  4403.8  703.83  4496.5  697.92  4582.4  693.98
  4762.7  690.55  4798.2  690.79  4866.3  689.33  4891.6  689.85  4899.0  689.15
  4905.8  689.49  4907.9  688.81  4928.3  689.45  4933.9  688.76  4951.1  688.94
  4953.6  688.35  4954.1  687.55  4959.2  687.55  4959.7  688.35  5107.3  689.33
  5131.1  690.09  5162.7  689.71  5309.4  690.94  5388.0  692.22  6141.7  699.44
#Mann=4,-1,0
  4287.1     0.1       0  4953.6    0.07       0  4959.7     0.1       0
  5388.0    0.05       0
Bank Sta=4953.6,4959.7
Exp/Cntr=0.3,0.1

Type RM Length L Ch R = 1,7707,361,361,361
BEGIN DESCRIPTION:
UNT 056 in HW 17.0
END DESCRIPTION:
XS GIS Cut Line= 3
      1984985.05     13604201.17      1984475.00     13603725.00
      1983474.99     13602724.99
#Sta/Elev= 30
  4306.0  703.56  4352.8  700.96  4360.1  701.64  4409.5  700.35  4473.0  697.81
  4551.2  695.87  4586.3  694.37  4600.5  694.50  4607.3  693.81  4706.5  690.58
  4883.4  687.22  4997.3  686.15  4997.8  685.35  5002.9  685.35  5003.4  686.15
  5258.3  688.14  5442.2  690.51  5470.5  689.50  5555.3  691.48  5781.6  693.43
  5888.5  695.95  5993.7  699.10  6023.4  699.06  6092.7  700.84  6234.1  705.73
  6333.1  707.94  6347.3  709.80  6361.4  710.59  6389.7  710.43  6418.0  711.29
#Mann=5,-1,0
  4306.0     0.1       0  4997.3    0.07       0  5003.4     0.1       0
  5888.5    0.05       0  6023.4     0.1       0
Bank Sta=4997.3,5003.4
Exp/Cntr=0.3,0.1

Type RM Length L Ch R = 1,7346,341,341,341
BEGIN DESCRIPTION:
UNT 056 in HW 16.0
END DESCRIPTION:
XS GIS Cut Line= 3
      1985225.00     13604025.00      1984725.00     13603525.00
      1983725.01     13602525.01
#Sta/Elev= 30
  4289.6  701.93  4346.2  700.36  4402.7  697.68  4487.6  695.54  4515.9  695.32
  4558.3  693.67  4572.4  693.97  4600.7  692.61  4770.4  688.84  4990.1  684.89
  4990.6  684.09  4995.7  684.09  4996.2  684.89  5124.0  686.70  5322.0  687.52
  5449.3  689.01  5477.5  688.66  5562.4  690.08  5746.2  691.99  5887.7  694.51
  6014.9  697.61  6071.5  699.38  6085.6  700.39  6128.1  701.05  6215.6  703.54
  6241.2  704.83  6340.2  707.64  6348.7  708.51  6396.8  711.95  6410.9  711.91
#Mann=5,-1,0
  4289.6     0.1       0  4990.1    0.07       0  4996.2     0.1       0
  6215.6    0.08       0  6348.7     0.1       0
Bank Sta=4990.1,4996.2
Exp/Cntr=0.3,0.1

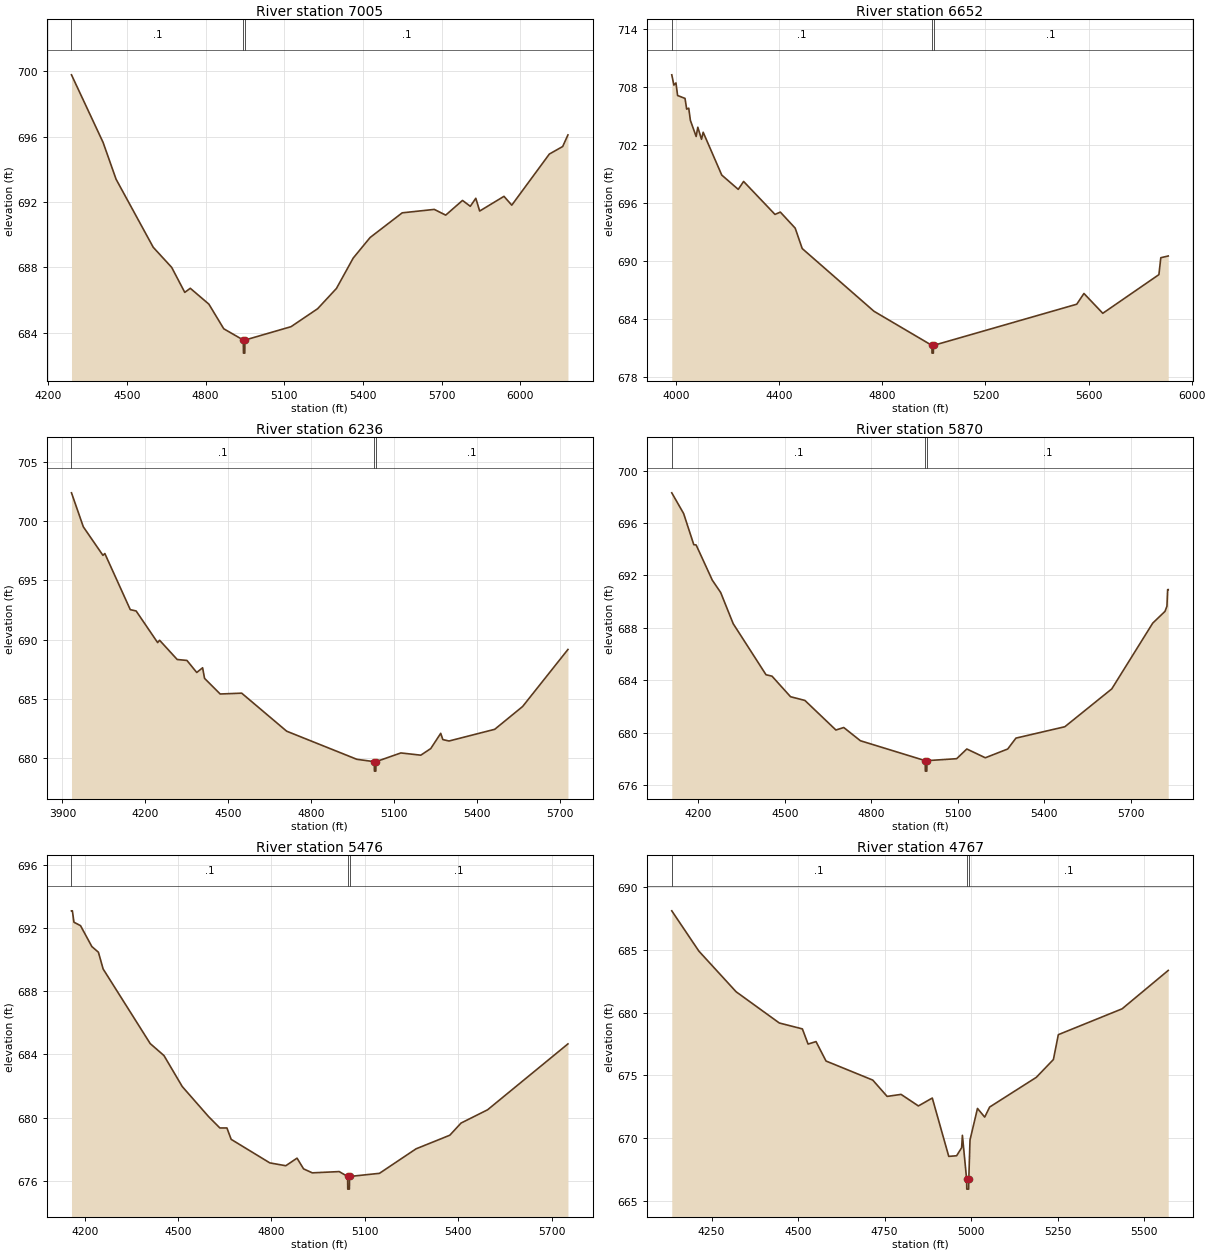
Type RM Length L Ch R = 1,7005,353,353,353
BEGIN DESCRIPTION:
UNT 056 in HW 15.0
END DESCRIPTION:
XS GIS Cut Line= 3
      1985375.01     13603775.01      1984885.95     13603244.85
      1984219.66     13602281.87
#Sta/Elev= 30
  4289.0  699.79  4409.5  695.65  4458.9  693.40  4600.6  689.23  4670.9  688.00
  4720.8  686.47  4741.8  686.72  4812.7  685.75  4869.4  684.24  4944.0  683.55
  4944.5  682.75  4949.6  682.75  4950.1  683.55  5125.9  684.37  5227.3  685.47
  5298.9  686.71  5362.8  688.57  5427.3  689.83  5549.6  691.34  5671.9  691.55
  5715.4  691.20  5779.4  692.10  5809.1  691.74  5830.1  692.23  5844.9  691.45
  5937.5  692.35  5967.2  691.81  6110.5  694.94  6161.2  695.40  6181.3  696.11
#Mann=3,-1,0
  4289.0     0.1       0  4944.0    0.07       0  4950.1     0.1       0
Bank Sta=4944,4950.1
Exp/Cntr=0.3,0.1

Type RM Length L Ch R = 1,6652,416,416,416
BEGIN DESCRIPTION:
UNT 056 in HW 14.0
END DESCRIPTION:
XS GIS Cut Line= 3
      1985802.64     13603859.47      1985175.00     13603075.00
      1984685.44     13602294.36
#Sta/Elev= 30
  3983.0  709.30  3991.2  708.24  3999.2  708.46  4005.6  707.16  4034.4  706.86
  4040.8  705.75  4048.8  705.85  4055.2  704.59  4077.6  702.92  4084.0  703.88
  4098.4  702.63  4104.8  703.36  4176.9  698.93  4240.9  697.45  4261.7  698.27
  4383.4  694.86  4404.2  695.10  4461.8  693.44  4489.0  691.33  4767.5  684.84
  4992.2  681.31  4992.7  680.51  4997.9  680.51  4998.4  681.31  5554.2  685.57
  5582.1  686.68  5655.2  684.63  5872.9  688.63  5880.3  690.38  5909.1  690.56
#Mann=3,-1,0
  3983.0     0.1       0  4992.2    0.07       0  4998.4     0.1       0
Bank Sta=4992.2,4998.4
Exp/Cntr=0.3,0.1

Type RM Length L Ch R = 1,6236,366,366,366
BEGIN DESCRIPTION:
UNT 056 in HW 13.0
END DESCRIPTION:
XS GIS Cut Line= 3
      1986141.16     13603549.55      1985425.00     13602825.00
      1984993.66     13602178.55
#Sta/Elev= 30
  3932.6  702.42  3975.5  699.54  4046.3  697.13  4053.3  697.28  4145.3  692.53
  4166.4  692.42  4244.3  689.74  4251.3  689.94  4315.0  688.31  4350.3  688.23
  4385.7  687.21  4406.9  687.61  4414.0  686.71  4470.5  685.39  4548.3  685.46
  4711.0  682.24  4964.9  679.86  5027.9  679.66  5028.4  678.86  5033.6  678.86
  5034.1  679.66  5124.1  680.40  5196.2  680.21  5232.2  680.77  5268.3  682.06
  5275.9  681.53  5298.3  681.41  5463.6  682.40  5564.5  684.33  5728.5  689.16
#Mann=3,-1,0
  3932.6     0.1       0  5027.9    0.07       0  5034.1     0.1       0
Bank Sta=5027.9,5034.1
Exp/Cntr=0.3,0.1

Type RM Length L Ch R = 1,5870,394,394,394
BEGIN DESCRIPTION:
UNT 056 in HW 12.0
END DESCRIPTION:
XS GIS Cut Line= 3
      1986263.57     13603364.67      1985725.00     13602675.00
      1985156.78     13602046.93
#Sta/Elev= 30
  4107.5  698.31  4148.6  696.73  4183.9  694.35  4192.0  694.33  4248.1  691.64
  4277.1  690.70  4320.5  688.32  4434.4  684.42  4455.2  684.31  4519.5  682.74
  4569.2  682.46  4676.8  680.20  4704.0  680.39  4761.8  679.38  4986.5  677.86
  4987.0  677.06  4992.2  677.06  4992.7  677.86  5095.7  678.01  5130.9  678.75
  5195.1  678.08  5272.8  678.75  5301.2  679.58  5470.9  680.45  5633.7  683.34
  5775.7  688.36  5818.3  689.26  5825.0  689.65  5827.4  690.92  5829.5  690.92
#Mann=3,-1,0
  4107.5     0.1       0  4986.5    0.07       0  4992.7     0.1       0
Bank Sta=4986.5,4992.7
Exp/Cntr=0.3,0.1

Type RM Length L Ch R = 1,5476,709,709,709
BEGIN DESCRIPTION:
UNT 056 in HW 11.0
END DESCRIPTION:
XS GIS Cut Line= 3
      1986435.41     13603184.93      1986075.00     13602625.00
      1985563.33     13601849.48
#Sta/Elev= 30
  4157.5  693.08  4160.4  693.08  4165.4  692.36  4186.6  692.14  4222.9  690.82
  4244.0  690.46  4259.2  689.40  4410.4  684.68  4454.7  683.92  4513.4  681.96
  4597.9  680.06  4634.2  679.34  4656.9  679.34  4670.5  678.62  4794.7  677.13
  4846.0  676.95  4882.1  677.43  4903.2  676.75  4931.2  676.50  5017.6  676.58
  5044.6  676.27  5045.1  675.47  5050.3  675.47  5050.8  676.27  5147.0  676.47
  5264.5  678.02  5372.9  678.88  5409.0  679.65  5494.3  680.49  5752.5  684.66
#Mann=3,-1,0
  4157.5     0.1       0  5044.6    0.07       0  5050.8     0.1       0
Bank Sta=5044.6,5050.8
Exp/Cntr=0.3,0.1

Type RM Length L Ch R = 1,4767,49,49,49
BEGIN DESCRIPTION:
Mapping XS b64fb3f8
END DESCRIPTION:
XS GIS Cut Line= 6
      1986611.39     13602934.32      1986442.11     13602328.82
      1986455.13     13602155.21      1986452.96     13602120.49
      1986435.60     13602109.64      1985999.71     13601732.31
#Sta/Elev= 30
  4134.9  688.11  4213.2  684.90  4320.8  681.66  4445.7  679.17  4512.3  678.70
  4528.8  677.49  4551.7  677.69  4580.6  676.14  4715.7  674.62  4757.2  673.32
  4797.5  673.48  4847.6  672.56  4887.7  673.19  4935.3  668.54  4958.0  668.59
  4972.5  669.23  4974.7  670.22  4986.9  666.73  4987.4  665.93  4992.7  665.93
  4993.2  666.73  4996.7  669.85  5018.3  672.36  5039.2  671.67  5053.4  672.47
  5188.3  674.84  5237.7  676.26  5251.9  678.24  5436.2  680.30  5569.5  683.36
#Mann=3,-1,0
  4134.9     0.1       0  4986.9    0.07       0  4993.2     0.1       0
Bank Sta=4986.9,4993.2
Exp/Cntr=0.3,0.1

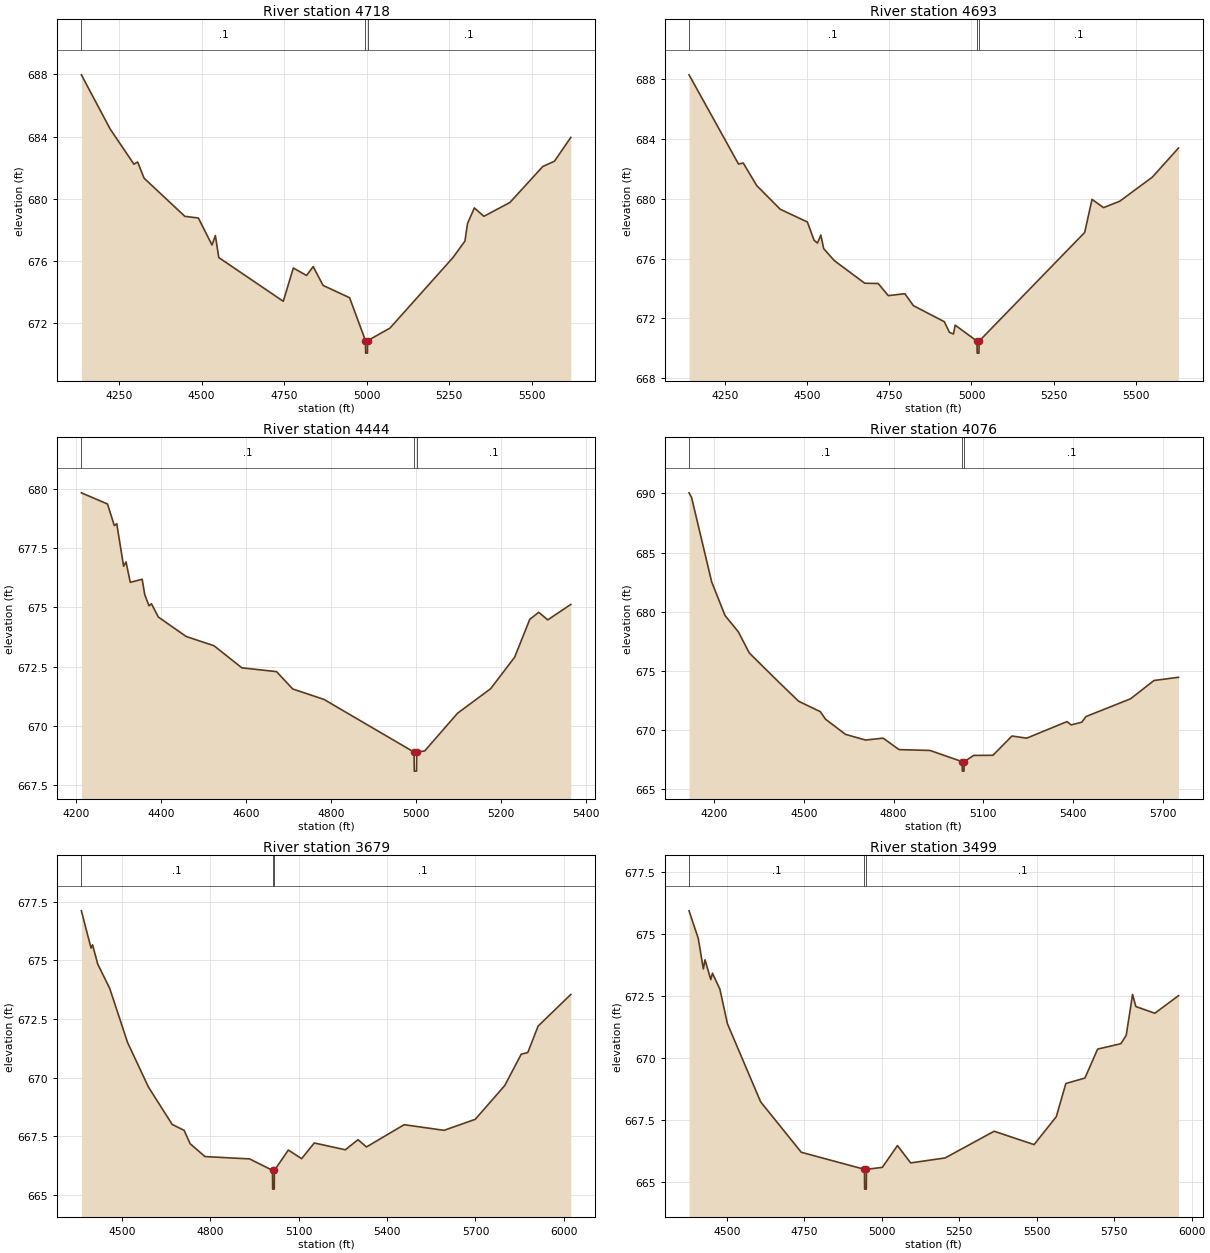
Type RM Length L Ch R = 1,4718,25,25,25
BEGIN DESCRIPTION:
UNT 056 in HW 10.0
END DESCRIPTION:
XS GIS Cut Line= 6
      1986628.14     13602929.76      1986483.34     13602315.80
      1986485.51     13602148.70      1986470.32     13602079.26
      1986429.09     13602020.66      1986002.06     13601688.75
#Sta/Elev= 30
  4136.4  687.97  4223.5  684.49  4295.4  682.23  4306.7  682.37  4326.2  681.33
  4449.5  678.88  4490.6  678.77  4531.7  677.04  4542.0  677.64  4552.3  676.23
  4747.5  673.42  4778.0  675.56  4818.0  675.08  4838.0  675.65  4868.0  674.44
  4948.3  673.65  4996.4  670.89  4996.9  670.09  5002.2  670.09  5002.7  670.89
  5070.6  671.70  5261.6  676.24  5297.5  677.29  5305.1  678.41  5325.9  679.42
  5354.8  678.88  5433.6  679.77  5533.1  682.08  5568.4  682.42  5617.9  683.95
#Mann=3,-1,0
  4136.4     0.1       0  4996.4    0.07       0  5002.7     0.1       0
Bank Sta=4996.4,5002.7
Exp/Cntr=0.3,0.1

Type RM Length L Ch R = 1,4693,249,249,249
BEGIN DESCRIPTION:
Mapping XS c03e6249
END DESCRIPTION:
XS GIS Cut Line= 6
      1986654.77     13602925.57      1986513.72     13602326.65
      1986513.72     13602148.70      1986489.85     13602059.73
      1986435.60     13601994.62      1986031.99     13601666.96
#Sta/Elev= 30
  4140.1  688.27  4290.7  682.31  4305.1  682.38  4346.2  680.87  4417.8  679.29
  4500.3  678.44  4520.8  677.22  4531.1  677.03  4541.4  677.57  4550.0  676.66
  4582.4  675.86  4674.9  674.35  4716.0  674.33  4746.8  673.52  4797.1  673.65
  4823.3  672.85  4917.3  671.78  4932.9  671.07  4945.3  670.96  4950.4  671.55
  5016.9  670.48  5017.4  669.68  5022.7  669.68  5023.2  670.48  5344.7  677.74
  5367.0  679.95  5402.2  679.40  5451.7  679.83  5550.9  681.44  5630.3  683.38
#Mann=3,-1,0
  4140.1     0.1       0  5016.9    0.07       0  5023.2     0.1       0
Bank Sta=5016.9,5023.2
Exp/Cntr=0.3,0.1

Type RM Length L Ch R = 1,4444,368,368,368
BEGIN DESCRIPTION:
UNT 056 in HW 9.0
END DESCRIPTION:
XS GIS Cut Line= 3
      1987068.26     13602645.93      1986675.00     13601925.00
      1986443.21     13601690.14
#Sta/Elev= 30
  4212.2  679.82  4273.6  679.35  4289.7  678.44  4295.4  678.52  4311.5  676.73
  4317.2  676.91  4327.2  676.05  4355.2  676.18  4361.3  675.53  4371.3  675.06
  4377.0  675.15  4393.2  674.59  4458.7  673.77  4524.2  673.38  4589.7  672.45
  4671.3  672.29  4709.3  671.56  4782.8  671.12  4994.7  668.90  4995.2  668.10
  5000.5  668.10  5001.0  668.90  5019.7  668.95  5097.1  670.54  5174.8  671.57
  5231.4  672.90  5266.8  674.49  5287.9  674.79  5309.2  674.47  5363.4  675.12
#Mann=3,-1,0
  4212.2     0.1       0  4994.7    0.07       0  5001.0     0.1       0
Bank Sta=4994.7,5001
Exp/Cntr=0.3,0.1

Type RM Length L Ch R = 1,4076,397,397,397
BEGIN DESCRIPTION:
UNT 056 in HW 8.0
END DESCRIPTION:
XS GIS Cut Line= 3
      1987425.00     13602675.00      1987025.00     13601875.00
      1986474.54     13601379.59
#Sta/Elev= 30
  4117.0  690.05  4125.4  689.66  4192.5  682.52  4237.2  679.67  4281.9  678.28
  4318.2  676.50  4416.1  674.05  4483.2  672.41  4555.8  671.53  4572.6  670.90
  4639.7  669.61  4706.8  669.13  4765.5  669.29  4818.6  668.32  4922.0  668.25
  5029.5  667.30  5030.0  666.50  5035.4  666.50  5035.9  667.30  5067.9  667.83
  5132.1  667.84  5195.7  669.47  5245.0  669.29  5379.5  670.69  5393.7  670.41
  5428.9  670.64  5443.1  671.12  5591.8  672.62  5670.3  674.17  5752.0  674.44
#Mann=3,-1,0
  4117.0     0.1       0  5029.5    0.07       0  5035.9     0.1       0
Bank Sta=5029.5,5035.9
Exp/Cntr=0.3,0.1

Type RM Length L Ch R = 1,3679,180,180,180
BEGIN DESCRIPTION:
UNT 056 in HW 7.0
END DESCRIPTION:
XS GIS Cut Line= 3
      1987484.90     13602440.16      1987385.95     13601739.65
      1986778.96     13601005.04
#Sta/Elev= 30
  4363.1  677.12  4395.9  675.53  4400.9  675.67  4418.8  674.84  4459.2  673.81
  4519.8  671.50  4590.5  669.60  4671.3  668.00  4711.7  667.75  4731.9  667.18
  4782.4  666.63  4933.9  666.53  5011.5  666.04  5012.0  665.24  5017.4  665.24
  5017.9  666.04  5065.2  666.91  5110.2  666.54  5153.2  667.21  5258.6  666.92
  5301.6  667.35  5330.3  667.04  5458.0  667.99  5593.5  667.75  5699.3  668.22
  5799.3  669.66  5855.3  671.00  5877.5  671.07  5912.6  672.20  6023.5  673.55
#Mann=3,-1,0
  4363.1     0.1       0  5011.5    0.07       0  5017.9     0.1       0
Bank Sta=5011.5,5017.9
Exp/Cntr=0.3,0.1

Type RM Length L Ch R = 1,3499,300,300,300
BEGIN DESCRIPTION:
UNT 056 in HW 6.0
END DESCRIPTION:
XS GIS Cut Line= 3
      1987797.41     13602372.46      1987578.65     13601833.40
      1987358.61     13600860.53
#Sta/Elev= 30
  4378.4  675.95  4408.0  674.84  4424.5  673.60  4429.9  673.97  4448.5  673.17
  4453.9  673.43  4478.0  672.78  4502.1  671.39  4609.3  668.23  4740.5  666.19
  4944.4  665.50  4944.9  664.70  4950.3  664.70  4950.8  665.50  5002.0  665.58
  5050.8  666.46  5093.5  665.76  5204.6  665.96  5362.8  667.04  5491.7  666.50
  5563.4  667.63  5594.2  668.97  5655.7  669.19  5696.7  670.36  5771.8  670.58
  5789.0  670.92  5809.5  672.57  5820.1  672.08  5881.3  671.81  5957.6  672.52
#Mann=3,-1,0
  4378.4     0.1       0  4944.4    0.07       0  4950.8     0.1       0
Bank Sta=4944.4,4950.8
Exp/Cntr=0.3,0.1

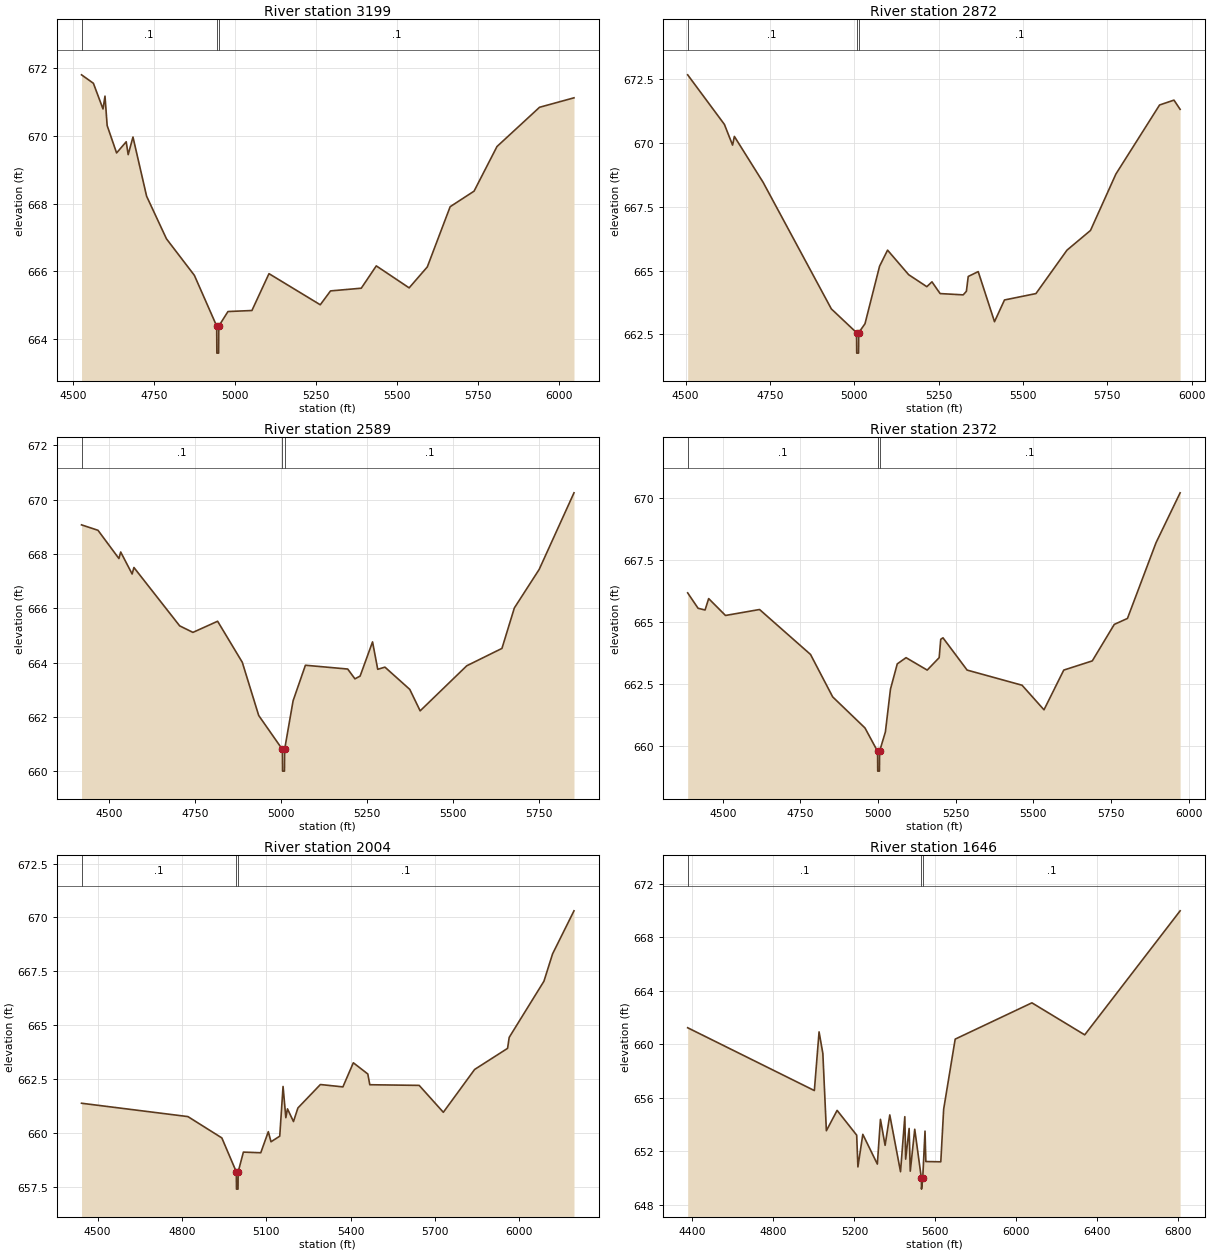
Type RM Length L Ch R = 1,3199,327,327,327
BEGIN DESCRIPTION:
Mapping XS 40d26ace
END DESCRIPTION:
XS GIS Cut Line= 3
      1988109.92     13602211.01      1987930.22     13602086.00
      1987514.85     13600852.68
#Sta/Elev= 30
  4526.3  671.81  4562.9  671.56  4592.6  670.80  4598.7  671.18  4605.4  670.31
  4634.5  669.50  4664.2  669.83  4670.3  669.45  4685.1  669.97  4727.2  668.22
  4788.5  666.96  4874.7  665.88  4943.6  664.38  4944.1  663.58  4949.5  663.58
  4950.0  664.38  4978.4  664.81  5052.3  664.84  5105.0  665.93  5263.3  665.01
  5295.0  665.42  5389.9  665.50  5436.3  666.16  5537.7  665.51  5593.8  666.13
  5664.3  667.91  5738.1  668.37  5808.9  669.69  5940.2  670.85  6046.6  671.13
#Mann=3,-1,0
  4526.3     0.1       0  4943.6    0.07       0  4950.0     0.1       0
Bank Sta=4943.6,4950
Exp/Cntr=0.3,0.1

Type RM Length L Ch R = 1,2872,283,283,283
BEGIN DESCRIPTION:
Mapping XS 8465d111
END DESCRIPTION:
XS GIS Cut Line= 2
      1988300.00     13602252.63      1987755.04     13600898.47
#Sta/Elev= 30
  4506.2  672.66  4615.1  670.72  4639.3  669.91  4644.6  670.25  4730.0  668.45
  4932.1  663.50  5006.8  662.57  5007.3  661.77  5012.7  661.77  5013.2  662.57
  5031.8  662.92  5075.0  665.17  5098.7  665.80  5161.2  664.84  5215.1  664.37
  5230.3  664.56  5254.5  664.10  5322.9  664.05  5332.4  664.19  5337.8  664.77
  5367.4  664.96  5415.7  663.00  5445.3  663.85  5538.5  664.10  5630.6  665.80
  5700.2  666.57  5775.6  668.78  5905.0  671.48  5947.7  671.67  5965.9  671.31
#Mann=3,-1,0
  4506.2     0.1       0  5006.8    0.07       0  5013.2     0.1       0
Bank Sta=5006.8,5013.2
Exp/Cntr=0.3,0.1

Type RM Length L Ch R = 1,2589,217,217,217
BEGIN DESCRIPTION:
Mapping XS 59b3377e
END DESCRIPTION:
XS GIS Cut Line= 3
      1988531.77     13602210.99      1988391.15     13601734.44
      1987876.83     13600951.65
#Sta/Elev= 30
  4419.5  669.07  4467.4  668.87  4528.3  667.83  4533.5  668.07  4566.8  667.26
  4572.0  667.50  4705.2  665.35  4743.8  665.11  4815.6  665.52  4887.4  664.01
  4935.2  662.05  5004.2  660.80  5004.7  660.00  5010.2  660.00  5010.7  660.80
  5035.3  662.59  5071.2  663.90  5194.3  663.76  5215.3  663.40  5230.4  663.50
  5266.6  664.76  5281.7  663.75  5302.7  663.83  5375.0  663.01  5405.2  662.22
  5540.8  663.88  5643.3  664.52  5679.4  666.01  5751.7  667.43  5853.0  670.25
#Mann=3,-1,0
  4419.5     0.1       0  5004.2    0.07       0  5010.7     0.1       0
Bank Sta=5004.2,5010.7
Exp/Cntr=0.3,0.1

Type RM Length L Ch R = 1,2372,368,368,368
BEGIN DESCRIPTION:
Mapping XS a20b87a8
END DESCRIPTION:
XS GIS Cut Line= 3
      1988839.07     13602174.53      1988456.26     13601461.00
      1987901.37     13600918.87
#Sta/Elev= 30
  4387.2  666.17  4420.7  665.55  4443.2  665.48  4454.8  665.94  4509.0  665.26
  4618.6  665.50  4782.7  663.69  4854.1  661.98  4958.0  660.73  4998.6  659.79
  4999.1  658.99  5004.6  658.99  5005.1  659.79  5023.8  660.57  5040.1  662.29
  5062.0  663.31  5090.3  663.56  5158.4  663.06  5196.9  663.56  5202.0  664.30
  5209.2  664.36  5286.9  663.06  5463.8  662.45  5534.4  661.46  5598.1  663.06
  5689.9  663.43  5760.7  664.90  5803.1  665.14  5895.1  668.19  5972.7  670.20
#Mann=3,-1,0
  4387.2     0.1       0  4998.6    0.07       0  5005.1     0.1       0
Bank Sta=4998.6,5005.1
Exp/Cntr=0.3,0.1

Type RM Length L Ch R = 1,2004,358,358,358
BEGIN DESCRIPTION:
Mapping XS 82a66ded
END DESCRIPTION:
XS GIS Cut Line= 3
      1989112.53     13602060.00      1988839.07     13601453.19
      1987902.88     13600902.16
#Sta/Elev= 30
  4442.6  661.37  4821.0  660.75  4941.7  659.76  4993.3  658.18  4993.8  657.38
  4999.3  657.38  4999.8  658.18  5018.4  659.10  5080.2  659.07  5107.1  660.05
  5116.6  659.58  5147.7  659.84  5159.5  662.15  5169.4  660.70  5175.2  661.11
  5196.6  660.52  5212.3  661.15  5292.3  662.24  5372.4  662.13  5409.5  663.25
  5461.0  662.73  5468.1  662.23  5643.8  662.20  5729.7  660.95  5841.0  662.94
  5958.2  663.92  5964.0  664.43  6087.6  667.04  6118.3  668.31  6194.5  670.31
#Mann=3,-1,0
  4442.6     0.1       0  4993.3    0.07       0  4999.8     0.1       0
Bank Sta=4993.3,4999.8
Exp/Cntr=0.3,0.1

Type RM Length L Ch R = 1,1646,26,26,26
BEGIN DESCRIPTION:
Mapping XS b26e458d
END DESCRIPTION:
XS GIS Cut Line= 6
      1989188.03     13602064.33      1989175.01     13601389.82
      1989255.74     13601238.78      1989104.70     13601238.78
      1988894.62     13601398.25      1987929.48     13600881.63
#Sta/Elev= 30
  4376.5  661.24  5002.3  656.55  5025.6  660.93  5044.3  659.32  5061.7  653.55
  5114.7  655.07  5211.4  653.22  5217.5  650.85  5241.7  653.28  5313.5  651.06
  5328.8  654.40  5351.8  652.46  5374.9  654.73  5428.0  650.49  5449.2  654.60
  5453.3  651.43  5470.5  653.72  5476.1  650.53  5498.2  653.66  5531.1  649.99
  5531.6  649.19  5537.6  649.99  5549.0  653.52  5553.0  651.25  5626.9  651.23
  5641.1  655.16  5698.0  660.39  6077.0  663.10  6337.9  660.71  6809.2  669.97
#Mann=3,-1,0
  4376.5     0.1       0  5531.1    0.07       0  5537.6     0.1       0
Bank Sta=5531.1,5537.6
Exp/Cntr=0.3,0.1

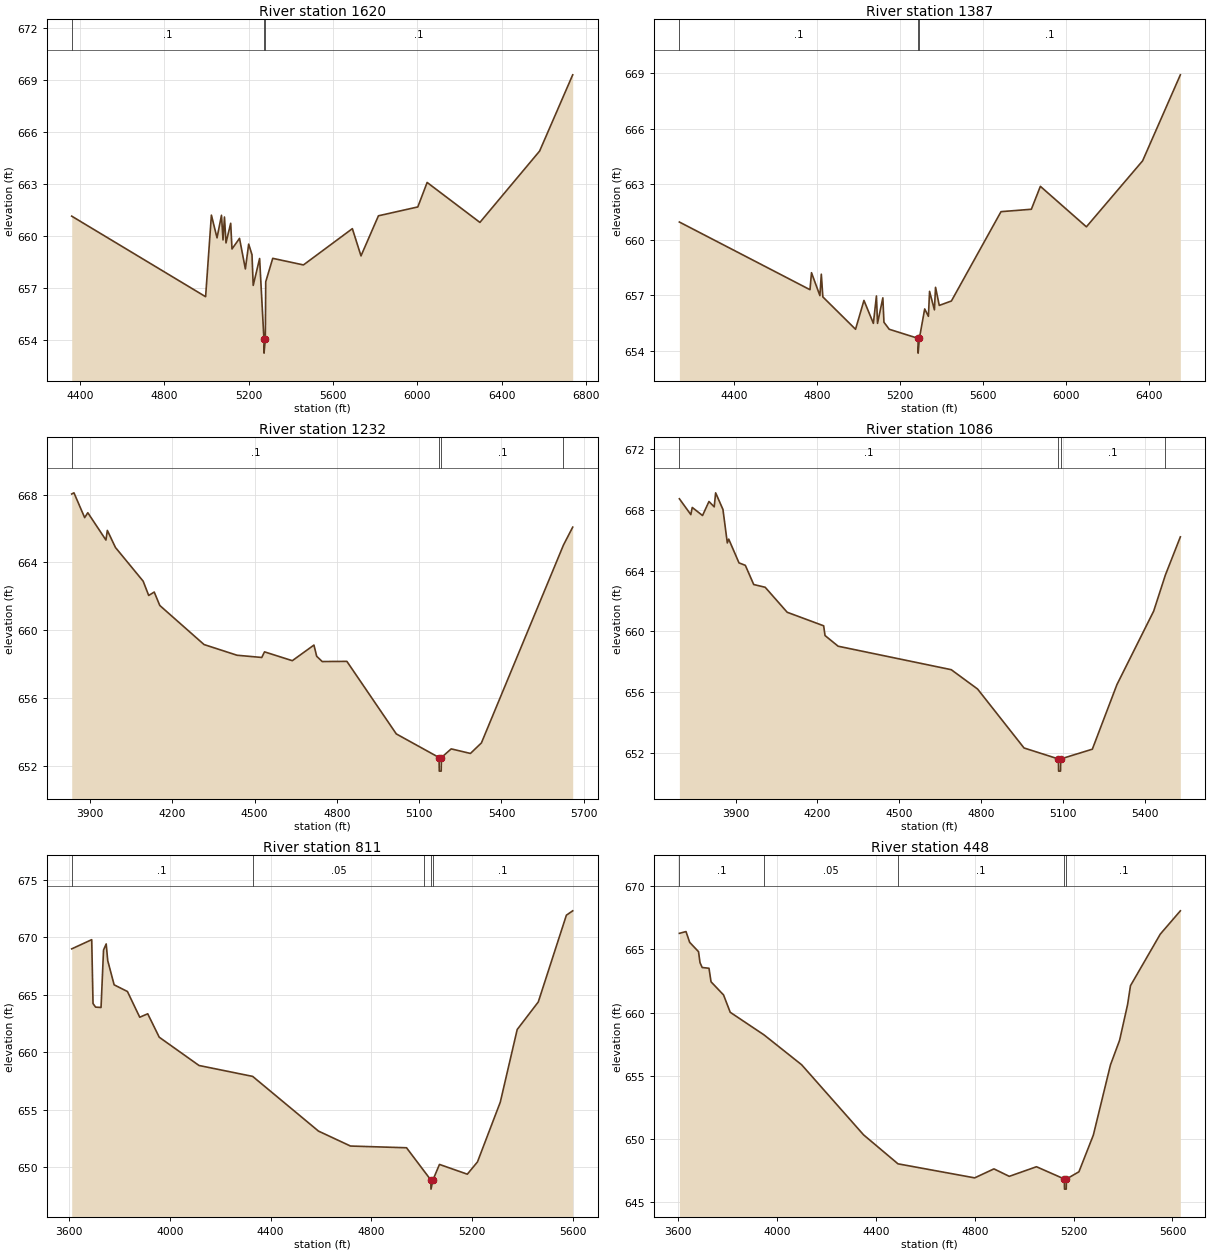
Type RM Length L Ch R = 1,1620,233,233,233
BEGIN DESCRIPTION:
Mapping XS 5e708a41
END DESCRIPTION:
XS GIS Cut Line= 6
      1989215.25     13602053.10      1989202.23     13601409.83
      1989275.15     13601227.54      1989045.98     13601227.54
      1988892.34     13601360.35      1987966.57     13600879.28
#Sta/Elev= 30
  4362.0  661.15  4996.3  656.51  5023.7  661.21  5050.4  659.90  5071.5  661.20
  5078.7  659.78  5085.6  661.10  5092.9  659.61  5115.1  660.74  5121.3  659.26
  5156.9  659.87  5184.6  658.11  5200.3  659.54  5216.0  658.93  5221.8  657.16
  5252.1  658.71  5272.6  654.06  5273.1  653.26  5279.1  654.06  5281.1  657.37
  5314.3  658.72  5459.7  658.34  5691.5  660.43  5732.4  658.86  5815.0  661.17
  6001.5  661.68  6045.7  663.09  6295.7  660.79  6578.6  664.90  6735.3  669.29
#Mann=3,-1,0
  4362.0     0.1       0  5272.6    0.07       0  5279.1     0.1       0
Bank Sta=5272.6,5279.1
Exp/Cntr=0.3,0.1

Type RM Length L Ch R = 1,1387,155,155,155
BEGIN DESCRIPTION:
UNT 056 in HW 5.0
END DESCRIPTION:
XS GIS Cut Line= 6
      1989243.90     13602063.46      1989314.21     13601196.29
      1989103.27     13601167.65      1988897.55     13601287.44
      1988743.90     13601274.42      1987983.57     13600850.06
#Sta/Elev= 30
  4135.9  660.95  4765.1  657.29  4772.3  658.21  4812.8  656.97  4819.6  658.13
  4827.0  656.90  4984.5  655.15  5025.0  656.71  5070.4  655.47  5085.1  656.95
  5090.4  655.47  5116.0  656.85  5121.3  655.53  5146.8  655.15  5285.5  654.66
  5286.0  653.86  5292.0  654.66  5317.6  656.25  5335.5  655.85  5341.0  657.20
  5364.4  656.20  5369.8  657.42  5387.8  656.44  5446.3  656.68  5685.1  661.51
  5831.4  661.64  5874.8  662.88  6096.5  660.69  6367.3  664.26  6549.1  668.91
#Mann=3,-1,0
  4135.9     0.1       0  5285.5    0.07       0  5292.0     0.1       0
Bank Sta=5285.5,5292
Exp/Cntr=0.3,0.1

Type RM Length L Ch R = 1,1232,146,146,146
BEGIN DESCRIPTION:
UNT 056 in HW 4.0
END DESCRIPTION:
XS GIS Cut Line= 3
      1989433.16     13602333.17      1989502.60     13601821.07
      1989444.44     13600512.45
#Sta/Elev= 30
  3833.1  668.03  3841.3  668.10  3880.3  666.64  3891.8  666.93  3957.9  665.32
  3963.0  665.89  3992.7  664.88  4093.6  662.90  4113.8  662.06  4134.0  662.26
  4154.2  661.47  4315.6  659.17  4436.0  658.54  4526.1  658.41  4536.1  658.74
  4637.4  658.22  4716.3  659.14  4726.3  658.48  4746.4  658.17  4836.4  658.18
  5016.6  653.91  5172.5  652.52  5173.3  651.72  5180.3  651.72  5181.0  652.52
  5216.8  653.03  5286.9  652.76  5326.9  653.38  5626.2  665.03  5659.8  666.08
#Mann=4,-1,0
  3833.1     0.1       0  5172.5    0.07       0  5181.0     0.1       0
  5626.2    0.05       0
Bank Sta=5172.5,5181
Exp/Cntr=0.3,0.1

Type RM Length L Ch R = 1,1086,275,275,275
BEGIN DESCRIPTION:
UNT 056 in HW 3.0
END DESCRIPTION:
XS GIS Cut Line= 3
      1989450.51     13602350.62      1989598.08     13601708.22
      1989534.71     13600532.86
#Sta/Elev= 30
  3693.8  668.71  3735.8  667.67  3741.0  668.14  3778.7  667.61  3802.2  668.53
  3821.5  668.18  3826.7  669.10  3853.5  668.01  3869.5  665.81  3874.7  666.06
  3912.4  664.50  3935.6  664.34  3966.3  663.08  4008.3  662.90  4088.9  661.26
  4222.6  660.37  4227.7  659.73  4275.7  659.03  4690.2  657.49  4786.8  656.22
  4957.0  652.35  5083.0  651.63  5083.7  650.83  5090.7  650.83  5091.5  651.63
  5207.4  652.27  5297.5  656.51  5432.3  661.34  5475.0  663.70  5530.0  666.21
#Mann=4,-1,0
  3693.8     0.1       0  5083.0    0.07       0  5091.5     0.1       0
  5475.0    0.05       0
Bank Sta=5083,5091.5
Exp/Cntr=0.3,0.1

Type RM Length L Ch R = 1,811,363,363,363
BEGIN DESCRIPTION:
UNT 056 in HW 2.0
END DESCRIPTION:
XS GIS Cut Line= 3
      1989475.02     13602324.95      1989835.35     13601231.63
      1989746.91     13600399.19
#Sta/Elev= 30
  3610.4  669.01  3689.8  669.81  3695.0  664.25  3705.1  663.94  3726.8  663.91
  3736.7  668.91  3747.2  669.44  3753.3  667.99  3778.8  665.88  3831.5  665.30
  3880.4  663.06  3912.1  663.36  3957.8  661.32  4115.7  658.86  4328.6  657.91
  4589.8  653.15  4716.8  651.85  4939.2  651.70  5009.0  649.67  5035.5  648.90
  5036.3  648.10  5044.0  648.90  5069.9  650.25  5180.5  649.40  5220.8  650.47
  5311.3  655.67  5378.4  661.99  5462.1  664.39  5573.6  671.94  5598.7  672.32
#Mann=5,-1,0
  3610.4     0.1       0  4328.6    0.05       0  5009.0     0.1       0
  5035.5   0.035       0  5044.0     0.1       0
Bank Sta=5035.5,5044
Exp/Cntr=0.3,0.1

Type RM Length L Ch R = 1,448,0,0,0
BEGIN DESCRIPTION:
UNT 056 in HW 1.0
END DESCRIPTION:
XS GIS Cut Line= 4
      1989595.74     13602153.54      1990127.02     13601387.88
      1990147.85     13600835.80      1989923.90     13600341.02
#Sta/Elev= 30
  3604.4  666.27  3631.2  666.41  3646.1  665.56  3681.9  664.82  3688.0  663.95
  3696.7  663.57  3724.3  663.51  3732.5  662.44  3783.2  661.40  3810.2  660.03
  3947.2  658.24  4099.3  655.88  4349.9  650.34  4489.2  648.05  4799.4  646.94
  4877.5  647.65  4939.5  647.06  5049.6  647.82  5162.3  646.85  5163.0  646.05
  5170.0  646.05  5170.8  646.85  5221.4  647.42  5279.7  650.32  5349.0  655.87
  5386.0  657.82  5418.3  660.64  5430.0  662.13  5550.7  666.21  5631.9  668.05
#Mann=5,-1,0
  3604.4     0.1       0  3947.2    0.05       0  4489.2     0.1       0
  5162.3    0.07       0  5170.8     0.1       0
Bank Sta=5162.3,5170.8
Exp/Cntr=0.3,0.1

Chan Stop Cuts=-1