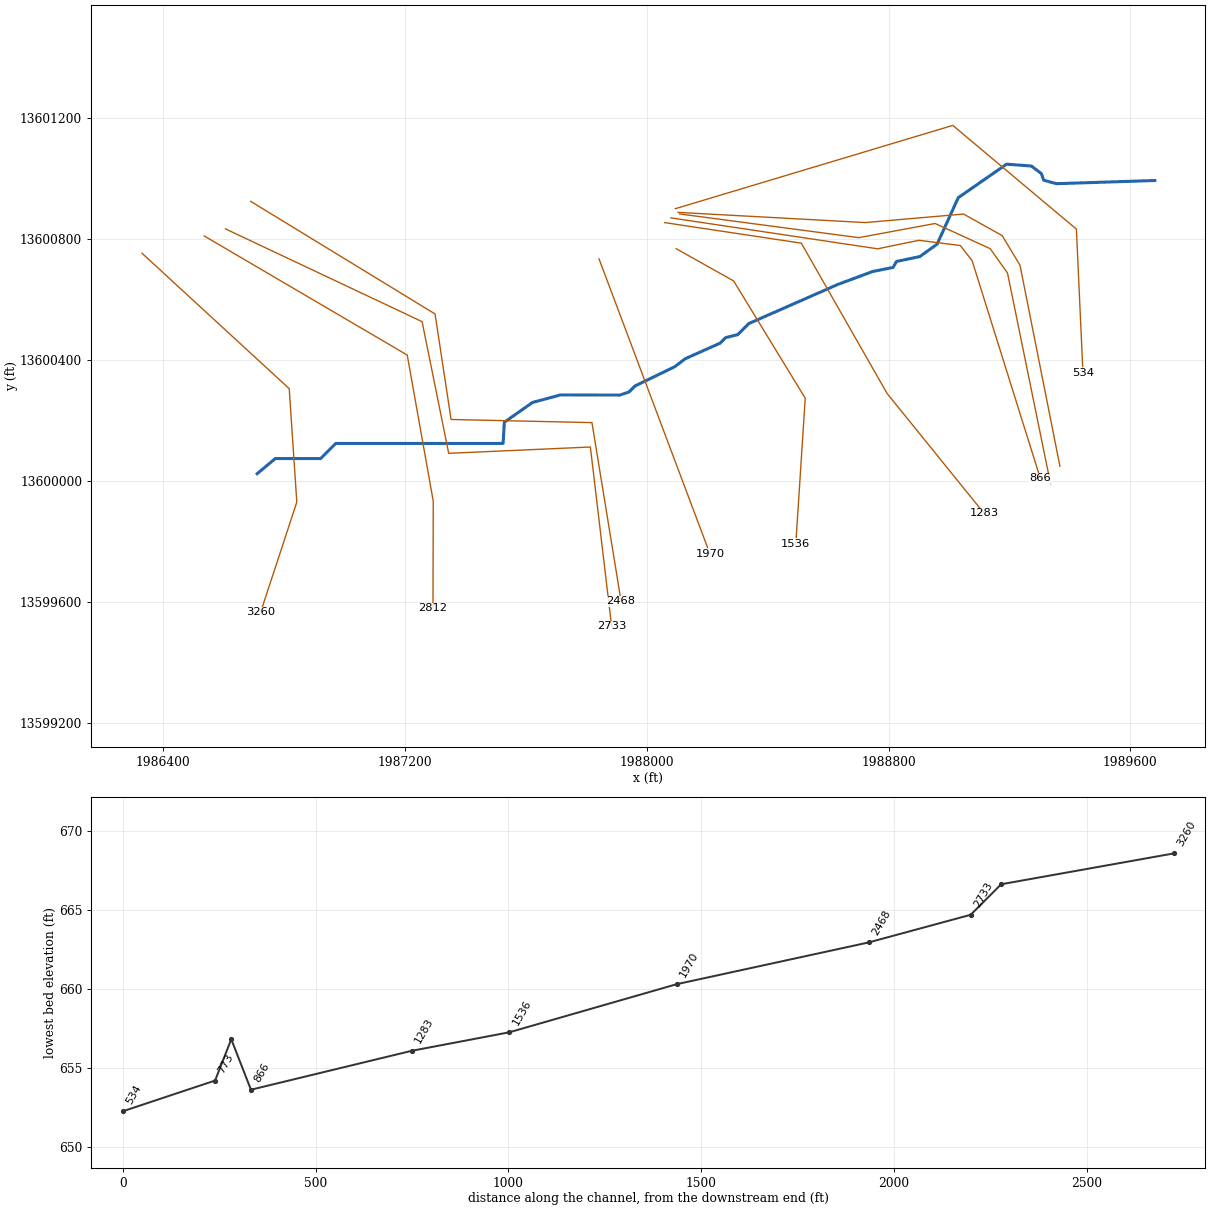
--- UNT 058 in HW.prj (project) ---

Proj Title=UNT 058 in HW Base Level Engineering
Current Plan=p01
Default Exp/Contr=0.3,0.1
English Units
Geom File=g01
Flow File=f01
Plan File=p01
BEGIN DESCRIPTION:
UNT 058 in HW
END DESCRIPTION:

--- UNT 058 in HW.p01 (plan) ---

Plan Title=Multiple Run
Short Identifier=Multiple
Geom File=g01
Flow File=f01
Subcritical Flow
K Sum by GR= 0
Std Step Tol= 0.01
Critical Tol= 0.01
Num of Std Step Trials= 20
Max Error Tol= 0.3
Flow Tol Ratio= 0.001
Split Flow NTrial= 30
Split Flow Tol= 0.02
Split Flow Ratio= 0.02
Log Output Level= 0
Friction Slope Method= 1
Unsteady Friction Slope Method= 2
Unsteady Bridges Friction Slope Method= 1
Parabolic Critical Depth
Global Vel Dist=  1 , 1 , 1
Global Log Level= 0
CheckData=True
Encroach Param= -1, 0, 0, 0
BEGIN DESCRIPTION:
Multiple Run
END DESCRIPTION:

--- UNT 058 in HW.f01 (steady flow) ---

Flow Title=Multiple
Number of Profiles=7
Profile Names=10-year,25-year,50-year,1pct_min,100-year,1pct_plu,500-year
River Rch & RM= UNT 058 in HW,Reach-1,3260
     634     908    1140     710    1418    2829    2198
River Rch & RM= UNT 058 in HW,Reach-1,2812
     911    1328    1690    1064    2123    4235    3364
Boundary for River Rch & Prof#=UNT 058 in HW,Reach-1,1
Up Type=0
Dn Type=3
Dn Slope=0.005
Boundary for River Rch & Prof#=UNT 058 in HW,Reach-1,2
Up Type=0
Dn Type=3
Dn Slope=0.005
Boundary for River Rch & Prof#=UNT 058 in HW,Reach-1,3
Up Type=0
Dn Type=3
Dn Slope=0.005
Boundary for River Rch & Prof#=UNT 058 in HW,Reach-1,4
Up Type=0
Dn Type=3
Dn Slope=0.005
Boundary for River Rch & Prof#=UNT 058 in HW,Reach-1,5
Up Type=0
Dn Type=3
Dn Slope=0.005
Boundary for River Rch & Prof#=UNT 058 in HW,Reach-1,6
Up Type=0
Dn Type=3
Dn Slope=0.005
Boundary for River Rch & Prof#=UNT 058 in HW,Reach-1,7
Up Type=0
Dn Type=3
Dn Slope=0.005

--- UNT 058 in HW.g01 (geometry) ---

Geom Title=Existing Conditions

River Reach=UNT 058 in HW,Reach-1
Reach XY= 30
      1986710.80     13600024.54      1986770.80     13600074.54
      1986920.80     13600074.54      1986970.80     13600124.54
      1987524.55     13600124.54      1987528.72     13600194.79
      1987621.78     13600260.07      1987714.14     13600285.07
      1987910.80     13600284.54      1987940.80     13600294.54
      1987960.80     13600314.54      1988092.61     13600378.47
      1988127.33     13600404.86      1988242.91     13600456.65
      1988260.80     13600474.54      1988300.80     13600484.54
      1988337.42     13600521.16      1988632.19     13600650.69
      1988747.12     13600693.40      1988814.83     13600706.94
      1988826.29     13600726.74      1988903.37     13600742.88
      1988960.67     13600784.03      1989030.46     13600937.67
      1989190.35     13601048.61      1989272.64     13601042.36
      1989305.46     13601017.36      1989313.27     13600995.49
      1989355.46     13600984.03      1989680.80     13600994.54

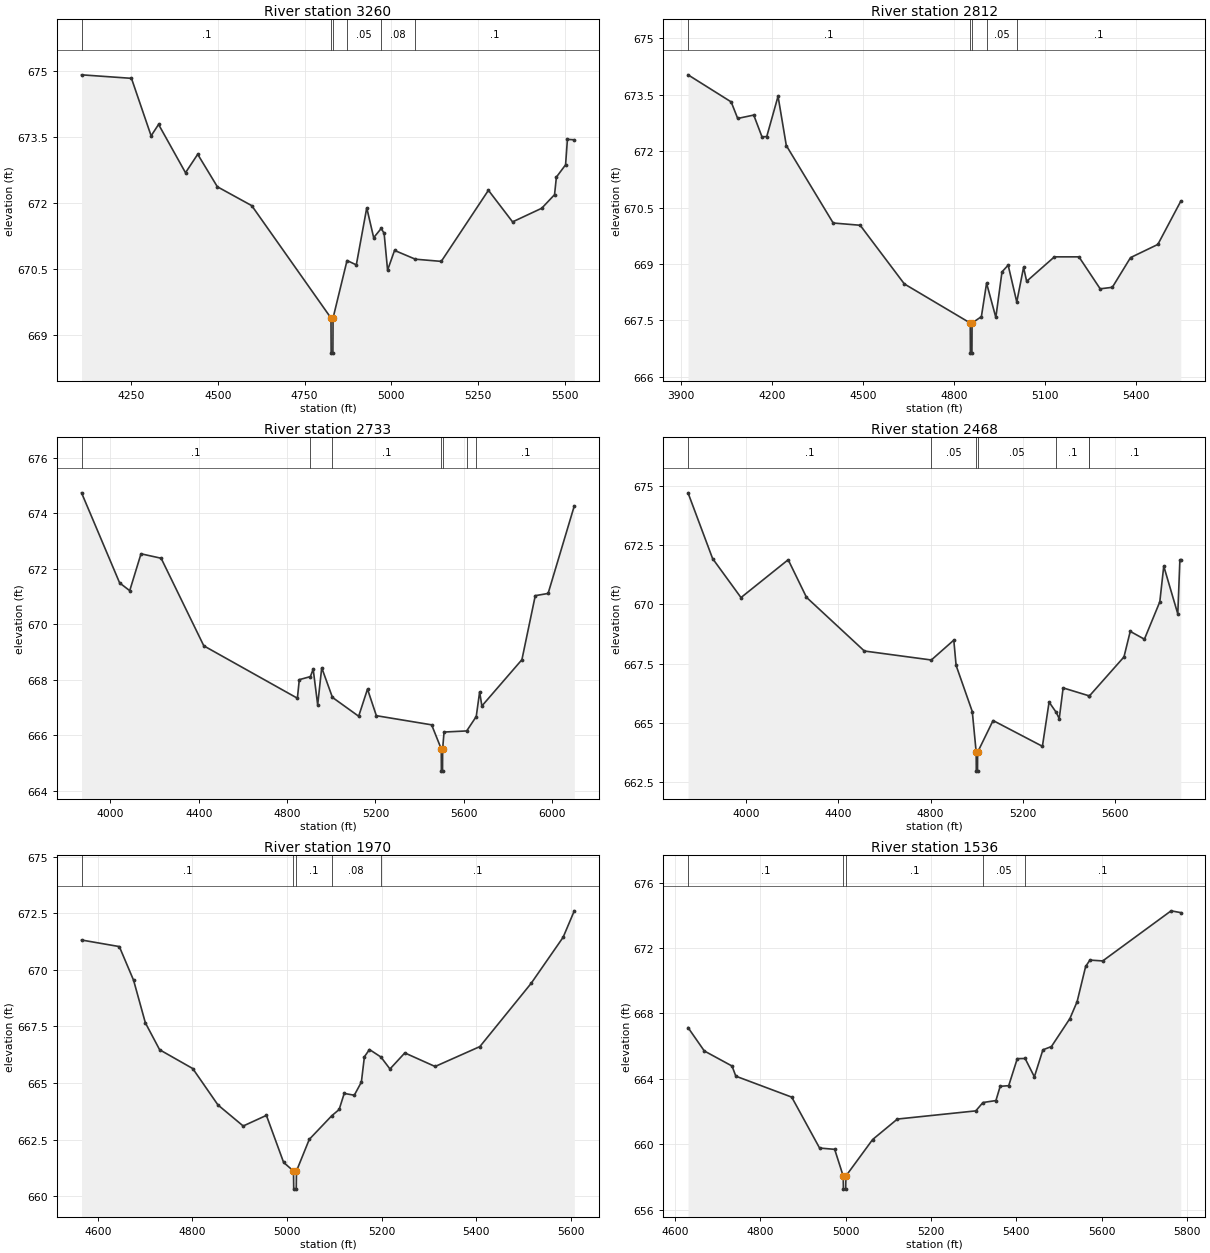
Type RM Length L Ch R = 1,3260,448,448,448
BEGIN DESCRIPTION:
UNT 058 in HW 1.0
END DESCRIPTION:
XS GIS Cut Line= 4
      1986329.97     13600753.70      1986816.93     13600305.81
      1986842.01     13599930.44      1986722.21     13599565.84
#Sta/Elev= 30
  4106.6  674.92  4250.6  674.84  4307.3  673.53  4328.8  673.79  4406.5  672.69
  4441.7  673.11  4498.4  672.37  4597.6  671.94  4826.2  669.38  4826.7  668.58
  4831.7  668.58  4832.2  669.38  4872.5  670.69  4899.3  670.59  4929.4  671.89
  4949.4  671.21  4971.0  671.42  4979.5  671.31  4989.5  670.47  5009.6  670.92
  5069.6  670.72  5144.4  670.67  5280.4  672.29  5350.1  671.57  5434.1  671.88
  5471.2  672.19  5476.5  672.59  5503.0  672.87  5508.3  673.45  5528.2  673.44
#Mann=6,-1,0
  4106.6     0.1       0  4826.2    0.07       0  4832.2     0.1       0
  4872.5    0.05       0  4971.0    0.08       0  5069.6     0.1       0
Bank Sta=4826.2,4832.2
Exp/Cntr=0.3,0.1

Type RM Length L Ch R = 1,2812,79,79,79
BEGIN DESCRIPTION:
UNT 058 in HW 2.0
END DESCRIPTION:
XS GIS Cut Line= 4
      1986535.67     13600811.02      1987207.37     13600417.01
      1987293.49     13599933.41      1987292.53     13599579.45
#Sta/Elev= 30
  3924.2  674.03  4066.4  673.31  4087.9  672.87  4140.8  672.96  4168.0  672.38
  4183.7  672.39  4220.9  673.46  4248.1  672.15  4402.6  670.09  4491.5  670.03
  4637.1  668.47  4854.3  667.43  4854.8  666.63  4859.8  666.63  4860.3  667.43
  4891.0  667.60  4908.1  668.49  4938.6  667.58  4958.9  668.79  4979.2  668.97
  5007.6  667.99  5030.0  668.91  5040.2  668.54  5131.6  669.19  5212.5  669.19
  5282.5  668.34  5322.5  668.38  5382.5  669.17  5472.5  669.52  5548.1  670.67
#Mann=5,-1,0
  3924.2     0.1       0  4854.3    0.04       0  4860.3     0.1       0
  4908.1    0.05       0  5007.6     0.1       0
Bank Sta=4854.3,4860.3
Exp/Cntr=0.3,0.1

Type RM Length L Ch R = 1,2733,265,265,265
BEGIN DESCRIPTION:
UNT 058 in HW 4.0
END DESCRIPTION:
XS GIS Cut Line= 5
      1986605.97     13600834.46      1987256.52     13600527.58
      1987344.61     13600091.90      1987813.36     13600112.74
      1987883.61     13599519.49
#Sta/Elev= 30
  3869.5  674.74  4041.9  671.49  4087.5  671.21  4138.6  672.54  4229.7  672.38
  4422.9  669.22  4846.5  667.33  4855.1  668.00  4905.3  668.11  4917.9  668.38
  4938.3  667.09  4956.6  668.43  5005.1  667.36  5123.8  666.68  5163.8  667.66
  5203.9  666.70  5454.1  666.37  5497.7  665.50  5498.2  664.70  5503.4  664.70
  5503.9  665.50  5510.3  666.11  5612.8  666.15  5656.0  666.67  5671.4  667.56
  5681.5  667.05  5862.7  668.72  5923.2  671.03  5981.3  671.11  6099.9  674.27
#Mann=7,-1,0
  3869.5     0.1       0  4905.3    0.05       0  5005.1     0.1       0
  5497.7    0.04       0  5503.9     0.1       0  5612.8    0.16       0
  5656.0     0.1       0
Bank Sta=5497.7,5503.9
Exp/Cntr=0.3,0.1

Type RM Length L Ch R = 1,2468,498,498,498
BEGIN DESCRIPTION:
UNT 058 in HW 3.0
END DESCRIPTION:
XS GIS Cut Line= 5
      1986689.34     13600925.59      1987299.47     13600552.92
      1987352.42     13600203.88      1987818.57     13600193.47
      1987914.93     13599602.30
#Sta/Elev= 30
  3750.1  674.72  3856.5  671.94  3979.4  670.29  4183.7  671.89  4263.0  670.30
  4513.5  668.03  4803.4  667.65  4900.7  668.49  4910.7  667.42  4980.7  665.47
  4997.6  663.75  4998.1  662.95  5003.3  662.95  5003.8  663.75  5070.7  665.09
  5284.3  664.00  5313.2  665.87  5343.7  665.44  5357.1  665.17  5374.0  666.47
  5487.8  666.13  5487.8  666.13  5637.4  667.78  5664.5  668.86  5725.9  668.53
  5792.5  670.11  5809.6  671.62  5870.4  669.60  5879.4  671.87  5883.3  671.87
#Mann=7,-1,0
  3750.1     0.1       0  4803.4    0.05       0  4997.6    0.04       0
  5003.8    0.05       0  5343.7     0.1       0  5487.8    0.16       0
  5487.8     0.1       0
Bank Sta=4997.6,5003.8
Exp/Cntr=0.3,0.1

Type RM Length L Ch R = 1,1970,434,434,434
BEGIN DESCRIPTION:
UNT 058 in HW 5.0
END DESCRIPTION:
XS GIS Cut Line= 2
      1987842.02     13600735.11      1988208.92     13599759.31
#Sta/Elev= 30
  4565.3  671.32  4645.2  671.03  4675.4  669.54  4700.3  667.66  4730.5  666.47
  4800.5  665.64  4853.9  664.03  4907.3  663.10  4956.4  663.57  4992.8  661.49
  5013.7  661.11  5014.2  660.31  5019.5  660.31  5020.0  661.11  5047.1  662.51
  5094.5  663.55  5110.3  663.83  5121.0  664.54  5142.3  664.46  5157.3  665.04
  5163.7  666.16  5174.4  666.48  5198.6  666.15  5217.8  665.62  5249.2  666.33
  5313.3  665.73  5408.0  666.61  5516.3  669.40  5584.1  671.44  5607.8  672.61
#Mann=5,-1,0
  4565.3     0.1       0  5013.7    0.07       0  5020.0     0.1       0
  5094.5    0.08       0  5198.6     0.1       0
Bank Sta=5013.7,5020
Exp/Cntr=0.3,0.1

Type RM Length L Ch R = 1,1536,253,253,253
BEGIN DESCRIPTION:
UNT 058 in HW 6.0
END DESCRIPTION:
XS GIS Cut Line= 4
      1988097.24     13600768.97      1988287.32     13600662.22
      1988524.30     13600274.19      1988493.05     13599792.38
#Sta/Elev= 30
  4630.2  667.14  4668.4  665.71  4733.4  664.79  4742.3  664.17  4873.4  662.89
  4938.7  659.78  4974.1  659.70  4994.1  658.07  4994.6  657.27  4999.9  657.27
  5000.4  658.07  5063.1  660.30  5121.1  661.55  5305.0  662.05  5321.8  662.56
  5352.2  662.68  5362.2  663.55  5382.2  663.59  5402.3  665.24  5420.7  665.25
  5442.4  664.13  5462.4  665.78  5482.4  665.98  5525.7  667.69  5542.6  668.72
  5562.6  670.87  5572.6  671.26  5602.7  671.21  5763.0  674.27  5785.7  674.16
#Mann=5,-1,0
  4630.2     0.1       0  4994.1    0.07       0  5000.4     0.1       0
  5321.8    0.05       0  5420.7     0.1       0
Bank Sta=4994.1,5000.4
Exp/Cntr=0.3,0.1

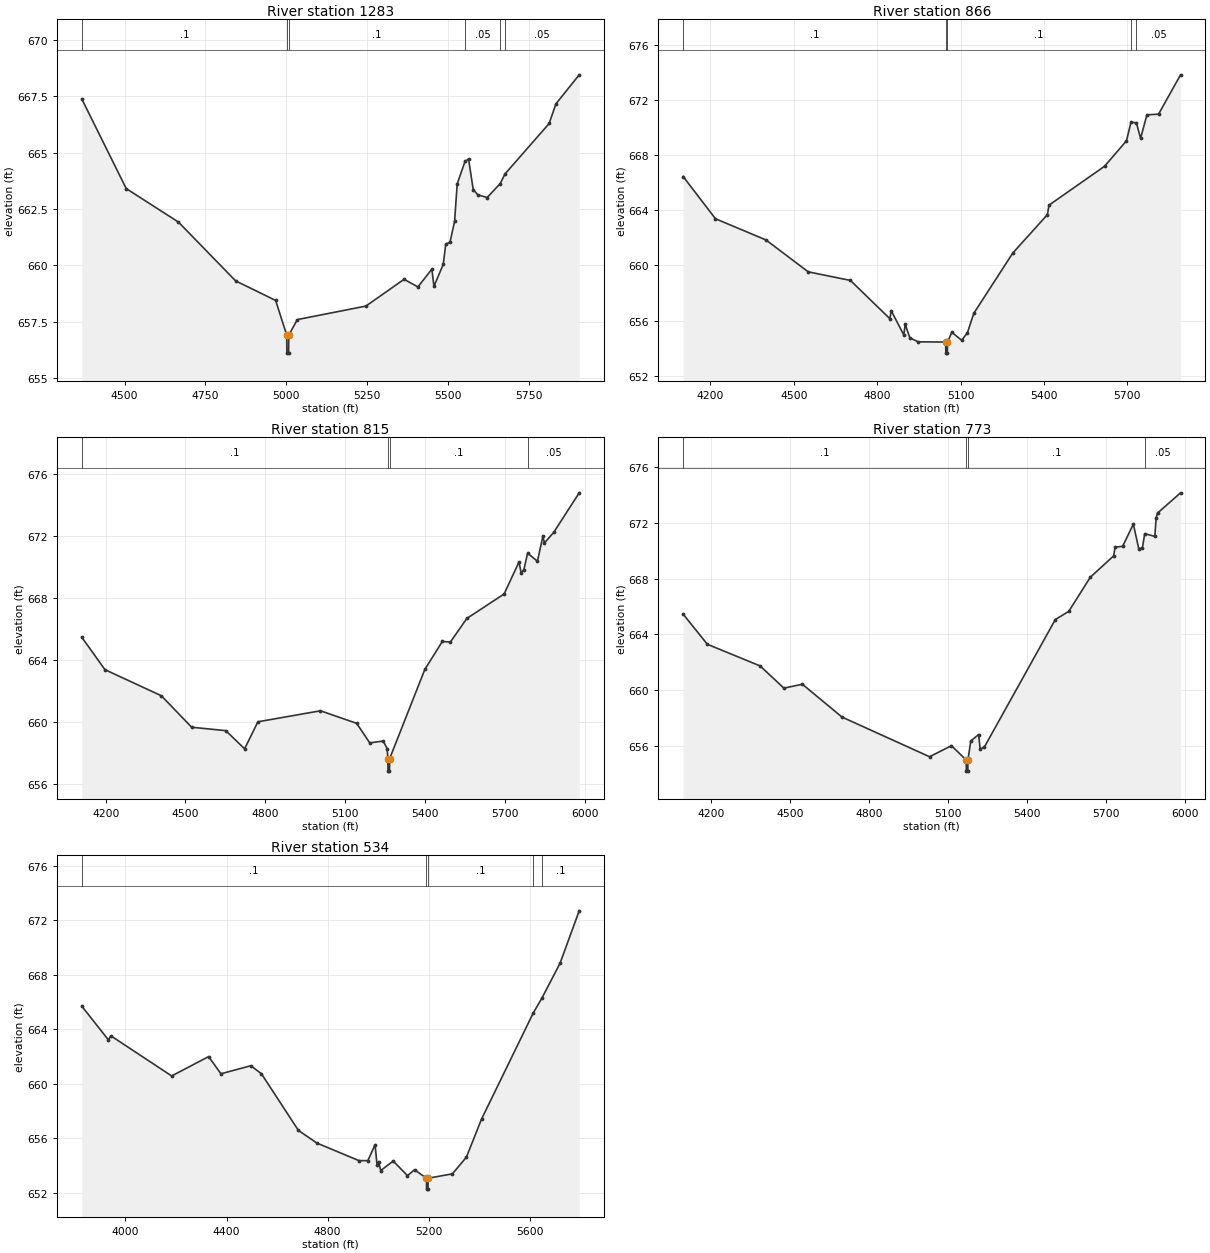
Type RM Length L Ch R = 1,1283,417,417,417
BEGIN DESCRIPTION:
UNT 058 in HW 7.0
END DESCRIPTION:
XS GIS Cut Line= 4
      1988059.15     13600855.28      1988511.28     13600787.22
      1988795.13     13600289.82      1989115.43     13599894.00
#Sta/Elev= 30
  4367.3  667.39  4504.7  663.41  4666.4  661.92  4843.2  659.31  4967.1  658.44
  5001.4  656.90  5001.9  656.10  5007.2  656.10  5007.7  656.90  5034.3  657.59
  5246.5  658.19  5364.6  659.38  5407.4  659.04  5450.5  659.83  5457.0  659.07
  5485.7  660.04  5493.5  660.94  5506.5  661.02  5520.9  661.96  5528.9  663.62
  5553.3  664.62  5564.1  664.72  5578.5  663.36  5592.8  663.13  5621.6  663.01
  5662.0  663.63  5676.9  664.06  5813.5  666.30  5834.3  667.17  5906.4  668.46
#Mann=6,-1,0
  4367.3     0.1       0  5001.4    0.07       0  5007.7     0.1       0
  5553.3    0.05       0  5662.0    0.08       0  5676.9    0.05       0
Bank Sta=5001.4,5007.7
Exp/Cntr=0.3,0.1

Type RM Length L Ch R = 1,866,51,51,51
BEGIN DESCRIPTION:
UNT 058 in HW 9.0
END DESCRIPTION:
XS GIS Cut Line= 6
      1988079.99     13600870.90      1988763.88     13600768.55
      1988900.60     13600796.76      1989037.32     13600779.40
      1989076.38     13600729.49      1989301.92     13600009.51
#Sta/Elev= 30
  4102.3  666.44  4218.6  663.38  4400.6  661.84  4552.3  659.53  4703.9  658.91
  4845.7  656.14  4850.8  656.71  4895.9  654.96  4901.1  655.74  4917.5  654.75
  4947.8  654.46  5046.6  654.44  5047.1  653.64  5052.6  653.64  5053.1  654.44
  5068.7  655.15  5104.2  654.57  5125.0  655.13  5147.8  656.53  5288.2  660.90
  5412.6  663.68  5417.9  664.36  5617.8  667.18  5696.9  669.03  5713.0  670.38
  5732.5  670.33  5747.6  669.21  5770.3  670.91  5812.2  670.96  5891.3  673.81
#Mann=5,-1,0
  4102.3     0.1       0  5046.6    0.07       0  5053.1     0.1       0
  5713.0    0.08       0  5732.5    0.05       0
Bank Sta=5046.6,5053.1
Exp/Cntr=0.3,0.1

Type RM Length L Ch R = 1,815,42,42,42
BEGIN DESCRIPTION:
UNT 058 in HW 8.0
END DESCRIPTION:
XS GIS Cut Line= 6
      1988108.64     13600883.92      1988701.38     13600805.44
      1988953.99     13600852.32      1989136.28     13600768.99
      1989193.57     13600688.26      1989335.94     13599991.18
#Sta/Elev= 30
  4110.3  665.46  4197.4  663.37  4409.2  661.69  4523.2  659.66  4651.3  659.44
  4722.2  658.27  4772.1  660.01  5007.3  660.72  5143.3  659.91  5192.5  658.65
  5243.0  658.77  5257.8  658.28  5260.6  657.63  5261.1  656.83  5266.6  656.83
  5267.1  657.63  5399.5  663.39  5465.3  665.19  5495.4  665.15  5557.1  666.67
  5697.4  668.25  5753.1  670.31  5761.3  669.63  5771.5  669.81  5785.6  670.88
  5822.5  670.36  5842.9  671.96  5849.0  671.54  5883.7  672.22  5979.5  674.77
#Mann=4,-1,0
  4110.3     0.1       0  5260.6    0.07       0  5267.1     0.1       0
  5785.6    0.05       0
Bank Sta=5260.6,5267.1
Exp/Cntr=0.3,0.1

Type RM Length L Ch R = 1,773,239,239,239
BEGIN DESCRIPTION:
UNT 058 in HW 10.0
END DESCRIPTION:
XS GIS Cut Line= 6
      1988103.34     13600889.14      1988722.65     13600855.36
      1989048.17     13600883.57      1989176.21     13600811.96
      1989234.80     13600714.30      1989366.99     13600049.08
#Sta/Elev= 30
  4095.1  665.46  4186.9  663.30  4387.2  661.75  4477.3  660.16  4547.4  660.44
  4697.7  658.09  5029.8  655.25  5112.8  656.04  5168.9  655.02  5169.4  654.22
  5174.9  654.22  5175.4  655.02  5186.1  656.37  5215.9  656.84  5221.7  655.80
  5237.3  655.93  5506.9  665.07  5558.0  665.66  5639.6  668.10  5728.3  669.63
  5733.4  670.25  5762.1  670.31  5802.8  671.90  5823.2  670.15  5836.9  670.18
  5846.0  671.22  5884.2  671.02  5889.4  672.36  5894.5  672.69  5981.8  674.14
#Mann=4,-1,0
  4095.1     0.1       0  5168.9    0.07       0  5175.4     0.1       0
  5846.0    0.05       0
Bank Sta=5168.9,5175.4
Exp/Cntr=0.3,0.1

Type RM Length L Ch R = 1,534,0,0,0
BEGIN DESCRIPTION:
UNT 058 in HW 11.0
END DESCRIPTION:
XS GIS Cut Line= 4
      1988094.45     13600901.28      1989012.46     13601176.90
      1989421.43     13600833.66      1989443.10     13600359.17
#Sta/Elev= 30
  3827.6  665.70  3932.6  663.23  3943.0  663.52  4183.2  660.58  4329.3  662.00
  4377.9  660.74  4496.4  661.33  4538.2  660.74  4684.3  656.59  4757.2  655.66
  4923.9  654.37  4959.1  654.37  4987.6  655.54  4995.4  654.06  5001.9  654.30
  5009.7  653.64  5059.2  654.34  5115.8  653.27  5143.7  653.70  5190.9  653.08
  5191.4  652.28  5196.9  652.28  5197.4  653.08  5293.3  653.40  5348.7  654.62
  5408.8  657.42  5613.0  665.19  5647.5  666.29  5719.1  668.84  5795.0  672.69
#Mann=5,-1,0
  3827.6     0.1       0  5190.9    0.07       0  5197.4     0.1       0
  5613.0    0.05       0  5647.5     0.1       0
Bank Sta=5190.9,5197.4
Exp/Cntr=0.3,0.1

Chan Stop Cuts=-1