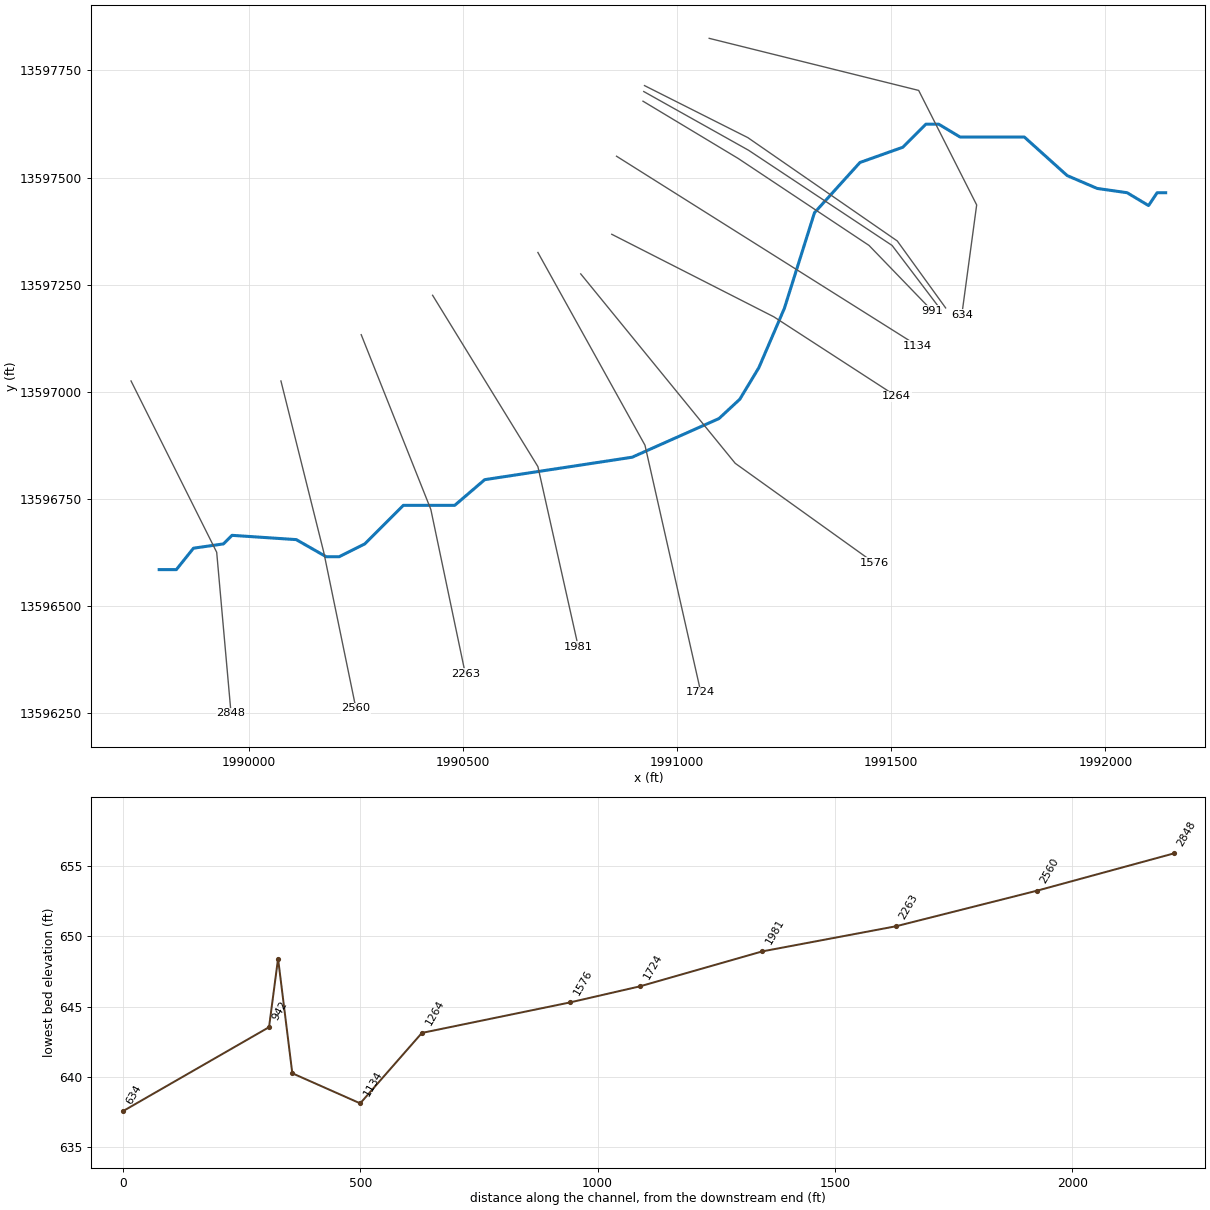
--- UNT 059 in HW.prj (project) ---

Proj Title=UNT 059 in HW Base Level Engineering
Current Plan=p01
Default Exp/Contr=0.3,0.1
English Units
Geom File=g01
Flow File=f01
Plan File=p01
BEGIN DESCRIPTION:
UNT 059 in HW
END DESCRIPTION:

--- UNT 059 in HW.p01 (plan) ---

Plan Title=Multiple Run
Short Identifier=Multiple
Geom File=g01
Flow File=f01
Subcritical Flow
K Sum by GR= 0
Std Step Tol= 0.01
Critical Tol= 0.01
Num of Std Step Trials= 20
Max Error Tol= 0.3
Flow Tol Ratio= 0.001
Split Flow NTrial= 30
Split Flow Tol= 0.02
Split Flow Ratio= 0.02
Log Output Level= 0
Friction Slope Method= 1
Unsteady Friction Slope Method= 2
Unsteady Bridges Friction Slope Method= 1
Parabolic Critical Depth
Global Vel Dist=  1 , 1 , 1
Global Log Level= 0
CheckData=True
Encroach Param= -1, 0, 0, 0
BEGIN DESCRIPTION:
Multiple Run
END DESCRIPTION:

--- UNT 059 in HW.f01 (steady flow) ---

Flow Title=Multiple
Number of Profiles=7
Profile Names=10-year,25-year,50-year,1pct_min,100-year,1pct_plu,500-year
River Rch & RM= UNT 059 in HW,Reach-1,2848
     376     515     629     381     760    1517    1113
Boundary for River Rch & Prof#=UNT 059 in HW,Reach-1,1
Up Type=0
Dn Type=3
Dn Slope=0.005
Boundary for River Rch & Prof#=UNT 059 in HW,Reach-1,2
Up Type=0
Dn Type=3
Dn Slope=0.005
Boundary for River Rch & Prof#=UNT 059 in HW,Reach-1,3
Up Type=0
Dn Type=3
Dn Slope=0.005
Boundary for River Rch & Prof#=UNT 059 in HW,Reach-1,4
Up Type=0
Dn Type=3
Dn Slope=0.005
Boundary for River Rch & Prof#=UNT 059 in HW,Reach-1,5
Up Type=0
Dn Type=3
Dn Slope=0.005
Boundary for River Rch & Prof#=UNT 059 in HW,Reach-1,6
Up Type=0
Dn Type=3
Dn Slope=0.005
Boundary for River Rch & Prof#=UNT 059 in HW,Reach-1,7
Up Type=0
Dn Type=3
Dn Slope=0.005

--- UNT 059 in HW.g01 (geometry) ---

Geom Title=Existing Conditions

River Reach=UNT 059 in HW,Reach-1
Reach XY= 30
      1989790.80     13596584.54      1989830.80     13596584.54
      1989870.80     13596634.54      1989940.80     13596644.54
      1989960.80     13596664.54      1990110.80     13596654.54
      1990180.80     13596614.54      1990210.80     13596614.54
      1990270.80     13596644.54      1990360.80     13596734.54
      1990480.80     13596734.54      1990550.80     13596794.54
      1990895.06     13596846.94      1991097.84     13596937.22
      1991146.45     13596982.36      1991190.89     13597055.97
      1991250.62     13597194.86      1991320.76     13597417.78
      1991427.01     13597535.14      1991526.91     13597570.65
      1991580.80     13597624.54      1991610.80     13597624.54
      1991660.80     13597594.54      1991810.80     13597594.54
      1991910.80     13597504.54      1991980.80     13597474.54
      1992050.80     13597464.54      1992100.80     13597434.54
      1992120.80     13597464.54      1992140.80     13597464.54

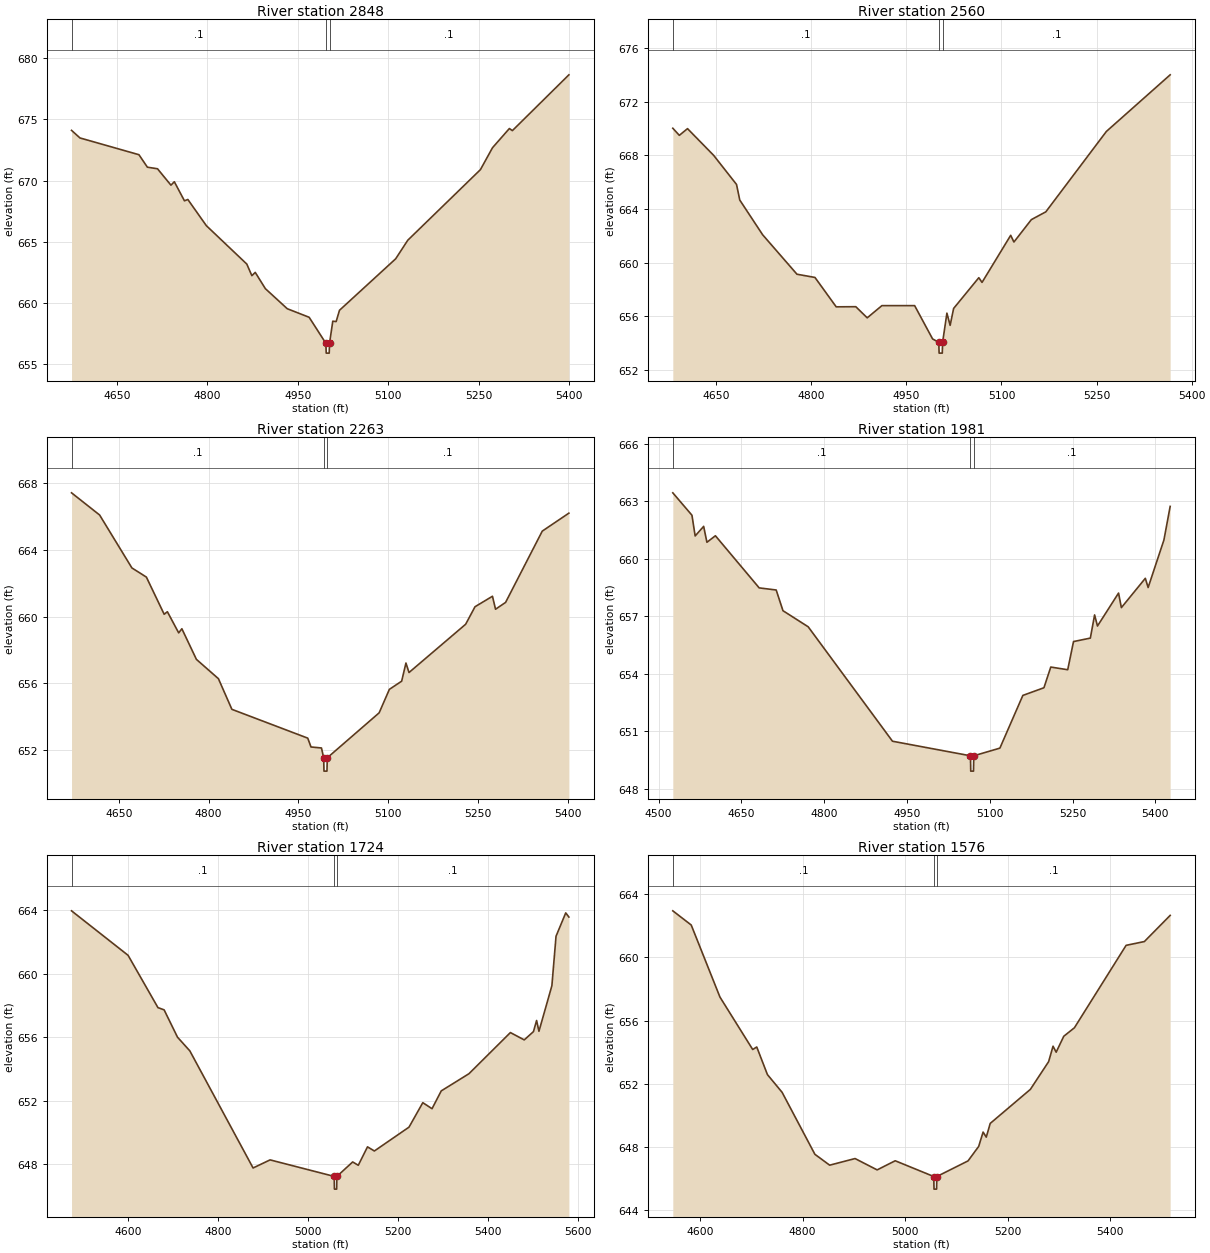
Type RM Length L Ch R = 1,2848,288,288,288
BEGIN DESCRIPTION:
UNT 059 in HW 9.0
END DESCRIPTION:
XS GIS Cut Line= 3
      1989724.99     13597025.03      1989925.00     13596625.00
      1989958.50     13596248.83
#Sta/Elev= 30
  4574.6  674.11  4588.6  673.49  4686.4  672.12  4700.4  671.10  4717.2  670.97
  4739.5  669.63  4745.1  669.91  4761.9  668.35  4767.5  668.46  4798.2  666.32
  4865.3  663.18  4873.7  662.23  4879.3  662.50  4896.1  661.17  4932.4  659.53
  4968.7  658.83  4996.5  656.70  4997.0  655.90  5002.0  655.90  5002.5  656.70
  5007.9  658.51  5013.5  658.48  5019.0  659.40  5112.2  663.61  5132.3  665.13
  5252.8  670.90  5272.8  672.69  5300.8  674.26  5305.8  674.09  5399.5  678.65
#Mann=3,-1,0
  4574.6     0.1       0  4996.5    0.07       0  5002.5     0.1       0
Bank Sta=4996.5,5002.5
Exp/Cntr=0.3,0.1

Type RM Length L Ch R = 1,2560,297,297,297
BEGIN DESCRIPTION:
UNT 059 in HW 8.0
END DESCRIPTION:
XS GIS Cut Line= 3
      1990075.00     13597024.99      1990175.00     13596625.00
      1990250.11     13596260.56
#Sta/Elev= 30
  4581.7  670.01  4592.0  669.48  4604.9  669.98  4646.1  667.99  4682.2  665.82
  4687.3  664.66  4723.4  662.07  4777.5  659.13  4805.9  658.89  4839.4  656.70
  4870.3  656.71  4888.3  655.88  4911.5  656.79  4963.1  656.79  4991.4  654.31
  5001.2  654.05  5001.7  653.25  5006.7  653.25  5007.2  654.05  5014.0  656.23
  5019.1  655.32  5024.6  656.58  5064.3  658.87  5069.4  658.52  5114.6  662.03
  5119.7  661.53  5147.2  663.20  5170.0  663.78  5265.5  669.77  5366.1  673.99
#Mann=3,-1,0
  4581.7     0.1       0  5001.2    0.07       0  5007.2     0.1       0
Bank Sta=5001.2,5007.2
Exp/Cntr=0.3,0.1

Type RM Length L Ch R = 1,2263,282,282,282
BEGIN DESCRIPTION:
UNT 059 in HW 7.0
END DESCRIPTION:
XS GIS Cut Line= 3
      1990262.42     13597133.07      1990425.00     13596725.00
      1990505.48     13596341.42
#Sta/Elev= 30
  4571.0  667.43  4617.9  666.10  4671.9  662.92  4696.1  662.37  4725.8  660.14
  4731.2  660.29  4750.1  659.02  4755.4  659.27  4779.7  657.43  4816.5  656.27
  4839.0  654.43  4965.8  652.70  4971.2  652.17  4988.7  652.11  4992.4  651.52
  4992.9  650.72  4997.9  650.72  4998.4  651.52  5085.1  654.22  5102.2  655.63
  5122.7  656.12  5129.9  657.21  5135.0  656.64  5229.7  659.54  5245.3  660.59
  5274.5  661.22  5279.6  660.44  5296.4  660.85  5357.7  665.13  5402.2  666.21
#Mann=3,-1,0
  4571.0     0.1       0  4992.4    0.07       0  4998.4     0.1       0
Bank Sta=4992.4,4998.4
Exp/Cntr=0.3,0.1

Type RM Length L Ch R = 1,1981,257,257,257
BEGIN DESCRIPTION:
UNT 059 in HW 6.0
END DESCRIPTION:
XS GIS Cut Line= 3
      1990429.11     13597225.06      1990675.00     13596825.00
      1990769.36     13596403.93
#Sta/Elev= 30
  4525.7  663.45  4560.4  662.28  4566.2  661.20  4581.6  661.70  4587.5  660.87
  4602.9  661.21  4682.2  658.49  4713.0  658.38  4725.3  657.30  4771.0  656.46
  4923.7  650.49  5065.0  649.73  5065.5  648.93  5070.5  648.93  5071.0  649.73
  5118.3  650.13  5159.9  652.88  5198.1  653.28  5210.5  654.36  5241.2  654.22
  5251.7  655.69  5282.2  655.87  5289.9  657.08  5295.1  656.50  5333.3  658.22
  5338.4  657.46  5381.8  658.99  5386.9  658.51  5415.5  660.99  5426.8  662.74
#Mann=3,-1,0
  4525.7     0.1       0  5065.0    0.07       0  5071.0     0.1       0
Bank Sta=5065,5071
Exp/Cntr=0.3,0.1

Type RM Length L Ch R = 1,1724,148,148,148
BEGIN DESCRIPTION:
UNT 059 in HW 5.0
END DESCRIPTION:
XS GIS Cut Line= 3
      1990675.00     13597325.00      1990925.00     13596875.00
      1991055.40     13596298.14
#Sta/Elev= 30
  4473.9  663.96  4599.7  661.16  4666.1  657.87  4679.8  657.73  4709.6  656.01
  4737.0  655.15  4877.7  647.78  4915.5  648.29  5058.1  647.25  5058.6  646.45
  5063.6  646.45  5064.1  647.25  5099.2  648.16  5111.7  647.95  5132.2  649.11
  5147.5  648.85  5224.5  650.35  5255.2  651.89  5275.7  651.51  5296.2  652.63
  5357.8  653.71  5450.0  656.30  5480.8  655.84  5501.3  656.36  5508.3  657.06
  5513.5  656.38  5542.3  659.25  5551.5  662.36  5573.1  663.83  5580.1  663.57
#Mann=3,-1,0
  4473.9     0.1       0  5058.1    0.07       0  5064.1     0.1       0
Bank Sta=5058.1,5064.1
Exp/Cntr=0.3,0.1

Type RM Length L Ch R = 1,1576,312,312,312
BEGIN DESCRIPTION:
UNT 059 in HW 4.0
END DESCRIPTION:
XS GIS Cut Line= 3
      1990775.02     13597274.97      1991135.69     13596832.73
      1991460.21     13596600.18
#Sta/Elev= 30
  4546.8  662.96  4582.7  662.06  4638.7  657.49  4702.6  654.16  4710.5  654.32
  4731.3  652.57  4760.0  651.44  4823.9  647.51  4852.7  646.82  4902.2  647.24
  4945.3  646.52  4980.5  647.10  5055.7  646.10  5056.2  645.30  5061.2  645.30
  5061.7  646.10  5122.5  647.09  5143.3  648.01  5151.9  648.92  5158.1  648.60
  5165.8  649.47  5244.1  651.63  5279.7  653.39  5288.3  654.37  5294.4  653.99
  5309.2  655.00  5330.0  655.54  5430.8  660.77  5466.4  661.01  5516.7  662.67
#Mann=3,-1,0
  4546.8     0.1       0  5055.7    0.07       0  5061.7     0.1       0
Bank Sta=5055.7,5061.7
Exp/Cntr=0.3,0.1

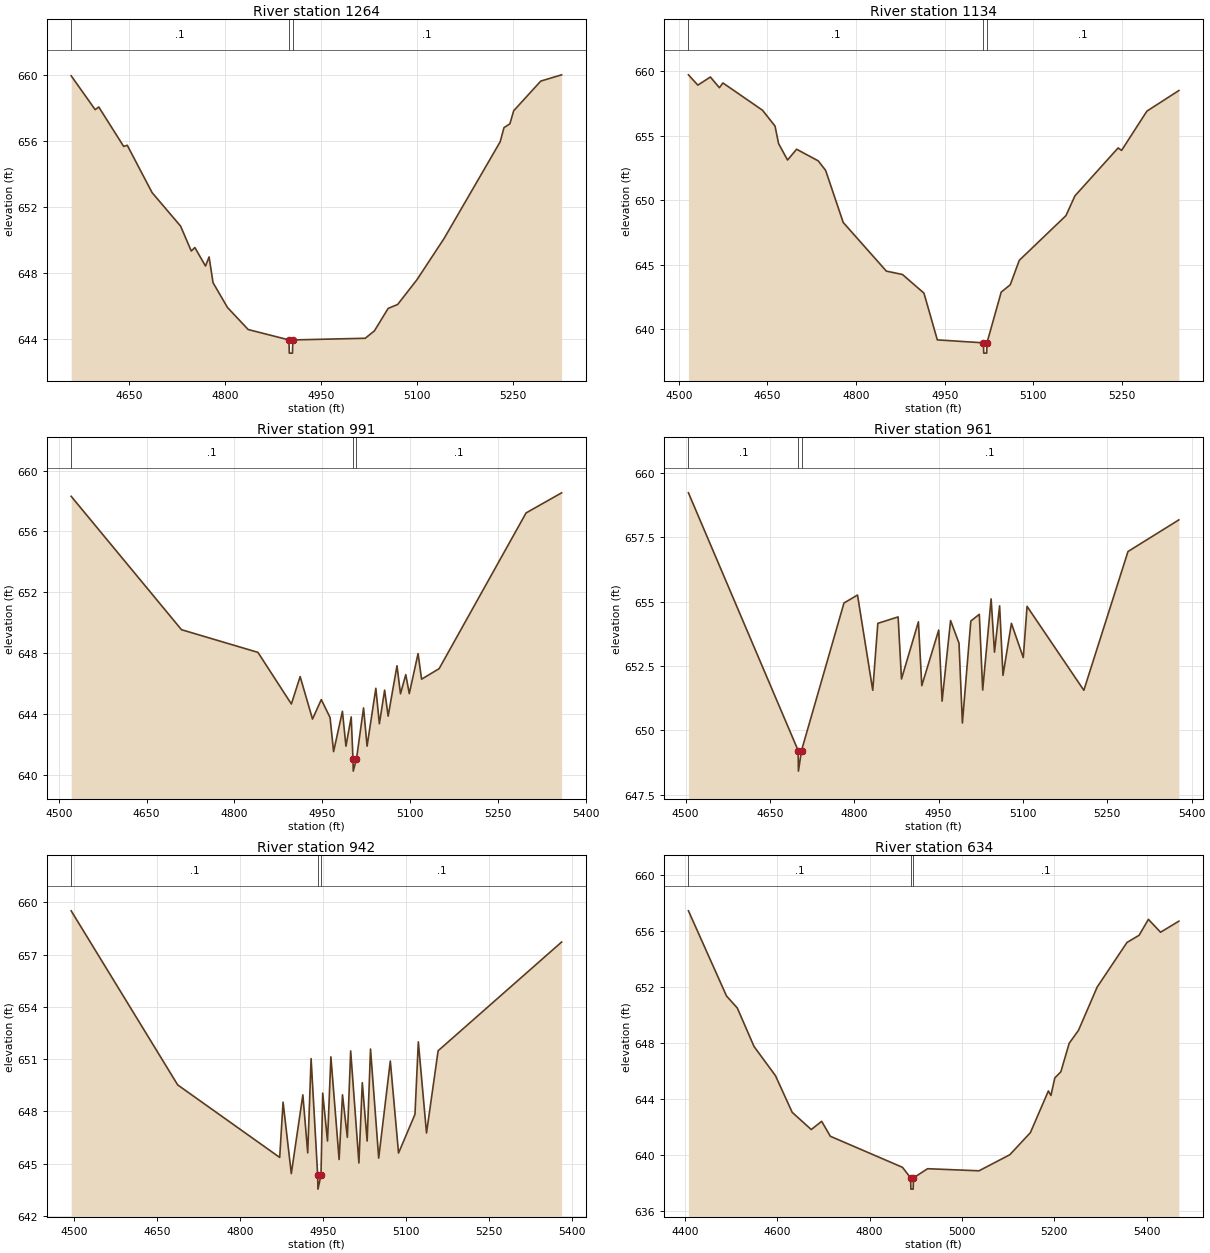
Type RM Length L Ch R = 1,1264,130,130,130
BEGIN DESCRIPTION:
UNT 059 in HW 3.0
END DESCRIPTION:
XS GIS Cut Line= 3
      1990847.48     13597367.46      1991225.96     13597174.74
      1991512.39     13596989.00
#Sta/Elev= 30
  4559.5  659.94  4597.0  657.89  4602.6  658.05  4641.5  655.66  4647.1  655.73
  4685.9  652.86  4730.4  650.83  4747.1  649.32  4752.7  649.53  4769.3  648.41
  4774.9  648.96  4781.1  647.40  4803.6  645.90  4836.0  644.56  4899.7  643.93
  4900.2  643.13  4905.2  643.13  4905.7  643.93  5018.8  644.03  5033.2  644.48
  5054.6  645.84  5069.5  646.08  5099.8  647.59  5142.0  650.08  5229.6  655.94
  5235.6  656.80  5244.8  657.03  5250.7  657.82  5293.0  659.62  5325.6  660.00
#Mann=3,-1,0
  4559.5     0.1       0  4899.7    0.07       0  4905.7     0.1       0
Bank Sta=4899.7,4905.7
Exp/Cntr=0.3,0.1

Type RM Length L Ch R = 1,1134,143,143,143
BEGIN DESCRIPTION:
Mapping XS 063a0bb4
END DESCRIPTION:
XS GIS Cut Line= 2
      1990858.62     13597549.73      1991560.82     13597107.61
#Sta/Elev= 30
  4516.4  659.74  4532.3  658.94  4553.5  659.57  4568.8  658.74  4574.7  659.11
  4641.7  656.99  4662.9  655.76  4668.9  654.40  4684.1  653.12  4699.4  653.96
  4735.9  653.06  4748.5  652.32  4778.3  648.27  4851.3  644.49  4878.5  644.23
  4914.9  642.78  4937.5  639.15  5015.5  638.92  5016.0  638.12  5021.0  638.12
  5021.5  638.92  5045.6  642.86  5060.9  643.43  5076.2  645.33  5155.1  648.80
  5170.4  650.34  5243.4  654.06  5249.3  653.87  5292.1  656.92  5346.2  658.52
#Mann=3,-1,0
  4516.4     0.1       0  5015.5    0.07       0  5021.5     0.1       0
Bank Sta=5015.5,5021.5
Exp/Cntr=0.3,0.1

Type RM Length L Ch R = 1,991,30,30,30
BEGIN DESCRIPTION:
Mapping XS ba453ef3
END DESCRIPTION:
XS GIS Cut Line= 4
      1990920.40     13597678.22      1991142.63     13597544.54
      1991448.19     13597341.41      1991595.09     13597189.33
#Sta/Elev= 30
  4521.1  658.31  4709.5  649.55  4840.1  648.06  4897.2  644.67  4912.2  646.47
  4933.3  643.68  4948.3  644.96  4963.3  643.78  4969.3  641.54  4984.4  644.19
  4990.4  641.90  4999.4  643.82  5002.4  641.06  5002.9  640.26  5008.4  641.06
  5020.5  644.41  5026.5  641.90  5041.5  645.70  5047.5  643.37  5056.5  645.58
  5062.5  643.87  5077.6  647.18  5083.6  645.34  5092.6  646.60  5098.6  645.35
  5113.6  647.98  5119.6  646.30  5149.6  646.99  5298.1  657.22  5358.8  658.54
#Mann=3,-1,0
  4521.1     0.1       0  5002.4    0.07       0  5008.4     0.1       0
Bank Sta=5002.4,5008.4
Exp/Cntr=0.3,0.1

Type RM Length L Ch R = 1,961,19,19,19
BEGIN DESCRIPTION:
Mapping XS 7a14014d
END DESCRIPTION:
XS GIS Cut Line= 4
      1990922.17     13597700.77      1991166.94     13597563.63
      1991502.00     13597341.41      1991616.58     13597190.38
#Sta/Elev= 30
  4505.1  659.23  4700.2  649.22  4700.7  648.42  4706.2  649.22  4781.7  654.95
  4805.8  655.26  4832.9  651.56  4841.9  654.16  4878.0  654.41  4884.0  652.00
  4914.1  654.22  4920.1  651.74  4950.2  653.90  4956.2  651.14  4971.3  654.27
  4986.3  653.39  4992.3  650.29  5007.3  654.25  5022.4  654.51  5028.4  651.57
  5043.4  655.11  5049.4  653.04  5058.5  654.84  5064.5  652.14  5079.5  654.16
  5100.6  652.83  5107.3  654.82  5208.3  651.56  5286.8  656.95  5377.3  658.18
#Mann=3,-1,0
  4505.1     0.1       0  4700.2    0.07       0  4706.2     0.1       0
Bank Sta=4700.2,4706.2
Exp/Cntr=0.3,0.1

Type RM Length L Ch R = 1,942,308,308,308
BEGIN DESCRIPTION:
UNT 059 in HW 2.0
END DESCRIPTION:
XS GIS Cut Line= 4
      1990923.89     13597714.67      1991165.20     13597593.15
      1991514.16     13597351.83      1991627.01     13597195.57
#Sta/Elev= 30
  4494.8  659.51  4687.5  649.52  4872.0  645.36  4878.1  648.53  4893.0  644.43
  4913.9  648.95  4922.7  645.62  4928.8  651.03  4940.7  644.34  4941.2  643.54
  4946.7  644.34  4949.8  649.05  4958.5  646.30  4964.6  651.13  4979.5  645.24
  4985.6  648.95  4994.4  646.51  5000.4  651.47  5015.3  645.04  5021.4  649.65
  5030.2  646.30  5036.3  651.58  5051.1  645.32  5072.1  650.89  5087.0  645.61
  5116.7  647.83  5122.8  651.99  5137.6  646.76  5158.6  651.48  5382.0  657.72
#Mann=3,-1,0
  4494.8     0.1       0  4940.7    0.07       0  4946.7     0.1       0
Bank Sta=4940.7,4946.7
Exp/Cntr=0.3,0.1

Type RM Length L Ch R = 1,634,0,0,0
BEGIN DESCRIPTION:
UNT 059 in HW 1.0
END DESCRIPTION:
XS GIS Cut Line= 4
      1991074.95     13597825.01      1991564.07     13597703.39
      1991699.49     13597436.03      1991664.83     13597179.57
#Sta/Elev= 30
  4407.6  657.46  4490.1  651.37  4513.5  650.51  4549.7  647.76  4596.2  645.67
  4632.4  643.05  4673.7  641.82  4696.2  642.41  4715.0  641.34  4871.3  639.12
  4889.0  638.36  4889.5  637.56  4894.5  637.56  4895.0  638.36  4925.7  639.02
  5037.1  638.87  5103.9  640.02  5148.4  641.60  5187.4  644.58  5193.0  644.26
  5201.3  645.51  5214.4  645.95  5232.5  647.99  5252.7  648.92  5293.1  652.01
  5357.7  655.20  5383.9  655.71  5404.1  656.85  5430.4  655.93  5470.1  656.72
#Mann=3,-1,0
  4407.6     0.1       0  4889.0    0.07       0  4895.0     0.1       0
Bank Sta=4889,4895
Exp/Cntr=0.3,0.1

Chan Stop Cuts=-1