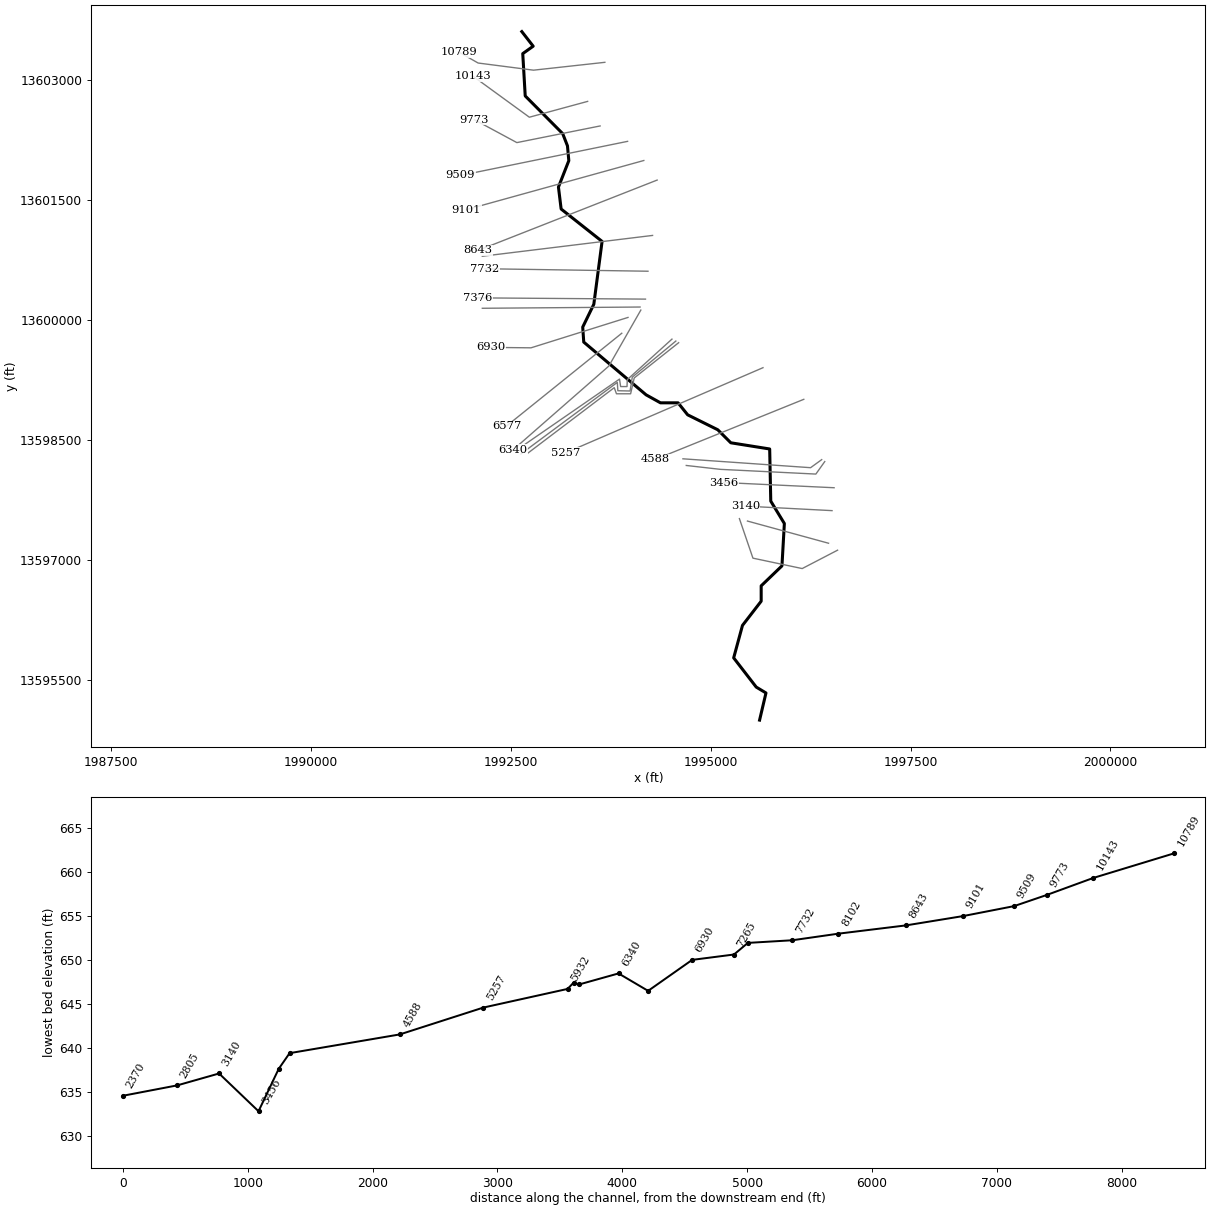
--- UNT 060 in HW.prj (project) ---

Proj Title=UNT 060 in HW Base Level Engineering
Current Plan=p01
Default Exp/Contr=0.3,0.1
English Units
Geom File=g01
Flow File=f01
Plan File=p01
BEGIN DESCRIPTION:
UNT 060 in HW
END DESCRIPTION:

--- UNT 060 in HW.p01 (plan) ---

Plan Title=Multiple Run
Short Identifier=Multiple
Geom File=g01
Flow File=f01
Subcritical Flow
K Sum by GR= 0
Std Step Tol= 0.01
Critical Tol= 0.01
Num of Std Step Trials= 20
Max Error Tol= 0.3
Flow Tol Ratio= 0.001
Split Flow NTrial= 30
Split Flow Tol= 0.02
Split Flow Ratio= 0.02
Log Output Level= 0
Friction Slope Method= 1
Unsteady Friction Slope Method= 2
Unsteady Bridges Friction Slope Method= 1
Parabolic Critical Depth
Global Vel Dist=  1 , 1 , 1
Global Log Level= 0
CheckData=True
Encroach Param= -1, 0, 0, 0
BEGIN DESCRIPTION:
Multiple Run
END DESCRIPTION:

--- UNT 060 in HW.f01 (steady flow) ---

Flow Title=Multiple
Number of Profiles=7
Profile Names=10-year,25-year,50-year,1pct_min,100-year,1pct_plu,500-year
River Rch & RM= UNT 060 in HW,Reach-1,10789
     358     479     575     342     682    1360     960
River Rch & RM= UNT 060 in HW,Reach-1,9773
     572     788     963     581    1159    2313    1689
Boundary for River Rch & Prof#=UNT 060 in HW,Reach-1,1
Up Type=0
Dn Type=3
Dn Slope=0.005
Boundary for River Rch & Prof#=UNT 060 in HW,Reach-1,2
Up Type=0
Dn Type=3
Dn Slope=0.005
Boundary for River Rch & Prof#=UNT 060 in HW,Reach-1,3
Up Type=0
Dn Type=3
Dn Slope=0.005
Boundary for River Rch & Prof#=UNT 060 in HW,Reach-1,4
Up Type=0
Dn Type=3
Dn Slope=0.005
Boundary for River Rch & Prof#=UNT 060 in HW,Reach-1,5
Up Type=0
Dn Type=3
Dn Slope=0.005
Boundary for River Rch & Prof#=UNT 060 in HW,Reach-1,6
Up Type=0
Dn Type=3
Dn Slope=0.005
Boundary for River Rch & Prof#=UNT 060 in HW,Reach-1,7
Up Type=0
Dn Type=3
Dn Slope=0.005

--- UNT 060 in HW.g01 (geometry) ---

Geom Title=Existing Conditions

River Reach=UNT 060 in HW,Reach-1
Reach XY= 30
      1992635.80     13603609.54      1992777.99     13603426.76
      1992647.64     13603333.82      1992678.45     13602804.31
      1993147.42     13602332.48      1993207.10     13602179.49
      1993223.99     13601994.68      1993094.25     13601664.08
      1993127.89     13601389.56      1993640.09     13600984.25
      1993536.79     13600197.79      1993397.90     13599912.20
      1993410.80     13599724.54      1994190.80     13599064.54
      1994370.80     13598964.54      1994590.80     13598964.54
      1994710.80     13598814.54      1995087.93     13598627.40
      1995250.80     13598464.54      1995737.18     13598387.13
      1995750.80     13597734.54      1995920.80     13597454.54
      1995890.80     13596924.54      1995630.80     13596674.54
      1995630.80     13596482.61      1995396.90     13596179.66
      1995286.66     13595773.41      1995568.78     13595407.96
      1995690.80     13595334.54      1995610.80     13594994.54

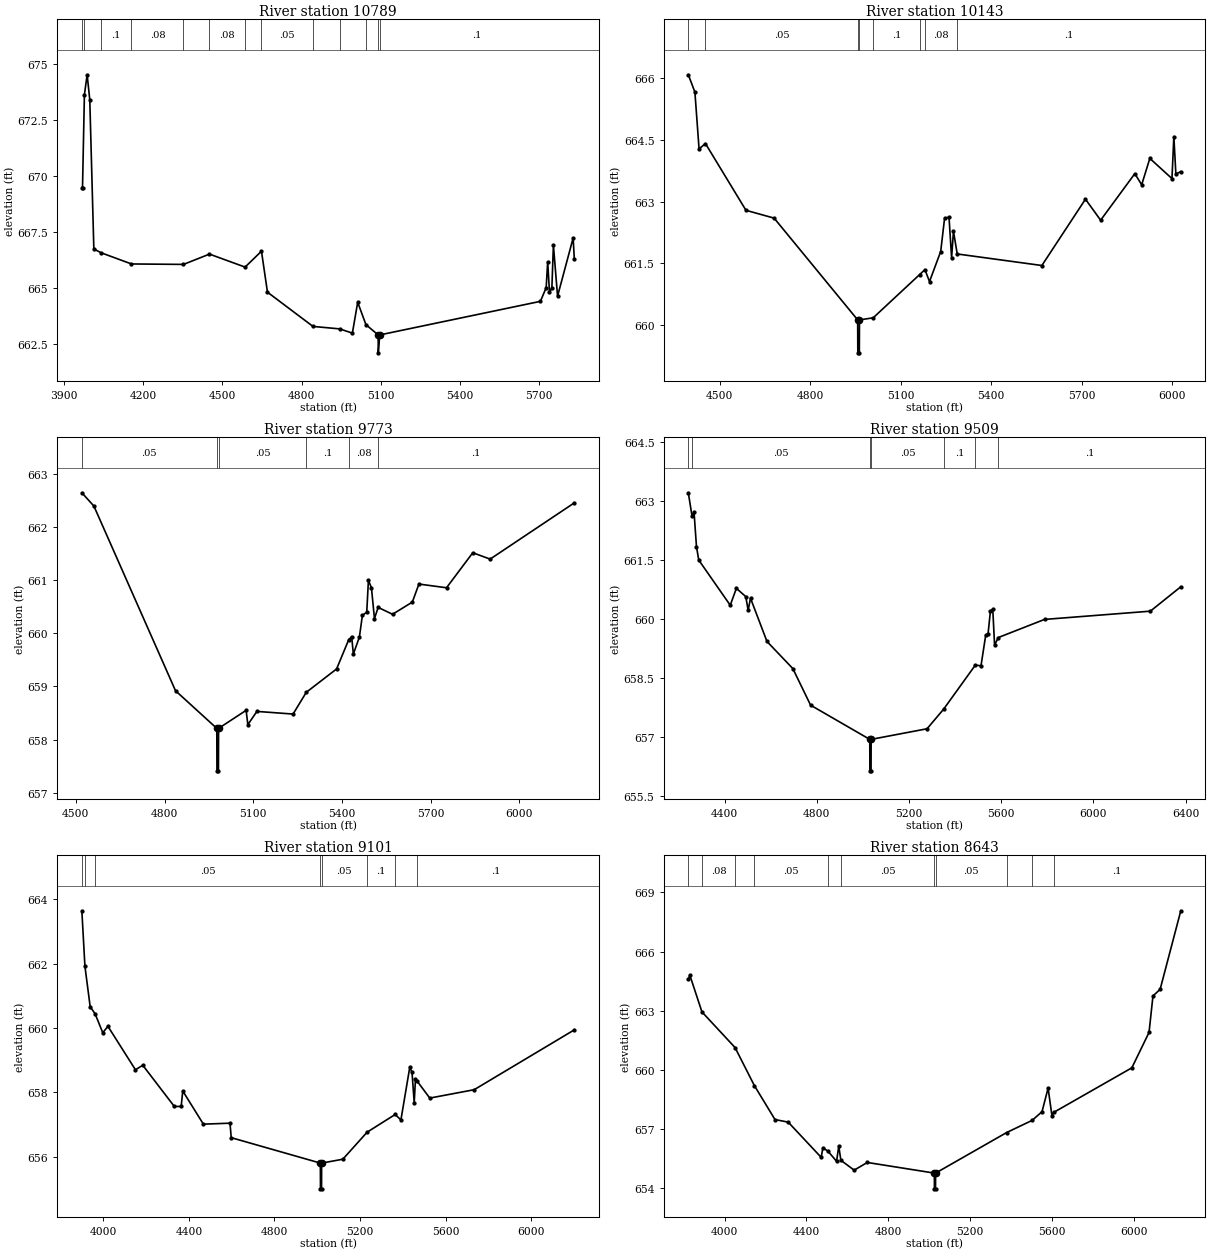
Type RM Length L Ch R = 1,10789,646,646,646
BEGIN DESCRIPTION:
UNT 060 in HW 7.0
END DESCRIPTION:
XS GIS Cut Line= 4
      1993674.96     13603225.00      1992782.27     13603126.77
      1992089.37     13603216.18      1991853.10     13603350.49
#Sta/Elev= 30
  3966.4  669.50  3968.9  669.50  3976.1  673.65  3986.5  674.54  3996.5  673.42
  4011.9  666.76  4039.4  666.59  4154.7  666.09  4352.0  666.07  4450.6  666.53
  4585.8  665.95  4647.9  666.66  4670.6  664.83  4843.3  663.30  4944.6  663.19
  4992.8  663.00  5013.0  664.38  5044.2  663.38  5090.6  662.92  5091.1  662.12
  5096.6  662.92  5706.2  664.42  5728.1  665.03  5733.8  666.19  5740.7  664.82
  5749.7  665.01  5755.5  666.93  5771.3  664.65  5830.4  667.25  5834.9  666.31
#Mann=13,-1,0
  3966.4     0.1       0  3976.1    0.15       0  4039.4     0.1       0
  4154.7    0.08       0  4352.0     0.1       0  4450.6    0.08       0
  4585.8     0.1       0  4647.9    0.05       0  4843.3     0.1       0
  4944.6    0.08       0  5044.2     0.1       0  5090.6    0.07       0
  5096.6     0.1       0
Bank Sta=5090.6,5096.6
Exp/Cntr=0.3,0.1

Type RM Length L Ch R = 1,10143,370,370,370
BEGIN DESCRIPTION:
Mapping XS c8ea9adc
END DESCRIPTION:
XS GIS Cut Line= 3
      1993459.37     13602736.15      1992730.19     13602538.23
      1992021.85     13603053.86
#Sta/Elev= 30
  4396.5  666.08  4418.3  665.66  4432.1  664.28  4453.3  664.41  4587.5  662.79
  4680.8  662.60  4957.6  660.13  4958.1  659.33  4963.1  659.33  4963.6  660.13
  5009.0  660.18  5162.9  661.23  5180.5  661.35  5195.6  661.06  5232.7  661.79
  5245.6  662.60  5260.3  662.62  5268.8  661.64  5275.0  662.28  5287.5  661.73
  5567.9  661.45  5712.3  663.06  5762.6  662.55  5875.9  663.68  5898.6  663.41
  5925.6  664.05  5999.0  663.56  6005.2  664.58  6011.9  663.67  6028.2  663.73
#Mann=8,-1,0
  4396.5    0.08       0  4453.3    0.05       0  4957.6   0.035       0
  4963.6    0.05       0  5009.0     0.1       0  5162.9    0.05       0
  5180.5    0.08       0  5287.5     0.1       0
Bank Sta=4957.6,4963.6
Exp/Cntr=0.3,0.1

Type RM Length L Ch R = 1,9773,264,264,264
BEGIN DESCRIPTION:
Mapping XS 89fa8108
END DESCRIPTION:
XS GIS Cut Line= 3
      1993615.61     13602428.85      1992573.94     13602220.52
      1992042.66     13602507.00
#Sta/Elev= 30
  4520.4  662.65  4561.1  662.40  4837.2  658.92  4976.9  658.21  4977.4  657.41
  4982.4  657.41  4982.9  658.21  5076.1  658.55  5081.9  658.28  5112.5  658.53
  5234.9  658.48  5279.6  658.89  5382.1  659.33  5423.0  659.88  5433.1  659.94
  5438.8  659.61  5459.2  659.93  5469.4  660.34  5484.1  660.40  5489.8  661.00
  5500.0  660.86  5510.2  660.28  5522.7  660.49  5571.4  660.36  5638.3  660.59
  5660.6  660.93  5753.9  660.86  5842.8  661.52  5901.5  661.40  6186.3  662.46
#Mann=6,-1,0
  4520.4    0.05       0  4976.9   0.035       0  4982.9    0.05       0
  5279.6     0.1       0  5423.0    0.08       0  5522.7     0.1       0
Bank Sta=4976.9,4982.9
Exp/Cntr=0.3,0.1

Type RM Length L Ch R = 1,9509,408,408,408
BEGIN DESCRIPTION:
Mapping XS dbcfb6db
END DESCRIPTION:
XS GIS Cut Line= 2
      1993959.33     13602236.14      1991865.64     13601809.07
#Sta/Elev= 30
  4242.3  663.20  4258.3  662.61  4267.1  662.71  4277.7  661.83  4287.5  661.49
  4424.2  660.34  4450.8  660.77  4491.7  660.56  4501.9  660.21  4512.1  660.52
  4583.5  659.42  4695.8  658.73  4772.8  657.80  5029.6  656.93  5030.1  656.13
  5035.1  656.13  5035.6  656.93  5278.2  657.20  5350.3  657.70  5487.9  658.82
  5512.2  658.80  5532.7  659.58  5542.9  659.62  5553.1  660.19  5563.3  660.24
  5571.1  659.33  5587.6  659.52  5787.8  659.98  6247.1  660.19  6379.1  660.81
#Mann=7,-1,0
  4242.3     0.1       0  4258.3    0.05       0  5029.6   0.035       0
  5035.6    0.05       0  5350.3     0.1       0  5487.9    0.05       0
  5587.6     0.1       0
Bank Sta=5029.6,5035.6
Exp/Cntr=0.3,0.1

Type RM Length L Ch R = 1,9101,458,458,458
BEGIN DESCRIPTION:
Mapping XS 07006ff9
END DESCRIPTION:
XS GIS Cut Line= 2
      1994162.46     13601996.56      1991943.71     13601381.97
#Sta/Elev= 30
  3899.4  663.64  3913.7  661.92  3938.3  660.66  3961.3  660.44  3997.1  659.85
  4021.3  660.05  4149.9  658.70  4184.2  658.84  4331.7  657.56  4363.7  657.56
  4371.2  658.04  4467.5  657.01  4592.0  657.04  4597.7  656.59  5014.4  655.80
  5014.9  655.00  5019.9  655.00  5020.4  655.80  5119.4  655.92  5232.9  656.76
  5364.1  657.31  5391.0  657.14  5432.5  658.78  5442.9  658.62  5453.2  657.68
  5459.1  658.42  5465.4  658.36  5525.9  657.82  5733.4  658.08  6201.7  659.94
#Mann=8,-1,0
  3899.4     0.1       0  3913.7    0.08       0  3961.3    0.05       0
  5014.4   0.035       0  5020.4    0.05       0  5232.9     0.1       0
  5364.1    0.08       0  5465.4     0.1       0
Bank Sta=5014.4,5020.4
Exp/Cntr=0.3,0.1

Type RM Length L Ch R = 1,8643,541,541,541
BEGIN DESCRIPTION:
Mapping XS 3ab9ce2f
END DESCRIPTION:
XS GIS Cut Line= 2
      1994329.15     13601751.77      1992089.79     13600871.65
#Sta/Elev= 30
  3822.7  664.58  3830.0  664.80  3889.3  662.93  4051.0  661.12  4145.2  659.19
  4246.2  657.46  4310.7  657.33  4471.8  655.54  4480.4  656.03  4505.3  655.85
  4547.0  655.34  4557.8  656.11  4568.0  655.39  4633.0  654.89  4697.2  655.28
  5024.7  654.74  5025.2  653.94  5030.4  653.94  5030.9  654.74  5377.8  656.80
  5502.7  657.42  5550.8  657.86  5580.5  659.06  5599.6  657.63  5607.1  657.82
  5989.7  660.09  6073.7  661.89  6092.8  663.74  6127.9  664.08  6228.8  668.07
#Mann=11,-1,0
  3822.7    0.05       0  3889.3    0.08       0  4051.0     0.1       0
  4145.2    0.05       0  4505.3     0.1       0  4568.0    0.05       0
  5024.7   0.035       0  5030.9    0.05       0  5377.8     0.1       0
  5502.7    0.08       0  5607.1     0.1       0
Bank Sta=5024.7,5030.9
Exp/Cntr=0.3,0.1

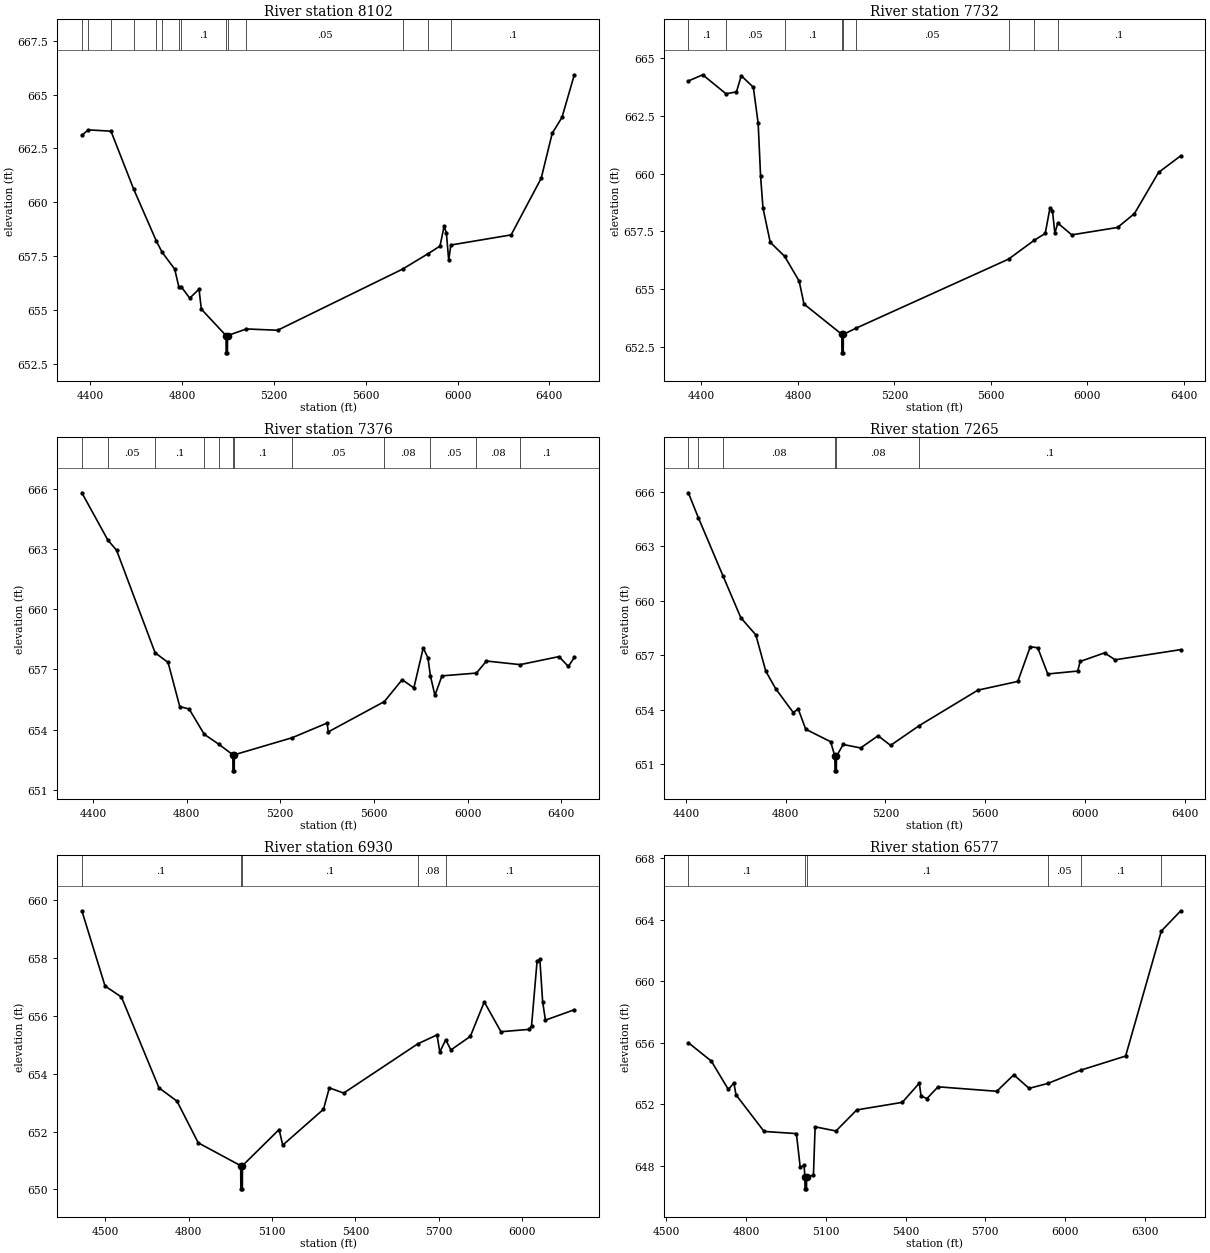
Type RM Length L Ch R = 1,8102,370,370,370
BEGIN DESCRIPTION:
Mapping XS 9f9c07af
END DESCRIPTION:
XS GIS Cut Line= 2
      1994271.86     13601059.06      1992141.62     13600798.64
#Sta/Elev= 30
  4362.9  663.11  4391.1  663.36  4489.8  663.30  4588.6  660.61  4687.3  658.20
  4712.3  657.68  4767.5  656.89  4786.1  656.04  4796.7  656.06  4833.2  655.54
  4873.5  655.96  4883.6  655.03  4991.3  653.80  4991.8  653.00  4997.1  653.00
  4997.6  653.80  5079.9  654.11  5216.1  654.05  5760.5  656.89  5872.2  657.61
  5923.6  657.96  5941.4  658.88  5951.5  658.57  5961.6  657.30  5970.9  658.01
  6233.6  658.48  6364.6  661.11  6412.6  663.20  6455.2  663.94  6509.0  665.92
#Mann=14,-1,0
  4362.9     0.1       0  4391.1    0.15       0  4489.8     0.1       0
  4588.6    0.08       0  4687.3    0.05       0  4712.3    0.08       0
  4786.1    0.05       0  4796.7     0.1       0  4991.3    0.07       0
  4997.6     0.1       0  5079.9    0.05       0  5760.5     0.1       0
  5872.2    0.08       0  5970.9     0.1       0
Bank Sta=4991.3,4997.6
Exp/Cntr=0.3,0.1

Type RM Length L Ch R = 1,7732,356,356,356
BEGIN DESCRIPTION:
Mapping XS a90df2a6
END DESCRIPTION:
XS GIS Cut Line= 2
      1994214.58     13600611.14      1992172.92     13600642.39
#Sta/Elev= 30
  4345.4  664.00  4405.0  664.27  4501.5  663.45  4545.0  663.53  4565.0  664.23
  4615.0  663.73  4635.0  662.17  4645.0  659.89  4655.0  658.51  4685.0  657.03
  4744.9  656.42  4805.0  655.35  4825.0  654.36  4981.9  653.05  4982.4  652.25
  4987.7  652.25  4988.2  653.05  5039.6  653.31  5673.0  656.30  5778.8  657.11
  5825.2  657.41  5845.2  658.53  5855.2  658.39  5865.2  657.42  5877.2  657.86
  5935.2  657.35  6125.2  657.67  6195.2  658.27  6295.2  660.05  6387.3  660.77
#Mann=9,-1,0
  4345.4     0.1       0  4501.5    0.05       0  4744.9     0.1       0
  4981.9    0.07       0  4988.2     0.1       0  5039.6    0.05       0
  5673.0     0.1       0  5778.8    0.05       0  5877.2     0.1       0
Bank Sta=4981.9,4988.2
Exp/Cntr=0.3,0.1

Type RM Length L Ch R = 1,7376,111,111,111
BEGIN DESCRIPTION:
Mapping XS 141428f4
END DESCRIPTION:
XS GIS Cut Line= 2
      1994183.27     13600262.19      1992079.53     13600277.81
#Sta/Elev= 30
  4352.3  665.80  4463.6  663.44  4500.6  662.94  4665.2  657.83  4720.6  657.35
  4770.6  655.15  4810.6  655.03  4875.2  653.77  4936.8  653.28  4997.4  652.75
  4997.9  651.95  5003.2  651.95  5003.7  652.75  5250.9  653.60  5400.0  654.33
  5405.0  653.89  5644.5  655.40  5720.6  656.49  5770.6  656.08  5810.6  658.07
  5830.6  657.58  5841.3  656.68  5860.6  655.71  5890.6  656.68  6038.1  656.82
  6080.6  657.42  6224.6  657.24  6390.6  657.64  6430.6  657.15  6456.1  657.60
#Mann=12,-1,0
  4352.3    0.08       0  4463.6    0.05       0  4665.2     0.1       0
  4875.2    0.05       0  4936.8     0.1       0  4997.4    0.07       0
  5003.7     0.1       0  5250.9    0.05       0  5644.5    0.08       0
  5841.3    0.05       0  6038.1    0.08       0  6224.6     0.1       0
Bank Sta=4997.4,5003.7
Exp/Cntr=0.3,0.1

Type RM Length L Ch R = 1,7265,335,335,335
BEGIN DESCRIPTION:
Mapping XS 7805d2ca
END DESCRIPTION:
XS GIS Cut Line= 2
      1994115.63     13600163.23      1992141.69     13600147.60
#Sta/Elev= 30
  4409.7  665.93  4450.2  664.55  4548.6  661.36  4620.3  659.05  4680.3  658.11
  4720.3  656.11  4760.3  655.14  4830.3  653.84  4850.3  654.03  4880.3  652.92
  4980.3  652.23  4997.2  651.43  4997.7  650.63  5003.0  650.63  5003.5  651.43
  5030.3  652.08  5100.4  651.89  5170.4  652.56  5220.4  652.03  5335.5  653.12
  5570.4  655.07  5730.4  655.55  5780.4  657.46  5810.4  657.40  5850.4  655.96
  5970.4  656.12  5980.4  656.65  6078.1  657.12  6120.4  656.74  6383.7  657.30
#Mann=6,-1,0
  4409.7    0.08       0  4450.2    0.05       0  4548.6    0.08       0
  4997.2    0.07       0  5003.5    0.08       0  5335.5     0.1       0
Bank Sta=4997.2,5003.5
Exp/Cntr=0.3,0.1

Type RM Length L Ch R = 1,6930,353,353,353
BEGIN DESCRIPTION:
Mapping XS 04f05e10
END DESCRIPTION:
XS GIS Cut Line= 3
      1993964.56     13600033.02      1992751.02     13599652.81
      1992251.05     13599658.02
#Sta/Elev= 30
  4415.6  659.63  4499.0  657.03  4558.0  656.65  4693.1  653.51  4757.9  653.05
  4834.3  651.61  4987.1  650.82  4987.6  650.02  4992.9  650.02  4993.4  650.82
  5125.3  652.07  5138.2  651.53  5284.9  652.77  5305.9  653.51  5357.6  653.33
  5623.9  655.03  5693.3  655.34  5703.3  654.75  5724.6  655.17  5743.3  654.82
  5813.3  655.29  5863.3  656.48  5923.3  655.45  6023.3  655.53  6033.3  655.64
  6053.3  657.89  6063.3  657.95  6073.3  656.49  6083.3  655.85  6187.3  656.21
#Mann=5,-1,0
  4415.6     0.1       0  4987.1    0.07       0  4993.4     0.1       0
  5623.9    0.08       0  5724.6     0.1       0
Bank Sta=4987.1,4993.4
Exp/Cntr=0.3,0.1

Type RM Length L Ch R = 1,6577,237,237,237
BEGIN DESCRIPTION:
Mapping XS a98fbd13
END DESCRIPTION:
XS GIS Cut Line= 2
      1993886.42     13599835.09      1992443.74     13598673.65
#Sta/Elev= 30
  4583.1  656.00  4669.7  654.80  4733.6  652.96  4754.5  653.38  4762.4  652.61
  4868.0  650.23  4989.6  650.09  5004.0  647.89  5018.4  648.02  5021.6  647.30
  5022.1  646.50  5027.5  646.50  5028.0  647.30  5053.6  647.37  5060.0  650.53
  5138.4  650.26  5216.8  651.63  5387.9  652.12  5451.9  653.37  5458.3  652.53
  5480.7  652.37  5522.3  653.13  5743.1  652.84  5807.1  653.91  5864.6  653.03
  5935.4  653.35  6058.6  654.21  6227.7  655.13  6361.8  663.25  6435.2  664.57
#Mann=6,-1,0
  4583.1     0.1       0  5021.6    0.07       0  5028.0     0.1       0
  5935.4    0.05       0  6058.6     0.1       0  6361.8    0.05       0
Bank Sta=5021.6,5028
Exp/Cntr=0.3,0.1

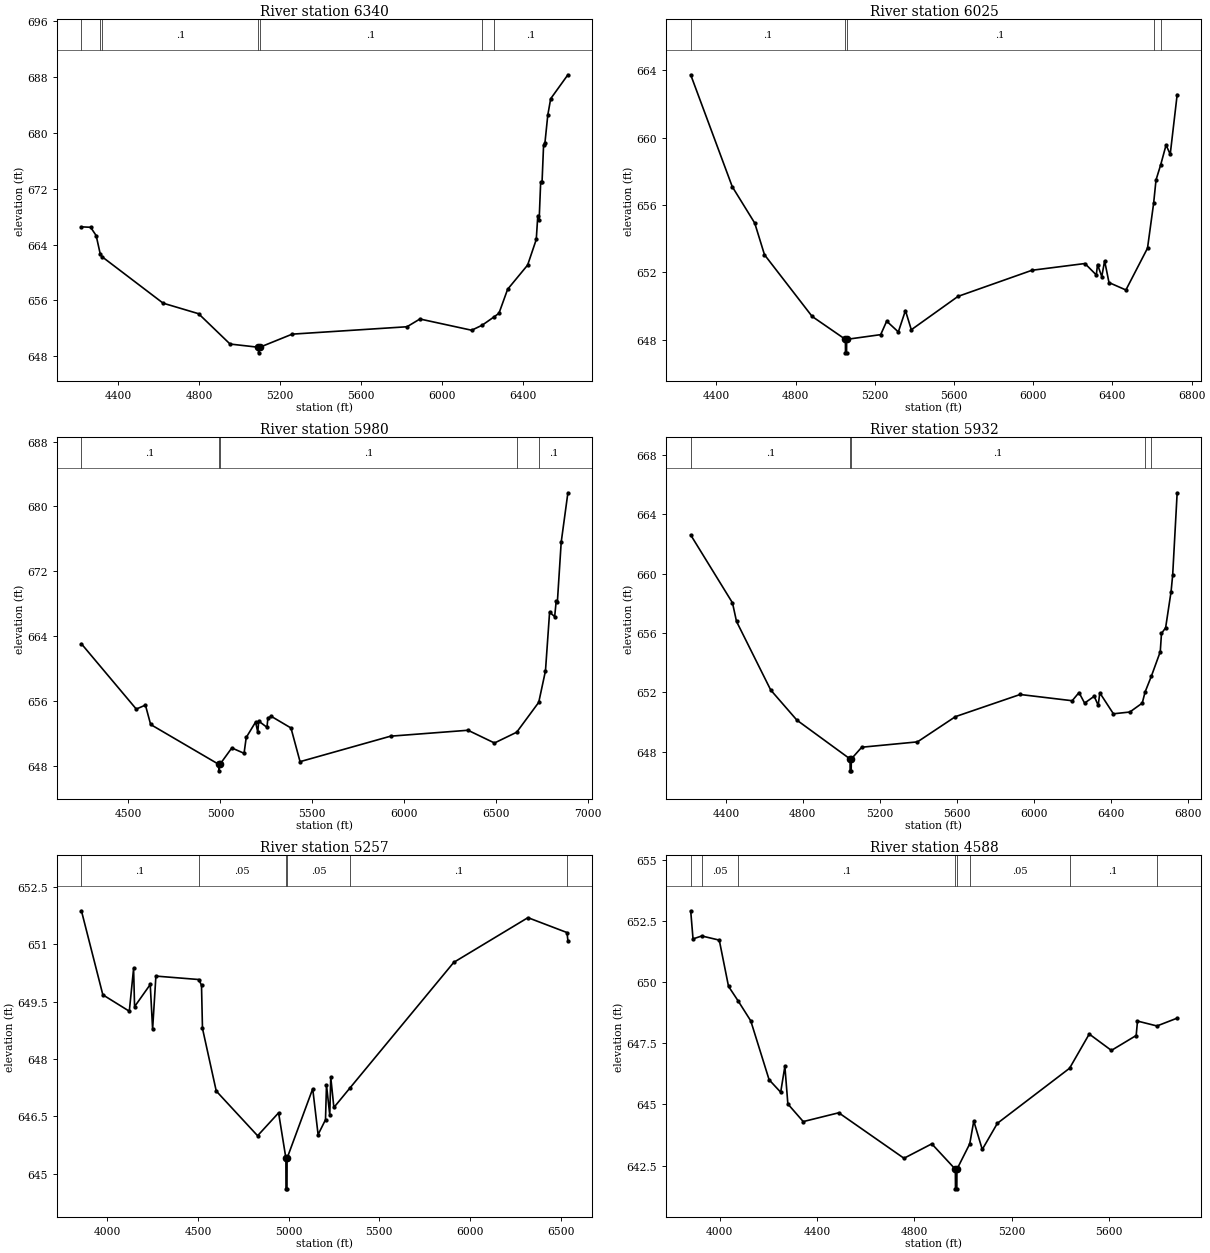
Type RM Length L Ch R = 1,6340,315,315,315
BEGIN DESCRIPTION:
UNT 060 in HW 3.0
END DESCRIPTION:
XS GIS Cut Line= 3
      1994124.99     13600124.98      1993725.00     13599425.00
      1992525.02     13598375.01
#Sta/Elev= 30
  4219.7  666.54  4265.0  666.48  4292.4  665.29  4312.7  662.63  4322.2  662.24
  4622.8  655.60  4797.7  654.09  4953.2  649.74  5093.4  649.28  5093.9  648.48
  5099.8  649.28  5259.9  651.16  5826.5  652.22  5890.1  653.33  6145.4  651.72
  6197.2  652.44  6253.9  653.59  6280.2  654.15  6322.9  657.59  6421.6  661.06
  6464.3  664.73  6471.9  668.16  6478.5  667.50  6486.1  673.00  6492.8  672.94
  6500.4  678.25  6507.0  678.55  6521.2  682.57  6535.5  684.91  6620.4  688.34
#Mann=7,-1,0
  4219.7    0.08       0  4312.7    0.05       0  4322.2     0.1       0
  5093.4    0.07       0  5099.8     0.1       0  6197.2    0.08       0
  6253.9     0.1       0
Bank Sta=5093.4,5099.8
Exp/Cntr=0.3,0.1

Type RM Length L Ch R = 1,6025,45,45,45
BEGIN DESCRIPTION:
Mapping XS 7ac6beec
END DESCRIPTION:
XS GIS Cut Line= 6
      1994514.53     13599761.81      1993955.54     13599254.89
      1993952.07     13599168.09      1993872.21     13599168.09
      1993858.32     13599261.84      1992681.68     13598449.65
#Sta/Elev= 30
  4270.1  663.73  4480.0  657.09  4593.5  654.93  4642.8  653.05  4883.4  649.39
  5051.4  648.03  5051.9  647.23  5057.3  647.23  5057.8  648.03  5229.6  648.31
  5259.9  649.11  5318.7  648.47  5354.6  649.74  5384.3  648.60  5620.2  650.58
  5993.8  652.13  6261.1  652.53  6318.6  651.85  6324.7  652.47  6346.2  651.75
  6360.5  652.69  6382.6  651.40  6468.0  650.96  6577.1  653.44  6608.1  656.11
  6620.1  657.49  6643.8  658.39  6670.8  659.56  6691.8  659.01  6726.9  662.55
#Mann=5,-1,0
  4270.1     0.1       0  5051.4    0.07       0  5057.8     0.1       0
  6608.1    0.08       0  6643.8     0.1       0
Bank Sta=5051.4,5057.8
Exp/Cntr=0.3,0.1

Type RM Length L Ch R = 1,5980,48,48,48
BEGIN DESCRIPTION:
UNT 060 in HW 2.0
END DESCRIPTION:
XS GIS Cut Line= 6
      1994563.20     13599737.55      1994018.04     13599286.14
      1993990.26     13599112.53      1993837.48     13599116.01
      1993830.54     13599220.17      1992625.02     13598325.01
#Sta/Elev= 30
  4243.9  663.08  4542.3  655.04  4592.1  655.53  4620.5  653.14  4991.0  648.23
  4991.5  647.43  4997.4  648.23  5062.1  650.25  5128.8  649.59  5140.5  651.54
  5191.5  653.44  5203.4  652.19  5208.5  653.56  5253.4  652.79  5258.5  653.94
  5277.1  654.14  5384.0  652.71  5433.4  648.56  5925.8  651.70  6347.2  652.43
  6491.2  650.86  6612.2  652.19  6732.0  655.87  6768.7  659.75  6791.1  666.98
  6818.7  666.43  6827.1  668.35  6833.3  668.18  6854.2  675.59  6890.7  681.69
#Mann=5,-1,0
  4243.9     0.1       0  4991.0    0.07       0  4997.4     0.1       0
  6612.2    0.08       0  6732.0     0.1       0
Bank Sta=4991,4997.4
Exp/Cntr=0.3,0.1

Type RM Length L Ch R = 1,5932,675,675,675
BEGIN DESCRIPTION:
Mapping XS 03f1d4b5
END DESCRIPTION:
XS GIS Cut Line= 6
      1994597.92     13599716.72      1994042.34     13599275.73
      1993997.21     13599077.81      1993820.12     13599077.81
      1993792.34     13599154.20      1992717.16     13598339.14
#Sta/Elev= 30
  4217.2  662.60  4434.3  658.03  4455.2  656.78  4633.0  652.16  4769.2  650.13
  5045.2  647.52  5045.7  646.72  5051.1  646.72  5051.6  647.52  5105.9  648.31
  5395.4  648.67  5592.8  650.37  5928.7  651.86  6199.2  651.44  6234.6  651.99
  6263.7  651.28  6313.6  651.74  6334.4  651.13  6342.7  651.97  6413.4  650.56
  6498.7  650.68  6563.2  651.28  6577.7  652.02  6610.8  653.10  6656.8  654.74
  6663.1  655.97  6684.6  656.35  6713.0  658.79  6721.3  659.91  6744.6  665.44
#Mann=5,-1,0
  4217.2     0.1       0  5045.2    0.07       0  5051.6     0.1       0
  6577.7    0.08       0  6610.8     0.1       0
Bank Sta=5045.2,5051.6
Exp/Cntr=0.3,0.1

Type RM Length L Ch R = 1,5257,669,669,669
BEGIN DESCRIPTION:
Mapping XS c0d4c635
END DESCRIPTION:
XS GIS Cut Line= 2
      1995653.47     13599404.21      1993189.92     13598341.71
#Sta/Elev= 30
  3856.9  651.88  3975.0  649.68  4121.0  649.25  4144.6  650.37  4150.0  649.37
  4236.4  649.95  4249.5  648.78  4267.6  650.17  4504.2  650.08  4519.1  649.93
  4524.5  648.80  4600.5  647.16  4828.5  645.99  4944.3  646.59  4984.6  645.40
  4985.1  644.60  4990.5  644.60  4991.0  645.40  5132.5  647.22  5162.1  646.02
  5203.0  646.41  5208.4  647.32  5226.5  646.53  5232.0  647.52  5249.2  646.73
  5337.7  647.24  5910.5  650.53  6319.4  651.70  6534.8  651.31  6539.8  651.10
#Mann=6,-1,0
  3856.9     0.1       0  4504.2    0.05       0  4984.6   0.035       0
  4991.0    0.05       0  5337.7     0.1       0  6534.8    0.05       0
Bank Sta=4984.6,4991
Exp/Cntr=0.3,0.1

Type RM Length L Ch R = 1,4588,883,883,883
BEGIN DESCRIPTION:
Mapping XS e67a609a
END DESCRIPTION:
XS GIS Cut Line= 2
      1996163.91     13599008.38      1994309.84     13598258.42
#Sta/Elev= 30
  3881.0  652.92  3890.6  651.77  3926.6  651.89  3998.5  651.72  4036.5  649.83
  4076.3  649.23  4127.9  648.42  4203.4  646.01  4251.0  645.50  4268.2  646.56
  4280.5  645.02  4343.7  644.30  4489.7  644.66  4757.9  642.80  4872.2  643.39
  4969.1  642.35  4969.6  641.55  4975.1  641.55  4975.6  642.35  5028.2  643.39
  5044.8  644.32  5079.7  643.16  5141.9  644.23  5438.6  646.48  5519.5  647.88
  5610.6  647.21  5712.5  647.82  5717.9  648.41  5797.9  648.21  5881.0  648.53
#Mann=8,-1,0
  3881.0    0.08       0  3926.6    0.05       0  4076.3     0.1       0
  4969.1    0.07       0  4975.6     0.1       0  5028.2    0.05       0
  5438.6     0.1       0  5797.9    0.08       0
Bank Sta=4969.1,4975.6
Exp/Cntr=0.3,0.1

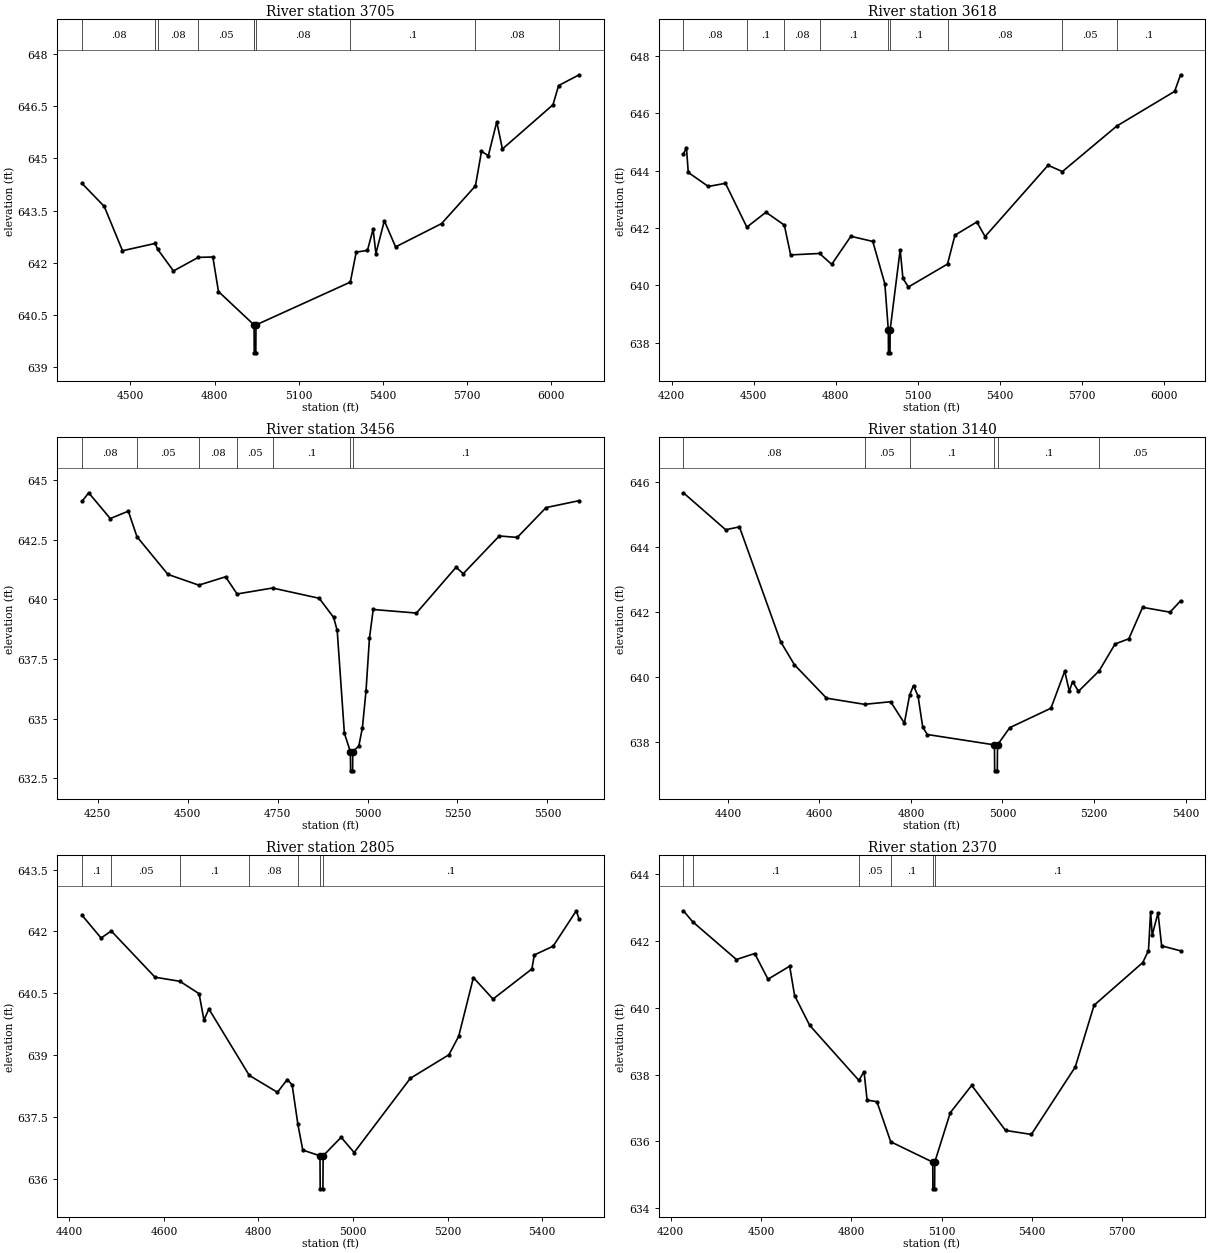
Type RM Length L Ch R = 1,3705,87,87,87
BEGIN DESCRIPTION:
Mapping XS 7f5fb5ad
END DESCRIPTION:
XS GIS Cut Line= 3
      1996387.91     13598253.74      1996249.00     13598153.03
      1994651.74     13598264.14
#Sta/Elev= 30
  4327.6  644.28  4406.8  643.62  4471.7  642.35  4588.1  642.56  4597.2  642.39
  4653.5  641.77  4741.9  642.16  4793.9  642.17  4813.9  641.18  4939.6  640.23
  4941.0  640.22  4941.5  639.42  4947.1  639.42  4947.6  640.22  5284.1  641.45
  5305.1  642.31  5345.2  642.36  5365.3  642.97  5375.3  642.27  5405.4  643.21
  5445.5  642.46  5609.6  643.13  5730.2  644.21  5751.8  645.20  5776.3  645.08
  5806.3  646.05  5826.4  645.27  6006.8  646.54  6026.7  647.09  6100.3  647.40
#Mann=10,-1,0
  4327.6    0.08       0  4588.1     0.1       0  4597.2    0.08       0
  4741.9    0.05       0  4939.6    0.08       0  4941.0    0.07       0
  4947.6    0.08       0  5284.1     0.1       0  5730.2    0.08       0
  6026.7    0.05       0
Bank Sta=4941,4947.6
Exp/Cntr=0.3,0.1

Type RM Length L Ch R = 1,3618,162,162,162
BEGIN DESCRIPTION:
Mapping XS 88545943
END DESCRIPTION:
XS GIS Cut Line= 4
      1996426.09     13598229.42      1996314.98     13598073.17
      1995120.53     13598132.19      1994693.43     13598180.81
#Sta/Elev= 30
  4243.4  644.58  4254.4  644.81  4261.1  643.94  4334.4  643.45  4397.1  643.56
  4475.2  642.03  4545.2  642.55  4612.3  642.10  4635.4  641.06  4741.1  641.11
  4785.5  640.73  4855.6  641.71  4935.7  641.53  4979.8  640.05  4992.5  638.44
  4993.0  637.64  4998.6  637.64  4999.1  638.44  5035.8  641.24  5045.9  640.24
  5065.9  639.94  5208.9  640.74  5236.1  641.75  5316.2  642.21  5346.2  641.70
  5576.5  644.19  5628.9  643.97  5827.7  645.56  6039.2  646.77  6060.9  647.35
#Mann=9,-1,0
  4243.4    0.08       0  4475.2     0.1       0  4612.3    0.08       0
  4741.1     0.1       0  4992.5    0.07       0  4999.1     0.1       0
  5208.9    0.08       0  5628.9    0.05       0  5827.7     0.1       0
Bank Sta=4992.5,4999.1
Exp/Cntr=0.3,0.1

Type RM Length L Ch R = 1,3456,316,316,316
BEGIN DESCRIPTION:
Mapping XS cd132862
END DESCRIPTION:
XS GIS Cut Line= 2
      1996543.32     13597902.16      1995163.05     13597967.26
#Sta/Elev= 30
  4206.6  644.11  4224.9  644.47  4285.0  643.39  4335.1  643.70  4359.1  642.63
  4445.2  641.05  4531.0  640.60  4605.4  640.95  4637.4  640.23  4736.0  640.48
  4865.6  640.05  4905.7  639.25  4915.7  638.70  4935.7  634.39  4952.4  633.62
  4952.9  632.82  4958.5  632.82  4959.0  633.62  4975.8  633.86  4985.8  634.63
  4995.8  636.17  5005.3  638.37  5015.8  639.58  5135.9  639.43  5246.1  641.35
  5266.1  641.08  5366.2  642.66  5416.3  642.60  5496.3  643.85  5588.4  644.14
#Mann=7,-1,0
  4206.6    0.08       0  4359.1    0.05       0  4531.0    0.08       0
  4637.4    0.05       0  4736.0     0.1       0  4952.4    0.07       0
  4959.0     0.1       0
Bank Sta=4952.4,4959
Exp/Cntr=0.3,0.1

Type RM Length L Ch R = 1,3140,335,335,335
BEGIN DESCRIPTION:
Mapping XS abec199b
END DESCRIPTION:
XS GIS Cut Line= 2
      1996517.26     13597615.70      1995432.12     13597672.13
#Sta/Elev= 30
  4302.6  645.68  4395.0  644.54  4425.0  644.63  4515.1  641.09  4545.2  640.38
  4615.3  639.35  4698.4  639.16  4755.5  639.24  4785.5  638.58  4797.1  639.45
  4805.5  639.74  4815.5  639.41  4825.6  638.46  4835.6  638.23  4982.4  637.91
  4982.9  637.11  4988.6  637.11  4989.1  637.91  5015.8  638.44  5105.9  639.04
  5136.0  640.18  5146.0  639.57  5153.3  639.86  5166.0  639.56  5211.2  640.19
  5246.1  641.02  5276.2  641.18  5306.2  642.15  5366.3  642.00  5389.2  642.35
#Mann=6,-1,0
  4302.6    0.08       0  4698.4    0.05       0  4797.1     0.1       0
  4982.4    0.07       0  4989.1     0.1       0  5211.2    0.05       0
Bank Sta=4982.4,4989.1
Exp/Cntr=0.3,0.1

Type RM Length L Ch R = 1,2805,435,435,435
BEGIN DESCRIPTION:
Mapping XS 420b1eda
END DESCRIPTION:
XS GIS Cut Line= 2
      1996473.79     13597207.73      1995459.06     13597485.26
#Sta/Elev= 30
  4426.7  642.39  4466.9  641.84  4488.5  642.01  4581.0  640.89  4633.8  640.79
  4674.3  640.49  4684.6  639.85  4695.0  640.12  4780.5  638.51  4840.1  638.10
  4860.9  638.41  4871.2  638.28  4883.4  637.32  4893.7  636.70  4930.1  636.56
  4930.6  635.76  4936.3  635.76  4936.8  636.56  4974.9  637.01  5002.4  636.64
  5121.4  638.44  5203.0  639.01  5223.7  639.46  5254.8  640.88  5296.3  640.36
  5378.5  641.09  5383.7  641.43  5423.4  641.64  5472.5  642.50  5478.7  642.29
#Mann=7,-1,0
  4426.7     0.1       0  4488.5    0.05       0  4633.8     0.1       0
  4780.5    0.08       0  4883.4     0.1       0  4930.1    0.07       0
  4936.8     0.1       0
Bank Sta=4930.1,4936.8
Exp/Cntr=0.3,0.1

Type RM Length L Ch R = 1,2370,0,0,0
BEGIN DESCRIPTION:
UNT 060 in HW 1.0
END DESCRIPTION:
XS GIS Cut Line= 4
      1996586.71     13597120.93      1996143.97     13596890.87
      1995527.65     13597021.08      1995358.38     13597515.87
#Sta/Elev= 30
  4242.3  642.91  4273.1  642.58  4418.4  641.45  4479.1  641.63  4523.3  640.86
  4595.3  641.25  4611.7  640.37  4661.6  639.48  4825.2  637.83  4842.4  638.09
  4852.6  637.24  4885.3  637.19  4931.0  635.99  5070.7  635.38  5071.2  634.58
  5076.9  634.58  5077.4  635.38  5128.9  636.86  5200.1  637.68  5312.5  636.33
  5398.3  636.21  5544.2  638.23  5606.8  640.08  5768.6  641.36  5787.5  641.72
  5794.6  642.88  5799.9  642.18  5819.2  642.85  5831.2  641.86  5894.1  641.71
#Mann=6,-1,0
  4242.3    0.05       0  4273.1     0.1       0  4825.2    0.05       0
  4931.0     0.1       0  5070.7    0.07       0  5077.4     0.1       0
Bank Sta=5070.7,5077.4
Exp/Cntr=0.3,0.1

Chan Stop Cuts=-1