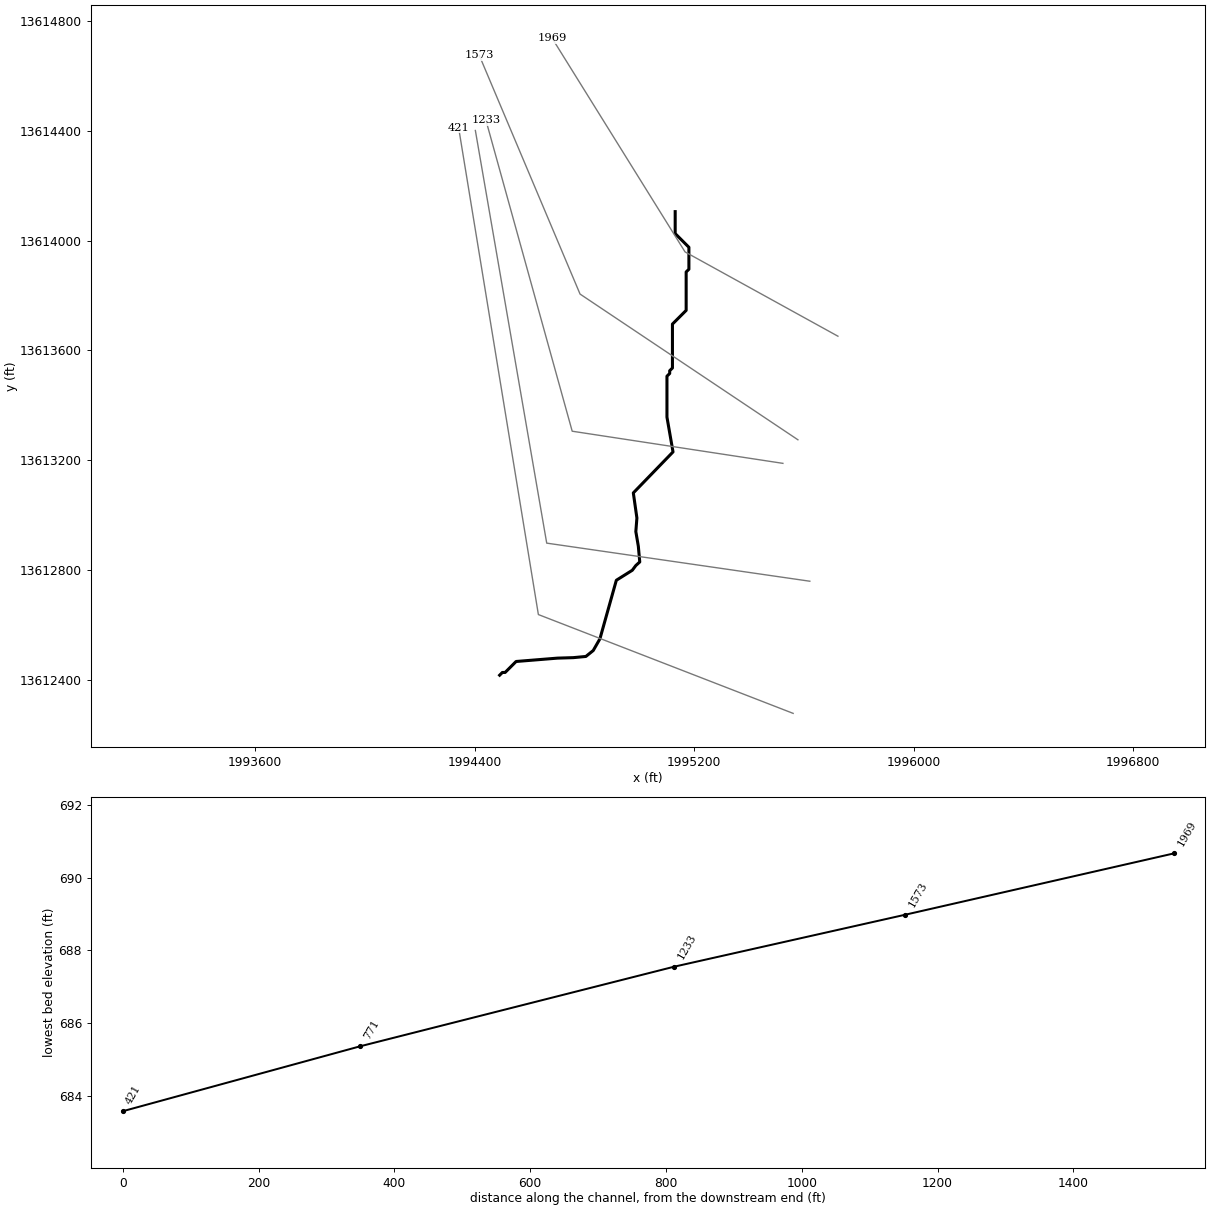
--- UNT 061 in HW.prj (project) ---

Proj Title=UNT 061 in HW Base Level Engineering
Current Plan=p01
Default Exp/Contr=0.3,0.1
English Units
Geom File=g01
Flow File=f01
Plan File=p01
BEGIN DESCRIPTION:
UNT 061 in HW
END DESCRIPTION:

--- UNT 061 in HW.p01 (plan) ---

Plan Title=Multiple Run
Short Identifier=Multiple
Geom File=g01
Flow File=f01
Subcritical Flow
K Sum by GR= 0
Std Step Tol= 0.01
Critical Tol= 0.01
Num of Std Step Trials= 20
Max Error Tol= 0.3
Flow Tol Ratio= 0.001
Split Flow NTrial= 30
Split Flow Tol= 0.02
Split Flow Ratio= 0.02
Log Output Level= 0
Friction Slope Method= 1
Unsteady Friction Slope Method= 2
Unsteady Bridges Friction Slope Method= 1
Parabolic Critical Depth
Global Vel Dist=  1 , 1 , 1
Global Log Level= 0
CheckData=True
Encroach Param= -1, 0, 0, 0
BEGIN DESCRIPTION:
Multiple Run
END DESCRIPTION:

--- UNT 061 in HW.f01 (steady flow) ---

Flow Title=Multiple
Number of Profiles=7
Profile Names=10-year,25-year,50-year,1pct_min,100-year,1pct_plu,500-year
River Rch & RM= UNT 061 in HW,Reach-1,1969
     430     594     730     444     886    1768    1310
River Rch & RM= UNT 061 in HW,Reach-1,1573
     652     924    1153     712    1421    2835    2166
Boundary for River Rch & Prof#=UNT 061 in HW,Reach-1,1
Up Type=0
Dn Type=3
Dn Slope=0.005
Boundary for River Rch & Prof#=UNT 061 in HW,Reach-1,2
Up Type=0
Dn Type=3
Dn Slope=0.005
Boundary for River Rch & Prof#=UNT 061 in HW,Reach-1,3
Up Type=0
Dn Type=3
Dn Slope=0.005
Boundary for River Rch & Prof#=UNT 061 in HW,Reach-1,4
Up Type=0
Dn Type=3
Dn Slope=0.005
Boundary for River Rch & Prof#=UNT 061 in HW,Reach-1,5
Up Type=0
Dn Type=3
Dn Slope=0.005
Boundary for River Rch & Prof#=UNT 061 in HW,Reach-1,6
Up Type=0
Dn Type=3
Dn Slope=0.005
Boundary for River Rch & Prof#=UNT 061 in HW,Reach-1,7
Up Type=0
Dn Type=3
Dn Slope=0.005

--- UNT 061 in HW.g01 (geometry) ---

Geom Title=Existing Conditions

River Reach=UNT 061 in HW,Reach-1
Reach XY= 30
      1995130.80     13614105.84      1995130.80     13614025.84
      1995180.80     13613975.84      1995180.80     13613895.84
      1995170.80     13613885.84      1995170.80     13613745.84
      1995120.80     13613695.84      1995120.80     13613535.84
      1995110.80     13613525.84      1995110.80     13613515.84
      1995100.80     13613505.84      1995100.80     13613356.56
      1995122.88     13613229.83      1994978.21     13613080.44
      1994991.24     13612988.86      1994987.33     13612939.38
      1994996.44     13612885.99      1995001.65     13612828.70
      1994987.33     13612815.68      1994974.44     13612798.40
      1994916.28     13612761.94      1994856.39     13612548.40
      1994832.08     13612505.87      1994805.17     13612484.17
      1994759.16     13612479.83      1994701.87     13612478.09
      1994550.80     13612465.84      1994510.80     13612425.84
      1994500.80     13612425.84      1994490.80     13612415.84

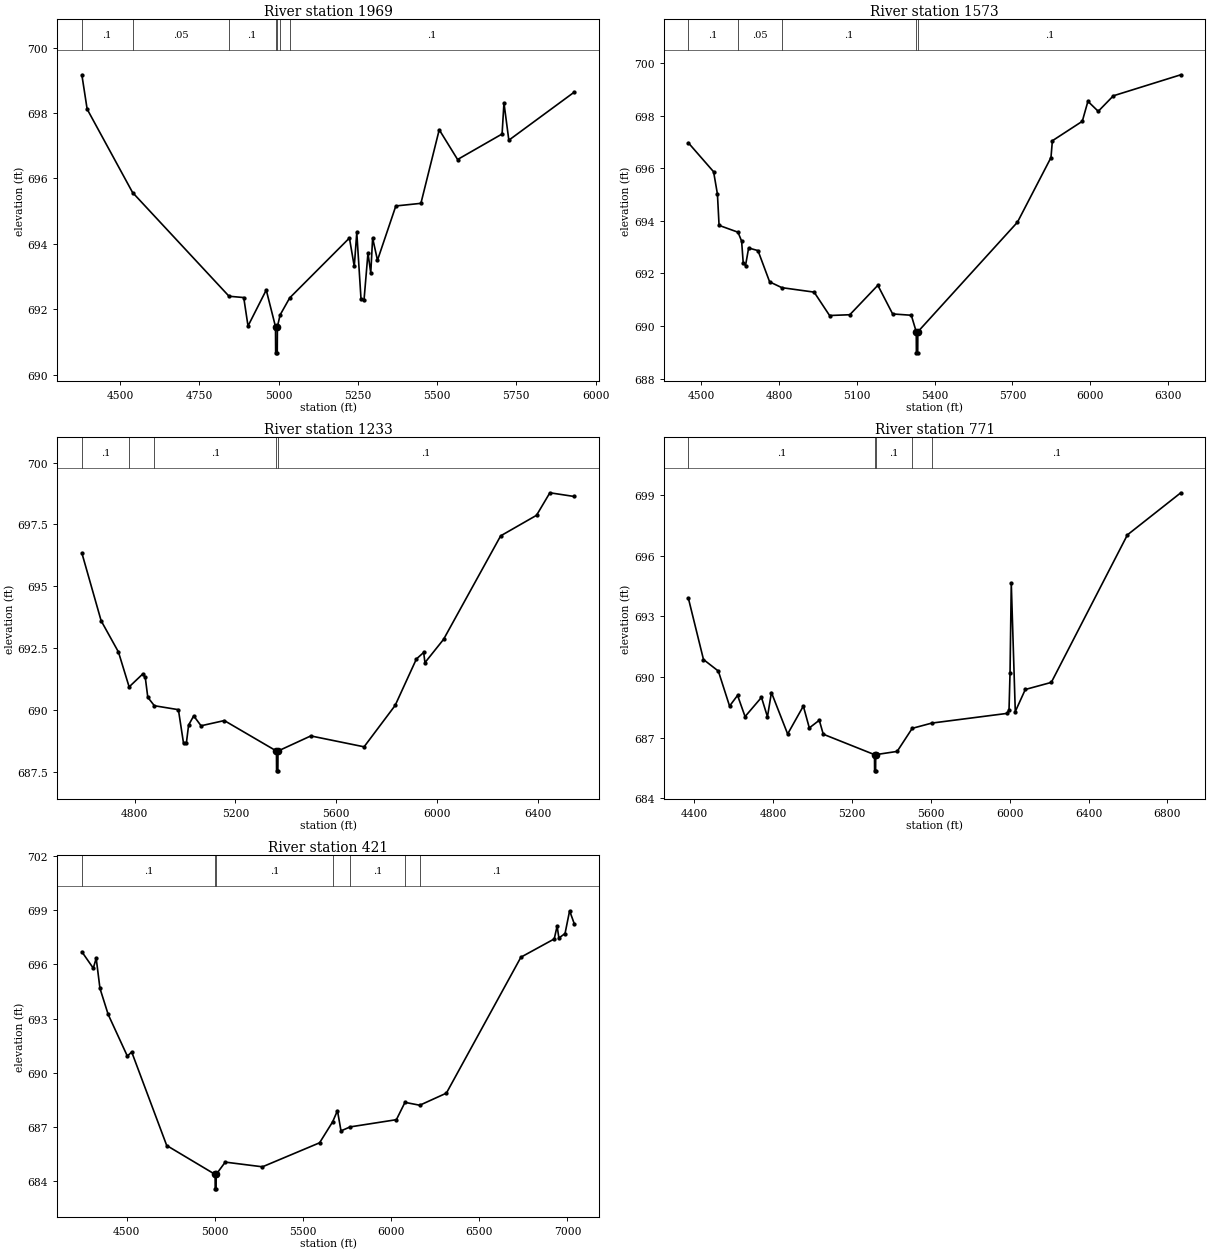
Type RM Length L Ch R = 1,1969,396,396,396
BEGIN DESCRIPTION:
UNT 061 in HW 1.0
END DESCRIPTION:
XS GIS Cut Line= 3
      1995724.08     13613651.67      1995166.79     13613958.96
      1994682.42     13614737.59
#Sta/Elev= 30
  4379.6  699.17  4396.3  698.12  4539.7  695.57  4843.9  692.40  4890.3  692.36
  4903.8  691.49  4961.3  692.59  4990.5  691.47  4991.0  690.67  4996.0  690.67
  4996.5  691.47  5005.1  691.83  5035.3  692.35  5223.7  694.18  5239.0  693.31
  5246.9  694.35  5260.3  692.31  5269.8  692.29  5282.2  693.72  5291.0  693.11
  5296.9  694.18  5312.2  693.50  5370.1  695.16  5449.2  695.24  5507.0  697.49
  5564.9  696.58  5705.3  697.36  5711.2  698.31  5726.6  697.17  5933.0  698.64
#Mann=7,-1,0
  4379.6     0.1       0  4539.7    0.05       0  4843.9     0.1       0
  4990.5    0.07       0  4996.5     0.1       0  5005.1    0.16       0
  5035.3     0.1       0
Bank Sta=4990.5,4996.5
Exp/Cntr=0.3,0.1

Type RM Length L Ch R = 1,1573,340,340,340
BEGIN DESCRIPTION:
UNT 061 in HW 2.0
END DESCRIPTION:
XS GIS Cut Line= 3
      1995578.21     13613274.08      1994783.97     13613805.31
      1994416.80     13614675.06
#Sta/Elev= 30
  4449.7  696.97  4547.0  695.87  4561.8  695.02  4568.1  693.83  4641.1  693.57
  4655.1  693.23  4661.2  692.41  4670.1  692.30  4682.2  692.97  4718.2  692.87
  4763.2  691.68  4810.4  691.46  4934.8  691.29  4994.4  690.40  5072.5  690.43
  5180.6  691.55  5237.7  690.46  5309.7  690.41  5328.8  689.78  5329.3  688.98
  5334.4  688.98  5334.9  689.78  5719.1  693.95  5848.5  696.41  5853.9  697.05
  5969.3  697.79  5991.0  698.55  6030.8  698.17  6089.1  698.76  6349.3  699.56
#Mann=5,-1,0
  4449.7     0.1       0  4641.1    0.05       0  4810.4     0.1       0
  5328.8    0.07       0  5334.9     0.1       0
Bank Sta=5328.8,5334.9
Exp/Cntr=0.3,0.1

Type RM Length L Ch R = 1,1233,462,462,462
BEGIN DESCRIPTION:
UNT 061 in HW 5.0
END DESCRIPTION:
XS GIS Cut Line= 3
      1995523.53     13613188.13      1994755.33     13613305.31
      1994441.08     13614438.15
#Sta/Elev= 30
  4591.2  696.35  4667.7  693.61  4736.3  692.35  4778.7  690.94  4832.5  691.46
  4842.6  691.33  4852.7  690.52  4878.7  690.18  4974.1  690.02  4994.3  688.67
  5005.5  688.66  5014.6  689.40  5034.8  689.77  5063.9  689.37  5156.2  689.58
  5362.9  688.35  5363.4  687.55  5368.5  687.55  5369.0  688.35  5499.1  688.96
  5710.4  688.52  5833.5  690.19  5918.0  692.07  5946.7  692.33  5951.8  691.92
  6025.6  692.86  6252.0  697.04  6394.2  697.87  6447.2  698.78  6543.9  698.63
#Mann=5,-1,0
  4591.2     0.1       0  4778.7    0.05       0  4878.7     0.1       0
  5362.9    0.07       0  5369.0     0.1       0
Bank Sta=5362.9,5369
Exp/Cntr=0.3,0.1

Type RM Length L Ch R = 1,771,350,350,350
BEGIN DESCRIPTION:
UNT 061 in HW 3.0
END DESCRIPTION:
XS GIS Cut Line= 3
      1995621.69     13612758.43      1994662.45     13612897.33
      1994402.33     13614401.66
#Sta/Elev= 30
  4371.5  693.89  4448.1  690.86  4523.4  690.29  4580.3  688.56  4620.8  689.09
  4658.8  688.04  4742.0  688.99  4772.3  688.03  4792.5  689.23  4874.7  687.18
  4954.2  688.56  4984.5  687.48  5035.0  687.86  5055.2  687.17  5314.9  686.16
  5315.4  685.36  5320.5  685.36  5321.0  686.16  5429.7  686.32  5506.1  687.46
  5605.5  687.72  5987.9  688.20  5996.8  688.39  6001.9  690.21  6008.2  694.62
  6028.5  688.29  6079.2  689.38  6211.1  689.73  6596.8  697.02  6867.4  699.10
#Mann=5,-1,0
  4371.5     0.1       0  5314.9    0.07       0  5321.0     0.1       0
  5506.1    0.05       0  5605.5     0.1       0
Bank Sta=5314.9,5321
Exp/Cntr=0.3,0.1

Type RM Length L Ch R = 1,421,0,0,0
BEGIN DESCRIPTION:
UNT 061 in HW 4.0
END DESCRIPTION:
XS GIS Cut Line= 3
      1995560.87     13612276.67      1994632.06     13612636.91
      1994341.43     13614411.05
#Sta/Elev= 30
  4244.8  696.70  4309.7  695.79  4326.2  696.34  4347.6  694.67  4394.1  693.23
  4503.0  690.92  4527.6  691.15  4726.3  685.97  5000.9  684.37  5001.4  683.57
  5006.5  683.57  5007.0  684.37  5058.4  685.05  5269.5  684.79  5593.7  686.12
  5667.7  687.28  5695.1  687.90  5715.3  686.78  5767.0  687.00  6029.5  687.40
  6078.2  688.36  6162.0  688.20  6313.2  688.87  6736.1  696.40  6925.1  697.41
  6941.5  698.12  6951.6  697.46  6986.4  697.71  7012.4  698.97  7038.8  698.25
#Mann=7,-1,0
  4244.8     0.1       0  5000.9    0.07       0  5007.0     0.1       0
  5667.7    0.05       0  5767.0     0.1       0  6078.2    0.08       0
  6162.0     0.1       0
Bank Sta=5000.9,5007
Exp/Cntr=0.3,0.1

Chan Stop Cuts=-1