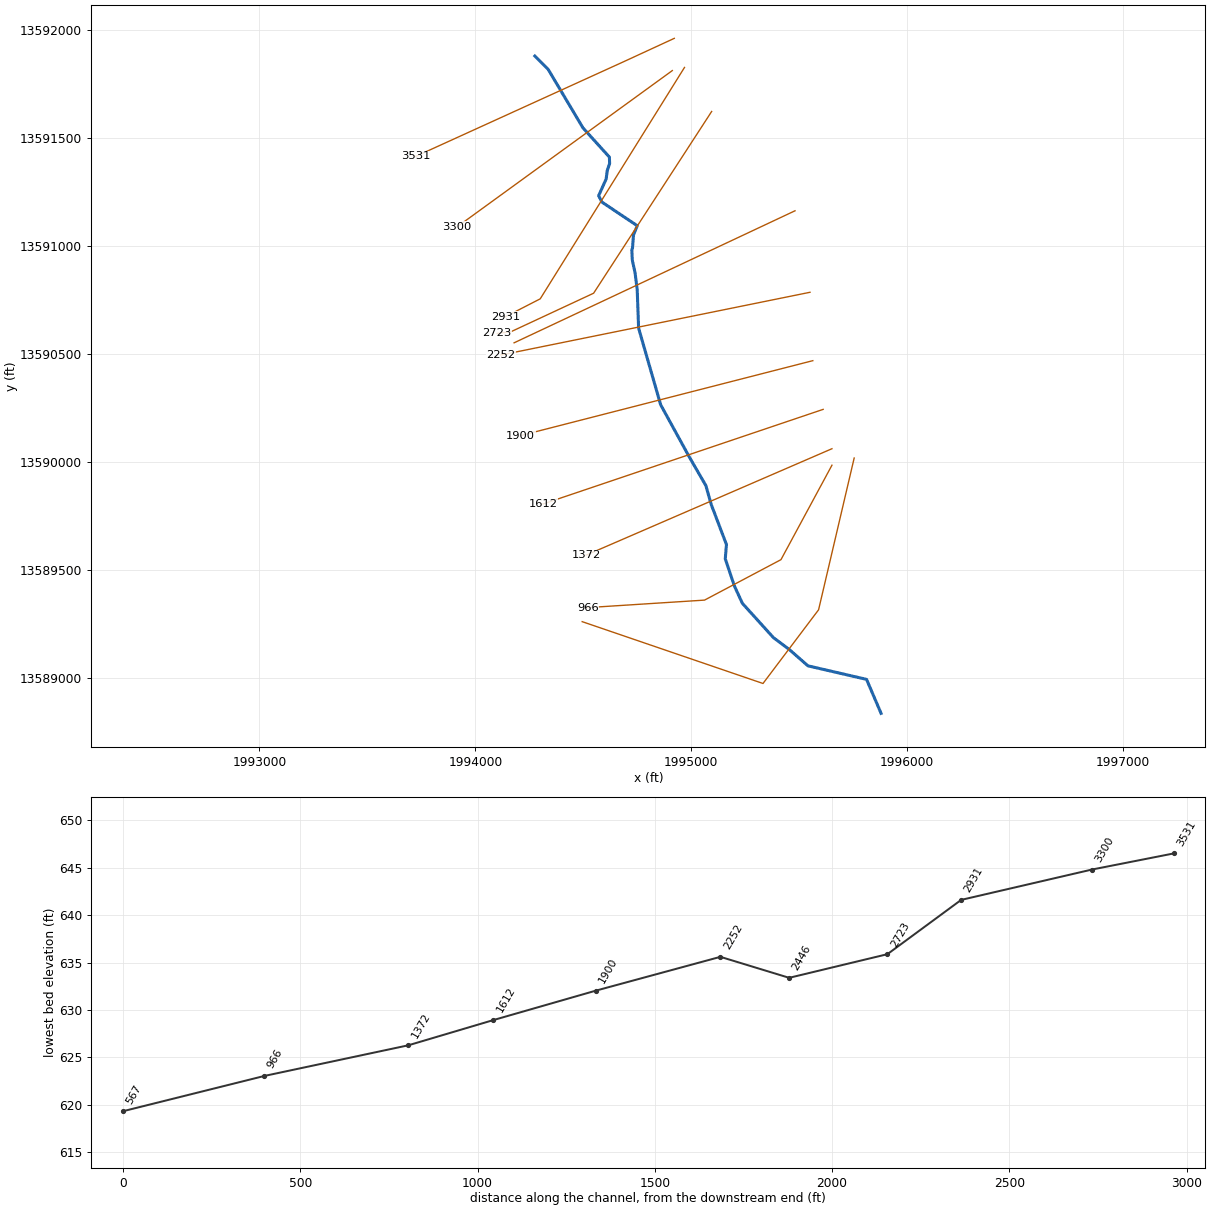
--- UNT 062 in HW.prj (project) ---

Proj Title=UNT 062 in HW Base Level Engineering
Current Plan=p01
Default Exp/Contr=0.3,0.1
English Units
Geom File=g01
Flow File=f01
Plan File=p01
BEGIN DESCRIPTION:
UNT 062 in HW
END DESCRIPTION:

--- UNT 062 in HW.p01 (plan) ---

Plan Title=Multiple Run
Short Identifier=Multiple
Geom File=g01
Flow File=f01
Subcritical Flow
K Sum by GR= 0
Std Step Tol= 0.01
Critical Tol= 0.01
Num of Std Step Trials= 20
Max Error Tol= 0.3
Flow Tol Ratio= 0.001
Split Flow NTrial= 30
Split Flow Tol= 0.02
Split Flow Ratio= 0.02
Log Output Level= 0
Friction Slope Method= 1
Unsteady Friction Slope Method= 2
Unsteady Bridges Friction Slope Method= 1
Parabolic Critical Depth
Global Vel Dist=  1 , 1 , 1
Global Log Level= 0
CheckData=True
Encroach Param= -1, 0, 0, 0
BEGIN DESCRIPTION:
Multiple Run
END DESCRIPTION:

--- UNT 062 in HW.f01 (steady flow) ---

Flow Title=Multiple
Number of Profiles=7
Profile Names=10-year,25-year,50-year,1pct_min,100-year,1pct_plu,500-year
River Rch & RM= UNT 062 in HW,Reach-1,3531
     271     367     444     267     533    1064     770
Boundary for River Rch & Prof#=UNT 062 in HW,Reach-1,1
Up Type=0
Dn Type=3
Dn Slope=0.005
Boundary for River Rch & Prof#=UNT 062 in HW,Reach-1,2
Up Type=0
Dn Type=3
Dn Slope=0.005
Boundary for River Rch & Prof#=UNT 062 in HW,Reach-1,3
Up Type=0
Dn Type=3
Dn Slope=0.005
Boundary for River Rch & Prof#=UNT 062 in HW,Reach-1,4
Up Type=0
Dn Type=3
Dn Slope=0.005
Boundary for River Rch & Prof#=UNT 062 in HW,Reach-1,5
Up Type=0
Dn Type=3
Dn Slope=0.005
Boundary for River Rch & Prof#=UNT 062 in HW,Reach-1,6
Up Type=0
Dn Type=3
Dn Slope=0.005
Boundary for River Rch & Prof#=UNT 062 in HW,Reach-1,7
Up Type=0
Dn Type=3
Dn Slope=0.005

--- UNT 062 in HW.g01 (geometry) ---

Geom Title=Existing Conditions

River Reach=UNT 062 in HW,Reach-1
Reach XY= 30
      1994275.80     13591879.54      1994337.56     13591817.78
      1994498.60     13591546.96      1994621.21     13591411.32
      1994622.30     13591382.02      1994611.45     13591349.47
      1994606.02     13591309.33      1994571.30     13591232.29
      1994586.49     13591202.99      1994750.33     13591093.40
      1994732.76     13591049.74      1994728.42     13590991.15
      1994725.16     13590980.30      1994727.33     13590934.72
      1994740.35     13590873.96      1994750.12     13590796.92
      1994756.63     13590618.97      1994858.62     13590264.15
      1994993.17     13590018.92      1995068.04     13589889.80
      1995093.00     13589801.91      1995163.53     13589616.36
      1995158.10     13589550.17      1995200.42     13589424.31
      1995237.31     13589344.01      1995381.63     13589184.51
      1995454.33     13589130.25      1995541.13     13589054.30
      1995812.62     13588991.58      1995879.99     13588834.07

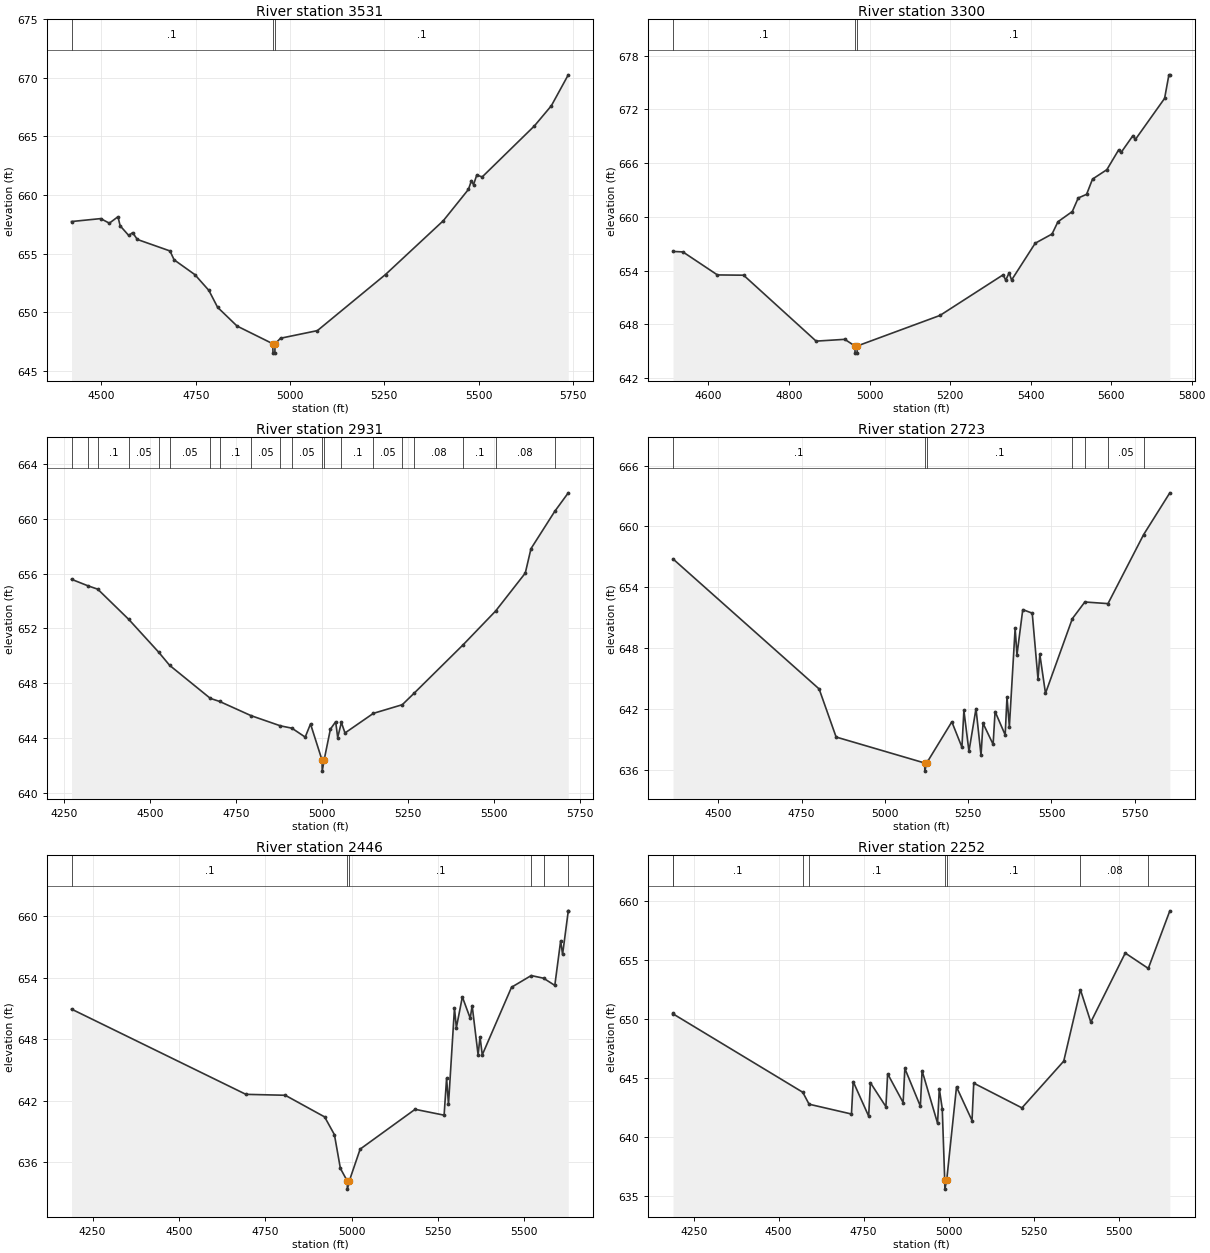
Type RM Length L Ch R = 1,3531,231,231,231
BEGIN DESCRIPTION:
UNT 062 in HW 2.0
END DESCRIPTION:
XS GIS Cut Line= 3
      1994922.07     13591961.57      1994696.34     13591857.38
      1993724.10     13591414.67
#Sta/Elev= 30
  4420.8  657.73  4498.1  657.98  4521.1  657.59  4544.0  658.14  4549.7  657.37
  4572.5  656.54  4582.8  656.78  4595.4  656.20  4681.8  655.22  4692.9  654.46
  4747.8  653.20  4785.0  651.85  4808.1  650.41  4859.7  648.81  4954.4  647.30
  4954.9  646.50  4959.9  646.50  4960.4  647.30  4974.9  647.77  5072.6  648.42
  5253.2  653.21  5406.4  657.80  5473.0  660.47  5481.0  661.22  5486.5  660.87
  5495.0  661.69  5509.6  661.54  5647.9  665.89  5692.8  667.61  5737.7  670.25
#Mann=3,-1,0
  4420.8     0.1       0  4954.4    0.07       0  4960.4     0.1       0
Bank Sta=4954.4,4960.4
Exp/Cntr=0.3,0.1

Type RM Length L Ch R = 1,3300,369,369,369
BEGIN DESCRIPTION:
Mapping XS 9f372e83
END DESCRIPTION:
XS GIS Cut Line= 2
      1994912.78     13591812.18      1993914.48     13591087.33
#Sta/Elev= 30
  4512.1  656.15  4536.5  656.10  4622.3  653.53  4687.3  653.50  4867.4  646.14
  4938.5  646.34  4963.6  645.60  4964.1  644.80  4969.1  644.80  4969.6  645.60
  5175.1  649.01  5332.0  653.55  5338.1  652.94  5346.7  653.76  5352.8  652.96
  5411.5  657.07  5453.3  658.10  5468.0  659.47  5503.6  660.61  5518.3  662.12
  5539.1  662.53  5553.8  664.23  5589.4  665.28  5618.8  667.50  5624.9  667.21
  5654.3  669.09  5660.5  668.67  5732.8  673.24  5743.5  675.87  5745.8  675.87
#Mann=3,-1,0
  4512.1     0.1       0  4963.6    0.07       0  4969.6     0.1       0
Bank Sta=4963.6,4969.6
Exp/Cntr=0.3,0.1

Type RM Length L Ch R = 1,2931,208,208,208
BEGIN DESCRIPTION:
Mapping XS 2be5420a
END DESCRIPTION:
XS GIS Cut Line= 3
      1994969.22     13591826.75      1994300.79     13590754.66
      1994140.22     13590672.21
#Sta/Elev= 30
  4271.3  655.58  4319.5  655.10  4347.5  654.86  4438.0  652.65  4524.6  650.27
  4556.5  649.31  4674.9  646.90  4701.6  646.68  4793.4  645.64  4878.6  644.90
  4911.8  644.73  4950.6  644.08  4966.0  645.04  4999.5  642.40  5000.0  641.60
  5005.5  642.40  5023.8  644.66  5039.1  645.20  5045.0  644.05  5055.7  645.15
  5066.2  644.38  5148.7  645.81  5232.7  646.44  5267.2  647.28  5409.7  650.81
  5504.1  653.27  5590.2  656.03  5606.8  657.81  5675.6  660.52  5715.2  661.88
#Mann=20,-1,0
  4271.3    0.05       0  4319.5    0.08       0  4347.5     0.1       0
  4438.0    0.05       0  4524.6     0.1       0  4556.5    0.05       0
  4674.9    0.08       0  4701.6     0.1       0  4793.4    0.05       0
  4878.6     0.1       0  4911.8    0.05       0  4999.5    0.04       0
  5005.5    0.05       0  5055.7     0.1       0  5148.7    0.05       0
  5232.7     0.1       0  5267.2    0.08       0  5409.7     0.1       0
  5504.1    0.08       0  5675.6     0.1       0
Bank Sta=4999.5,5005.5
Exp/Cntr=0.3,0.1

Type RM Length L Ch R = 1,2723,277,277,277
BEGIN DESCRIPTION:
Mapping XS faeb0b93
END DESCRIPTION:
XS GIS Cut Line= 4
      1995095.05     13591622.70      1994548.19     13590780.71
      1994166.24     13590602.75      1994101.18     13590594.08
#Sta/Elev= 30
  4364.3  656.79  4802.7  643.98  4853.7  639.24  5119.5  636.68  5120.0  635.88
  5125.5  636.68  5201.0  640.74  5231.3  638.24  5237.2  641.86  5252.4  637.83
  5273.5  642.04  5288.6  637.44  5294.6  640.60  5324.9  638.52  5330.8  641.75
  5361.1  639.45  5366.6  643.19  5373.7  640.27  5391.0  649.96  5396.5  647.34
  5413.9  651.80  5442.3  651.45  5459.6  644.97  5465.1  647.39  5482.1  643.55
  5562.7  650.91  5600.2  652.55  5669.7  652.39  5776.6  659.19  5855.3  663.31
#Mann=7,-1,0
  4364.3     0.1       0  5119.5    0.07       0  5125.5     0.1       0
  5562.7    0.08       0  5600.2     0.1       0  5669.7    0.05       0
  5776.6     0.1       0
Bank Sta=5119.5,5125.5
Exp/Cntr=0.3,0.1

Type RM Length L Ch R = 1,2446,194,194,194
BEGIN DESCRIPTION:
Mapping XS ceaa920f
END DESCRIPTION:
XS GIS Cut Line= 2
      1995481.36     13591162.66      1994179.67     13590550.86
#Sta/Elev= 30
  4189.1  650.94  4694.0  642.63  4808.0  642.54  4922.0  640.43  4950.3  638.70
  4967.6  635.41  4987.4  634.19  4987.9  633.39  4993.4  634.19  5024.8  637.29
  5183.9  641.17  5267.9  640.60  5275.1  644.20  5280.6  641.66  5297.9  651.03
  5303.4  649.13  5320.7  652.13  5343.5  650.05  5349.1  651.28  5366.3  646.48
  5371.9  648.23  5378.4  646.48  5463.1  653.07  5520.1  654.21  5555.9  653.95
  5588.4  653.25  5605.4  657.61  5610.9  656.27  5627.2  660.46  5627.4  660.52
#Mann=6,-1,0
  4189.1     0.1       0  4987.4    0.07       0  4993.4     0.1       0
  5520.1    0.05       0  5555.9    0.08       0  5627.2    0.05       0
Bank Sta=4987.4,4993.4
Exp/Cntr=0.3,0.1

Type RM Length L Ch R = 1,2252,352,352,352
BEGIN DESCRIPTION:
Mapping XS 931dafa5
END DESCRIPTION:
XS GIS Cut Line= 2
      1995550.81     13590785.05      1994119.22     13590494.39
#Sta/Elev= 30
  4189.5  650.45  4190.5  650.40  4570.9  643.79  4589.5  642.78  4714.1  641.95
  4719.2  644.69  4764.7  641.77  4769.8  644.60  4815.4  642.57  4820.5  645.35
  4866.0  642.92  4871.1  645.80  4916.7  642.61  4921.8  645.61  4967.3  641.17
  4972.4  644.09  4981.1  642.40  4988.3  636.40  4988.8  635.60  4994.3  636.40
  5023.0  644.24  5068.6  641.40  5073.7  644.56  5215.4  642.47  5338.3  646.42
  5387.5  652.45  5417.9  649.72  5519.2  655.56  5587.0  654.26  5650.3  659.13
#Mann=8,-1,0
  4189.5    0.08       0  4190.5     0.1       0  4570.9    0.08       0
  4589.5     0.1       0  4988.3    0.07       0  4994.3     0.1       0
  5387.5    0.08       0  5587.0    0.05       0
Bank Sta=4988.3,4994.3
Exp/Cntr=0.3,0.1

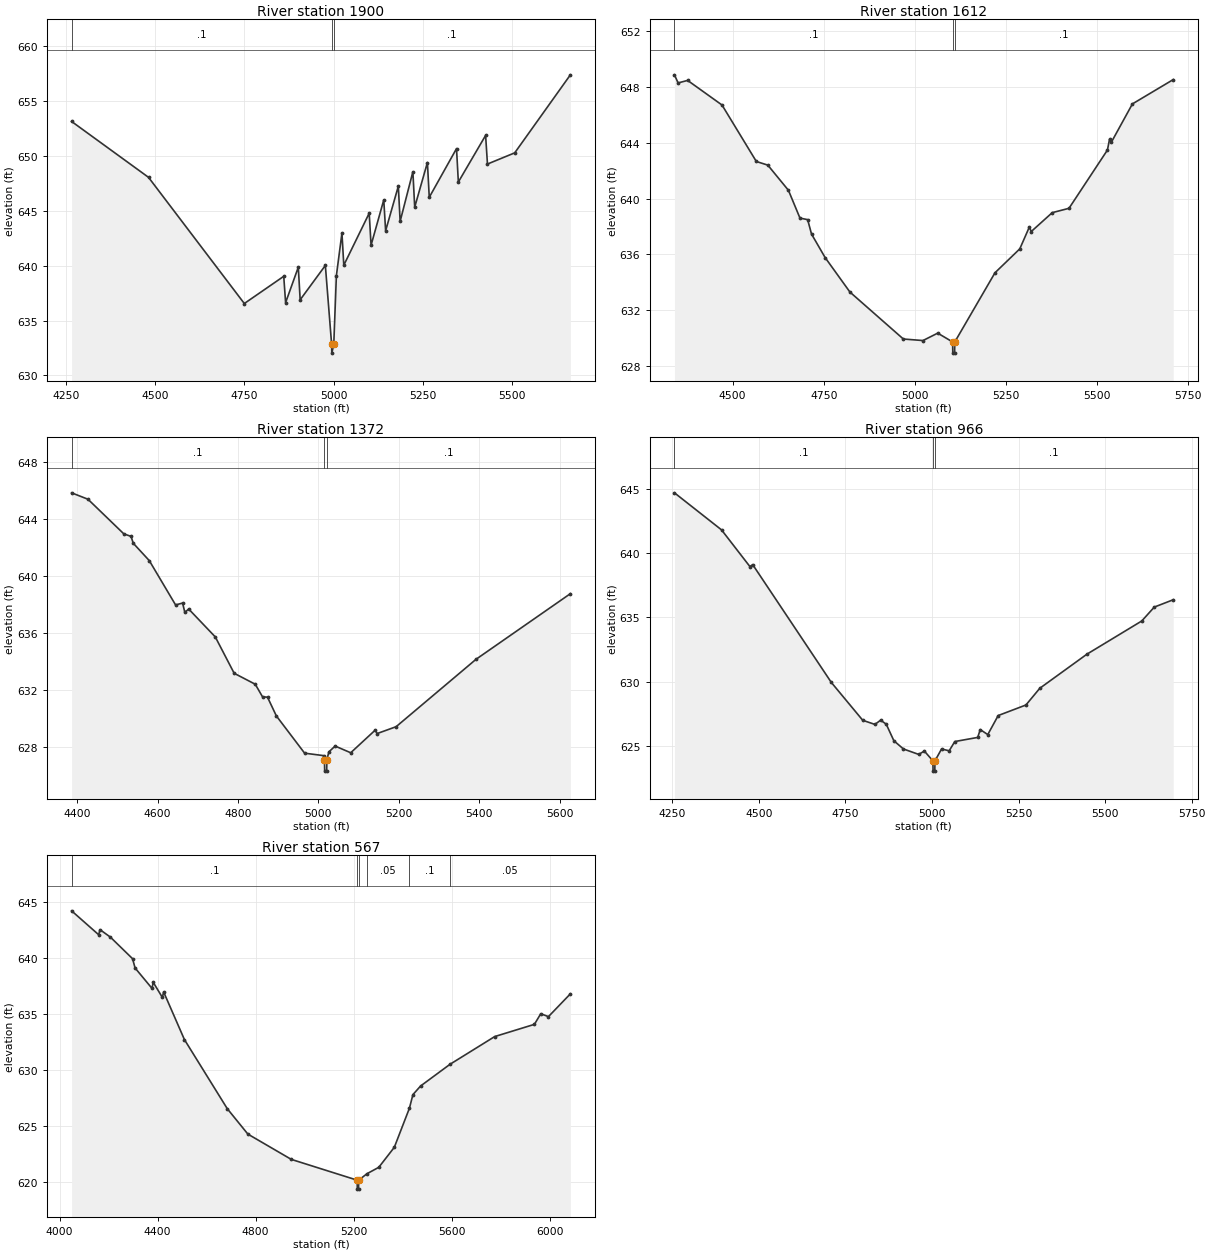
Type RM Length L Ch R = 1,1900,288,288,288
BEGIN DESCRIPTION:
Mapping XS d83821ff
END DESCRIPTION:
XS GIS Cut Line= 2
      1995563.79     13590468.20      1994209.79     13590121.02
#Sta/Elev= 30
  4265.6  653.14  4481.1  648.05  4749.6  636.55  4860.1  639.03  4865.3  636.63
  4900.9  639.86  4906.1  636.89  4976.7  640.02  4994.3  632.83  4994.8  632.03
  5000.3  632.83  5007.6  639.09  5023.2  642.97  5028.4  640.04  5099.6  644.78
  5104.8  641.86  5140.4  645.99  5145.6  643.18  5181.2  647.24  5186.3  644.04
  5222.0  648.56  5227.1  645.33  5262.7  649.40  5267.9  646.23  5344.3  650.67
  5349.4  647.62  5425.8  651.87  5431.0  649.26  5507.4  650.28  5663.4  657.39
#Mann=3,-1,0
  4265.6     0.1       0  4994.3    0.07       0  5000.3     0.1       0
Bank Sta=4994.3,5000.3
Exp/Cntr=0.3,0.1

Type RM Length L Ch R = 1,1612,240,240,240
BEGIN DESCRIPTION:
Mapping XS 2afba4ba
END DESCRIPTION:
XS GIS Cut Line= 2
      1995611.56     13590242.51      1994313.80     13589804.14
#Sta/Elev= 30
  4340.1  648.85  4350.1  648.27  4376.3  648.45  4470.7  646.69  4565.0  642.65
  4596.5  642.39  4653.1  640.59  4684.8  638.60  4705.9  638.49  4716.5  637.46
  4753.8  635.78  4822.0  633.31  4968.7  629.95  5022.6  629.84  5063.1  630.37
  5104.0  629.74  5104.5  628.94  5109.5  628.94  5110.0  629.74  5220.4  634.69
  5288.5  636.40  5314.7  637.96  5320.0  637.64  5377.6  638.99  5423.6  639.30
  5529.2  643.47  5534.9  644.24  5540.2  644.04  5597.8  646.77  5709.9  648.51
#Mann=3,-1,0
  4340.1     0.1       0  5104.0    0.07       0  5110.0     0.1       0
Bank Sta=5104,5110
Exp/Cntr=0.3,0.1

Type RM Length L Ch R = 1,1372,406,406,406
BEGIN DESCRIPTION:
Mapping XS dd1efe47
END DESCRIPTION:
XS GIS Cut Line= 2
      1995652.38     13590060.23      1994513.43     13589567.15
#Sta/Elev= 30
  4386.0  645.82  4426.7  645.37  4515.9  642.94  4533.9  642.76  4539.4  642.28
  4579.3  641.06  4644.7  637.95  4662.2  638.08  4667.7  637.43  4677.4  637.66
  4743.6  635.70  4790.5  633.15  4843.0  632.38  4861.0  631.50  4873.5  631.47
  4895.4  630.16  4965.8  627.54  5012.8  627.37  5015.2  627.08  5015.7  626.28
  5020.7  626.28  5021.2  627.08  5026.1  627.63  5041.7  628.04  5080.5  627.57
  5141.1  629.15  5146.5  628.92  5193.5  629.40  5392.2  634.13  5627.1  638.74
#Mann=3,-1,0
  4386.0     0.1       0  5015.2    0.07       0  5021.2     0.1       0
Bank Sta=5015.2,5021.2
Exp/Cntr=0.3,0.1

Type RM Length L Ch R = 1,966,399,399,399
BEGIN DESCRIPTION:
Mapping XS 6a8f319e
END DESCRIPTION:
XS GIS Cut Line= 4
      1995652.38     13589983.87      1995416.24     13589546.33
      1995062.08     13589358.83      1994520.42     13589324.11
#Sta/Elev= 30
  4256.1  644.68  4392.1  641.80  4474.0  638.95  4482.1  639.10  4709.3  629.94
  4800.0  627.00  4835.2  626.68  4851.6  627.01  4867.8  626.70  4889.9  625.41
  4917.6  624.77  4961.6  624.35  4977.9  624.61  5002.6  623.85  5003.1  623.05
  5008.1  623.05  5008.6  623.85  5027.6  624.77  5049.6  624.63  5065.9  625.35
  5132.0  625.67  5139.4  626.28  5161.1  625.89  5191.2  627.37  5271.3  628.19
  5311.4  629.49  5447.5  632.14  5605.9  634.72  5642.1  635.80  5696.8  636.37
#Mann=3,-1,0
  4256.1     0.1       0  5002.6    0.07       0  5008.6     0.1       0
Bank Sta=5002.6,5008.6
Exp/Cntr=0.3,0.1

Type RM Length L Ch R = 1,567,0,0,0
BEGIN DESCRIPTION:
UNT 062 in HW 1.0
END DESCRIPTION:
XS GIS Cut Line= 4
      1995755.37     13590017.14      1995590.43     13589313.98
      1995332.91     13588972.55      1994495.25     13589259.00
#Sta/Elev= 30
  4049.1  644.21  4159.7  642.07  4164.8  642.53  4207.3  641.86  4297.8  639.93
  4308.1  639.10  4377.0  637.28  4382.1  637.82  4419.4  636.47  4424.6  636.96
  4509.4  632.70  4684.3  626.52  4768.3  624.25  4945.4  621.99  5214.4  620.13
  5214.9  619.33  5219.9  619.33  5220.4  620.13  5254.5  620.71  5302.5  621.28
  5365.9  623.07  5427.6  626.57  5441.8  627.78  5473.1  628.55  5593.1  630.49
  5775.6  632.97  5937.4  634.06  5963.4  635.01  5994.7  634.75  6084.3  636.79
#Mann=6,-1,0
  4049.1     0.1       0  5214.4    0.07       0  5220.4     0.1       0
  5254.5    0.05       0  5427.6     0.1       0  5593.1    0.05       0
Bank Sta=5214.4,5220.4
Exp/Cntr=0.3,0.1

Chan Stop Cuts=-1