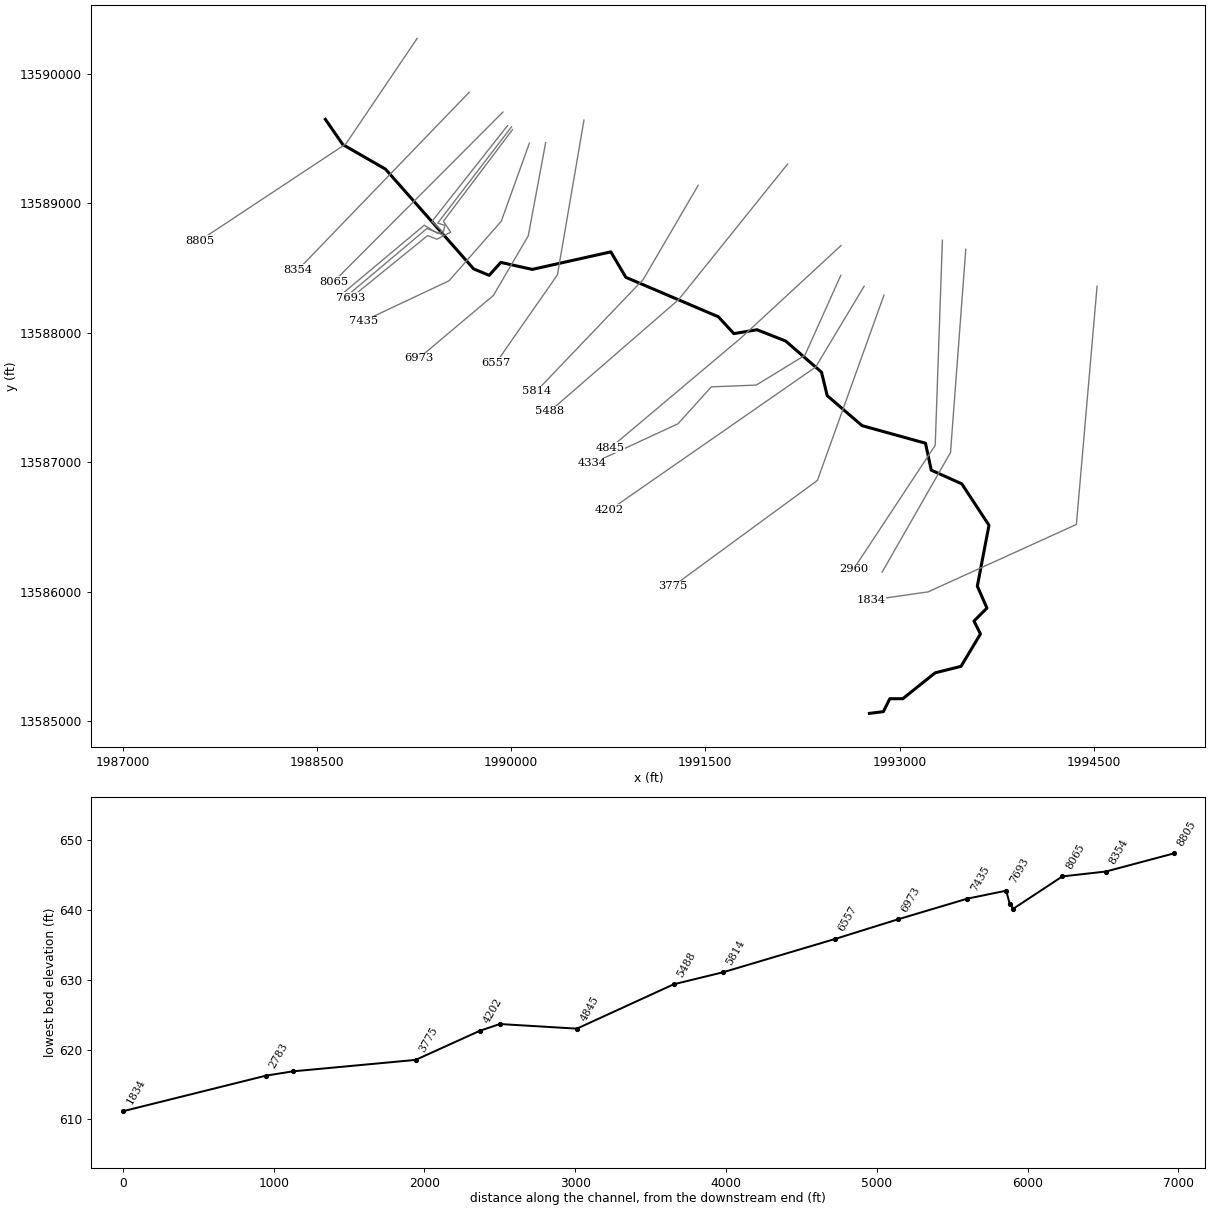
--- UNT 063 in HW.prj (project) ---

Proj Title=UNT 063 in HW Base Level Engineering
Current Plan=p01
Default Exp/Contr=0.3,0.1
English Units
Geom File=g01
Flow File=f01
Plan File=p01
BEGIN DESCRIPTION:
UNT 063 in HW
END DESCRIPTION:

--- UNT 063 in HW.p01 (plan) ---

Plan Title=Multiple Run
Short Identifier=Multiple
Geom File=g01
Flow File=f01
Subcritical Flow
K Sum by GR= 0
Std Step Tol= 0.01
Critical Tol= 0.01
Num of Std Step Trials= 20
Max Error Tol= 0.3
Flow Tol Ratio= 0.001
Split Flow NTrial= 30
Split Flow Tol= 0.02
Split Flow Ratio= 0.02
Log Output Level= 0
Friction Slope Method= 1
Unsteady Friction Slope Method= 2
Unsteady Bridges Friction Slope Method= 1
Parabolic Critical Depth
Global Vel Dist=  1 , 1 , 1
Global Log Level= 0
CheckData=True
Encroach Param= -1, 0, 0, 0
BEGIN DESCRIPTION:
Multiple Run
END DESCRIPTION:

--- UNT 063 in HW.f01 (steady flow) ---

Flow Title=Multiple
Number of Profiles=7
Profile Names=10-year,25-year,50-year,1pct_min,100-year,1pct_plu,500-year
River Rch & RM= UNT 063 in HW,Reach-1,8805
     629     895    1120     695    1386    2766    2130
River Rch & RM= UNT 063 in HW,Reach-1,8354
     778    1120    1411     881    1757    3506    2735
River Rch & RM= UNT 063 in HW,Reach-1,5488
    1075    1569    1996    1256    2506    4999    3965
Boundary for River Rch & Prof#=UNT 063 in HW,Reach-1,1
Up Type=0
Dn Type=3
Dn Slope=0.005
Boundary for River Rch & Prof#=UNT 063 in HW,Reach-1,2
Up Type=0
Dn Type=3
Dn Slope=0.005
Boundary for River Rch & Prof#=UNT 063 in HW,Reach-1,3
Up Type=0
Dn Type=3
Dn Slope=0.005
Boundary for River Rch & Prof#=UNT 063 in HW,Reach-1,4
Up Type=0
Dn Type=3
Dn Slope=0.005
Boundary for River Rch & Prof#=UNT 063 in HW,Reach-1,5
Up Type=0
Dn Type=3
Dn Slope=0.005
Boundary for River Rch & Prof#=UNT 063 in HW,Reach-1,6
Up Type=0
Dn Type=3
Dn Slope=0.005
Boundary for River Rch & Prof#=UNT 063 in HW,Reach-1,7
Up Type=0
Dn Type=3
Dn Slope=0.005

--- UNT 063 in HW.g01 (geometry) ---

Geom Title=Existing Conditions

River Reach=UNT 063 in HW,Reach-1
Reach XY= 30
      1988565.80     13589649.54      1988700.80     13589454.54
      1989030.80     13589264.54      1989710.80     13588494.54
      1989830.80     13588444.54      1989920.80     13588544.54
      1990163.64     13588490.54      1990770.41     13588625.96
      1990886.29     13588429.34      1991600.80     13588124.68
      1991720.80     13587994.54      1991899.45     13588024.54
      1992120.80     13587937.13      1992397.49     13587697.11
      1992441.46     13587515.52      1992710.99     13587283.75
      1993200.44     13587148.28      1993245.16     13586940.18
      1993480.80     13586834.54      1993690.80     13586514.54
      1993600.80     13586044.54      1993675.00     13585875.00
      1993575.00     13585775.00      1993625.00     13585675.00
      1993475.00     13585425.00      1993275.00     13585375.00
      1993025.00     13585175.00      1992925.00     13585175.00
      1992875.00     13585075.00      1992767.41     13585061.81

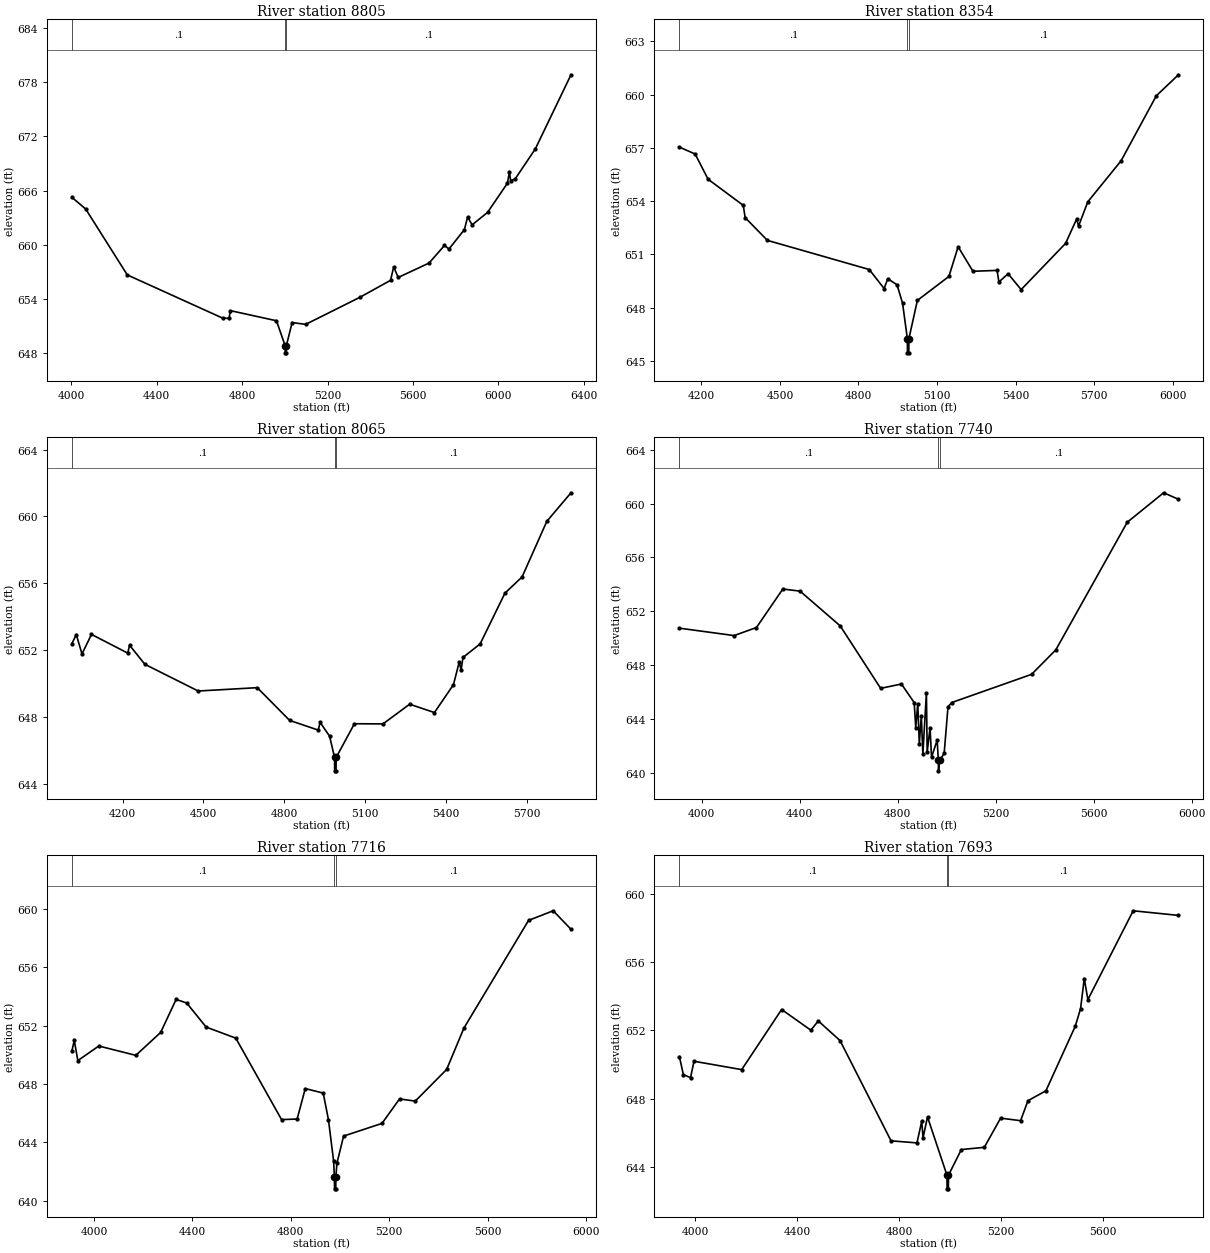
Type RM Length L Ch R = 1,8805,451,451,451
BEGIN DESCRIPTION:
UNT 063 in HW 11.0
END DESCRIPTION:
XS GIS Cut Line= 3
      1989274.98     13590274.97      1988724.39     13589459.74
      1987595.91     13588713.21
#Sta/Elev= 30
  4002.7  665.25  4067.1  663.96  4261.9  656.67  4708.5  651.89  4738.4  651.87
  4744.5  652.72  4960.3  651.60  5000.9  648.85  5001.4  648.05  5006.4  648.05
  5006.9  648.85  5033.7  651.40  5097.2  651.20  5349.9  654.18  5494.4  656.07
  5509.4  657.55  5530.5  656.39  5674.9  657.98  5747.1  659.93  5768.2  659.54
  5840.4  661.68  5855.5  663.08  5876.5  662.21  5948.7  663.58  6042.0  666.82
  6051.1  668.06  6057.1  667.08  6078.1  667.29  6172.7  670.62  6339.5  678.81
#Mann=3,-1,0
  4002.7     0.1       0  5000.9    0.07       0  5006.9     0.1       0
Bank Sta=5000.9,5006.9
Exp/Cntr=0.3,0.1

Type RM Length L Ch R = 1,8354,289,289,289
BEGIN DESCRIPTION:
Mapping XS 84b6a70f
END DESCRIPTION:
XS GIS Cut Line= 2
      1989676.63     13589858.38      1988353.70     13588486.83
#Sta/Elev= 30
  4116.2  657.04  4176.4  656.65  4225.8  655.23  4360.1  653.76  4367.3  653.07
  4452.2  651.79  4841.2  650.15  4897.8  649.08  4911.9  649.63  4947.2  649.29
  4968.4  648.25  4986.6  646.26  4987.1  645.46  4992.1  645.46  4992.6  646.26
  5024.9  648.41  5145.3  649.76  5180.5  651.43  5237.1  650.05  5329.2  650.10
  5336.2  649.45  5371.4  649.91  5421.1  649.02  5590.8  651.62  5633.3  653.00
  5640.2  652.59  5675.7  653.96  5802.8  656.27  5937.4  659.93  6021.8  661.11
#Mann=3,-1,0
  4116.2     0.1       0  4986.6    0.07       0  4992.6     0.1       0
Bank Sta=4986.6,4992.6
Exp/Cntr=0.3,0.1

Type RM Length L Ch R = 1,8065,325,325,325
BEGIN DESCRIPTION:
Mapping XS ee444cd7
END DESCRIPTION:
XS GIS Cut Line= 2
      1989937.08     13589705.64      1988629.04     13588394.13
#Sta/Elev= 30
  4011.9  652.38  4028.0  652.92  4049.2  651.76  4084.5  652.93  4218.9  651.81
  4225.9  652.28  4282.5  651.14  4480.5  649.54  4699.7  649.74  4819.9  647.78
  4926.0  647.20  4933.1  647.66  4968.4  646.83  4986.6  645.56  4987.1  644.76
  4992.1  644.76  4992.6  645.56  5060.3  647.58  5166.4  647.57  5265.4  648.75
  5357.3  648.25  5428.0  649.92  5449.3  651.27  5456.3  650.80  5463.4  651.55
  5527.0  652.36  5619.0  655.40  5682.6  656.37  5774.5  659.70  5864.2  661.41
#Mann=3,-1,0
  4011.9     0.1       0  4986.6    0.07       0  4992.6     0.1       0
Bank Sta=4986.6,4992.6
Exp/Cntr=0.3,0.1

Type RM Length L Ch R = 1,7740,24,24,24
BEGIN DESCRIPTION:
Mapping XS e230d41b
END DESCRIPTION:
XS GIS Cut Line= 6
      1989972.23     13589600.31      1989388.45     13588860.28
      1989468.75     13588784.32      1989431.85     13588769.13
      1989329.86     13588832.07      1988705.40     13588309.51
#Sta/Elev= 30
  3909.6  650.74  4132.9  650.19  4224.2  650.79  4331.7  653.65  4402.2  653.49
  4565.9  650.91  4730.9  646.27  4815.8  646.59  4867.9  645.21  4874.2  643.35
  4882.4  645.14  4888.7  642.15  4896.9  644.23  4903.2  641.38  4917.7  645.93
  4920.8  641.53  4932.5  643.34  4938.6  641.15  4961.5  642.42  4966.4  640.94
  4966.9  640.14  4972.4  640.94  4990.1  641.43  5005.8  644.89  5020.3  645.21
  5347.0  647.31  5445.9  649.13  5737.3  658.61  5885.7  660.80  5946.3  660.32
#Mann=3,-1,0
  3909.6     0.1       0  4966.4    0.07       0  4972.4     0.1       0
Bank Sta=4966.4,4972.4
Exp/Cntr=0.3,0.1

Type RM Length L Ch R = 1,7716,23,23,23
BEGIN DESCRIPTION:
Mapping XS 7734c3eb
END DESCRIPTION:
XS GIS Cut Line= 6
      1990003.05     13589591.06      1989433.59     13588847.98
      1989489.15     13588830.62      1989471.79     13588757.70
      1989350.26     13588806.31      1988732.23     13588285.50
#Sta/Elev= 30
  3910.6  650.28  3920.1  650.99  3934.6  649.61  4019.8  650.61  4170.2  649.97
  4271.0  651.54  4334.0  653.81  4377.0  653.56  4455.9  651.91  4576.4  651.15
  4762.4  645.56  4825.7  645.60  4858.7  647.69  4931.7  647.38  4953.0  645.54
  4973.9  642.71  4977.1  641.61  4977.6  640.81  4982.6  640.81  4983.1  641.61
  4987.1  642.55  5014.4  644.43  5170.4  645.30  5241.7  646.98  5305.6  646.83
  5433.1  649.00  5503.3  651.84  5766.0  659.23  5866.1  659.89  5938.4  658.62
#Mann=3,-1,0
  3910.6     0.1       0  4977.1    0.07       0  4983.1     0.1       0
Bank Sta=4977.1,4983.1
Exp/Cntr=0.3,0.1

Type RM Length L Ch R = 1,7693,258,258,258
BEGIN DESCRIPTION:
Mapping XS a4c9feaf
END DESCRIPTION:
XS GIS Cut Line= 6
      1990011.27     13589569.89      1989477.43     13588862.45
      1989533.85     13588777.81      1989427.51     13588723.56
      1989355.90     13588751.77      1988760.92     13588269.29
#Sta/Elev= 30
  3938.9  650.46  3954.4  649.41  3982.6  649.23  3996.1  650.19  4183.1  649.70
  4339.5  653.22  4454.0  652.01  4483.2  652.55  4568.5  651.40  4768.3  645.53
  4869.9  645.41  4888.4  646.67  4893.8  645.72  4911.2  646.93  4987.4  643.52
  4987.9  642.72  4992.9  642.72  4993.4  643.52  5043.8  645.02  5133.8  645.15
  5197.7  646.86  5276.0  646.71  5304.8  647.88  5375.2  648.46  5490.2  652.24
  5511.0  653.27  5525.4  655.03  5539.7  653.80  5717.2  659.00  5894.6  658.73
#Mann=3,-1,0
  3938.9     0.1       0  4987.4    0.07       0  4993.4     0.1       0
Bank Sta=4987.4,4993.4
Exp/Cntr=0.3,0.1

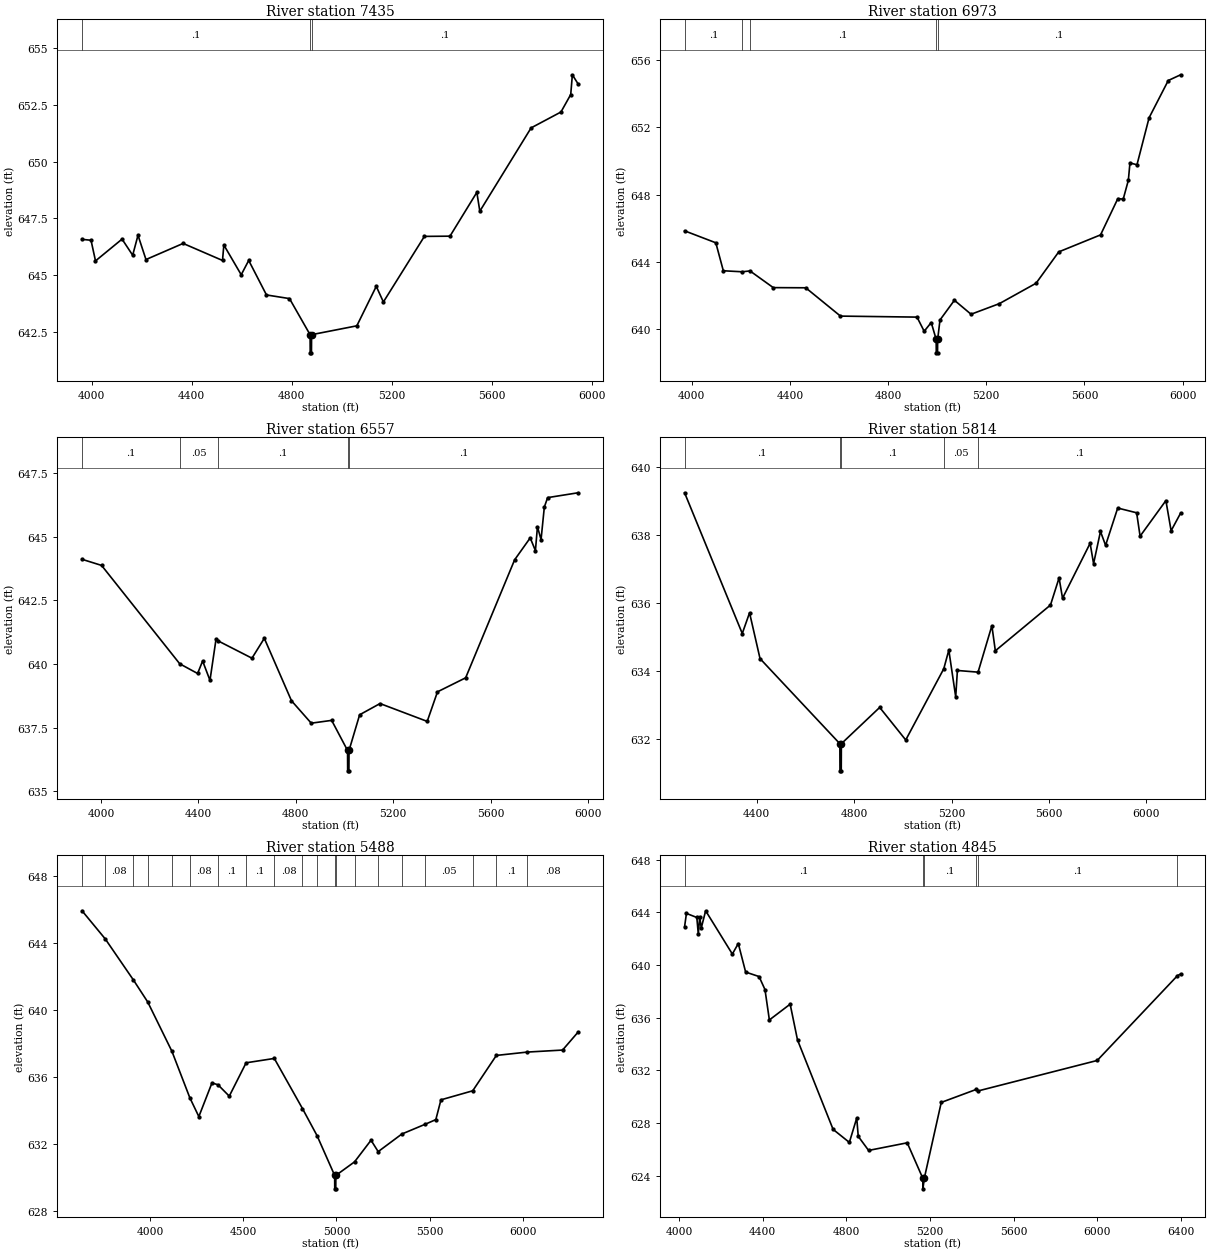
Type RM Length L Ch R = 1,7435,462,462,462
BEGIN DESCRIPTION:
Mapping XS 8d28efce
END DESCRIPTION:
XS GIS Cut Line= 4
      1990141.49     13589465.75      1989924.48     13588862.45
      1989520.83     13588402.38      1988858.50     13588090.69
#Sta/Elev= 30
  3960.9  646.58  3996.9  646.54  4014.8  645.63  4121.1  646.59  4163.6  645.88
  4184.9  646.76  4216.8  645.69  4365.5  646.40  4523.1  645.65  4528.5  646.33
  4598.0  645.02  4628.0  645.65  4699.1  644.13  4791.2  643.97  4873.6  642.38
  4874.1  641.58  4879.1  641.58  4879.6  642.38  5060.7  642.77  5138.5  644.51
  5167.0  643.82  5331.1  646.71  5433.5  646.72  5541.0  648.65  5553.0  647.82
  5758.2  651.49  5877.7  652.19  5916.8  652.96  5923.3  653.83  5946.1  653.43
#Mann=3,-1,0
  3960.9     0.1       0  4873.6    0.07       0  4879.6     0.1       0
Bank Sta=4873.6,4879.6
Exp/Cntr=0.3,0.1

Type RM Length L Ch R = 1,6973,416,416,416
BEGIN DESCRIPTION:
Mapping XS 5ddc7de3
END DESCRIPTION:
XS GIS Cut Line= 4
      1990267.36     13589470.08      1990132.81     13588749.60
      1989863.71     13588289.53      1989286.45     13587803.41
#Sta/Elev= 30
  3971.0  645.85  4098.2  645.14  4128.8  643.48  4205.4  643.42  4237.5  643.47
  4332.2  642.48  4464.5  642.47  4606.0  640.79  4917.8  640.73  4947.0  639.89
  4975.7  640.41  4995.8  639.41  4996.3  638.61  5001.4  638.61  5001.9  639.41
  5011.4  640.56  5070.1  641.73  5137.9  640.90  5253.3  641.53  5402.8  642.74
  5495.1  644.60  5665.5  645.61  5735.8  647.76  5757.8  647.73  5778.7  648.85
  5785.2  649.88  5813.8  649.77  5863.2  652.56  5941.3  654.77  5991.6  655.11
#Mann=5,-1,0
  3971.0     0.1       0  4205.4    0.05       0  4237.5     0.1       0
  4995.8    0.07       0  5001.9     0.1       0
Bank Sta=4995.8,5001.9
Exp/Cntr=0.3,0.1

Type RM Length L Ch R = 1,6557,743,743,743
BEGIN DESCRIPTION:
UNT 063 in HW 7.0
END DESCRIPTION:
XS GIS Cut Line= 3
      1990562.93     13589642.92      1990358.07     13588448.46
      1989885.84     13587771.37
#Sta/Elev= 30
  3922.1  644.11  4002.4  643.87  4323.4  640.01  4396.8  639.63  4417.5  640.12
  4447.6  639.36  4472.4  640.97  4480.8  640.91  4620.1  640.23  4670.8  641.01
  4782.4  638.56  4863.6  637.68  4947.5  637.79  5012.7  636.61  5013.2  635.81
  5018.3  635.81  5018.8  636.61  5062.4  638.01  5146.2  638.45  5339.9  637.75
  5382.1  638.91  5497.8  639.46  5699.0  644.09  5763.0  644.95  5784.4  644.45
  5792.7  645.39  5807.5  644.88  5821.0  646.16  5834.6  646.53  5959.5  646.72
#Mann=5,-1,0
  3922.1     0.1       0  4323.4    0.05       0  4480.8     0.1       0
  5012.7    0.07       0  5018.8     0.1       0
Bank Sta=5012.7,5018.8
Exp/Cntr=0.3,0.1

Type RM Length L Ch R = 1,5814,326,326,326
BEGIN DESCRIPTION:
UNT 063 in HW 6.0
END DESCRIPTION:
XS GIS Cut Line= 3
      1991444.86     13589139.40      1991021.26     13588413.73
      1990195.26     13587549.55
#Sta/Elev= 30
  4104.4  639.25  4341.1  635.10  4371.0  635.71  4414.0  634.36  4741.6  631.85
  4742.1  631.05  4747.3  631.05  4747.8  631.85  4905.1  632.92  5012.0  631.96
  5168.1  634.06  5188.8  634.61  5217.1  633.23  5224.0  634.01  5308.8  633.96
  5365.5  635.33  5379.7  634.59  5606.1  635.94  5641.3  636.74  5655.5  636.14
  5768.7  637.76  5782.9  637.16  5811.2  638.11  5832.2  637.70  5881.9  638.80
  5959.6  638.66  5973.8  637.97  6079.7  639.02  6101.1  638.13  6140.1  638.65
#Mann=5,-1,0
  4104.4     0.1       0  4741.6    0.07       0  4747.8     0.1       0
  5168.1    0.05       0  5308.8     0.1       0
Bank Sta=4741.6,4747.8
Exp/Cntr=0.3,0.1

Type RM Length L Ch R = 1,5488,643,643,643
BEGIN DESCRIPTION:
UNT 063 in HW 5.0
END DESCRIPTION:
XS GIS Cut Line= 3
      1992135.84     13589304.34      1991294.53     13588257.83
      1990299.03     13587394.14
#Sta/Elev= 30
  3635.2  645.93  3759.8  644.25  3910.9  641.80  3987.5  640.49  4117.2  637.55
  4213.2  634.78  4261.8  633.65  4332.2  635.66  4364.3  635.55  4425.0  634.87
  4515.4  636.86  4666.5  637.12  4817.6  634.13  4895.6  632.52  4990.3  630.14
  4990.8  629.34  4996.2  629.34  4996.7  630.14  5097.0  630.95  5185.4  632.24
  5223.8  631.56  5350.6  632.61  5477.4  633.20  5533.0  633.47  5560.5  634.65
  5730.9  635.19  5857.7  637.30  6023.6  637.50  6212.9  637.62  6295.9  638.69
#Mann=20,-1,0
  3635.2    0.08       0  3759.8    0.08       0  3910.9    0.08       0
  3987.5    0.05       0  4117.2    0.05       0  4213.2    0.08       0
  4364.3     0.1       0  4515.4     0.1       0  4666.5    0.08       0
  4817.6     0.1       0  4895.6    0.05       0  4990.3    0.07       0
  4996.7    0.08       0  5097.0     0.1       0  5223.8     0.1       0
  5350.6    0.08       0  5477.4    0.05       0  5730.9     0.1       0
  5857.7     0.1       0  6023.6    0.08       0
Bank Sta=4990.3,4996.7
Exp/Cntr=0.3,0.1

Type RM Length L Ch R = 1,4845,511,511,511
BEGIN DESCRIPTION:
UNT 063 in HW 4.0
END DESCRIPTION:
XS GIS Cut Line= 3
      1992548.00     13588674.50      1991777.17     13587962.69
      1990766.72     13587111.97
#Sta/Elev= 30
  4027.2  642.92  4036.0  643.93  4085.7  643.62  4092.7  642.35  4099.5  643.68
  4106.8  642.82  4127.8  644.13  4255.4  640.84  4283.8  641.64  4318.9  639.47
  4383.0  639.13  4411.3  638.14  4432.3  635.83  4531.6  637.03  4566.7  634.31
  4736.8  627.51  4814.5  626.52  4849.7  628.37  4857.0  626.98  4906.4  625.91
  5091.0  626.49  5165.5  623.79  5166.0  622.99  5172.5  623.79  5253.6  629.56
  5421.1  630.55  5428.7  630.43  5998.8  632.75  6382.4  639.20  6397.3  639.32
#Mann=6,-1,0
  4027.2     0.1       0  5165.5    0.07       0  5172.5     0.1       0
  5421.1    0.05       0  5428.7     0.1       0  6382.4    0.08       0
Bank Sta=5165.5,5172.5
Exp/Cntr=0.3,0.1

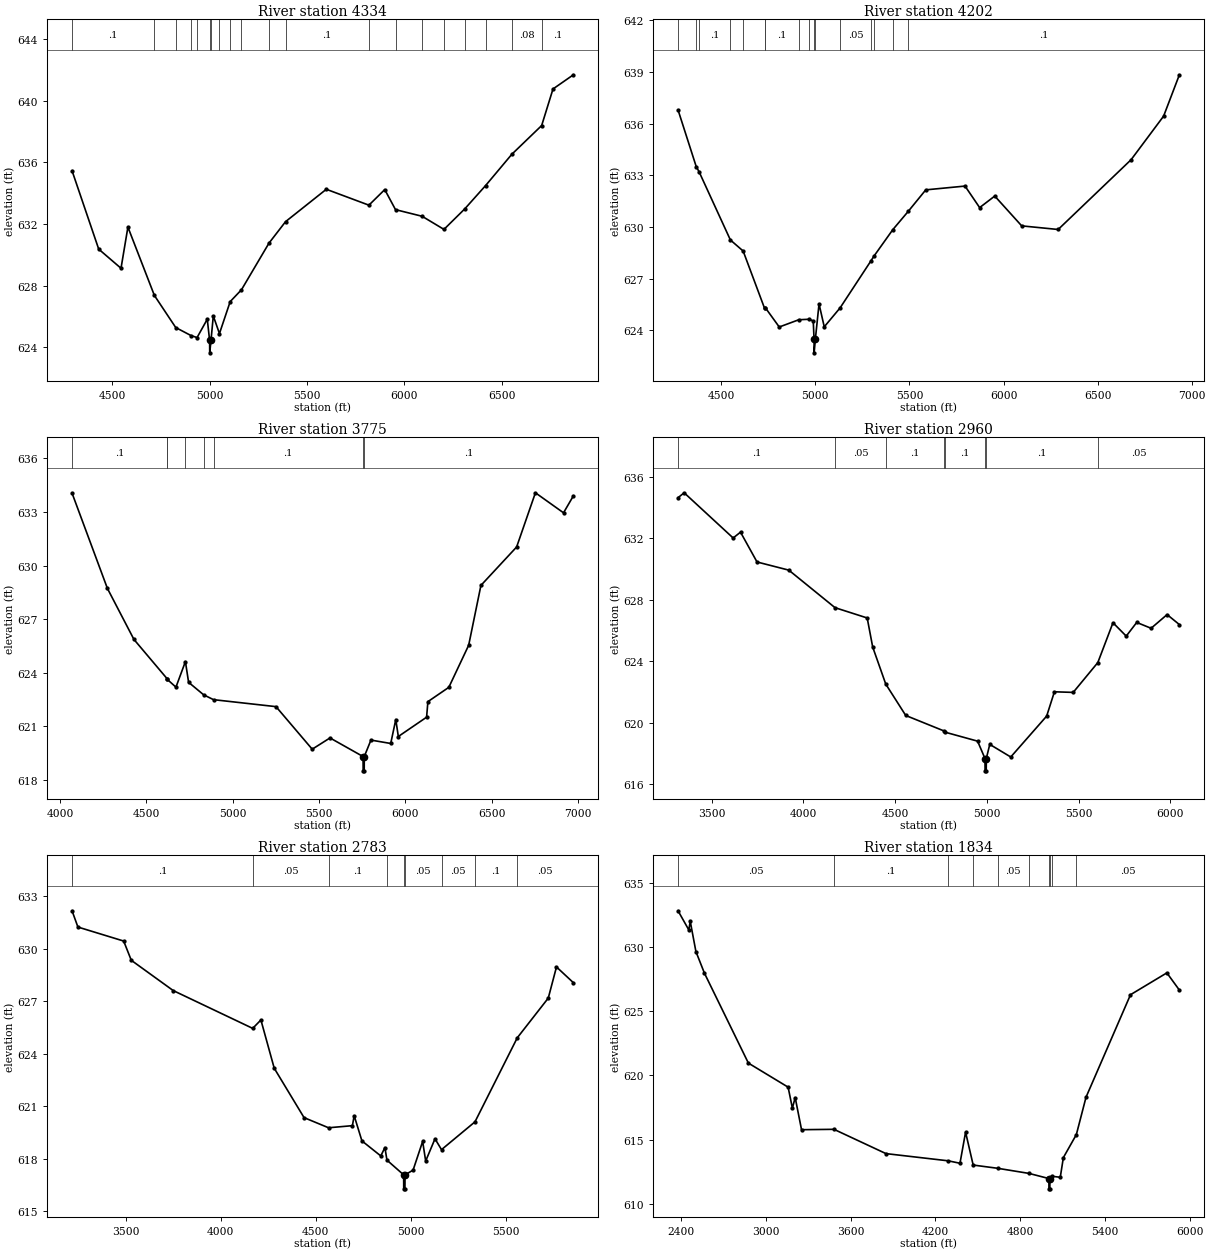
Type RM Length L Ch R = 1,4334,132,132,132
BEGIN DESCRIPTION:
UNT 063 in HW 3.0
END DESCRIPTION:
XS GIS Cut Line= 6
      1992546.39     13588444.43      1992268.60     13587826.35
      1991893.60     13587597.18      1991546.38     13587583.29
      1991289.44     13587298.57      1990629.88     13586993.09
#Sta/Elev= 30
  4292.5  635.45  4429.5  630.37  4544.0  629.13  4579.4  631.80  4715.4  627.37
  4825.0  625.29  4903.5  624.77  4934.6  624.64  4987.1  625.83  4999.1  624.45
  4999.6  623.65  5006.1  624.45  5018.0  626.04  5049.6  624.90  5104.7  626.97
  5162.8  627.74  5304.0  630.76  5389.0  632.15  5598.4  634.25  5817.2  633.22
  5898.6  634.23  5953.8  632.93  6090.5  632.50  6202.7  631.65  6309.6  632.98
  6416.5  634.49  6551.4  636.52  6704.5  638.38  6762.7  640.75  6867.5  641.67
#Mann=20,-1,0
  4292.5     0.1       0  4715.4    0.05       0  4825.0    0.08       0
  4903.5     0.1       0  4934.6    0.08       0  4999.1    0.07       0
  5006.1    0.08       0  5049.6     0.1       0  5104.7    0.05       0
  5162.8     0.1       0  5304.0    0.08       0  5389.0     0.1       0
  5817.2    0.08       0  5953.8    0.05       0  6090.5    0.05       0
  6202.7     0.1       0  6309.6    0.05       0  6416.5     0.1       0
  6551.4    0.08       0  6704.5     0.1       0
Bank Sta=4999.1,5006.1
Exp/Cntr=0.3,0.1

Type RM Length L Ch R = 1,4202,427,427,427
BEGIN DESCRIPTION:
UNT 063 in HW 2.0
END DESCRIPTION:
XS GIS Cut Line= 3
      1992726.92     13588361.05      1992351.94     13587736.07
      1990761.62     13586631.88
#Sta/Elev= 30
  4270.0  636.79  4366.7  633.50  4381.9  633.20  4548.4  629.24  4616.1  628.60
  4730.1  625.27  4733.3  625.32  4808.0  624.19  4911.8  624.61  4967.5  624.64
  4988.7  624.54  4993.0  623.49  4993.5  622.69  5000.0  623.49  5019.5  625.53
  5047.2  624.20  5131.5  625.30  5294.3  628.01  5312.5  628.32  5411.6  629.84
  5493.5  630.90  5586.8  632.15  5795.5  632.37  5873.2  631.12  5953.5  631.79
  6096.7  630.06  6290.5  629.85  6678.2  633.90  6851.1  636.43  6934.9  638.83
#Mann=16,-1,0
  4270.0     0.1       0  4366.7    0.08       0  4381.9     0.1       0
  4548.4    0.05       0  4616.1     0.1       0  4730.1    0.08       0
  4733.3     0.1       0  4911.8    0.05       0  4967.5    0.08       0
  4993.0    0.07       0  5000.0    0.08       0  5131.5    0.05       0
  5294.3    0.08       0  5312.5     0.1       0  5411.6    0.05       0
  5493.5     0.1       0
Bank Sta=4993,5000
Exp/Cntr=0.3,0.1

Type RM Length L Ch R = 1,3775,815,815,815
BEGIN DESCRIPTION:
Mapping XS 5a151b7b
END DESCRIPTION:
XS GIS Cut Line= 3
      1992879.70     13588291.59      1992365.82     13586861.07
      1991248.90     13586042.46
#Sta/Elev= 30
  4068.9  634.05  4273.8  628.72  4427.4  625.87  4619.8  623.67  4621.0  623.63
  4670.9  623.20  4725.7  624.63  4744.2  623.47  4831.6  622.77  4888.7  622.50
  5250.6  622.11  5460.4  619.73  5563.5  620.36  5755.0  619.32  5755.6  618.52
  5761.6  618.52  5762.1  619.32  5800.7  620.24  5915.3  620.05  5944.6  621.39
  5959.3  620.44  6123.1  621.52  6130.7  622.39  6251.9  623.19  6366.8  625.54
  6437.9  628.89  6644.8  631.04  6753.6  634.07  6916.5  632.95  6973.7  633.90
#Mann=8,-1,0
  4068.9     0.1       0  4619.8    0.08       0  4621.0    0.05       0
  4725.7     0.1       0  4831.6    0.05       0  4888.7     0.1       0
  5755.0    0.07       0  5762.1     0.1       0
Bank Sta=5755,5762.1
Exp/Cntr=0.3,0.1

Type RM Length L Ch R = 1,2960,177,177,177
BEGIN DESCRIPTION:
Mapping XS d617dcdc
END DESCRIPTION:
XS GIS Cut Line= 3
      1993331.10     13588715.26      1993275.55     13587131.91
      1992643.58     13586173.54
#Sta/Elev= 30
  3317.5  634.64  3350.9  634.96  3617.9  632.02  3658.0  632.40  3748.0  630.46
  3921.2  629.93  4173.0  627.49  4348.4  626.82  4378.4  624.93  4449.6  622.52
  4558.5  620.48  4767.7  619.47  4770.9  619.40  4950.1  618.81  4990.3  617.68
  4990.9  616.88  4997.1  616.88  4997.6  617.68  5016.4  618.60  5130.8  617.78
  5326.5  620.44  5368.7  622.02  5471.1  621.98  5605.3  623.92  5687.9  626.51
  5760.1  625.64  5817.3  626.53  5895.6  626.15  5982.9  627.04  6049.8  626.39
#Mann=8,-1,0
  3317.5     0.1       0  4173.0    0.05       0  4449.6     0.1       0
  4767.7    0.05       0  4770.9     0.1       0  4990.3    0.07       0
  4997.6     0.1       0  5605.3    0.05       0
Bank Sta=4990.3,4997.6
Exp/Cntr=0.3,0.1

Type RM Length L Ch R = 1,2783,949,949,949
BEGIN DESCRIPTION:
Mapping XS 1b026fc5
END DESCRIPTION:
XS GIS Cut Line= 3
      1993511.66     13588645.81      1993393.60     13587076.35
      1992865.81     13586152.71
#Sta/Elev= 30
  3217.5  632.16  3248.4  631.23  3489.1  630.43  3529.2  629.33  3749.8  627.60
  4167.9  625.44  4211.1  625.92  4281.3  623.16  4438.1  620.34  4567.0  619.76
  4692.5  619.88  4701.8  620.45  4742.6  619.01  4841.9  618.15  4863.5  618.63
  4874.3  617.91  4962.1  617.07  4962.6  616.27  4968.8  616.27  4969.4  617.07
  5011.8  617.34  5062.1  618.98  5078.0  617.86  5127.0  619.13  5161.3  618.51
  5337.5  620.10  5559.8  624.90  5723.0  627.17  5766.2  628.95  5855.2  628.05
#Mann=9,-1,0
  3217.5     0.1       0  4167.9    0.05       0  4567.0     0.1       0
  4874.3    0.05       0  4962.1    0.07       0  4969.4    0.05       0
  5161.3    0.05       0  5337.5     0.1       0  5559.8    0.05       0
Bank Sta=4962.1,4969.4
Exp/Cntr=0.3,0.1

Type RM Length L Ch R = 1,1834,0,0,0
BEGIN DESCRIPTION:
UNT 063 in HW 1.0
END DESCRIPTION:
XS GIS Cut Line= 4
      1994525.54     13588361.03      1994365.82     13586520.79
      1993219.99     13585999.96      1992782.44     13585937.45
#Sta/Elev= 30
  2378.4  632.81  2454.7  631.32  2464.8  631.99  2504.9  629.64  2565.1  627.96
  2876.3  620.96  3157.4  619.09  3187.5  617.46  3207.5  618.28  3252.4  615.78
  3481.7  615.81  3849.9  613.92  4290.1  613.36  4373.6  613.17  4413.2  615.59
  4467.0  613.03  4639.3  612.78  4862.1  612.38  5002.7  611.98  5003.3  611.18
  5009.5  611.18  5010.0  611.98  5022.0  612.16  5083.3  612.08  5105.2  613.61
  5197.1  615.40  5265.6  618.31  5580.2  626.28  5837.6  627.98  5926.2  626.64
#Mann=10,-1,0
  2378.4    0.05       0  3481.7     0.1       0  4290.1    0.05       0
  4467.0     0.1       0  4639.3    0.05       0  4862.1     0.1       0
  5002.7    0.07       0  5010.0     0.1       0  5022.0    0.12       0
  5197.1    0.05       0
Bank Sta=5002.7,5010
Exp/Cntr=0.3,0.1

Chan Stop Cuts=-1