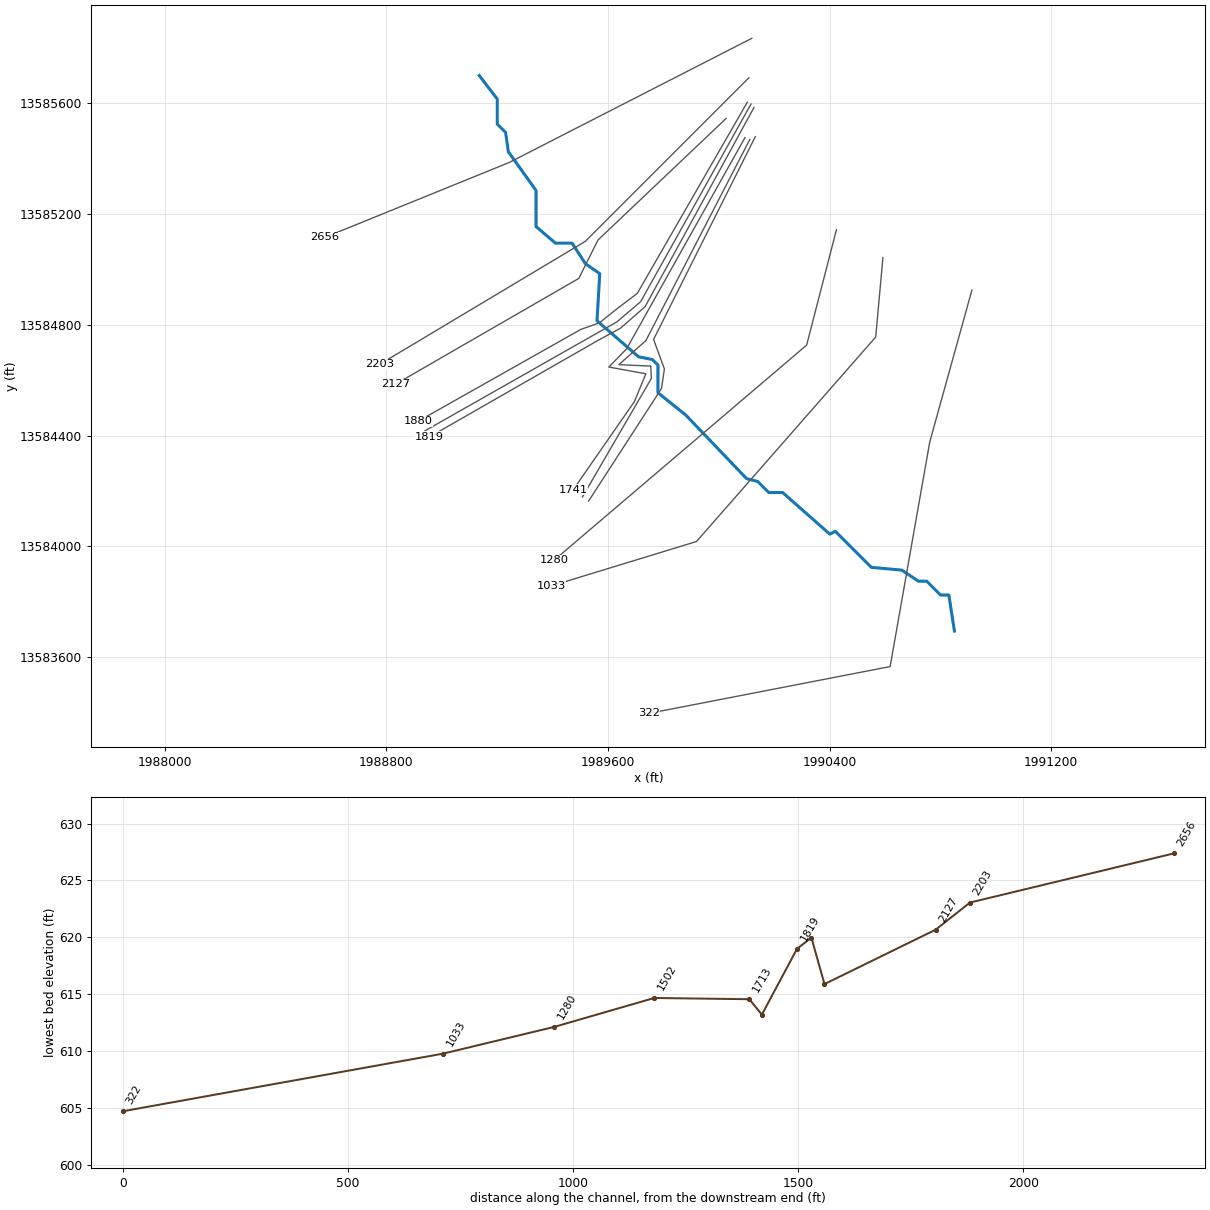
--- UNT 064 in HW.prj (project) ---

Proj Title=UNT 064 in HW Base Level Engineering
Current Plan=p01
Default Exp/Contr=0.3,0.1
English Units
Geom File=g01
Flow File=f01
Plan File=p01
BEGIN DESCRIPTION:
UNT 064 in HW
END DESCRIPTION:

--- UNT 064 in HW.p01 (plan) ---

Plan Title=Multiple Run
Short Identifier=Multiple
Geom File=g01
Flow File=f01
Subcritical Flow
K Sum by GR= 0
Std Step Tol= 0.01
Critical Tol= 0.01
Num of Std Step Trials= 20
Max Error Tol= 0.3
Flow Tol Ratio= 0.001
Split Flow NTrial= 30
Split Flow Tol= 0.02
Split Flow Ratio= 0.02
Log Output Level= 0
Friction Slope Method= 1
Unsteady Friction Slope Method= 2
Unsteady Bridges Friction Slope Method= 1
Parabolic Critical Depth
Global Vel Dist=  1 , 1 , 1
Global Log Level= 0
CheckData=True
Encroach Param= -1, 0, 0, 0
BEGIN DESCRIPTION:
Multiple Run
END DESCRIPTION:

--- UNT 064 in HW.f01 (steady flow) ---

Flow Title=Multiple
Number of Profiles=7
Profile Names=10-year,25-year,50-year,1pct_min,100-year,1pct_plu,500-year
River Rch & RM= UNT 064 in HW,Reach-1,2656
     243     325     390     233     465     928     661
Boundary for River Rch & Prof#=UNT 064 in HW,Reach-1,1
Up Type=0
Dn Type=3
Dn Slope=0.005
Boundary for River Rch & Prof#=UNT 064 in HW,Reach-1,2
Up Type=0
Dn Type=3
Dn Slope=0.005
Boundary for River Rch & Prof#=UNT 064 in HW,Reach-1,3
Up Type=0
Dn Type=3
Dn Slope=0.005
Boundary for River Rch & Prof#=UNT 064 in HW,Reach-1,4
Up Type=0
Dn Type=3
Dn Slope=0.005
Boundary for River Rch & Prof#=UNT 064 in HW,Reach-1,5
Up Type=0
Dn Type=3
Dn Slope=0.005
Boundary for River Rch & Prof#=UNT 064 in HW,Reach-1,6
Up Type=0
Dn Type=3
Dn Slope=0.005
Boundary for River Rch & Prof#=UNT 064 in HW,Reach-1,7
Up Type=0
Dn Type=3
Dn Slope=0.005

--- UNT 064 in HW.g01 (geometry) ---

Geom Title=Existing Conditions

River Reach=UNT 064 in HW,Reach-1
Reach XY= 30
      1989135.80     13585699.54      1989200.80     13585614.54
      1989200.80     13585524.54      1989230.80     13585494.54
      1989240.80     13585424.54      1989340.80     13585284.54
      1989340.80     13585154.54      1989410.80     13585094.54
      1989470.80     13585094.54      1989519.38     13585019.98
      1989570.80     13584984.54      1989560.80     13584814.54
      1989710.80     13584684.54      1989760.80     13584674.54
      1989780.80     13584654.54      1989780.80     13584554.54
      1989880.80     13584474.54      1990100.80     13584244.54
      1990140.80     13584234.54      1990180.80     13584194.54
      1990230.80     13584194.54      1990400.80     13584044.54
      1990420.80     13584054.54      1990550.80     13583924.54
      1990660.80     13583914.54      1990720.80     13583874.54
      1990750.80     13583874.54      1990800.80     13583824.54
      1990830.80     13583824.54      1990850.80     13583694.54

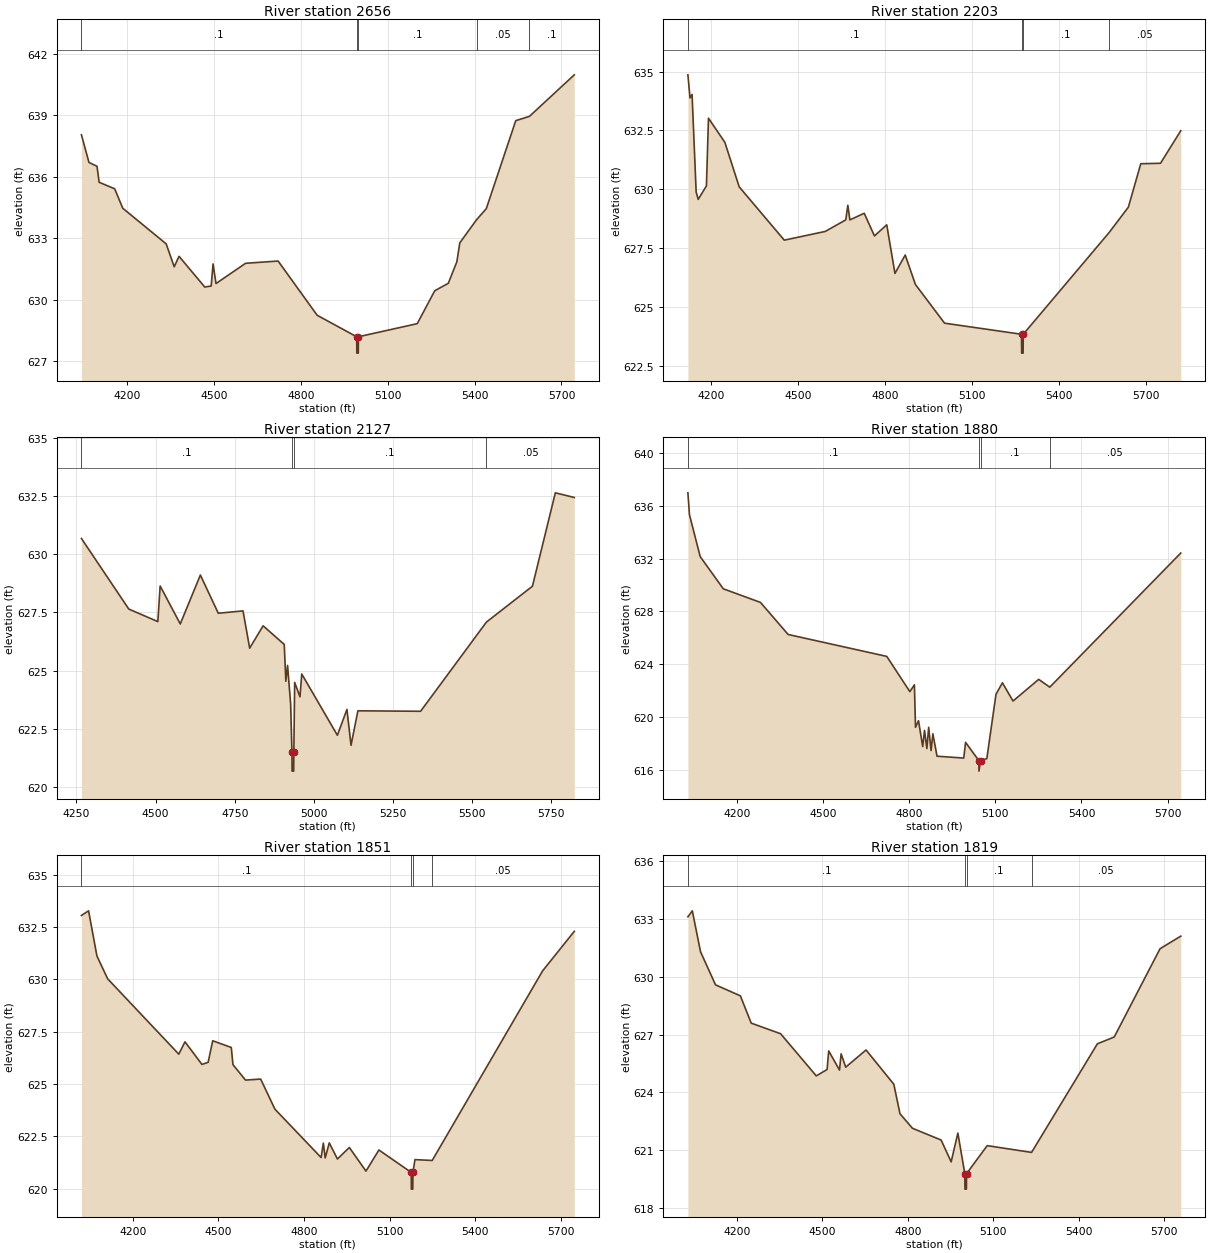
Type RM Length L Ch R = 1,2656,453,453,453
BEGIN DESCRIPTION:
UNT 064 in HW 1.0
END DESCRIPTION:
XS GIS Cut Line= 3
      1990119.35     13585833.80      1989244.35     13585385.88
      1988578.85     13585115.52
#Sta/Elev= 30
  4043.1  638.05  4069.1  636.70  4096.9  636.51  4104.2  635.73  4157.9  635.41
  4185.8  634.46  4335.6  632.72  4363.4  631.60  4380.0  632.11  4468.8  630.61
  4491.0  630.66  4497.4  631.74  4507.6  630.78  4609.7  631.77  4722.0  631.88
  4856.8  629.23  4993.2  628.18  4993.7  627.38  4998.7  627.38  4999.2  628.18
  5202.3  628.82  5262.8  630.43  5309.4  630.79  5338.9  631.84  5349.2  632.77
  5407.1  633.90  5440.6  634.44  5542.3  638.74  5589.5  638.95  5744.4  640.98
#Mann=5,-1,0
  4043.1     0.1       0  4993.2    0.07       0  4999.2     0.1       0
  5407.1    0.05       0  5589.5     0.1       0
Bank Sta=4993.2,4999.2
Exp/Cntr=0.3,0.1

Type RM Length L Ch R = 1,2203,76,76,76
BEGIN DESCRIPTION:
UNT 064 in HW 3.0
END DESCRIPTION:
XS GIS Cut Line= 3
      1990108.93     13585691.43      1989518.66     13585101.16
      1988775.60     13584656.71
#Sta/Elev= 30
  4119.9  634.86  4127.2  633.88  4134.3  634.03  4148.4  629.89  4155.5  629.58
  4183.8  630.15  4190.9  633.02  4247.4  632.00  4296.9  630.11  4452.5  627.85
  4593.9  628.22  4664.6  628.71  4671.7  629.33  4678.8  628.71  4728.3  628.99
  4763.6  628.03  4806.0  628.50  4834.3  626.44  4869.7  627.22  4905.0  625.97
  5005.5  624.33  5271.0  623.86  5271.5  623.06  5276.5  623.06  5277.0  623.86
  5573.1  628.17  5639.7  629.25  5682.5  631.09  5750.6  631.11  5820.5  632.49
#Mann=4,-1,0
  4119.9     0.1       0  5271.0    0.07       0  5277.0     0.1       0
  5573.1    0.05       0
Bank Sta=5271,5277
Exp/Cntr=0.3,0.1

Type RM Length L Ch R = 1,2127,247,247,247
BEGIN DESCRIPTION:
Mapping XS a9ed02ae
END DESCRIPTION:
XS GIS Cut Line= 4
      1990026.68     13585544.54      1989564.44     13585106.18
      1989495.00     13584967.29      1988833.11     13584585.35
#Sta/Elev= 30
  4265.8  630.67  4415.3  627.64  4507.1  627.10  4514.4  628.63  4577.9  627.00
  4641.4  629.10  4698.0  627.46  4776.1  627.56  4797.1  625.96  4839.6  626.92
  4906.3  626.12  4911.3  624.54  4916.8  625.22  4926.5  623.56  4930.6  621.48
  4931.1  620.68  4936.1  620.68  4936.6  621.48  4939.2  624.49  4956.0  623.87
  4961.6  624.85  5074.1  622.22  5104.3  623.33  5117.2  621.79  5138.9  623.27
  5336.9  623.25  5544.8  627.08  5690.1  628.62  5762.4  632.63  5822.3  632.43
#Mann=4,-1,0
  4265.8     0.1       0  4930.6    0.07       0  4936.6     0.1       0
  5544.8    0.05       0
Bank Sta=4930.6,4936.6
Exp/Cntr=0.3,0.1

Type RM Length L Ch R = 1,1880,29,29,29
BEGIN DESCRIPTION:
Mapping XS 424a26f1
END DESCRIPTION:
XS GIS Cut Line= 6
      1990103.43     13585603.57      1989706.27     13584913.43
      1989634.66     13584859.17      1989569.55     13584807.09
      1989502.28     13584783.22      1988914.19     13584451.20
#Sta/Elev= 30
  4029.5  636.98  4035.0  635.32  4072.3  632.15  4152.8  629.71  4282.2  628.68
  4378.5  626.25  4722.0  624.59  4802.4  621.92  4818.2  622.44  4822.0  619.22
  4832.5  619.72  4847.1  617.76  4853.4  618.99  4861.6  617.61  4867.9  619.22
  4876.2  617.46  4882.5  618.73  4897.0  617.03  4990.0  616.89  4996.4  618.08
  5042.5  616.70  5043.0  615.90  5048.5  616.70  5070.4  616.85  5102.3  621.72
  5124.7  622.59  5161.6  621.21  5251.0  622.85  5289.6  622.26  5745.7  632.42
#Mann=4,-1,0
  4029.5     0.1       0  5042.5    0.07       0  5048.5     0.1       0
  5289.6    0.05       0
Bank Sta=5042.5,5048.5
Exp/Cntr=0.3,0.1

Type RM Length L Ch R = 1,1851,32,32,32
BEGIN DESCRIPTION:
UNT 064 in HW 4.0
END DESCRIPTION:
XS GIS Cut Line= 4
      1990116.75     13585596.83      1989718.31     13584883.28
      1989632.38     13584810.36      1988939.84     13584417.23
#Sta/Elev= 30
  4020.6  633.06  4045.6  633.28  4074.9  631.12  4112.5  630.03  4361.6  626.43
  4383.3  627.02  4442.7  625.94  4464.4  626.04  4480.4  627.07  4545.5  626.75
  4551.3  625.93  4595.4  625.19  4648.3  625.24  4698.4  623.80  4860.1  621.49
  4867.9  622.18  4874.4  621.47  4888.7  622.19  4917.3  621.42  4959.0  621.97
  5017.2  620.84  5062.5  621.85  5175.7  620.78  5176.2  619.98  5181.2  619.98
  5181.7  620.78  5188.8  621.39  5249.2  621.35  5635.9  630.41  5746.9  632.30
#Mann=4,-1,0
  4020.6     0.1       0  5175.7    0.07       0  5181.7     0.1       0
  5249.2    0.05       0
Bank Sta=5175.7,5181.7
Exp/Cntr=0.3,0.1

Type RM Length L Ch R = 1,1819,78,78,78
BEGIN DESCRIPTION:
Mapping XS 390096da
END DESCRIPTION:
XS GIS Cut Line= 5
      1990127.27     13585583.98      1989734.48     13584865.68
      1989645.51     13584787.56      1989565.21     13584744.16
      1988955.37     13584394.75
#Sta/Elev= 30
  4027.7  633.09  4043.2  633.40  4072.1  631.28  4124.8  629.57  4212.1  629.00
  4250.0  627.59  4353.4  627.04  4478.6  624.86  4516.6  625.19  4522.3  626.15
  4560.2  625.16  4565.9  626.00  4582.0  625.31  4653.4  626.20  4750.9  624.43
  4772.7  622.90  4816.3  622.15  4917.2  621.54  4952.4  620.41  4975.9  621.90
  5000.4  619.80  5000.9  619.00  5005.9  619.00  5006.4  619.80  5079.1  621.25
  5234.8  620.90  5466.1  626.52  5525.1  626.87  5686.2  631.44  5758.9  632.09
#Mann=4,-1,0
  4027.7     0.1       0  5000.4    0.07       0  5006.4     0.1       0
  5234.8    0.05       0
Bank Sta=5000.4,5006.4
Exp/Cntr=0.3,0.1

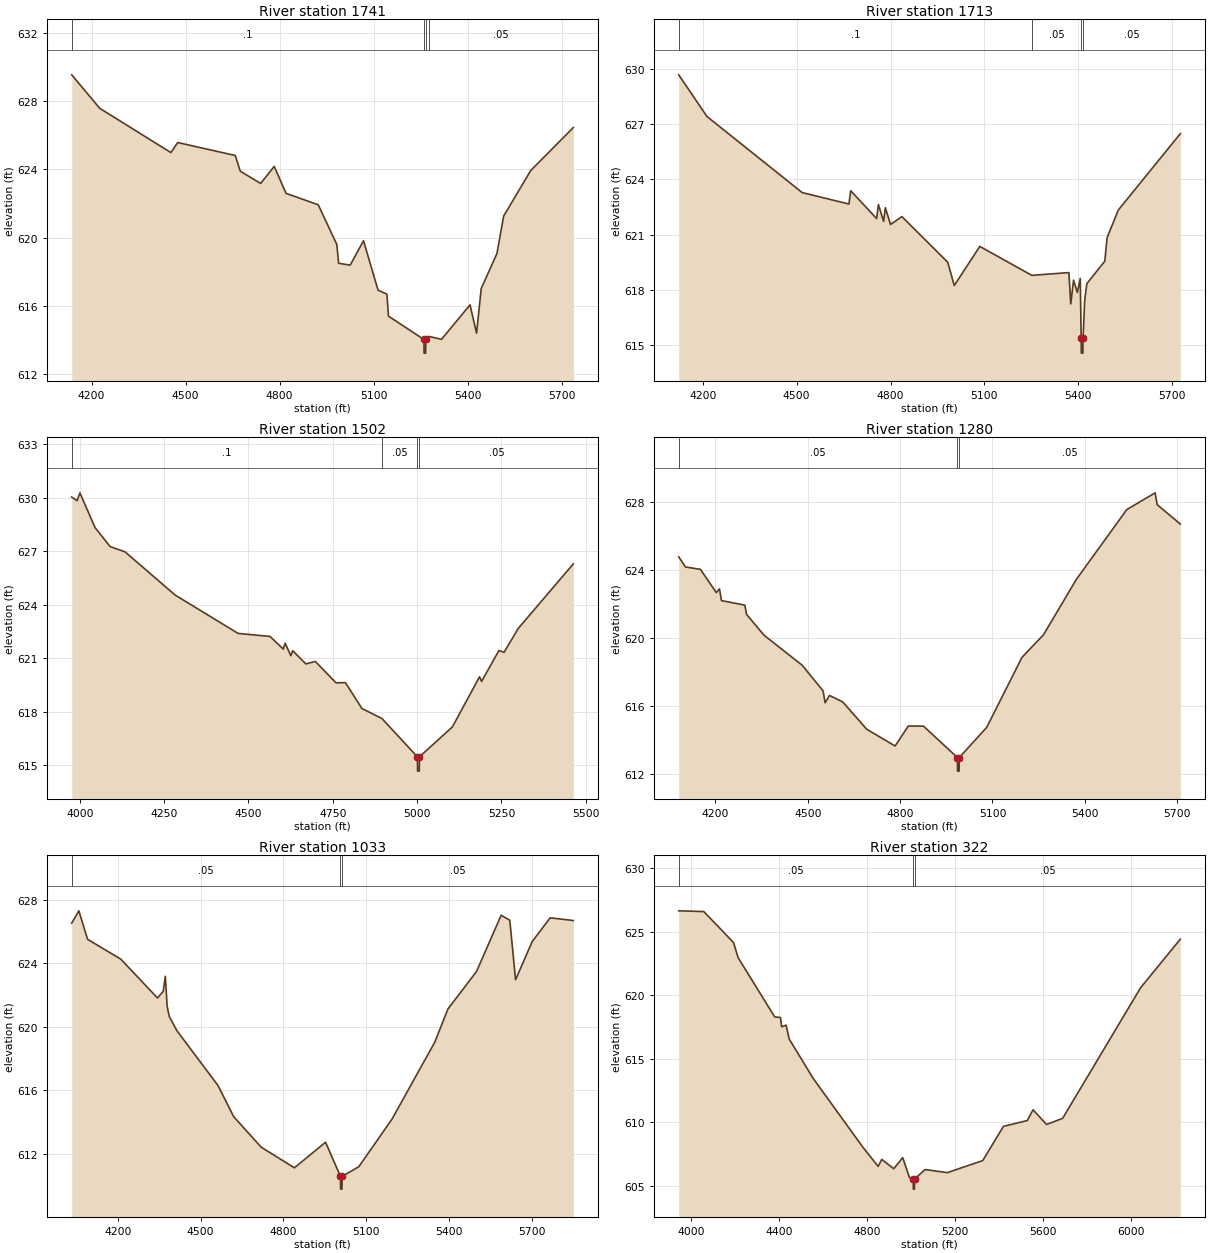
Type RM Length L Ch R = 1,1741,28,28,28
BEGIN DESCRIPTION:
Mapping XS cde470dd
END DESCRIPTION:
XS GIS Cut Line= 6
      1990094.82     13585475.52      1989667.74     13584713.38
      1989603.50     13584647.41      1989737.18     13584623.10
      1989695.52     13584522.41      1989475.05     13584204.72
#Sta/Elev= 30
  4136.8  629.54  4225.9  627.58  4453.1  624.98  4474.8  625.57  4658.5  624.81
  4674.5  623.89  4739.5  623.17  4782.9  624.17  4820.6  622.59  4923.3  621.92
  4982.6  619.59  4988.4  618.49  5025.3  618.38  5067.8  619.81  5114.2  616.91
  5142.4  616.68  5147.4  615.39  5260.5  614.02  5261.0  613.22  5266.0  613.22
  5266.5  614.02  5276.2  614.20  5316.7  614.03  5407.6  616.05  5428.5  614.39
  5443.4  617.01  5493.5  619.06  5515.0  621.26  5601.4  623.93  5737.3  626.45
#Mann=4,-1,0
  4136.8     0.1       0  5260.5    0.07       0  5266.5     0.1       0
  5276.2    0.05       0
Bank Sta=5260.5,5266.5
Exp/Cntr=0.3,0.1

Type RM Length L Ch R = 1,1713,211,211,211
BEGIN DESCRIPTION:
Mapping XS b828c631
END DESCRIPTION:
XS GIS Cut Line= 6
      1990112.20     13585468.61      1989737.18     13584742.89
      1989639.96     13584656.09      1989754.55     13584650.88
      1989757.15     13584606.61      1989508.14     13584178.45
#Sta/Elev= 30
  4123.1  629.67  4213.3  627.41  4517.7  623.28  4667.1  622.66  4672.8  623.38
  4755.7  621.87  4761.4  622.63  4777.9  621.72  4783.5  622.46  4800.0  621.55
  4836.3  621.98  4982.9  619.50  5003.8  618.24  5085.4  620.36  5251.6  618.79
  5370.1  618.94  5376.1  617.24  5385.0  618.53  5397.2  617.86  5406.4  618.62
  5409.4  615.37  5409.9  614.57  5414.9  614.57  5415.4  615.37  5420.7  617.45
  5427.5  618.34  5484.9  619.56  5492.2  620.83  5527.9  622.33  5726.3  626.48
#Mann=4,-1,0
  4123.1     0.1       0  5251.6    0.05       0  5409.4    0.07       0
  5415.4    0.05       0
Bank Sta=5409.4,5415.4
Exp/Cntr=0.3,0.1

Type RM Length L Ch R = 1,1502,222,222,222
BEGIN DESCRIPTION:
Mapping XS 52f05c23
END DESCRIPTION:
XS GIS Cut Line= 5
      1990132.17     13585479.05      1989764.96     13584747.23
      1989804.03     13584640.46      1989793.61     13584570.15
      1989530.59     13584163.91
#Sta/Elev= 30
  3975.9  630.04  3991.6  629.84  4000.1  630.28  4044.8  628.34  4089.5  627.27
  4134.1  626.97  4282.5  624.55  4469.2  622.40  4564.1  622.23  4603.2  621.52
  4608.8  621.85  4625.6  621.15  4631.2  621.43  4670.2  620.69  4698.2  620.83
  4759.6  619.63  4787.5  619.64  4836.4  618.19  4895.8  617.63  5001.0  615.48
  5001.5  614.68  5006.5  614.68  5007.0  615.48  5104.7  617.16  5185.3  619.97
  5191.3  619.71  5242.7  621.44  5257.9  621.34  5300.1  622.68  5463.4  626.30
#Mann=4,-1,0
  3975.9     0.1       0  4895.8    0.05       0  5001.0   0.035       0
  5007.0    0.05       0
Bank Sta=5001,5007
Exp/Cntr=0.3,0.1

Type RM Length L Ch R = 1,1280,247,247,247
BEGIN DESCRIPTION:
Mapping XS 1581d0b3
END DESCRIPTION:
XS GIS Cut Line= 3
      1990425.02     13585143.20      1990317.39     13584726.58
      1989404.91     13583949.40
#Sta/Elev= 30
  4081.2  624.77  4103.2  624.17  4151.6  624.03  4203.3  622.66  4213.6  622.88
  4220.0  622.19  4296.1  621.92  4301.3  621.38  4358.2  620.15  4482.1  618.38
  4550.0  616.87  4556.6  616.17  4570.8  616.60  4613.7  616.22  4691.6  614.61
  4783.9  613.62  4826.7  614.80  4876.1  614.79  4986.2  612.94  4986.7  612.14
  4991.7  612.14  4992.2  612.94  5081.4  614.72  5195.7  618.84  5265.9  620.18
  5372.5  623.44  5536.1  627.55  5628.3  628.54  5634.9  627.84  5710.1  626.70
#Mann=3,-1,0
  4081.2    0.05       0  4986.2   0.035       0  4992.2    0.05       0
Bank Sta=4986.2,4992.2
Exp/Cntr=0.3,0.1

Type RM Length L Ch R = 1,1033,711,711,711
BEGIN DESCRIPTION:
UNT 064 in HW 5.0
END DESCRIPTION:
XS GIS Cut Line= 4
      1990592.66     13585042.12      1990566.62     13584755.68
      1989919.92     13584017.83      1989394.78     13583857.25
#Sta/Elev= 30
  4032.7  626.52  4058.5  627.29  4090.1  625.50  4210.5  624.25  4343.4  621.81
  4364.2  622.23  4371.8  623.17  4378.5  621.29  4386.1  620.65  4414.3  619.74
  4562.6  616.31  4619.5  614.35  4719.2  612.43  4839.7  611.13  4952.6  612.74
  5006.6  610.59  5007.1  609.79  5012.1  609.79  5012.6  610.59  5073.1  611.20
  5193.7  614.20  5348.4  619.03  5396.1  621.12  5499.6  623.47  5588.9  627.01
  5620.3  626.70  5641.2  622.96  5701.6  625.36  5766.7  626.85  5850.6  626.68
#Mann=3,-1,0
  4032.7    0.05       0  5006.6   0.035       0  5012.6    0.05       0
Bank Sta=5006.6,5012.6
Exp/Cntr=0.3,0.1

Type RM Length L Ch R = 1,322,0,0,0
BEGIN DESCRIPTION:
UNT 064 in HW 6.0
END DESCRIPTION:
XS GIS Cut Line= 4
      1990913.85     13584924.98      1990761.93     13584378.07
      1990618.70     13583566.44      1989748.13     13583397.52
#Sta/Elev= 30
  3945.0  626.64  4059.1  626.58  4194.1  624.14  4214.8  622.95  4380.9  618.29
  4407.3  618.24  4412.5  617.51  4432.8  617.64  4446.7  616.55  4556.4  613.43
  4779.8  608.07  4850.8  606.52  4867.5  607.07  4921.7  606.34  4962.5  607.21
  4993.0  605.65  5010.3  605.53  5010.8  604.73  5015.8  604.73  5016.3  605.53
  5064.1  606.27  5165.6  606.03  5326.2  606.98  5420.0  609.67  5528.6  610.13
  5554.5  610.98  5615.6  609.82  5688.8  610.30  6043.4  620.59  6223.6  624.41
#Mann=3,-1,0
  3945.0    0.05       0  5010.3   0.035       0  5016.3    0.05       0
Bank Sta=5010.3,5016.3
Exp/Cntr=0.3,0.1

Chan Stop Cuts=-1