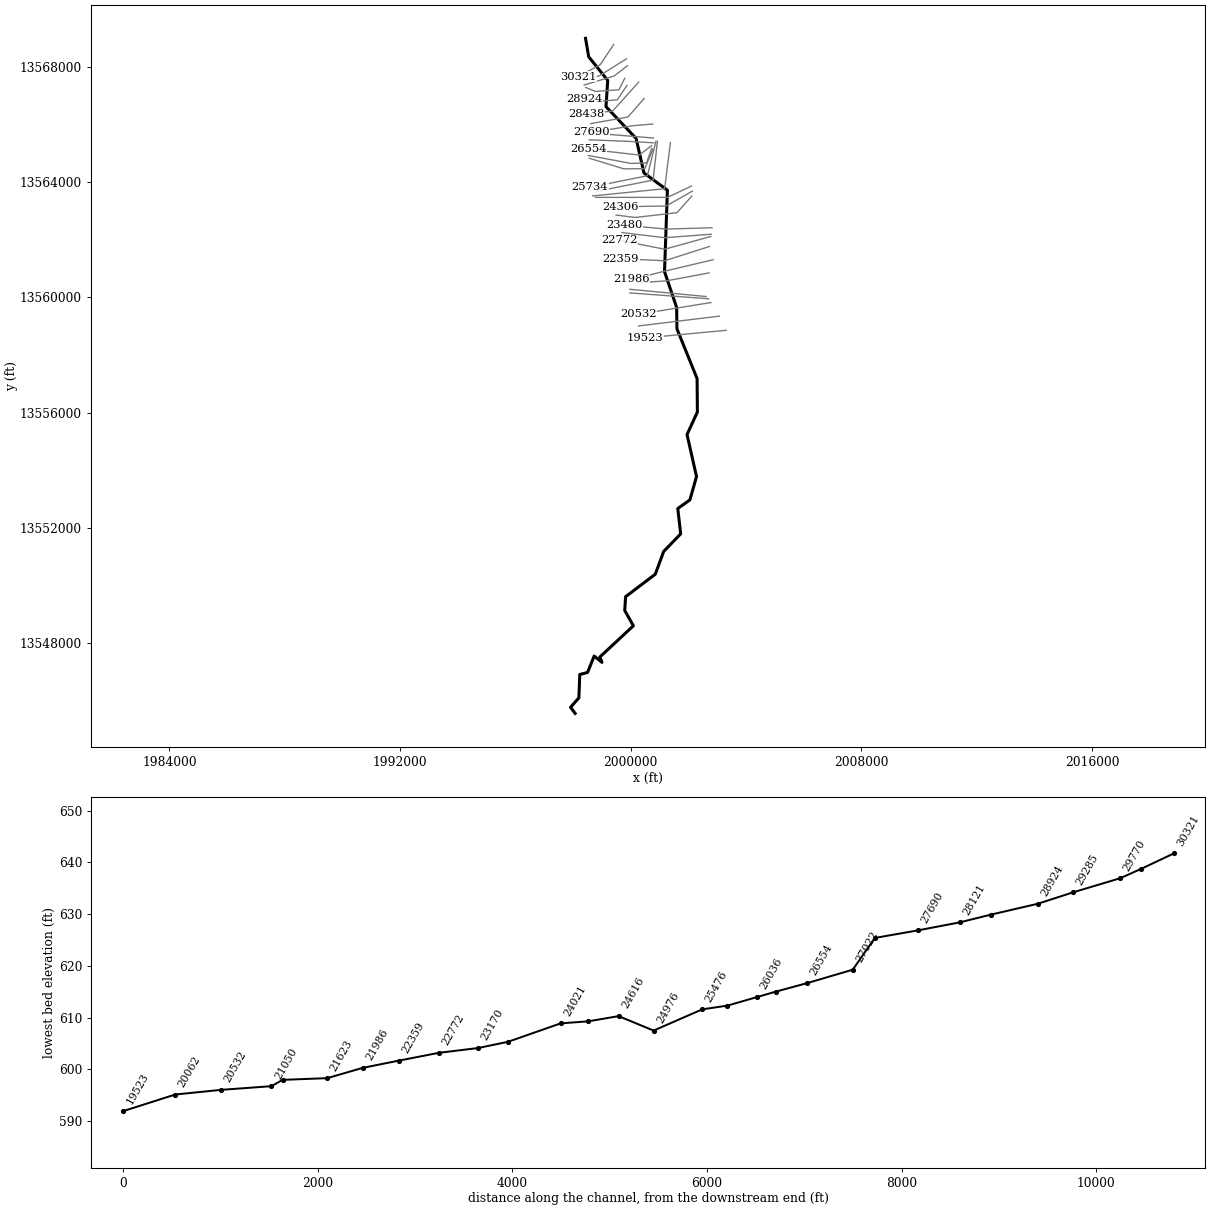
--- UNT 068 in HW.prj (project) ---

Proj Title=UNT 068 in HW Base Level Engineering
Current Plan=p01
Default Exp/Contr=0.3,0.1
English Units
Geom File=g01
Flow File=f01
Plan File=p01
Y Axis Title=Elevation
X Axis Title(PF)=Main Channel Distance
X Axis Title(XS)=Station
BEGIN DESCRIPTION:
UNT 068 in HW
END DESCRIPTION:
DSS Export Rating Curves= 0
DSS Export Rating Curve Sorted= 0
DSS Export Volume Flow Curves= 0
DXF OffsetX= 0
DXF OffsetY= 0
DXF ScaleX= 1
DXF ScaleY= 10

--- UNT 068 in HW.p01 (plan) ---

Plan Title=Multiple Run
Short Identifier=Multiple
Geom File=g01
Flow File=f01
Subcritical Flow
K Sum by GR= 0
Std Step Tol= 0.01
Critical Tol= 0.01
Num of Std Step Trials= 20
Max Error Tol= 0.3
Flow Tol Ratio= 0.001
Split Flow NTrial= 30
Split Flow Tol= 0.02
Split Flow Ratio= 0.02
Log Output Level= 0
Friction Slope Method= 1
Unsteady Friction Slope Method= 2
Unsteady Bridges Friction Slope Method= 1
Parabolic Critical Depth
Global Vel Dist=  1 , 1 , 1
Global Log Level= 0
CheckData=True
Encroach Param= -1, 0, 0, 0
BEGIN DESCRIPTION:
Multiple Run
END DESCRIPTION:

--- UNT 068 in HW.f01 (steady flow) ---

Flow Title=Multiple
Number of Profiles=7
Profile Names=10-year,25-year,50-year,1pct_min,100-year,1pct_plu,500-year
River Rch & RM= UNT 068 in HW,Reach-1,30321
     450     627     773     472     942    1879    1403
River Rch & RM= UNT 068 in HW,Reach-1,24976
     784    1128    1421     885    1766    3524    2743
River Rch & RM= UNT 068 in HW,Reach-1,23480
    1424    2113    2717    1725    3442    6867    5554
River Rch & RM= UNT 068 in HW,Reach-1,22359
    1613    2401    3093    1966    3923    7828    6347
River Rch & RM= UNT 068 in HW,Reach-1,18299
    1771    2636    3395    2156    4302    8584    6947
River Rch & RM= UNT 068 in HW,Reach-1,10548
    1918    2858    3685    2341    4671    9319    7548
Boundary for River Rch & Prof#=UNT 068 in HW,Reach-1,1
Up Type=0
Dn Type=3
Dn Slope=0.005
Boundary for River Rch & Prof#=UNT 068 in HW,Reach-1,2
Up Type=0
Dn Type=3
Dn Slope=0.005
Boundary for River Rch & Prof#=UNT 068 in HW,Reach-1,3
Up Type=0
Dn Type=3
Dn Slope=0.005
Boundary for River Rch & Prof#=UNT 068 in HW,Reach-1,4
Up Type=0
Dn Type=3
Dn Slope=0.005
Boundary for River Rch & Prof#=UNT 068 in HW,Reach-1,5
Up Type=0
Dn Type=3
Dn Slope=0.005
Boundary for River Rch & Prof#=UNT 068 in HW,Reach-1,6
Up Type=0
Dn Type=3
Dn Slope=0.005
Boundary for River Rch & Prof#=UNT 068 in HW,Reach-1,7
Up Type=0
Dn Type=3
Dn Slope=0.005

--- UNT 068 in HW.g01 (geometry) ---

Geom Title=Existing Conditions
Program Version=5.05

River Reach=UNT 068 in HW   ,Reach-1
Reach XY= 30
       1998430.8     13568994.93       1998540.8     13568354.54
       1999200.8     13567534.54       1999140.8     13566624.54
      2000183.72     13565521.94      2000458.89     13564319.68
       2001270.8      13563724.2       2001170.8     13560894.54
       2001590.8     13559654.54       2001600.8     13558914.54
       2002300.8     13557184.54       2002310.8     13556024.54
      2001951.64     13555241.15       2002280.8     13553784.54
       2002050.8     13552974.54       2001630.8     13552674.54
       2001730.8     13551794.54       2001140.8     13551184.54
       2000850.8     13550394.54       1999820.8     13549614.54
       1999790.8     13549134.54       2000090.8     13548604.54
       1998930.8     13547524.54       1999000.8     13547334.54
       1998730.8     13547554.54       1998500.8     13546984.54
       1998230.8     13546914.54       1998200.8     13546104.54
       1997910.8     13545774.54       1998070.8     13545564.54

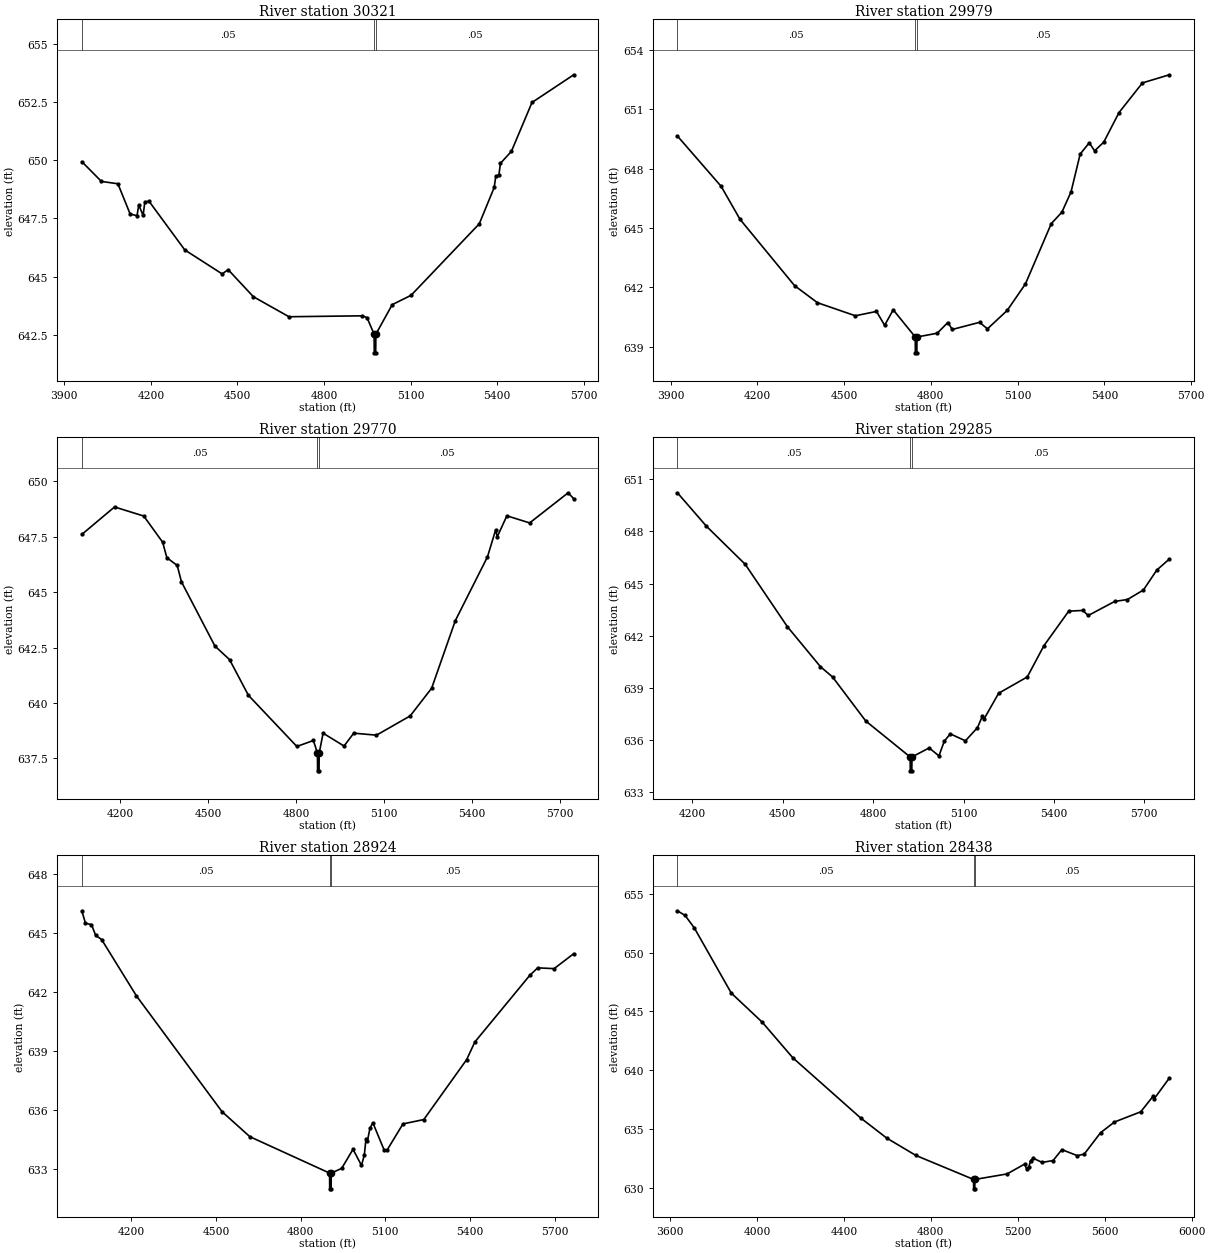
Type RM Length L Ch R = 1 ,30321   ,342,342,342
BEGIN DESCRIPTION:
UNT 068 in HW 38.0
END DESCRIPTION:
XS GIS Cut Line= 3
      1999408.94     13568784.47      1998943.66     13568083.09
      1998188.32      13567667.3
#Sta/Elev= 30
    3961  649.94  4028.9  649.09    4086  648.99  4128.4  647.69  4152.2  647.62
  4158.2  648.08  4173.3  647.63  4179.3  648.22  4194.3  648.23  4317.6  646.15
  4446.9  645.12    4468   645.3  4555.2  644.14  4678.5  643.28    4933  643.32
    4949  643.24  4973.5  642.53    4974  641.73    4979  641.73  4979.5  642.53
  5036.2   643.8  5101.5   644.2  5337.7  647.27  5389.4  648.83  5395.1  649.33
  5405.4  649.35  5411.2  649.87    5449  650.38  5520.3  652.48  5664.9  653.67
#Mann= 3 ,-1 , 0
    3961     .05       0  4973.5    .035       0  4979.5     .05       0
Bank Sta=4973.5,4979.5
XS Rating Curve= 0 ,0
Exp/Cntr=0.3,0.1

Type RM Length L Ch R = 1 ,29979   ,209,209,209
BEGIN DESCRIPTION:
UNT 068 in HW 37.0
END DESCRIPTION:
XS GIS Cut Line= 3
      1999853.42      13568284.5      1998915.88     13567701.14
      1998349.96      13567511.1
#Sta/Elev= 30
  3923.6  649.64  4074.9   647.1    4140  645.44  4328.8  642.09  4407.9  641.23
    4539  640.57  4612.1  640.79  4640.2  640.09    4670  640.87  4746.1   639.5
  4746.6   638.7  4751.6   638.7  4752.1   639.5  4822.3  639.69  4858.8  640.23
  4874.2  639.88  4968.6  640.24  4995.8  639.91  5064.2  640.84  5127.3  642.18
  5216.6  645.22  5253.4   645.8  5284.9  646.82  5316.5  648.73    5348   649.3
  5366.3  648.89    5398  649.33  5450.7  650.82  5531.9  652.32  5624.8  652.73
#Mann= 3 ,-1 , 0
  3923.6     .05       0  4746.1    .035       0  4752.1     .05       0
Bank Sta=4746.1,4752.1
XS Rating Curve= 0 ,0
Exp/Cntr=0.3,0.1

Type RM Length L Ch R = 1 ,29770   ,485,485,485
BEGIN DESCRIPTION:
UNT 068 in HW 36.0
END DESCRIPTION:
XS GIS Cut Line= 3
      1999888.12     13568048.38      1999422.83     13567687.25
      1998381.18     13567374.76
#Sta/Elev= 30
  4069.9  647.61  4181.4  648.85    4281  648.44  4345.3  647.26  4359.7  646.56
    4395  646.21  4409.5  645.47  4523.6  642.57  4573.4  641.96  4637.6  640.35
  4802.8  638.04  4859.2  638.31  4872.9  637.74  4873.4  636.94  4878.4  636.94
  4878.9  637.74  4892.2  638.64  4963.6  638.06  4996.6  638.64  5074.2  638.55
  5189.1  639.42  5262.2  640.67  5342.9  643.72  5452.5   646.6  5480.4  647.82
  5485.6   647.5  5518.6  648.45  5596.2  648.13  5727.5  649.49  5746.4  649.22
#Mann= 3 ,-1 , 0
  4069.9     .05       0  4872.9    .035       0  4878.9     .05       0
Bank Sta=4872.9,4878.9
XS Rating Curve= 0 ,0
Exp/Cntr=0.3,0.1

Type RM Length L Ch R = 1 ,29285   ,361,361,361
BEGIN DESCRIPTION:
Mapping XS 4de8ef7f
END DESCRIPTION:
XS GIS Cut Line= 4
      1999790.87     13567610.84      1999589.49     13567208.09
      1998770.05     13567152.53      1998436.74     13567291.41
#Sta/Elev= 30
  4150.1  650.23  4246.6   648.3  4375.1  646.11  4514.9  642.52  4624.9  640.21
    4665  639.62  4775.3  637.08  4922.6  635.01  4923.1  634.21  4928.1  634.21
  4928.6  635.01  4985.8  635.53  5018.2  635.07  5035.9  635.92  5055.9  636.34
    5106  635.94  5146.1   636.7  5162.3  637.36  5167.3  637.18  5216.3  638.68
  5311.4  639.62  5366.6  641.42  5448.9  643.41  5495.4  643.45  5513.8  643.16
  5601.5  643.97  5643.8  644.08  5696.9  644.63  5741.4  645.78  5782.8  646.41
#Mann= 3 ,-1 , 0
  4150.1     .05       0  4922.6    .035       0  4928.6     .05       0
Bank Sta=4922.6,4928.6
XS Rating Curve= 0 ,0
Exp/Cntr=0.3,0.1

Type RM Length L Ch R = 1 ,28924   ,486,486,486
BEGIN DESCRIPTION:
Mapping XS 4c58db49
END DESCRIPTION:
XS GIS Cut Line= 4
      1999867.25     13567360.83      1999533.94     13566860.86
      1998895.05     13566812.25      1998401.96     13566902.54
#Sta/Elev= 30
  4024.9  646.14  4037.9   645.5    4059  645.44    4074  644.89    4095  644.68
  4218.2  641.82  4521.7  635.93  4620.3  634.66  4902.7  632.81  4903.2  632.01
  4908.2  632.01  4908.7  632.81  4945.6  633.05  4985.8  634.02  5015.8   633.2
  5025.9  633.73  5031.7  634.56  5036.7  634.44  5045.9  635.09    5056  635.37
  5096.1  633.98  5106.1  633.97  5162.8  635.31  5236.5  635.53  5388.6  638.58
  5417.3  639.47  5612.2  642.86  5640.2  643.24  5698.4   643.2  5767.8  643.96
#Mann= 3 ,-1 , 0
  4024.9     .05       0  4902.7    .035       0  4908.7     .05       0
Bank Sta=4902.7,4908.7
XS Rating Curve= 0 ,0
Exp/Cntr=0.3,0.1

Type RM Length L Ch R = 1 ,28438   ,317,317,317
BEGIN DESCRIPTION:
UNT 068 in HW 35.0
END DESCRIPTION:
XS GIS Cut Line= 3
        2000275.       13567475.        1999375.       13566475.
      1998464.49     13566360.86
#Sta/Elev= 30
  3634.2  653.57  3669.7  653.17  3712.3   652.1    3882  646.56    4024  644.09
  4165.2  641.05  4476.9  635.93  4597.3  634.21  4731.8  632.73  4996.7  630.69
  4997.2  629.89  5002.2  629.89  5002.7  630.69  5150.9  631.16  5231.5     632
  5241.6  631.54  5251.7  631.79  5258.8   632.3  5271.8  632.49  5312.1  632.14
  5362.5   632.3  5402.9  633.23  5473.4  632.72  5505.4  632.84  5580.9  634.67
  5644.7  635.58  5765.7  636.45  5822.4  637.77  5827.5  637.56  5897.2  639.32
#Mann= 3 ,-1 , 0
  3634.2     .05       0  4996.7    .035       0  5002.7     .05       0
Bank Sta=4996.7,5002.7
XS Rating Curve= 0 ,0
Exp/Cntr=0.3,0.1

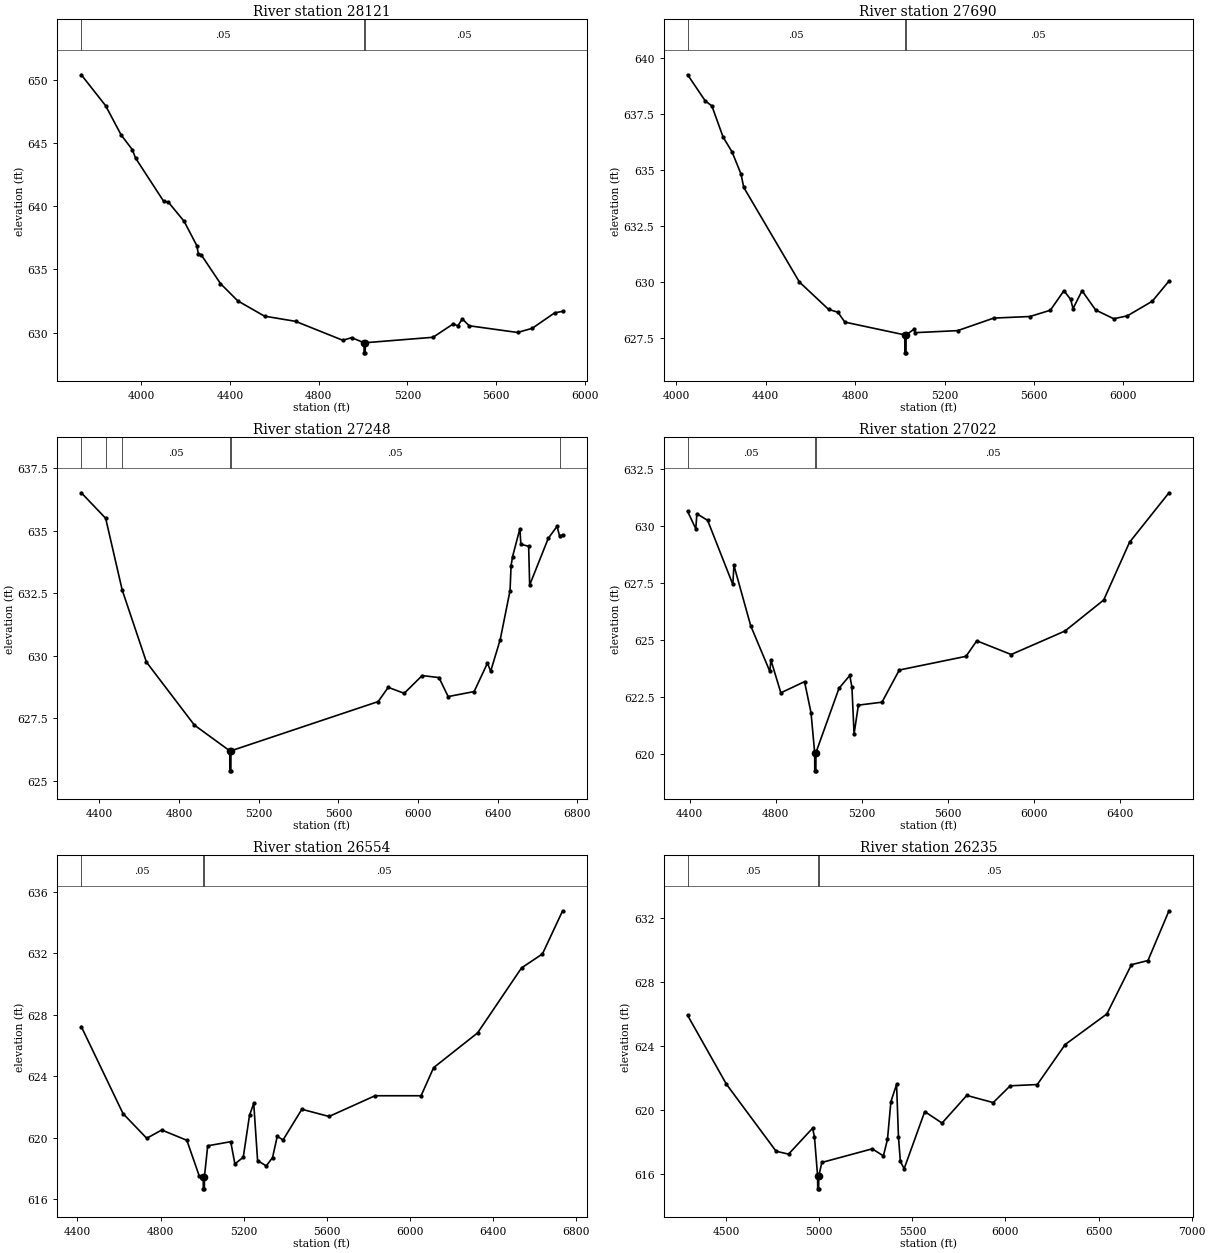
Type RM Length L Ch R = 1 ,28121   ,431,431,431
BEGIN DESCRIPTION:
UNT 068 in HW 34.0
END DESCRIPTION:
XS GIS Cut Line= 3
      2000464.48     13566909.46      1999901.99     13566263.64
       1998610.3     13566034.47
#Sta/Elev= 30
  3730.6  650.39    3840  647.95  3910.2  645.63  3960.6  644.47  3974.8  643.81
    4102  640.38  4122.9  640.32  4194.1   638.8  4251.1  636.88  4257.7  636.25
    4272  636.13  4357.4  633.89  4435.3  632.52  4555.9  631.31  4695.7   630.9
    4909   629.4  4947.9  629.61    5004  629.21  5004.5  628.41  5009.5  628.41
    5010  629.21  5315.2  629.64  5405.4  630.69  5426.9  630.55  5447.3  631.09
  5477.7  630.55  5695.8  630.02  5762.1  630.35  5862.9  631.57  5898.9  631.69
#Mann= 3 ,-1 , 0
  3730.6     .05       0    5004    .035       0    5010     .05       0
Bank Sta=5004,5010
XS Rating Curve= 0 ,0
Exp/Cntr=0.3,0.1

Type RM Length L Ch R = 1 ,27690   ,442,442,442
BEGIN DESCRIPTION:
UNT 068 in HW 33.0
END DESCRIPTION:
XS GIS Cut Line= 3
      2000763.12     13566020.59      2000096.44     13565965.03
      1998631.13     13565728.91
#Sta/Elev= 30
  4050.6  639.26    4129   638.1  4159.1  637.87  4209.3  636.48  4249.4  635.82
  4289.5  634.83  4301.5  634.24  4550.4  630.02  4680.9   628.8  4722.8  628.67
  4753.9  628.23  5021.9  627.66  5022.4  626.86  5027.4  626.86  5027.9  627.66
  5062.9  627.91    5068  627.76  5258.5  627.85  5419.9  628.41    5582  628.48
  5673.2  628.76  5733.9  629.63  5764.3  629.24  5774.5  628.83  5814.9  629.63
  5875.8  628.77  5956.8  628.38  6017.6  628.51    6129  629.16  6203.8  630.06
#Mann= 3 ,-1 , 0
  4050.6     .05       0  5021.9    .035       0  5027.9     .05       0
Bank Sta=5021.9,5027.9
XS Rating Curve= 0 ,0
Exp/Cntr=0.3,0.1

Type RM Length L Ch R = 1 ,27248   ,226,226,226
BEGIN DESCRIPTION:
Mapping XS 97473bf7
END DESCRIPTION:
XS GIS Cut Line= 3
      2000790.93     13565534.47      1998742.27     13565701.14
      1998389.02     13565624.95
#Sta/Elev= 30
  4308.8  636.52  4431.1   635.5  4514.2  632.63  4635.8  629.75  4876.6  627.23
  5054.2   626.2  5054.7   625.4  5059.7   625.4  5060.2   626.2  5799.6  628.17
  5849.8  628.74  5930.1   628.5  6020.4  629.21  6104.6  629.13  6150.8  628.37
  6281.2  628.57  6348.3  629.71  6364.2  629.38  6412.3  630.65  6461.6  632.61
  6466.7   633.6    6474  633.96  6510.9  635.08    6516  634.46    6555  634.38
  6560.1  632.83  6653.6   634.7  6697.8  635.18  6710.2  634.79  6725.6  634.84
#Mann= 6 ,-1 , 0
  4308.8     .05       0  4431.1     .08       0  4514.2     .05       0
  5054.2    .035       0  5060.2     .05       0  6710.2     .08       0
Bank Sta=5054.2,5060.2
XS Rating Curve= 0 ,0
Exp/Cntr=0.3,0.1

Type RM Length L Ch R = 1 ,27022   ,468,468,468
BEGIN DESCRIPTION:
UNT 068 in HW 32.0
END DESCRIPTION:
XS GIS Cut Line= 3
      2000797.81     13565367.81      1999832.55     13565423.36
      1998561.73     13565471.97
#Sta/Elev= 30
  4390.5  630.64  4428.5  629.88  4433.5  630.54  4483.5  630.25  4600.7  627.44
  4605.7  628.28  4683.8  625.63  4772.8  623.63  4777.8  624.13    4824  622.69
  4934.2  623.18  4964.3  621.82  4981.3  620.07  4981.8  619.27  4986.8  619.27
  4987.3  620.07  5094.5  622.89  5144.6  623.45  5154.6  622.94  5164.6  620.89
  5184.6  622.15  5294.3  622.28  5374.9  623.69  5685.1  624.29  5735.2  624.97
  5895.3  624.37  6145.5   625.4  6325.6  626.76  6445.7  629.29  6629.1  631.46
#Mann= 3 ,-1 , 0
  4390.5     .05       0  4981.3    .035       0  4987.3     .05       0
Bank Sta=4981.3,4987.3
XS Rating Curve= 0 ,0
Exp/Cntr=0.3,0.1

Type RM Length L Ch R = 1 ,26554   ,319,319,319
BEGIN DESCRIPTION:
Mapping XS 439278ff
END DESCRIPTION:
XS GIS Cut Line= 3
      2000721.43     13565270.58      2000297.83      13564944.2
      1998528.49     13565145.41
#Sta/Elev= 30
  4418.8  627.24  4619.5  621.58  4733.6  619.97  4805.6  620.51  4926.6  619.84
  4986.6   617.5  5005.3  617.48  5005.8  616.68  5010.8  616.68  5011.3  617.48
  5026.9  619.48  5137.6  619.75  5157.7   618.3    5198  618.74  5228.1  621.47
  5248.3  622.24  5266.9  618.52  5308.7  618.17  5338.9  618.72  5361.5   620.1
  5389.2  619.86  5479.8  621.86  5610.6  621.39    5832  622.74  6053.4  622.74
  6113.8  624.57  6325.2  626.83  6536.5  631.06  6637.2  631.97  6734.3  634.78
#Mann= 3 ,-1 , 0
  4418.8     .05       0  5005.3    .035       0  5011.3     .05       0
Bank Sta=5005.3,5011.3
XS Rating Curve= 0 ,0
Exp/Cntr=0.3,0.1

Type RM Length L Ch R = 1 ,26235   ,199,199,199
BEGIN DESCRIPTION:
Mapping XS fff6ec2e
END DESCRIPTION:
XS GIS Cut Line= 4
      2000728.39     13565180.34      2000547.83     13564673.36
       2000013.1     13564652.53      1998526.95     13564930.32
#Sta/Elev= 30
  4292.9  625.89  4501.2  621.59    4768   617.4    4835  617.22    4964  618.84
    4974   618.3    4991  615.85  4991.5  615.05  4996.5  615.05    4997  615.85
    5014   616.7  5284.2  617.55  5344.3  617.11  5366.2  618.14  5384.6   620.5
  5415.1  621.58  5425.3  618.28  5435.5  616.76  5455.8  616.31  5566.4  619.88
  5659.3  619.16  5792.2  620.89    5934  620.44  6025.5  621.49  6170.9  621.57
  6320.6  624.07  6544.4  625.98  6676.6  629.06  6765.3  629.32  6878.1  632.43
#Mann= 3 ,-1 , 0
  4292.9     .05       0    4991    .035       0    4997     .05       0
Bank Sta=4991,4997
XS Rating Curve= 0 ,0
Exp/Cntr=0.3,0.1

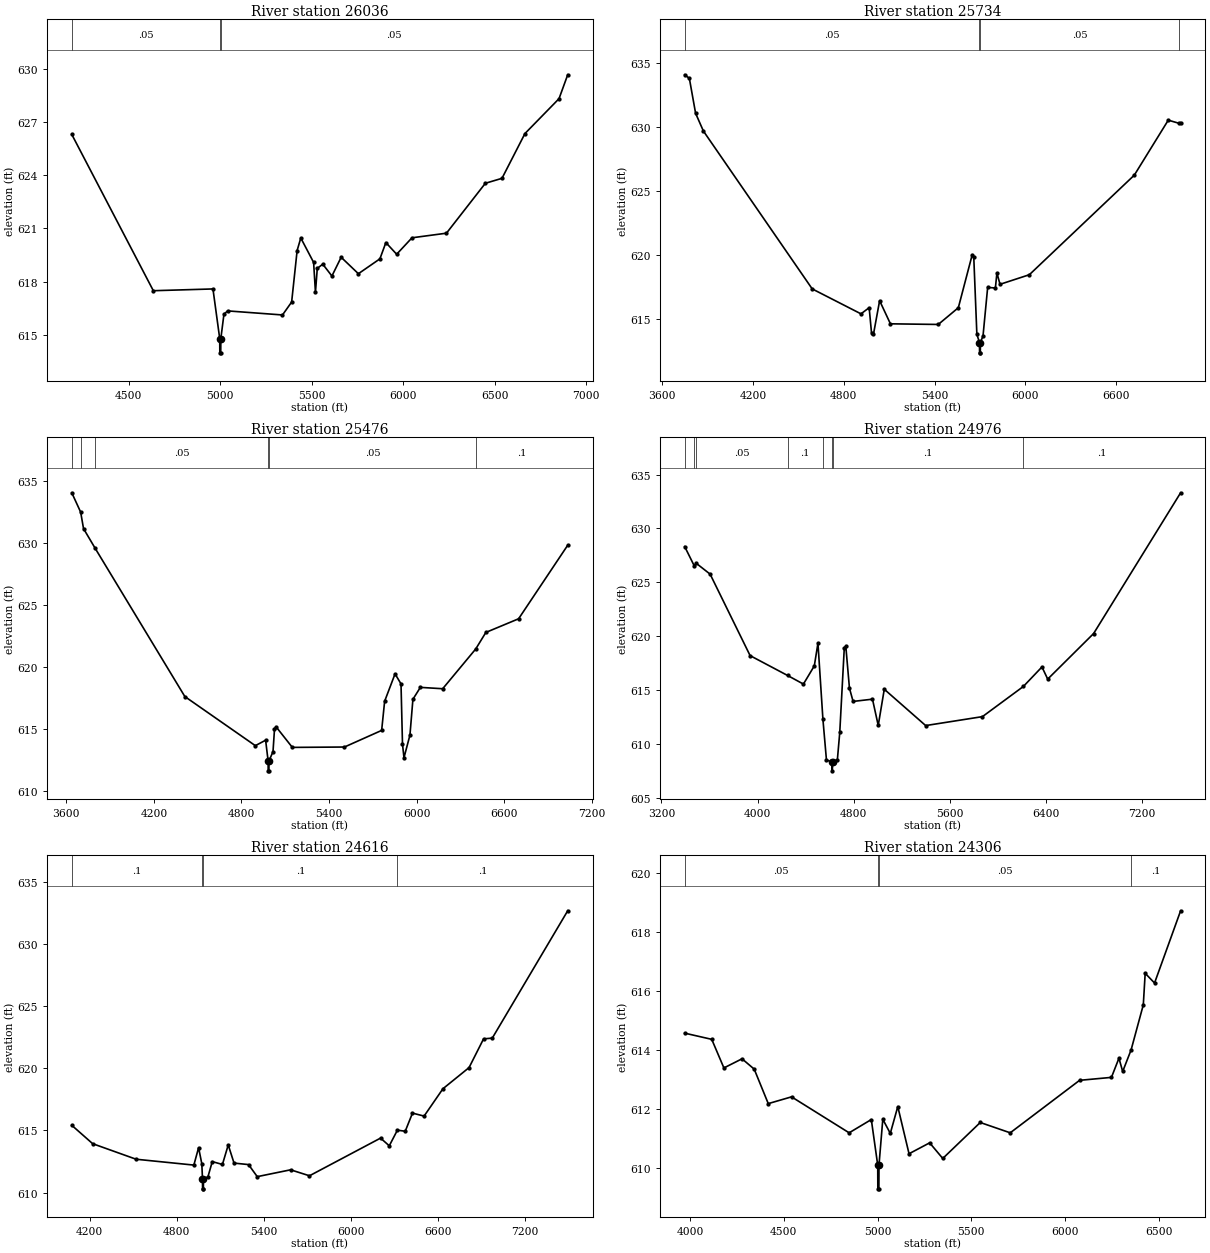
Type RM Length L Ch R = 1 ,26036   ,302,302,302
BEGIN DESCRIPTION:
Mapping XS 23dd4ad9
END DESCRIPTION:
XS GIS Cut Line= 4
      2000770.04     13565145.57      2000485.33     13564471.97
      1999756.16     13564465.03      1998561.68      13564833.1
#Sta/Elev= 30
  4188.6  626.31  4634.3  617.48  4960.2  617.58  4997.2  614.77  4997.7  613.97
  5002.7  613.97  5003.2  614.77  5020.2  616.15  5040.2  616.34  5340.2  616.11
  5390.2  616.84  5420.2  619.75  5440.2  620.46  5510.3  619.08  5520.3  617.39
  5530.3  618.74  5560.3  618.98  5610.3  618.31  5660.8  619.37    5755  618.44
  5872.5  619.28  5905.2   620.2  5964.2  619.54  6047.9  620.47  6236.3  620.73
  6448.9  623.55  6539.8  623.83  6665.3  626.36  6851.5  628.33    6899  629.68
#Mann= 3 ,-1 , 0
  4188.6     .05       0  4997.2    .035       0  5003.2     .05       0
Bank Sta=4997.2,5003.2
XS Rating Curve= 0 ,0
Exp/Cntr=0.3,0.1

Type RM Length L Ch R = 1 ,25734   ,258,258,258
BEGIN DESCRIPTION:
UNT 068 in HW 31.0
END DESCRIPTION:
XS GIS Cut Line= 3
      2000874.99     13565424.96        2000575.       13564225.
      1998574.99       13563825.
#Sta/Elev= 30
  3748.4  634.08  3779.3   633.8  3820.5  631.07    3872  629.68    4591  617.33
  4913.1  615.38  4967.2  615.86  4982.7   613.9  4995.5  613.77  5036.3  616.41
  5107.7   614.6  5423.8  614.55  5556.4  615.86  5648.2  620.01  5658.4   619.8
  5678.8  613.78  5696.1  613.13  5696.6  612.33  5701.6  612.33  5702.1  613.13
  5719.5  613.66  5750.1  617.45  5801.1   617.4  5811.3  618.58  5831.7  617.69
  6025.5  618.44    6719  626.23  6943.3  630.53  7012.9  630.29  7024.9  630.33
#Mann= 4 ,-1 , 0
  3748.4     .05       0  5696.1    .035       0  5702.1     .05       0
  7012.9      .1       0
Bank Sta=5696.1,5702.1
XS Rating Curve= 0 ,0
Exp/Cntr=0.3,0.1

Type RM Length L Ch R = 1 ,25476   ,500,500,500
BEGIN DESCRIPTION:
UNT 068 in HW 30.0
END DESCRIPTION:
XS GIS Cut Line= 3
        2000925.     13565424.96        2000775.       13564075.
      1998774.98       13563675.
#Sta/Elev= 30
  3637.8  634.03  3698.7  632.47  3718.3  631.14  3798.2  629.55  4412.5   617.6
  4895.5  613.64  4965.9  614.08    4983  612.41  4983.5  611.61  4988.5  611.61
    4989  612.41  5016.5  613.16  5026.7  614.96  5036.9  615.17    5149   613.5
    5506  613.53  5760.9  614.87  5781.3  617.22  5852.7  619.43  5893.5  618.62
  5903.7  613.76  5913.9  612.67  5954.7  614.49  5975.1  617.38  6026.1  618.34
    6179  618.23  6405.7  621.44  6474.8  622.77  6699.1  623.87  7035.7   629.8
#Mann= 6 ,-1 , 0
  3637.8     .05       0  3698.7      .1       0  3798.2     .05       0
    4983    .035       0    4989     .05       0  6405.7      .1       0
Bank Sta=4983,4989
XS Rating Curve= 0 ,0
Exp/Cntr=0.3,0.1

Type RM Length L Ch R = 1 ,24976   ,360,360,360
BEGIN DESCRIPTION:
UNT 068 in HW 29.0
END DESCRIPTION:
XS GIS Cut Line= 3
        2001375.     13565374.96        2001175.       13563775.
      1998674.98       13563525.
#Sta/Elev= 30
  3394.2  628.32  3472.5  626.56    3490  626.77  3605.8  625.76  3938.4   618.2
  4249.9  616.36  4381.8  615.56  4472.5  617.25  4502.7  619.36    4544  612.29
  4573.3  608.53  4620.7  608.31  4621.2  607.51  4626.7  608.31    4664  608.51
  4684.1  611.08  4721.9  618.95  4734.5  619.05  4764.7  615.18    4795  613.95
  4956.2  614.16  5004.1  611.72  5054.3  615.08  5398.6  611.71  5870.9  612.54
  6211.3  615.34  6365.9  617.15  6413.6  616.02  6795.5  620.25  7519.1  633.31
#Mann= 8 ,-1 , 0
  3394.2      .1       0  3472.5      .1       0    3490     .05       0
  4249.9      .1       0    4544      .1       0  4620.7     .05       0
  4626.7      .1       0  6211.3      .1       0
Bank Sta=4620.7,4626.7
XS Rating Curve= 0 ,0
Exp/Cntr=0.3,0.1

Type RM Length L Ch R = 1 ,24616   ,310,310,310
BEGIN DESCRIPTION:
UNT 068 in HW 28.0
END DESCRIPTION:
XS GIS Cut Line= 3
      2002105.15     13563867.82        2001275.       13563475.
        1998775.       13563475.
#Sta/Elev= 30
  4077.4  615.41  4221.4  613.93  4521.1  612.68  4918.9  612.21  4951.5  613.61
  4973.7  612.32  4978.4   611.1  4978.9   610.3  4984.5   610.3    4985   611.1
  5015.8  611.26  5045.8  612.49  5115.8  612.26  5155.8  613.83  5195.8  612.37
  5295.8  612.25  5355.8  611.28  5585.8  611.83  5715.8  611.35  6205.8  614.38
  6265.8  613.76  6321.9  615.02  6375.8  614.93  6425.8  616.39  6505.8  616.15
  6635.8  618.35  6815.8  620.05  6915.8  622.36  6975.8  622.42  7495.8  632.66
#Mann= 4 ,-1 , 0
  4077.4      .1       0  4978.4     .05       0    4985      .1       0
  6321.9      .1       0
Bank Sta=4978.4,4985
XS Rating Curve= 0 ,0
Exp/Cntr=0.3,0.1

Type RM Length L Ch R = 1 ,24306   ,285,285,285
BEGIN DESCRIPTION:
UNT 068 in HW 27.0
END DESCRIPTION:
XS GIS Cut Line= 3
      2002136.35     13563690.72        2001225.       13563175.
      1999625.96     13563149.06
#Sta/Elev= 30
    3971  614.58  4115.4  614.37  4180.3   613.4    4277  613.71    4342  613.36
    4417  612.19  4541.2  612.42  4848.6   611.2  4966.9  611.65  5001.2   610.1
  5001.7   609.3  5007.3   609.3  5007.8   610.1  5028.2  611.66  5068.2  611.18
  5108.2  612.09  5168.2  610.49  5278.2  610.86  5348.2  610.33  5548.2  611.55
  5708.2   611.2  6078.3  612.98  6248.3  613.08  6288.3  613.73  6308.3  613.28
  6353.1  614.01  6418.3  615.54  6428.3  616.61  6478.3  616.28  6617.4  618.73
#Mann= 4 ,-1 , 0
    3971     .05       0  5001.2    .035       0  5007.8     .05       0
  6353.1      .1       0
Bank Sta=5001.2,5007.8
XS Rating Curve= 0 ,0
Exp/Cntr=0.3,0.1

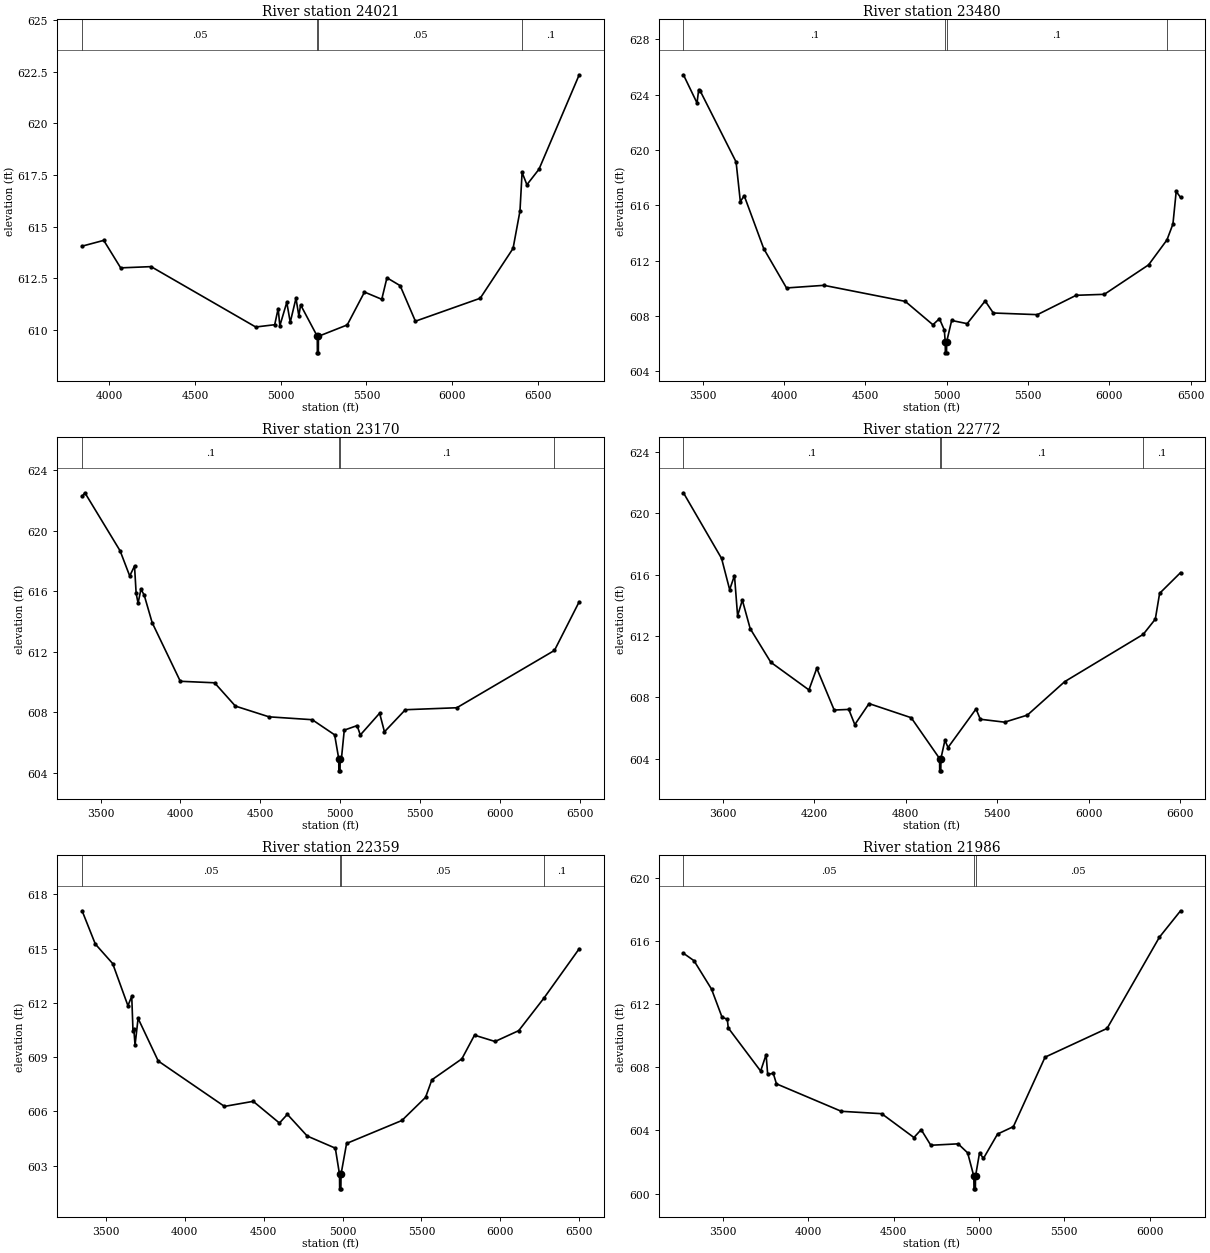
Type RM Length L Ch R = 1 ,24021   ,541,541,541
BEGIN DESCRIPTION:
Mapping XS 4fe5ebf4
END DESCRIPTION:
XS GIS Cut Line= 4
      2002117.26     13563520.57      2001603.38      13562944.2
      2000158.94     13562777.53      1999492.25     13562860.87
#Sta/Elev= 30
  3842.1  614.06  3968.3  614.34    4067  613.01  4244.2  613.07  4854.3  610.15
    4965  610.26  4985.1  611.04    4995  610.21  5035.4  611.34  5055.6  610.38
    5089  611.54  5105.9  610.68    5116  611.22  5213.3   609.7  5213.8   608.9
  5219.4   608.9  5219.9   609.7  5387.8  610.25  5488.4  611.84  5589.1  611.49
  5619.3  612.53  5696.3  612.15  5785.2  610.43    6163  611.54  6354.5  613.95
  6394.8  615.76  6407.2  617.63  6435.1  617.03  6505.6  617.78  6740.2  622.35
#Mann= 4 ,-1 , 0
  3842.1     .05       0  5213.3    .035       0  5219.9     .05       0
  6407.2      .1       0
Bank Sta=5213.3,5219.9
XS Rating Curve= 0 ,0
Exp/Cntr=0.3,0.1

Type RM Length L Ch R = 1 ,23480   ,310,310,310
BEGIN DESCRIPTION:
UNT 068 in HW 25.0
END DESCRIPTION:
XS GIS Cut Line= 3
      2002818.67     13562419.89        2001225.       13562375.
      1999768.28     13562508.28
#Sta/Elev= 30
  3381.4  625.44  3465.1   623.4  3475.1  624.36  3485.1  624.26  3705.2  619.14
  3731.4  616.27  3755.2   616.7  3875.3  612.87  4015.3  610.03  4245.4  610.22
  4745.6  609.06  4915.7  607.37  4955.7  607.81  4985.7  606.99  4991.4  606.14
  4992.2  605.34  4999.4  605.34  5000.2  606.14  5030.8  607.68  5126.3  607.45
  5236.8  609.09    5287  608.22  5558.1   608.1  5796.5   609.5  5969.8  609.57
  6241.9   611.7  6354.7   613.5  6391.6  614.65  6411.7  617.01  6438.5  616.57
#Mann= 4 ,-1 , 0
  3381.4      .1       0  4991.4     .05       0  5000.2      .1       0
  6354.7      .1       0
Bank Sta=4991.4,5000.2
XS Rating Curve= 0 ,0
Exp/Cntr=0.3,0.1

Type RM Length L Ch R = 1 ,23170   ,398,398,398
BEGIN DESCRIPTION:
UNT 068 in HW 24.0
END DESCRIPTION:
XS GIS Cut Line= 3
       2002792.6     13562195.93        2001175.       13562075.
       1999693.7     13562253.22
#Sta/Elev= 30
  3383.7  622.27  3401.3  622.51    3622  618.67  3682.1  617.01  3712.2  617.67
  3722.2  615.88  3734.4  615.21  3752.3  616.13  3772.4  615.76  3822.5  613.93
  3998.9  610.05  4213.6  609.95    4344  608.41  4554.6   607.7  4825.3  607.51
  4965.7  606.51  4991.4  604.93  4992.2  604.13  4999.4  604.13  5000.2  604.93
  5008.3  604.94    5026  606.82  5106.5  607.12  5126.5   606.5  5247.5  607.94
  5277.8  606.71  5408.7  608.17    5731   608.3  6342.8  612.09  6497.8  615.31
#Mann= 4 ,-1 , 0
  3383.7      .1       0  4991.4     .05       0  5000.2      .1       0
  6342.8      .1       0
Bank Sta=4991.4,5000.2
XS Rating Curve= 0 ,0
Exp/Cntr=0.3,0.1

Type RM Length L Ch R = 1 ,22772   ,413,413,413
BEGIN DESCRIPTION:
UNT 068 in HW 23.0
END DESCRIPTION:
XS GIS Cut Line= 3
      2002776.95     13562117.79        2001175.       13561675.
      1999610.32     13561982.39
#Sta/Elev= 30
    3344  621.33  3594.1  617.05  3646.9  615.02  3678.4  615.94  3698.8  613.32
  3729.9  614.34  3781.4  612.48  3916.6  610.29  4166.2  608.49  4217.5   609.9
  4331.6  607.18  4427.2  607.22  4466.7  606.23  4559.9   607.6    4836  606.68
    5022  604.02  5022.8  603.22    5030  603.22  5030.8  604.02    5057  605.21
  5077.4  604.74  5260.8  607.25  5288.8  606.58  5448.1  606.39  5597.1  606.85
  5841.7  609.03  6356.1  612.11  6435.2   613.1  6463.4  614.78  6600.6  616.13
#Mann= 4 ,-1 , 0
    3344      .1       0    5022     .05       0  5030.8      .1       0
  6356.1      .1       0
Bank Sta=5022,5030.8
XS Rating Curve= 0 ,0
Exp/Cntr=0.3,0.1

Type RM Length L Ch R = 1 ,22359   ,373,373,373
BEGIN DESCRIPTION:
UNT 068 in HW 22.0
END DESCRIPTION:
XS GIS Cut Line= 3
       2002724.9     13561768.84        2001175.       13561275.
      1999651.97     13561346.98
#Sta/Elev= 30
  3349.1  617.09    3433  615.25    3543  614.17  3639.7  611.84  3663.9  612.36
  3671.9  610.42  3677.1  610.54  3684.8  609.66  3704.1  611.14  3831.8  608.78
  4251.6  606.27  4433.8  606.55  4600.1  605.35  4650.4  605.83  4776.4  604.63
  4954.4  603.96    4981  602.51  4981.9  601.71  4989.6  601.71  4990.5  602.51
  5025.8  604.22  5376.2  605.49  5526.4  606.77  5566.4  607.74  5756.6   608.9
  5836.7  610.21  5966.9  609.86    6117  610.46  6276.8  612.26  6500.5  614.99
#Mann= 4 ,-1 , 0
  3349.1     .05       0    4981    .035       0  4990.5     .05       0
  6276.8      .1       0
Bank Sta=4981,4990.5
XS Rating Curve= 0 ,0
Exp/Cntr=0.3,0.1

Type RM Length L Ch R = 1 ,21986   ,363,363,363
BEGIN DESCRIPTION:
UNT 068 in HW 21.0
END DESCRIPTION:
XS GIS Cut Line= 3
      2002855.16     13561310.53        2001225.       13560925.
      2000024.96     13560624.99
#Sta/Elev= 30
    3269  615.22  3330.8  614.75  3433.6  612.95  3495.2  611.17  3526.1  611.04
  3531.6  610.49  3721.3  607.76  3753.3   608.8  3762.4  607.56  3795.5  607.61
  3813.8  606.95    4194  605.21  4430.3  605.06  4619.3  603.55  4661.6  604.05
  4718.1  603.06  4878.1  603.15  4933.9  602.58  4970.1   601.1  4971.1   600.3
  4979.1   600.3    4980   601.1  5003.4  602.57  5026.6  602.23  5109.1  603.77
  5201.8  604.24  5387.4  608.64  5750.7  610.46  6057.4  616.24  6181.1  617.91
#Mann= 3 ,-1 , 0
    3269     .05       0  4970.1    .035       0    4980     .05       0
Bank Sta=4970.1,4980
XS Rating Curve= 0 ,0
Exp/Cntr=0.3,0.1

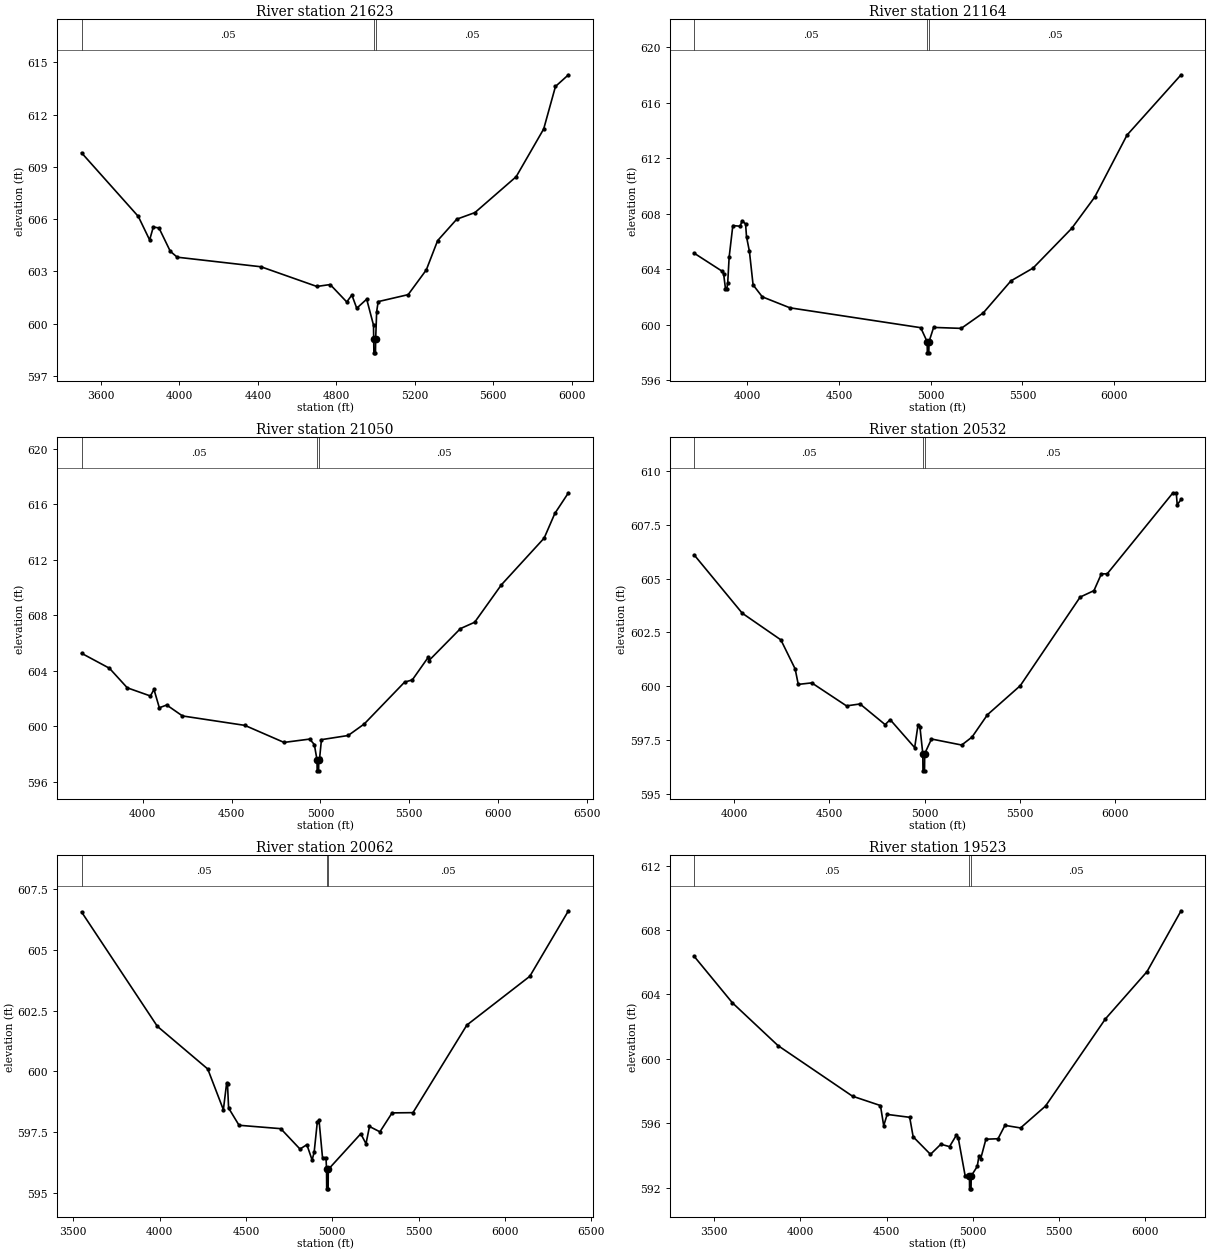
Type RM Length L Ch R = 1 ,21623   ,459,459,459
BEGIN DESCRIPTION:
UNT 068 in HW 20.0
END DESCRIPTION:
XS GIS Cut Line= 3
      2002714.54     13560853.06        2001225.       13560575.
      2000258.96     13560514.58
#Sta/Elev= 30
  3500.8   609.8  3790.1  606.15  3847.9   604.8  3866.6  605.54  3895.5  605.49
  3953.2  604.15  3988.6  603.81  4415.9  603.26  4700.7  602.13  4768.8  602.24
  4853.3  601.24  4879.3  601.64  4904.2  600.88    4955   601.4  4989.7  599.91
  4990.7  599.12  4991.7  598.32  4999.7  598.32  5000.7  599.12  5005.9  600.69
  5013.5  601.26  5166.4  601.66    5259  603.08  5316.7  604.76  5414.2  605.99
    5507  606.37  5717.4  608.43  5857.7  611.17  5917.8  613.61    5984  614.28
#Mann= 3 ,-1 , 0
  3500.8     .05       0  4990.7    .035       0  5000.7     .05       0
Bank Sta=4990.7,5000.7
XS Rating Curve= 0 ,0
Exp/Cntr=0.3,0.1

Type RM Length L Ch R = 1 ,21164   ,114,114,114
BEGIN DESCRIPTION:
Mapping XS feb3f65e
END DESCRIPTION:
XS GIS Cut Line= 3
      2002614.71     13560032.73      2001577.34     13560132.56
      1999971.47     13560284.47
#Sta/Elev= 30
  3710.2  605.16  3860.6  603.88  3870.6  603.69  3880.7  602.61  3888.1   602.6
  3893.1  603.04  3900.8  604.87  3920.9  607.15  3961.1   607.1  3971.1   607.5
  3990.5  607.27  3995.5  606.35  4011.3   605.3  4031.4  602.88  4081.6  602.02
  4232.3  601.23  4945.6   599.8  4980.7  598.79  4981.7  597.99  4989.8  597.99
  4990.8  598.79  5015.9  599.82  5166.5  599.75  5287.1  600.87  5437.7  603.17
  5558.3  604.09  5769.2  606.95    5894  609.19  6070.6  613.66  6365.4     618
#Mann= 3 ,-1 , 0
  3710.2     .05       0  4980.7    .035       0  4990.8     .05       0
Bank Sta=4980.7,4990.8
XS Rating Curve= 0 ,0
Exp/Cntr=0.3,0.1

Type RM Length L Ch R = 1 ,21050   ,518,518,518
BEGIN DESCRIPTION:
UNT 068 in HW 19.0
END DESCRIPTION:
XS GIS Cut Line= 2
      2002701.47     13559954.61      1999968.57      13560158.5
#Sta/Elev= 30
  3655.6  605.25  3812.5  604.17  3912.8  602.76  4043.1  602.17  4063.2  602.64
  4093.3  601.32  4134.8  601.52  4223.6  600.73  4574.6  600.05  4795.2  598.82
  4939.2  599.06  4965.7  598.67  4980.7  597.57  4981.7  596.77  4989.8  596.77
  4990.8  597.57  4995.8  597.73  5005.8  599.02  5156.2  599.32  5246.5  600.15
  5473.8  603.17  5517.2  603.33  5606.1  604.95  5611.2  604.73    5788  607.03
  5868.2  607.49  6018.6  610.19  6259.3  613.56  6319.5  615.34  6396.1  616.83
#Mann= 3 ,-1 , 0
  3655.6     .05       0  4980.7    .035       0  4990.8     .05       0
Bank Sta=4980.7,4990.8
XS Rating Curve= 0 ,0
Exp/Cntr=0.3,0.1

Type RM Length L Ch R = 1 ,20532   ,470,470,470
BEGIN DESCRIPTION:
UNT 068 in HW 18.0
END DESCRIPTION:
XS GIS Cut Line= 2
      2002783.98     13559824.41      2000262.27     13559416.42
#Sta/Elev= 30
  3791.3   606.1  4043.5  603.39  4246.1  602.15    4321   600.8  4337.3  600.08
  4408.2  600.15  4590.5  599.08  4661.5  599.17  4793.1  598.21  4819.6  598.44
  4948.1  597.14  4965.4  598.18  4975.5  598.12  4990.7  596.86  4991.7  596.06
  4999.8  596.06  5000.8  596.86  5036.3  597.54  5194.8  597.26    5249  597.63
    5330  598.67  5502.2  600.02  5816.3  604.14  5888.7  604.44  5927.7  605.22
  5958.1  605.22  6302.5  608.98  6320.6  608.99  6325.6  608.43  6345.8  608.68
#Mann= 3 ,-1 , 0
  3791.3     .05       0  4990.7    .035       0  5000.8     .05       0
Bank Sta=4990.7,5000.8
XS Rating Curve= 0 ,0
Exp/Cntr=0.3,0.1

Type RM Length L Ch R = 1 ,20062   ,539,539,539
BEGIN DESCRIPTION:
Mapping XS a928b5b4
END DESCRIPTION:
XS GIS Cut Line= 2
       2003070.4     13559351.31      2000270.89     13559012.77
#Sta/Elev= 30
  3547.5  606.57  3986.1  601.86  4278.2   600.1  4368.8  598.42  4387.7  599.52
  4392.7  599.47  4399.1  598.49  4459.5  597.78  4701.2  597.64  4812.5   596.8
  4852.3  596.98  4882.6  596.35  4894.4  596.66  4912.8  597.91  4922.8  597.99
    4943  596.44  4963.1  596.45  4966.3  595.96  4967.2  595.16  4975.4  595.16
  4976.4  595.96  5164.6  597.43  5194.8  597.02    5215  597.73  5275.4  597.51
  5345.9  598.29  5466.8   598.3    5779  601.91  6143.6  603.92  6367.4  606.62
#Mann= 3 ,-1 , 0
  3547.5     .05       0  4966.3    .035       0  4976.4     .05       0
Bank Sta=4966.3,4976.4
XS Rating Curve= 0 ,0
Exp/Cntr=0.3,0.1

Type RM Length L Ch R = 1 ,19523   ,516,516,516
BEGIN DESCRIPTION:
Mapping XS 940346c7
END DESCRIPTION:
XS GIS Cut Line= 2
      2003309.09     13558860.86      2000498.31     13558596.27
#Sta/Elev= 30
  3384.6  606.36  3605.9  603.48  3870.8  600.82  4302.7  597.68  4464.6   597.1
  4483.5  595.85  4503.6  596.55  4634.2  596.37  4654.3  595.16  4754.7  594.07
    4815   594.7  4865.2  594.55  4905.4  595.27  4915.4  595.11  4955.6  592.75
  4980.6  592.73  4981.5  591.93  4989.9  591.93  4990.9  592.73  5025.9  593.32
    5036  593.98    5046   593.8  5076.1  595.01  5146.4  595.04  5186.6  595.87
    5277  595.71  5421.9  597.07  5769.2  602.48  6010.2  605.41  6207.8  609.19
#Mann= 3 ,-1 , 0
  3384.6     .05       0  4980.6    .035       0  4990.9     .05       0
Bank Sta=4980.6,4990.9
XS Rating Curve= 0 ,0
Exp/Cntr=0.3,0.1