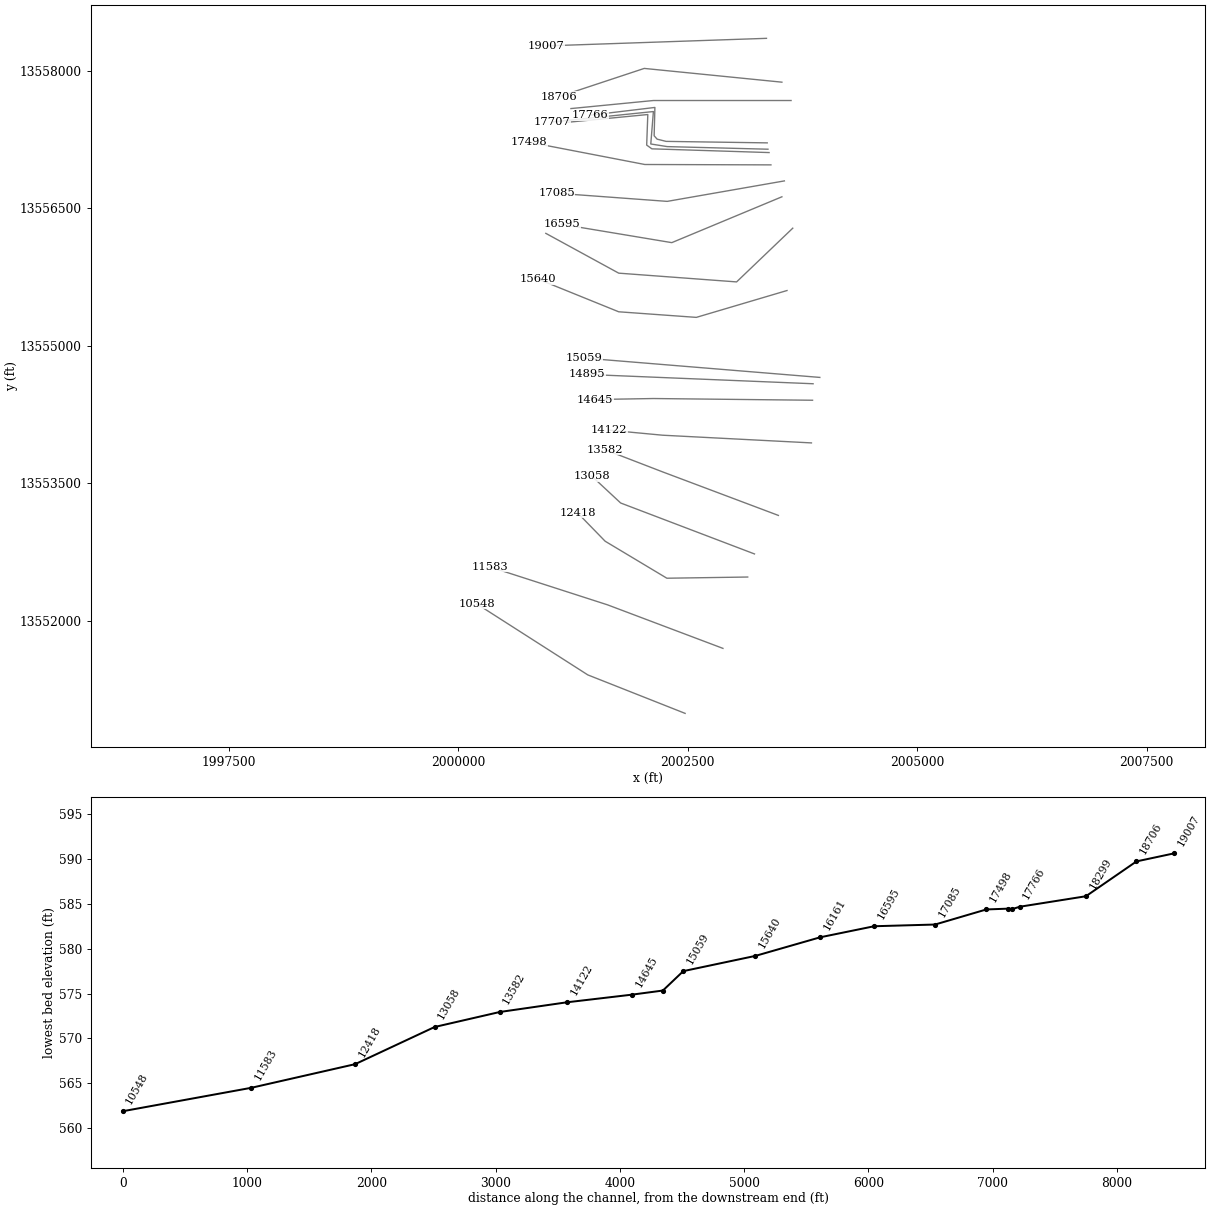
HEC-RAS study UNT 068 in HW.prj: UNT 068 in HW Base Level Engineering

--- UNT 068 in HW.g01 (geometry) --- (continued)

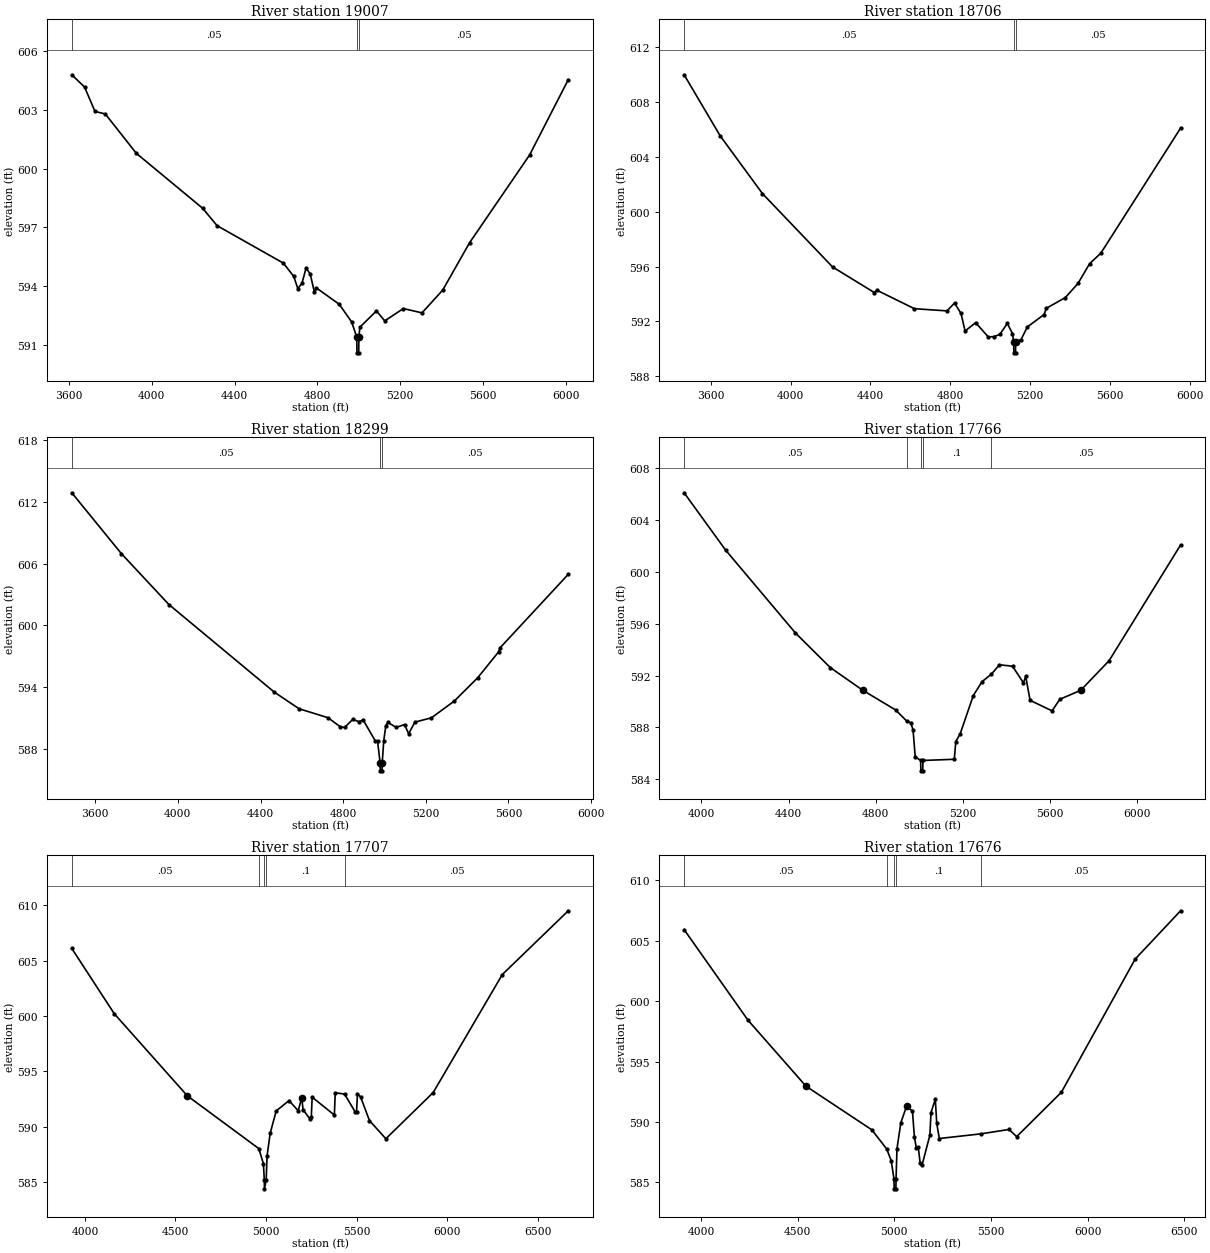
Type RM Length L Ch R = 1 ,19007   ,301,301,301
BEGIN DESCRIPTION:
Mapping XS 67b59cc4
END DESCRIPTION:
XS GIS Cut Line= 2
      2003356.88     13558353.05       2000958.3     13558270.64
#Sta/Elev= 30
  3613.1  604.79    3675  604.16    3725  602.92  3775.1  602.79  3925.2  600.78
  4245.4  597.98  4315.4  597.09  4635.6  595.18  4685.6  594.51  4705.6  593.88
  4725.6  594.14  4745.6  594.93  4765.7  594.62  4785.7   593.7  4795.7  593.91
  4905.7  593.08  4965.8  592.18  4990.6   591.4  4991.5   590.6    5000   590.6
  5000.9   591.4  5005.8  591.91  5085.8  592.74  5125.9  592.23  5215.9  592.86
    5306  592.64    5406   593.8  5536.1  596.22  5826.3   600.7  6013.1  604.54
#Mann= 3 ,-1 , 0
  3613.1     .05       0  4990.6    .035       0  5000.9     .05       0
Bank Sta=4990.6,5000.9
XS Rating Curve= 0 ,0
Exp/Cntr=0.3,0.1

Type RM Length L Ch R = 1 ,18706   ,407,407,407
BEGIN DESCRIPTION:
UNT 068 in HW 12.0
END DESCRIPTION:
XS GIS Cut Line= 3
      2003525.02       13557875.        2002025.       13558025.
      2001095.84     13557717.26
#Sta/Elev= 30
    3467  609.99  3647.9  605.53    3859  601.33  4210.7  595.97  4419.2  594.11
  4431.8  594.28  4620.2  592.93  4783.6  592.77  4821.2  593.34  4853.9  592.58
    4874   591.3  4926.8  591.91  4990.4  590.87  5016.6  590.89  5048.2  591.05
  5085.5  591.86  5111.5  591.11  5117.3  590.51  5118.2  589.71  5126.7  589.71
  5127.6  590.51  5154.1  590.67  5185.8   591.6  5269.5   592.5    5281  592.96
  5376.1  593.74  5439.5  594.77  5497.6  596.21  5553.9  596.98  5953.3   606.1
#Mann= 3 ,-1 , 0
    3467     .05       0  5117.3    .035       0  5127.6     .05       0
Bank Sta=5117.3,5127.6
XS Rating Curve= 0 ,0
Exp/Cntr=0.3,0.1

Type RM Length L Ch R = 1 ,18299   ,533,533,533
BEGIN DESCRIPTION:
UNT 068 in HW 11.0
END DESCRIPTION:
XS GIS Cut Line= 3
      2003624.98       13557675.        2002125.       13557675.
      2001226.06     13557587.15
#Sta/Elev= 30
  3486.6  612.88  3726.6  606.96  3956.6  602.01  4466.6  593.49  4586.6  591.87
  4726.6     591  4786.6  590.11  4806.6  590.05  4846.6  590.83  4876.6  590.61
  4896.6  590.79  4956.6  588.71  4966.6  588.71  4978.9  586.63  4979.7  585.83
  4988.4  585.83  4989.3  586.63  4996.6  588.76  5006.7  590.24  5016.7  590.54
  5056.9  590.06  5097.1  590.33  5117.2  589.44  5147.3  590.57  5227.7  590.99
  5338.2  592.62  5451.5  594.89  5553.2  597.42  5559.3  597.79  5889.8  604.95
#Mann= 3 ,-1 , 0
  3486.6     .05       0  4978.9    .035       0  4989.3     .05       0
Bank Sta=4978.9,4989.3
XS Rating Curve= 0 ,0
Exp/Cntr=0.3,0.1

Type RM Length L Ch R = 1 ,17766   ,59,59,59
BEGIN DESCRIPTION:
Mapping XS b3653a37
END DESCRIPTION:
XS GIS Cut Line= 6
        2003365.     13557213.04      2002262.95      13557229.3
      2002165.36      13557253.7      2002132.83      13557290.3
      2002140.96     13557599.35      2001429.65     13557513.99
#Sta/Elev= 30
    3921  606.08    4111  601.67  4431.1  595.29  4591.1  592.62 4740.53590.8657
  4891.1  589.35  4941.1  588.51  4961.1  588.35  4971.1  587.81  4981.1  585.74
  5005.9  585.46  5006.8  584.66  5015.5  584.66  5016.4  585.46  5160.4  585.55
  5167.1  586.91  5187.4  587.52  5247.5  590.46  5287.5  591.53    5330   592.1
  5367.5  592.83  5427.5  592.72  5477.2  591.44  5487.9  591.93    5508  590.09
  5608.8  589.28  5644.1  590.17 5740.39590.8657  5870.6  593.15  6198.3  602.06
#Mann= 5 ,-1 , 0
    3921     .05       0  4941.1      .1       0  5005.9     .07       0
  5016.4      .1       0    5330     .05       0
Bank Sta=4740.53,5740.39
XS Rating Curve= 0 ,0
Exp/Cntr=0.3,0.1

Type RM Length L Ch R = 1 ,17707   ,31,31,31
BEGIN DESCRIPTION:
UNT 068 in HW 10.0
END DESCRIPTION:
XS GIS Cut Line= 5
      2003373.14     13557143.91      2002275.15     13557172.37
      2002096.23     13557200.84       2002124.7     13557554.62
      2001022.71     13557440.76
#Sta/Elev= 30
  3927.3  606.09  4161.5  600.21  4565.7  592.79  4960.4  588.03  4985.8  586.66
  4990.5   585.2  4991.4   584.4    5001   585.2  5005.8  587.37  5023.2  589.42
  5056.2  591.43  5127.1  592.36  5177.7  591.45  5197.2   592.6  5204.9  591.53
  5241.1  590.74    5250  590.84    5255  592.67  5377.5  591.06  5382.5  593.07
  5434.2  592.95  5491.9  591.35  5500.1  591.33  5505.1  592.96    5522  592.71
  5571.5  590.56    5662  588.92  5923.4  593.09  6305.4  603.74  6669.6  609.49
#Mann= 5 ,-1 , 0
  3927.3     .05       0  4960.4      .1       0  4990.5     .07       0
    5001      .1       0  5434.2     .05       0
Bank Sta=4565.7,5197.2
XS Rating Curve= 0 ,0
Exp/Cntr=0.3,0.1

Type RM Length L Ch R = 1 ,17676   ,178,178,178
BEGIN DESCRIPTION:
Mapping XS c14eb1cb
END DESCRIPTION:
XS GIS Cut Line= 5
      2003385.34     13557107.31      2002108.43     13557147.97
       2002051.5     13557188.64       2002063.7     13557522.08
      2001181.31     13557436.69
#Sta/Elev= 30
  3913.1  605.93  4243.6  598.42  4543.8  592.95  4883.9  589.34    4961  587.75
    4984  586.79  4998.7  585.25  4999.6  584.45  5008.3  584.45  5009.2  585.25
    5014  587.78    5034  589.93    5064  591.31    5094  590.89    5104  588.78
    5114  587.82  5124.1  587.88  5134.1  586.58  5144.1  586.44  5184.1  588.89
  5189.9  590.77  5212.3  591.87  5219.5  589.88  5233.2  588.62  5449.9  589.01
  5593.2  589.37  5633.2  588.78  5864.2  592.45    6246  603.49  6480.8  607.49
#Mann= 5 ,-1 , 0
  3913.1     .05       0    4961      .1       0  4998.7     .07       0
  5009.2      .1       0  5449.9     .05       0
Bank Sta=4543.8,5064
XS Rating Curve= 0 ,0
Exp/Cntr=0.3,0.1

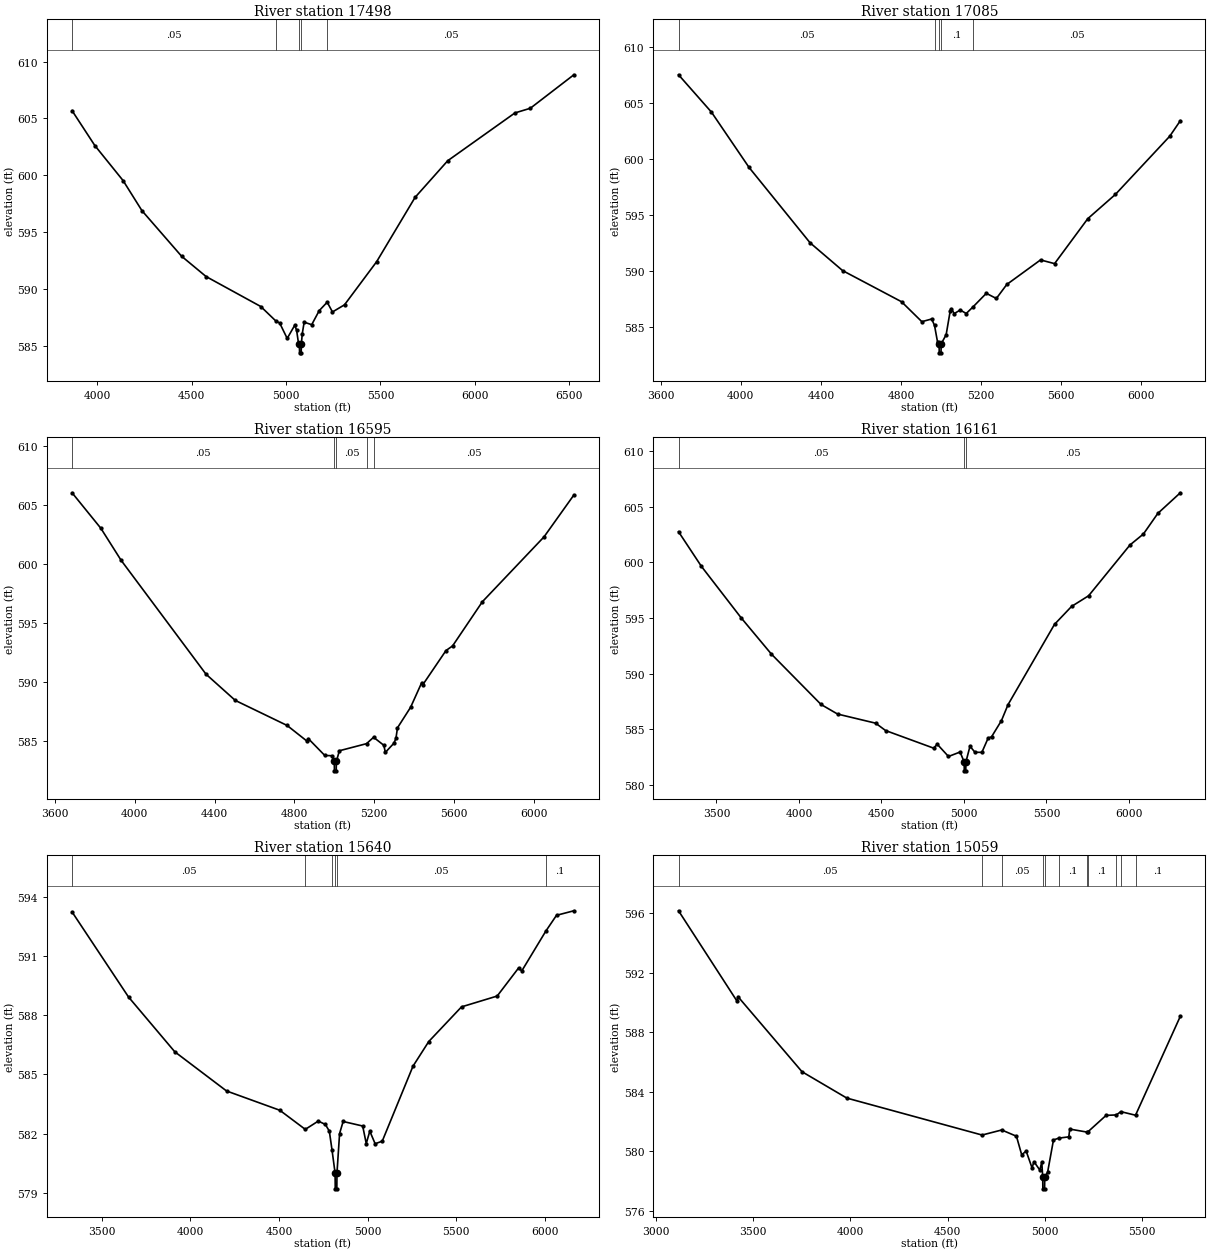
Type RM Length L Ch R = 1 ,17498   ,413,413,413
BEGIN DESCRIPTION:
Mapping XS 9df9adf9
END DESCRIPTION:
XS GIS Cut Line= 3
      2003405.59     13556973.12      2002031.17     13556977.18
      2000768.29     13557220.83
#Sta/Elev= 30
  3865.2  605.69  3985.8  602.62  4135.8  599.53  4235.8  596.88  4445.8  592.87
  4575.8  591.08  4865.8  588.44    4946  587.16  4965.8  586.99  5005.8  585.63
  5045.8  586.79  5055.8  586.35  5065.8  585.19  5070.5  585.16  5071.4  584.36
  5080.1  584.36    5081  585.16  5085.8  586.05  5095.8  587.06  5135.8  586.84
  5175.8  588.08  5217.9  588.82  5245.9  587.96  5309.7  588.59  5480.2  592.39
  5683.8  598.05    5857  601.28  6213.4  605.49  6294.9   605.9  6525.8  608.85
#Mann= 5 ,-1 , 0
  3865.2     .05       0    4946      .1       0  5070.5     .07       0
    5081      .1       0  5217.9     .05       0
Bank Sta=5070.5,5081
XS Rating Curve= 0 ,0
Exp/Cntr=0.3,0.1

Type RM Length L Ch R = 1 ,17085   ,490,490,490
BEGIN DESCRIPTION:
UNT 068 in HW 9.0
END DESCRIPTION:
XS GIS Cut Line= 3
      2003551.99     13556798.26        2002275.       13556575.
      2001068.74     13556663.97
#Sta/Elev= 30
  3689.4  607.49  3853.7  604.16  4041.7  599.22  4346.2   592.5  4508.6  590.02
    4803  587.24  4904.5  585.46  4953.5   585.7  4967.7  585.13  4983.2  583.61
  4990.5  583.48  4991.4  582.68  5000.2  582.68    5001  583.48  5025.9   584.3
  5045.9   586.4  5052.3  586.62    5066  586.18  5096.1   586.5  5126.1  586.19
  5161.2   586.8  5226.4  587.99  5276.5  587.53  5328.7  588.78  5497.1  590.97
  5567.3  590.64  5733.1  594.65  5871.3  596.82  6142.6  602.01  6195.3  603.39
#Mann= 5 ,-1 , 0
  3689.4     .05       0  4967.7      .1       0  4990.5     .07       0
    5001      .1       0  5161.2     .05       0
Bank Sta=4990.5,5001
XS Rating Curve= 0 ,0
Exp/Cntr=0.3,0.1

Type RM Length L Ch R = 1 ,16595   ,434,434,434
BEGIN DESCRIPTION:
UNT 068 in HW 8.0
END DESCRIPTION:
XS GIS Cut Line= 3
        2003525.       13556625.        2002325.       13556125.
      2001124.96     13556325.01
#Sta/Elev= 30
  3685.6  606.02  3830.2  603.01    3931  600.32  4357.3  590.67  4504.1  588.45
  4764.1  586.33  4864.8  584.99  4870.2  585.22  4953.1  583.79  4988.1  583.77
  5000.6  583.29  5001.4  582.49  5010.3  582.49  5011.2  583.29  5026.2  584.19
  5162.5  584.79  5197.8  585.33  5249.2  584.65  5256.8  584.05  5299.9  584.83
    5310  585.25  5317.6  586.13  5383.5  587.87  5439.3  589.96  5444.3  589.77
  5560.9  592.67  5593.9  593.06  5743.4   596.8  6052.6  602.29  6202.2  605.83
#Mann= 5 ,-1 , 0
  3685.6     .05       0  5000.6    .035       0  5011.2     .05       0
  5162.5      .1       0  5197.8     .05       0
Bank Sta=5000.6,5011.2
XS Rating Curve= 0 ,0
Exp/Cntr=0.3,0.1

Type RM Length L Ch R = 1 ,16161   ,521,521,521
BEGIN DESCRIPTION:
Mapping XS 4e449643
END DESCRIPTION:
XS GIS Cut Line= 4
      2003643.33     13556282.76      2003031.33      13555696.8
      2001746.61     13555792.29      2000952.31     13556226.33
#Sta/Elev= 30
  3270.3  602.74  3408.9  599.63  3649.5  595.01  3833.5  591.74    4134  587.22
  4234.2  586.36  4464.9  585.54    4525  584.88  4815.8   583.3  4838.1  583.65
  4906.1  582.55  4976.3  582.95  5001.1  582.06  5001.9  581.26  5010.8  581.26
  5011.7  582.06  5036.4  583.47  5066.5  582.93  5108.4  582.92  5146.7  584.21
  5166.8  584.31    5227  585.77  5267.1  587.21  5548.6  594.42    5652  596.03
  5755.4  596.99  6005.9  601.55  6087.5  602.54  6174.8  604.39    6311  606.24
#Mann= 3 ,-1 , 0
  3270.3     .05       0  5001.1    .035       0  5011.7     .05       0
Bank Sta=5001.1,5011.7
XS Rating Curve= 0 ,0
Exp/Cntr=0.3,0.1

Type RM Length L Ch R = 1 ,15640   ,581,581,581
BEGIN DESCRIPTION:
Mapping XS de574df2
END DESCRIPTION:
XS GIS Cut Line= 4
      2003580.49     13555602.73      2002592.34     13555309.95
      2001746.52     13555370.94      2000864.15     13555728.77
#Sta/Elev= 30
  3332.1  593.25  3650.7  588.93  3911.5  586.15  4203.5  584.16    4504  583.18
  4647.7  582.21    4721  582.63  4761.1  582.46  4783.4  582.12  4798.5  581.17
  4815.9  579.99  4816.8  579.19  4825.7  579.19  4826.5  579.99  4841.3     582
  4861.3  582.61  4971.6  582.38  4991.7  581.49  5011.7  582.12  5041.8  581.48
  5081.9  581.61  5255.5  585.42  5344.3  586.67  5529.1  588.43  5730.3  588.98
  5850.6   590.4  5869.3  590.26  6004.2  592.27    6065  593.08  6162.9  593.31
#Mann= 6 ,-1 , 0
  3332.1     .05       0  4647.7      .1       0  4798.5     .05       0
  4815.9    .035       0  4826.5     .05       0  6004.2      .1       0
Bank Sta=4815.9,4826.5
XS Rating Curve= 0 ,0
Exp/Cntr=0.3,0.1

Type RM Length L Ch R = 1 ,15059   ,164,164,164
BEGIN DESCRIPTION:
Mapping XS 5db8e09e
END DESCRIPTION:
XS GIS Cut Line= 2
      2003938.33     13554655.25       2001364.3      13554866.7
#Sta/Elev= 30
  3115.6  596.15  3416.4  590.09  3421.4  590.39  3751.1  585.35  3981.8  583.58
    4678   581.1    4779  581.44  4854.8  581.02  4881.7  579.78  4904.9  580.02
    4935   578.9  4945.1  579.31  4975.2  578.75  4985.2  579.29  4989.9  578.29
  4990.8  577.49  4999.7  577.49  5000.5  578.29  5015.3  578.61  5045.4  580.77
    5072  580.89  5124.3  580.98  5129.3   581.5  5217.3   581.3  5223.8  581.33
  5316.3  582.42  5368.8  582.45  5392.1  582.67  5467.7  582.43  5698.3  589.07
#Mann= 11 ,-1 , 0
  3115.6     .05       0    4678      .1       0    4779     .05       0
  4989.9    .035       0  5000.5     .05       0    5072      .1       0
  5217.3     .05       0  5223.8      .1       0  5368.8     .08       0
  5392.1     .05       0  5467.7      .1       0
Bank Sta=4989.9,5000.5
XS Rating Curve= 0 ,0
Exp/Cntr=0.3,0.1

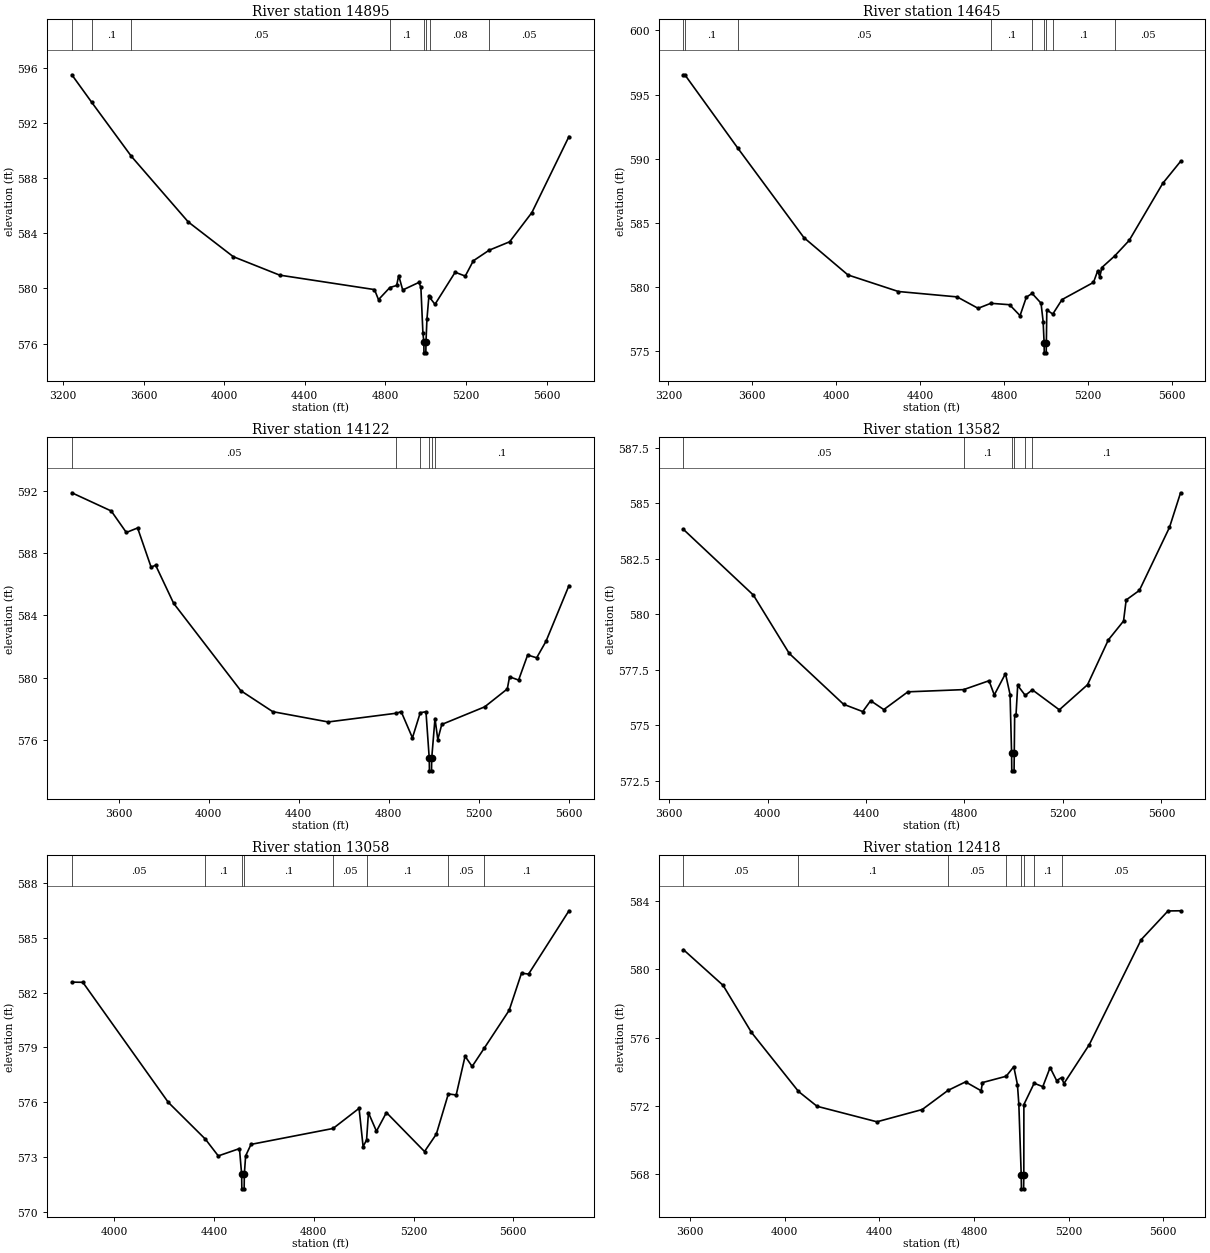
Type RM Length L Ch R = 1 ,14895   ,250,250,250
BEGIN DESCRIPTION:
Mapping XS 6de19fce
END DESCRIPTION:
XS GIS Cut Line= 2
      2003865.11     13554586.12       2001400.9     13554687.78
#Sta/Elev= 30
  3244.2  595.51  3343.4   593.5  3539.6  589.59  3821.7  584.83    4045  582.31
  4275.2  580.97  4745.6  579.92  4765.6  579.19  4821.9  580.07  4855.7  580.22
  4865.7  580.94  4885.7  579.89  4965.8  580.44  4975.8   580.1  4985.8   576.8
  4990.4  576.13  4991.2  575.33  5000.4  575.33  5001.2  576.13  5005.8  577.75
  5015.8  579.48    5019  579.36  5045.8  578.85  5145.9  581.18    5196   580.9
    5236  582.01  5314.7  582.78  5416.2  583.39  5526.5  585.51  5710.5  591.03
#Mann= 8 ,-1 , 0
  3244.2     .05       0  3343.4      .1       0  3539.6     .05       0
  4821.9      .1       0  4990.4     .04       0  5001.2      .1       0
    5019     .08       0  5314.7     .05       0
Bank Sta=4990.4,5001.2
XS Rating Curve= 0 ,0
Exp/Cntr=0.3,0.1

Type RM Length L Ch R = 1 ,14645   ,523,523,523
BEGIN DESCRIPTION:
UNT 068 in HW 6.0
END DESCRIPTION:
XS GIS Cut Line= 3
      2003859.09     13554406.32        2002125.       13554425.
      2001490.19     13554414.13
#Sta/Elev= 30
    3272  596.54    3281  596.49  3531.3  590.82  3846.1  583.85  4056.1  580.94
  4296.2  579.65  4576.2  579.23  4676.2  578.34  4736.9  578.73  4826.2  578.62
  4876.2  577.77  4906.2  579.21  4933.7   579.5  4976.2  578.74  4986.2  577.31
  4990.8  575.67  4991.6  574.87  5000.8  574.87  5001.6  575.67  5003.7  578.22
  5032.1  577.89  5076.2  579.02  5226.2  580.36  5246.2  581.26  5256.2  580.79
  5266.2  581.52  5327.2  582.42  5396.3  583.63  5556.3  588.08  5641.1  589.79
#Mann= 9 ,-1 , 0
    3272     .05       0    3281      .1       0  3531.3     .05       0
  4736.9      .1       0  4933.7     .07       0  4990.8     .07       0
  5001.6     .07       0  5032.1      .1       0  5327.2     .05       0
Bank Sta=4990.8,5001.6
XS Rating Curve= 0 ,0
Exp/Cntr=0.3,0.1

Type RM Length L Ch R = 1 ,14122   ,540,540,540
BEGIN DESCRIPTION:
UNT 068 in HW 5.0
END DESCRIPTION:
XS GIS Cut Line= 3
      2003846.92     13553941.04        2002225.       13554025.
      2001642.08     13554079.93
#Sta/Elev= 30
  3392.1  591.88  3567.3  590.71  3634.3  589.33  3684.4  589.62  3744.5   587.1
  3764.5  587.23  3844.6  584.78  4142.9  579.17  4285.2  577.82  4531.6  577.16
    4834  577.72    4856  577.82    4906  576.14  4940.6  577.75  4966.1  577.82
  4980.7  574.82  4981.5  574.02  4990.8  574.02  4991.6  574.82  5006.2  577.38
  5018.7  576.03  5036.3     577  5227.1  578.13  5327.6  579.28  5337.6  580.06
  5377.8  579.85    5418  581.46  5458.1  581.28  5499.6  582.34  5601.7  585.92
#Mann= 6 ,-1 , 0
  3392.1     .05       0    4834      .1       0  4940.6     .07       0
  4980.7     .07       0  4991.6     .07       0  5006.2      .1       0
Bank Sta=4980.7,4991.6
XS Rating Curve= 0 ,0
Exp/Cntr=0.3,0.1

Type RM Length L Ch R = 1 ,13582   ,524,524,524
BEGIN DESCRIPTION:
UNT 068 in HW 4.0
END DESCRIPTION:
XS GIS Cut Line= 3
      2003486.65     13553150.26        2002225.       13553625.
      2001598.89     13553866.54
#Sta/Elev= 30
  3658.5  583.82  3942.6  580.86  4088.3  578.23  4308.8  575.94  4386.8  575.61
  4418.9   576.1  4472.3   575.7  4570.1   576.5  4796.5   576.6  4899.7     577
    4921  576.36  4966.5  577.32  4985.1  576.38  4991.3  573.74  4992.1  572.94
  5001.4  572.94  5002.2  573.74  5003.8  575.44  5009.2  575.44  5016.1  576.79
  5046.8  576.34  5075.7  576.59  5185.2  575.69  5299.8  576.82  5384.3  578.84
    5446  579.69  5456.7  580.64  5510.3  581.07  5632.6  583.91  5677.6  585.47
#Mann= 6 ,-1 , 0
  3658.5     .05       0  4796.5      .1       0  4991.3     .07       0
  5002.2      .1       0  5046.8     .07       0  5075.7      .1       0
Bank Sta=4991.3,5002.2
XS Rating Curve= 0 ,0
Exp/Cntr=0.3,0.1

Type RM Length L Ch R = 1 ,13058   ,640,640,640
BEGIN DESCRIPTION:
Mapping XS 1bf42a8c
END DESCRIPTION:
XS GIS Cut Line= 3
      2003226.24     13552730.12      2001767.93     13553285.66
      2001451.49     13553580.42
#Sta/Elev= 30
    3830  582.57  3874.1  582.56  4216.6     576  4365.1  573.99  4417.1  573.07
    4502  573.47  4510.7  572.07  4511.5  571.27  4520.8  571.27  4521.6  572.07
  4526.7  573.07  4548.3   573.7  4877.2  574.57  4981.5  575.67  4997.7  573.58
  5011.6  573.94  5019.1  575.43  5051.2  574.42  5091.2  575.44  5243.9  573.31
  5291.2  574.26  5339.4  576.46  5370.8   576.4  5406.5  578.52  5434.8  577.96
  5482.9  578.95  5583.3  581.03  5632.7  583.06    5661  583.01    5823  586.47
#Mann= 8 ,-1 , 0
    3830     .05       0  4365.1      .1       0  4510.7    .035       0
  4521.6      .1       0  4877.2     .05       0  5011.6      .1       0
  5339.4     .05       0  5482.9      .1       0
Bank Sta=4510.7,4521.6
XS Rating Curve= 0 ,0
Exp/Cntr=0.3,0.1

Type RM Length L Ch R = 1 ,12418   ,835,835,835
BEGIN DESCRIPTION:
Mapping XS a19617b5
END DESCRIPTION:
XS GIS Cut Line= 4
      2003152.51     13552478.37       2002271.4     13552465.35
      2001598.66       13552869.       2001295.6     13553180.71
#Sta/Elev= 30
  3572.3  581.15  3739.8  579.06  3859.8   576.3  4058.4  572.84  4136.8  571.97
  4389.9  571.06  4581.3  571.78  4690.1   572.9  4764.2   573.4  4830.1  572.88
  4835.9  573.36    4936  573.73  4968.1  574.29  4983.6  573.24  4989.5  572.09
  4999.6  567.93  5000.4  567.13  5009.7  567.13  5010.5  567.93  5010.8  572.07
  5054.2  573.32  5090.7  573.12  5121.6  574.24    5149  573.48  5169.8  573.65
  5179.9   573.3  5287.4  575.59  5506.6  581.74  5619.7  583.42  5672.8  583.43
#Mann= 8 ,-1 , 0
  3572.3     .05       0  4058.4      .1       0  4690.1     .05       0
    4936     .07       0  4999.6     .07       0  5010.5     .07       0
  5054.2      .1       0  5169.8     .05       0
Bank Sta=4999.6,5010.5
XS Rating Curve= 0 ,0
Exp/Cntr=0.3,0.1

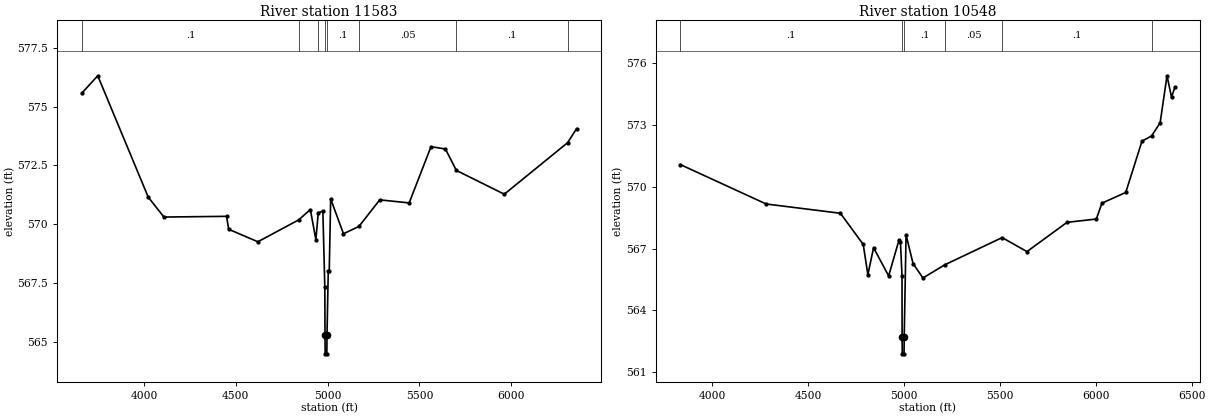
Type RM Length L Ch R = 1 ,11583   ,1035,1035,1035
BEGIN DESCRIPTION:
UNT 068 in HW 3.0
END DESCRIPTION:
XS GIS Cut Line= 3
      2002882.49     13551700.31        2001625.       13552175.
      2000340.84     13552589.19
#Sta/Elev= 30
  3662.1  575.58  3748.2  576.31  4022.8  571.16  4108.3  570.31  4449.5  570.34
  4461.1  569.79    4620  569.26  4842.7  570.19  4905.9  570.63  4936.1  569.35
  4949.1  570.49  4974.1  570.56  4984.8  567.32  4985.7   565.3  4986.5   564.5
  4995.8   564.5  4996.6   565.3  5003.5  568.01  5008.8  568.01  5016.7  571.08
  5086.3   569.6  5170.5  569.91  5283.9  571.04  5444.1  570.91  5563.1   573.3
  5641.7   573.2  5701.1  572.29  5962.2  571.28  6307.3  573.47  6355.5  574.06
#Mann= 8 ,-1 , 0
  3662.1      .1       0  4842.7     .07       0  4949.1      .1       0
  4985.7     .07       0  4996.6      .1       0  5170.5     .05       0
  5701.1      .1       0  6307.3     .05       0
Bank Sta=4985.7,4996.6
XS Rating Curve= 0 ,0
Exp/Cntr=0.3,0.1

Type RM Length L Ch R = 1 ,10548   ,935,935,935
BEGIN DESCRIPTION:
UNT 068 in HW 2.0
END DESCRIPTION:
XS GIS Cut Line= 3
      2002470.29     13550991.45      2001409.72     13551411.11
      2000199.71     13552185.73
#Sta/Elev= 30
    3836  571.07  4282.6  569.16  4669.5  568.71  4788.4   567.2  4812.7  565.73
  4842.4  567.04  4920.9  565.67  4974.9  567.41  4982.4  567.31  4990.6  565.68
  4991.1  562.69  4991.9  561.89  5001.2  561.89    5002  562.69  5011.7  567.66
  5048.1  566.27  5099.7  565.57  5213.6  566.21  5512.3  567.53  5641.7  566.85
  5850.6  568.27  6003.3  568.43  6032.4   569.2  6156.6  569.72  6241.2  572.21
  6291.2  572.46  6335.8   573.1  6371.5  575.38  6395.1  574.34  6413.3  574.84
#Mann= 6 ,-1 , 0
    3836      .1       0  4991.1     .07       0    5002      .1       0
  5213.6     .05       0  5512.3      .1       0  6291.2     .05       0
Bank Sta=4991.1,5002
XS Rating Curve= 0 ,0
Exp/Cntr=0.3,0.1