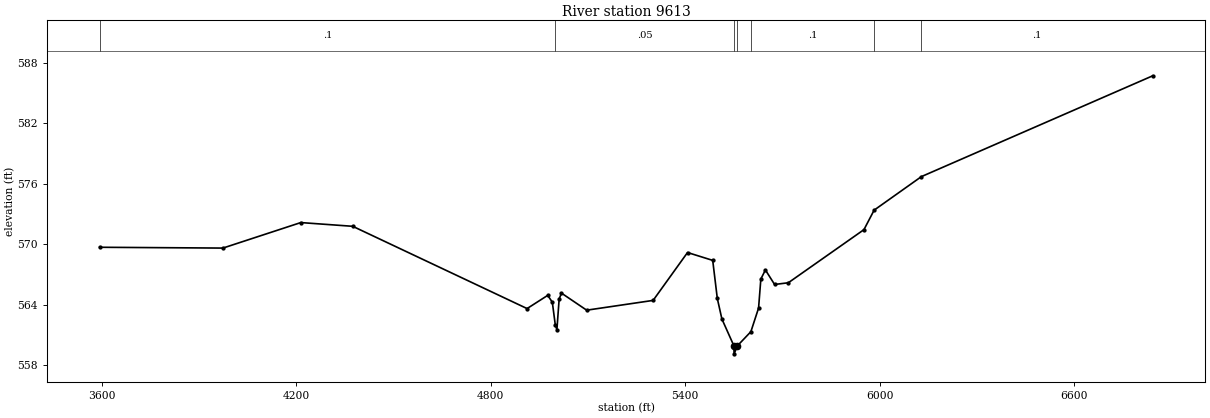
HEC-RAS study UNT 068 in HW.prj: UNT 068 in HW Base Level Engineering

--- UNT 068 in HW.g01 (geometry) --- (continued)

Type RM Length L Ch R = 1 ,9613    ,0,0,0
BEGIN DESCRIPTION:
UNT 068 in HW 1.0
END DESCRIPTION:
XS GIS Cut Line= 3
      2002255.04      13550609.5      2001039.74     13550665.05
      1999625.02     13552124.98
#Sta/Elev= 30
  3593.6  569.72    3974  569.64  4214.3  572.17  4374.5   571.8  4912.5  563.64
  4976.2  564.95  4990.4  564.27  4999.4  562.06  5004.5  561.54  5011.5   564.6
  5018.7  565.17  5096.4  563.48  5301.4  564.45  5407.6   569.2  5485.3  568.42
  5499.5  564.64  5513.6  562.61  5550.6  559.95  5551.3  559.15  5561.6  559.95
  5603.1  561.35  5626.8  563.69  5633.8  566.57  5647.9  567.47  5676.2  566.03
  5718.6   566.2    5952  571.47  5983.3   573.4  6129.3  576.73  6843.1  586.73
#Mann= 7 ,-1 , 0
  3593.6      .1       0  4999.4     .05       0  5550.6    .035       0
  5561.6     .05       0  5603.1      .1       0  5983.3     .05       0
  6129.3      .1       0
Bank Sta=5550.6,5561.6
XS Rating Curve= 0 ,0
Exp/Cntr=0.3,0.1
LCMann Table=0

Chan Stop Cuts=-1
Use User Specified Reach Order=0
Composite Channel Slope=5