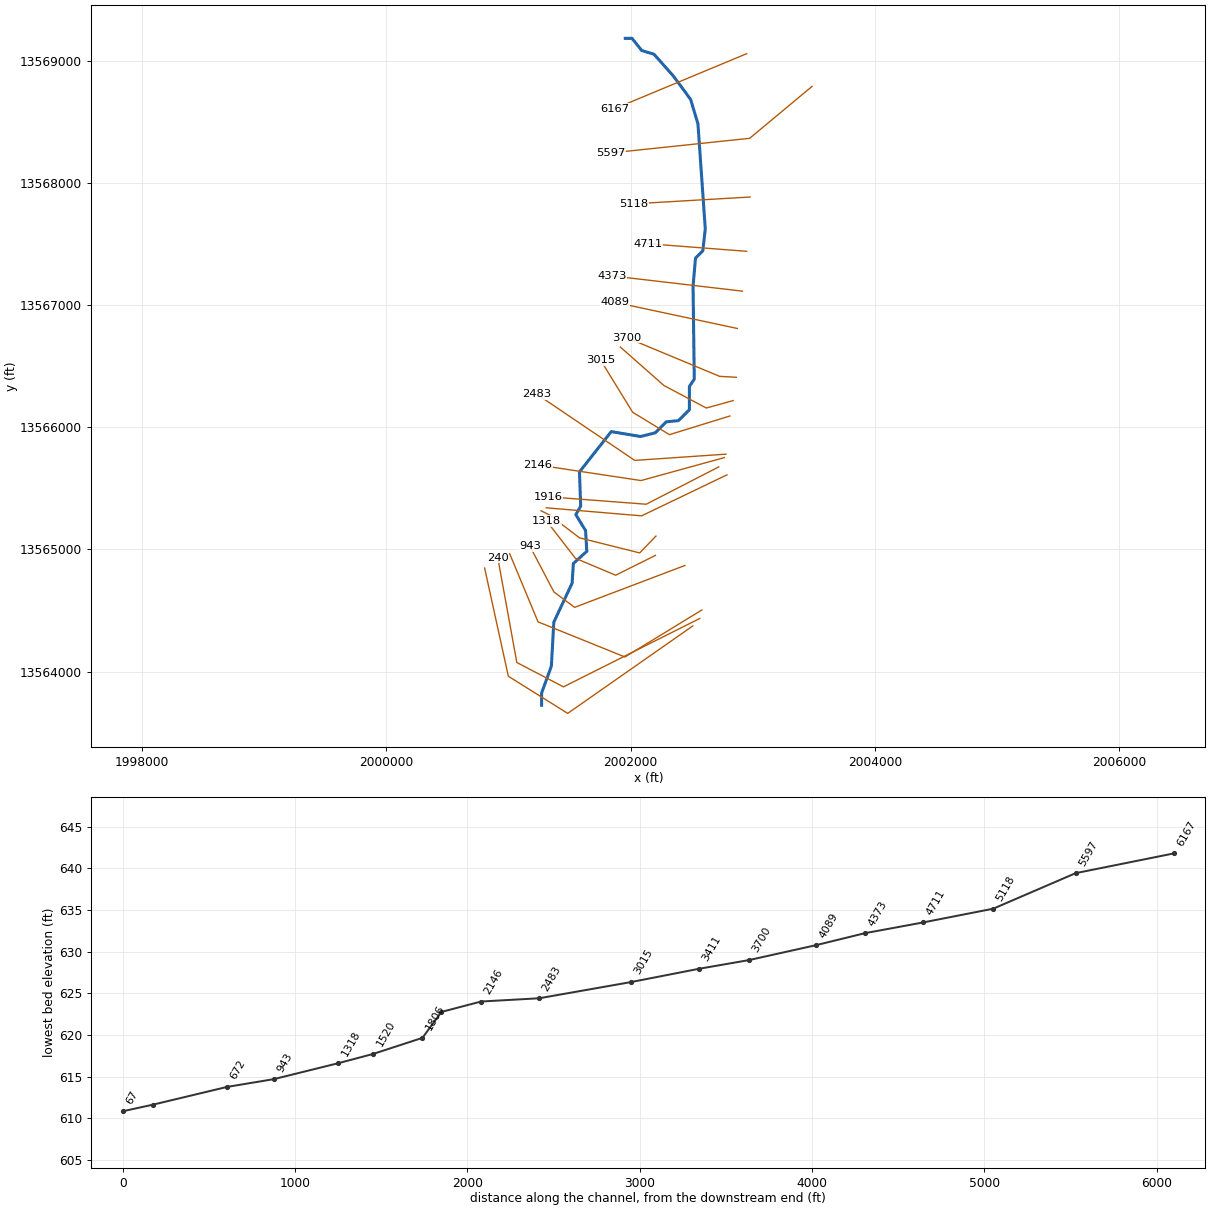
--- UNT 071 in HW.prj (project) ---

Proj Title=UNT 071 in HW Base Level Engineering
Current Plan=p01
Default Exp/Contr=0.3,0.1
English Units
Geom File=g01
Flow File=f01
Plan File=p01
Y Axis Title=Elevation
X Axis Title(PF)=Main Channel Distance
X Axis Title(XS)=Station
BEGIN DESCRIPTION:
UNT 071 in HW
END DESCRIPTION:
DSS Export Rating Curves= 0
DSS Export Rating Curve Sorted= 0
DSS Export Volume Flow Curves= 0
DXF OffsetX= 0
DXF OffsetY= 0
DXF ScaleX= 1
DXF ScaleY= 10

--- UNT 071 in HW.p01 (plan) ---

Plan Title=Multiple Run
Short Identifier=Multiple
Geom File=g01
Flow File=f01
Subcritical Flow
K Sum by GR= 0
Std Step Tol= 0.01
Critical Tol= 0.01
Num of Std Step Trials= 20
Max Error Tol= 0.3
Flow Tol Ratio= 0.001
Split Flow NTrial= 30
Split Flow Tol= 0.02
Split Flow Ratio= 0.02
Log Output Level= 0
Friction Slope Method= 1
Unsteady Friction Slope Method= 2
Unsteady Bridges Friction Slope Method= 1
Parabolic Critical Depth
Global Vel Dist=  1 , 1 , 1
Global Log Level= 0
CheckData=True
Encroach Param= -1, 0, 0, 0
BEGIN DESCRIPTION:
Multiple Run
END DESCRIPTION:

--- UNT 071 in HW.f01 (steady flow) ---

Flow Title=Multiple
Program Version=5.05
Number of Profiles= 7
Profile Names=10-year,25-year,50-year,1pct_min,100-year,1pct_plu,500-year
River Rch & RM=UNT 071 in HW,Reach-1         ,6167
     441     613     755     461     920    1836    1370
Boundary for River Rch & Prof#=UNT 071 in HW,Reach-1         , 1
Up Type= 0
Dn Type= 3
Dn Slope=0.005
Boundary for River Rch & Prof#=UNT 071 in HW,Reach-1         , 2
Up Type= 0
Dn Type= 3
Dn Slope=0.005
Boundary for River Rch & Prof#=UNT 071 in HW,Reach-1         , 3
Up Type= 0
Dn Type= 3
Dn Slope=0.005
Boundary for River Rch & Prof#=UNT 071 in HW,Reach-1         , 4
Up Type= 0
Dn Type= 3
Dn Slope=0.005
Boundary for River Rch & Prof#=UNT 071 in HW,Reach-1         , 5
Up Type= 0
Dn Type= 3
Dn Slope=0.005
Boundary for River Rch & Prof#=UNT 071 in HW,Reach-1         , 6
Up Type= 0
Dn Type= 3
Dn Slope=0.005
Boundary for River Rch & Prof#=UNT 071 in HW,Reach-1         , 7
Up Type= 0
Dn Type= 3
Dn Slope=0.005
DSS Import GetInterval= 0
DSS Import GetPeak= 0
DSS Import FillOption= 0

--- UNT 071 in HW.g01 (geometry) ---

Geom Title=Existing Conditions
Program Version=5.05

River Reach=UNT 071 in HW   ,Reach-1
Reach XY= 30
       2001955.8     13569184.54       2002010.8     13569184.54
       2002090.8     13569084.54       2002190.8     13569054.54
       2002350.8     13568874.54       2002490.8     13568684.54
       2002550.8     13568484.54       2002610.8     13567624.54
       2002590.8     13567444.54       2002530.8     13567384.54
       2002510.8     13567154.54       2002520.8     13566394.54
       2002480.8     13566334.54       2002480.8     13566144.54
       2002390.8     13566054.54       2002290.8     13566044.54
       2002200.8     13565954.54       2002080.8     13565924.54
       2001840.8     13565964.54       2001580.8     13565634.54
       2001590.8     13565354.54       2001550.8     13565284.54
       2001630.8     13565154.54       2001640.8     13564984.54
       2001530.8     13564884.54       2001520.8     13564724.54
       2001370.8     13564404.54       2001350.8     13564044.54
       2001270.8     13563824.54       2001270.8      13563724.2

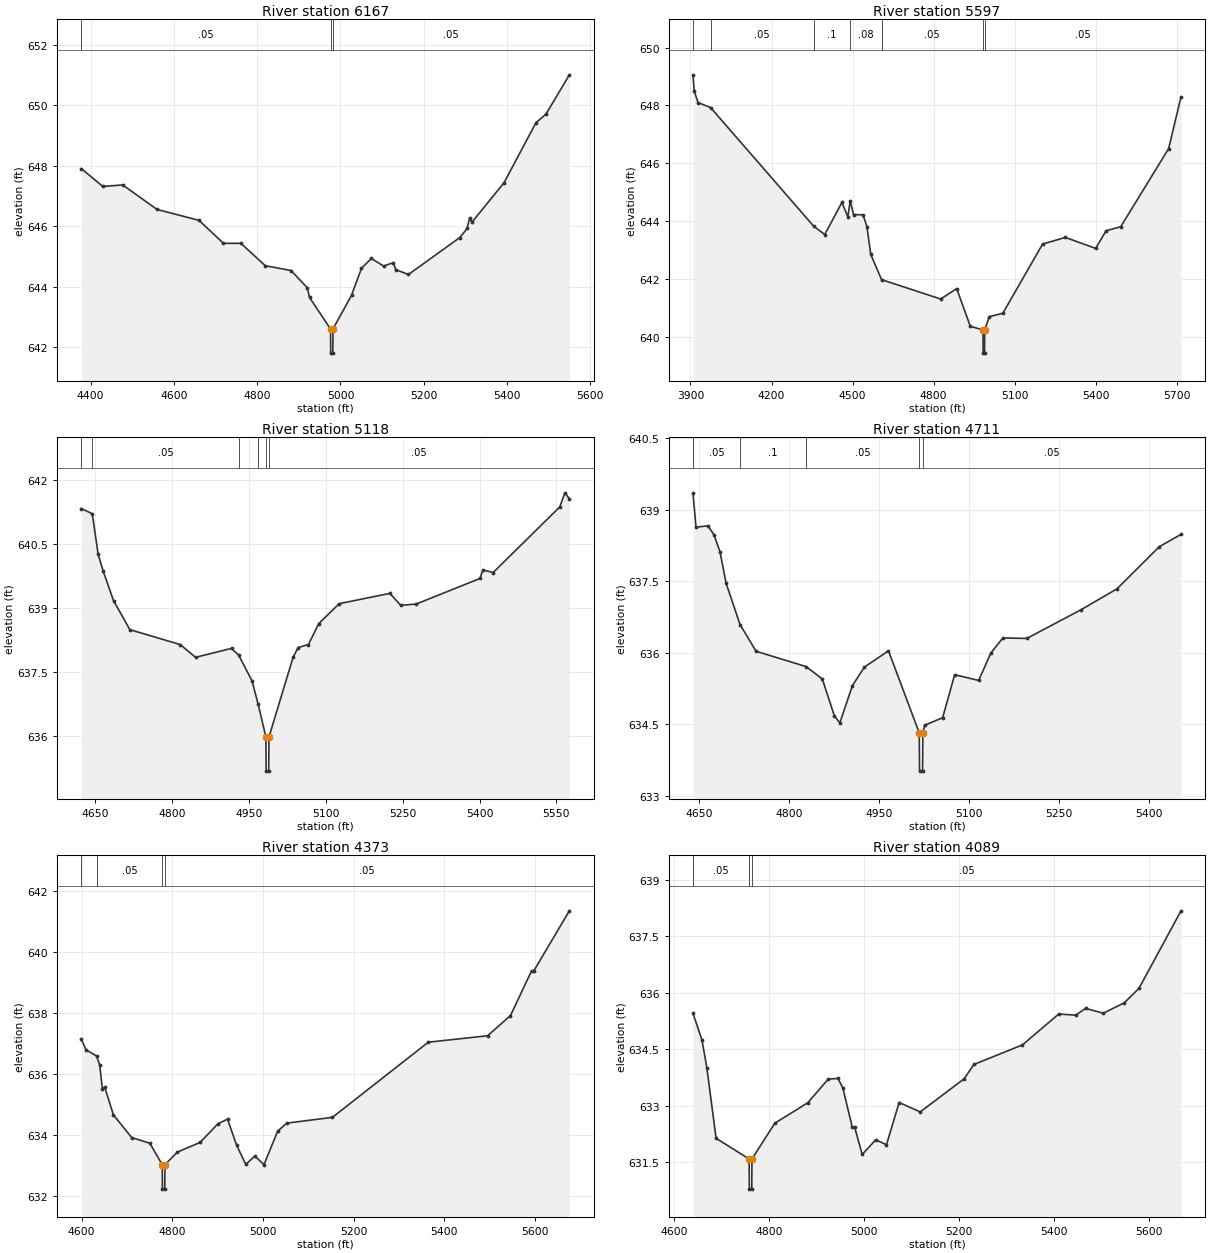
Type RM Length L Ch R = 1 ,6167    ,570,570,570
BEGIN DESCRIPTION:
UNT 071 in HW 18.0
END DESCRIPTION:
XS GIS Cut Line= 2
      2002950.03     13569058.95      2001868.37     13568608.26
#Sta/Elev= 30
  4377.8  647.91  4429.5  647.32  4477.2  647.37  4559.5  646.56  4660.3   646.2
  4719.1  645.44    4761  645.44  4819.5   644.7  4881.6  644.54  4920.3  643.97
  4925.7  643.65  4976.1  642.61  4976.6  641.81  4981.6  641.81  4982.1  642.61
  5026.5  643.72  5050.3  644.61  5074.1  644.94  5103.4  644.69  5127.2   644.8
  5132.6  644.57  5163.2  644.41  5286.5  645.63  5304.1  645.93  5310.3  646.28
  5315.7  646.14  5392.6  647.44  5469.5  649.43  5493.4  649.71  5549.6  651.01
#Mann= 3 ,-1 , 0
  4377.8     .05       0  4976.1    .035       0  4982.1     .05       0
Bank Sta=4976.1,4982.1
XS Rating Curve= 0 ,0
Exp/Cntr=0.3,0.1

Type RM Length L Ch R = 1 ,5597    ,479,479,479
BEGIN DESCRIPTION:
UNT 071 in HW 17.0
END DESCRIPTION:
XS GIS Cut Line= 3
      2003485.42     13568791.32      2002974.31     13568365.97
      2001839.43     13568246.51
#Sta/Elev= 30
  3909.2  649.06  3913.8   648.5  3928.1   648.1  3974.3  647.93  4355.8  643.83
  4396.8  643.54  4460.5  644.65  4482.2  644.15  4491.2  644.71  4503.5  644.23
  4538.7  644.22    4553  643.81  4567.3  642.85  4607.2  641.98    4826  641.31
  4885.2  641.67  4935.4  640.37  4982.7  640.24  4983.2  639.44  4988.2  639.44
  4988.7  640.24  5005.8   640.7  5056.1  640.82  5203.1  643.21  5287.4  643.44
  5399.2  643.06  5438.2  643.67  5492.2  643.81  5669.5  646.51  5715.3   648.3
#Mann= 7 ,-1 , 0
  3909.2      .1       0  3974.3     .05       0  4355.8      .1       0
  4491.2     .08       0  4607.2     .05       0  4982.7    .035       0
  4988.7     .05       0
Bank Sta=4982.7,4988.7
XS Rating Curve= 0 ,0
Exp/Cntr=0.3,0.1

Type RM Length L Ch R = 1 ,5118    ,407,407,407
BEGIN DESCRIPTION:
UNT 071 in HW 16.0
END DESCRIPTION:
XS GIS Cut Line= 2
      2002977.76     13567885.34      2002026.38     13567829.78
#Sta/Elev= 30
  4622.4  641.33  4643.8  641.21  4655.2  640.26  4665.2  639.86  4685.3  639.17
  4717.2  638.49  4815.5  638.14  4845.5  637.84  4915.7  638.05  4929.7  637.89
  4955.7  637.29  4967.7  636.74  4982.8  635.97  4983.3  635.17  4988.3  635.17
  4988.8  635.97  5035.9  637.84  5045.9  638.07  5065.9  638.14  5085.9  638.63
    5126   639.1  5224.9  639.34  5246.2  639.06  5276.3  639.09  5400.8  639.69
  5406.5  639.89  5426.5  639.83  5556.7  641.37  5566.7   641.7  5575.4  641.56
#Mann= 6 ,-1 , 0
  4622.4     .08       0  4643.8     .05       0  4929.7      .1       0
  4967.7     .05       0  4982.8    .035       0  4988.8     .05       0
Bank Sta=4982.8,4988.8
XS Rating Curve= 0 ,0
Exp/Cntr=0.3,0.1

Type RM Length L Ch R = 1 ,4711    ,338,338,338
BEGIN DESCRIPTION:
UNT 071 in HW 15.0
END DESCRIPTION:
XS GIS Cut Line= 2
      2002950.04      13567440.9      2002138.73      13567503.3
#Sta/Elev= 30
  4639.7  639.35  4644.8  638.63  4664.8  638.66  4674.8  638.47  4684.9  638.11
  4694.9  637.46  4718.2  636.59    4745  636.03  4828.4  635.71  4855.4  635.45
  4875.4  634.68  4884.6  634.53  4905.5  635.31  4925.6   635.7  4965.7  636.04
    5017  634.32  5017.5  633.52  5022.5  633.52    5023  634.32  5025.9  634.48
    5056  634.64    5076  635.54  5116.1  635.42  5136.2  635.99  5156.3  636.31
  5196.4   636.3  5286.6   636.9  5346.8  637.34    5417  638.22  5453.4  638.48
#Mann= 5 ,-1 , 0
  4639.7     .05       0  4718.2      .1       0  4828.4     .05       0
    5017    .035       0    5023     .05       0
Bank Sta=5017,5023
XS Rating Curve= 0 ,0
Exp/Cntr=0.3,0.1

Type RM Length L Ch R = 1 ,4373    ,284,284,284
BEGIN DESCRIPTION:
UNT 071 in HW 14.0
END DESCRIPTION:
XS GIS Cut Line= 2
      2002915.28     13567114.51      2001845.86     13567239.51
#Sta/Elev= 30
  4599.3  637.14  4609.7  636.79  4632.8  636.59  4639.9  636.29  4645.7  635.52
  4650.8  635.57  4670.1  634.66  4710.3  633.92  4750.6  633.73  4777.8  633.03
  4778.3  632.23  4783.3  632.23  4783.8  633.03    4811  633.44  4861.4  633.76
  4900.8  634.37  4921.8  634.52  4941.9  633.67    4962  633.04  4982.2  633.31
  5002.3  633.03  5032.5  634.13  5052.6  634.39  5153.3  634.58  5364.8  637.04
  5495.6  637.25    5546  637.91  5592.7  639.38  5597.7  639.38    5676  641.34
#Mann= 4 ,-1 , 0
  4599.3     .08       0  4632.8     .05       0  4777.8    .035       0
  4783.8     .05       0
Bank Sta=4777.8,4783.8
XS Rating Curve= 0 ,0
Exp/Cntr=0.3,0.1

Type RM Length L Ch R = 1 ,4089    ,389,389,389
BEGIN DESCRIPTION:
UNT 071 in HW 13.0
END DESCRIPTION:
XS GIS Cut Line= 2
      2002873.63     13566808.96      2001868.34     13567023.88
#Sta/Elev= 30
  4639.2  635.46  4658.2  634.75  4668.5  634.01  4687.9  632.14  4757.5  631.59
    4758  630.79    4763  630.79  4763.5  631.59  4811.6  632.54  4880.7  633.08
  4924.1  633.71  4944.6  633.73  4954.8  633.48  4974.6  632.44  4979.7  632.44
  4995.7  631.71  5024.1   632.1  5046.8  631.97  5073.5  633.09  5117.9  632.84
  5210.4  633.72  5230.9   634.1  5333.2  634.62  5409.7  635.44  5445.6  635.41
  5466.1  635.59  5503.5  635.46  5547.9  635.74  5578.6  636.12  5667.2  638.18
#Mann= 3 ,-1 , 0
  4639.2     .05       0  4757.5    .035       0  4763.5     .05       0
Bank Sta=4757.5,4763.5
XS Rating Curve= 0 ,0
Exp/Cntr=0.3,0.1

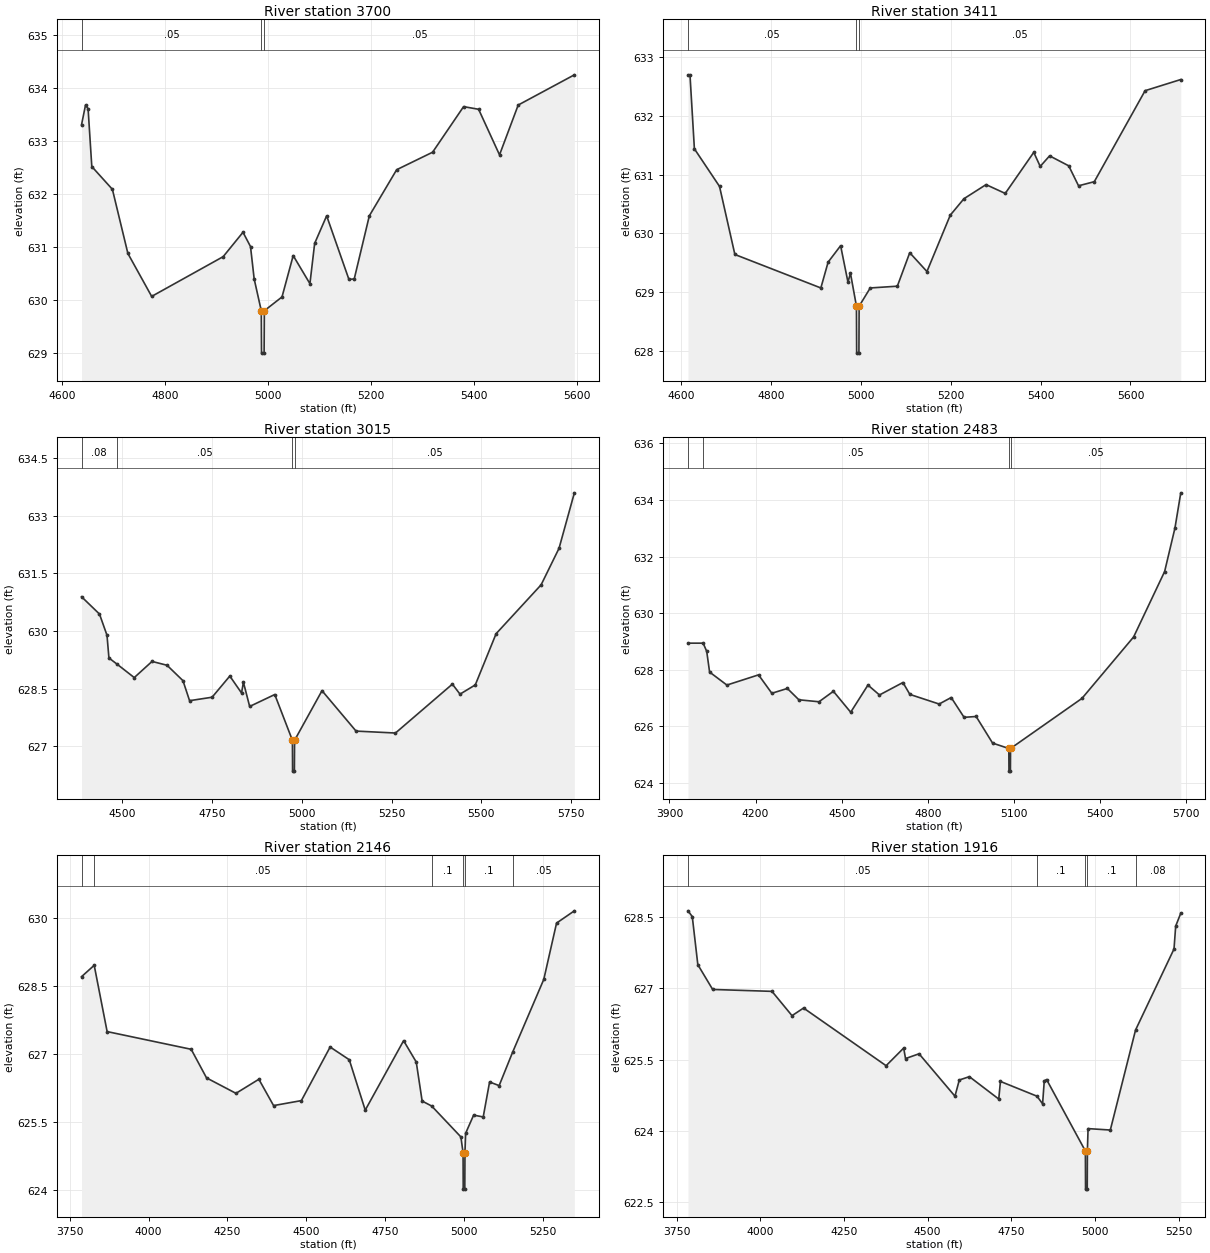
Type RM Length L Ch R = 1 ,3700    ,289,289,289
BEGIN DESCRIPTION:
UNT 071 in HW 12.0
END DESCRIPTION:
XS GIS Cut Line= 3
      2002864.83      13566409.4      2002727.71     13566417.21
      2001970.83     13566732.58
#Sta/Elev= 30
  4638.5  633.31  4646.2  633.68  4651.2  633.61  4658.4  632.52  4698.4  632.09
  4728.5  630.88  4774.7  630.07  4913.6  630.82  4952.1  631.28  4966.7  631.01
  4973.8   630.4  4987.6   629.8  4988.1     629  4993.1     629  4993.6   629.8
  5027.9  630.06  5049.6  630.84  5082.1  630.31  5091.3  631.07  5114.6  631.59
  5157.9  630.39  5168.2   630.4  5197.5  631.59  5250.6  632.46  5320.4  632.79
  5380.6  633.65  5409.8   633.6  5450.4  632.74  5486.7  633.68  5595.8  634.25
#Mann= 3 ,-1 , 0
  4638.5     .05       0  4987.6    .035       0  4993.6     .05       0
Bank Sta=4987.6,4993.6
XS Rating Curve= 0 ,0
Exp/Cntr=0.3,0.1

Type RM Length L Ch R = 1 ,3411    ,396,396,396
BEGIN DESCRIPTION:
UNT 071 in HW 11.0
END DESCRIPTION:
XS GIS Cut Line= 4
      2002838.75     13566218.43      2002619.53     13566157.63
      2002272.34     13566342.13      2001915.32     13566656.86
#Sta/Elev= 30
  4615.4   632.7  4619.9   632.7  4629.7  631.44  4685.6   630.8  4719.8  629.64
  4911.1  629.07  4927.3  629.51  4955.1  629.79  4971.4  629.17    4977  629.32
  4990.3  628.76  4990.8  627.96  4995.8  627.96  4996.3  628.76    5021  629.07
  5081.3   629.1  5108.9  629.67  5147.2  629.35  5199.1  630.31  5229.5  630.59
  5278.7  630.83  5321.4  630.68  5384.9  631.38  5399.2  631.14  5420.1  631.32
  5462.7  631.15  5484.5  630.81  5519.6  630.88  5632.6  632.43    5712  632.62
#Mann= 3 ,-1 , 0
  4615.4     .05       0  4990.3    .035       0  4996.3     .05       0
Bank Sta=4990.3,4996.3
XS Rating Curve= 0 ,0
Exp/Cntr=0.3,0.1

Type RM Length L Ch R = 1 ,3015    ,532,532,532
BEGIN DESCRIPTION:
UNT 071 in HW 10.0
END DESCRIPTION:
XS GIS Cut Line= 4
      2002812.73     13566092.57      2002317.31     13565939.66
      2002016.27     13566122.95      2001752.94     13566551.35
#Sta/Elev= 30
  4385.9  630.89  4435.9  630.44  4456.8  629.89  4462.2   629.3  4484.7  629.14
  4532.8  628.79  4582.4  629.21  4624.2  629.11  4668.6  628.71    4687  628.19
  4749.8  628.28  4799.2  628.83  4831.9  628.39  4837.1  628.67  4854.5  628.04
  4924.5  628.35  4973.7  627.16  4974.2  626.36  4979.2  626.36  4979.7  627.16
  5056.2  628.45  5151.1   627.4    5261  627.35  5419.6  628.62  5440.9  628.36
  5483.5   628.6  5541.5  629.93    5667   631.2    5717  632.15  5759.7  633.59
#Mann= 4 ,-1 , 0
  4385.9     .08       0  4484.7     .05       0  4973.7    .035       0
  4979.7     .05       0
Bank Sta=4973.7,4979.7
XS Rating Curve= 0 ,0
Exp/Cntr=0.3,0.1

Type RM Length L Ch R = 1 ,2483    ,337,337,337
BEGIN DESCRIPTION:
UNT 071 in HW 9.0
END DESCRIPTION:
XS GIS Cut Line= 3
      2002780.15     13565780.07      2002033.52     13565728.86
      2001232.35     13566270.73
#Sta/Elev= 30
  3964.7  628.94  4017.6  628.94    4030  628.65    4040  627.92  4100.2  627.46
  4210.4  627.82  4256.7  627.17  4310.7  627.34  4350.8  626.94  4420.9  626.87
    4471  627.24  4531.2   626.5  4591.3  627.46  4631.4  627.11  4713.1  627.55
  4737.2  627.13  4839.1  626.79  4881.1  627.02  4925.9  626.32  4967.9  626.35
  5025.2  625.41  5081.7  625.22  5082.2  624.42  5087.2  624.42  5087.7  625.22
  5336.4  626.99  5516.2  629.16  5624.1  631.47  5660.1  633.01  5680.3  634.25
#Mann= 4 ,-1 , 0
  3964.7     .08       0  4017.6     .05       0  5081.7    .035       0
  5087.7     .05       0
Bank Sta=5081.7,5087.7
XS Rating Curve= 0 ,0
Exp/Cntr=0.3,0.1

Type RM Length L Ch R = 1 ,2146    ,230,230,230
BEGIN DESCRIPTION:
UNT 071 in HW 8.0
END DESCRIPTION:
XS GIS Cut Line= 3
      2002767.11     13565751.85      2002085.18     13565563.88
       2001239.1     13565691.46
#Sta/Elev= 30
  3787.3  628.71  3827.4  628.96  3868.4   627.5    4135  627.11  4183.7  626.48
    4277  626.14  4349.6  626.45  4396.3  625.87  4484.5  625.98  4575.7  627.16
  4636.4  626.88    4687  625.77  4808.7   627.3  4848.8  626.83  4867.5  625.97
  4897.8  625.86  4990.4  625.18  4997.3  624.83  4997.8  624.03  5002.8  624.03
  5003.3  624.83  5005.4  625.26  5030.8  625.66  5061.2  625.62  5081.4  626.39
  5111.7  626.31  5154.1  627.04  5253.3  628.65  5293.8  629.89  5350.3  630.16
#Mann= 6 ,-1 , 0
  3787.3     .08       0  3827.4     .05       0  4897.8      .1       0
  4997.3     .07       0  5003.3      .1       0  5154.1     .05       0
Bank Sta=4997.3,5003.3
XS Rating Curve= 0 ,0
Exp/Cntr=0.3,0.1

Type RM Length L Ch R = 1 ,1916    ,110,110,110
BEGIN DESCRIPTION:
UNT 071 in HW 6.0
END DESCRIPTION:
XS GIS Cut Line= 3
      2002721.53     13565675.88      2002127.12       13565370.
      2001325.04     13565431.17
#Sta/Elev= 30
  3783.6  628.62  3796.5   628.5  3813.1  627.49  3857.4  626.97  4034.8  626.93
  4094.6  626.42  4129.1  626.58  4375.8  625.37  4428.3  625.74  4433.9  625.52
  4474.3  625.62  4581.6  624.73  4594.6  625.07  4624.7  625.14  4712.5  624.67
  4717.5  625.04  4826.8  624.73  4843.5  624.57  4848.5  625.05  4855.4  625.08
  4971.4  623.58  4971.9  622.78  4976.9  622.78  4977.4  623.58  4979.4  624.05
  5045.9  624.02  5121.4  626.12  5236.3  627.82  5241.3   628.3  5256.5  628.57
#Mann= 5 ,-1 , 0
  3783.6     .05       0  4826.8      .1       0  4971.4     .07       0
  4977.4      .1       0  5121.4     .08       0
Bank Sta=4971.4,4977.4
XS Rating Curve= 0 ,0
Exp/Cntr=0.3,0.1

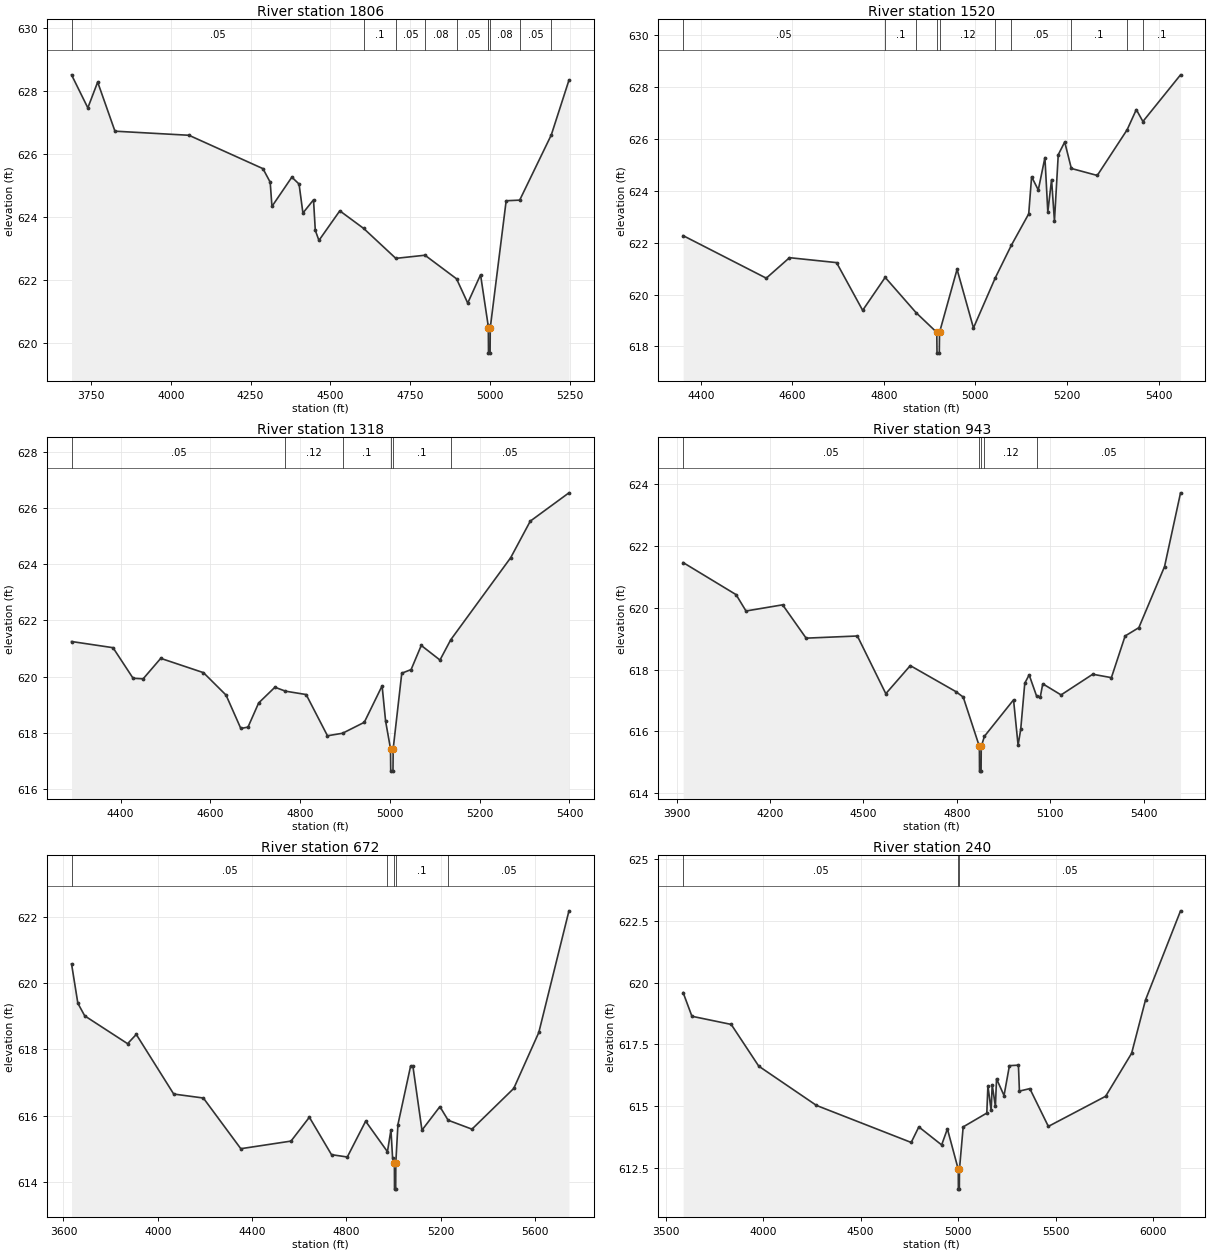
Type RM Length L Ch R = 1 ,1806    ,286,286,286
BEGIN DESCRIPTION:
UNT 071 in HW 5.0
END DESCRIPTION:
XS GIS Cut Line= 3
      2002788.81     13565610.78      2002089.54     13565274.92
      2001308.87      13565340.8
#Sta/Elev= 30
    3689  628.51  3740.1  627.46  3770.9  628.28  3825.1  626.72  4057.1  626.59
    4289  625.53  4311.7   625.1  4317.2  624.33  4379.6  625.26  4402.2  625.04
  4414.3  624.12  4447.5  624.54  4453.1  623.57  4464.5  623.25  4529.9  624.19
  4604.8  623.63  4705.5  622.68  4796.9  622.78  4895.9  622.03  4930.9  621.26
  4971.1  622.16  4994.9  620.55  4995.5  620.47    4996  619.67    5001  619.67
  5001.5  620.47  5051.4  624.51  5093.8  624.53  5192.8   626.6  5248.2  628.34
#Mann= 10 ,-1 , 0
    3689     .05       0  4604.8      .1       0  4705.5     .05       0
  4796.9     .08       0  4895.9     .05       0  4994.9     .08       0
  4995.5     .07       0  5001.5     .08       0  5093.8     .05       0
  5192.8      .1       0
Bank Sta=4995.5,5001.5
XS Rating Curve= 0 ,0
Exp/Cntr=0.3,0.1

Type RM Length L Ch R = 1 ,1520    ,202,202,202
BEGIN DESCRIPTION:
UNT 071 in HW 7.0
END DESCRIPTION:
XS GIS Cut Line= 5
      2002207.21     13565109.47      2002073.97     13564971.37
      2001581.97     13565094.37      2001335.44     13565281.87
      2001266.01     13565316.59
#Sta/Elev= 30
  4361.6  622.27  4543.2  620.63  4593.9  621.42  4696.7  621.23  4753.7  619.39
  4802.9  620.66  4870.4   619.3  4915.6  618.54  4916.1  617.74  4921.1  617.74
  4921.6  618.54  4959.9  620.97  4995.7  618.71  5043.3  620.64  5078.2  621.89
  5116.4  623.11  5122.7  624.54  5137.3  624.03  5151.8  625.28  5158.1  623.18
  5166.3  624.43  5172.6  622.83  5180.9  625.39    5195  625.88  5209.5  624.86
  5266.1  624.59  5331.3  626.35  5351.4  627.13  5365.8  626.67    5448  628.47
#Mann= 10 ,-1 , 0
  4361.6     .05       0  4802.9      .1       0  4870.4     .12       0
  4915.6     .07       0  4921.6     .12       0  5043.3      .1       0
  5078.2     .05       0  5209.5      .1       0  5331.3     .05       0
  5365.8      .1       0
Bank Sta=4915.6,4921.6
XS Rating Curve= 0 ,0
Exp/Cntr=0.3,0.1

Type RM Length L Ch R = 1 ,1318    ,375,375,375
BEGIN DESCRIPTION:
UNT 071 in HW 4.0
END DESCRIPTION:
XS GIS Cut Line= 4
      2002202.89     13564951.07      2001877.11     13564788.81
      2001547.25      13564927.7      2001311.15     13565233.25
#Sta/Elev= 30
  4290.9  621.25  4383.3  621.03    4428  619.94  4450.4  619.92  4489.6  620.65
  4584.8  620.14  4635.1  619.34    4668  618.15    4684   618.2  4707.7  619.06
  4743.9  619.62  4767.5  619.48  4813.5  619.36    4861  617.89  4894.6  617.98
    4943  618.37  4982.7  619.67  4990.5  618.41  5001.4  617.43  5001.9  616.63
  5006.9  616.63  5007.4  617.43  5026.5  620.12  5047.3  620.25  5069.9  621.11
  5111.6  620.59  5135.5  621.31  5269.2  624.24  5312.7  625.54  5398.9  626.55
#Mann= 6 ,-1 , 0
  4290.9     .05       0  4767.5     .12       0  4894.6      .1       0
  5001.4     .07       0  5007.4      .1       0  5135.5     .05       0
Bank Sta=5001.4,5007.4
XS Rating Curve= 0 ,0
Exp/Cntr=0.3,0.1

Type RM Length L Ch R = 1 ,943     ,271,271,271
BEGIN DESCRIPTION:
UNT 071 in HW 3.0
END DESCRIPTION:
XS GIS Cut Line= 4
      2002443.83     13564868.63      2001541.01     13564525.73
      2001371.74     13564651.59      2001175.74     13565024.88
#Sta/Elev= 30
  3920.6  621.47  4090.8  620.43  4122.6   619.9  4240.3   620.1  4315.8  619.02
  4480.5  619.09  4571.9  617.22  4650.5  618.13  4796.5  617.29  4820.6  617.11
  4872.5  615.51    4873  614.71    4878  614.71  4878.5  615.51  4888.8  615.84
  4982.3  617.02  4996.9  615.55  5005.3  616.06  5018.4  617.56  5032.4  617.83
  5056.8  617.13  5068.3  617.12  5076.2  617.54    5135  617.18  5236.7  617.85
  5296.7  617.74  5340.8  619.09  5384.9  619.36  5467.5  621.34  5518.9  623.73
#Mann= 5 ,-1 , 0
  3920.6     .05       0  4872.5     .07       0  4878.5     .05       0
  4888.8     .12       0  5056.8     .05       0
Bank Sta=4872.5,4878.5
XS Rating Curve= 0 ,0
Exp/Cntr=0.3,0.1

Type RM Length L Ch R = 1 ,672     ,432,432,432
BEGIN DESCRIPTION:
UNT 071 in HW 2.0
END DESCRIPTION:
XS GIS Cut Line= 4
       2002582.7     13564504.04      2001953.11     13564119.46
      2001241.69     13564406.87      2001009.53     13564964.75
#Sta/Elev= 30
  3634.2  620.58    3661  619.39  3690.1  619.01  3871.9  618.17  3908.7  618.45
  4067.5  616.65  4193.2  616.53    4352     615  4564.9  615.23  4642.7  615.95
  4736.6  614.82  4803.6  614.75  4881.4  615.83  4973.8  614.91  4988.7  615.57
  4995.5  614.73  5003.3  614.58  5003.8  613.78  5008.8  613.78  5009.3  614.58
  5018.3  615.73  5071.9  617.49  5081.8  617.49  5120.2  615.56  5196.2  616.27
  5231.1  615.86  5332.2  615.59  5509.5  616.82  5615.7  618.51  5743.5  622.18
#Mann= 5 ,-1 , 0
  3634.2     .05       0  4973.8      .1       0  5003.3     .07       0
  5009.3      .1       0  5231.1     .05       0
Bank Sta=5003.3,5009.3
XS Rating Curve= 0 ,0
Exp/Cntr=0.3,0.1

Type RM Length L Ch R = 1 ,240     ,173,173,173
BEGIN DESCRIPTION:
Mapping XS c786f794
END DESCRIPTION:
XS GIS Cut Line= 4
      2002565.31     13564434.58      2001449.86     13563874.68
      2001067.92     13564074.34      2000912.01     13564931.82
#Sta/Elev= 30
  3589.7   619.6  3634.8  618.64  3836.2  618.31  3977.5  616.62  4273.4  615.03
  4759.2  613.53  4798.3  614.16  4915.3  613.43  4944.8  614.08  5000.6  612.44
  5001.1  611.64  5006.1  611.64  5006.6  612.44  5025.7  614.16  5146.9  614.72
  5152.5  615.83    5169  614.83  5174.6  615.86    5191  614.99  5196.7  616.11
  5235.2  615.43  5262.9  616.64    5309  616.66  5314.1  615.61  5367.5  615.71
  5462.5  614.18  5756.2   615.4  5889.4  617.14  5960.6   619.3  6140.3  622.91
#Mann= 3 ,-1 , 0
  3589.7     .05       0  5000.6    .035       0  5006.6     .05       0
Bank Sta=5000.6,5006.6
XS Rating Curve= 0 ,0
Exp/Cntr=0.3,0.1

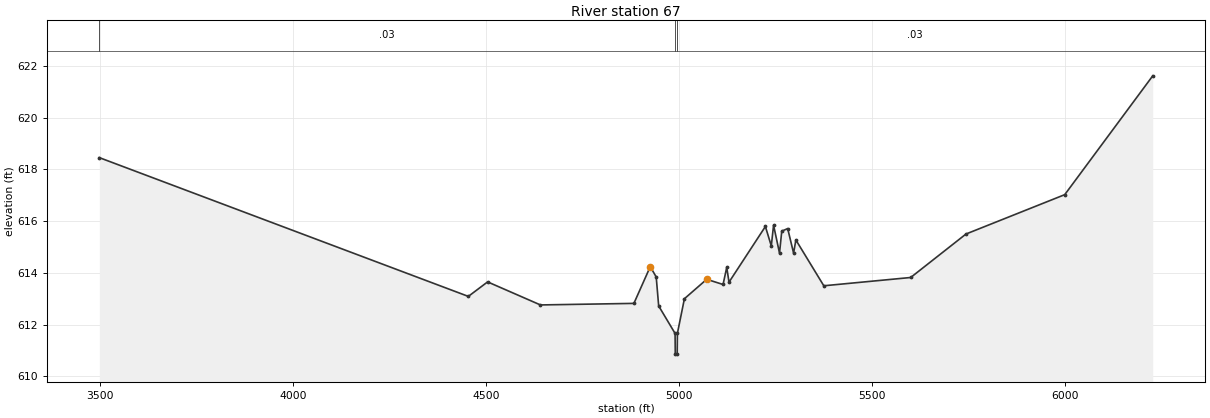
Type RM Length L Ch R = 1 ,67      ,0,0,0
BEGIN DESCRIPTION:
UNT 071 in HW 1.0
END DESCRIPTION:
XS GIS Cut Line= 4
      2002508.86      13564373.8      2001484.58     13563657.67
      2000998.47     13563961.49       2000804.2     13564847.81
#Sta/Elev= 30
  3498.1  618.45  4454.5  613.09  4504.5  613.65  4641.4  612.76  4883.7  612.82
  4926.1  614.24  4941.5  613.84  4947.9  612.72  4990.4  611.66  4990.9  610.86
  4995.9  610.86  4996.4  611.66  5014.6     613  5072.4  613.75  5114.8  613.55
  5124.3  614.21  5130.2  613.64  5224.5  615.79  5239.8  615.04  5245.7  615.84
  5261.1  614.76  5266.9  615.61  5282.3  615.71  5297.6  614.76  5303.5  615.27
  5375.9   613.5  5601.1  613.82  5744.5   615.5  6000.4  617.02  6228.5  621.61
#Mann= 3 ,-1 , 0
  3498.1     .03       0  4990.4     .02       0  4996.4     .03       0
Bank Sta=4926.1,5072.4
XS Rating Curve= 0 ,0
Exp/Cntr=0.3,0.1
LCMann Table=0

Chan Stop Cuts=-1
Use User Specified Reach Order=0
Composite Channel Slope=5