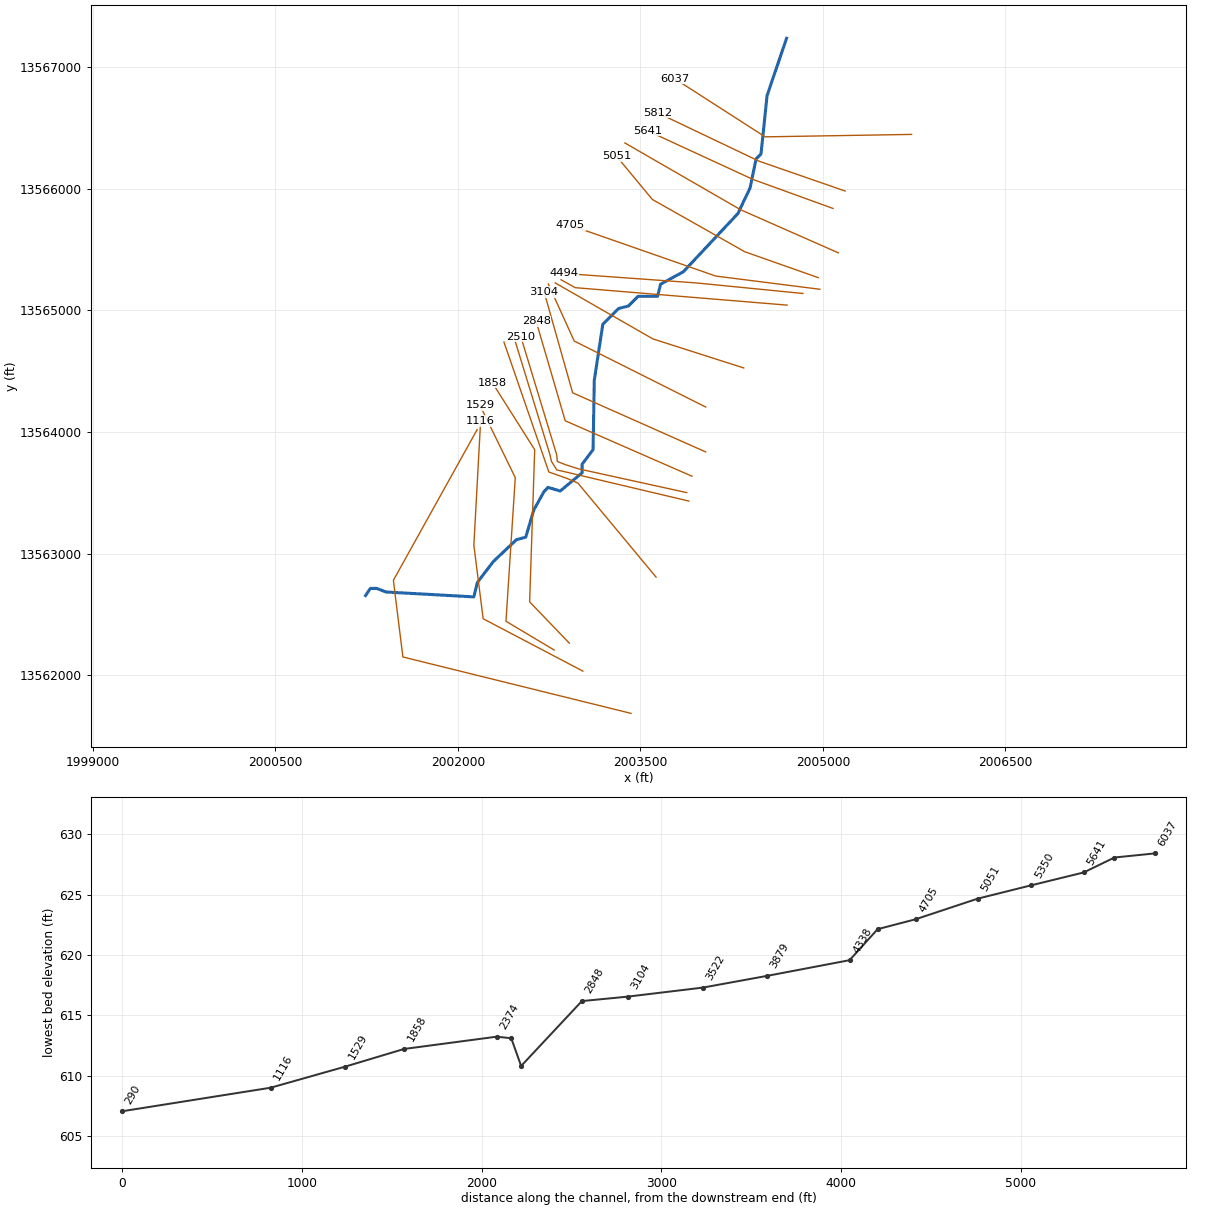
--- UNT 072 in HW.prj (project) ---

Proj Title=UNT 072 in HW Base Level Engineering
Current Plan=p01
Default Exp/Contr=0.3,0.1
English Units
Geom File=g01
Flow File=f01
Plan File=p01
BEGIN DESCRIPTION:
UNT 072 in HW
END DESCRIPTION:

--- UNT 072 in HW.p01 (plan) ---

Plan Title=Multiple Run
Short Identifier=Multiple
Geom File=g01
Flow File=f01
Subcritical Flow
K Sum by GR= 0
Std Step Tol= 0.01
Critical Tol= 0.01
Num of Std Step Trials= 20
Max Error Tol= 0.3
Flow Tol Ratio= 0.001
Split Flow NTrial= 30
Split Flow Tol= 0.02
Split Flow Ratio= 0.02
Log Output Level= 0
Friction Slope Method= 1
Unsteady Friction Slope Method= 2
Unsteady Bridges Friction Slope Method= 1
Parabolic Critical Depth
Global Vel Dist=  1 , 1 , 1
Global Log Level= 0
CheckData=True
Encroach Param= -1, 0, 0, 0
BEGIN DESCRIPTION:
Multiple Run
END DESCRIPTION:

--- UNT 072 in HW.f01 (steady flow) ---

Flow Title=Multiple
Number of Profiles=7
Profile Names=10-year,25-year,50-year,1pct_min,100-year,1pct_plu,500-year
River Rch & RM= UNT 072 in HW,Reach-1,6037
     452     627     770     469     935    1866    1385
River Rch & RM= UNT 072 in HW,Reach-1,2510
     650     919    1145     705    1406    2806    2133
Boundary for River Rch & Prof#=UNT 072 in HW,Reach-1,1
Up Type=0
Dn Type=3
Dn Slope=0.005
Boundary for River Rch & Prof#=UNT 072 in HW,Reach-1,2
Up Type=0
Dn Type=3
Dn Slope=0.005
Boundary for River Rch & Prof#=UNT 072 in HW,Reach-1,3
Up Type=0
Dn Type=3
Dn Slope=0.005
Boundary for River Rch & Prof#=UNT 072 in HW,Reach-1,4
Up Type=0
Dn Type=3
Dn Slope=0.005
Boundary for River Rch & Prof#=UNT 072 in HW,Reach-1,5
Up Type=0
Dn Type=3
Dn Slope=0.005
Boundary for River Rch & Prof#=UNT 072 in HW,Reach-1,6
Up Type=0
Dn Type=3
Dn Slope=0.005
Boundary for River Rch & Prof#=UNT 072 in HW,Reach-1,7
Up Type=0
Dn Type=3
Dn Slope=0.005

--- UNT 072 in HW.g01 (geometry) ---

Geom Title=Existing Conditions

River Reach=UNT 072 in HW,Reach-1
Reach XY= 30
      2004700.80     13567234.54      2004540.80     13566764.54
      2004490.80     13566284.54      2004450.80     13566244.54
      2004400.80     13566004.54      2004300.80     13565794.54
      2003852.40     13565316.14      2003665.45     13565214.03
      2003640.80     13565114.54      2003480.80     13565114.54
      2003400.80     13565034.54      2003320.80     13565014.54
      2003190.80     13564884.54      2003120.80     13564424.54
      2003110.80     13563854.54      2003020.80     13563734.54
      2003020.80     13563664.54      2002840.80     13563514.54
      2002740.80     13563544.54      2002706.35     13563507.65
      2002622.40     13563356.14      2002557.70     13563135.47
      2002480.80     13563114.54      2002290.80     13562934.54
      2002160.80     13562764.54      2002130.80     13562644.54
      2001410.80     13562684.54      2001330.80     13562714.54
      2001280.80     13562714.54      2001240.80     13562654.54

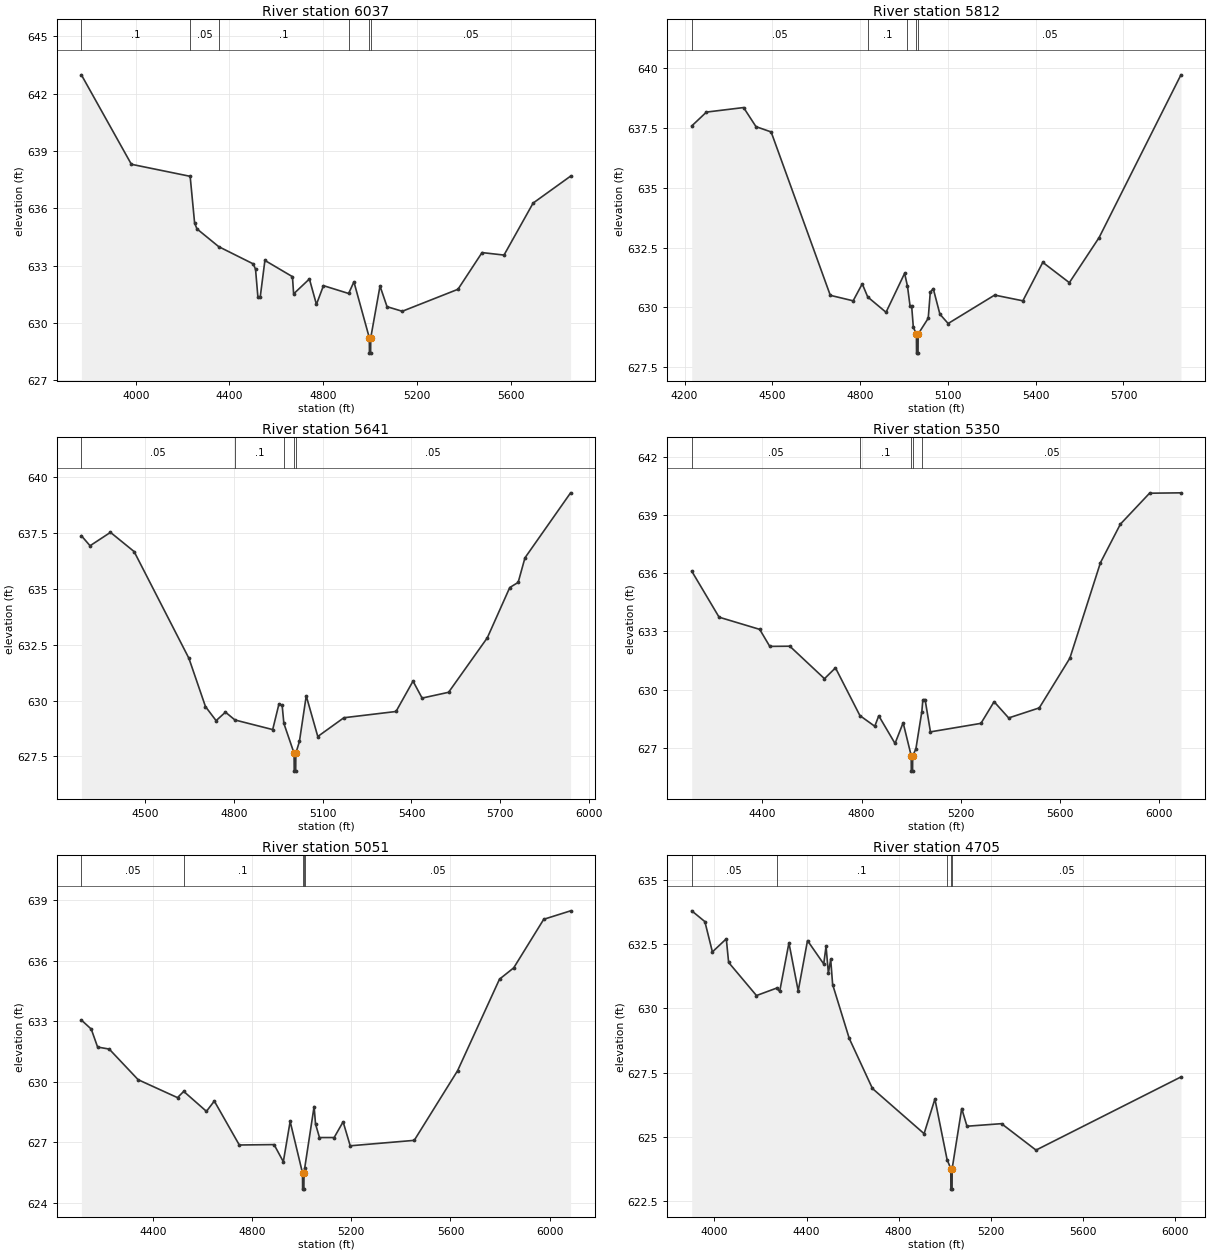
Type RM Length L Ch R = 1,6037,225,225,225
BEGIN DESCRIPTION:
UNT 072 in HW 8.0
END DESCRIPTION:
XS GIS Cut Line= 3
      2005728.37     13566445.06      2004525.00     13566425.00
      2003780.48     13566903.39
#Sta/Elev= 30
  3767.7  642.98  3981.1  638.30  4232.1  637.67  4251.1  635.23  4261.1  634.92
  4354.1  633.99  4501.2  633.09  4511.2  632.81  4521.2  631.37  4531.2  631.35
  4551.2  633.27  4668.8  632.42  4673.8  631.52  4741.2  632.30  4771.2  630.97
  4801.2  631.95  4908.7  631.54  4931.2  632.15  4997.0  629.22  4997.5  628.42
  5002.5  628.42  5003.0  629.22  5042.6  631.93  5072.6  630.85  5137.6  630.61
  5375.4  631.76  5478.2  633.68  5572.0  633.55  5696.2  636.27  5856.2  637.68
#Mann=6,-1,0
  3767.7     0.1       0  4232.1    0.05       0  4354.1     0.1       0
  4908.7    0.05       0  4997.0   0.035       0  5003.0    0.05       0
Bank Sta=4997,5003
Exp/Cntr=0.3,0.1

Type RM Length L Ch R = 1,5812,171,171,171
BEGIN DESCRIPTION:
UNT 072 in HW 7.0
END DESCRIPTION:
XS GIS Cut Line= 3
      2005182.39     13565979.78      2004475.00     13566225.00
      2003641.58     13566622.15
#Sta/Elev= 30
  4224.5  637.59  4274.7  638.17  4401.7  638.36  4444.1  637.56  4495.8  637.34
  4698.0  630.50  4776.1  630.27  4807.2  630.98  4826.0  630.43  4888.5  629.79
  4952.0  631.42  4961.8  630.88  4970.5  630.06  4976.0  630.06  4981.8  629.16
  4992.3  628.88  4992.8  628.08  4997.8  628.08  4998.3  628.88  5032.7  629.54
  5039.7  630.63  5049.9  630.78  5072.6  629.71  5100.8  629.32  5259.7  630.51
  5356.1  630.27  5424.2  631.88  5515.0  631.03  5616.8  632.92  5896.4  639.73
#Mann=5,-1,0
  4224.5    0.05       0  4826.0     0.1       0  4961.8    0.05       0
  4992.3   0.035       0  4998.3    0.05       0
Bank Sta=4992.3,4998.3
Exp/Cntr=0.3,0.1

Type RM Length L Ch R = 1,5641,291,291,291
BEGIN DESCRIPTION:
UNT 072 in HW 6.0
END DESCRIPTION:
XS GIS Cut Line= 3
      2005082.56     13565836.55      2004425.00     13566075.00
      2003559.56     13566474.37
#Sta/Elev= 30
  4284.9  637.38  4314.2  636.93  4383.2  637.53  4463.1  636.67  4648.2  631.89
  4704.1  629.73  4740.0  629.10  4771.6  629.48  4803.7  629.13  4931.2  628.70
  4952.4  629.85  4963.1  629.79  4968.9  628.98  5003.4  627.64  5003.9  626.84
  5008.9  626.84  5009.4  627.64  5021.5  628.17  5044.5  630.21  5083.5  628.39
  5171.6  629.23  5347.8  629.51  5405.2  630.87  5435.9  630.11  5525.4  630.37
  5656.2  632.81  5732.0  635.06  5760.4  635.29  5783.4  636.39  5937.5  639.30
#Mann=5,-1,0
  4284.9    0.05       0  4803.7     0.1       0  4968.9    0.05       0
  5003.4   0.035       0  5009.4    0.05       0
Bank Sta=5003.4,5009.4
Exp/Cntr=0.3,0.1

Type RM Length L Ch R = 1,5350,299,299,299
BEGIN DESCRIPTION:
UNT 072 in HW 5.0
END DESCRIPTION:
XS GIS Cut Line= 3
      2005125.99     13565471.96      2004325.00     13565825.00
      2003372.50     13566374.74
#Sta/Elev= 30
  4114.6  636.12  4225.0  633.74  4388.9  633.11  4429.6  632.23  4510.5  632.24
  4650.5  630.56  4694.9  631.12  4793.6  628.65  4853.5  628.10  4869.7  628.64
  4935.3  627.21  4968.1  628.28  5000.6  626.58  5001.1  625.78  5006.1  625.78
  5006.6  626.58  5019.4  626.92  5043.6  628.86  5047.7  629.47  5056.7  629.48
  5078.3  627.81  5282.2  628.25  5335.3  629.37  5394.1  628.53  5517.7  629.05
  5641.2  631.62  5764.7  636.56  5845.1  638.55  5962.9  640.15  6089.7  640.17
#Mann=5,-1,0
  4114.6    0.05       0  4793.6     0.1       0  5000.6    0.07       0
  5006.6     0.1       0  5043.6    0.05       0
Bank Sta=5000.6,5006.6
Exp/Cntr=0.3,0.1

Type RM Length L Ch R = 1,5051,346,346,346
BEGIN DESCRIPTION:
Mapping XS 2730db1f
END DESCRIPTION:
XS GIS Cut Line= 4
      2004961.05     13565267.97      2004357.72     13565480.65
      2003598.17     13565910.34      2003303.06     13566266.22
#Sta/Elev= 30
  4110.2  633.06  4150.1  632.61  4175.7  631.72  4222.6  631.62  4339.3  630.10
  4498.3  629.21  4523.3  629.52  4615.0  628.53  4646.8  629.04  4747.7  626.86
  4888.0  626.88  4925.4  626.03  4952.9  628.03  5002.8  625.47  5003.3  624.67
  5008.3  624.67  5008.8  625.47  5011.6  625.71  5049.6  628.77  5055.4  627.90
  5071.3  627.23  5130.5  627.23  5166.7  628.01  5195.4  626.82  5453.8  627.09
  5628.9  630.55  5798.0  635.09  5855.3  635.65  5976.5  638.06  6084.9  638.48
#Mann=5,-1,0
  4110.2    0.05       0  4523.3     0.1       0  5002.8    0.07       0
  5008.8     0.1       0  5011.6    0.05       0
Bank Sta=5002.8,5008.8
Exp/Cntr=0.3,0.1

Type RM Length L Ch R = 1,4705,211,211,211
BEGIN DESCRIPTION:
UNT 072 in HW 4.0
END DESCRIPTION:
XS GIS Cut Line= 3
      2004974.05     13565172.49      2004119.01     13565281.00
      2002925.44     13565697.66
#Sta/Elev= 30
  3901.2  633.80  3958.3  633.38  3991.0  632.20  4051.4  632.71  4061.5  631.79
  4182.5  630.50  4270.1  630.79  4283.4  630.66  4323.6  632.55  4363.9  630.68
  4404.3  632.64  4474.8  631.73  4484.9  632.42  4495.0  631.37  4505.1  631.91
  4513.5  630.93  4585.7  628.83  4686.5  626.88  4911.0  625.12  4958.0  626.47
  5010.9  624.11  5027.0  623.76  5027.5  622.96  5032.5  622.96  5033.0  623.76
  5074.5  626.10  5097.4  625.41  5247.4  625.51  5397.4  624.48  6027.3  627.33
#Mann=5,-1,0
  3901.2    0.05       0  4270.1     0.1       0  5010.9    0.05       0
  5027.0    0.07       0  5033.0    0.05       0
Bank Sta=5027,5033
Exp/Cntr=0.3,0.1

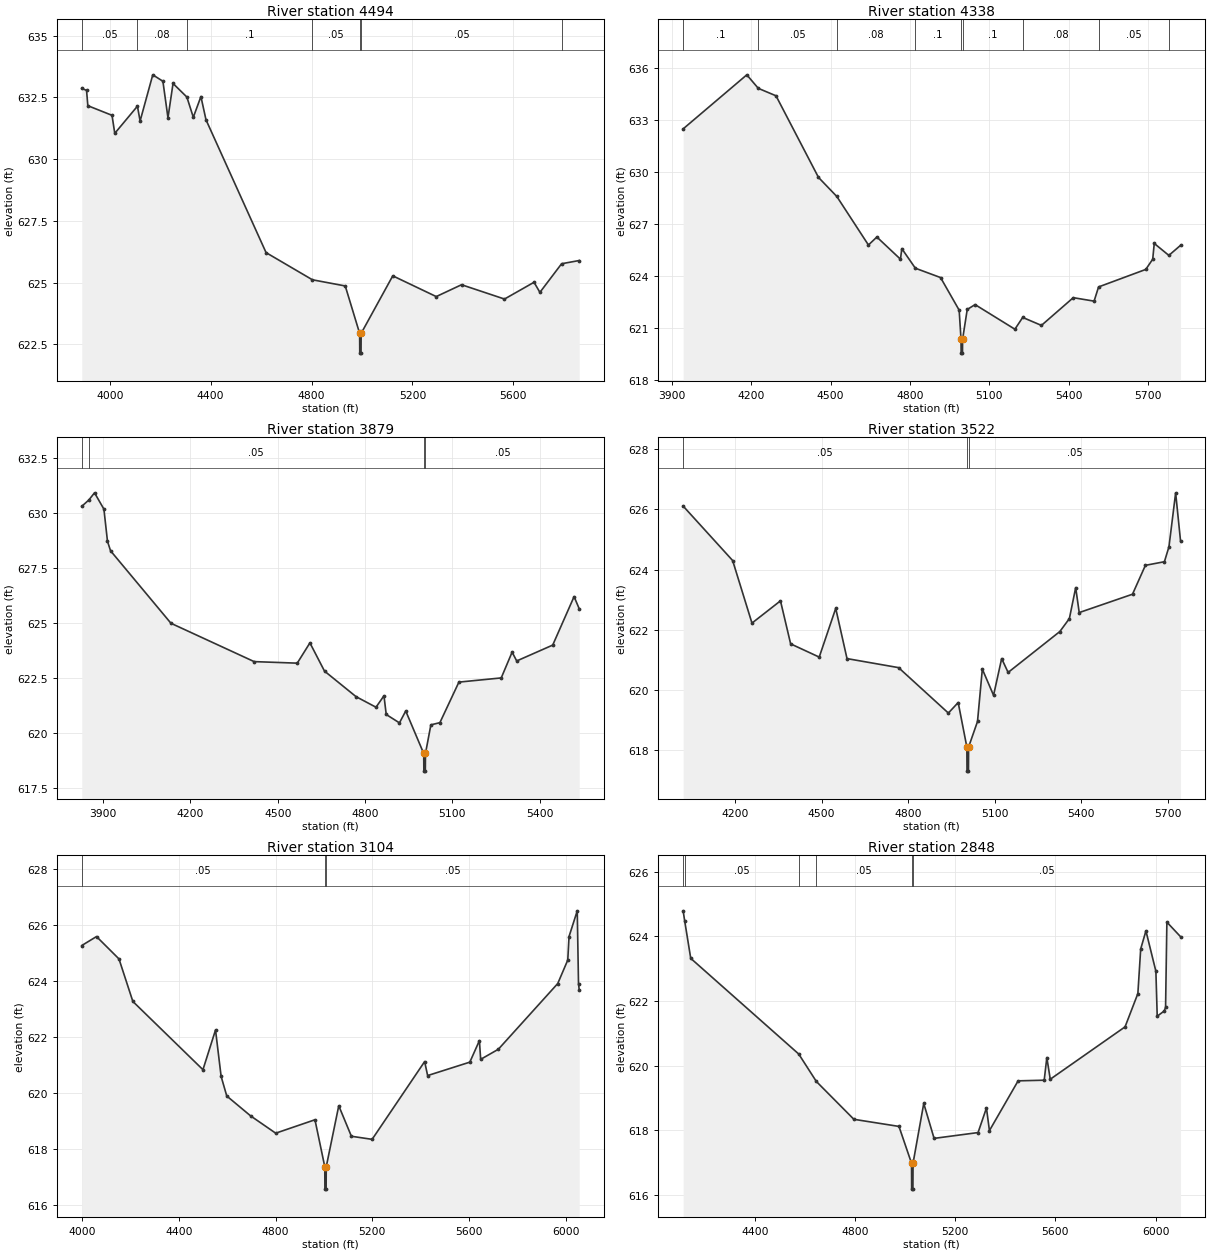
Type RM Length L Ch R = 1,4494,156,156,156
BEGIN DESCRIPTION:
UNT 072 in HW 3.0
END DESCRIPTION:
XS GIS Cut Line= 3
      2004835.18     13565137.77      2003958.42     13565224.58
      2002869.46     13565302.67
#Sta/Elev= 30
  3888.8  632.86  3907.7  632.78  3912.8  632.16  4008.7  631.77  4019.6  631.04
  4109.5  632.14  4120.1  631.54  4170.3  633.41  4210.5  633.15  4230.6  631.67
  4250.7  633.06  4305.6  632.51  4331.1  631.69  4361.3  632.53  4381.4  631.59
  4619.7  626.21  4803.5  625.11  4933.7  624.86  4990.8  622.94  4991.3  622.14
  4996.3  622.14  4996.8  622.94  5122.2  625.27  5294.6  624.43  5394.9  624.91
  5565.3  624.33  5682.5  625.01  5705.7  624.60  5791.8  625.76  5861.6  625.89
#Mann=7,-1,0
  3888.8    0.05       0  4109.5    0.08       0  4305.6     0.1       0
  4803.5    0.05       0  4990.8    0.04       0  4996.8    0.05       0
  5791.8    0.08       0
Bank Sta=4990.8,4996.8
Exp/Cntr=0.3,0.1

Type RM Length L Ch R = 1,4338,459,459,459
BEGIN DESCRIPTION:
Mapping XS 2f0f81c6
END DESCRIPTION:
XS GIS Cut Line= 3
      2004704.93     13565042.29      2002964.49     13565185.52
      2002847.29     13565250.63
#Sta/Elev= 30
  3942.3  632.51  4183.0  635.63  4226.5  634.85  4293.4  634.42  4454.0  629.71
  4523.3  628.61  4642.8  625.81  4674.7  626.27  4763.9  624.99  4769.0  625.60
  4820.2  624.47  4915.5  623.93  4985.8  622.05  4992.8  620.37  4993.3  619.57
  4998.3  619.57  4998.8  620.37  5016.3  622.09  5046.0  622.37  5196.5  620.95
  5226.0  621.63  5296.8  621.17  5417.2  622.77  5495.9  622.57  5512.8  623.39
  5691.2  624.40  5717.5  624.99  5723.3  625.90  5778.5  625.21  5822.7  625.79
#Mann=9,-1,0
  3942.3     0.1       0  4226.5    0.05       0  4523.3    0.08       0
  4820.2     0.1       0  4992.8    0.07       0  4998.8     0.1       0
  5226.0    0.08       0  5512.8    0.05       0  5778.5    0.08       0
Bank Sta=4992.8,4998.8
Exp/Cntr=0.3,0.1

Type RM Length L Ch R = 1,3879,357,357,357
BEGIN DESCRIPTION:
UNT 072 in HW 2.0
END DESCRIPTION:
XS GIS Cut Line= 3
      2004349.07     13564525.79      2003602.51     13564764.51
      2002799.74     13565224.48
#Sta/Elev= 30
  3826.6  630.29  3850.5  630.57  3870.4  630.90  3902.6  630.16  3914.9  628.70
  3925.4  628.27  4133.0  624.98  4418.8  623.24  4566.9  623.17  4610.4  624.09
  4660.5  622.81  4768.9  621.65  4837.5  621.17  4864.8  621.69  4872.6  620.84
  4918.0  620.46  4939.6  621.00  5001.4  619.07  5001.9  618.27  5006.9  618.27
  5007.4  619.07  5026.0  620.37  5057.0  620.47  5122.3  622.31  5267.7  622.50
  5305.1  623.67  5320.9  623.27  5444.6  623.99  5518.0  626.19  5535.6  625.64
#Mann=4,-1,0
  3826.6     0.1       0  3850.5    0.05       0  5001.4   0.035       0
  5007.4    0.05       0
Bank Sta=5001.4,5007.4
Exp/Cntr=0.3,0.1

Type RM Length L Ch R = 1,3522,418,418,418
BEGIN DESCRIPTION:
Mapping XS 8076bc40
END DESCRIPTION:
XS GIS Cut Line= 3
      2004036.54     13564204.61      2002955.81     13564747.15
      2002743.14     13565215.89
#Sta/Elev= 30
  4020.1  626.11  4191.7  624.30  4258.7  622.22  4357.5  622.96  4392.7  621.53
  4491.8  621.09  4549.0  622.71  4588.1  621.04  4766.8  620.74  4939.4  619.23
  4973.4  619.58  5003.5  618.10  5004.0  617.30  5009.0  617.30  5009.5  618.10
  5040.4  618.95  5057.1  620.69  5096.0  619.82  5124.1  621.04  5146.5  620.58
  5325.8  621.94  5358.8  622.37  5380.7  623.40  5392.9  622.57  5577.6  623.18
  5622.3  624.14  5688.2  624.26  5704.0  624.76  5727.1  626.55  5744.1  624.95
#Mann=3,-1,0
  4020.1    0.05       0  5003.5   0.035       0  5009.5    0.05       0
Bank Sta=5003.5,5009.5
Exp/Cntr=0.3,0.1

Type RM Length L Ch R = 1,3104,256,256,256
BEGIN DESCRIPTION:
Mapping XS 517e5d16
END DESCRIPTION:
XS GIS Cut Line= 3
      2004036.53     13563835.70      2002942.79     13564321.80
      2002708.52     13565150.42
#Sta/Elev= 30
  3997.9  625.26  4058.8  625.58  4151.8  624.78  4209.2  623.26  4499.2  620.82
  4551.2  622.24  4574.4  620.58  4597.7  619.88  4696.2  619.17  4800.2  618.55
  4962.6  619.03  5003.3  617.35  5003.8  616.55  5008.8  616.55  5009.3  617.35
  5061.1  619.53  5113.4  618.44  5199.1  618.33  5416.4  621.11  5428.8  620.61
  5603.4  621.09  5643.0  621.86  5648.2  621.19  5721.3  621.55  5967.1  623.90
  6008.6  624.74  6013.8  625.58  6047.8  626.50  6053.0  623.90  6055.9  623.68
#Mann=3,-1,0
  3997.9    0.05       0  5003.3   0.035       0  5009.3    0.05       0
Bank Sta=5003.3,5009.3
Exp/Cntr=0.3,0.1

Type RM Length L Ch R = 1,2848,338,338,338
BEGIN DESCRIPTION:
Mapping XS 0d45e4c4
END DESCRIPTION:
XS GIS Cut Line= 3
      2003923.70     13563636.03      2002882.03     13564091.77
      2002643.31     13564907.76
#Sta/Elev= 30
  4112.7  624.79  4119.1  624.47  4143.1  623.32  4574.5  620.36  4645.0  619.51
  4794.9  618.34  4975.0  618.12  5025.2  616.98  5025.7  616.18  5030.7  616.18
  5031.2  616.98  5074.0  618.83  5115.3  617.75  5291.0  617.93  5324.5  618.69
  5336.4  617.99  5451.0  619.53  5555.2  619.55  5565.7  620.25  5579.4  619.58
  5878.2  621.20  5929.4  622.23  5940.7  623.61  5961.6  624.17  6001.4  622.92
  6006.7  621.53  6034.5  621.69  6040.1  621.80  6045.3  624.44  6099.9  623.99
#Mann=6,-1,0
  4112.7     0.1       0  4119.1    0.05       0  4574.5     0.1       0
  4645.0    0.05       0  5025.2   0.035       0  5031.2    0.05       0
Bank Sta=5025.2,5031.2
Exp/Cntr=0.3,0.1

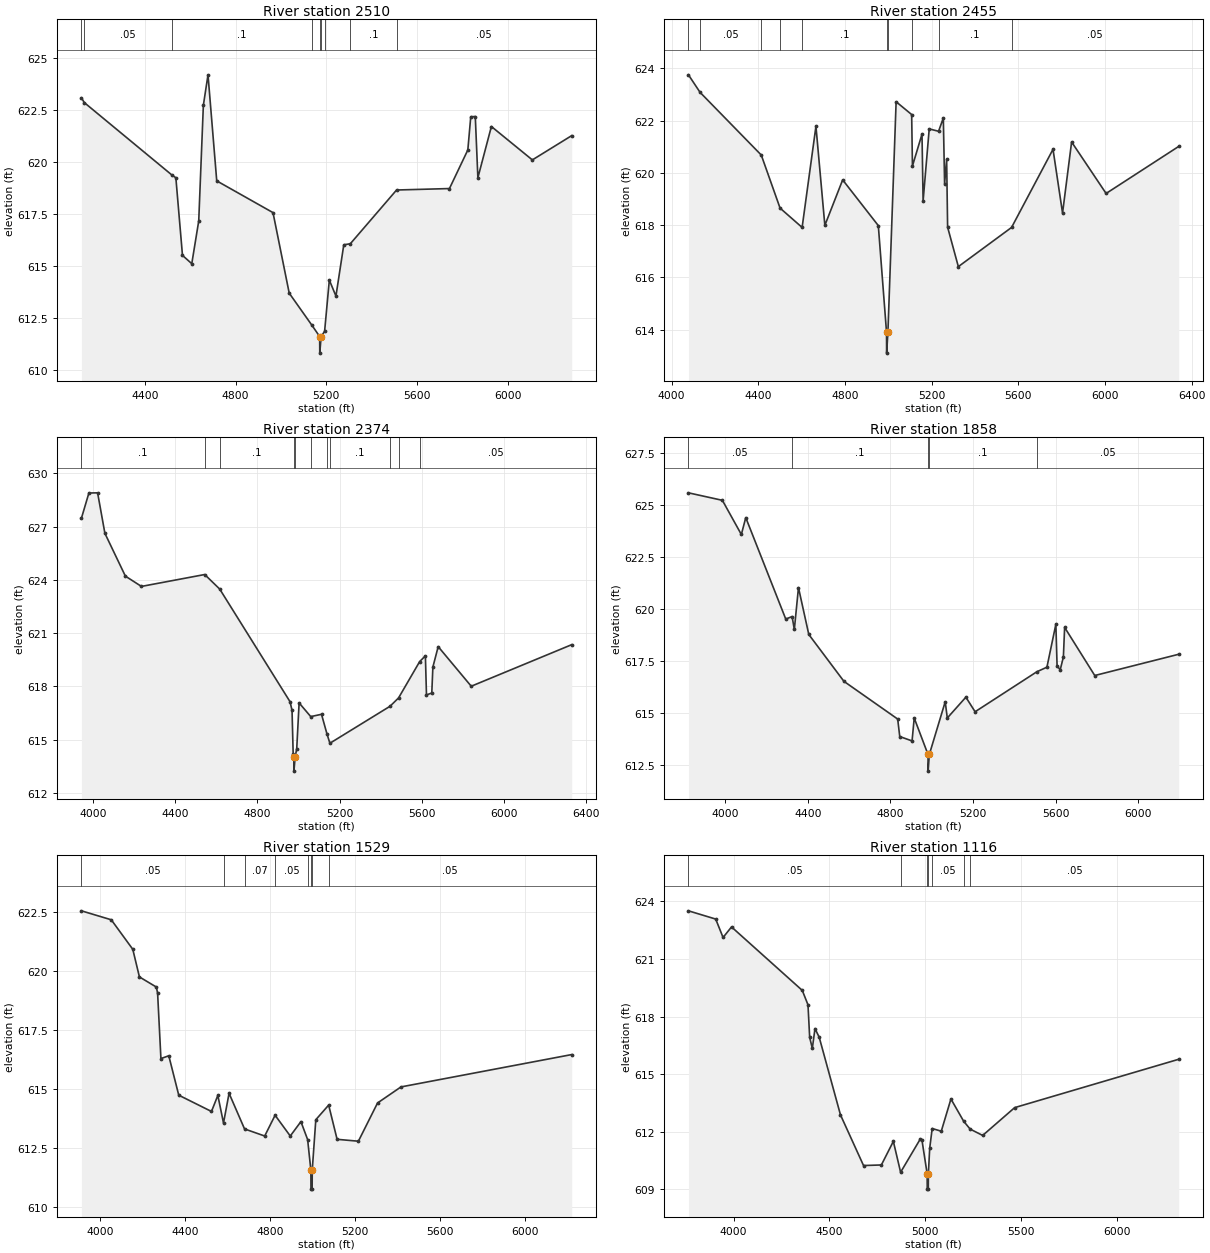
Type RM Length L Ch R = 1,2510,55,55,55
BEGIN DESCRIPTION:
Mapping XS e5a01d58
END DESCRIPTION:
XS GIS Cut Line= 6
      2003880.33     13563501.48      2002990.54     13563696.80
      2002882.03     13563731.52      2002816.92     13563757.56
      2002812.58     13563809.65      2002517.71     13564780.98
#Sta/Elev= 30
  4120.0  623.10  4132.9  622.87  4518.2  619.39  4536.5  619.25  4565.7  615.51
  4606.7  615.11  4637.4  617.17  4657.8  622.74  4678.3  624.21  4716.8  619.10
  4965.0  617.57  5036.5  613.69  5136.8  612.14  5170.8  611.60  5171.3  610.80
  5177.2  611.60  5192.6  611.85  5213.4  614.32  5242.6  613.55  5277.2  616.02
  5306.0  616.07  5510.0  618.66  5743.2  618.73  5824.3  620.59  5837.2  622.19
  5857.2  622.20  5868.6  619.25  5928.2  621.72  6108.9  620.11  6282.4  621.28
#Mann=9,-1,0
  4120.0     0.1       0  4132.9    0.05       0  4518.2     0.1       0
  5136.8    0.12       0  5170.8    0.07       0  5177.2    0.12       0
  5192.6    0.07       0  5306.0     0.1       0  5510.0    0.05       0
Bank Sta=5170.8,5177.2
Exp/Cntr=0.3,0.1

Type RM Length L Ch R = 1,2455,81,81,81
BEGIN DESCRIPTION:
Mapping XS 4822becb
END DESCRIPTION:
XS GIS Cut Line= 6
      2003897.66     13563432.04      2002942.79     13563657.74
      2002812.58     13563688.12      2002769.18     13563757.56
      2002756.16     13563813.99      2002461.03     13564777.52
#Sta/Elev= 30
  4078.0  623.75  4131.6  623.08  4414.1  620.68  4500.8  618.65  4602.6  617.91
  4666.4  621.78  4707.5  617.99  4789.7  619.73  4954.2  617.98  4992.1  613.90
  4992.6  613.10  4998.5  613.90  5036.4  622.72  5108.1  622.23  5111.7  620.26
  5155.8  621.48  5160.9  618.92  5189.1  621.68  5232.4  621.59  5254.2  622.10
  5260.1  619.58  5269.5  620.51  5274.0  617.92  5323.5  616.41  5569.2  617.91
  5760.4  620.90  5804.4  618.46  5846.2  621.18  6005.4  619.21  6340.4  621.01
#Mann=10,-1,0
  4078.0     0.1       0  4131.6    0.05       0  4414.1     0.1       0
  4500.8    0.05       0  4602.6     0.1       0  4992.1    0.07       0
  4998.5     0.1       0  5111.7    0.12       0  5232.4     0.1       0
  5569.2    0.05       0
Bank Sta=4992.1,4998.5
Exp/Cntr=0.3,0.1

Type RM Length L Ch R = 1,2374,516,516,516
BEGIN DESCRIPTION:
Mapping XS dc808544
END DESCRIPTION:
XS GIS Cut Line= 5
      2003628.56     13562807.04      2002986.19     13563579.61
      2002895.05     13563618.68      2002747.48     13563670.76
      2002378.57     13564738.42
#Sta/Elev= 30
  3941.7  627.47  3978.1  628.89  4020.6  628.90  4056.1  626.62  4156.0  624.21
  4234.2  623.63  4542.7  624.30  4615.9  623.48  4958.6  617.14  4968.4  616.65
  4973.9  614.22  4977.2  614.03  4977.7  613.23  4983.6  614.03  4991.3  614.49
  5002.9  617.07  5059.6  616.30  5112.1  616.43  5138.8  615.32  5153.0  614.80
  5445.8  616.88  5487.6  617.35  5590.7  619.40  5618.5  619.72  5623.8  617.52
  5649.7  617.63  5655.0  619.09  5680.9  620.24  5842.0  618.01  6331.7  620.35
#Mann=11,-1,0
  3941.7     0.1       0  4542.7    0.05       0  4615.9     0.1       0
  4977.2    0.07       0  4983.6     0.1       0  5059.6    0.07       0
  5138.8    0.12       0  5153.0     0.1       0  5445.8    0.05       0
  5487.6    0.08       0  5590.7    0.05       0
Bank Sta=4977.2,4983.6
Exp/Cntr=0.3,0.1

Type RM Length L Ch R = 1,1858,329,329,329
BEGIN DESCRIPTION:
Mapping XS 0dfbab90
END DESCRIPTION:
XS GIS Cut Line= 4
      2002915.87     13562263.66      2002589.49     13562603.92
      2002631.16     13563853.92      2002283.22     13564404.16
#Sta/Elev= 30
  3822.0  625.57  3986.3  625.21  4078.1  623.57  4099.5  624.38  4293.1  619.51
  4323.8  619.63  4334.6  619.01  4354.6  621.02  4404.6  618.77  4574.7  616.52
  4834.9  614.71  4844.9  613.87  4904.5  613.66  4914.9  614.76  4981.7  613.01
  4982.2  612.21  4988.1  613.01  5065.0  615.54  5075.0  614.76  5165.0  615.76
  5209.6  615.06  5508.5  616.98  5557.3  617.20  5600.6  619.26  5606.5  617.25
  5621.8  617.08  5637.0  617.69  5643.0  619.11  5788.8  616.80  6195.2  617.82
#Mann=5,-1,0
  3822.0    0.05       0  4323.8     0.1       0  4981.7    0.07       0
  4988.1     0.1       0  5508.5    0.05       0
Bank Sta=4981.7,4988.1
Exp/Cntr=0.3,0.1

Type RM Length L Ch R = 1,1529,413,413,413
BEGIN DESCRIPTION:
Mapping XS 871c28d2
END DESCRIPTION:
XS GIS Cut Line= 4
      2002790.84     13562208.11      2002395.05     13562444.20
      2002471.44     13563624.75      2002180.35     13564220.79
#Sta/Elev= 30
  3912.8  622.53  4053.3  622.15  4154.5  620.90  4185.7  619.73  4265.5  619.30
  4271.3  619.04  4286.9  616.27  4323.9  616.39  4370.8  614.72  4524.8  614.03
  4554.8  614.71  4581.4  613.54  4607.6  614.80  4680.4  613.29  4775.3  612.99
  4824.2  613.87  4895.6  612.99  4945.7  613.60  4977.3  612.84  4992.6  611.54
  4993.1  610.74  4998.5  610.74  4999.0  611.54  5015.8  613.68  5076.3  614.30
  5116.0  612.85  5216.2  612.77  5306.4  614.39  5416.6  615.07  6220.0  616.44
#Mann=8,-1,0
  3912.8    0.05       0  4581.4     0.1       0  4680.4    0.07       0
  4824.2    0.05       0  4977.3     0.1       0  4992.6    0.07       0
  4999.0     0.1       0  5076.3    0.05       0
Bank Sta=4992.6,4999
Exp/Cntr=0.3,0.1

Type RM Length L Ch R = 1,1116,826,826,826
BEGIN DESCRIPTION:
Mapping XS 85fdda24
END DESCRIPTION:
XS GIS Cut Line= 4
      2003026.98     13562034.48      2002207.55     13562465.03
      2002131.16     13563069.20      2002186.72     13564090.05
#Sta/Elev= 30
  3764.5  623.51  3906.7  623.08  3945.1  622.12  3989.2  622.67  4358.3  619.36
  4388.0  618.61  4396.8  616.91  4410.6  616.34  4424.5  617.37  4446.5  616.92
  4557.5  612.87  4677.7  610.23  4770.8  610.26  4833.2  611.49  4871.1  609.88
  4972.4  611.59  4982.4  611.56  5009.5  609.80  5010.0  609.00  5015.4  609.00
  5015.9  609.80  5022.8  611.13  5035.8  612.16  5083.2  612.02  5133.6  613.70
  5199.9  612.54  5233.7  612.13  5299.1  611.80  5466.0  613.25  6321.5  615.77
#Mann=7,-1,0
  3764.5    0.05       0  4871.1     0.1       0  5009.5    0.07       0
  5015.9     0.1       0  5035.8    0.05       0  5199.9     0.1       0
  5233.7    0.05       0
Bank Sta=5009.5,5015.9
Exp/Cntr=0.3,0.1

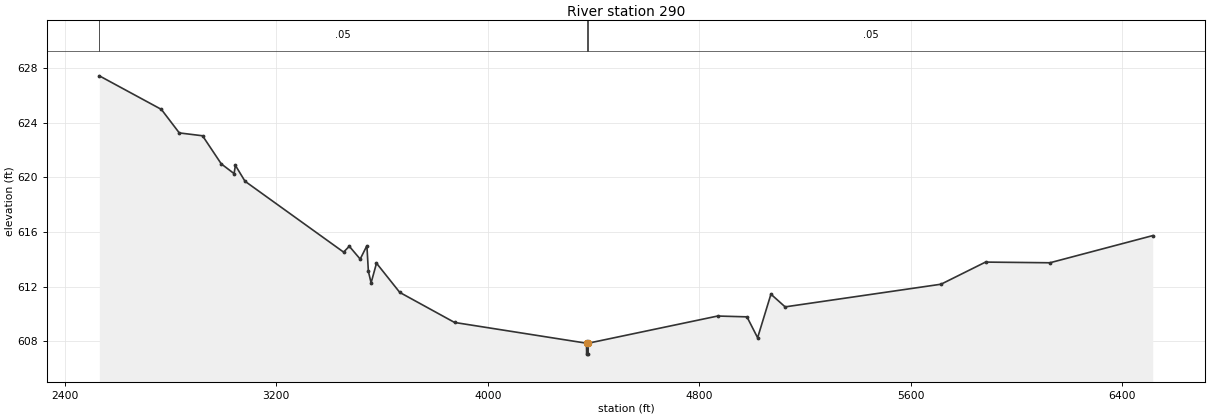
Type RM Length L Ch R = 1,290,0,0,0
BEGIN DESCRIPTION:
UNT 072 in HW 1.0
END DESCRIPTION:
XS GIS Cut Line= 4
      2003422.82     13561687.25      2001547.95     13562150.73
      2001469.83     13562780.93      2002158.77     13564020.28
#Sta/Elev= 30
  2530.8  627.43  2765.5  624.97  2833.2  623.25  2921.2  623.04  2992.1  620.98
  3040.4  620.27  3045.5  620.87  3081.8  619.71  3454.7  614.52  3476.2  614.95
  3517.4  614.01  3542.8  614.99  3548.4  613.11  3558.7  612.27  3579.1  613.71
  3667.1  611.57  3874.3  609.37  4373.4  607.85  4373.9  607.05  4379.4  607.05
  4379.9  607.85  4869.5  609.84  4980.3  609.78  5020.6  608.25  5071.0  611.44
  5124.7  610.51  5714.4  612.17  5882.6  613.79  6126.2  613.74  6515.1  615.73
#Mann=3,-1,0
  2530.8    0.05       0  4373.4   0.035       0  4379.9    0.05       0
Bank Sta=4373.4,4379.9
Exp/Cntr=0.3,0.1

Chan Stop Cuts=-1