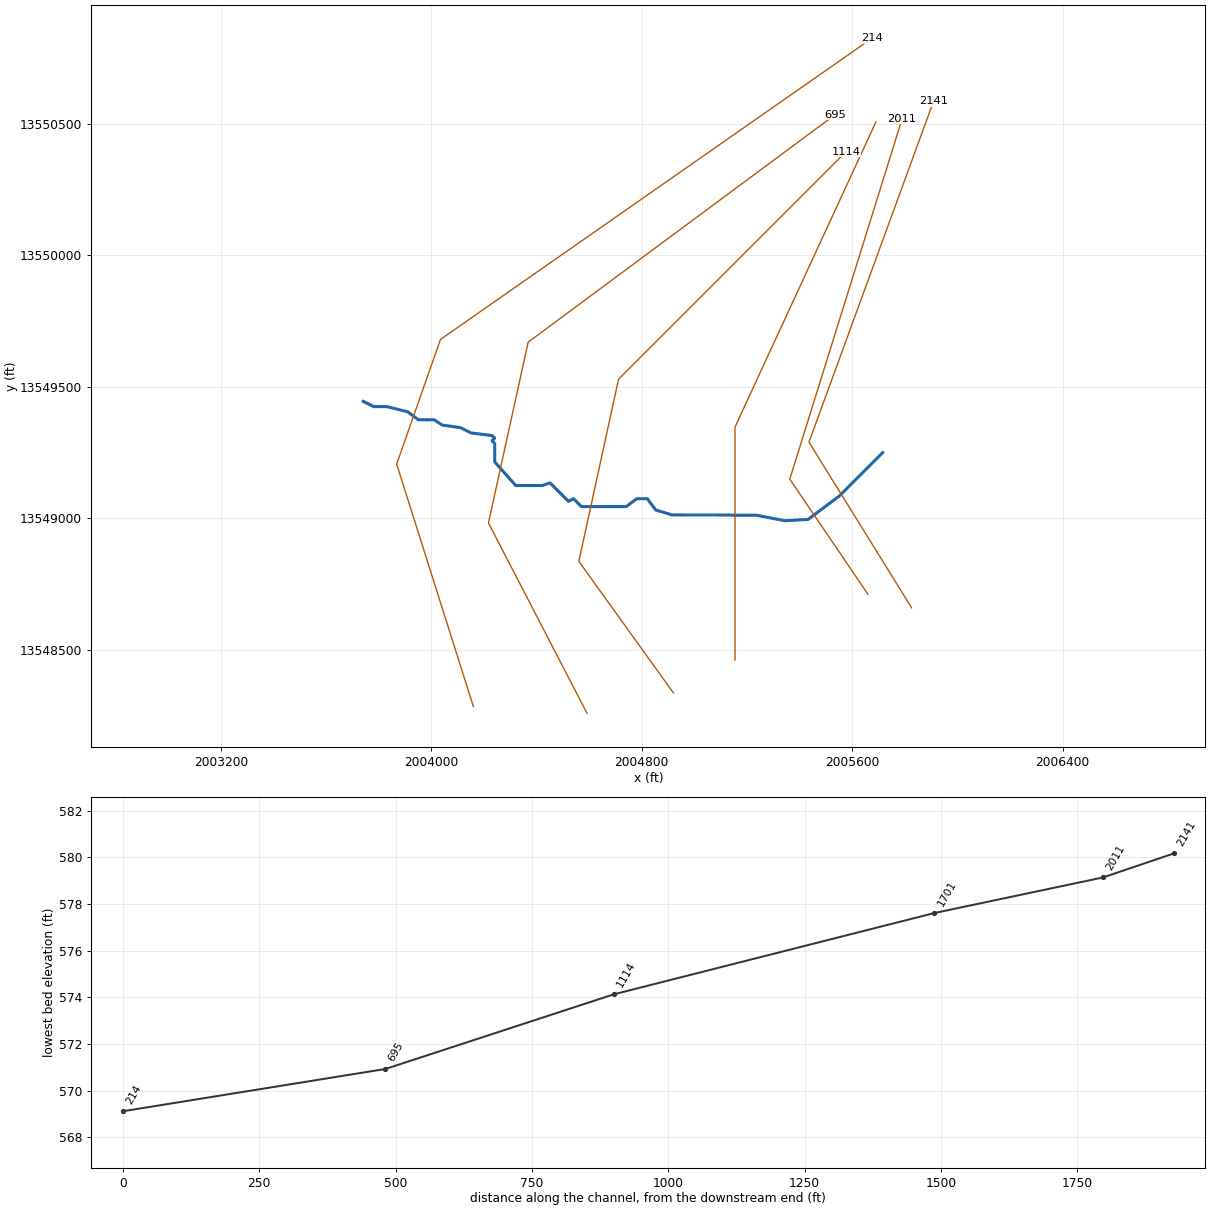
--- UNT 074 in HW.prj (project) ---

Proj Title=UNT 074 in HW Base Level Engineering
Current Plan=p01
Default Exp/Contr=0.3,0.1
English Units
Geom File=g01
Flow File=f01
Plan File=p01
BEGIN DESCRIPTION:
UNT 074 in HW
END DESCRIPTION:

--- UNT 074 in HW.p01 (plan) ---

Plan Title=Multiple Run
Short Identifier=Multiple
Geom File=g01
Flow File=f01
Subcritical Flow
K Sum by GR= 0
Std Step Tol= 0.01
Critical Tol= 0.01
Num of Std Step Trials= 20
Max Error Tol= 0.3
Flow Tol Ratio= 0.001
Split Flow NTrial= 30
Split Flow Tol= 0.02
Split Flow Ratio= 0.02
Log Output Level= 0
Friction Slope Method= 1
Unsteady Friction Slope Method= 2
Unsteady Bridges Friction Slope Method= 1
Parabolic Critical Depth
Global Vel Dist=  1 , 1 , 1
Global Log Level= 0
CheckData=True
Encroach Param= -1, 0, 0, 0
BEGIN DESCRIPTION:
Multiple Run
END DESCRIPTION:

--- UNT 074 in HW.f01 (steady flow) ---

Flow Title=Multiple
Number of Profiles=7
Profile Names=10-year,25-year,50-year,1pct_min,100-year,1pct_plu,500-year
River Rch & RM= UNT 074 in HW,Reach-1,2141
     444     620     766     469     937    1869    1409
Boundary for River Rch & Prof#=UNT 074 in HW,Reach-1,1
Up Type=0
Dn Type=3
Dn Slope=0.005
Boundary for River Rch & Prof#=UNT 074 in HW,Reach-1,2
Up Type=0
Dn Type=3
Dn Slope=0.005
Boundary for River Rch & Prof#=UNT 074 in HW,Reach-1,3
Up Type=0
Dn Type=3
Dn Slope=0.005
Boundary for River Rch & Prof#=UNT 074 in HW,Reach-1,4
Up Type=0
Dn Type=3
Dn Slope=0.005
Boundary for River Rch & Prof#=UNT 074 in HW,Reach-1,5
Up Type=0
Dn Type=3
Dn Slope=0.005
Boundary for River Rch & Prof#=UNT 074 in HW,Reach-1,6
Up Type=0
Dn Type=3
Dn Slope=0.005
Boundary for River Rch & Prof#=UNT 074 in HW,Reach-1,7
Up Type=0
Dn Type=3
Dn Slope=0.005

--- UNT 074 in HW.g01 (geometry) ---

Geom Title=Existing Conditions

River Reach=UNT 074 in HW,Reach-1
Reach XY= 30
      2005715.80     13549249.54      2005550.80     13549084.54
      2005431.78     13548995.64      2005343.58     13548990.78
      2005236.64     13549011.62      2004914.41     13549013.01
      2004852.61     13549031.76      2004820.80     13549074.54
      2004780.80     13549074.54      2004740.80     13549044.54
      2004570.80     13549044.54      2004540.80     13549074.54
      2004520.80     13549064.54      2004450.80     13549134.54
      2004420.80     13549124.54      2004320.80     13549124.54
      2004240.80     13549214.54      2004240.80     13549284.54
      2004230.80     13549294.54      2004240.80     13549304.54
      2004230.80     13549314.54      2004150.80     13549324.54
      2004110.80     13549344.54      2004040.80     13549354.54
      2004010.80     13549374.54      2003950.80     13549374.54
      2003910.80     13549404.54      2003830.80     13549424.54
      2003780.80     13549424.54      2003740.80     13549444.54

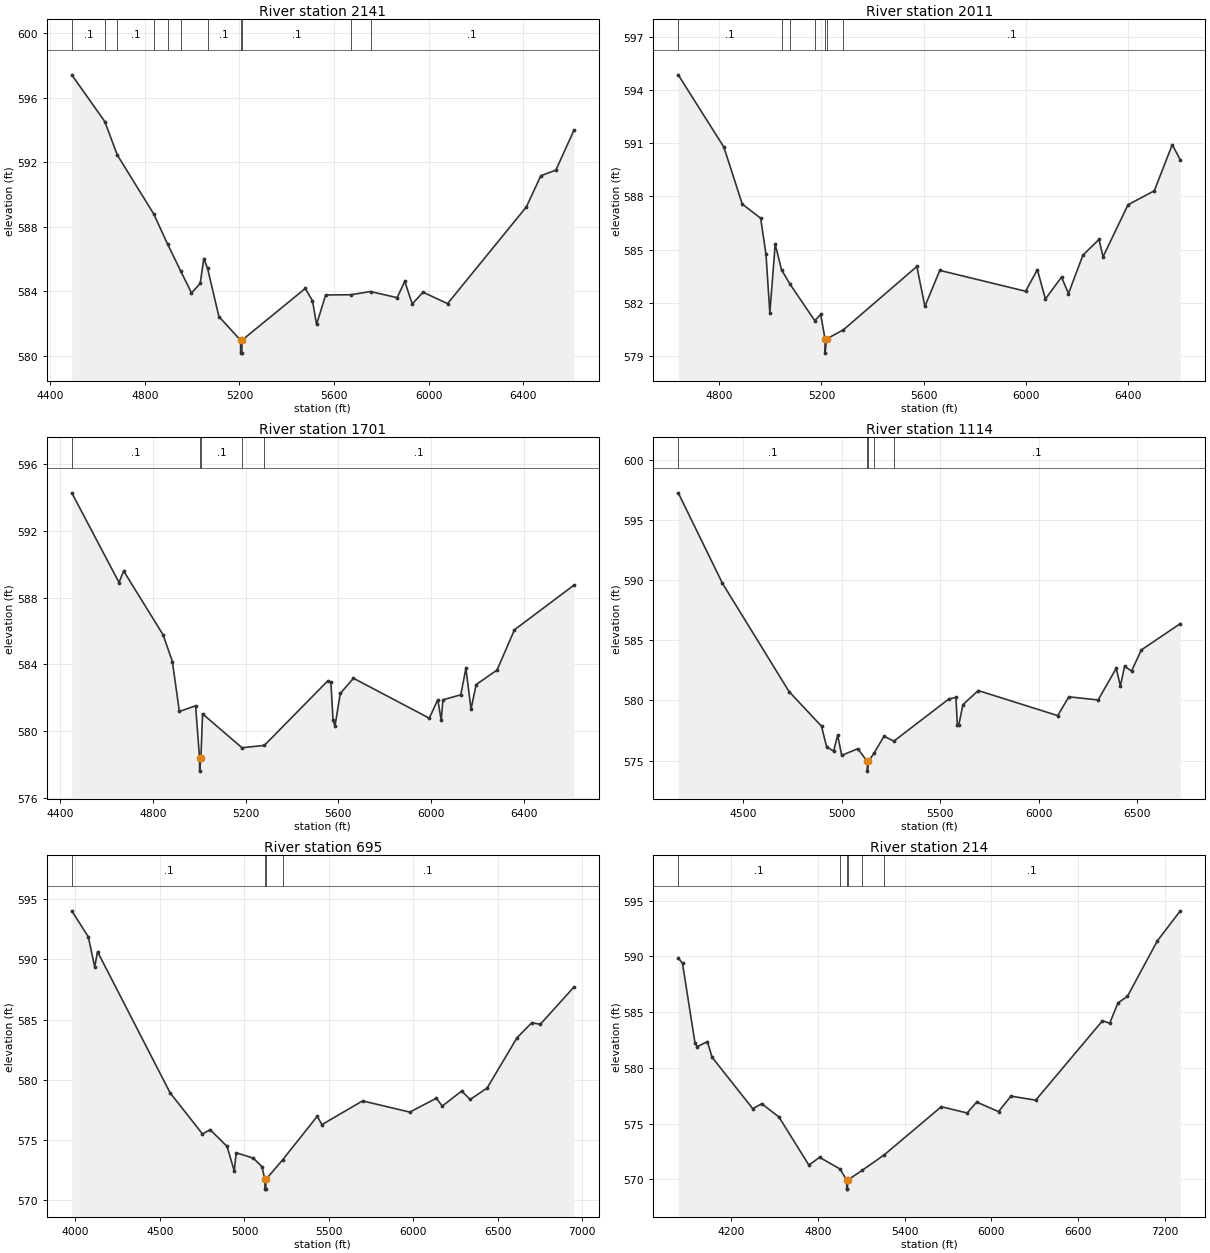
Type RM Length L Ch R = 1,2141,130,130,130
BEGIN DESCRIPTION:
UNT 074 in HW 4.0
END DESCRIPTION:
XS GIS Cut Line= 3
      2005826.33     13548659.27      2005435.69     13549289.51
      2005909.66     13550586.43
#Sta/Elev= 30
  4491.0  597.43  4630.7  594.53  4683.3  592.46  4837.5  588.80  4896.4  586.92
  4951.2  585.27  4997.1  583.90  5033.8  584.49  5049.1  586.03  5065.0  585.43
  5112.9  582.44  5204.4  580.97  5204.9  580.17  5209.9  580.17  5210.4  580.97
  5478.0  584.18  5508.5  583.42  5525.8  581.95  5564.3  583.78  5669.4  583.79
  5753.8  583.99  5866.5  583.61  5898.4  584.62  5930.4  583.22  5975.8  583.95
  6079.4  583.24  6412.6  589.24  6473.7  591.17  6537.3  591.52  6613.3  593.98
#Mann=11,-1,0
  4491.0     0.1       0  4630.7    0.08       0  4683.3     0.1       0
  4837.5    0.08       0  4896.4    0.05       0  4951.2    0.08       0
  5065.0     0.1       0  5204.4    0.07       0  5210.4     0.1       0
  5669.4    0.05       0  5753.8     0.1       0
Bank Sta=5204.4,5210.4
Exp/Cntr=0.3,0.1

Type RM Length L Ch R = 1,2011,310,310,310
BEGIN DESCRIPTION:
Mapping XS 73f7661d
END DESCRIPTION:
XS GIS Cut Line= 3
      2005659.64     13548711.39      2005362.77     13549148.89
      2005789.84     13550518.65
#Sta/Elev= 30
  4639.9  594.88  4818.4  590.79  4890.3  587.57  4962.2  586.77  4983.2  584.72
  4998.1  581.41  5019.1  585.30  5043.9  583.85  5077.6  583.03  5173.7  580.98
  5197.0  581.33  5213.9  579.94  5214.4  579.14  5219.9  579.94  5285.8  580.46
  5573.1  584.04  5604.5  581.78  5662.7  583.82  5998.2  582.64  6044.4  583.86
  6075.8  582.20  6138.8  583.44  6166.0  582.51  6222.5  584.68  6285.3  585.57
  6301.3  584.59  6398.8  587.53  6501.6  588.32  6571.9  590.93  6603.4  590.07
#Mann=7,-1,0
  4639.9     0.1       0  5043.9    0.08       0  5077.6     0.1       0
  5173.7    0.05       0  5213.9    0.07       0  5219.9    0.05       0
  5285.8     0.1       0
Bank Sta=5213.9,5219.9
Exp/Cntr=0.3,0.1

Type RM Length L Ch R = 1,1701,587,587,587
BEGIN DESCRIPTION:
Mapping XS 586cd87d
END DESCRIPTION:
XS GIS Cut Line= 3
      2005154.44     13548461.42      2005154.44     13549346.80
      2005690.45     13550507.31
#Sta/Elev= 30
  4451.0  594.27  4654.6  588.90  4674.6  589.59  4844.6  585.77  4884.6  584.17
  4914.6  581.18  4984.6  581.52  5001.6  578.41  5002.1  577.61  5007.6  578.41
  5014.6  581.04  5184.4  579.01  5280.9  579.15  5554.7  583.02  5567.8  582.92
  5576.7  580.70  5585.2  580.30  5608.1  582.26  5665.0  583.17  5991.7  580.78
  6028.4  581.89  6043.1  580.65  6050.4  581.88  6127.5  582.18  6149.5  583.77
  6171.6  581.32  6193.6  582.79  6283.5  583.66  6358.8  586.07  6614.7  588.74
#Mann=5,-1,0
  4451.0     0.1       0  5001.6    0.07       0  5007.6     0.1       0
  5184.4    0.05       0  5280.9     0.1       0
Bank Sta=5001.6,5007.6
Exp/Cntr=0.3,0.1

Type RM Length L Ch R = 1,1114,419,419,419
BEGIN DESCRIPTION:
UNT 074 in HW 3.0
END DESCRIPTION:
XS GIS Cut Line= 4
      2004920.06     13548336.38      2004560.69     13548836.39
      2004711.73     13549529.09      2005576.28     13550393.64
#Sta/Elev= 30
  4171.2  597.24  4395.7  589.72  4733.3  580.74  4898.1  577.86  4924.1  576.14
  4959.5  575.79  4980.0  577.12  5000.5  575.44  5082.4  575.99  5130.5  574.93
  5131.0  574.13  5136.5  574.93  5165.6  575.65  5215.4  577.03  5265.2  576.62
  5544.9  580.13  5580.2  580.25  5587.3  577.98  5594.4  577.94  5615.6  579.65
  5693.4  580.82  6096.4  578.74  6153.0  580.30  6301.5  580.04  6393.4  582.67
  6414.6  581.20  6435.8  582.83  6471.2  582.44  6520.7  584.19  6718.6  586.38
#Mann=5,-1,0
  4171.2     0.1       0  5130.5    0.07       0  5136.5     0.1       0
  5165.6    0.05       0  5265.2     0.1       0
Bank Sta=5130.5,5136.5
Exp/Cntr=0.3,0.1

Type RM Length L Ch R = 1,695,481,481,481
BEGIN DESCRIPTION:
UNT 074 in HW 2.0
END DESCRIPTION:
XS GIS Cut Line= 4
      2004591.95     13548258.23      2004216.94     13548982.22
      2004367.98     13549669.72      2005534.68     13550534.33
#Sta/Elev= 30
  3978.0  594.02  4075.7  591.87  4113.9  589.36  4130.4  590.63  4560.0  578.92
  4751.4  575.51  4797.3  575.86  4897.1  574.47  4939.5  572.44  4951.2  573.95
  5052.2  573.50  5103.3  572.80  5120.8  571.73  5121.3  570.93  5126.3  570.93
  5126.8  571.73  5225.9  573.36  5431.0  576.98  5458.3  576.28  5699.1  578.25
  5978.8  577.32  6135.2  578.47  6170.7  577.82  6285.5  579.07  6335.6  578.37
  6435.8  579.31  6613.7  583.50  6700.8  584.74  6750.6  584.60  6949.4  587.69
#Mann=4,-1,0
  3978.0     0.1       0  5120.8    0.07       0  5126.8     0.1       0
  5225.9     0.1       0
Bank Sta=5120.8,5126.8
Exp/Cntr=0.3,0.1

Type RM Length L Ch R = 1,214,0,0,0
BEGIN DESCRIPTION:
UNT 074 in HW 1.0
END DESCRIPTION:
XS GIS Cut Line= 4
      2004159.64     13548284.31      2003867.98     13549206.18
      2004034.64     13549680.14      2005675.01     13550825.01
#Sta/Elev= 30
  3836.1  589.86  3865.6  589.37  3952.2  582.20  3967.7  581.90  4037.6  582.35
  4069.9  580.95  4350.8  576.34  4413.7  576.78  4532.7  575.58  4738.8  571.28
  4813.4  571.97  4954.7  570.92  5000.1  569.92  5000.6  569.12  5005.7  569.12
  5006.2  569.92  5106.6  570.80  5259.3  572.19  5654.0  576.51  5832.8  575.95
  5898.3  576.93  6049.7  576.07  6135.1  577.46  6306.5  577.10  6768.0  584.22
  6818.0  584.00  6875.3  585.83  6939.9  586.40  7147.3  591.39  7305.8  594.08
#Mann=6,-1,0
  3836.1     0.1       0  4954.7    0.05       0  5000.1    0.04       0
  5006.2    0.05       0  5106.6    0.16       0  5259.3     0.1       0
Bank Sta=5000.1,5006.2
Exp/Cntr=0.3,0.1

Chan Stop Cuts=-1