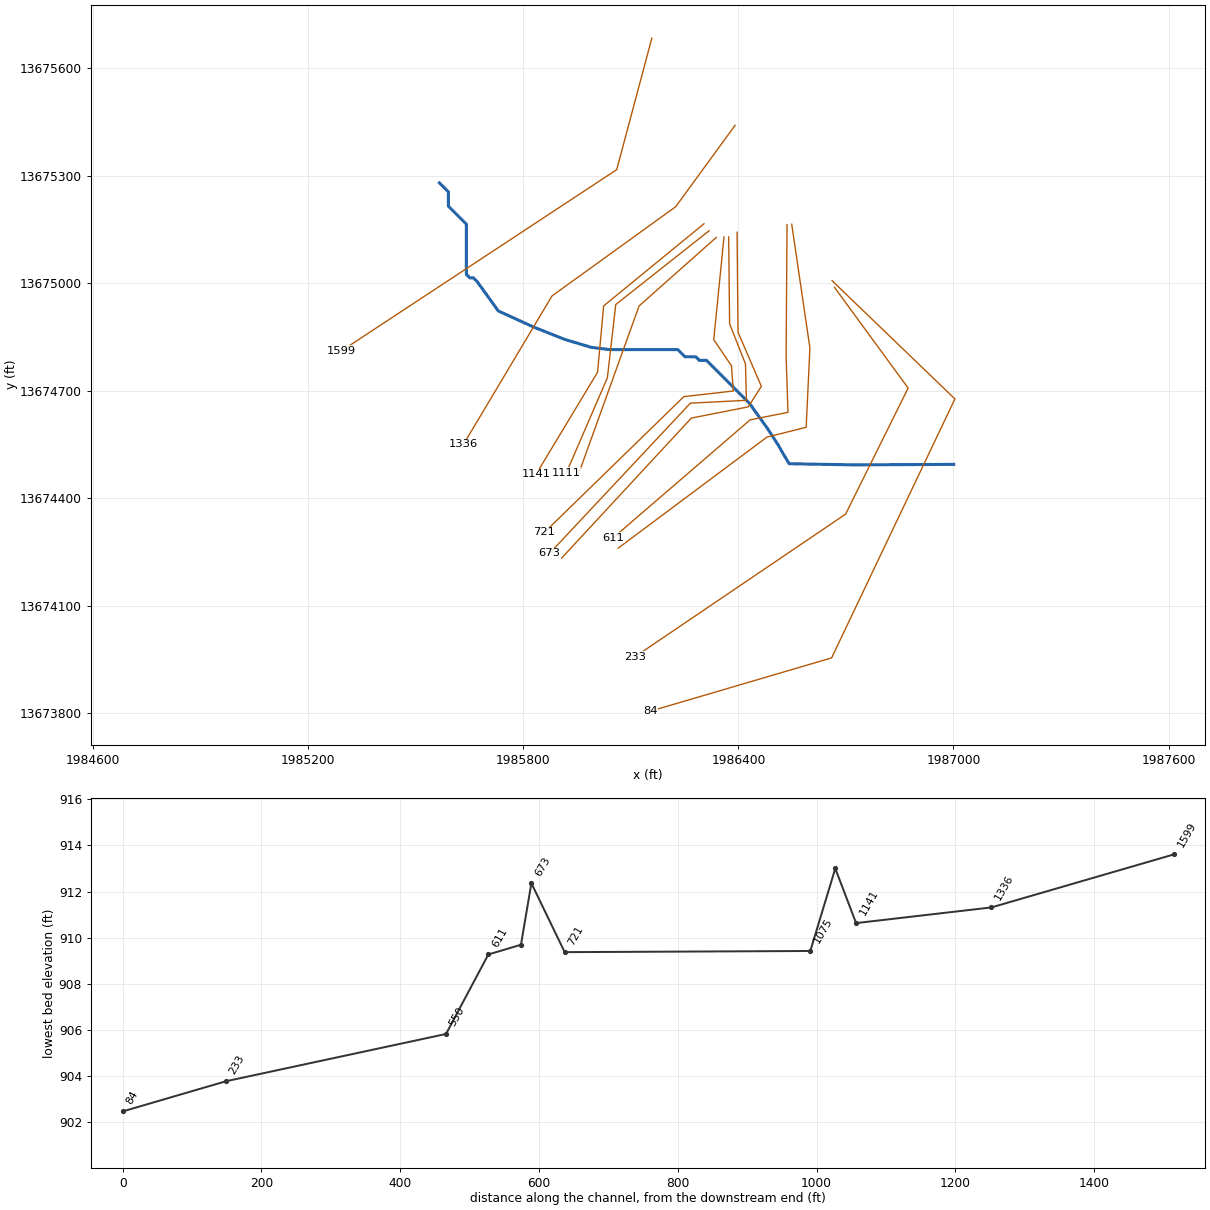
--- UNT 079 in HW.prj (project) ---

Proj Title=UNT 079 in HW Base Level Engineering
Current Plan=p01
Default Exp/Contr=0.3,0.1
English Units
Geom File=g01
Flow File=f01
Plan File=p01
Y Axis Title=Elevation
X Axis Title(PF)=Main Channel Distance
X Axis Title(XS)=Station
BEGIN DESCRIPTION:
UNT 079 in HW
END DESCRIPTION:
DSS Export Rating Curves= 0
DSS Export Rating Curve Sorted= 0
DSS Export Volume Flow Curves= 0
DXF OffsetX= 0
DXF OffsetY= 0
DXF ScaleX= 1
DXF ScaleY= 10

--- UNT 079 in HW.p01 (plan) ---

Plan Title=Multiple Run
Short Identifier=Multiple
Geom File=g01
Flow File=f01
Subcritical Flow
K Sum by GR= 0
Std Step Tol= 0.01
Critical Tol= 0.01
Num of Std Step Trials= 20
Max Error Tol= 0.3
Flow Tol Ratio= 0.001
Split Flow NTrial= 30
Split Flow Tol= 0.02
Split Flow Ratio= 0.02
Log Output Level= 0
Friction Slope Method= 1
Unsteady Friction Slope Method= 2
Unsteady Bridges Friction Slope Method= 1
Parabolic Critical Depth
Global Vel Dist=  1 , 1 , 1
Global Log Level= 0
CheckData=True
Encroach Param= -1, 0, 0, 0
BEGIN DESCRIPTION:
Multiple Run
END DESCRIPTION:

--- UNT 079 in HW.f01 (steady flow) ---

Flow Title=Multiple
Number of Profiles=7
Profile Names=10-year,25-year,50-year,1pct_min,100-year,1pct_plu,500-year
River Rch & RM= UNT 079 in HW,Reach-1,1599
     515     712     873     530    1057    2110    1556
Boundary for River Rch & Prof#=UNT 079 in HW,Reach-1,1
Up Type=0
Dn Type=3
Dn Slope=0.005
Boundary for River Rch & Prof#=UNT 079 in HW,Reach-1,2
Up Type=0
Dn Type=3
Dn Slope=0.005
Boundary for River Rch & Prof#=UNT 079 in HW,Reach-1,3
Up Type=0
Dn Type=3
Dn Slope=0.005
Boundary for River Rch & Prof#=UNT 079 in HW,Reach-1,4
Up Type=0
Dn Type=3
Dn Slope=0.005
Boundary for River Rch & Prof#=UNT 079 in HW,Reach-1,5
Up Type=0
Dn Type=3
Dn Slope=0.005
Boundary for River Rch & Prof#=UNT 079 in HW,Reach-1,6
Up Type=0
Dn Type=3
Dn Slope=0.005
Boundary for River Rch & Prof#=UNT 079 in HW,Reach-1,7
Up Type=0
Dn Type=3
Dn Slope=0.005

--- UNT 079 in HW.g01 (geometry) ---

Geom Title=Existing Conditions
Program Version=5.05

River Reach=UNT 079 in HW   ,Reach-1
Reach XY= 25
       1985565.8     13675279.54       1985590.8     13675254.54
       1985590.8     13675214.54       1985640.8     13675164.54
       1985640.8     13675024.54       1985650.8     13675014.54
       1985660.8     13675014.54       1985670.8     13675004.54
      1985729.91     13674922.38      1985828.86     13674877.24
      1985916.54     13674842.51      1985989.45     13674820.81
       1986040.8     13674814.54       1986230.8     13674814.54
       1986250.8     13674794.54       1986280.8     13674794.54
       1986290.8     13674784.54       1986310.8     13674784.54
       1986430.8     13674664.54      1986479.91     13674595.99
      1986511.16     13674548.24      1986523.31     13674526.54
      1986541.54     13674496.16      1986722.37     13674492.97
      1987000.74     13674494.42

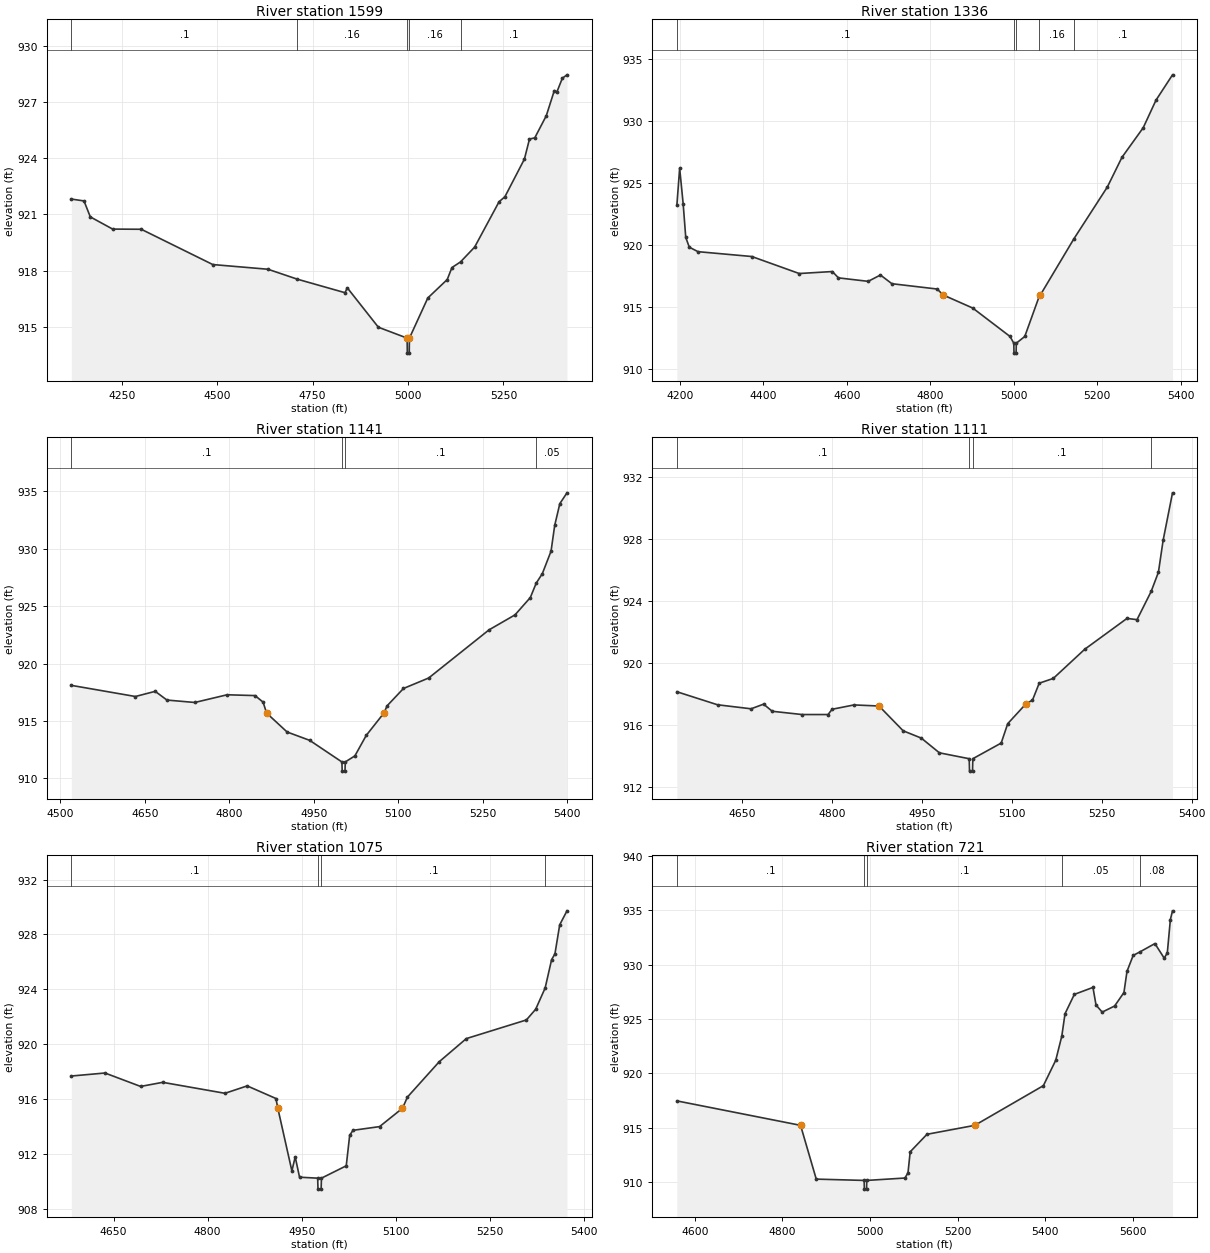
Type RM Length L Ch R = 1 ,1599    ,263,263,263
BEGIN DESCRIPTION:
UNT 079 in HW 1.0
END DESCRIPTION:
XS GIS Cut Line= 3
      1986158.33       13675683.      1986060.43      13675316.4
      1985292.97     13674811.32
#Sta/Elev= 30
  4118.2  921.82  4151.4  921.72  4167.9  920.87  4226.4  920.22  4301.4  920.21
  4488.7  918.33  4633.2  918.08  4710.2  917.55    4835  916.83    4841  917.09
  4922.4  914.99  4997.7  914.41  4998.2  913.61  5003.2  913.61  5003.7  914.41
  5051.9  916.55  5102.7  917.53  5115.1  918.17  5137.5  918.47  5174.5  919.26
  5238.6  921.68  5253.7  921.94  5304.9  923.95  5318.2  925.02    5332  925.08
  5362.2  926.26  5383.2   927.6    5390  927.53  5404.3  928.26  5416.4  928.44
#Mann= 5 ,-1 , 0
  4118.2      .1       0  4710.2     .16       0  4997.7     .07       0
  5003.7     .16       0  5137.5      .1       0
Bank Sta=4997.7,5003.7
XS Rating Curve= 0 ,0
Exp/Cntr=0.3,0.1

Type RM Length L Ch R = 1 ,1336    ,195,195,195
BEGIN DESCRIPTION:
UNT 079 in HW 2.0
END DESCRIPTION:
XS GIS Cut Line= 4
      1986390.57     13675439.99      1986224.94     13675213.01
      1985879.81     13674964.12      1985633.31     13674550.97
#Sta/Elev= 30
  4192.7   923.2  4199.4   926.2  4207.8  923.34    4214  920.63  4222.5  919.84
  4243.4  919.48  4372.2  919.09  4485.9  917.72  4565.2  917.88  4579.9  917.37
  4651.1  917.09  4680.5   917.6  4707.9   916.9  4816.7  916.47 4830.16916.0025
  4901.6  914.94    4991  912.65    5000  912.11  5000.5  911.31  5005.5  911.31
    5006  912.11  5026.3  912.65  5061.2  915.91 5063.81916.0024  5143.9  920.51
  5224.2  924.69  5259.2  927.08  5310.1  929.46  5340.7  931.68  5380.3  933.72
#Mann= 5 ,-1 , 0
  4192.7      .1       0    5000     .07       0    5006      .1       0
  5061.2     .16       0  5143.9      .1       0
Bank Sta=4830.16,5063.81
XS Rating Curve= 0 ,0
Exp/Cntr=0.3,0.1

Type RM Length L Ch R = 1 ,1141    ,30,30,30
BEGIN DESCRIPTION:
UNT 079 in HW 5.0
END DESCRIPTION:
XS GIS Cut Line= 4
      1986303.86     13675165.51      1986023.91     13674936.35
      1986006.98     13674751.45      1985835.11      13674466.3
#Sta/Elev= 30
  4519.3   918.1  4633.1  917.13  4668.3  917.58  4689.1  916.82  4738.6  916.61
    4796  917.28  4845.6  917.21  4859.9  916.64 4866.18915.6843  4902.5  914.04
  4942.7  913.31  4999.9  911.43  5000.4  910.63  5005.4  910.63  5005.9  911.43
    5023  911.96  5043.1  913.74 5074.43915.6843  5080.2  916.32  5109.3  917.83
    5154  918.74  5261.1  922.93  5307.4  924.24  5334.6  925.75    5345     927
  5355.9  927.83  5371.4  929.79  5377.9  932.04    5387  933.93  5399.7  934.87
#Mann= 4 ,-1 , 0
  4519.3      .1       0  4999.9     .07       0  5005.9      .1       0
    5345     .05       0
Bank Sta=4866.18,5074.43
XS Rating Curve= 0 ,0
Exp/Cntr=0.3,0.1

Type RM Length L Ch R = 1 ,1111    ,36,36,36
BEGIN DESCRIPTION:
UNT 079 in HW 4.0
END DESCRIPTION:
XS GIS Cut Line= 4
      1986318.17     13675145.97      1986057.76     13674940.25
      1986034.33     13674735.83      1985919.76     13674470.64
#Sta/Elev= 30
  4541.6  918.12  4609.4  917.28  4665.4  917.02  4686.2  917.32  4700.7  916.86
  4750.4  916.65  4793.7  916.65  4800.5  916.99    4837  917.27  4878.7   917.2
    4919   915.6  4949.2  915.13  4979.4  914.18  5029.1   913.8  5029.6     913
  5034.6     913  5035.1   913.8  5082.4  914.81  5093.3  916.06  5123.7  917.34
  5134.6  917.58  5145.8  918.67  5169.3  918.98  5221.7  920.86  5292.2  922.85
  5308.9  922.77  5332.5  924.59  5344.6  925.83  5352.5   927.9  5368.1  930.95
#Mann= 4 ,-1 , 0
  4541.6      .1       0  5029.1     .07       0  5035.1      .1       0
  5332.5     .05       0
Bank Sta=4878.7,5123.7
XS Rating Curve= 0 ,0
Exp/Cntr=0.3,0.1

Type RM Length L Ch R = 1 ,1075    ,354,354,354
BEGIN DESCRIPTION:
UNT 079 in HW 3.0
END DESCRIPTION:
XS GIS Cut Line= 3
      1986338.11     13675127.29      1986122.87     13674936.35
      1985952.72     13674464.09
#Sta/Elev= 30
  4582.8  917.67  4636.4  917.89  4693.2  916.91  4728.4  917.21  4827.6  916.41
    4863  916.95  4908.8  916.03  4911.8915.3195  4934.2  910.75  4939.5  911.77
  4946.4  910.29  4975.3  910.22  4975.8  909.42  4980.8  909.42  4981.3  910.22
  5020.8  911.12  5026.3  913.35  5031.6  913.71  5073.9  913.98  5110.4915.3192
  5118.4  916.14  5169.1  918.72  5212.1   920.4  5307.8  921.76  5322.6  922.54
  5337.7  924.09    5348  926.16  5353.3  926.58  5360.9   928.7  5372.5  929.72
#Mann= 4 ,-1 , 0
  4582.8      .1       0  4975.3     .07       0  4981.3      .1       0
  5337.7     .05       0
Bank Sta=4911.8,5110.4
XS Rating Curve= 0 ,0
Exp/Cntr=0.3,0.1

Type RM Length L Ch R = 1 ,721     ,48,48,48
BEGIN DESCRIPTION:
UNT 079 in HW 12.0
END DESCRIPTION:
XS GIS Cut Line= 6
      1986359.76     13675128.72      1986331.12     13674842.25
      1986380.59     13674769.33       1986385.8     13674699.02
      1986247.78      13674683.4      1985858.57     13674304.56
#Sta/Elev= 30
  4559.2  917.48 4841.57915.2329  4877.4  910.29  4986.7  910.17  4987.2  909.37
  4992.2  909.37  4992.7  910.17  5079.8  910.39  5086.8  910.87  5091.8   912.8
  5130.1  914.41 5239.25915.2325  5395.8  918.88  5424.1  921.22  5437.9  923.44
  5445.2  925.49  5466.5  927.27    5509  927.91    5516  926.29  5530.1  925.64
  5558.4   926.2  5579.7  927.44  5586.7  929.39  5600.8  930.85  5617.3   931.2
  5650.4  931.94  5671.6   930.6  5678.7  931.08  5685.7  934.15  5690.6  934.95
#Mann= 5 ,-1 , 0
  4559.2      .1       0  4986.7     .07       0  4992.7      .1       0
  5437.9     .05       0  5617.3     .08       0
Bank Sta=4841.57,5239.25
XS Rating Curve= 0 ,0
Exp/Cntr=0.3,0.1

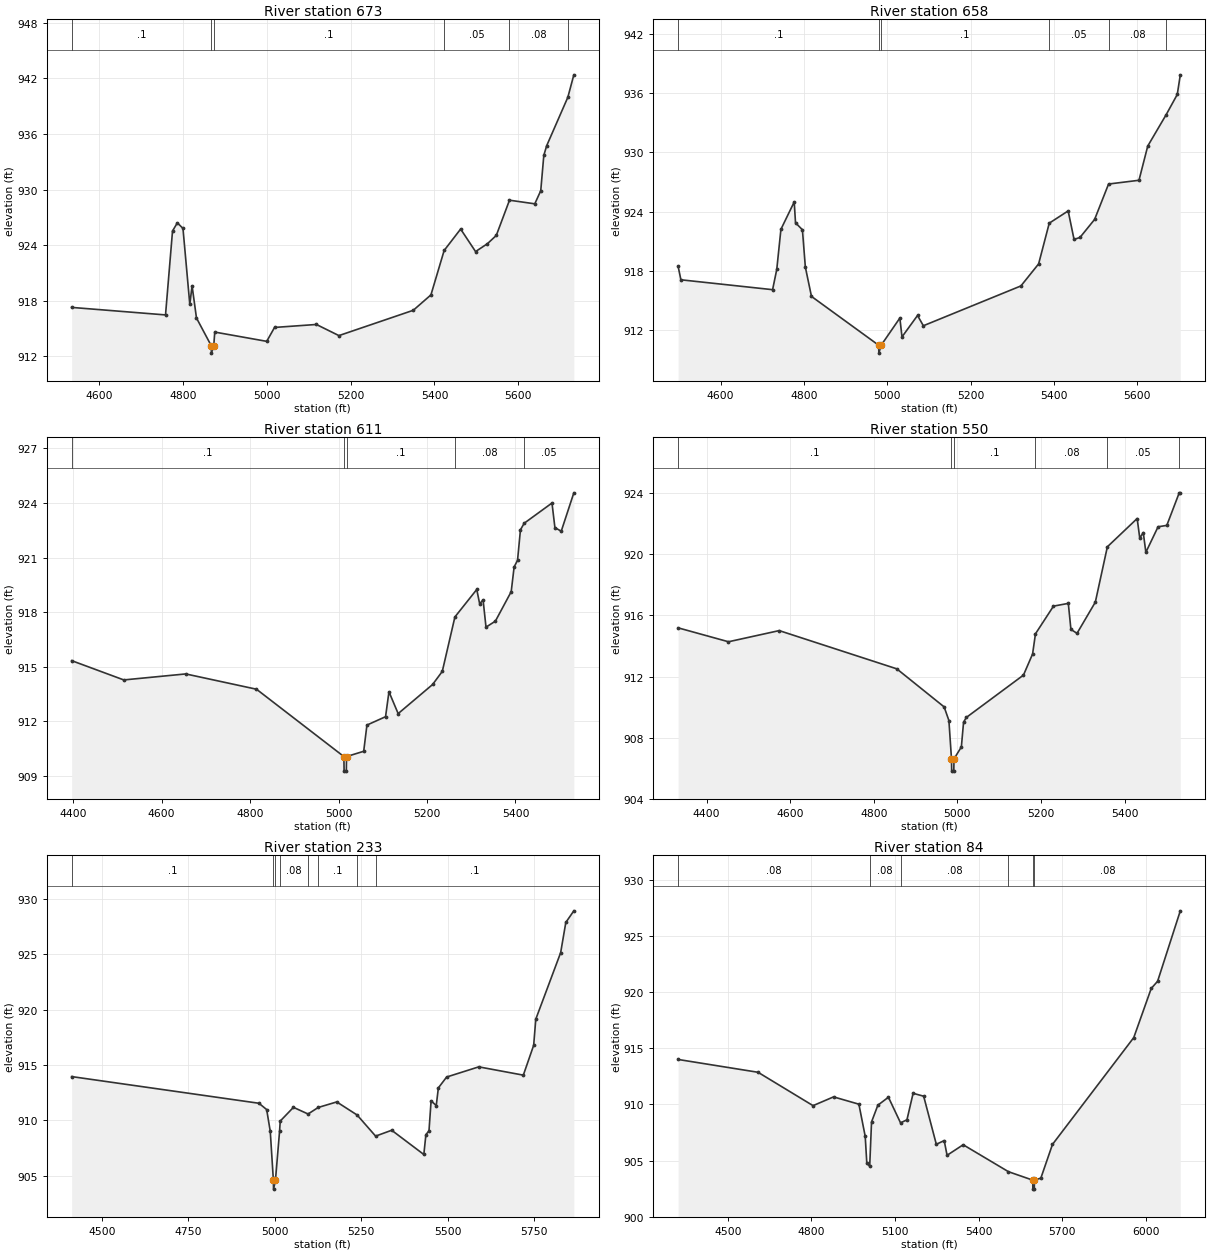
Type RM Length L Ch R = 1 ,673     ,15,15,15
BEGIN DESCRIPTION:
UNT 079 in HW 10.0
END DESCRIPTION:
XS GIS Cut Line= 6
      1986372.78     13675128.75      1986375.39     13674886.52
      1986419.66     13674774.54      1986422.26     13674672.98
      1986266.01     13674665.17      1985872.76     13674245.88
#Sta/Elev= 30
    4535  917.29  4758.8  916.48  4775.5  925.53    4787  926.41  4800.4  925.81
  4816.7  917.61  4822.1  919.62  4832.6  916.15  4867.8  913.16  4868.3  912.36
  4873.8  913.16  4876.2  914.63  5000.1  913.63  5018.7  915.13  5118.5  915.45
  5172.2  914.25  5349.5  916.98  5391.6  918.64  5423.1  923.43  5462.4  925.74
    5498  923.31  5526.3  924.16  5547.4  925.05  5578.9  928.85  5639.2  928.46
  5653.4  929.87  5660.7  933.68  5667.5  934.72    5718  939.95  5732.3  942.37
#Mann= 6 ,-1 , 0
    4535      .1       0  4867.8     .07       0  4873.8      .1       0
  5423.1     .05       0  5578.9     .08       0    5718      .1       0
Bank Sta=4867.8,4873.8
XS Rating Curve= 0 ,0
Exp/Cntr=0.3,0.1

Type RM Length L Ch R = 1 ,658     ,47,47,47
BEGIN DESCRIPTION:
UNT 079 in HW 11.0
END DESCRIPTION:
XS GIS Cut Line= 6
      1986396.22     13675141.75      1986398.82     13674863.08
      1986463.93     13674712.04      1986427.47     13674654.75
      1986268.62      13674623.5      1985906.65     13674232.89
#Sta/Elev= 30
    4498  918.47  4504.7  917.11  4724.8  916.11  4734.8  918.16  4744.8  922.22
  4776.7  924.99  4779.8  922.88  4796.4  922.17  4803.4   918.4  4818.1  915.43
  4979.4  910.49  4979.9  909.69  4985.4  910.49  5030.3  913.24  5035.4  911.33
  5072.7   913.5  5086.7  912.46  5320.9  916.49  5363.4  918.72  5388.9  922.84
  5434.3  924.08  5448.4   921.2  5462.6  921.39  5497.8  923.22  5531.3   926.8
  5604.3  927.18  5625.3  930.64  5669.6  933.82  5696.2  935.86  5703.5  937.85
#Mann= 6 ,-1 , 0
    4498      .1       0  4979.4     .07       0  4985.4      .1       0
  5388.9     .05       0  5531.3     .08       0  5669.6      .1       0
Bank Sta=4979.4,4985.4
XS Rating Curve= 0 ,0
Exp/Cntr=0.3,0.1

Type RM Length L Ch R = 1 ,611     ,61,61,61
BEGIN DESCRIPTION:
UNT 079 in HW 7.0
END DESCRIPTION:
XS GIS Cut Line= 5
      1986535.63     13675162.87      1986533.03     13674795.72
      1986538.23     13674639.47      1986432.76     13674618.64
      1986050.53     13674289.53
#Sta/Elev= 30
  4396.6  915.34  4514.5  914.28  4654.5  914.61  4814.5  913.77  5012.1  910.07
  5012.6  909.27  5017.6  909.27  5018.1  910.07  5056.9  910.36  5064.2   911.8
  5106.3  912.26    5114  913.63  5134.8  912.43  5212.7  914.03  5234.6  914.75
  5263.1  917.74  5312.5  919.25  5319.1  918.46  5326.8  918.68  5333.4  917.18
  5354.6  917.51  5390.4  919.13    5397  920.49  5404.7  920.85  5411.3  922.53
  5419.8  922.89  5482.6     924  5489.2  922.65  5503.5  922.45    5532  924.56
#Mann= 5 ,-1 , 0
  4396.6      .1       0  5012.1     .07       0  5018.1      .1       0
  5263.1     .08       0  5419.8     .05       0
Bank Sta=5012.1,5018.1
XS Rating Curve= 0 ,0
Exp/Cntr=0.3,0.1

Type RM Length L Ch R = 1 ,550     ,317,317,317
BEGIN DESCRIPTION:
UNT 079 in HW 6.0
END DESCRIPTION:
XS GIS Cut Line= 5
      1986548.65     13675164.24      1986599.43     13674819.16
      1986589.01      13674597.8      1986479.64     13674570.46
      1986064.25     13674260.54
#Sta/Elev= 30
  4331.9  915.19  4452.4  914.28  4573.7  915.01    4855  912.51  4968.3  910.02
  4979.7  909.13  4985.9  906.62  4986.4  905.82  4991.4  905.82  4991.9  906.62
  5009.5   907.4  5014.8  909.02  5021.4  909.33  5158.1   912.1  5179.9  913.48
  5186.8   914.8  5229.9  916.61  5265.4  916.79  5271.6  915.09  5286.2  914.83
    5330  916.87  5358.8  920.49  5430.1  922.34  5436.3  921.06  5444.7  921.42
  5450.9  920.13  5480.1   921.8    5501  921.89  5530.7  924.02  5533.3  924.02
#Mann= 6 ,-1 , 0
  4331.9      .1       0  4985.9     .07       0  4991.9      .1       0
  5186.8     .08       0  5358.8     .05       0  5530.7      .1       0
Bank Sta=4985.9,4991.9
XS Rating Curve= 0 ,0
Exp/Cntr=0.3,0.1

Type RM Length L Ch R = 1 ,233     ,149,149,149
BEGIN DESCRIPTION:
UNT 079 in HW 9.0
END DESCRIPTION:
XS GIS Cut Line= 4
      1986667.82     13674988.39      1986873.52     13674707.18
      1986699.04     13674355.62      1986110.52     13673957.19
#Sta/Elev= 30
  4412.7  913.94    4954  911.53  4976.4  910.96  4986.8  908.99  4995.8  904.57
  4996.3  903.77  5001.8  904.57  5013.7     909  5015.6  909.92  5053.8  911.16
  5096.1  910.56  5125.4  911.15    5179  911.65  5237.8  910.47  5291.3  908.56
  5337.8  909.09  5430.7   906.9  5436.7   908.7  5445.6  909.03  5451.7  911.75
  5466.6  911.32  5472.7  912.92  5496.6   913.9  5589.5  914.82  5718.3  914.07
  5748.2  916.77  5754.3  919.13  5826.2  925.14  5841.1  927.87  5864.3  928.92
#Mann= 8 ,-1 , 0
  4412.7      .1       0  4995.8     .07       0  5001.8      .1       0
  5013.7     .08       0  5096.1     .05       0  5125.4      .1       0
  5237.8     .08       0  5291.3      .1       0
Bank Sta=4995.8,5001.8
XS Rating Curve= 0 ,0
Exp/Cntr=0.3,0.1

Type RM Length L Ch R = 1 ,84      ,0,0,0
BEGIN DESCRIPTION:
UNT 079 in HW 8.0
END DESCRIPTION:
XS GIS Cut Line= 4
      1986661.18     13675006.77      1987004.04     13674676.93
      1986659.98     13673954.58       1986154.8     13673806.15
#Sta/Elev= 30
  4321.6     914  4608.4  912.86  4805.9  909.89  4879.5  910.67  4970.4  910.02
  4993.1  907.16  4998.9  904.75  5009.2   904.5  5015.8  908.44  5038.5  909.93
  5076.4  910.64  5119.9  908.36  5142.9  908.63    5165  910.99  5202.9  910.73
  5248.3  906.45  5276.6  906.78  5286.9  905.47  5344.7  906.41  5507.3  904.01
  5594.4  903.26  5594.9  902.46  5599.9  902.46  5600.4  903.26  5623.5  903.44
  5665.2  906.44    5957  915.95  6019.6  920.32  6042.5  920.96    6124  927.23
#Mann= 6 ,-1 , 0
  4321.6     .08       0  5009.2     .08       0  5119.9     .08       0
  5507.3     .08       0  5594.4     .07       0  5600.4     .08       0
Bank Sta=5594.4,5600.4
XS Rating Curve= 0 ,0
Exp/Cntr=0.3,0.1
LCMann Table=0

Chan Stop Cuts=-1
Use User Specified Reach Order=0
Composite Channel Slope=5