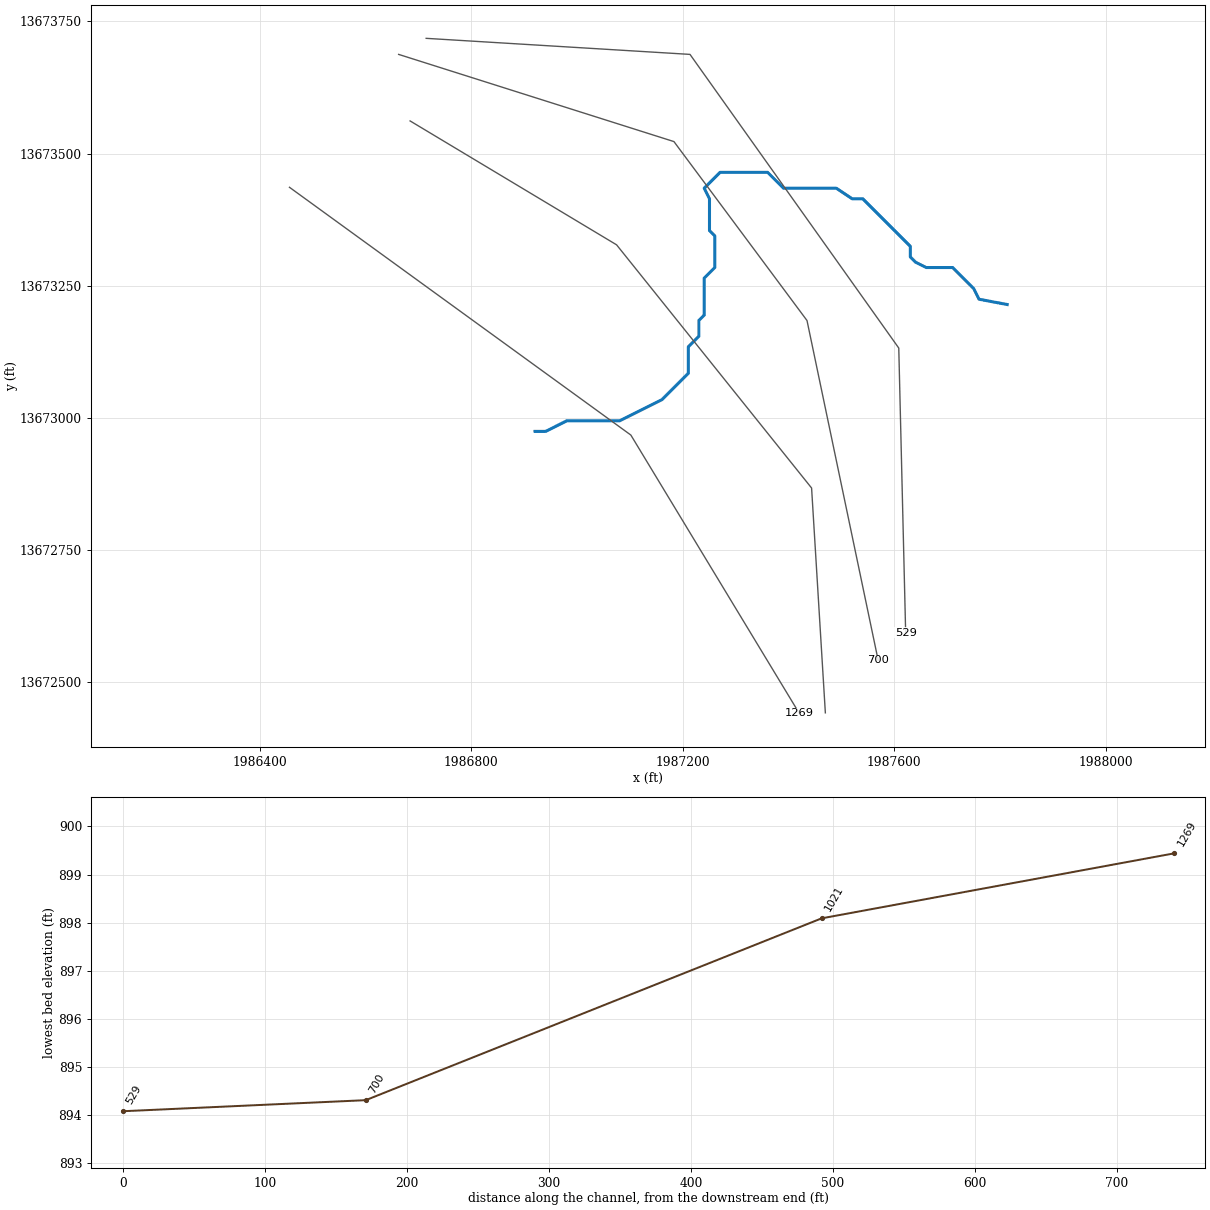
--- UNT 080 in HW.prj (project) ---

Proj Title=UNT 080 in HW Base Level Engineering
Current Plan=p01
Default Exp/Contr=0.3,0.1
English Units
Geom File=g01
Flow File=f01
Plan File=p01
BEGIN DESCRIPTION:
UNT 080 in HW
END DESCRIPTION:

--- UNT 080 in HW.p01 (plan) ---

Plan Title=Multiple Run
Short Identifier=Multiple
Geom File=g01
Flow File=f01
Subcritical Flow
K Sum by GR= 0
Std Step Tol= 0.01
Critical Tol= 0.01
Num of Std Step Trials= 20
Max Error Tol= 0.3
Flow Tol Ratio= 0.001
Split Flow NTrial= 30
Split Flow Tol= 0.02
Split Flow Ratio= 0.02
Log Output Level= 0
Friction Slope Method= 1
Unsteady Friction Slope Method= 2
Unsteady Bridges Friction Slope Method= 1
Parabolic Critical Depth
Global Vel Dist=  1 , 1 , 1
Global Log Level= 0
CheckData=True
Encroach Param= -1, 0, 0, 0
BEGIN DESCRIPTION:
Multiple Run
END DESCRIPTION:

--- UNT 080 in HW.f01 (steady flow) ---

Flow Title=Multiple
Number of Profiles=7
Profile Names=10-year,25-year,50-year,1pct_min,100-year,1pct_plu,500-year
River Rch & RM= UNT 080 in HW,Reach-1,1269
     331     451     548     331     661    1318     961
Boundary for River Rch & Prof#=UNT 080 in HW,Reach-1,1
Up Type=0
Dn Type=3
Dn Slope=0.005
Boundary for River Rch & Prof#=UNT 080 in HW,Reach-1,2
Up Type=0
Dn Type=3
Dn Slope=0.005
Boundary for River Rch & Prof#=UNT 080 in HW,Reach-1,3
Up Type=0
Dn Type=3
Dn Slope=0.005
Boundary for River Rch & Prof#=UNT 080 in HW,Reach-1,4
Up Type=0
Dn Type=3
Dn Slope=0.005
Boundary for River Rch & Prof#=UNT 080 in HW,Reach-1,5
Up Type=0
Dn Type=3
Dn Slope=0.005
Boundary for River Rch & Prof#=UNT 080 in HW,Reach-1,6
Up Type=0
Dn Type=3
Dn Slope=0.005
Boundary for River Rch & Prof#=UNT 080 in HW,Reach-1,7
Up Type=0
Dn Type=3
Dn Slope=0.005

--- UNT 080 in HW.g01 (geometry) ---

Geom Title=Existing Conditions

River Reach=UNT 080 in HW,Reach-1
Reach XY= 30
      1986920.80     13672974.54      1986940.80     13672974.54
      1986980.80     13672994.54      1987080.80     13672994.54
      1987160.80     13673034.54      1987210.80     13673084.54
      1987210.80     13673134.54      1987230.80     13673154.54
      1987230.80     13673184.54      1987240.80     13673194.54
      1987240.80     13673264.54      1987260.80     13673284.54
      1987260.80     13673344.54      1987250.80     13673354.54
      1987250.80     13673414.54      1987240.80     13673434.54
      1987270.80     13673464.54      1987360.80     13673464.54
      1987390.80     13673434.54      1987490.80     13673434.54
      1987520.80     13673414.54      1987540.80     13673414.54
      1987630.80     13673324.54      1987630.80     13673304.54
      1987640.80     13673294.54      1987660.80     13673284.54
      1987710.80     13673284.54      1987750.80     13673244.54
      1987760.80     13673224.54      1987814.06     13673214.54

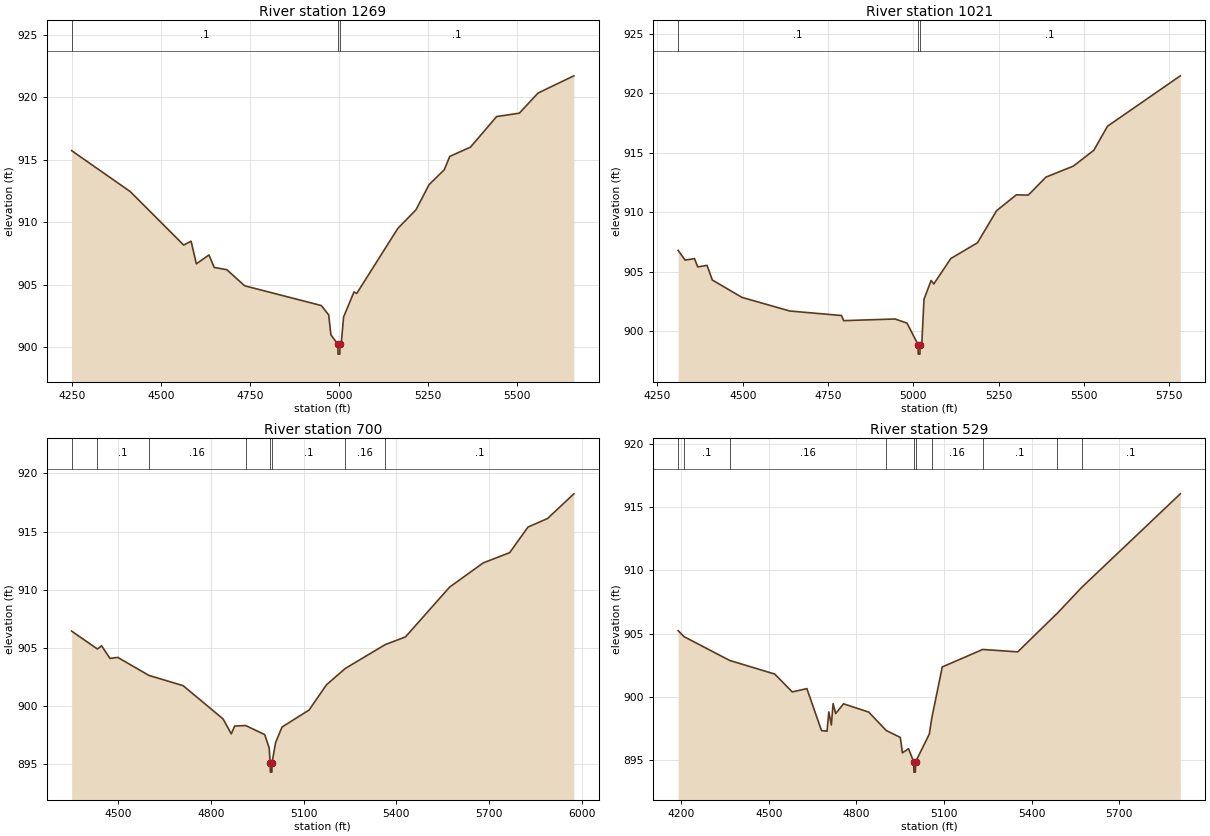
Type RM Length L Ch R = 1,1269,248,248,248
BEGIN DESCRIPTION:
UNT 080 in HW 1.0
END DESCRIPTION:
XS GIS Cut Line= 3
      1986456.24     13673436.32      1987102.04     13672967.60
      1987420.71     13672441.09
#Sta/Elev= 30
  4247.9  915.73  4412.5  912.46  4563.3  908.17  4584.1  908.48  4598.8  906.67
  4634.4  907.38  4649.1  906.38  4684.6  906.20  4734.9  904.91  4950.6  903.33
  4971.4  902.58  4977.6  900.98  4997.1  900.24  4997.6  899.44  5002.6  899.44
  5003.1  900.24  5007.0  900.38  5013.2  902.41  5042.6  904.42  5050.3  904.30
  5165.8  909.50  5217.1  911.00  5253.9  913.01  5296.6  914.20  5312.1  915.27
  5370.3  916.01  5444.0  918.46  5508.0  918.73  5560.4  920.34  5661.3  921.72
#Mann=3,-1,0
  4247.9     0.1       0  4997.1    0.07       0  5003.1     0.1       0
Bank Sta=4997.1,5003.1
Exp/Cntr=0.3,0.1

Type RM Length L Ch R = 1,1021,321,321,321
BEGIN DESCRIPTION:
UNT 080 in HW 4.0
END DESCRIPTION:
XS GIS Cut Line= 4
      1986684.40     13673561.88      1987075.04     13673327.49
      1987443.96     13672867.42      1987470.00     13672442.10
#Sta/Elev= 30
  4310.6  906.80  4331.2  905.98  4358.5  906.11  4368.2  905.41  4395.4  905.54
  4410.9  904.31  4497.9  902.85  4637.8  901.71  4789.3  901.33  4795.7  900.90
  4946.2  901.04  4981.4  900.69  5013.6  898.89  5014.1  898.09  5019.1  898.09
  5019.6  898.89  5024.6  898.96  5031.0  902.69  5051.8  904.27  5059.8  903.98
  5109.4  906.11  5187.8  907.44  5243.8  910.13  5301.5  911.46  5336.7  911.44
  5388.4  912.95  5468.5  913.87  5528.6  915.20  5568.7  917.22  5782.0  921.45
#Mann=3,-1,0
  4310.6     0.1       0  5013.6    0.07       0  5019.6     0.1       0
Bank Sta=5013.6,5019.6
Exp/Cntr=0.3,0.1

Type RM Length L Ch R = 1,700,171,171,171
BEGIN DESCRIPTION:
UNT 080 in HW 3.0
END DESCRIPTION:
XS GIS Cut Line= 4
      1986662.74     13673687.73      1987183.55     13673522.80
      1987435.28     13673184.26      1987569.84     13672541.88
#Sta/Elev= 30
  4349.7  906.44  4433.1  904.90  4446.6  905.18  4473.7  904.09  4498.9  904.18
  4599.6  902.63  4710.2  901.75  4839.4  898.89  4866.1  897.60  4877.0  898.27
  4912.4  898.32  4974.1  897.54  4988.7  896.39  4991.9  895.11  4992.4  894.31
  4997.4  894.31  4997.9  895.11  5009.5  896.86  5030.3  898.19  5117.6  899.65
  5174.3  901.83  5234.9  903.23  5364.1  905.28  5429.5  905.94  5572.5  910.23
  5681.1  912.31  5766.7  913.19  5825.8  915.39  5889.3  916.13  5974.2  918.25
#Mann=8,-1,0
  4349.7    0.16       0  4433.1     0.1       0  4599.6    0.16       0
  4912.4     0.1       0  4991.9    0.07       0  4997.9     0.1       0
  5234.9    0.16       0  5364.1     0.1       0
Bank Sta=4991.9,4997.9
Exp/Cntr=0.3,0.1

Type RM Length L Ch R = 1,529,0,0,0
BEGIN DESCRIPTION:
UNT 080 in HW 2.0
END DESCRIPTION:
XS GIS Cut Line= 4
      1986714.82     13673718.12      1987213.93     13673687.74
      1987608.89     13673132.18      1987621.91     13672594.02
#Sta/Elev= 30
  4189.3  905.24  4210.4  904.76  4366.2  902.89  4520.1  901.82  4580.2  900.41
  4630.3  900.67  4680.4  897.36  4699.3  897.31  4705.5  898.83  4714.1  897.80
  4720.2  899.48  4728.8  898.70  4755.9  899.47  4842.0  898.82  4902.3  897.36
  4950.4  896.82  4957.6  895.60  4978.5  895.93  4996.4  894.88  4996.9  894.08
  5001.9  894.08  5002.4  894.88  5049.8  897.09  5057.8  898.31  5094.1  902.38
  5232.5  903.76  5352.4  903.57  5488.6  906.63  5571.3  908.65  5909.3  916.04
#Mann=10,-1,0
  4189.3    0.16       0  4210.4     0.1       0  4366.2    0.16       0
  4902.3     0.1       0  4996.4    0.07       0  5002.4     0.1       0
  5057.8    0.16       0  5232.5     0.1       0  5488.6    0.16       0
  5571.3     0.1       0
Bank Sta=4996.4,5002.4
Exp/Cntr=0.3,0.1

Chan Stop Cuts=-1