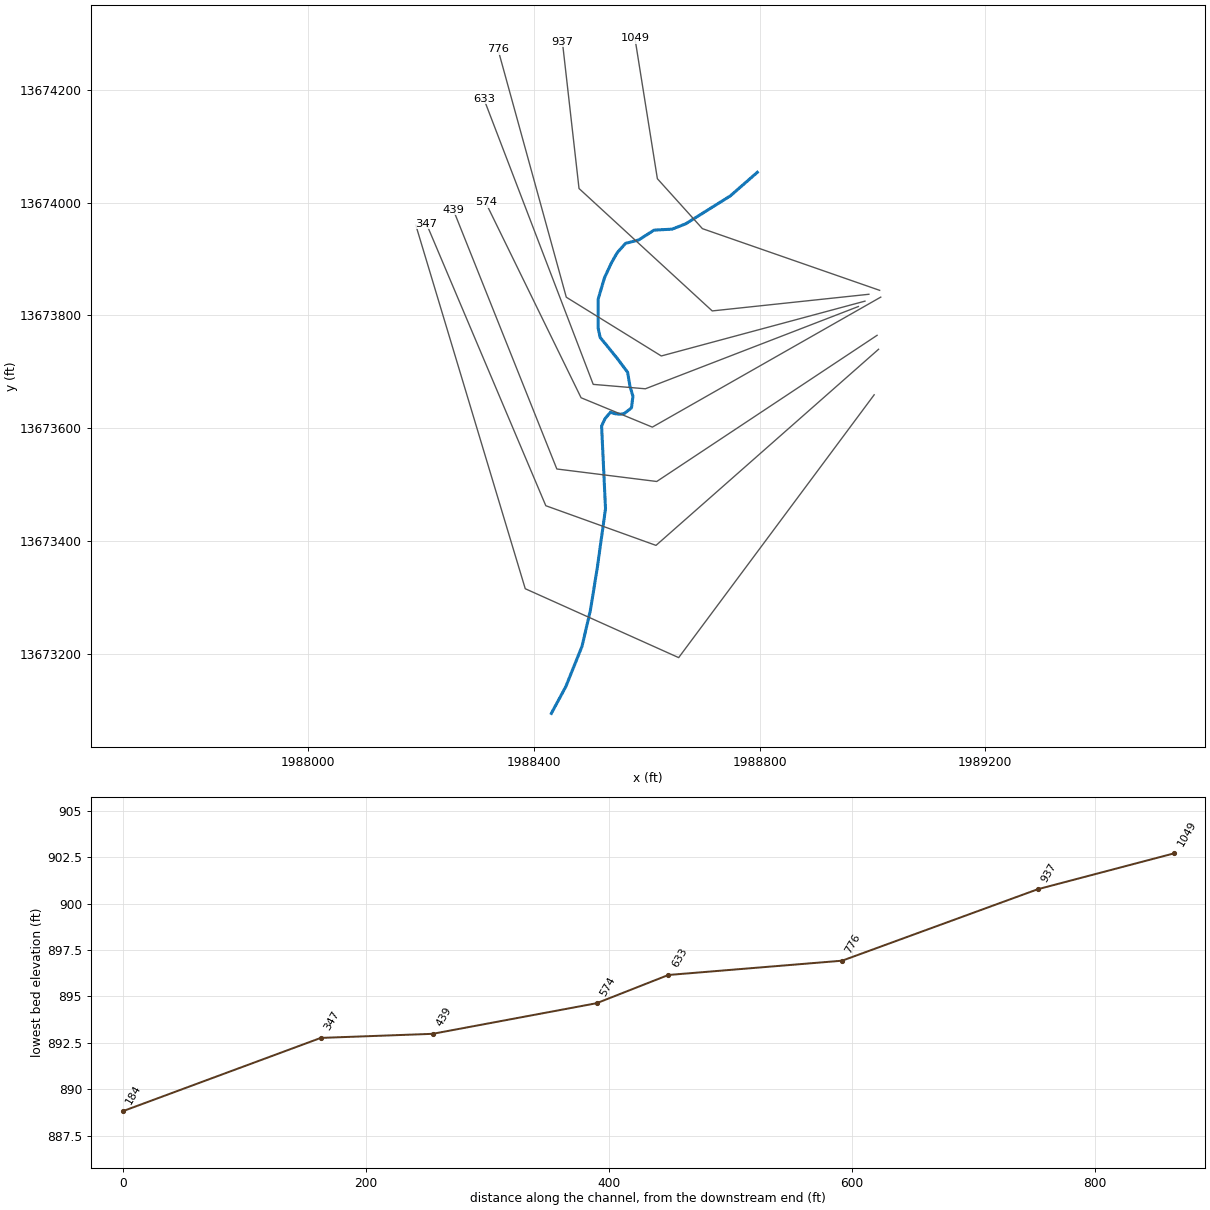
--- UNT 081 in HW.prj (project) ---

Proj Title=UNT 081 in HW Base Level Engineering
Current Plan=p01
Default Exp/Contr=0.3,0.1
English Units
Geom File=g01
Flow File=f01
Plan File=p01
Y Axis Title=Elevation
X Axis Title(PF)=Main Channel Distance
X Axis Title(XS)=Station
BEGIN DESCRIPTION:
UNT 081 in HW
END DESCRIPTION:
DSS Export Rating Curves= 0
DSS Export Rating Curve Sorted= 0
DSS Export Volume Flow Curves= 0
DXF OffsetX= 0
DXF OffsetY= 0
DXF ScaleX= 1
DXF ScaleY= 10

--- UNT 081 in HW.p01 (plan) ---

Plan Title=Multiple Run
Short Identifier=Multiple
Geom File=g01
Flow File=f01
Subcritical Flow
K Sum by GR= 0
Std Step Tol= 0.01
Critical Tol= 0.01
Num of Std Step Trials= 20
Max Error Tol= 0.3
Flow Tol Ratio= 0.001
Split Flow NTrial= 30
Split Flow Tol= 0.02
Split Flow Ratio= 0.02
Log Output Level= 0
Friction Slope Method= 1
Unsteady Friction Slope Method= 2
Unsteady Bridges Friction Slope Method= 1
Parabolic Critical Depth
Global Vel Dist=  1 , 1 , 1
Global Log Level= 0
CheckData=True
Encroach Param= -1, 0, 0, 0
BEGIN DESCRIPTION:
Multiple Run
END DESCRIPTION:

--- UNT 081 in HW.f01 (steady flow) ---

Flow Title=Multiple
Program Version=5.05
Number of Profiles= 7
Profile Names=10-year,25-year,50-year,1pct_min,100-year,1pct_plu,500-year
River Rch & RM=UNT 081 in HW,Reach-1         ,1049
     321     435     526     316     631    1259     908
Boundary for River Rch & Prof#=UNT 081 in HW,Reach-1         , 1
Up Type= 0
Dn Type= 3
Dn Slope=0.005
Boundary for River Rch & Prof#=UNT 081 in HW,Reach-1         , 2
Up Type= 0
Dn Type= 3
Dn Slope=0.005
Boundary for River Rch & Prof#=UNT 081 in HW,Reach-1         , 3
Up Type= 0
Dn Type= 3
Dn Slope=0.005
Boundary for River Rch & Prof#=UNT 081 in HW,Reach-1         , 4
Up Type= 0
Dn Type= 3
Dn Slope=0.005
Boundary for River Rch & Prof#=UNT 081 in HW,Reach-1         , 5
Up Type= 0
Dn Type= 3
Dn Slope=0.005
Boundary for River Rch & Prof#=UNT 081 in HW,Reach-1         , 6
Up Type= 0
Dn Type= 3
Dn Slope=0.005
Boundary for River Rch & Prof#=UNT 081 in HW,Reach-1         , 7
Up Type= 0
Dn Type= 3
Dn Slope=0.005
DSS Import GetInterval= 0
DSS Import GetPeak= 0
DSS Import FillOption= 0

--- UNT 081 in HW.g01 (geometry) ---

Geom Title=Existing Conditions
Program Version=5.05

River Reach=UNT 081 in HW   ,Reach-1
Reach XY= 30
      1988795.88      13674053.6      1988748.13     13674011.93
      1988669.14     13673962.45      1988644.84      13673952.9
      1988612.72     13673951.17      1988585.81      13673933.8
      1988562.37     13673927.73      1988547.61     13673911.24
       1988537.2     13673893.01      1988525.04     13673866.96
      1988513.76     13673828.77      1988513.76     13673777.55
      1988517.23     13673761.06      1988547.61     13673723.74
      1988565.84     13673699.43      1988570.18     13673674.26
      1988575.39     13673656.89      1988572.79     13673636.06
      1988560.63     13673626.51      1988553.69     13673624.78
      1988544.14     13673625.65      1988535.46     13673628.25
      1988525.91     13673616.96      1988519.84     13673603.94
      1988526.78     13673457.24      1988512.02     13673351.34
      1988499.87     13673276.69      1988485.11     13673213.32
      1988456.47     13673142.14       1988430.8     13673094.54

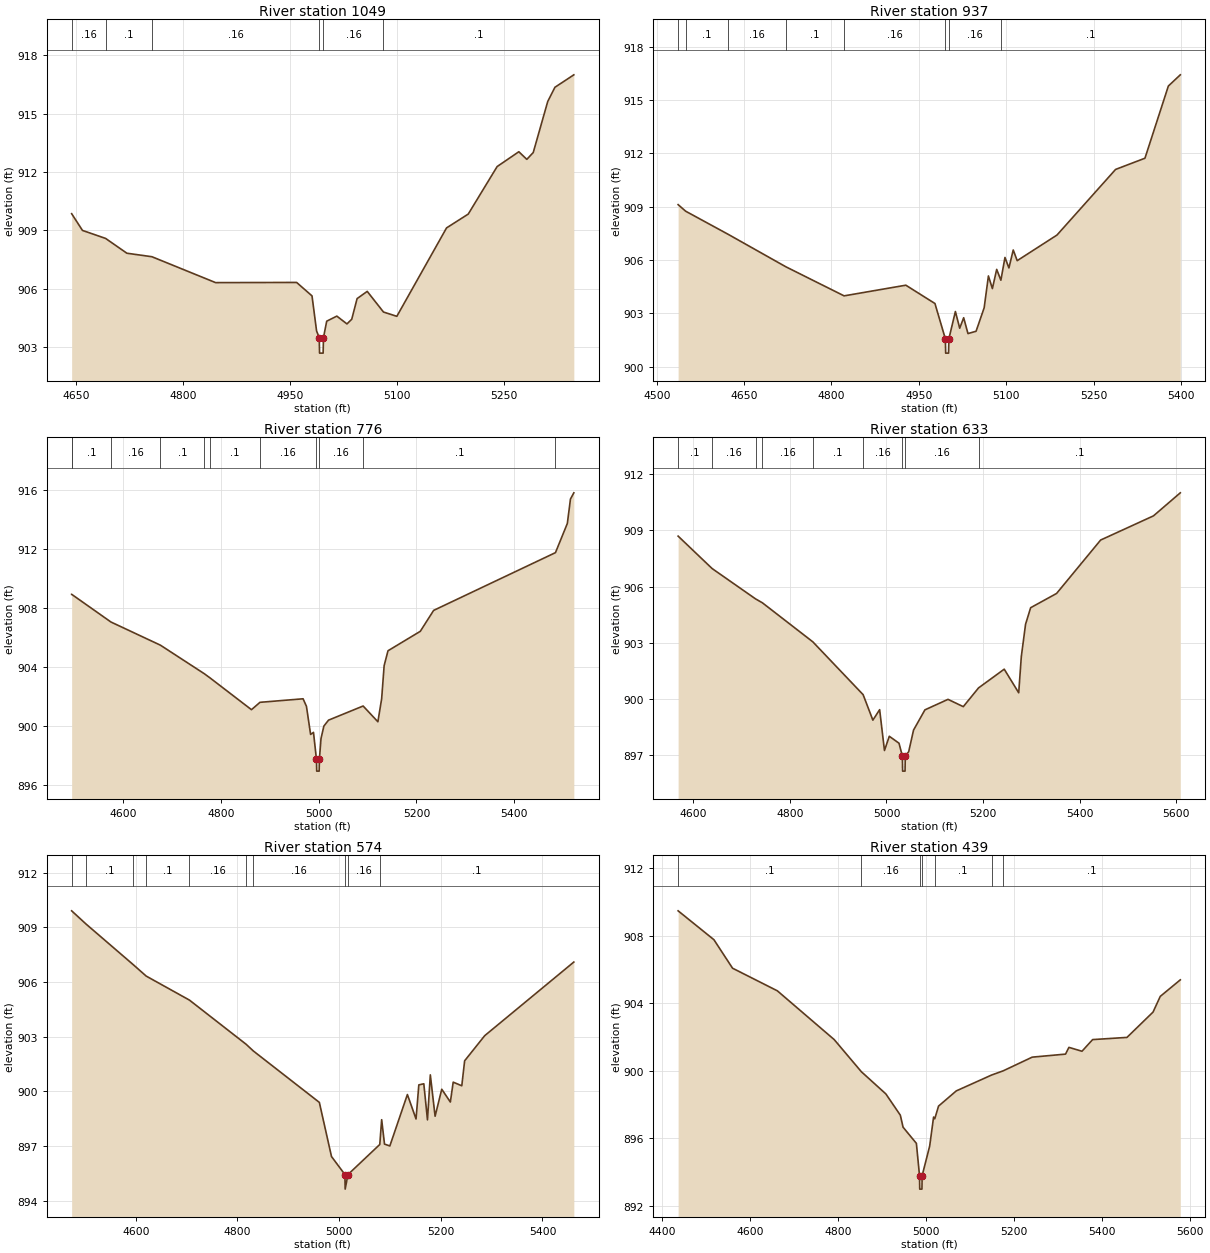
Type RM Length L Ch R = 1 ,1049    ,112,112,112
BEGIN DESCRIPTION:
UNT 081 in HW 5.0
END DESCRIPTION:
XS GIS Cut Line= 4
      1989012.76     13673844.42      1988698.57     13673953.78
      1988618.71     13674042.33      1988578.96     13674291.15
#Sta/Elev= 30
    4644  909.86  4659.2     909  4691.6  908.59  4721.4  907.83  4756.5  907.65
  4845.8  906.32  4959.3  906.33  4980.9  905.64  4987.3  903.84    4991   903.5
  4991.5   902.7  4996.5   902.7    4997   903.5  5001.5  904.34  5015.7   904.6
  5029.9   904.2  5036.6  904.44  5044.1   905.5  5058.3  905.87  5081.1  904.81
  5099.8  904.59  5169.5  909.13  5199.9  909.84  5240.4  912.28  5270.8  913.04
    5282  912.65    5291     913  5311.3  915.62  5321.4  916.35  5347.9  916.99
#Mann= 6 ,-1 , 0
    4644     .16       0  4691.6      .1       0  4756.5     .16       0
    4991     .07       0    4997     .16       0  5081.1      .1       0
Bank Sta=4991,4997
XS Rating Curve= 0 ,0
Exp/Cntr=0.3,0.1

Type RM Length L Ch R = 1 ,937     ,161,161,161
BEGIN DESCRIPTION:
UNT 081 in HW 6.0
END DESCRIPTION:
XS GIS Cut Line= 4
      1988993.72     13673837.47      1988715.93     13673807.95
      1988479.82     13674024.96      1988450.31     13674285.35
#Sta/Elev= 30
  4536.7  909.12  4549.7  908.75  4622.7  907.45  4721.4  905.63  4821.6  903.99
  4927.6  904.59  4977.6  903.56  4995.5  901.57    4996  900.77    5001  900.77
  5001.5  901.57  5012.7  903.11  5020.1  902.17  5026.9  902.76  5034.3  901.87
  5048.2     902  5062.1  903.32  5069.4  905.11  5076.2   904.4  5083.6  905.48
  5090.8  904.87  5097.8  906.15  5104.6  905.56    5112  906.57  5118.8  905.97
  5187.1  907.41  5287.7   911.1  5338.1  911.73  5378.3  915.79  5398.8  916.42
#Mann= 8 ,-1 , 0
  4536.7     .16       0  4549.7      .1       0  4622.7     .16       0
  4721.4      .1       0  4821.6     .16       0  4995.5     .07       0
  5001.5     .16       0  5090.8      .1       0
Bank Sta=4995.5,5001.5
XS Rating Curve= 0 ,0
Exp/Cntr=0.3,0.1

Type RM Length L Ch R = 1 ,776     ,143,143,143
BEGIN DESCRIPTION:
UNT 081 in HW 7.0
END DESCRIPTION:
XS GIS Cut Line= 4
      1988986.73      13673825.3      1988625.65     13673728.09
      1988457.25     13673832.26      1988336.16     13674271.63
#Sta/Elev= 30
  4494.5  908.92  4494.6  908.92    4575  907.04  4676.1  905.47  4765.6  903.54
  4777.2  903.26  4862.5  901.09  4879.9  901.59  4968.1  901.83    4975  901.32
  4983.5  899.41  4989.4  899.55  4995.5  897.72    4996  896.92    5001  896.92
  5001.5  897.72  5004.8  899.13  5010.7  899.98  5020.2  900.38    5091  901.34
  5121.2  900.27  5128.9  901.83    5134  904.08  5141.9  905.09    5208  906.41
  5235.3  907.83  5484.6  911.75  5508.9  913.73  5515.3  915.39  5522.2  915.81
#Mann= 11 ,-1 , 0
  4494.5     .16       0  4494.6      .1       0    4575     .16       0
  4676.1      .1       0  4765.6     .16       0  4777.2      .1       0
  4879.9     .16       0  4995.5     .07       0  5001.5     .16       0
    5091      .1       0  5484.6     .08       0
Bank Sta=4995.5,5001.5
XS Rating Curve= 0 ,0
Exp/Cntr=0.3,0.1

Type RM Length L Ch R = 1 ,633     ,59,59,59
BEGIN DESCRIPTION:
UNT 081 in HW 8.0
END DESCRIPTION:
XS GIS Cut Line= 4
      1988975.03     13673815.76      1988597.44     13673669.93
      1988504.99     13673677.74        1988311.     13674184.21
#Sta/Elev= 30
  4568.5  908.69  4638.9  906.96  4728.9  905.34  4743.1  905.13  4847.4  903.05
  4951.6  900.23  4971.8  898.87  4985.8  899.43  4995.8  897.25  5005.8  898.01
  5025.9  897.64  5032.9  896.95  5033.4  896.15  5038.4  896.15  5038.9  896.95
    5046  897.19    5056  898.34  5079.6  899.42  5127.4  899.98    5159  899.59
  5190.6  900.59  5243.8  901.59  5273.8  900.33  5279.2  902.27    5288  903.99
  5298.5  904.87  5352.2  905.63  5443.4  908.48  5552.8  909.77  5608.4     911
#Mann= 9 ,-1 , 0
  4568.5      .1       0  4638.9     .16       0  4728.9      .1       0
  4743.1     .16       0  4847.4      .1       0  4951.6     .16       0
  5032.9     .07       0  5038.9     .16       0  5190.6      .1       0
Bank Sta=5032.9,5038.9
XS Rating Curve= 0 ,0
Exp/Cntr=0.3,0.1

Type RM Length L Ch R = 1 ,574     ,135,135,135
BEGIN DESCRIPTION:
UNT 081 in HW 4.0
END DESCRIPTION:
XS GIS Cut Line= 4
      1989014.72     13673832.43      1988609.77     13673601.96
      1988483.46     13673654.04      1988314.31     13674000.16
#Sta/Elev= 30
  4473.9   909.9    4502  909.18  4594.5  906.96  4620.5  906.32  4705.7     905
    4817  902.58  4831.3  902.21  4961.1  899.39    4985  896.42  5011.4  895.43
  5011.9  894.63  5017.4  895.43    5080  897.08  5083.7  898.44  5089.3   897.1
  5099.8     897  5134.3  899.82  5151.3  898.48  5156.8  900.35  5166.6  900.41
  5173.8  898.43  5179.4   900.9  5188.8  898.63  5201.9  900.11  5218.8  899.41
  5224.4   900.5  5241.3   900.3  5246.9  901.67  5286.4  903.05  5461.7  907.09
#Mann= 10 ,-1 , 0
  4473.9     .16       0    4502      .1       0  4594.5     .16       0
  4620.5      .1       0  4705.7     .16       0    4817      .1       0
  4831.3     .16       0  5011.4     .07       0  5017.4     .16       0
    5080      .1       0
Bank Sta=5011.4,5017.4
XS Rating Curve= 0 ,0
Exp/Cntr=0.3,0.1

Type RM Length L Ch R = 1 ,439     ,92,92,92
BEGIN DESCRIPTION:
UNT 081 in HW 3.0
END DESCRIPTION:
XS GIS Cut Line= 4
      1989008.19     13673764.71      1988617.58     13673505.61
       1988440.5     13673527.74      1988256.92     13673987.34
#Sta/Elev= 30
  4436.9  909.47  4518.3  907.76  4560.7  906.07  4662.6  904.73  4791.9  901.84
  4853.5  899.94  4909.4  898.62  4942.3  897.36  4948.5  896.65  4978.8  895.69
  4985.9  893.78  4986.4  892.98  4991.4  892.98  4991.9  893.78    5009  895.53
  5017.9  897.25  5020.6  897.15  5029.2   897.9  5069.5   898.8  5149.8  899.74
  5176.3  899.99  5242.2   900.8    5318  900.98  5325.7  901.38  5355.4  901.15
  5379.6  901.84  5457.7  901.97    5517  903.47  5533.4   904.4    5579  905.38
#Mann= 7 ,-1 , 0
  4436.9      .1       0  4853.5     .16       0  4985.9     .07       0
  4991.9     .16       0  5020.6      .1       0  5149.8     .16       0
  5176.3      .1       0
Bank Sta=4985.9,4991.9
XS Rating Curve= 0 ,0
Exp/Cntr=0.3,0.1

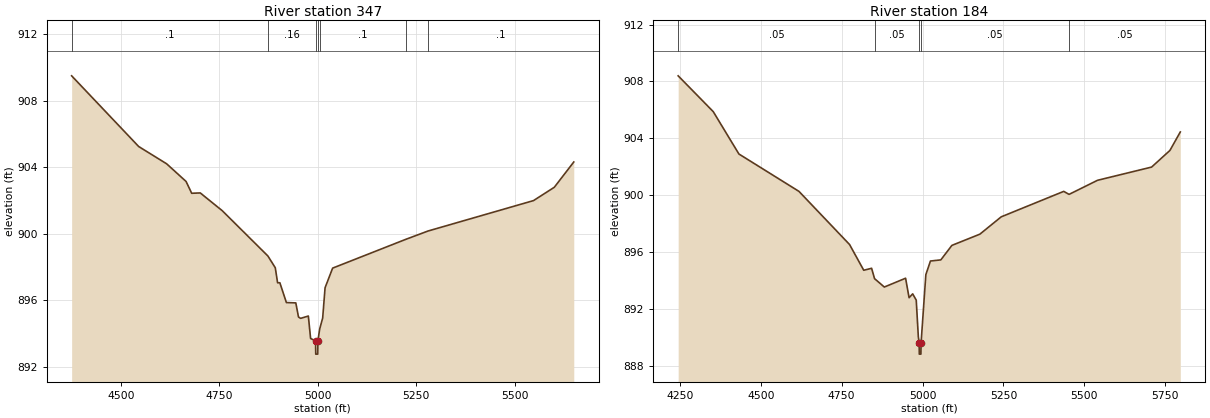
Type RM Length L Ch R = 1 ,347     ,163,163,163
BEGIN DESCRIPTION:
UNT 081 in HW 2.0
END DESCRIPTION:
XS GIS Cut Line= 4
      1989010.82     13673739.99      1988616.28     13673392.33
      1988420.96     13673462.64      1988209.36     13673962.44
#Sta/Elev= 30
  4374.4  909.49  4544.8  905.24  4615.9   904.2  4665.2  903.14  4679.5  902.43
  4701.3  902.45  4757.3  901.38  4873.2  898.66    4892  897.95  4897.8  897.05
  4903.6  897.05  4920.2  895.86  4944.1  895.84    4951  894.99  4956.3  894.91
    4976  895.05  4981.7   893.7  4994.3  893.56  4994.8  892.76  4999.8  892.76
  5000.3  893.56  5004.8  894.27  5012.4  894.93  5018.5  896.75  5037.7  897.93
  5223.6  899.66  5280.1  900.16  5548.3  901.99  5601.1  902.79  5650.6  904.31
#Mann= 7 ,-1 , 0
  4374.4      .1       0  4873.2     .16       0  4994.3     .07       0
  5000.3     .16       0  5004.8      .1       0  5223.6     .16       0
  5280.1      .1       0
Bank Sta=4994.3,5000.3
XS Rating Curve= 0 ,0
Exp/Cntr=0.3,0.1

Type RM Length L Ch R = 1 ,184     ,0,0,0
BEGIN DESCRIPTION:
UNT 081 in HW 1.0
END DESCRIPTION:
XS GIS Cut Line= 4
        1989003.     13673659.25      1988656.47     13673193.37
      1988384.51      13673315.5      1988190.51     13673959.98
#Sta/Elev= 30
  4244.7  908.39  4353.1  905.87  4432.4  902.89    4618  900.26  4774.4  896.52
  4818.2  894.71  4842.5  894.85  4851.6  894.12  4881.8  893.53  4947.5  894.15
  4958.3  892.78  4969.4  893.05  4980.4  892.61  4986.9  890.03  4989.4  889.61
  4989.9  888.81  4994.9  888.81  4995.4  889.61  5010.1   894.4  5024.3  895.36
  5056.4  895.44  5090.6  896.46  5177.1  897.25  5243.1  898.47  5436.2  900.26
  5452.8  900.05  5540.7  901.04  5707.8  901.97  5764.4  903.14  5796.5  904.44
#Mann= 5 ,-1 , 0
  4244.7     .05       0  4851.6     .05       0  4989.4     .03       0
  4995.4     .05       0  5452.8     .05       0
Bank Sta=4989.4,4995.4
XS Rating Curve= 0 ,0
Exp/Cntr=0.3,0.1
LCMann Table=0

Chan Stop Cuts=-1
Use User Specified Reach Order=0
Composite Channel Slope=5