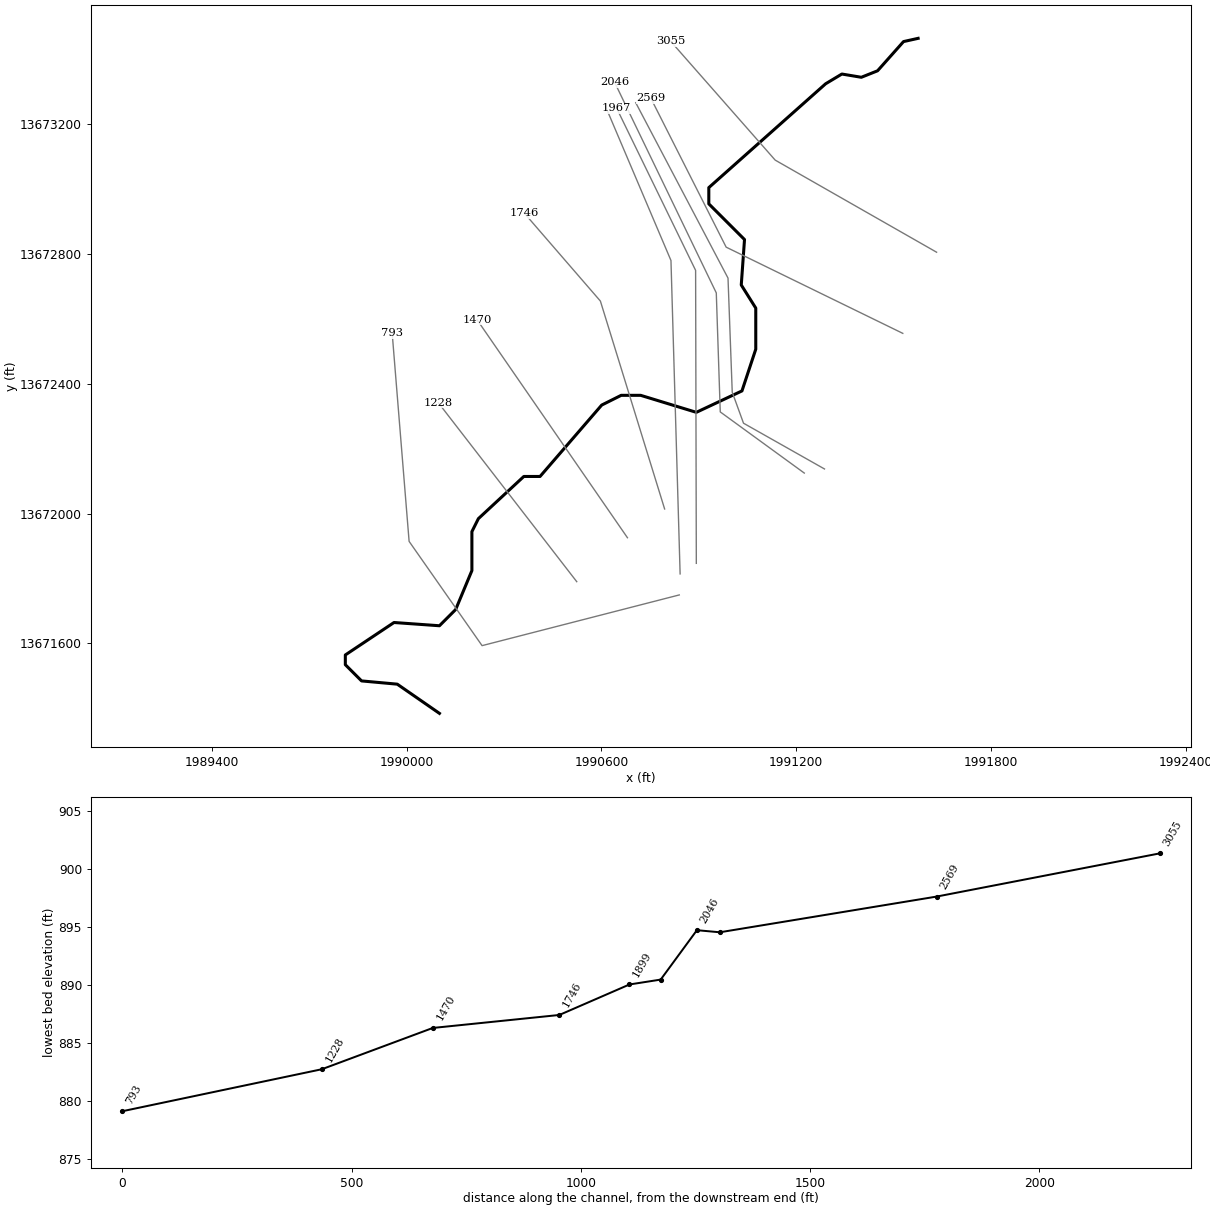
--- UNT 082 in HW.prj (project) ---

Proj Title=UNT 082 in HW Base Level Engineering
Current Plan=p01
Default Exp/Contr=0.3,0.1
English Units
Geom File=g01
Flow File=f01
Plan File=p01
BEGIN DESCRIPTION:
UNT 082 in HW
END DESCRIPTION:

--- UNT 082 in HW.p01 (plan) ---

Plan Title=Multiple Run
Short Identifier=Multiple
Geom File=g01
Flow File=f01
Subcritical Flow
K Sum by GR= 0
Std Step Tol= 0.01
Critical Tol= 0.01
Num of Std Step Trials= 20
Max Error Tol= 0.3
Flow Tol Ratio= 0.001
Split Flow NTrial= 30
Split Flow Tol= 0.02
Split Flow Ratio= 0.02
Log Output Level= 0
Friction Slope Method= 1
Unsteady Friction Slope Method= 2
Unsteady Bridges Friction Slope Method= 1
Parabolic Critical Depth
Global Vel Dist=  1 , 1 , 1
Global Log Level= 0
CheckData=True
Encroach Param= -1, 0, 0, 0
BEGIN DESCRIPTION:
Multiple Run
END DESCRIPTION:

--- UNT 082 in HW.f01 (steady flow) ---

Flow Title=Multiple
Number of Profiles=7
Profile Names=10-year,25-year,50-year,1pct_min,100-year,1pct_plu,500-year
River Rch & RM= UNT 082 in HW,Reach-1,3055
     434     598     734     446     890    1776    1313
Boundary for River Rch & Prof#=UNT 082 in HW,Reach-1,1
Up Type=0
Dn Type=3
Dn Slope=0.005
Boundary for River Rch & Prof#=UNT 082 in HW,Reach-1,2
Up Type=0
Dn Type=3
Dn Slope=0.005
Boundary for River Rch & Prof#=UNT 082 in HW,Reach-1,3
Up Type=0
Dn Type=3
Dn Slope=0.005
Boundary for River Rch & Prof#=UNT 082 in HW,Reach-1,4
Up Type=0
Dn Type=3
Dn Slope=0.005
Boundary for River Rch & Prof#=UNT 082 in HW,Reach-1,5
Up Type=0
Dn Type=3
Dn Slope=0.005
Boundary for River Rch & Prof#=UNT 082 in HW,Reach-1,6
Up Type=0
Dn Type=3
Dn Slope=0.005
Boundary for River Rch & Prof#=UNT 082 in HW,Reach-1,7
Up Type=0
Dn Type=3
Dn Slope=0.005

--- UNT 082 in HW.g01 (geometry) ---

Geom Title=Existing Conditions
Program Version=5.05

River Reach=UNT 082 in HW   ,Reach-1
Reach XY= 30
       1991575.8     13673464.54       1991530.8     13673454.54
       1991450.8     13673364.54       1991400.8     13673344.54
       1991340.8     13673354.54       1991290.8     13673324.54
       1990930.8     13673004.54       1990930.8     13672954.54
       1991040.8     13672844.54       1991030.8     13672704.54
      1991075.49     13672633.33      1991075.49     13672506.59
      1991032.96     13672378.12      1990892.33     13672312.15
       1990720.8     13672364.54       1990660.8     13672364.54
       1990600.8     13672334.54       1990410.8     13672114.54
       1990360.8     13672114.54       1990220.8     13671984.54
       1990200.8     13671944.54       1990200.8     13671824.54
       1990150.8     13671704.54       1990100.8     13671654.54
       1989960.8     13671664.54       1989810.8     13671564.54
       1989810.8     13671534.54       1989860.8     13671484.54
       1989970.8     13671474.54       1990100.8     13671384.54

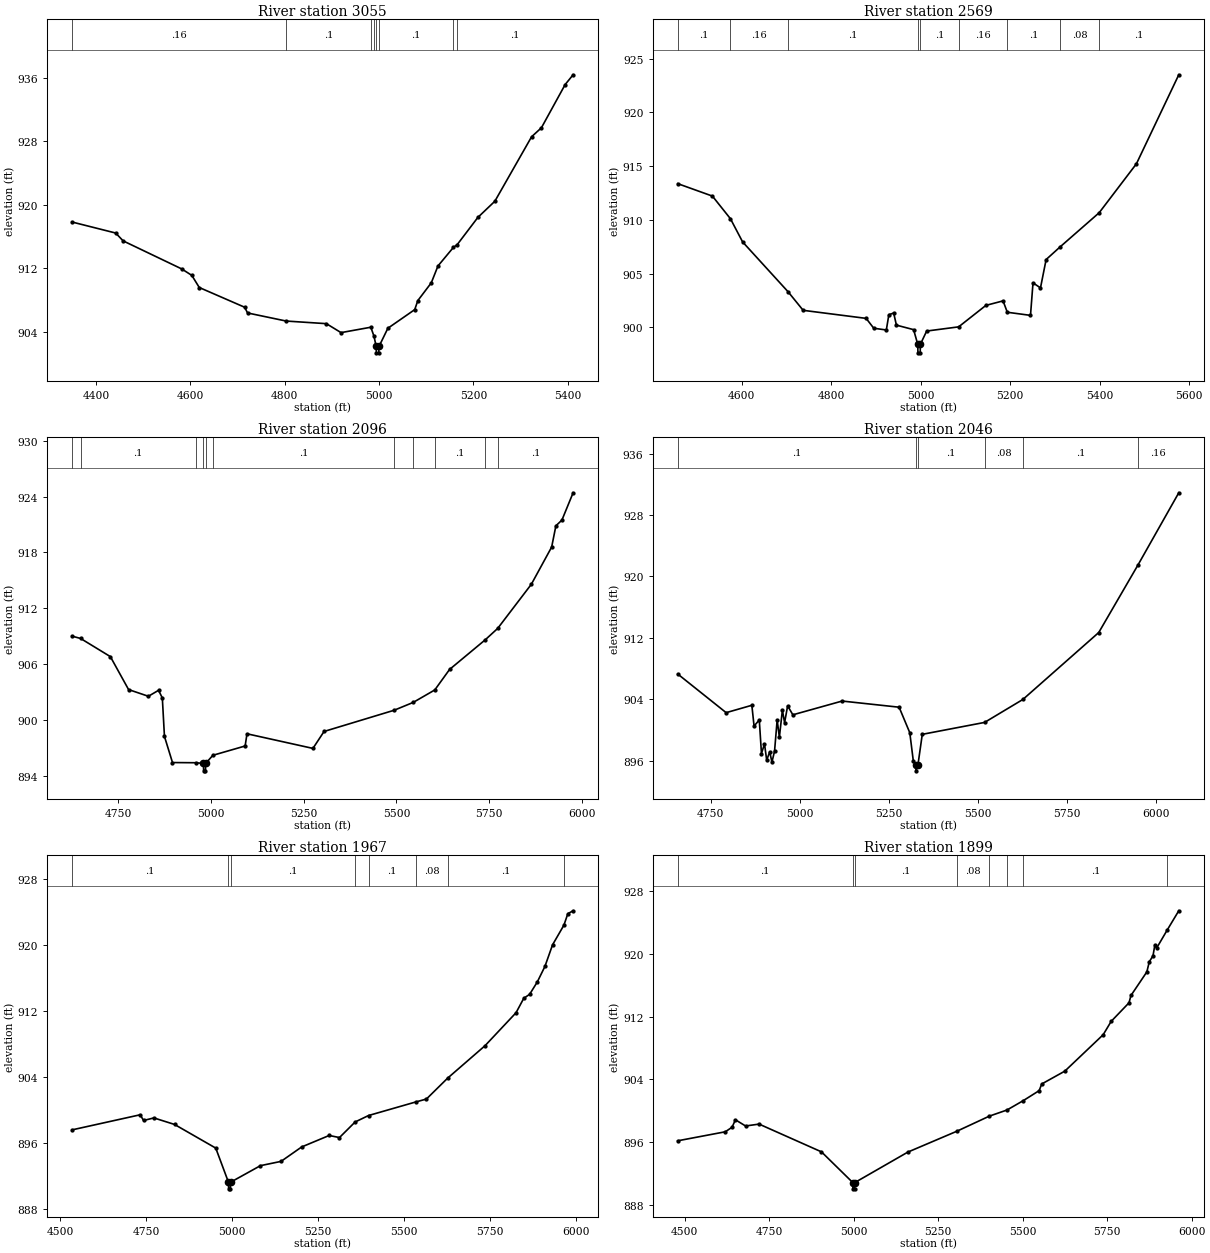
Type RM Length L Ch R = 1 ,3055    ,486,486,486
BEGIN DESCRIPTION:
UNT 082 in HW 3.0
END DESCRIPTION:
XS GIS Cut Line= 3
      1991632.67     13672805.49      1991135.28     13673089.34
      1990812.34     13673456.55
#Sta/Elev= 30
  4349.6  917.83  4442.1  916.44  4457.9  915.45  4581.8  911.92  4603.4   911.1
  4619.2  909.57  4715.4  907.08  4721.5  906.36  4803.3  905.34  4888.5  905.01
  4919.6  903.88  4982.7  904.56  4989.5  903.41    4994  902.13  4994.5  901.33
  4999.5  901.33    5000  902.13  5018.8  904.43  5075.7  906.78  5082.3  907.92
  5110.8  910.16    5125  912.29  5157.7  914.63  5165.5  914.96  5209.5  918.41
  5245.5  920.45  5323.3  928.58  5344.2  929.72  5394.5  935.17  5411.3   936.4
#Mann= 8 ,-1 , 0
  4349.6     .16       0  4803.3      .1       0  4982.7     .16       0
  4989.5      .1       0    4994     .07       0    5000      .1       0
  5157.7     .16       0  5165.5      .1       0
Bank Sta=4994,5000
XS Rating Curve= 0 ,0
Exp/Cntr=0.3,0.1

Type RM Length L Ch R = 1 ,2569    ,473,473,473
BEGIN DESCRIPTION:
Mapping XS 52c8dfb2
END DESCRIPTION:
XS GIS Cut Line= 3
      1991528.52     13672555.49      1990984.24     13672821.11
      1990752.49     13673279.41
#Sta/Elev= 30
  4457.3  913.37  4534.8  912.21  4575.1   910.1  4602.3  907.94  4703.8   903.3
  4737.5  901.57  4878.2  900.82  4895.2   899.9  4923.3  899.74  4928.9  901.16
  4939.7  901.32  4945.8  900.19  4984.2  899.77  4993.4  898.41  4993.9  897.61
  4998.9  897.61  4999.4  898.41  5013.4  899.64  5084.8  900.03  5145.7  902.03
    5184  902.45  5193.5  901.39  5245.3   901.1  5250.9  904.13  5267.6  903.66
  5280.2   906.3  5311.2  907.47  5398.7  910.66  5481.9  915.22  5576.5  923.51
#Mann= 9 ,-1 , 0
  4457.3      .1       0  4575.1     .16       0  4703.8      .1       0
  4993.4     .07       0  4999.4      .1       0  5084.8     .16       0
  5193.5      .1       0  5311.2     .08       0  5398.7      .1       0
Bank Sta=4993.4,4999.4
XS Rating Curve= 0 ,0
Exp/Cntr=0.3,0.1

Type RM Length L Ch R = 1 ,2096    ,50,50,50
BEGIN DESCRIPTION:
Mapping XS f6c4e313
END DESCRIPTION:
XS GIS Cut Line= 5
      1991287.24     13672137.63      1991037.71     13672278.66
      1991002.99     13672374.15      1990989.97     13672725.71
      1990705.69     13673266.06
#Sta/Elev= 30
  4625.6     909  4648.7  908.75  4728.9   906.8    4778  903.26  4831.4  902.54
  4858.8  903.18    4869  902.36  4874.7  898.23  4896.4  895.42  4958.6   895.4
  4979.8  895.33  4980.3  894.53  4985.3  894.53  4985.8  895.33  5005.3   896.2
  5092.2   897.2  5097.2  898.51  5274.9  896.94  5304.9  898.76  5493.9  901.04
  5545.2  901.88  5603.4  903.22  5643.2  905.42  5739.5  908.61  5772.9  909.83
  5863.6  914.57  5918.4  918.57  5929.8  920.85  5946.1  921.47  5976.2   924.4
#Mann= 11 ,-1 , 0
  4625.6     .16       0  4648.7      .1       0  4958.6     .05       0
  4979.8    .035       0  4985.8     .05       0  5005.3      .1       0
  5493.9     .16       0  5545.2     .08       0  5603.4      .1       0
  5739.5     .08       0  5772.9      .1       0
Bank Sta=4979.8,4985.8
XS Rating Curve= 0 ,0
Exp/Cntr=0.3,0.1

Type RM Length L Ch R = 1 ,2046    ,79,79,79
BEGIN DESCRIPTION:
UNT 082 in HW 2.0
END DESCRIPTION:
XS GIS Cut Line= 4
      1991225.03     13672124.98       1990966.1     13672313.39
      1990953.83     13672680.17      1990640.58       13673329.
#Sta/Elev= 30
  4657.4  907.31  4793.5  902.28  4865.7  903.24  4871.9  900.54  4886.6  901.33
  4892.7  896.96  4901.2  898.22  4907.4   896.1  4915.9  897.19  4922.1  895.84
  4929.5  897.28  4936.8  901.34    4943  899.08  4951.5   902.6  4957.7  900.97
  4966.2  903.17  4980.9     902  5119.3  903.79  5279.4  902.99  5309.4  899.67
  5319.4  895.96  5326.4  895.51  5326.9  894.71  5332.4  895.51  5344.5  899.46
  5519.5  901.01  5627.2     904  5840.3  912.71  5950.4  921.49  6065.1  930.89
#Mann= 6 ,-1 , 0
  4657.4      .1       0  5326.4     .07       0  5332.4      .1       0
  5519.5     .08       0  5627.2      .1       0  5950.4     .16       0
Bank Sta=5326.4,5332.4
XS Rating Curve= 0 ,0
Exp/Cntr=0.3,0.1

Type RM Length L Ch R = 1 ,1967    ,68,68,68
BEGIN DESCRIPTION:
Mapping XS 614d532e
END DESCRIPTION:
XS GIS Cut Line= 3
      1990892.31     13671846.79      1990890.14     13672749.58
      1990647.07     13673248.75
#Sta/Elev= 30
  4534.2   897.6  4732.4  899.43  4742.4  898.74  4772.4  899.05  4832.4  898.26
  4952.4  895.39  4989.4  891.25  4989.9  890.45  4994.9  890.45  4995.4  891.25
  5082.4  893.26  5142.4  893.78  5202.4  895.53  5282.4  896.92  5312.4  896.67
    5358  898.56  5396.9  899.34  5533.9  900.98  5565.4  901.34  5627.3  903.88
    5736  907.81  5826.2  911.81  5848.7  913.56  5865.7  914.04  5887.9  915.53
  5910.2  917.42  5932.4  920.04  5965.5  922.43  5976.9  923.82  5992.2  924.17
#Mann= 8 ,-1 , 0
  4534.2      .1       0  4989.4     .07       0  4995.4      .1       0
    5358     .08       0  5396.9      .1       0  5533.9     .08       0
  5627.3      .1       0  5965.5     .16       0
Bank Sta=4989.4,4995.4
XS Rating Curve= 0 ,0
Exp/Cntr=0.3,0.1

Type RM Length L Ch R = 1 ,1899    ,153,153,153
BEGIN DESCRIPTION:
Mapping XS 638f204a
END DESCRIPTION:
XS GIS Cut Line= 3
       1990842.4     13671814.26      1990814.19     13672779.97
      1990612.35     13673255.27
#Sta/Elev= 30
  4479.5  896.16  4620.3  897.31  4640.3  897.89  4650.3  898.84  4680.3  898.05
  4720.3  898.29  4904.8  894.75  4997.5  890.83    4998  890.03    5003  890.03
  5003.5  890.83  5160.5  894.72  5305.4  897.38  5401.7  899.31  5453.8  900.09
  5502.5   901.3  5548.9  902.56  5556.5  903.41  5624.9  905.05  5738.4   909.7
    5762   911.4  5814.8  913.77  5820.5   914.7  5867.5  917.71  5874.8  919.01
  5885.7  919.76  5891.2  921.14  5896.6  920.76  5927.7  923.05    5962  925.51
#Mann= 8 ,-1 , 0
  4479.5      .1       0  4997.5     .07       0  5003.5      .1       0
  5305.4     .08       0  5401.7      .1       0  5453.8     .16       0
  5502.5      .1       0  5927.7     .16       0
Bank Sta=4997.5,5003.5
XS Rating Curve= 0 ,0
Exp/Cntr=0.3,0.1

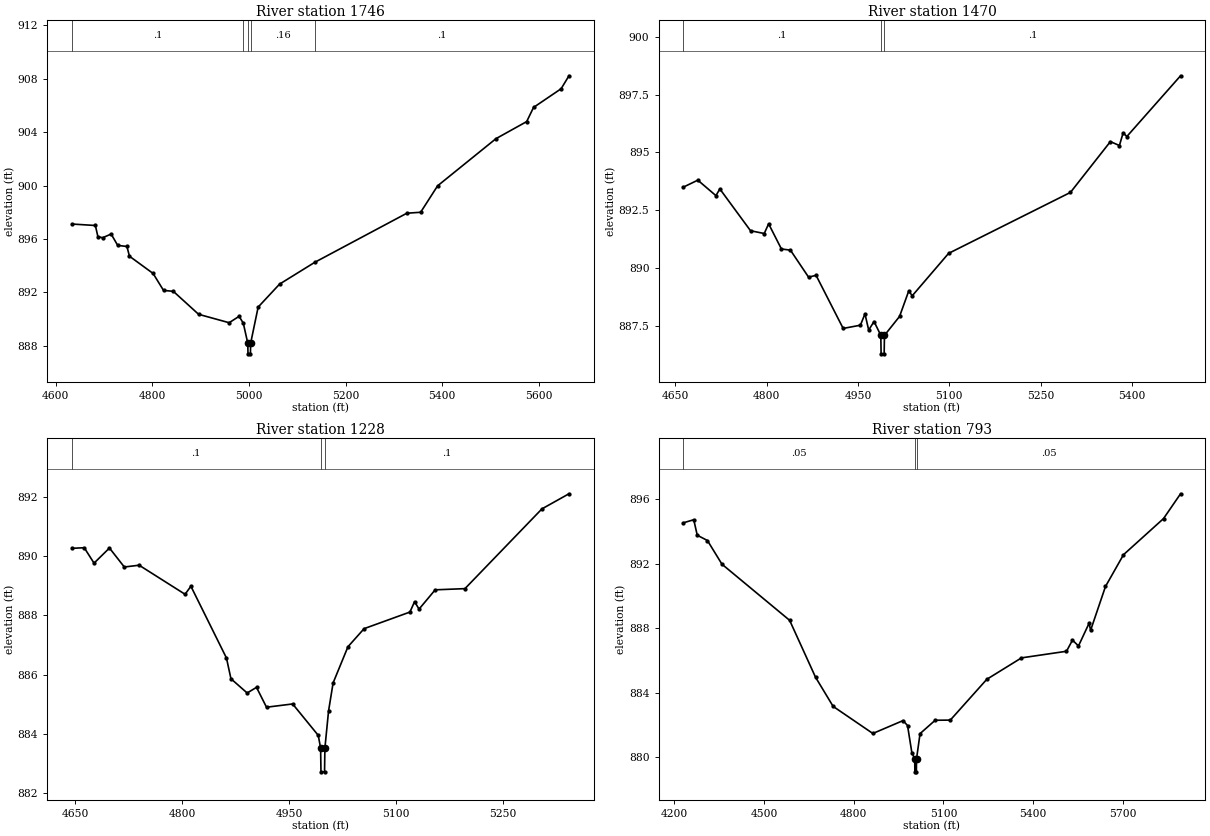
Type RM Length L Ch R = 1 ,1746    ,276,276,276
BEGIN DESCRIPTION:
Mapping XS 2864ff3c
END DESCRIPTION:
XS GIS Cut Line= 3
      1990794.65     13672014.37      1990596.74     13672654.97
      1990362.39     13672925.77
#Sta/Elev= 30
  4633.5  897.12  4682.2  897.01  4687.4  896.18    4697  896.09  4714.8  896.37
  4728.4  895.52  4747.5  895.44  4752.7  894.71  4801.6  893.42  4823.2  892.15
  4843.5  892.08  4895.8  890.36    4959  889.73  4979.6  890.21  4988.3  889.69
  4997.5   888.2    4998   887.4    5003   887.4  5003.5   888.2    5019   890.9
  5063.3  892.62  5136.5  894.26  5326.7  897.93  5355.2     898  5390.3  899.98
    5511  903.51  5574.6  904.79  5588.8  905.85  5645.9  907.25  5662.1  908.22
#Mann= 5 ,-1 , 0
  4633.5      .1       0  4988.3     .16       0  4997.5     .07       0
  5003.5     .16       0  5136.5      .1       0
Bank Sta=4997.5,5003.5
XS Rating Curve= 0 ,0
Exp/Cntr=0.3,0.1

Type RM Length L Ch R = 1 ,1470    ,242,242,242
BEGIN DESCRIPTION:
Mapping XS dd72bdb2
END DESCRIPTION:
XS GIS Cut Line= 2
       1990680.1     13671925.77      1990216.53     13672597.67
#Sta/Elev= 30
  4663.5   893.5  4687.1   893.8  4716.9  893.13  4723.3  893.42  4773.7  891.61
  4796.2  891.49  4803.4  891.91  4824.4  890.82  4839.2  890.77    4869   889.6
  4881.3  889.68  4925.8  887.38  4954.1  887.52  4961.6  888.01  4967.7  887.31
  4976.5  887.68  4987.6  887.08  4988.1  886.28  4993.1  886.28  4993.6  887.08
  5018.4   887.9  5033.3  888.99  5039.4   888.8  5098.9  890.63    5299  893.27
  5364.6  895.47  5379.4   895.3  5385.5  895.85  5391.6  895.69  5479.8  898.32
#Mann= 3 ,-1 , 0
  4663.5      .1       0  4987.6     .07       0  4993.6      .1       0
Bank Sta=4987.6,4993.6
XS Rating Curve= 0 ,0
Exp/Cntr=0.3,0.1

Type RM Length L Ch R = 1 ,1228    ,435,435,435
BEGIN DESCRIPTION:
Mapping XS 9be809a1
END DESCRIPTION:
XS GIS Cut Line= 2
      1990523.82     13671790.39      1990097.71     13672341.22
#Sta/Elev= 30
  4645.6  890.26    4663  890.28  4676.7  889.76  4698.3  890.27  4719.1  889.63
  4739.9  889.69  4804.2  888.71  4812.4  888.98  4862.2  886.56  4868.5  885.86
  4891.2  885.38  4904.3  885.57  4918.3   884.9  4954.9  885.01  4990.8  883.95
  4994.1  883.52  4994.6  882.72  4999.6  882.72  5000.1  883.52  5005.2  884.77
  5011.6  885.72  5032.4  886.94    5055  887.55  5119.2  888.11  5125.7  888.46
    5132  888.21  5154.6  888.86  5196.3   888.9  5304.1  891.59    5342   892.1
#Mann= 3 ,-1 , 0
  4645.6      .1       0  4994.1     .07       0  5000.1      .1       0
Bank Sta=4994.1,5000.1
XS Rating Curve= 0 ,0
Exp/Cntr=0.3,0.1

Type RM Length L Ch R = 1 ,793     ,0,0,0
BEGIN DESCRIPTION:
UNT 082 in HW 1.0
END DESCRIPTION:
XS GIS Cut Line= 4
      1990839.79      13671749.5      1990232.16     13671593.25
      1990007.33     13671914.52      1989955.24     13672555.18
#Sta/Elev= 30
  4230.7  894.55  4265.2  894.74  4276.9  893.78    4311  893.45  4359.6  891.98
  4585.8   888.5  4672.4  884.97  4731.3  883.16  4864.1  881.48  4965.2  882.28
  4980.1  881.97  4994.5  880.29  5004.1   879.9  5004.6   879.1  5009.6   879.1
  5010.1   879.9  5021.9  881.47  5072.5   882.3  5123.1  882.31  5245.1  884.84
  5361.1  886.17  5511.6  886.58  5531.6  887.27  5551.7  886.91  5587.2  888.32
  5592.2  887.88    5642   890.6  5702.2  892.57    5836  894.81    5893  896.35
#Mann= 3 ,-1 , 0
  4230.7     .05       0  5004.1     .03       0  5010.1     .05       0
Bank Sta=5004.1,5010.1
XS Rating Curve= 0 ,0
Exp/Cntr=0.3,0.1
LCMann Table=0

Chan Stop Cuts=-1
Use User Specified Reach Order=0
Composite Channel Slope=5