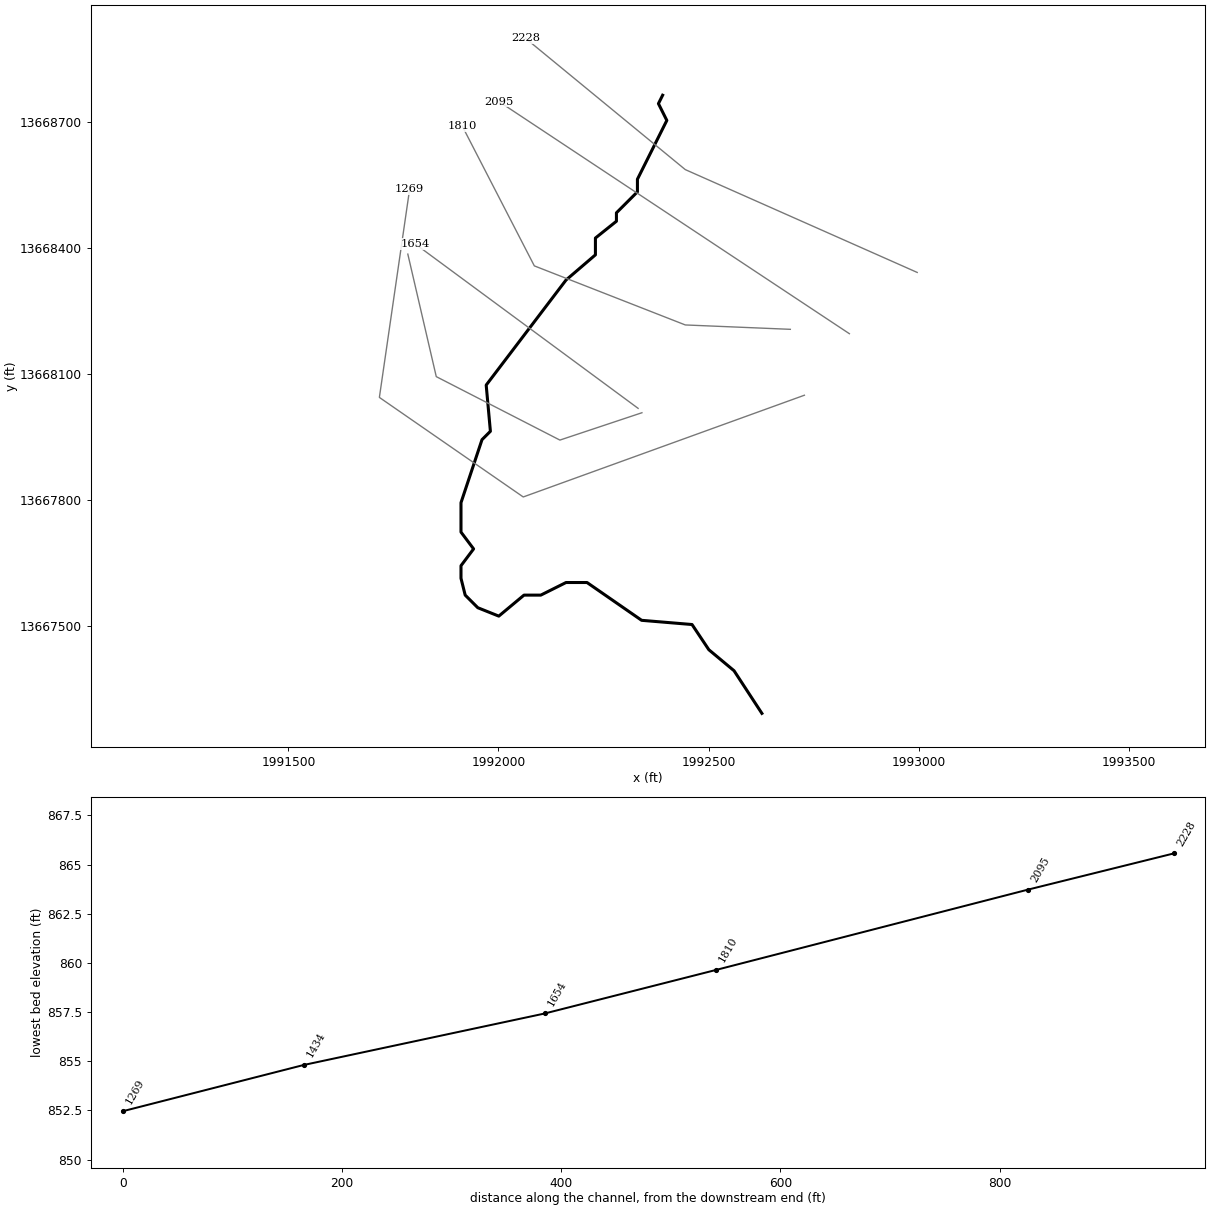
--- UNT 083 in HW.prj (project) ---

Proj Title=UNT 083 in HW Base Level Engineering
Current Plan=p01
Default Exp/Contr=0.3,0.1
English Units
Geom File=g01
Flow File=f01
Plan File=p01
BEGIN DESCRIPTION:
UNT 083 in HW
END DESCRIPTION:

--- UNT 083 in HW.p01 (plan) ---

Plan Title=Multiple Run
Short Identifier=Multiple
Geom File=g01
Flow File=f01
Subcritical Flow
K Sum by GR= 0
Std Step Tol= 0.01
Critical Tol= 0.01
Num of Std Step Trials= 20
Max Error Tol= 0.3
Flow Tol Ratio= 0.001
Split Flow NTrial= 30
Split Flow Tol= 0.02
Split Flow Ratio= 0.02
Log Output Level= 0
Friction Slope Method= 1
Unsteady Friction Slope Method= 2
Unsteady Bridges Friction Slope Method= 1
Parabolic Critical Depth
Global Vel Dist=  1 , 1 , 1
Global Log Level= 0
CheckData=True
Encroach Param= -1, 0, 0, 0
BEGIN DESCRIPTION:
Multiple Run
END DESCRIPTION:

--- UNT 083 in HW.f01 (steady flow) ---

Flow Title=Multiple
Number of Profiles=7
Profile Names=10-year,25-year,50-year,1pct_min,100-year,1pct_plu,500-year
River Rch & RM= UNT 083 in HW,Reach-1,2228
     340     464     565     341     681    1359     993
Boundary for River Rch & Prof#=UNT 083 in HW,Reach-1,1
Up Type=0
Dn Type=3
Dn Slope=0.005
Boundary for River Rch & Prof#=UNT 083 in HW,Reach-1,2
Up Type=0
Dn Type=3
Dn Slope=0.005
Boundary for River Rch & Prof#=UNT 083 in HW,Reach-1,3
Up Type=0
Dn Type=3
Dn Slope=0.005
Boundary for River Rch & Prof#=UNT 083 in HW,Reach-1,4
Up Type=0
Dn Type=3
Dn Slope=0.005
Boundary for River Rch & Prof#=UNT 083 in HW,Reach-1,5
Up Type=0
Dn Type=3
Dn Slope=0.005
Boundary for River Rch & Prof#=UNT 083 in HW,Reach-1,6
Up Type=0
Dn Type=3
Dn Slope=0.005
Boundary for River Rch & Prof#=UNT 083 in HW,Reach-1,7
Up Type=0
Dn Type=3
Dn Slope=0.005

--- UNT 083 in HW.g01 (geometry) ---

Geom Title=Existing Conditions

River Reach=UNT 083 in HW,Reach-1
Reach XY= 30
      1992390.80     13668764.54      1992380.80     13668744.54
      1992400.80     13668704.54      1992330.80     13668564.54
      1992330.80     13668534.54      1992280.80     13668484.54
      1992280.80     13668464.54      1992230.80     13668424.54
      1992230.80     13668384.54      1992160.80     13668324.54
      1991970.80     13668074.54      1991980.80     13667964.54
      1991960.80     13667944.54      1991910.80     13667794.54
      1991910.80     13667724.54      1991940.80     13667684.54
      1991910.80     13667644.54      1991910.80     13667614.54
      1991920.80     13667574.54      1991950.80     13667544.54
      1992000.80     13667524.54      1992060.80     13667574.54
      1992100.80     13667574.54      1992160.80     13667604.54
      1992210.80     13667604.54      1992340.80     13667514.54
      1992460.80     13667504.54      1992500.80     13667444.54
      1992560.80     13667394.54      1992627.09     13667293.03

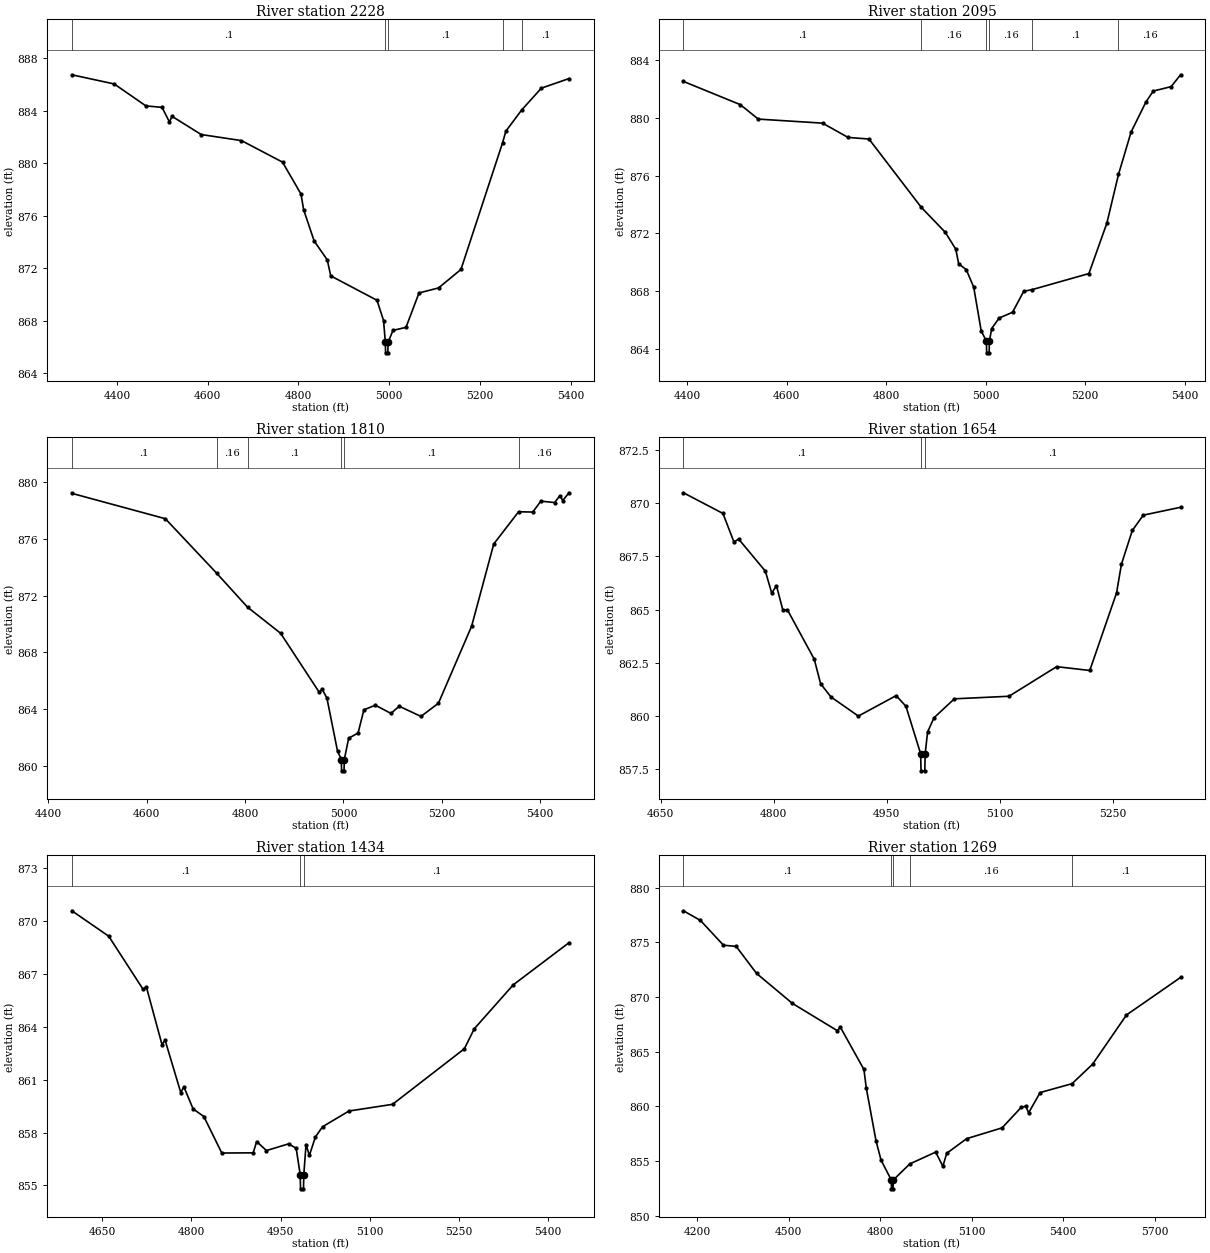
Type RM Length L Ch R = 1,2228,133,133,133
BEGIN DESCRIPTION:
UNT 083 in HW 2.0
END DESCRIPTION:
XS GIS Cut Line= 3
      1992996.79     13668342.68      1992444.74     13668587.46
      1992064.56     13668899.94
#Sta/Elev= 30
  4300.4  886.74  4393.9  886.04  4463.7  884.37  4499.3  884.26  4515.7  883.14
  4521.2  883.58  4585.6  882.19  4674.3  881.73  4764.9  880.09  4805.6  877.66
  4811.4  876.47  4834.7  874.08  4863.5  872.65  4871.2  871.43  4973.2  869.57
  4987.6  868.03  4991.6  866.37  4992.1  865.57  4997.1  865.57  4997.6  866.37
  5008.4  867.28  5037.1  867.51  5065.8  870.13  5108.8  870.51  5158.3  871.92
  5250.0  881.56  5257.3  882.45  5292.4  884.07  5335.5  885.72  5396.4  886.45
#Mann=5,-1,0
  4300.4     0.1       0  4991.6    0.07       0  4997.6     0.1       0
  5250.0    0.16       0  5292.4     0.1       0
Bank Sta=4991.6,4997.6
Exp/Cntr=0.3,0.1

Type RM Length L Ch R = 1,2095,285,285,285
BEGIN DESCRIPTION:
Mapping XS 5801778f
END DESCRIPTION:
XS GIS Cut Line= 2
      1992835.35     13668196.85      1992002.03     13668748.92
#Sta/Elev= 30
  4392.3  882.53  4506.7  880.92  4542.8  879.92  4672.1  879.64  4723.3  878.65
  4765.4  878.54  4870.5  873.81  4918.8  872.08  4939.9  870.91  4945.8  869.89
  4960.9  869.50  4976.0  868.28  4991.0  865.26  5001.5  864.53  5002.0  863.73
  5007.0  863.73  5007.5  864.53  5012.1  865.41  5027.1  866.14  5054.1  866.54
  5076.5  867.99  5093.5  868.11  5207.6  869.22  5243.7  872.71  5267.1  876.09
  5292.4  879.02  5321.9  881.08  5336.9  881.86  5373.0  882.17  5391.9  882.99
#Mann=6,-1,0
  4392.3     0.1       0  4870.5    0.16       0  5001.5    0.07       0
  5007.5    0.16       0  5093.5     0.1       0  5267.1    0.16       0
Bank Sta=5001.5,5007.5
Exp/Cntr=0.3,0.1

Type RM Length L Ch R = 1,1810,156,156,156
BEGIN DESCRIPTION:
Mapping XS a320b089
END DESCRIPTION:
XS GIS Cut Line= 4
      1992694.79     13668207.25      1992444.74     13668217.67
      1992085.37     13668358.29      1991913.91     13668690.82
#Sta/Elev= 30
  4448.1  879.22  4638.1  877.43  4742.3  873.59  4805.1  871.19  4872.3  869.35
  4951.1  865.17  4956.5  865.42  4966.5  864.77  4988.0  861.04  4995.8  860.44
  4996.3  859.64  5001.3  859.64  5001.8  860.44  5010.7  861.94  5029.8  862.31
  5041.7  863.95  5065.0  864.27  5096.7  863.69  5113.3  864.20  5157.6  863.48
  5193.1  864.41  5260.6  869.85  5305.6  875.65  5356.0  877.92  5384.8  877.90
  5401.3  878.67  5429.3  878.57  5440.0  879.06  5445.7  878.71  5458.4  879.26
#Mann=6,-1,0
  4448.1     0.1       0  4742.3    0.16       0  4805.1     0.1       0
  4995.8    0.07       0  5001.8     0.1       0  5356.0    0.16       0
Bank Sta=4995.8,5001.8
Exp/Cntr=0.3,0.1

Type RM Length L Ch R = 1,1654,220,220,220
BEGIN DESCRIPTION:
Mapping XS f4c39c70
END DESCRIPTION:
XS GIS Cut Line= 2
      1992332.44     13668019.11      1991801.89     13668410.52
#Sta/Elev= 30
  4680.3  870.48  4732.7  869.51  4747.3  868.17  4753.5  868.31  4789.0  866.80
  4797.4  865.77  4803.7  866.12  4812.1  864.98  4818.3  864.98  4853.8  862.67
  4862.2  861.52  4875.9  860.90  4912.3  860.00  4962.4  860.96  4975.4  860.46
  4994.9  858.23  4995.4  857.43  5000.4  857.43  5000.9  858.23  5004.1  859.25
  5012.6  859.92  5039.6  860.81  5112.1  860.93  5175.3  862.32  5219.2  862.14
  5254.7  865.78  5261.2  867.13  5275.6  868.71  5290.2  869.43  5339.6  869.80
#Mann=3,-1,0
  4680.3     0.1       0  4994.9    0.07       0  5000.9     0.1       0
Bank Sta=4994.9,5000.9
Exp/Cntr=0.3,0.1

Type RM Length L Ch R = 1,1434,165,165,165
BEGIN DESCRIPTION:
Mapping XS 7511b137
END DESCRIPTION:
XS GIS Cut Line= 4
      1992341.54     13668008.71      1992146.23     13667943.60
      1991851.95     13668094.64      1991784.24     13668386.34
#Sta/Elev= 30
  4599.0  870.57  4661.0  869.13  4719.0  866.11  4724.3  866.26  4750.6  862.99
  4755.9  863.23  4782.2  860.27  4787.5  860.59  4802.9  859.34  4821.0  858.91
  4851.2  856.84  4904.1  856.85  4909.8  857.49  4926.3  856.98  4963.6  857.36
  4976.3  857.11  4983.1  855.61  4983.6  854.81  4988.6  854.81  4989.1  855.61
  4992.9  857.32  4998.5  856.70  5008.6  857.75  5020.7  858.33  5065.1  859.22
  5138.4  859.60  5259.2  862.75  5275.8  863.88  5341.3  866.37  5435.1  868.76
#Mann=3,-1,0
  4599.0     0.1       0  4983.1    0.07       0  4989.1     0.1       0
Bank Sta=4983.1,4989.1
Exp/Cntr=0.3,0.1

Type RM Length L Ch R = 1,1269,0,0,0
BEGIN DESCRIPTION:
UNT 083 in HW 1.0
END DESCRIPTION:
XS GIS Cut Line= 4
      1992728.28     13668050.38      1992058.99     13667808.19
      1991716.54     13668045.17      1991788.45     13668540.25
#Sta/Elev= 30
  4155.6  877.90  4211.2  877.02  4286.7  874.75  4328.5  874.64  4395.1  872.17
  4512.4  869.43  4660.3  866.92  4669.5  867.26  4746.9  863.38  4754.6  861.68
  4786.5  856.85  4802.9  855.09  4836.7  853.26  4837.2  852.46  4842.2  852.46
  4842.7  853.26  4897.1  854.74  4981.9  855.82  5005.5  854.52  5018.1  855.71
  5083.2  857.05  5199.5  858.04  5262.3  859.92  5277.2  860.02  5286.3  859.41
  5324.1  861.27  5428.5  862.08  5495.9  863.86  5607.0  868.37  5784.1  871.80
#Mann=5,-1,0
  4155.6     0.1       0  4836.7    0.07       0  4842.7     0.1       0
  4897.1    0.16       0  5428.5     0.1       0
Bank Sta=4836.7,4842.7
Exp/Cntr=0.3,0.1

Chan Stop Cuts=-1