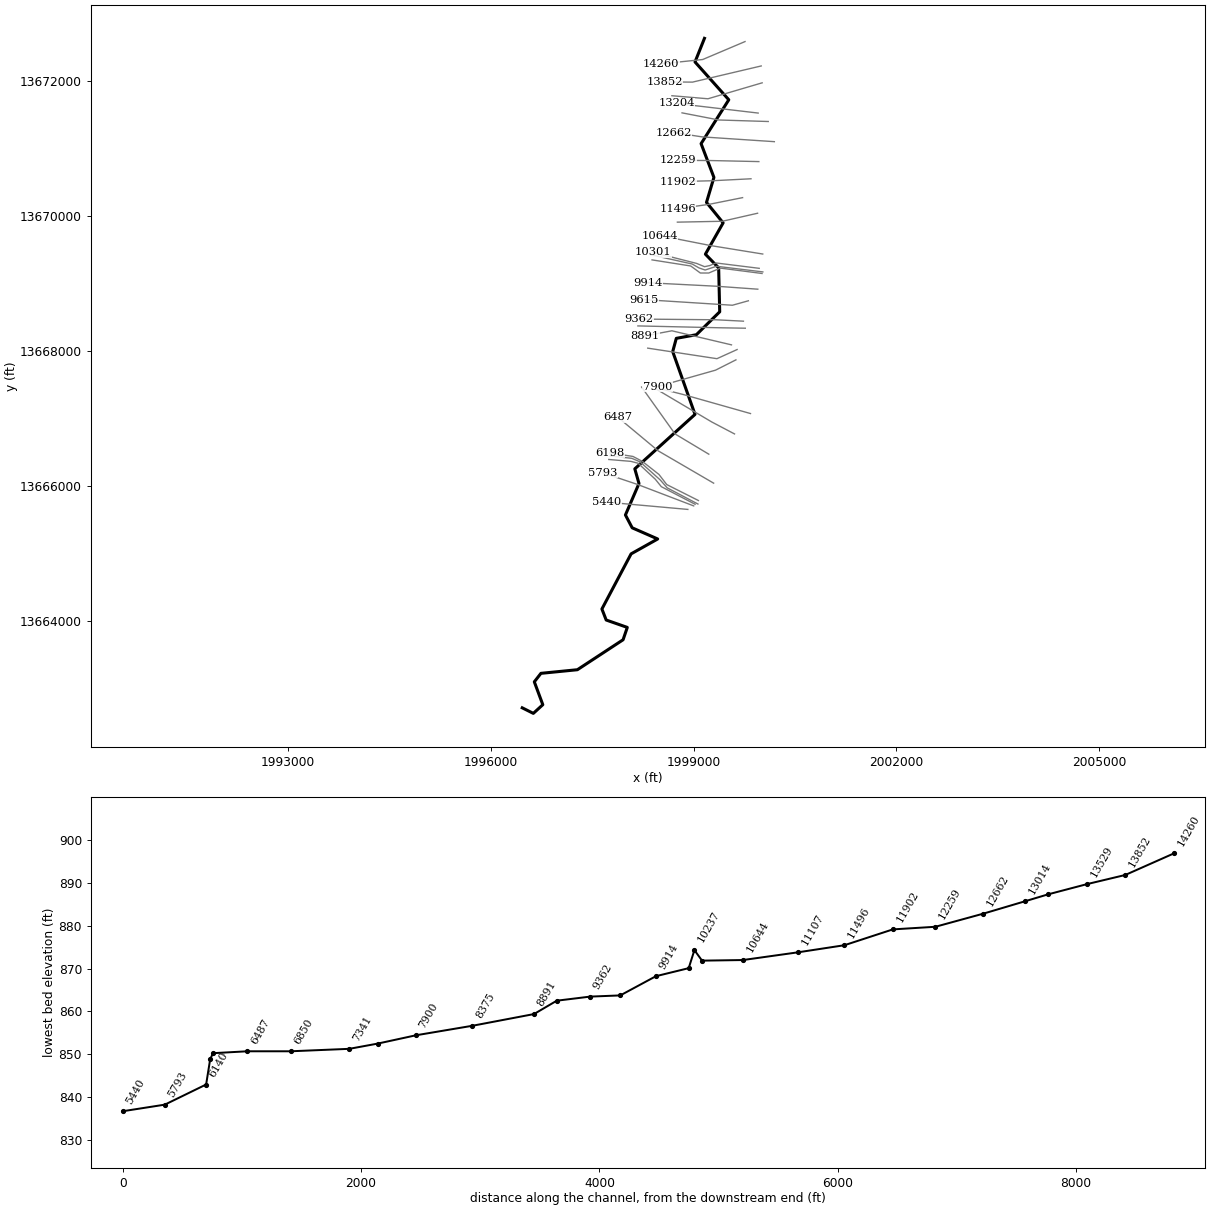
--- UNT 084 in HW.prj (project) ---

Proj Title=UNT 084 in HW Base Level Engineering
Current Plan=p01
Default Exp/Contr=0.3,0.1
English Units
Geom File=g01
Flow File=f01
Plan File=p01
BEGIN DESCRIPTION:
UNT 084 in HW
END DESCRIPTION:

--- UNT 084 in HW.p01 (plan) ---

Plan Title=Multiple Run
Short Identifier=Multiple
Geom File=g01
Flow File=f01
Subcritical Flow
K Sum by GR= 0
Std Step Tol= 0.01
Critical Tol= 0.01
Num of Std Step Trials= 20
Max Error Tol= 0.3
Flow Tol Ratio= 0.001
Split Flow NTrial= 30
Split Flow Tol= 0.02
Split Flow Ratio= 0.02
Log Output Level= 0
Friction Slope Method= 1
Unsteady Friction Slope Method= 2
Unsteady Bridges Friction Slope Method= 1
Parabolic Critical Depth
Global Vel Dist=  1 , 1 , 1
Global Log Level= 0
CheckData=True
Encroach Param= -1, 0, 0, 0
BEGIN DESCRIPTION:
Multiple Run
END DESCRIPTION:

--- UNT 084 in HW.f01 (steady flow) ---

Flow Title=Multiple
Number of Profiles=7
Profile Names=10-year,25-year,50-year,1pct_min,100-year,1pct_plu,500-year
River Rch & RM= UNT 084 in HW,Reach-1,14260
     586     823    1021     628    1252    2498    1889
River Rch & RM= UNT 084 in HW,Reach-1,13852
     857    1228    1543     959    1913    3818    2954
River Rch & RM= UNT 084 in HW,Reach-1,7341
    1326    1939    2471    1555    3102    6189    4909
Boundary for River Rch & Prof#=UNT 084 in HW,Reach-1,1
Up Type=0
Dn Type=3
Dn Slope=0.005
Boundary for River Rch & Prof#=UNT 084 in HW,Reach-1,2
Up Type=0
Dn Type=3
Dn Slope=0.005
Boundary for River Rch & Prof#=UNT 084 in HW,Reach-1,3
Up Type=0
Dn Type=3
Dn Slope=0.005
Boundary for River Rch & Prof#=UNT 084 in HW,Reach-1,4
Up Type=0
Dn Type=3
Dn Slope=0.005
Boundary for River Rch & Prof#=UNT 084 in HW,Reach-1,5
Up Type=0
Dn Type=3
Dn Slope=0.005
Boundary for River Rch & Prof#=UNT 084 in HW,Reach-1,6
Up Type=0
Dn Type=3
Dn Slope=0.005
Boundary for River Rch & Prof#=UNT 084 in HW,Reach-1,7
Up Type=0
Dn Type=3
Dn Slope=0.005

--- UNT 084 in HW.g01 (geometry) ---

Geom Title=Existing Conditions

River Reach=UNT 084 in HW,Reach-1
Reach XY= 30
      1999160.80     13672634.54      1999020.80     13672284.54
      1999520.80     13671724.54      1999110.80     13671074.54
      1999300.80     13670574.54      1999190.80     13670204.54
      1999436.98     13669901.40      1999174.48     13669437.51
      1999370.80     13669234.54      1999386.29     13668584.04
      1999040.80     13668244.54      1998743.93     13668190.98
      1998690.80     13667994.54      1999020.80     13667064.54
      1998129.70     13666257.87      1998191.55     13666040.86
      1997990.80     13665574.54      1998090.80     13665384.54
      1998468.19     13665219.24      1998074.96     13664998.76
      1997642.67     13664181.92      1997706.03     13664018.72
      1998018.53     13663909.35      1997956.03     13663726.19
      1997279.65     13663282.53      1996740.06     13663229.05
      1996642.15     13663103.36      1996767.84     13662764.47
      1996627.56     13662636.00      1996463.29     13662718.27

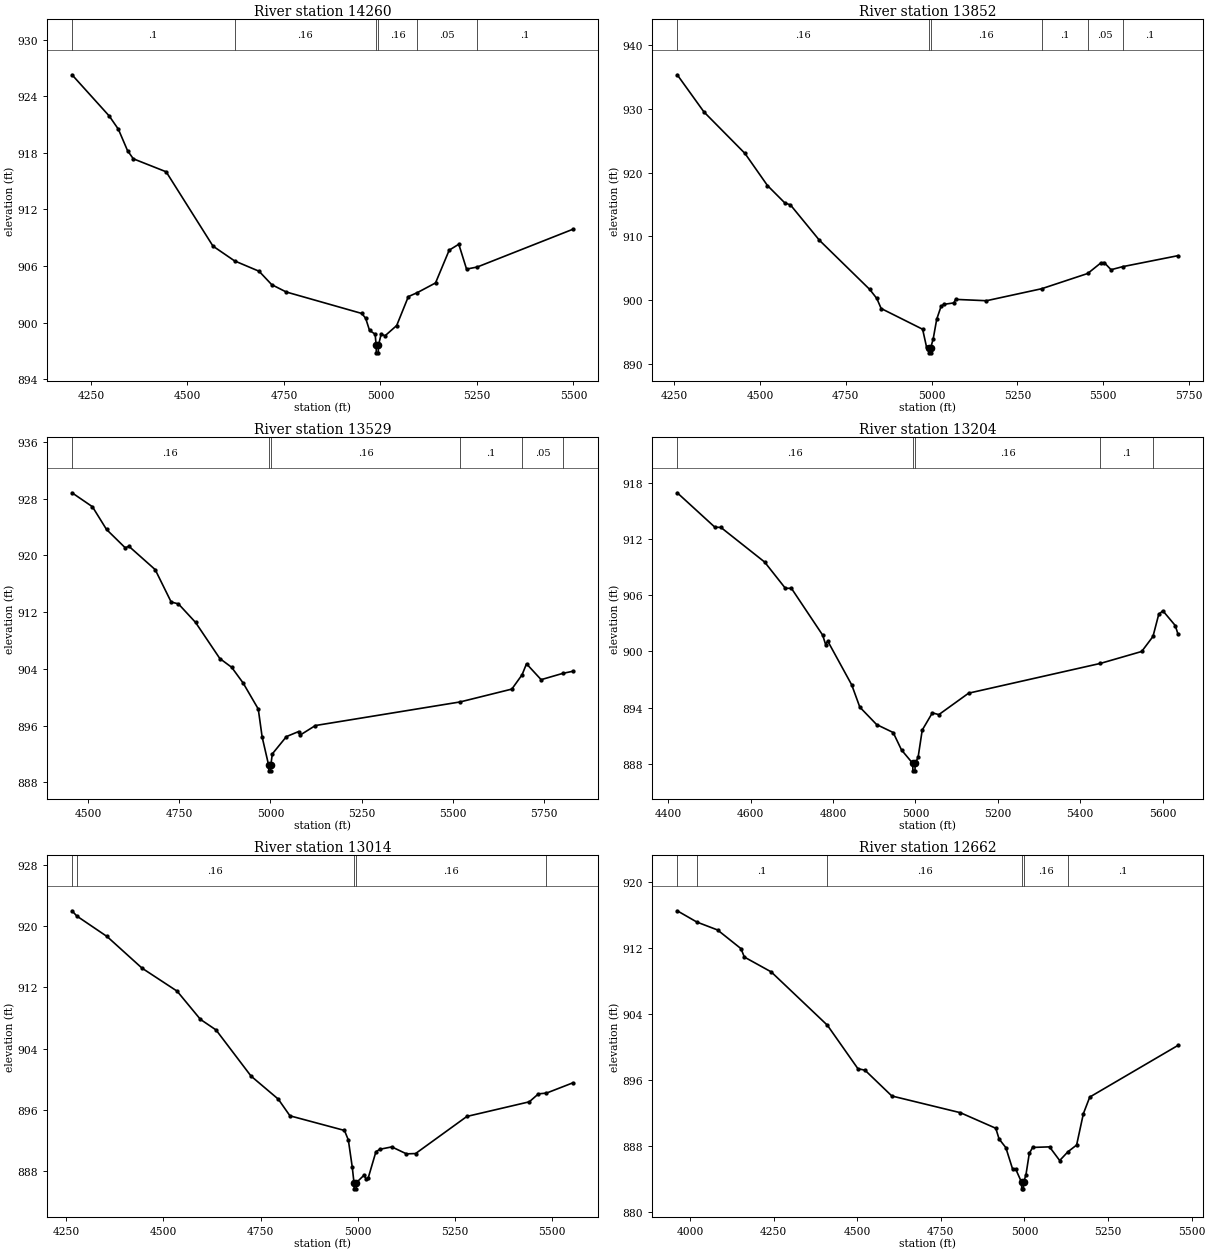
Type RM Length L Ch R = 1,14260,408,408,408
BEGIN DESCRIPTION:
UNT 084 in HW 28.0
END DESCRIPTION:
XS GIS Cut Line= 3
      1999761.22     13672586.64      1999134.72     13672320.83
      1998521.62     13672256.77
#Sta/Elev= 30
  4200.9  926.30  4297.4  921.92  4321.0  920.52  4344.7  918.25  4359.7  917.38
  4444.8  916.00  4566.1  908.11  4622.1  906.54  4685.6  905.44  4718.2  904.02
  4755.9  903.24  4951.6  900.96  4961.6  900.45  4971.7  899.16  4986.2  898.76
  4988.8  897.58  4989.3  896.78  4994.3  896.78  4994.8  897.58  5001.8  898.77
  5011.9  898.59  5042.0  899.68  5072.2  902.75  5095.8  903.18  5142.6  904.20
  5178.0  907.68  5202.9  908.31  5223.0  905.67  5250.6  905.89  5497.9  909.89
#Mann=6,-1,0
  4200.9     0.1       0  4622.1    0.16       0  4988.8    0.07       0
  4994.8    0.16       0  5095.8    0.05       0  5250.6     0.1       0
Bank Sta=4988.8,4994.8
Exp/Cntr=0.3,0.1

Type RM Length L Ch R = 1,13852,323,323,323
BEGIN DESCRIPTION:
Mapping XS 792b0700
END DESCRIPTION:
XS GIS Cut Line= 3
      2000000.81     13672225.53      1998983.44     13671985.94
      1998570.26     13671989.41
#Sta/Elev= 30
  4259.1  935.35  4337.0  929.52  4456.4  923.02  4521.9  917.99  4573.3  915.22
  4588.6  914.97  4673.4  909.40  4819.8  901.70  4840.4  900.29  4853.1  898.71
  4973.9  895.46  4985.3  892.68  4991.5  892.56  4992.0  891.76  4997.0  891.76
  4997.5  892.56  5004.8  893.97  5015.0  897.04  5027.7  899.05  5035.6  899.36
  5064.9  899.59  5070.0  900.14  5159.9  899.93  5320.6  901.81  5454.8  904.20
  5492.7  905.84  5502.7  905.92  5522.8  904.79  5556.6  905.27  5717.5  906.99
#Mann=6,-1,0
  4259.1    0.16       0  4991.5    0.07       0  4997.5    0.16       0
  5320.6     0.1       0  5454.8    0.05       0  5556.6     0.1       0
Bank Sta=4991.5,4997.5
Exp/Cntr=0.3,0.1

Type RM Length L Ch R = 1,13529,325,325,325
BEGIN DESCRIPTION:
Mapping XS 62e36d6b
END DESCRIPTION:
XS GIS Cut Line= 3
      2000014.67     13671975.52      1999212.60     13671739.41
      1998678.90     13671784.47
#Sta/Elev= 30
  4456.5  928.84  4512.5  926.87  4551.0  923.67  4602.1  921.09  4612.5  921.29
  4684.4  918.00  4728.2  913.43  4748.0  913.17  4794.9  910.56  4861.5  905.46
  4894.0  904.22  4925.3  902.01  4966.8  898.34  4977.4  894.40  4995.2  890.42
  4995.7  889.62  5000.7  889.62  5001.2  890.42  5005.3  892.01  5043.9  894.45
  5077.2  895.16  5082.4  894.69  5123.3  896.01  5520.0  899.34  5661.5  901.15
  5689.6  903.17  5701.7  904.72  5741.8  902.48  5801.3  903.37  5828.2  903.66
#Mann=6,-1,0
  4456.5    0.16       0  4995.2    0.07       0  5001.2    0.16       0
  5520.0     0.1       0  5689.6    0.05       0  5801.3     0.1       0
Bank Sta=4995.2,5001.2
Exp/Cntr=0.3,0.1

Type RM Length L Ch R = 1,13204,190,190,190
BEGIN DESCRIPTION:
Mapping XS f6227d9e
END DESCRIPTION:
XS GIS Cut Line= 2
      1999955.64     13671527.61      1998748.69     13671669.81
#Sta/Elev= 30
  4421.9  916.93  4513.2  913.26  4528.0  913.23  4634.0  909.54  4684.3  906.74
  4699.1  906.73  4775.0  901.73  4782.1  900.73  4787.1  901.11  4845.5  896.42
  4865.1  894.05  4905.9  892.19  4946.1  891.34  4966.3  889.48  4993.5  888.05
  4994.0  887.25  4999.0  887.25  4999.5  888.05  5006.6  888.70  5016.6  891.60
  5041.2  893.44  5056.9  893.25  5129.2  895.54  5449.3  898.72  5549.3  899.99
  5576.7  901.59  5590.6  903.94  5600.6  904.34  5630.8  902.76  5637.2  901.87
#Mann=5,-1,0
  4421.9    0.16       0  4993.5    0.07       0  4999.5    0.16       0
  5449.3     0.1       0  5576.7    0.05       0
Bank Sta=4993.5,4999.5
Exp/Cntr=0.3,0.1

Type RM Length L Ch R = 1,13014,352,352,352
BEGIN DESCRIPTION:
UNT 084 in HW 27.0
END DESCRIPTION:
XS GIS Cut Line= 3
      2000104.98     13671402.61      1999375.00     13671425.00
      1998828.57     13671530.81
#Sta/Elev= 30
  4265.4  922.00  4277.8  921.31  4355.4  918.64  4445.5  914.50  4535.5  911.50
  4595.5  907.81  4635.6  906.43  4725.6  900.40  4795.6  897.39  4825.6  895.21
  4965.7  893.30  4975.7  892.05  4985.7  888.53  4990.2  886.47  4990.7  885.67
  4995.7  885.67  4996.2  886.47  5016.1  887.46  5021.6  886.91  5026.7  887.08
  5046.6  890.52  5056.8  890.84  5087.4  891.15  5125.1  890.24  5148.5  890.28
  5280.4  895.13  5440.8  897.04  5464.3  898.08  5485.0  898.18  5552.3  899.51
#Mann=5,-1,0
  4265.4     0.1       0  4277.8    0.16       0  4990.2    0.07       0
  4996.2    0.16       0  5485.0     0.1       0
Bank Sta=4990.2,4996.2
Exp/Cntr=0.3,0.1

Type RM Length L Ch R = 1,12662,403,403,403
BEGIN DESCRIPTION:
UNT 084 in HW 26.0
END DESCRIPTION:
XS GIS Cut Line= 3
      2000195.20     13671104.00      1999125.00     13671175.00
      1998705.67     13671239.41
#Sta/Elev= 30
  3962.1  916.55  4020.8  915.18  4082.6  914.22  4152.7  911.95  4162.7  910.93
  4242.9  909.13  4410.9  902.65  4502.2  897.37  4523.5  897.18  4603.7  894.05
  4808.6  892.02  4914.4  890.13  4924.4  888.82  4944.5  887.78  4964.5  885.20
  4974.5  885.12  4991.5  883.57  4992.0  882.77  4997.1  882.77  4997.6  883.57
  5004.6  884.46  5014.6  887.07  5024.6  887.80  5075.1  887.87  5105.5  886.21
  5130.3  887.28  5156.1  888.09  5176.3  891.90  5195.4  893.92  5458.9  900.19
#Mann=6,-1,0
  3962.1    0.16       0  4020.8     0.1       0  4410.9    0.16       0
  4991.5    0.07       0  4997.6    0.16       0  5130.3     0.1       0
Bank Sta=4991.5,4997.6
Exp/Cntr=0.3,0.1

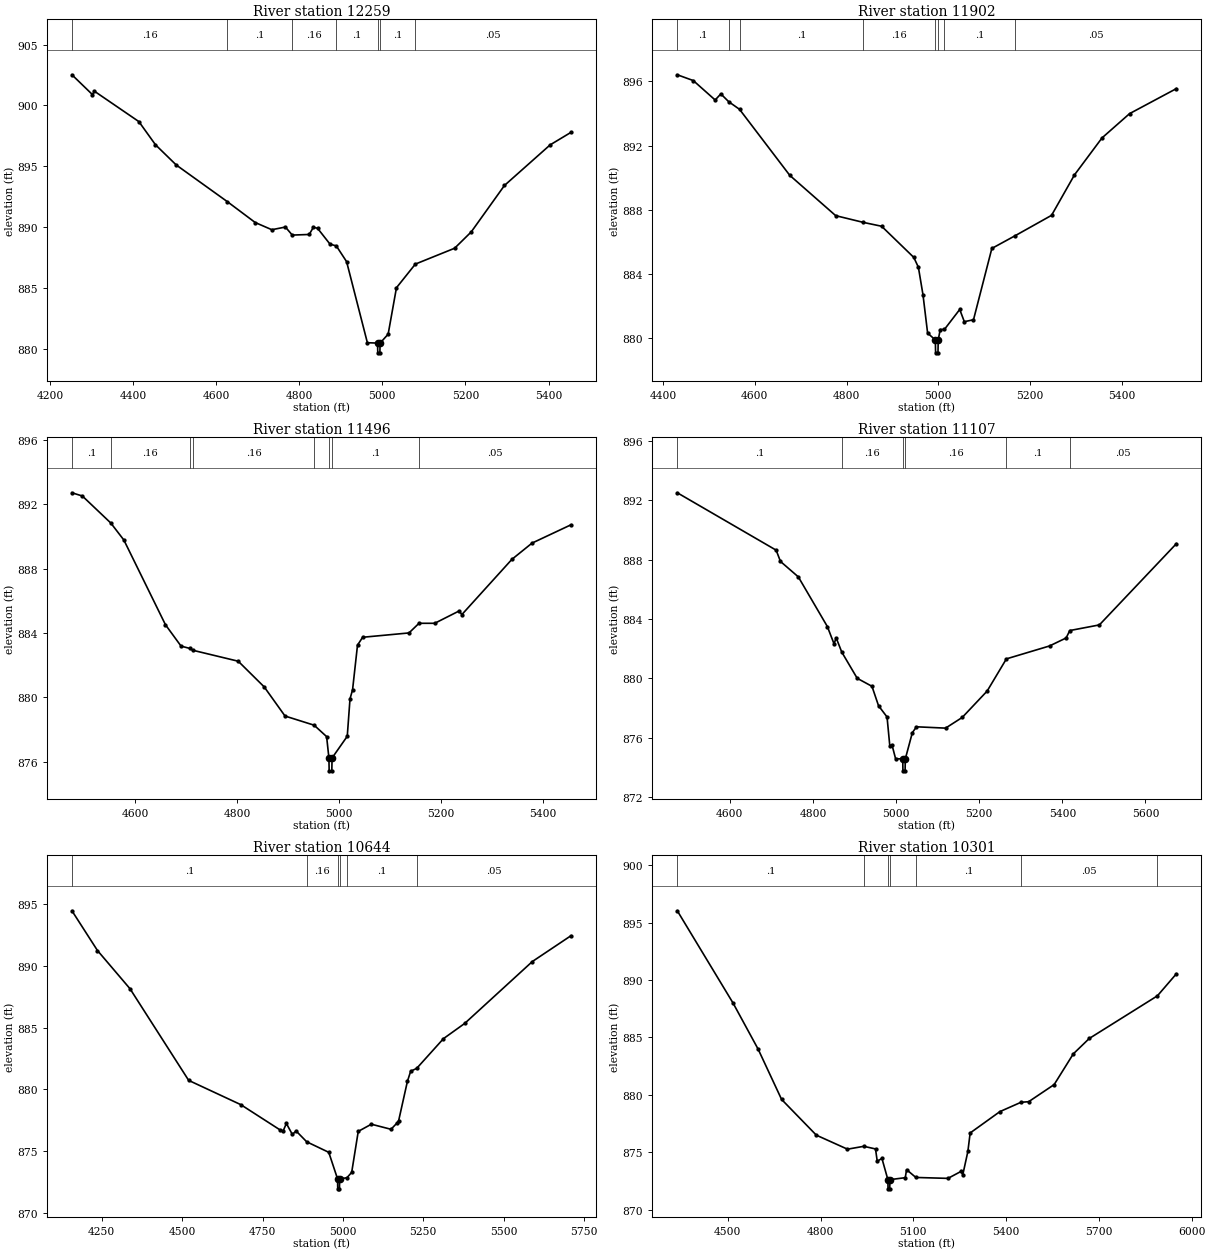
Type RM Length L Ch R = 1,12259,357,357,357
BEGIN DESCRIPTION:
UNT 084 in HW 25.0
END DESCRIPTION:
XS GIS Cut Line= 3
      1999966.05     13670808.86      1999225.00     13670825.00
      1998764.73     13670826.22
#Sta/Elev= 30
  4252.7  902.52  4301.9  900.90  4306.9  901.17  4413.8  898.68  4453.8  896.78
  4503.8  895.12  4626.9  892.11  4693.9  890.40  4733.9  889.81  4766.6  890.03
  4783.1  889.37  4823.9  889.42  4833.9  890.01  4843.9  889.93  4873.9  888.63
  4889.2  888.48  4913.9  887.19  4963.9  880.54  4988.4  880.51  4988.9  879.71
  4994.0  879.71  4994.5  880.51  5013.9  881.24  5033.9  885.05  5079.4  886.99
  5173.9  888.29  5213.9  889.63  5293.9  893.44  5403.9  896.77  5454.2  897.80
#Mann=7,-1,0
  4252.7    0.16       0  4626.9     0.1       0  4783.1    0.16       0
  4889.2     0.1       0  4988.4    0.07       0  4994.5     0.1       0
  5079.4    0.05       0
Bank Sta=4988.4,4994.5
Exp/Cntr=0.3,0.1

Type RM Length L Ch R = 1,11902,406,406,406
BEGIN DESCRIPTION:
UNT 084 in HW 24.0
END DESCRIPTION:
XS GIS Cut Line= 3
      1999849.76     13670554.34      1999275.00     13670525.00
      1998762.95     13670512.68
#Sta/Elev= 30
  4431.1  896.41  4465.9  896.05  4513.6  894.84  4526.0  895.22  4543.3  894.73
  4566.7  894.26  4676.2  890.15  4776.3  887.64  4836.6  887.22  4876.4  886.98
  4946.5  885.04  4956.5  884.43  4966.6  882.70  4976.6  880.33  4993.5  879.90
  4994.0  879.10  4999.2  879.10  4999.7  879.90  5004.1  880.55  5013.3  880.56
  5046.6  881.80  5056.6  881.04  5076.6  881.16  5116.6  885.60  5167.9  886.40
  5246.7  887.66  5296.7  890.18  5356.7  892.48  5416.7  893.99  5518.8  895.55
#Mann=8,-1,0
  4431.1     0.1       0  4543.3    0.16       0  4566.7     0.1       0
  4836.6    0.16       0  4993.5    0.07       0  4999.7    0.16       0
  5013.3     0.1       0  5167.9    0.05       0
Bank Sta=4993.5,4999.7
Exp/Cntr=0.3,0.1

Type RM Length L Ch R = 1,11496,389,389,389
BEGIN DESCRIPTION:
UNT 084 in HW 23.0
END DESCRIPTION:
XS GIS Cut Line= 3
      1999724.96     13670274.99      1999225.00     13670175.00
      1998760.08     13670109.98
#Sta/Elev= 30
  4475.8  892.72  4496.2  892.52  4552.0  890.84  4577.7  889.78  4659.3  884.51
  4689.9  883.18  4706.7  883.04  4713.2  882.92  4802.1  882.24  4853.1  880.64
  4893.9  878.83  4951.0  878.26  4975.5  877.55  4980.0  876.22  4980.5  875.42
  4985.7  875.42  4986.2  876.22  5016.0  877.57  5021.4  879.90  5026.4  880.46
  5036.1  883.24  5046.2  883.73  5137.1  884.00  5156.8  884.60  5187.6  884.60
  5235.7  885.37  5240.8  885.14  5339.1  888.58  5378.6  889.59  5455.1  890.73
#Mann=8,-1,0
  4475.8     0.1       0  4552.0    0.16       0  4706.7     0.1       0
  4713.2    0.16       0  4951.0     0.1       0  4980.0    0.07       0
  4986.2     0.1       0  5156.8    0.05       0
Bank Sta=4980,4986.2
Exp/Cntr=0.3,0.1

Type RM Length L Ch R = 1,11107,463,463,463
BEGIN DESCRIPTION:
UNT 084 in HW 22.0
END DESCRIPTION:
XS GIS Cut Line= 3
      1999946.98     13670043.93      1999425.00     13669925.00
      1998759.78     13669911.99
#Sta/Elev= 30
  4473.7  892.52  4711.5  888.65  4721.9  887.89  4764.8  886.85  4834.7  883.50
  4850.8  882.33  4855.9  882.74  4869.3  881.78  4906.5  880.01  4942.0  879.47
  4957.8  878.16  4978.3  877.40  4985.0  875.43  4990.1  875.53  4998.8  874.59
  5016.0  874.57  5016.5  873.77  5021.7  873.77  5022.2  874.57  5039.1  876.34
  5049.1  876.74  5119.1  876.65  5159.1  877.37  5219.1  879.15  5265.4  881.32
  5369.1  882.19  5409.1  882.73  5417.9  883.23  5489.1  883.61  5674.4  889.09
#Mann=6,-1,0
  4473.7     0.1       0  4869.3    0.16       0  5016.0    0.07       0
  5022.2    0.16       0  5265.4     0.1       0  5417.9    0.05       0
Bank Sta=5016,5022.2
Exp/Cntr=0.3,0.1

Type RM Length L Ch R = 1,10644,343,343,343
BEGIN DESCRIPTION:
UNT 084 in HW 21.0
END DESCRIPTION:
XS GIS Cut Line= 3
      2000023.38     13669439.76      1999252.53     13669564.76
      1998495.63     13669714.06
#Sta/Elev= 30
  4157.2  894.43  4236.6  891.22  4337.9  888.13  4520.3  880.73  4682.4  878.77
  4803.9  876.74  4814.0  876.64  4824.2  877.25  4842.6  876.37  4854.6  876.64
  4887.4  875.77  4956.0  874.92  4983.4  872.77  4983.9  871.97  4989.3  871.97
  4989.8  872.77  5012.6  872.87  5027.3  873.30  5047.7  876.61  5088.5  877.19
  5149.6  876.78  5168.4  877.29  5173.5  877.49  5200.6  880.65  5210.8  881.47
  5229.5  881.70  5312.7  884.10  5378.8  885.33  5589.2  890.33  5709.6  892.42
#Mann=6,-1,0
  4157.2     0.1       0  4887.4    0.16       0  4983.4    0.07       0
  4989.8    0.16       0  5012.6     0.1       0  5229.5    0.05       0
Bank Sta=4983.4,4989.8
Exp/Cntr=0.3,0.1

Type RM Length L Ch R = 1,10301,64,64,64
BEGIN DESCRIPTION:
Mapping XS 1f953e3a
END DESCRIPTION:
XS GIS Cut Line= 6
      1999971.24     13669227.96      1999328.92     13669307.82
      1999242.12     13669269.62      1999162.26     13669252.26
      1999044.20     13669300.87      1998401.80     13669464.08
#Sta/Elev= 30
  4336.5  896.02  4517.1  887.98  4598.0  883.98  4673.8  879.61  4786.2  876.50
  4886.9  875.28  4939.8  875.53  4977.6  875.30  4983.2  874.23  4998.3  874.48
  5017.6  872.63  5018.1  871.83  5023.6  871.83  5024.1  872.63  5073.8  872.80
  5078.1  873.50  5108.1  872.82  5211.9  872.74  5254.4  873.35  5259.8  873.05
  5276.3  875.08  5283.7  876.69  5380.0  878.55  5448.1  879.36  5472.9  879.41
  5555.4  880.90  5617.3  883.57  5668.9  884.91  5889.3  888.62  5950.8  890.54
#Mann=7,-1,0
  4336.5     0.1       0  4939.8    0.05       0  5017.6   0.033       0
  5024.1    0.05       0  5108.1     0.1       0  5448.1    0.05       0
  5889.3     0.1       0
Bank Sta=5017.6,5024.1
Exp/Cntr=0.3,0.1

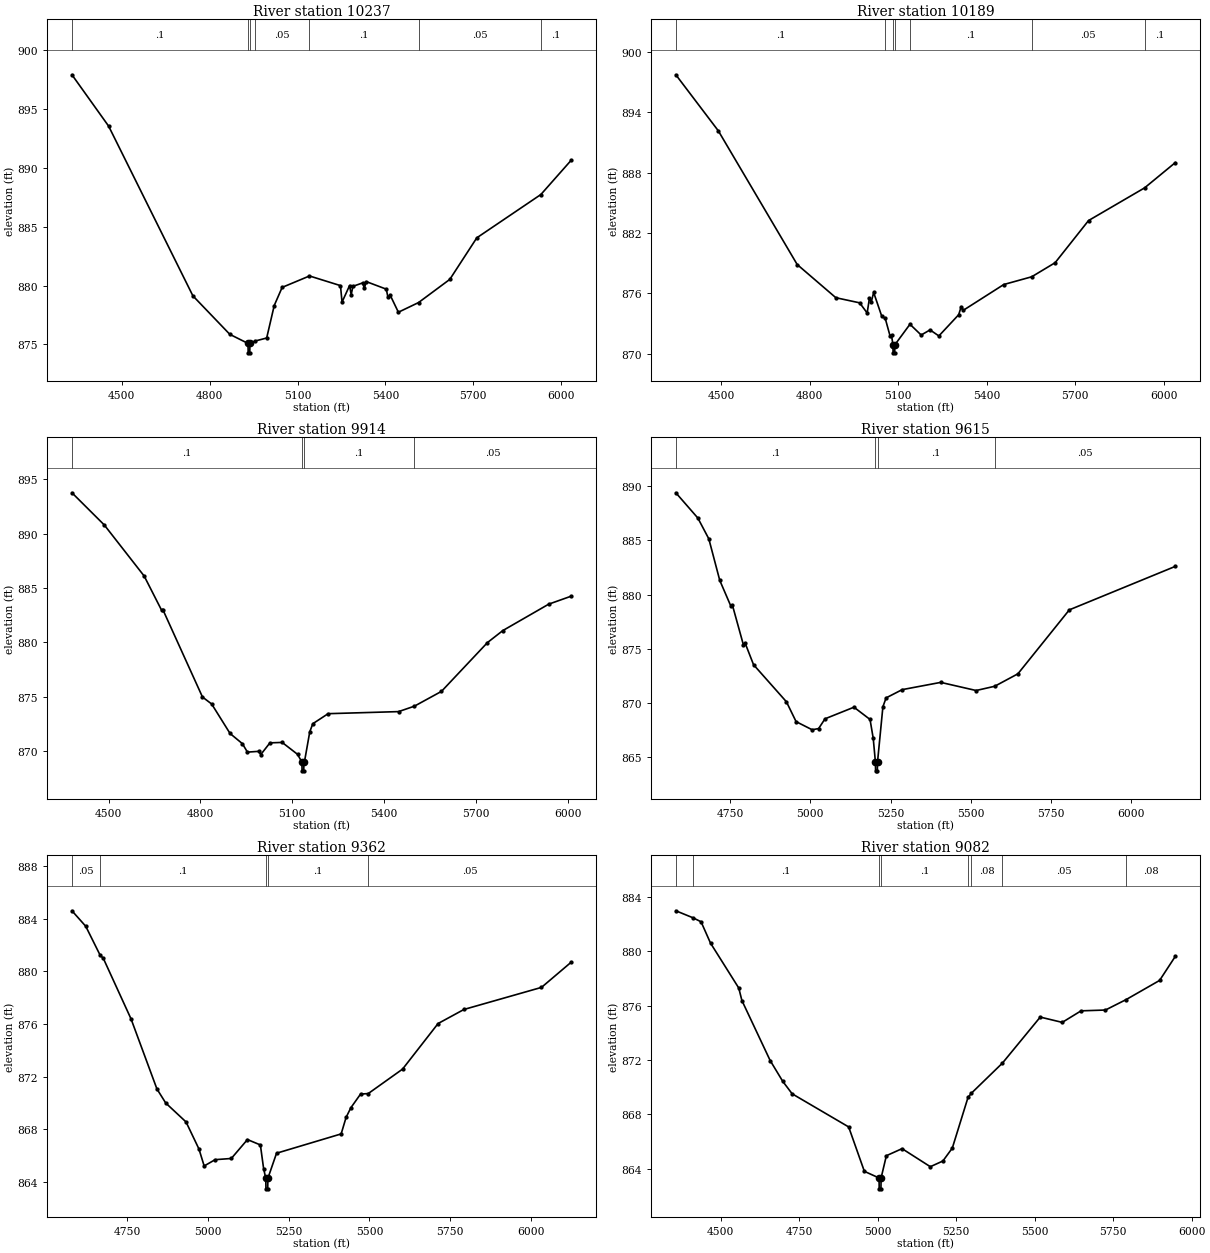
Type RM Length L Ch R = 1,10237,48,48,48
BEGIN DESCRIPTION:
UNT 084 in HW 20.0
END DESCRIPTION:
XS GIS Cut Line= 6
      2000025.03     13669175.00      1999338.76     13669258.34
      1999170.36     13669202.78      1999080.08     13669234.03
      1998977.19     13669292.37      1998369.76     13669427.73
#Sta/Elev= 30
  4329.6  897.90  4454.8  893.54  4742.6  879.12  4868.7  875.85  4930.8  875.08
  4931.3  874.28  4936.8  874.28  4937.3  875.08  4954.5  875.28  4994.5  875.54
  5020.3  878.30  5047.3  879.84  5140.7  880.81  5246.5  879.99  5251.8  878.59
  5277.7  880.00  5283.0  879.22  5289.1  879.93  5322.1  880.22  5327.9  879.78
  5334.7  880.33  5402.9  879.69  5408.7  878.99  5416.4  879.17  5444.2  877.73
  5513.0  878.55  5619.8  880.52  5712.0  884.05  5930.8  887.73  6035.0  890.66
#Mann=7,-1,0
  4329.6     0.1       0  4930.8   0.033       0  4937.3     0.1       0
  4954.5    0.05       0  5140.7     0.1       0  5513.0    0.05       0
  5930.8     0.1       0
Bank Sta=4930.8,4937.3
Exp/Cntr=0.3,0.1

Type RM Length L Ch R = 1,10189,275,275,275
BEGIN DESCRIPTION:
Mapping XS a7bb1a55
END DESCRIPTION:
XS GIS Cut Line= 6
      2000013.00     13669151.56      1999394.90     13669231.43
      1999224.76     13669158.51      1999099.76     13669158.51
      1998957.40     13669262.68      1998384.53     13669352.95
#Sta/Elev= 30
  4345.9  897.72  4489.9  892.15  4757.3  878.86  4888.4  875.56  4969.1  875.05
  4994.6  874.04  5002.2  875.50  5008.6  875.15  5016.6  876.08  5043.9  873.73
  5055.8  873.51  5071.9  871.79  5077.1  871.83  5082.0  870.88  5082.5  870.08
  5088.0  870.08  5088.5  870.88  5139.7  872.92  5177.7  871.85  5207.7  872.36
  5237.7  871.76  5304.9  873.87  5313.4  874.67  5319.6  874.29  5457.7  876.87
  5552.5  877.64  5631.9  879.04  5745.2  883.23  5935.3  886.48  6039.3  888.99
#Mann=7,-1,0
  4345.9     0.1       0  5055.8    0.05       0  5082.0    0.07       0
  5088.5    0.05       0  5139.7     0.1       0  5552.5    0.05       0
  5935.3     0.1       0
Bank Sta=5082,5088.5
Exp/Cntr=0.3,0.1

Type RM Length L Ch R = 1,9914,299,299,299
BEGIN DESCRIPTION:
UNT 084 in HW 19.0
END DESCRIPTION:
XS GIS Cut Line= 3
      1999950.48     13668918.93      1999341.77     13668962.50
      1998320.97     13669014.59
#Sta/Elev= 30
  4380.3  893.75  4486.1  890.79  4616.4  886.10  4673.5  882.95  4678.5  882.95
  4806.9  874.99  4836.9  874.35  4897.1  871.64  4937.2  870.71  4953.9  869.93
  4990.6  870.00  4997.3  869.70  5027.4  870.78  5067.4  870.82  5117.5  869.73
  5131.9  869.01  5132.4  868.21  5137.9  868.21  5138.4  869.01  5140.1  869.02
  5157.6  871.80  5167.6  872.54  5217.6  873.46  5447.9  873.65  5499.6  874.15
  5588.1  875.51  5738.3  879.99  5788.4  881.09  5938.6  883.52  6012.7  884.26
#Mann=4,-1,0
  4380.3     0.1       0  5131.9    0.07       0  5138.4     0.1       0
  5499.6    0.05       0
Bank Sta=5131.9,5138.4
Exp/Cntr=0.3,0.1

Type RM Length L Ch R = 1,9615,253,253,253
BEGIN DESCRIPTION:
UNT 084 in HW 18.0
END DESCRIPTION:
XS GIS Cut Line= 3
      1999810.50     13668747.22      1999574.41     13668681.25
      1998265.40     13668764.59
#Sta/Elev= 30
  4580.9  889.39  4649.5  887.06  4683.7  885.14  4717.8  881.31  4752.0  878.96
  4757.2  879.03  4791.3  875.38  4796.5  875.55  4823.1  873.53  4925.6  870.11
  4955.7  868.28  5005.8  867.53  5025.9  867.64  5045.9  868.54  5136.1  869.61
  5186.2  868.48  5196.2  866.73  5203.0  864.54  5203.5  863.74  5209.0  863.74
  5209.5  864.54  5226.3  869.65  5236.3  870.47  5286.4  871.23  5406.6  871.90
  5516.8  871.15  5574.7  871.54  5647.1  872.69  5807.4  878.59  6137.7  882.60
#Mann=4,-1,0
  4580.9     0.1       0  5203.0    0.07       0  5209.5     0.1       0
  5574.7    0.05       0
Bank Sta=5203,5209.5
Exp/Cntr=0.3,0.1

Type RM Length L Ch R = 1,9362,280,280,280
BEGIN DESCRIPTION:
UNT 084 in HW 17.0
END DESCRIPTION:
XS GIS Cut Line= 3
      1999737.64     13668445.14      1999327.88     13668465.98
      1998192.42     13668476.39
#Sta/Elev= 30
  4579.4  884.62  4622.1  883.44  4667.0  881.22  4676.1  881.02  4762.3  876.39
  4842.4  871.06  4869.7  869.99  4932.5  868.55  4972.5  866.49  4988.6  865.20
  5022.6  865.68  5072.6  865.77  5122.6  867.21  5162.6  866.80  5172.6  865.00
  5179.3  864.26  5179.8  863.46  5185.3  863.46  5185.8  864.26  5212.6  866.17
  5412.6  867.64  5427.9  868.90  5442.6  869.63  5472.6  870.67  5496.4  870.71
  5602.6  872.57  5712.6  876.04  5792.6  877.11  6032.6  878.79  6125.2  880.72
#Mann=5,-1,0
  4579.4    0.05       0  4667.0     0.1       0  5179.3    0.07       0
  5185.8     0.1       0  5496.4    0.05       0
Bank Sta=5179.3,5185.8
Exp/Cntr=0.3,0.1

Type RM Length L Ch R = 1,9082,191,191,191
BEGIN DESCRIPTION:
UNT 084 in HW 16.0
END DESCRIPTION:
XS GIS Cut Line= 3
      1999765.33     13668340.98      1999366.08     13668347.92
      1998175.00     13668375.00
#Sta/Elev= 30
  4357.2  882.99  4412.2  882.47  4437.5  882.18  4467.6  880.61  4557.6  877.30
  4567.6  876.38  4657.6  871.96  4697.6  870.43  4727.6  869.51  4907.6  867.07
  4957.6  863.80  5004.4  863.31  5004.9  862.51  5010.4  862.51  5010.9  863.31
  5027.7  864.95  5077.7  865.47  5167.7  864.14  5207.7  864.56  5237.7  865.51
  5287.7  869.24  5298.8  869.56  5397.3  871.77  5517.8  875.16  5587.8  874.77
  5647.8  875.62  5725.4  875.68  5791.4  876.45  5897.9  877.86  5947.9  879.63
#Mann=8,-1,0
  4357.2    0.08       0  4412.2     0.1       0  5004.4    0.07       0
  5010.9     0.1       0  5287.7    0.05       0  5298.8    0.08       0
  5397.3    0.05       0  5791.4    0.08       0
Bank Sta=5004.4,5010.9
Exp/Cntr=0.3,0.1

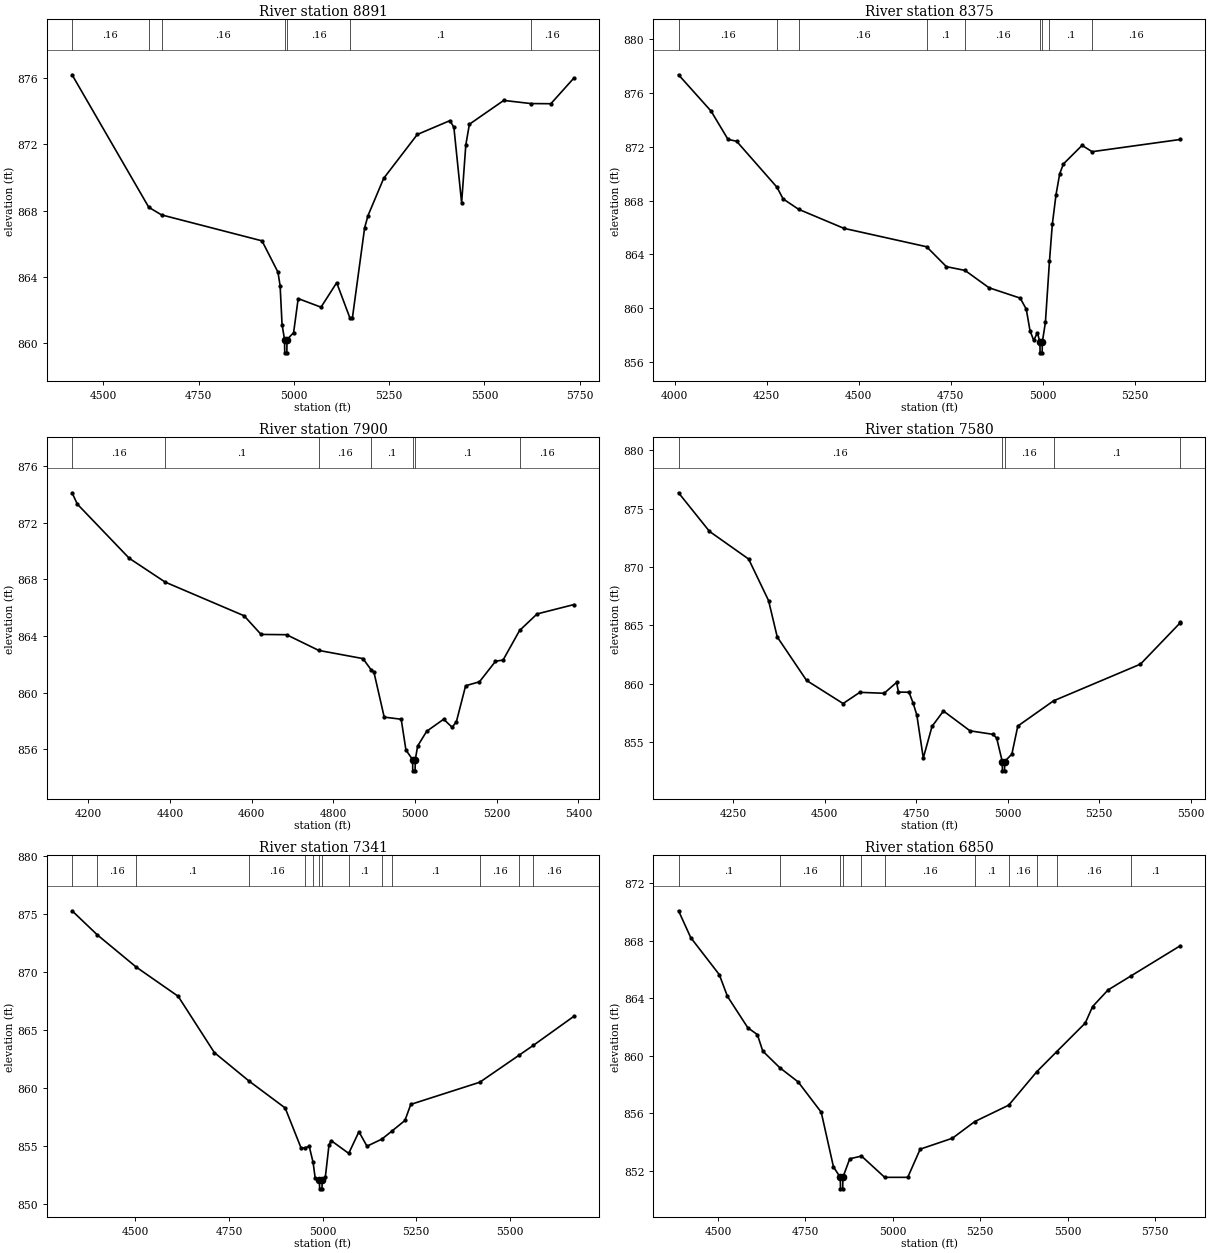
Type RM Length L Ch R = 1,8891,516,516,516
BEGIN DESCRIPTION:
Mapping XS d6ead3a4
END DESCRIPTION:
XS GIS Cut Line= 3
      1999560.55     13668094.44      1998678.58     13668302.78
      1998275.80     13668226.39
#Sta/Elev= 30
  4418.3  876.21  4619.5  868.20  4652.9  867.74  4916.5  866.17  4958.3  864.28
  4964.0  863.46  4969.1  861.11  4975.6  860.20  4976.1  859.40  4981.6  859.40
  4982.1  860.20  4999.4  860.62  5011.4  862.68  5071.3  862.16  5112.4  863.64
  5147.2  861.50  5153.5  861.49  5185.7  866.96  5194.6  867.70  5235.7  869.95
  5323.8  872.60  5409.6  873.44  5419.8  873.03  5440.1  868.47  5451.1  871.97
  5460.5  873.22  5550.6  874.66  5621.7  874.47  5674.2  874.46  5734.5  876.01
#Mann=7,-1,0
  4418.3    0.16       0  4619.5     0.1       0  4652.9    0.16       0
  4975.6    0.07       0  4982.1    0.16       0  5147.2     0.1       0
  5621.7    0.16       0
Bank Sta=4975.6,4982.1
Exp/Cntr=0.3,0.1

Type RM Length L Ch R = 1,8375,475,475,475
BEGIN DESCRIPTION:
Mapping XS c5c68057
END DESCRIPTION:
XS GIS Cut Line= 3
      1999643.86     13668025.01      1999345.24     13667889.59
      1998320.98     13668045.83
#Sta/Elev= 30
  4010.1  877.36  4098.5  874.66  4144.7  872.55  4167.8  872.42  4277.6  869.00
  4294.3  868.13  4336.2  867.36  4459.6  865.94  4684.5  864.57  4738.2  863.09
  4788.8  862.81  4854.1  861.52  4938.8  860.75  4955.3  859.93  4965.4  858.34
  4975.5  857.61  4985.6  858.17  4992.4  857.48  4992.9  856.68  4998.5  856.68
  4999.0  857.48  5007.4  858.96  5018.4  863.50  5026.1  866.23  5036.2  868.44
  5046.3  870.01  5056.4  870.73  5107.0  872.11  5134.3  871.64  5374.1  872.55
#Mann=9,-1,0
  4010.1    0.16       0  4277.6     0.1       0  4336.2    0.16       0
  4684.5     0.1       0  4788.8    0.16       0  4992.4    0.07       0
  4999.0    0.16       0  5018.4     0.1       0  5134.3    0.16       0
Bank Sta=4992.4,4999
Exp/Cntr=0.3,0.1

Type RM Length L Ch R = 1,7900,320,320,320
BEGIN DESCRIPTION:
UNT 084 in HW 15.0
END DESCRIPTION:
XS GIS Cut Line= 3
      1999626.46     13667872.21      1999324.41     13667719.45
      1998468.40     13667476.86
#Sta/Elev= 30
  4160.6  874.13  4173.4  873.33  4300.4  869.50  4388.6  867.81  4581.6  865.43
  4623.2  864.11  4685.6  864.09  4764.3  862.98  4872.6  862.40  4892.5  861.61
  4899.6  861.42  4924.6  858.26  4966.2  858.11  4977.8  855.93  4994.0  855.26
  4994.5  854.46  5000.2  854.46  5000.7  855.26  5006.5  856.22  5028.6  857.26
  5070.1  858.11  5090.9  857.54  5101.3  857.94  5123.9  860.48  5157.8  860.76
  5197.0  862.21  5215.6  862.30  5256.0  864.39  5298.8  865.56  5388.8  866.22
#Mann=7,-1,0
  4160.6    0.16       0  4388.6     0.1       0  4764.3    0.16       0
  4892.5     0.1       0  4994.0    0.07       0  5000.7     0.1       0
  5256.0    0.16       0
Bank Sta=4994,5000.7
Exp/Cntr=0.3,0.1

Type RM Length L Ch R = 1,7580,239,239,239
BEGIN DESCRIPTION:
Mapping XS 0be6b4b8
END DESCRIPTION:
XS GIS Cut Line= 3
      1999841.79     13667077.08      1998848.72     13667358.34
      1998519.39     13667441.53
#Sta/Elev= 30
  4100.1  876.37  4184.7  873.06  4291.7  870.69  4346.2  867.13  4369.9  864.01
  4450.1  860.28  4550.0  858.30  4595.6  859.26  4662.2  859.18  4696.2  860.11
  4701.4  859.28  4730.1  859.27  4741.1  858.37  4751.5  857.32  4769.2  853.63
  4793.1  856.34  4824.3  857.66  4897.0  855.96  4959.7  855.66  4969.8  855.34
  4985.1  853.33  4985.6  852.53  4991.3  852.53  4991.8  853.33  5011.4  853.97
  5027.6  856.37  5125.2  858.53  5363.0  861.68  5470.6  865.19  5471.9  865.25
#Mann=5,-1,0
  4100.1    0.16       0  4985.1    0.07       0  4991.8    0.16       0
  5125.2     0.1       0  5470.6    0.16       0
Bank Sta=4985.1,4991.8
Exp/Cntr=0.3,0.1

Type RM Length L Ch R = 1,7341,491,491,491
BEGIN DESCRIPTION:
UNT 084 in HW 14.0
END DESCRIPTION:
XS GIS Cut Line= 3
      1999605.62     13666775.02      1999268.85     13666952.09
      1998443.85     13667440.85
#Sta/Elev= 30
  4331.2  875.31  4398.6  873.23  4502.9  870.44  4614.4  867.93  4711.0  863.07
  4803.7  860.61  4900.0  858.29  4942.9  854.80  4953.1  854.86  4964.3  854.97
  4974.5  853.60  4980.0  852.28  4991.4  852.11  4992.0  851.31  4998.3  851.31
  4998.8  852.11  5007.2  852.31  5017.0  855.10  5022.8  855.47  5069.7  854.37
  5096.9  856.24  5118.4  854.99  5158.0  855.60  5186.3  856.33  5219.7  857.21
  5235.3  858.60  5419.4  860.51  5525.1  862.86  5562.7  863.70  5670.6  866.20
#Mann=14,-1,0
  4331.2     0.1       0  4398.6    0.16       0  4502.9     0.1       0
  4803.7    0.16       0  4953.1     0.1       0  4974.5    0.16       0
  4991.4    0.07       0  4998.8    0.16       0  5069.7     0.1       0
  5158.0    0.16       0  5186.3     0.1       0  5419.4    0.16       0
  5525.1     0.1       0  5562.7    0.16       0
Bank Sta=4991.4,4998.8
Exp/Cntr=0.3,0.1

Type RM Length L Ch R = 1,6850,363,363,363
BEGIN DESCRIPTION:
UNT 084 in HW 13.0
END DESCRIPTION:
XS GIS Cut Line= 3
      1999225.00     13666475.00      1998725.00     13666775.00
      1998230.68     13667469.43
#Sta/Elev= 30
  4387.2  870.08  4422.2  868.21  4503.8  865.64  4527.1  864.13  4585.5  861.94
  4612.7  861.47  4628.2  860.32  4676.6  859.17  4729.3  858.18  4795.4  856.07
  4830.4  852.27  4849.9  851.54  4850.5  850.74  4856.8  850.74  4857.4  851.54
  4877.0  852.83  4910.6  853.02  4977.0  851.54  5042.9  851.54  5078.5  853.50
  5170.7  854.26  5234.7  855.42  5331.8  856.56  5412.2  858.89  5468.9  860.28
  5550.7  862.27  5571.8  863.42  5615.8  864.57  5682.3  865.56  5822.7  867.65
#Mann=11,-1,0
  4387.2     0.1       0  4676.6    0.16       0  4849.9    0.07       0
  4857.4    0.16       0  4910.6    0.05       0  4977.0    0.16       0
  5234.7     0.1       0  5331.8    0.16       0  5412.2     0.1       0
  5468.9    0.16       0  5682.3     0.1       0
Bank Sta=4849.9,4857.4
Exp/Cntr=0.3,0.1

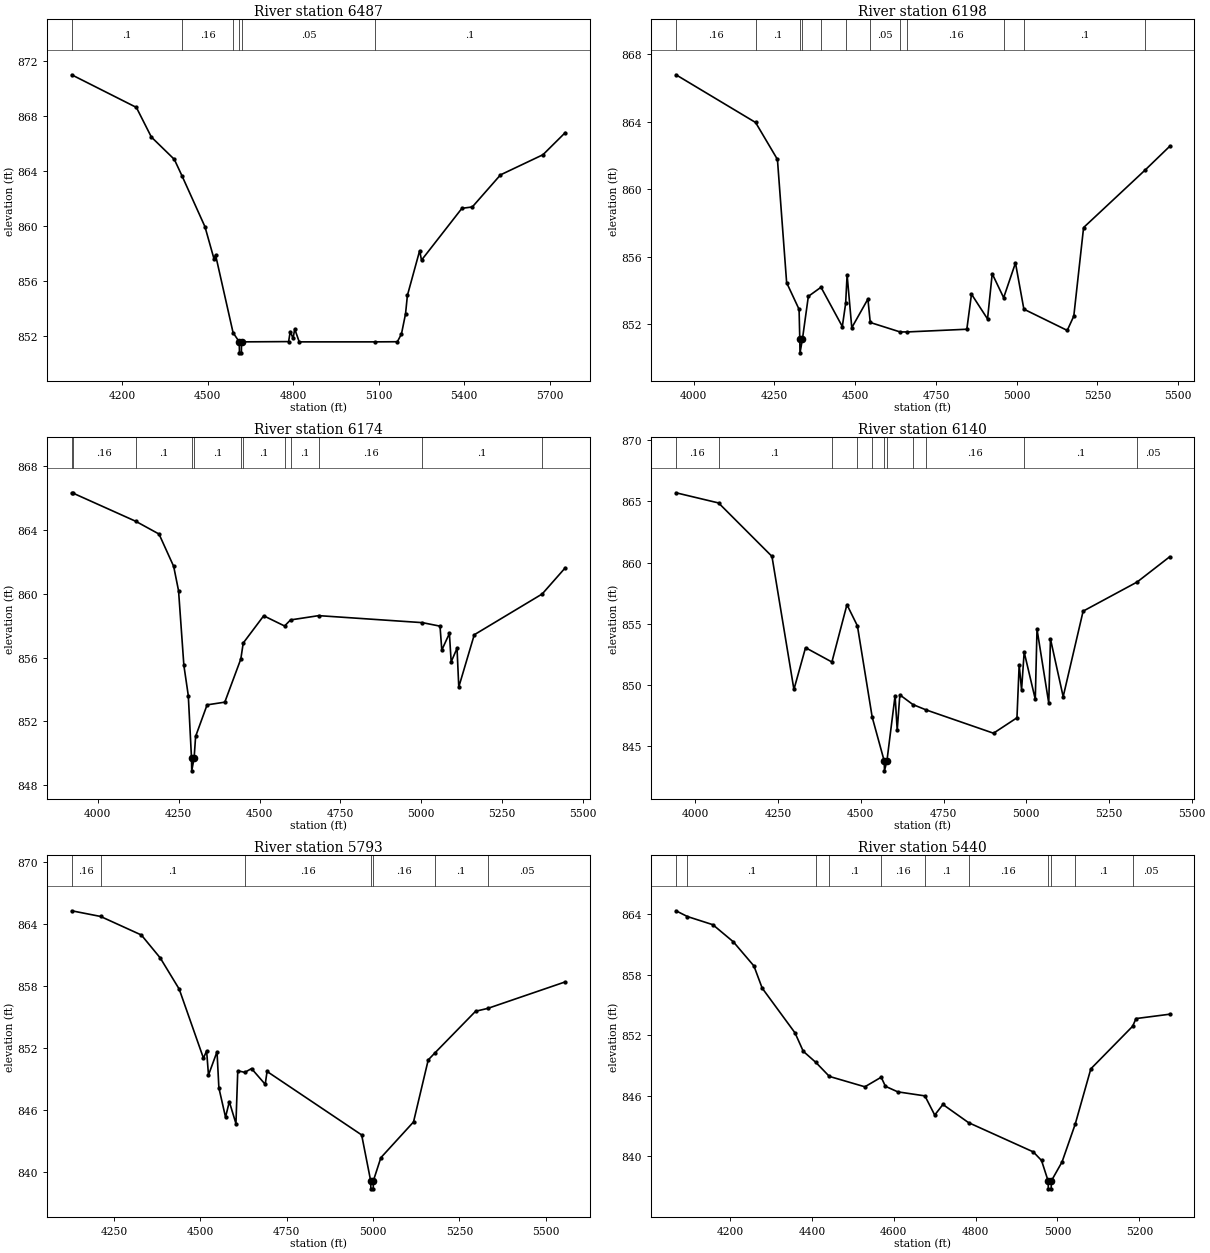
Type RM Length L Ch R = 1,6487,289,289,289
BEGIN DESCRIPTION:
UNT 084 in HW 12.0
END DESCRIPTION:
XS GIS Cut Line= 3
      1999296.63     13666045.84      1998475.00     13666525.00
      1997874.98     13667025.02
#Sta/Elev= 30
  4022.1  871.02  4249.2  868.64  4301.8  866.48  4382.4  864.85  4410.2  863.61
  4489.9  859.94  4521.3  857.62  4527.1  857.88  4588.6  852.21  4610.3  851.54
  4611.0  850.74  4617.7  850.74  4618.4  851.54  4783.5  851.56  4789.2  852.29
  4799.2  851.80  4805.0  852.48  4820.7  851.54  5087.6  851.54  5165.2  851.55
  5179.6  852.12  5193.9  853.59  5200.4  854.93  5243.4  858.19  5249.9  857.50
  5391.7  861.28  5428.2  861.38  5527.1  863.72  5676.2  865.19  5754.3  866.80
#Mann=6,-1,0
  4022.1     0.1       0  4410.2    0.16       0  4588.6    0.05       0
  4610.3   0.033       0  4618.4    0.05       0  5087.6     0.1       0
Bank Sta=4610.3,4618.4
Exp/Cntr=0.3,0.1

Type RM Length L Ch R = 1,6198,24,24,24
BEGIN DESCRIPTION:
Mapping XS fbc77d14
END DESCRIPTION:
XS GIS Cut Line= 6
      1999070.96     13665788.88      1998602.19     13666025.00
      1998487.60     13666174.31      1998241.08     13666368.75
      1998102.19     13666441.67      1997761.89     13666493.76
#Sta/Elev= 30
  3945.2  866.79  4191.7  863.96  4259.3  861.77  4287.8  854.46  4326.3  852.88
  4328.5  851.10  4329.2  850.30  4336.6  851.10  4355.0  853.65  4394.2  854.19
  4460.2  851.86  4470.5  853.23  4475.0  854.93  4489.5  851.79  4539.4  853.49
  4546.7  852.10  4639.0  851.54  4661.9  851.54  4845.7  851.70  4860.1  853.78
  4909.8  852.31  4924.3  854.99  4959.7  853.57  4996.3  855.63  5022.3  852.89
  5156.6  851.63  5176.9  852.48  5207.2  857.73  5398.8  861.16  5473.4  862.54
#Mann=12,-1,0
  3945.2    0.16       0  4191.7     0.1       0  4328.5   0.033       0
  4336.6     0.1       0  4394.2    0.16       0  4470.5     0.1       0
  4546.7    0.05       0  4639.0     0.1       0  4661.9    0.16       0
  4959.7    0.05       0  5022.3     0.1       0  5398.8    0.05       0
Bank Sta=4328.5,4336.6
Exp/Cntr=0.3,0.1

Type RM Length L Ch R = 1,6174,34,34,34
BEGIN DESCRIPTION:
UNT 084 in HW 11.0
END DESCRIPTION:
XS GIS Cut Line= 6
      1999064.02     13665736.80      1998609.13     13665976.39
      1998504.97     13666094.45      1998206.35     13666361.81
      1998084.83     13666413.89      1997765.41     13666448.61
#Sta/Elev= 30
  3919.0  866.35  3922.9  866.33  4117.2  864.56  4189.1  863.76  4234.4  861.73
  4249.5  860.20  4265.9  855.52  4279.6  853.62  4289.5  849.70  4290.2  848.90
  4297.6  849.70  4302.2  851.06  4337.7  853.04  4392.4  853.21  4442.0  855.92
  4449.4  856.92  4512.7  858.63  4577.3  857.99  4595.6  858.37  4682.7  858.64
  5003.4  858.20  5057.8  857.98  5063.3  856.48  5086.8  857.52  5092.3  855.74
  5110.4  856.59  5115.8  854.16  5163.7  857.44  5373.7  860.00  5444.9  861.64
#Mann=12,-1,0
  3919.0     0.1       0  3922.9    0.16       0  4117.2     0.1       0
  4289.5    0.07       0  4297.6     0.1       0  4442.0    0.16       0
  4449.4     0.1       0  4577.3    0.05       0  4595.6     0.1       0
  4682.7    0.16       0  5003.4     0.1       0  5373.7    0.05       0
Bank Sta=4289.5,4297.6
Exp/Cntr=0.3,0.1

Type RM Length L Ch R = 1,6140,347,347,347
BEGIN DESCRIPTION:
Mapping XS 1c52b6a5
END DESCRIPTION:
XS GIS Cut Line= 6
      1999022.32     13665733.34      1998522.33     13665993.75
      1998432.05     13666104.87      1998178.58     13666340.98
      1998070.94     13666368.75      1997744.60     13666396.53
#Sta/Elev= 30
  3941.2  865.70  4069.9  864.87  4231.3  860.51  4297.7  849.65  4332.8  853.06
  4412.5  851.89  4458.0  856.57  4489.6  854.84  4534.3  847.39  4570.7  843.81
  4571.4  843.01  4578.8  843.81  4603.5  849.15  4609.9  846.33  4617.9  849.21
  4657.3  848.42  4697.5  847.98  4901.0  846.08  4971.9  847.34  4978.6  851.67
  4985.8  849.62  4993.7  852.70  5027.3  848.85  5032.5  854.57  5068.0  848.54
  5073.2  853.77  5111.6  849.06  5171.9  856.04  5335.3  858.42  5433.2  860.47
#Mann=11,-1,0
  3941.2    0.16       0  4069.9     0.1       0  4412.5    0.16       0
  4489.6     0.1       0  4534.3    0.16       0  4570.7    0.07       0
  4578.8    0.16       0  4657.3     0.1       0  4697.5    0.16       0
  4993.7     0.1       0  5335.3    0.05       0
Bank Sta=4570.7,4578.8
Exp/Cntr=0.3,0.1

Type RM Length L Ch R = 1,5793,353,353,353
BEGIN DESCRIPTION:
UNT 084 in HW 10.0
END DESCRIPTION:
XS GIS Cut Line= 3
      1999001.45     13665709.05      1998175.00     13666025.00
      1997658.88     13666198.23
#Sta/Elev= 30
  4127.3  865.30  4211.0  864.75  4329.1  862.95  4383.9  860.72  4438.7  857.70
  4508.9  851.00  4518.1  851.71  4523.5  849.36  4548.2  851.62  4553.6  848.12
  4572.9  845.27  4583.8  846.78  4603.0  844.65  4608.3  849.78  4628.6  849.62
  4648.1  849.99  4687.8  848.46  4693.1  849.71  4967.0  843.55  4993.0  839.12
  4993.7  838.32  5000.5  838.32  5001.1  839.12  5022.6  841.34  5117.2  844.81
  5159.8  850.83  5178.3  851.48  5296.9  855.55  5332.4  855.83  5556.5  858.40
#Mann=7,-1,0
  4127.3    0.16       0  4211.0     0.1       0  4628.6    0.16       0
  4993.0    0.07       0  5001.1    0.16       0  5178.3     0.1       0
  5332.4    0.05       0
Bank Sta=4993,5001.1
Exp/Cntr=0.3,0.1

Type RM Length L Ch R = 1,5440,292,292,292
BEGIN DESCRIPTION:
UNT 084 in HW 9.0
END DESCRIPTION:
XS GIS Cut Line= 3
      1998914.72     13665656.95      1998529.27     13665691.67
      1997713.33     13665764.58
#Sta/Elev= 30
  4067.7  864.34  4095.6  863.77  4157.8  862.96  4208.0  861.26  4258.2  858.87
  4278.3  856.68  4358.6  852.24  4378.7  850.42  4409.7  849.31  4442.5  847.93
  4529.3  846.90  4569.2  847.85  4579.5  846.95  4609.6  846.40  4676.0  846.00
  4700.0  844.10  4720.0  845.15  4782.6  843.35  4940.9  840.45  4961.0  839.60
  4977.0  837.59  4977.7  836.79  4984.5  836.79  4985.2  837.59  5011.2  839.46
  5043.4  843.21  5081.5  848.68  5183.7  852.90  5191.9  853.66  5273.9  854.09
#Mann=11,-1,0
  4067.7    0.16       0  4095.6     0.1       0  4409.7    0.16       0
  4442.5     0.1       0  4569.2    0.16       0  4676.0     0.1       0
  4782.6    0.16       0  4977.0    0.07       0  4985.2    0.16       0
  5043.4     0.1       0  5183.7    0.05       0
Bank Sta=4977,4985.2
Exp/Cntr=0.3,0.1