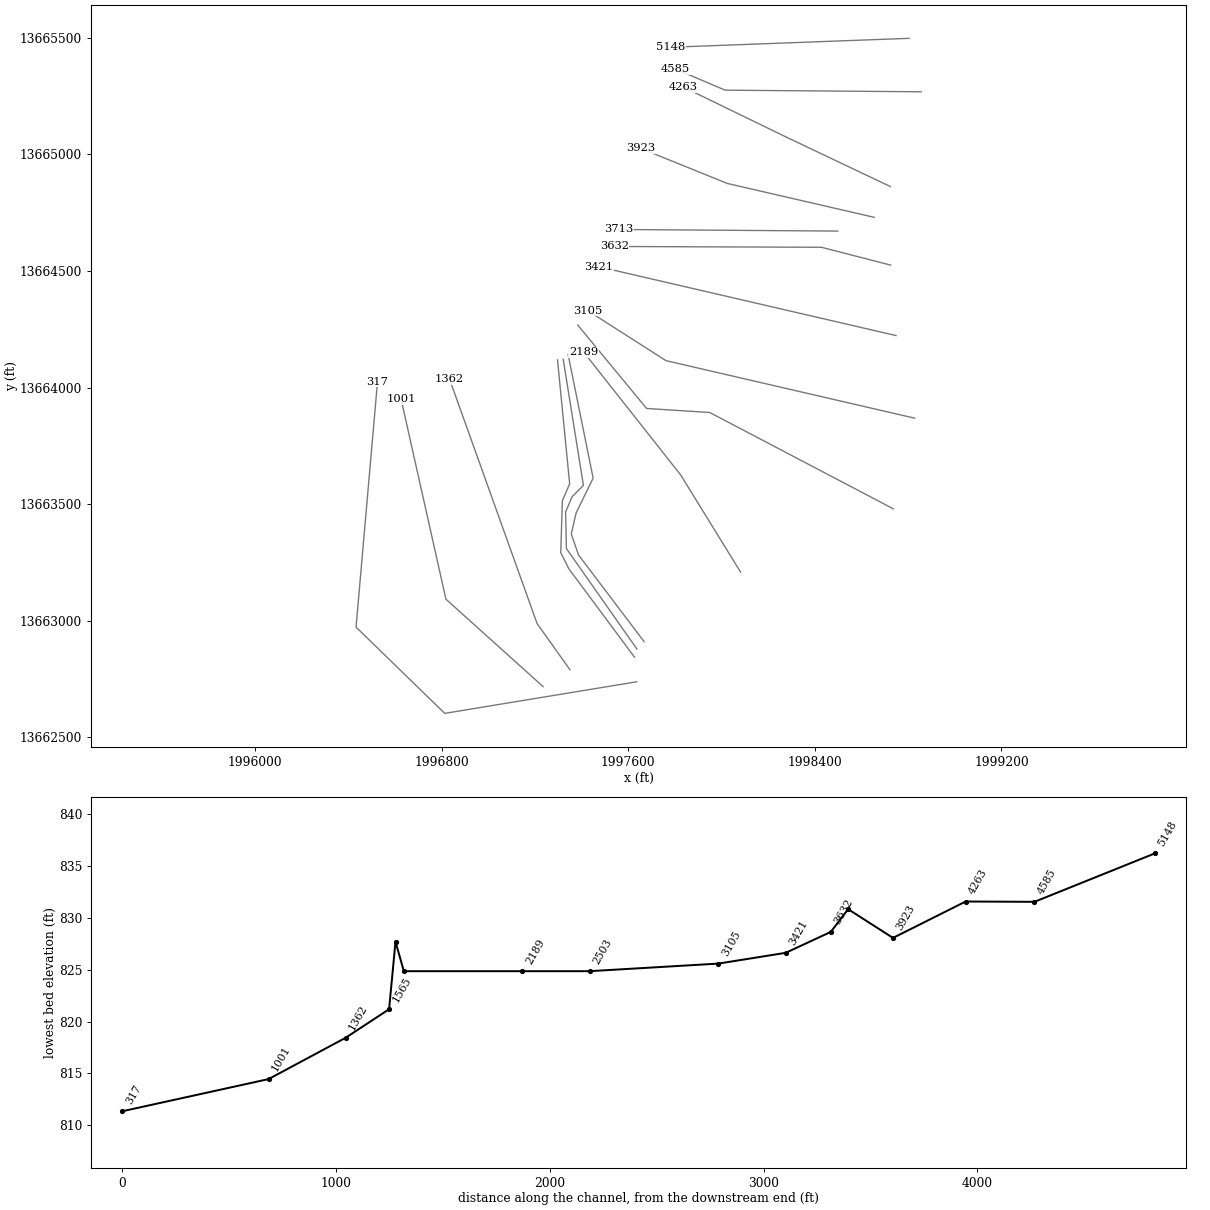
HEC-RAS study UNT 084 in HW.prj: UNT 084 in HW Base Level Engineering

--- UNT 084 in HW.g01 (geometry) --- (continued)

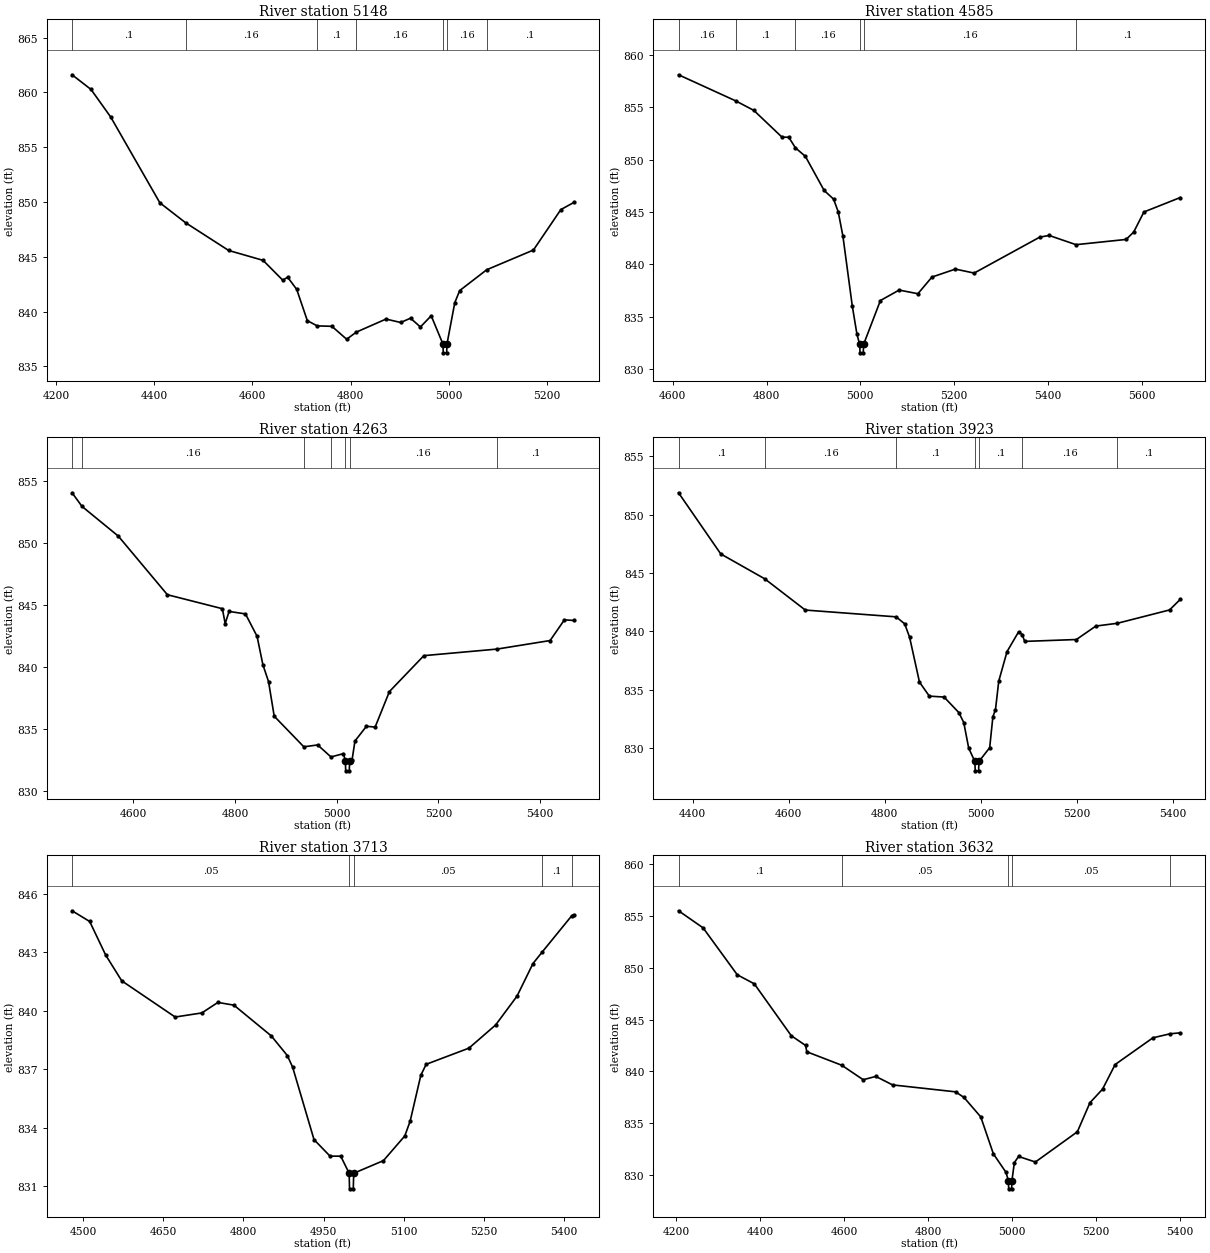
Type RM Length L Ch R = 1,5148,563,563,563
BEGIN DESCRIPTION:
Mapping XS 4468dde7
END DESCRIPTION:
XS GIS Cut Line= 2
      1998803.56     13665497.23      1997782.78     13665459.03
#Sta/Elev= 30
  4232.7  861.60  4271.3  860.26  4311.3  857.75  4411.4  849.92  4463.8  848.10
  4551.5  845.57  4621.5  844.67  4661.6  842.86  4671.6  843.13  4690.0  842.02
  4711.6  839.17  4731.6  838.69  4761.6  838.65  4791.7  837.47  4811.3  838.12
  4871.7  839.31  4901.7  839.00  4921.7  839.39  4941.8  838.59  4963.8  839.61
  4987.7  837.03  4988.4  836.23  4995.2  836.23  4995.9  837.03  5011.8  840.81
  5021.8  841.91  5076.8  843.81  5171.9  845.61  5227.7  849.30  5254.2  849.95
#Mann=7,-1,0
  4232.7     0.1       0  4463.8    0.16       0  4731.6     0.1       0
  4811.3    0.16       0  4987.7    0.07       0  4995.9    0.16       0
  5076.8     0.1       0
Bank Sta=4987.7,4995.9
Exp/Cntr=0.3,0.1

Type RM Length L Ch R = 1,4585,322,322,322
BEGIN DESCRIPTION:
Mapping XS a2283b0a
END DESCRIPTION:
XS GIS Cut Line= 3
      1998855.66     13665268.06      1998015.38     13665275.00
      1997803.53     13665365.30
#Sta/Elev= 30
  4612.2  858.09  4734.2  855.60  4772.9  854.69  4832.9  852.14  4847.4  852.13
  4861.4  851.13  4882.9  850.30  4922.9  847.05  4942.9  846.23  4952.9  845.02
  4962.9  842.70  4982.9  836.03  4992.9  833.32  4998.7  832.36  4999.5  831.56
  5006.3  831.56  5007.0  832.36  5042.9  836.55  5082.9  837.55  5122.9  837.20
  5152.9  838.79  5202.9  839.55  5242.9  839.17  5382.9  842.60  5402.9  842.76
  5460.2  841.88  5567.2  842.38  5583.4  843.09  5605.1  845.00  5682.8  846.38
#Mann=6,-1,0
  4612.2    0.16       0  4734.2     0.1       0  4861.4    0.16       0
  4998.7    0.07       0  5007.0    0.16       0  5460.2     0.1       0
Bank Sta=4998.7,5007
Exp/Cntr=0.3,0.1

Type RM Length L Ch R = 1,4263,340,340,340
BEGIN DESCRIPTION:
UNT 084 in HW 8.0
END DESCRIPTION:
XS GIS Cut Line= 3
      1998723.76     13664861.79      1998275.00     13665075.00
      1997834.85     13665288.88
#Sta/Elev= 30
  4480.0  854.04  4499.5  852.94  4570.9  850.54  4667.3  845.81  4775.4  844.68
  4780.9  843.48  4788.6  844.46  4820.8  844.26  4843.6  842.45  4855.0  840.16
  4866.1  838.80  4877.3  836.00  4935.5  833.53  4962.7  833.68  4988.9  832.71
  5013.4  832.98  5017.1  832.39  5017.8  831.59  5024.8  831.59  5025.5  832.39
  5030.4  832.50  5036.0  834.00  5058.6  835.19  5075.6  835.12  5103.7  837.99
  5171.4  840.89  5315.1  841.42  5419.5  842.11  5447.6  843.78  5466.2  843.73
#Mann=7,-1,0
  4480.0     0.1       0  4499.5    0.16       0  4935.5     0.1       0
  4988.9    0.16       0  5017.1    0.07       0  5025.5    0.16       0
  5315.1     0.1       0
Bank Sta=5017.1,5025.5
Exp/Cntr=0.3,0.1

Type RM Length L Ch R = 1,3923,210,210,210
BEGIN DESCRIPTION:
UNT 084 in HW 7.0
END DESCRIPTION:
XS GIS Cut Line= 3
      1998654.23     13664729.88      1998025.00     13664875.00
      1997654.25     13665025.01
#Sta/Elev= 30
  4370.3  851.86  4458.3  846.63  4550.0  844.50  4634.5  841.83  4823.8  841.25
  4841.6  840.65  4851.8  839.51  4872.4  835.67  4892.9  834.47  4923.7  834.39
  4954.5  833.06  4964.7  832.21  4975.0  830.02  4987.8  828.88  4988.6  828.08
  4995.6  828.08  4996.3  828.88  5018.7  830.06  5025.4  832.71  5030.8  833.31
  5037.6  835.75  5054.9  838.28  5079.0  839.97  5086.6  839.73  5091.6  839.15
  5199.4  839.31  5239.9  840.46  5284.9  840.70  5393.6  841.84  5416.0  842.75
#Mann=7,-1,0
  4370.3     0.1       0  4550.0    0.16       0  4823.8     0.1       0
  4987.8    0.07       0  4996.3     0.1       0  5086.6    0.16       0
  5284.9     0.1       0
Bank Sta=4987.8,4996.3
Exp/Cntr=0.3,0.1

Type RM Length L Ch R = 1,3713,81,81,81
BEGIN DESCRIPTION:
Mapping XS bb828191
END DESCRIPTION:
XS GIS Cut Line= 2
      1998498.01     13664670.84      1997558.54     13664677.77
#Sta/Elev= 30
  4479.1  845.14  4512.1  844.59  4542.1  842.86  4572.1  841.54  4672.1  839.68
  4722.1  839.89  4752.1  840.43  4782.1  840.29  4852.1  838.71  4882.1  837.70
  4892.1  837.10  4932.1  833.38  4962.1  832.53  4982.1  832.53  4997.9  831.65
  4998.6  830.85  5005.6  830.85  5006.4  831.65  5062.1  832.30  5102.1  833.57
  5112.1  834.33  5132.1  836.69  5142.1  837.25  5222.1  838.08  5272.1  839.27
  5312.1  840.75  5342.1  842.43  5359.3  843.02  5414.8  844.89  5418.6  844.94
#Mann=5,-1,0
  4479.1    0.05       0  4997.9    0.04       0  5006.4    0.05       0
  5359.3     0.1       0  5414.8    0.05       0
Bank Sta=4997.9,5006.4
Exp/Cntr=0.3,0.1

Type RM Length L Ch R = 1,3632,211,211,211
BEGIN DESCRIPTION:
UNT 084 in HW 6.0
END DESCRIPTION:
XS GIS Cut Line= 3
      1998725.01     13664525.00      1998428.58     13664601.39
      1997539.80     13664604.86
#Sta/Elev= 30
  4206.1  855.52  4264.6  853.87  4345.9  849.34  4386.6  848.46  4474.6  843.45
  4508.7  842.51  4511.5  841.90  4594.7  840.60  4645.8  839.20  4675.8  839.52
  4715.8  838.70  4865.8  838.03  4885.8  837.49  4925.8  835.61  4955.8  832.04
  4985.8  830.26  4991.5  829.46  4992.3  828.66  4999.3  828.66  5000.0  829.46
  5005.8  831.19  5015.8  831.79  5055.8  831.25  5155.8  834.17  5185.8  836.98
  5215.8  838.29  5245.8  840.67  5335.8  843.25  5376.9  843.64  5401.0  843.73
#Mann=5,-1,0
  4206.1     0.1       0  4594.7    0.05       0  4991.5    0.04       0
  5000.0    0.05       0  5376.9    0.08       0
Bank Sta=4991.5,5000
Exp/Cntr=0.3,0.1

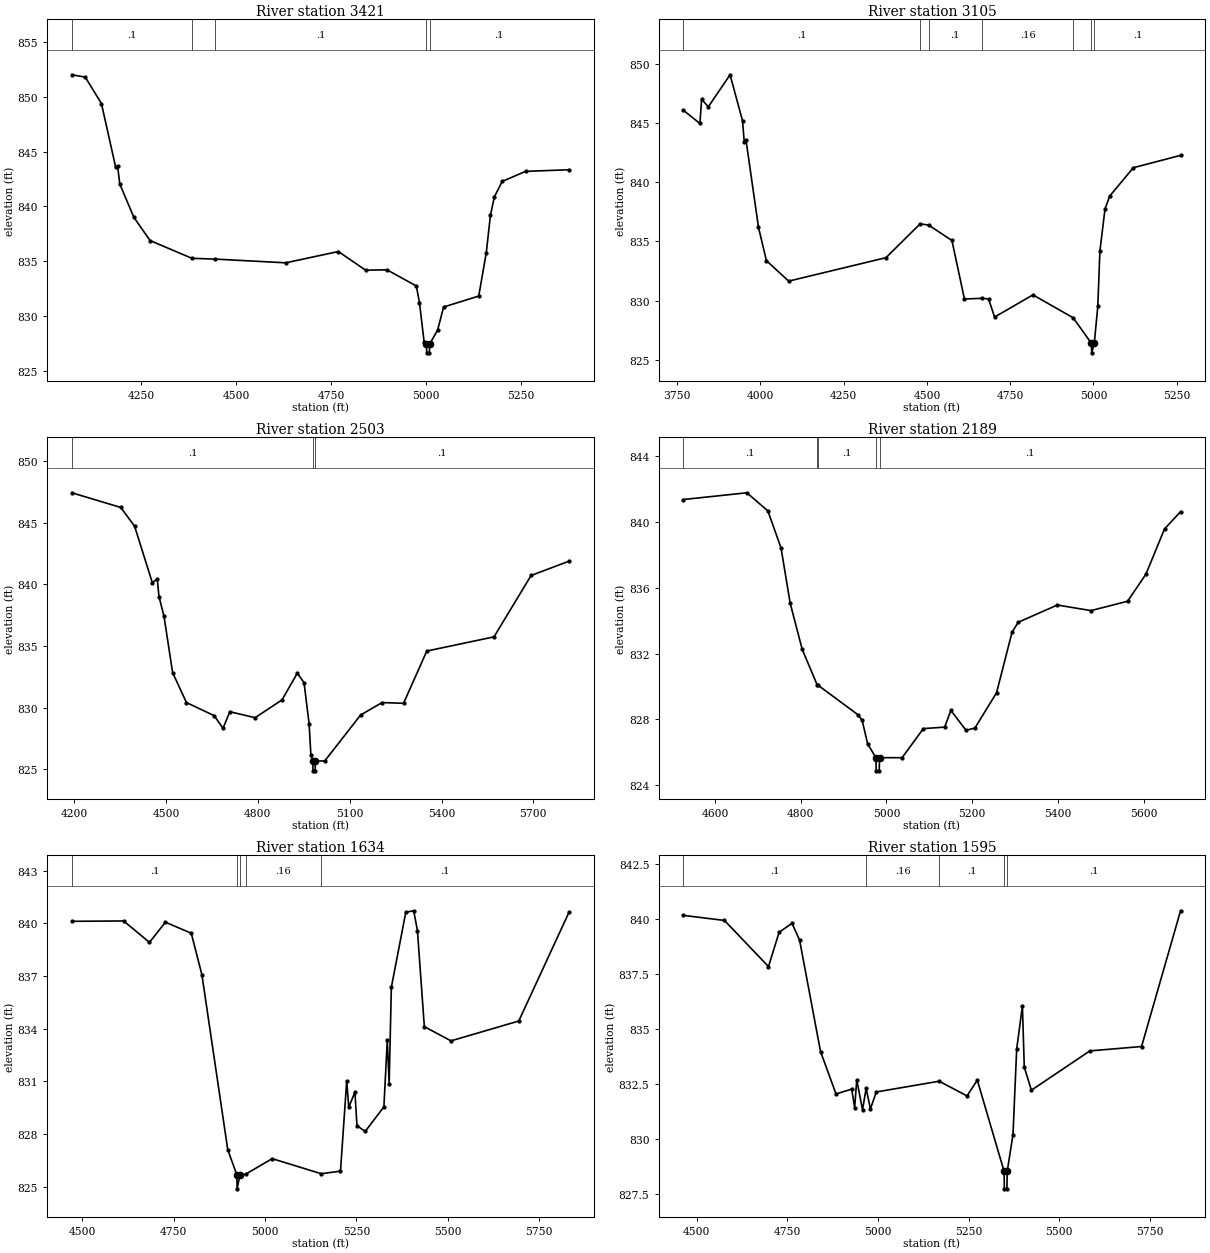
Type RM Length L Ch R = 1,3421,316,316,316
BEGIN DESCRIPTION:
Mapping XS 7e359ad7
END DESCRIPTION:
XS GIS Cut Line= 2
      1998747.99     13664222.93      1997473.72     13664518.06
#Sta/Elev= 30
  4067.8  852.00  4103.0  851.79  4145.7  849.38  4183.2  843.56  4188.3  843.64
  4194.0  842.03  4231.0  839.00  4273.7  836.88  4383.8  835.26  4445.1  835.19
  4630.6  834.85  4769.0  835.88  4840.7  834.18  4897.0  834.21  4974.2  832.74
  4982.4  831.23  4994.7  827.63  5000.7  827.44  5001.5  826.64  5008.5  826.64
  5009.2  827.44  5030.2  828.72  5046.0  830.82  5138.4  831.82  5158.3  835.78
  5169.2  839.20  5179.5  840.86  5200.0  842.27  5261.6  843.19  5375.8  843.34
#Mann=5,-1,0
  4067.8     0.1       0  4383.8    0.16       0  4445.1     0.1       0
  5000.7    0.07       0  5009.2     0.1       0
Bank Sta=5000.7,5009.2
Exp/Cntr=0.3,0.1

Type RM Length L Ch R = 1,3105,602,602,602
BEGIN DESCRIPTION:
UNT 084 in HW 5.0
END DESCRIPTION:
XS GIS Cut Line= 3
      1998827.89     13663868.75      1997761.91     13664115.28
      1997425.56     13664330.27
#Sta/Elev= 30
  3768.5  846.06  3818.0  844.95  3823.2  846.99  3843.3  846.36  3908.6  849.06
  3946.0  845.18  3951.3  843.35  3956.5  843.55  3994.0  836.18  4017.8  833.38
  4084.6  831.65  4377.0  833.63  4479.4  836.48  4505.0  836.38  4575.0  835.08
  4612.6  830.14  4664.6  830.20  4685.0  830.15  4703.2  828.62  4818.4  830.49
  4939.1  828.56  4994.1  826.40  4994.9  825.60  5002.6  826.40  5013.2  829.52
  5019.5  834.18  5034.8  837.73  5048.8  838.82  5120.0  841.22  5261.8  842.26
#Mann=7,-1,0
  3768.5     0.1       0  4479.4    0.16       0  4505.0     0.1       0
  4664.6    0.16       0  4939.1     0.1       0  4994.1    0.07       0
  5002.6     0.1       0
Bank Sta=4994.1,5002.6
Exp/Cntr=0.3,0.1

Type RM Length L Ch R = 1,2503,314,314,314
BEGIN DESCRIPTION:
Mapping XS 70d32407
END DESCRIPTION:
XS GIS Cut Line= 4
      1998736.54     13663480.04      1997949.41     13663893.06
      1997678.58     13663910.42      1997383.43     13664268.06
#Sta/Elev= 30
  4192.3  847.43  4352.1  846.24  4397.3  844.72  4455.0  840.15  4471.4  840.41
  4477.0  839.01  4493.4  837.41  4521.5  832.84  4566.7  830.41  4657.1  829.35
  4686.3  828.32  4708.3  829.67  4790.9  829.18  4879.1  830.63  4928.9  832.80
  4950.9  832.02  4967.3  828.71  4973.3  826.13  4979.5  825.67  4980.2  824.87
  4987.2  824.87  4988.0  825.67  5018.4  825.67  5135.7  829.40  5205.9  830.41
  5276.0  830.35  5351.9  834.59  5571.4  835.74  5692.6  840.72  5816.3  841.88
#Mann=3,-1,0
  4192.3     0.1       0  4979.5    0.07       0  4988.0     0.1       0
Bank Sta=4979.5,4988
Exp/Cntr=0.3,0.1

Type RM Length L Ch R = 1,2189,555,555,555
BEGIN DESCRIPTION:
UNT 084 in HW 4.0
END DESCRIPTION:
XS GIS Cut Line= 3
      1998081.34     13663209.05      1997825.00     13663625.00
      1997408.88     13664152.03
#Sta/Elev= 30
  4526.3  841.38  4674.3  841.79  4723.3  840.69  4754.1  838.43  4775.4  835.07
  4803.5  832.26  4838.1  830.12  4840.4  830.08  4933.8  828.28  4943.4  827.94
  4956.2  826.51  4975.4  825.67  4976.2  824.87  4983.2  824.87  4983.9  825.67
  5036.6  825.67  5086.2  827.44  5135.9  827.53  5150.4  828.55  5185.6  827.34
  5206.4  827.47  5257.0  829.62  5293.1  833.30  5307.5  833.91  5398.8  834.96
  5477.4  834.62  5562.8  835.19  5605.6  836.84  5649.0  839.59  5686.4  840.64
#Mann=5,-1,0
  4526.3     0.1       0  4838.1    0.05       0  4840.4     0.1       0
  4975.4    0.07       0  4983.9     0.1       0
Bank Sta=4975.4,4983.9
Exp/Cntr=0.3,0.1

Type RM Length L Ch R = 1,1634,39,39,39
BEGIN DESCRIPTION:
Mapping XS c93950b7
END DESCRIPTION:
XS GIS Cut Line= 6
      1997668.15     13662910.43      1997386.91     13663281.95
      1997355.66     13663372.23      1997376.49     13663462.50
      1997449.41     13663611.81      1997342.08     13664141.54
#Sta/Elev= 30
  4471.3  840.11  4613.0  840.13  4683.8  838.91  4727.5  840.06  4798.2  839.43
  4827.3  837.07  4898.1  827.10  4922.9  825.67  4923.7  824.87  4931.6  825.67
  4946.8  825.70  5019.7  826.59  5154.0  825.73  5206.7  825.88  5223.7  831.02
  5229.3  829.52  5246.2  830.38  5251.8  828.47  5274.3  828.14  5325.5  829.54
  5334.8  833.34  5339.9  830.86  5345.9  836.35  5385.5  840.63  5407.1  840.71
  5417.3  839.58  5436.2  834.11  5509.1  833.30  5694.7  834.43  5832.1  840.62
#Mann=5,-1,0
  4471.3     0.1       0  4922.9    0.07       0  4931.6     0.1       0
  4946.8    0.16       0  5154.0     0.1       0
Bank Sta=4922.9,4931.6
Exp/Cntr=0.3,0.1

Type RM Length L Ch R = 1,1595,30,30,30
BEGIN DESCRIPTION:
Mapping XS f23c3f76
END DESCRIPTION:
XS GIS Cut Line= 6
      1997636.94     13662879.13      1997334.83     13663309.73
      1997331.35     13663465.98      1997359.13     13663531.95
      1997407.74     13663580.56      1997321.11     13664121.14
#Sta/Elev= 30
  4463.7  840.17  4576.8  839.94  4698.2  837.84  4727.5  839.40  4763.1  839.81
  4784.0  839.04  4841.7  833.97  4884.4  832.04  4927.6  832.26  4935.8  831.42
  4941.5  832.68  4957.5  831.32  4967.4  832.29  4979.3  831.36  4995.4  832.13
  5168.9  832.62  5245.6  831.95  5273.9  832.67  5347.7  828.52  5348.5  827.72
  5355.6  827.72  5356.4  828.52  5372.3  830.19  5382.5  834.09  5398.3  836.04
  5403.4  833.27  5423.0  832.21  5584.2  834.00  5726.8  834.20  5834.3  840.38
#Mann=5,-1,0
  4463.7     0.1       0  4967.4    0.16       0  5168.9     0.1       0
  5347.7    0.07       0  5356.4     0.1       0
Bank Sta=5347.7,5356.4
Exp/Cntr=0.3,0.1

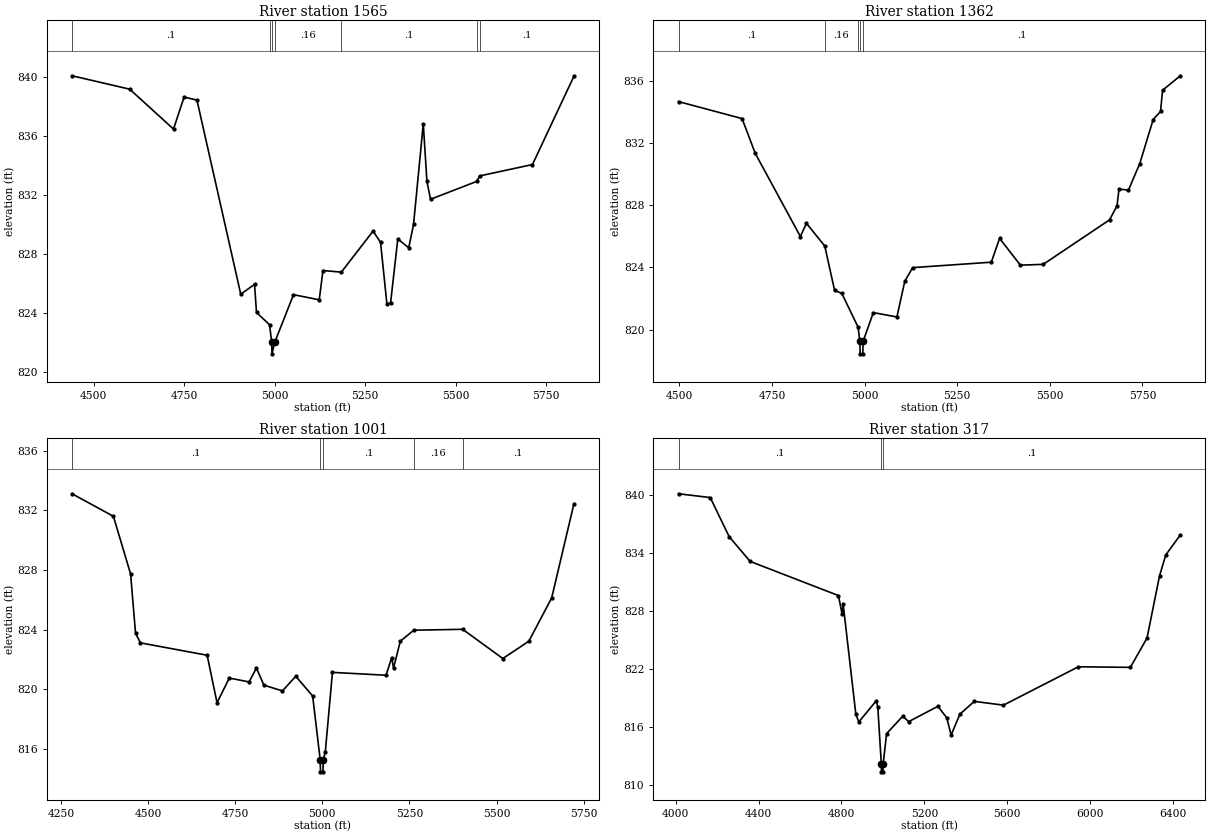
Type RM Length L Ch R = 1,1565,203,203,203
BEGIN DESCRIPTION:
Mapping XS bdac1863
END DESCRIPTION:
XS GIS Cut Line= 6
      1997626.52     13662844.41      1997345.24     13663222.92
      1997310.52     13663292.37      1997317.47     13663514.59
      1997348.72     13663587.50      1997296.63     13664118.80
#Sta/Elev= 30
  4440.4  840.09  4599.5  839.18  4720.5  836.47  4749.7  838.64  4785.2  838.44
  4906.2  825.25  4944.2  825.92  4949.7  824.01  4985.6  823.18  4991.6  822.00
  4992.4  821.20  5000.3  822.00  5051.8  825.22  5122.9  824.87  5133.2  826.86
  5183.9  826.75  5271.6  829.54  5292.2  828.77  5309.7  824.61  5319.8  824.64
  5339.9  829.01  5370.0  828.40  5383.3  829.99  5410.2  836.82  5420.3  832.91
  5430.3  831.70  5557.2  832.91  5566.6  833.29  5711.7  834.06  5826.0  840.05
#Mann=7,-1,0
  4440.4     0.1       0  4985.6    0.16       0  4991.6    0.07       0
  5000.3    0.16       0  5183.9     0.1       0  5557.2    0.16       0
  5566.6     0.1       0
Bank Sta=4991.6,5000.3
Exp/Cntr=0.3,0.1

Type RM Length L Ch R = 1,1362,361,361,361
BEGIN DESCRIPTION:
UNT 084 in HW 3.0
END DESCRIPTION:
XS GIS Cut Line= 3
      1997349.60     13662790.60      1997208.96     13662988.55
      1996833.97     13664035.39
#Sta/Elev= 30
  4497.4  834.66  4668.9  833.57  4704.6  831.33  4826.4  825.99  4842.7  826.84
  4892.2  825.38  4918.7  822.53  4938.3  822.33  4982.1  820.17  4987.0  819.25
  4987.8  818.45  4994.9  818.45  4995.7  819.25  5023.3  821.10  5087.0  820.82
  5108.2  823.11  5129.5  823.99  5341.9  824.34  5364.2  825.87  5420.4  824.15
  5481.9  824.20  5661.1  827.06  5681.3  827.96  5686.6  829.04  5712.0  828.97
  5742.8  830.68  5778.9  833.51  5798.7  834.03  5804.3  835.39  5852.2  836.32
#Mann=5,-1,0
  4497.4     0.1       0  4892.2    0.16       0  4982.1     0.1       0
  4987.0    0.07       0  4995.7     0.1       0
Bank Sta=4987,4995.7
Exp/Cntr=0.3,0.1

Type RM Length L Ch R = 1,1001,684,684,684
BEGIN DESCRIPTION:
UNT 084 in HW 2.0
END DESCRIPTION:
XS GIS Cut Line= 3
      1997234.97     13662717.74      1996818.33     13663092.71
      1996625.85     13663951.07
#Sta/Elev= 30
  4281.8  833.11  4400.4  831.60  4449.8  827.73  4464.0  823.75  4478.2  823.11
  4669.5  822.28  4697.9  819.09  4733.0  820.75  4789.9  820.49  4810.8  821.42
  4832.5  820.27  4885.7  819.89  4923.8  820.87  4972.3  819.55  4994.0  815.26
  4994.8  814.46  5001.9  814.46  5002.7  815.26  5008.6  815.80  5029.1  821.13
  5182.9  820.94  5199.3  822.12  5204.4  821.42  5223.9  823.22  5262.5  823.96
  5403.0  824.02  5518.1  822.06  5592.8  823.22  5658.4  826.13  5722.0  832.42
#Mann=5,-1,0
  4281.8     0.1       0  4994.0    0.07       0  5002.7     0.1       0
  5262.5    0.16       0  5403.0     0.1       0
Bank Sta=4994,5002.7
Exp/Cntr=0.3,0.1

Type RM Length L Ch R = 1,317,0,0,0
BEGIN DESCRIPTION:
UNT 084 in HW 1.0
END DESCRIPTION:
XS GIS Cut Line= 4
      1997636.01     13662738.54      1996813.13     13662603.13
      1996432.92     13662972.92      1996525.00     13664024.96
#Sta/Elev= 30
  4014.1  840.13  4167.1  839.74  4258.4  835.69  4359.7  833.13  4785.3  829.60
  4803.1  827.69  4808.2  828.70  4869.3  817.33  4883.5  816.52  4968.3  818.72
  4975.3  818.03  4992.3  812.16  4993.1  811.36  5000.2  811.36  5001.0  812.16
  5017.7  815.31  5095.6  817.12  5123.9  816.55  5265.2  818.14  5307.6  816.96
  5329.0  815.17  5371.4  817.33  5440.8  818.65  5581.3  818.26  5942.7  822.23
  6193.6  822.17  6273.9  825.21  6334.2  831.64  6364.3  833.80  6434.5  835.87
#Mann=3,-1,0
  4014.1     0.1       0  4992.3    0.07       0  5001.0     0.1       0
Bank Sta=4992.3,5001
Exp/Cntr=0.3,0.1

Chan Stop Cuts=-1