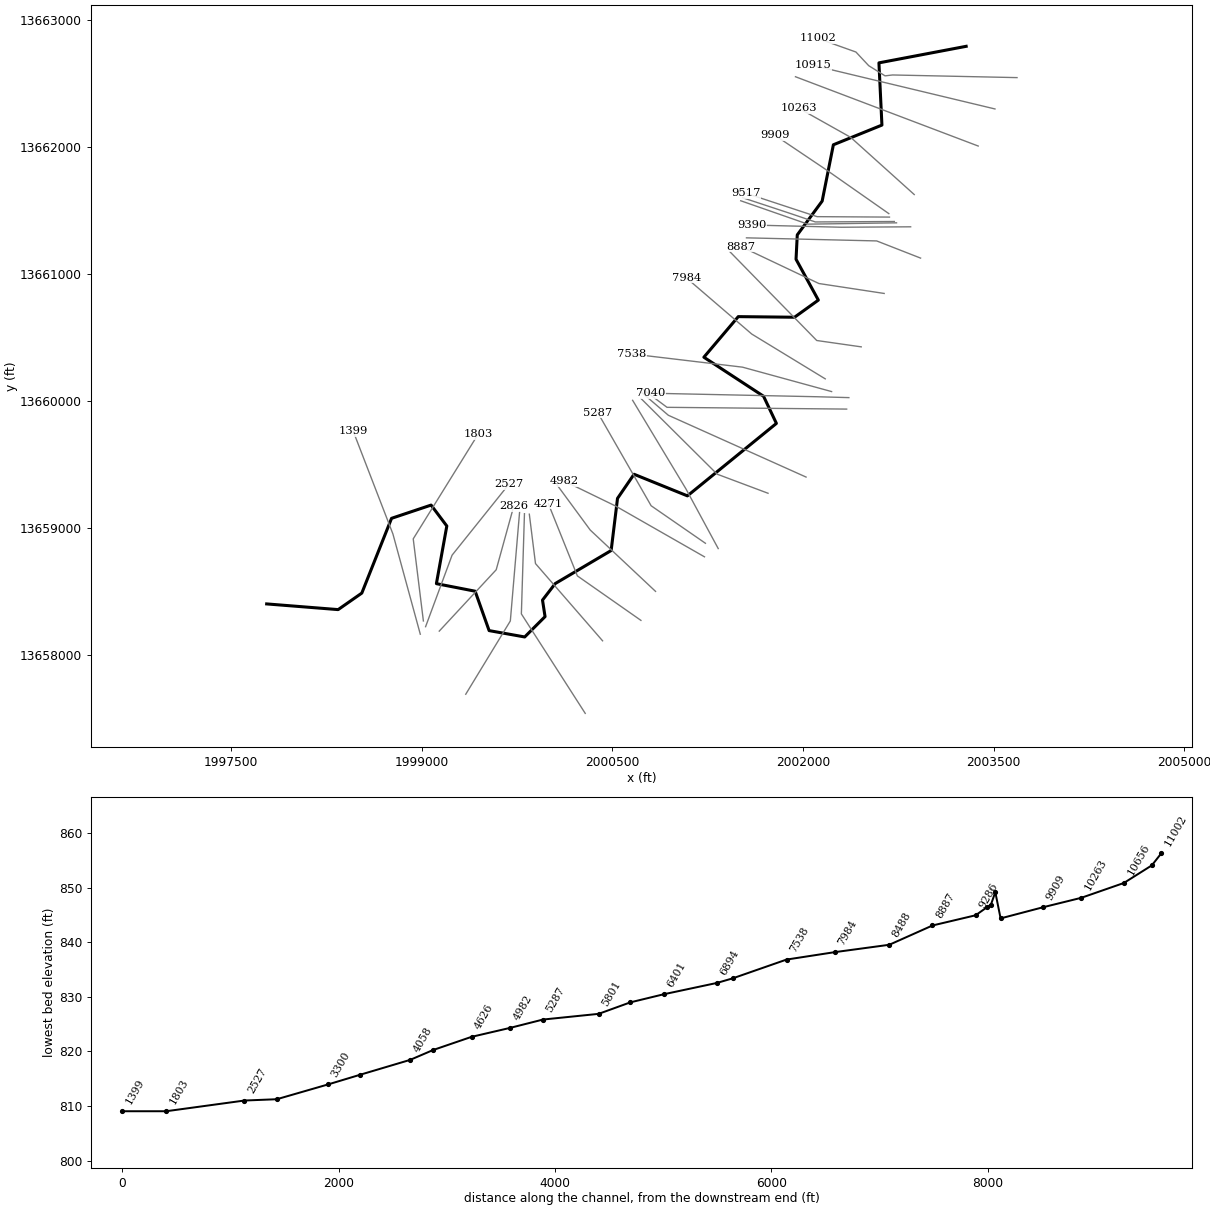
--- UNT 085 in HW.prj (project) ---

Proj Title=UNT 085 in HW Base Level Engineering
Current Plan=p01
Default Exp/Contr=0.3,0.1
English Units
Geom File=g01
Flow File=f01
Plan File=p01
BEGIN DESCRIPTION:
UNT 085 in HW
END DESCRIPTION:

--- UNT 085 in HW.p01 (plan) ---

Plan Title=Multiple Run
Short Identifier=Multiple
Geom File=g01
Flow File=f01
Subcritical Flow
K Sum by GR= 0
Std Step Tol= 0.01
Critical Tol= 0.01
Num of Std Step Trials= 20
Max Error Tol= 0.3
Flow Tol Ratio= 0.001
Split Flow NTrial= 30
Split Flow Tol= 0.02
Split Flow Ratio= 0.02
Log Output Level= 0
Friction Slope Method= 1
Unsteady Friction Slope Method= 2
Unsteady Bridges Friction Slope Method= 1
Parabolic Critical Depth
Global Vel Dist=  1 , 1 , 1
Global Log Level= 0
CheckData=True
Encroach Param= -1, 0, 0, 0
BEGIN DESCRIPTION:
Multiple Run
END DESCRIPTION:

--- UNT 085 in HW.f01 (steady flow) ---

Flow Title=Multiple
Number of Profiles=7
Profile Names=10-year,25-year,50-year,1pct_min,100-year,1pct_plu,500-year
River Rch & RM= UNT 085 in HW,Reach-1,11002
     592     834    1036     638    1273    2541    1929
River Rch & RM= UNT 085 in HW,Reach-1,10656
     828    1182    1482     919    1834    3659    2818
Boundary for River Rch & Prof#=UNT 085 in HW,Reach-1,1
Up Type=0
Dn Type=3
Dn Slope=0.005
Boundary for River Rch & Prof#=UNT 085 in HW,Reach-1,2
Up Type=0
Dn Type=3
Dn Slope=0.005
Boundary for River Rch & Prof#=UNT 085 in HW,Reach-1,3
Up Type=0
Dn Type=3
Dn Slope=0.005
Boundary for River Rch & Prof#=UNT 085 in HW,Reach-1,4
Up Type=0
Dn Type=3
Dn Slope=0.005
Boundary for River Rch & Prof#=UNT 085 in HW,Reach-1,5
Up Type=0
Dn Type=3
Dn Slope=0.005
Boundary for River Rch & Prof#=UNT 085 in HW,Reach-1,6
Up Type=0
Dn Type=3
Dn Slope=0.005
Boundary for River Rch & Prof#=UNT 085 in HW,Reach-1,7
Up Type=0
Dn Type=3
Dn Slope=0.005

--- UNT 085 in HW.g01 (geometry) ---

Geom Title=Existing Conditions

River Reach=UNT 085 in HW,Reach-1
Reach XY= 30
      2003283.58     13662791.04      2002597.38     13662660.84
      2002620.91     13662171.34      2002238.96     13662016.48
      2002150.77     13661573.42      2001954.94     13661307.45
      2001945.21     13661115.78      2002120.80     13660794.54
      2001933.41     13660659.77      2001490.80     13660664.54
      2001220.21     13660345.18      2001689.66     13660038.24
      2001790.80     13659824.54      2001090.80     13659254.54
      2000670.80     13659424.54      2000540.80     13659234.54
      2000490.80     13658824.54      2000050.80     13658564.54
      1999950.80     13658434.54      1999970.80     13658304.54
      1999810.80     13658144.54      1999530.80     13658194.54
      1999420.80     13658504.54      1999116.05     13658563.93
      1999197.99     13659017.40      1999074.38     13659181.99
      1998763.27     13659077.82      1998529.24     13658489.63
      1998343.13     13658359.77      1997780.80     13658404.54

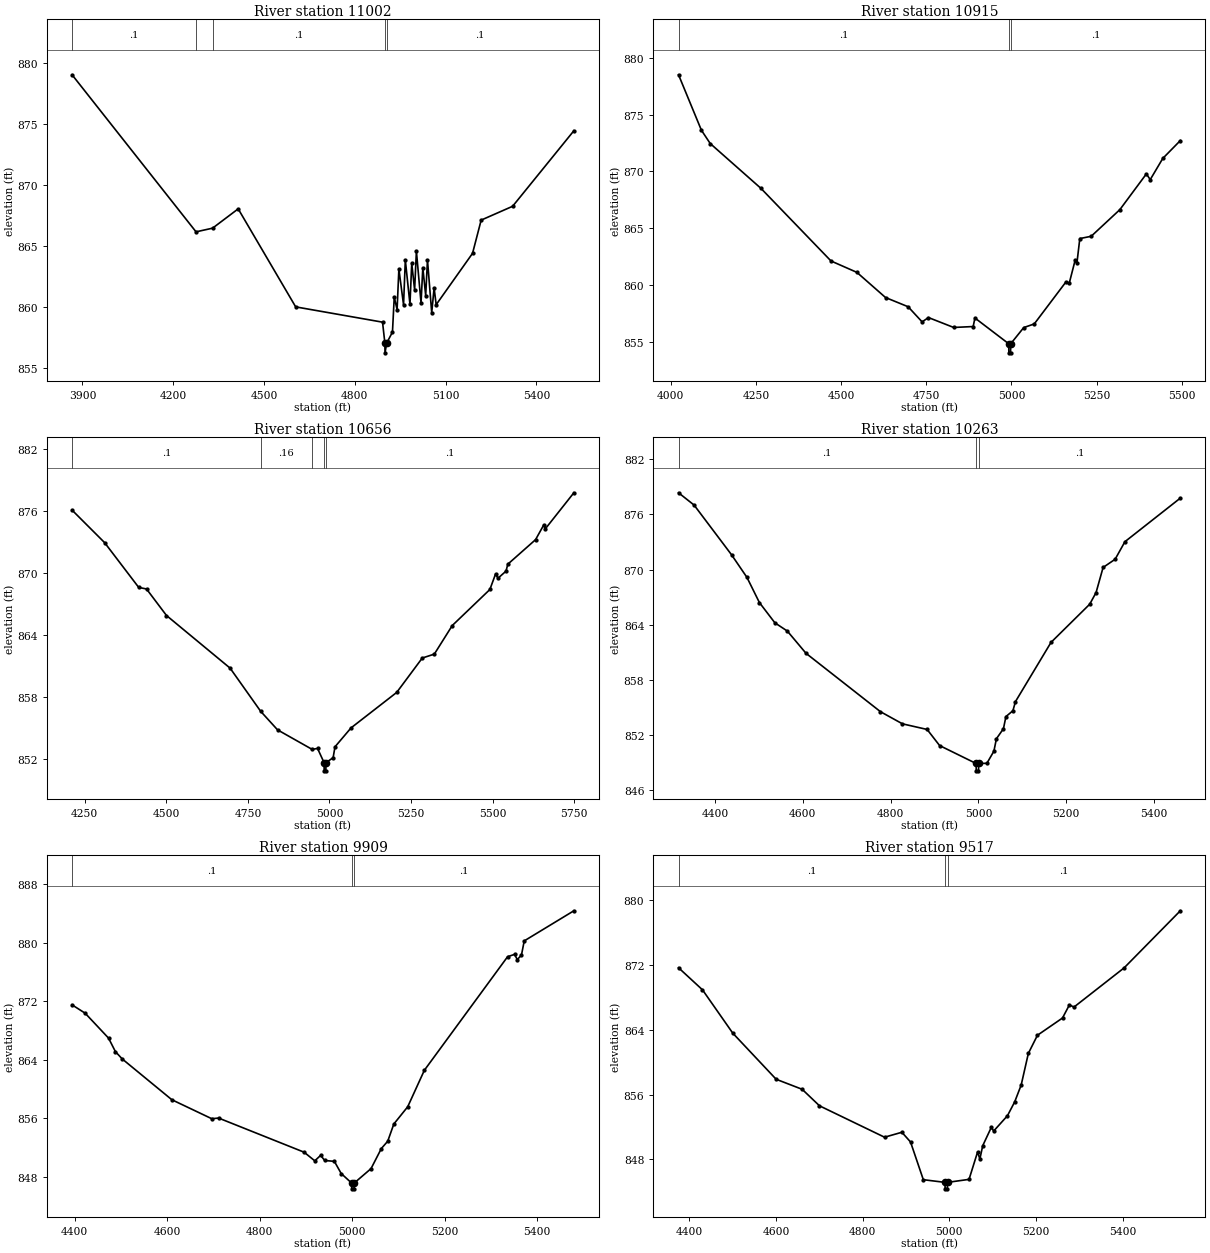
Type RM Length L Ch R = 1,11002,87,87,87
BEGIN DESCRIPTION:
UNT 085 in HW 21.0
END DESCRIPTION:
XS GIS Cut Line= 6
      2003683.74     13662544.80      2002704.62     13662565.63
      2002645.59     13662558.68      2002517.12     13662638.55
      2002416.42     13662746.18      2002114.37     13662853.81
#Sta/Elev= 30
  3865.7  879.00  4275.3  866.15  4330.0  866.45  4414.6  868.03  4604.6  860.01
  4891.6  858.76  4899.3  857.05  4899.8  856.25  4905.3  857.05  4924.4  857.95
  4930.3  860.82  4939.7  859.78  4945.6  863.11  4961.0  860.18  4966.9  863.84
  4982.2  860.23  4988.1  863.57  4997.6  861.40  5003.5  864.57  5018.8  860.33
  5024.7  863.22  5034.2  860.94  5040.1  863.85  5054.1  859.53  5062.0  861.56
  5068.8  860.19  5189.0  864.39  5217.5  867.11  5321.4  868.24  5523.8  874.42
#Mann=5,-1,0
  3865.7     0.1       0  4275.3    0.05       0  4330.0     0.1       0
  4899.3    0.07       0  4905.3     0.1       0
Bank Sta=4899.3,4905.3
Exp/Cntr=0.3,0.1

Type RM Length L Ch R = 1,10915,259,259,259
BEGIN DESCRIPTION:
Mapping XS 5a3fd499
END DESCRIPTION:
XS GIS Cut Line= 2
      2003510.22     13662298.26      2002078.09     13662641.55
#Sta/Elev= 30
  4022.9  878.49  4090.0  873.62  4115.9  872.45  4264.8  868.51  4470.4  862.13
  4546.4  861.13  4630.4  858.92  4696.7  858.11  4737.8  856.78  4756.4  857.16
  4830.4  856.29  4887.6  856.37  4892.8  857.12  4991.9  854.86  4992.4  854.06
  4997.4  854.06  4997.9  854.86  5036.0  856.28  5066.9  856.60  5159.4  860.27
  5169.7  860.19  5186.9  862.20  5192.0  861.92  5200.6  864.10  5234.0  864.30
  5318.1  866.64  5395.9  869.78  5407.3  869.28  5444.1  871.14  5495.6  872.71
#Mann=3,-1,0
  4022.9     0.1       0  4991.9    0.07       0  4997.9     0.1       0
Bank Sta=4991.9,4997.9
Exp/Cntr=0.3,0.1

Type RM Length L Ch R = 1,10656,393,393,393
BEGIN DESCRIPTION:
Mapping XS c679d5fc
END DESCRIPTION:
XS GIS Cut Line= 2
      2003378.25     13662006.59      2001940.75     13662551.73
#Sta/Elev= 30
  4211.3  876.09  4311.0  872.94  4415.5  868.60  4439.4  868.45  4500.6  865.88
  4695.5  860.78  4789.1  856.60  4840.9  854.80  4946.8  852.91  4963.4  853.00
  4983.3  851.63  4983.8  850.83  4988.8  850.83  4989.3  851.63  5011.1  852.10
  5016.9  853.16  5066.0  854.99  5206.0  858.43  5284.3  861.76  5321.2  862.14
  5376.2  864.91  5491.4  868.40  5508.9  869.91  5516.2  869.49  5540.9  870.18
  5546.3  870.85  5631.4  873.23  5656.2  874.64  5661.6  874.29  5748.7  877.77
#Mann=5,-1,0
  4211.3     0.1       0  4789.1    0.16       0  4946.8     0.1       0
  4983.3    0.07       0  4989.3     0.1       0
Bank Sta=4983.3,4989.3
Exp/Cntr=0.3,0.1

Type RM Length L Ch R = 1,10263,354,354,354
BEGIN DESCRIPTION:
UNT 085 in HW 20.0
END DESCRIPTION:
XS GIS Cut Line= 3
      2002875.00     13661625.00      2002375.00     13662075.00
      2001965.00     13662305.23
#Sta/Elev= 30
  4317.0  878.36  4352.5  877.02  4437.7  871.62  4472.8  869.16  4501.2  866.42
  4536.4  864.22  4564.8  863.32  4607.4  860.90  4777.0  854.55  4827.1  853.23
  4883.2  852.62  4911.6  850.87  4994.7  848.92  4995.2  848.12  5000.2  848.12
  5000.7  848.92  5019.3  848.94  5035.3  850.26  5041.0  851.61  5057.0  852.70
  5062.7  854.02  5078.6  854.66  5084.4  855.65  5165.4  862.09  5253.5  866.24
  5268.0  867.51  5284.0  870.24  5311.4  871.13  5333.7  873.04  5459.9  877.78
#Mann=3,-1,0
  4317.0     0.1       0  4994.7    0.07       0  5000.7     0.1       0
Bank Sta=4994.7,5000.7
Exp/Cntr=0.3,0.1

Type RM Length L Ch R = 1,9909,392,392,392
BEGIN DESCRIPTION:
UNT 085 in HW 19.0
END DESCRIPTION:
XS GIS Cut Line= 3
      2002675.01     13661475.00      2002175.00     13661825.00
      2001781.02     13662089.92
#Sta/Elev= 30
  4394.1  871.50  4422.4  870.36  4473.0  866.96  4487.8  865.12  4502.7  864.11
  4609.9  858.55  4696.2  855.96  4711.0  856.05  4895.9  851.39  4919.0  850.21
  4931.6  850.96  4940.4  850.26  4961.3  850.14  4976.1  848.48  4998.4  847.19
  4998.9  846.39  5003.9  846.39  5004.4  847.19  5040.6  849.15  5062.9  851.89
  5076.7  852.89  5089.9  855.24  5119.9  857.59  5155.9  862.57  5335.9  878.07
  5350.9  878.39  5356.9  877.68  5365.9  878.30  5371.9  880.23  5479.2  884.34
#Mann=3,-1,0
  4394.1     0.1       0  4998.4    0.07       0  5004.4     0.1       0
Bank Sta=4998.4,5004.4
Exp/Cntr=0.3,0.1

Type RM Length L Ch R = 1,9517,49,49,49
BEGIN DESCRIPTION:
Mapping XS ea4fb1c3
END DESCRIPTION:
XS GIS Cut Line= 3
      2002680.34     13661447.57      2002110.87     13661451.05
      2001551.86     13661635.07
#Sta/Elev= 30
  4375.3  871.67  4430.6  868.94  4500.6  863.58  4600.6  857.89  4660.6  856.65
  4700.6  854.61  4850.7  850.73  4890.7  851.34  4910.7  850.14  4940.2  845.48
  4990.1  845.15  4990.6  844.35  4995.6  844.35  4996.1  845.15  5045.7  845.52
  5065.4  848.90  5070.7  848.04  5077.3  849.68  5097.2  851.96  5102.5  851.49
  5134.3  853.38  5151.0  855.09  5166.0  857.17  5182.6  861.09  5203.6  863.33
  5261.4  865.46  5277.3  867.08  5287.9  866.81  5403.7  871.66  5533.3  878.71
#Mann=3,-1,0
  4375.3     0.1       0  4990.1    0.07       0  4996.1     0.1       0
Bank Sta=4990.1,4996.1
Exp/Cntr=0.3,0.1

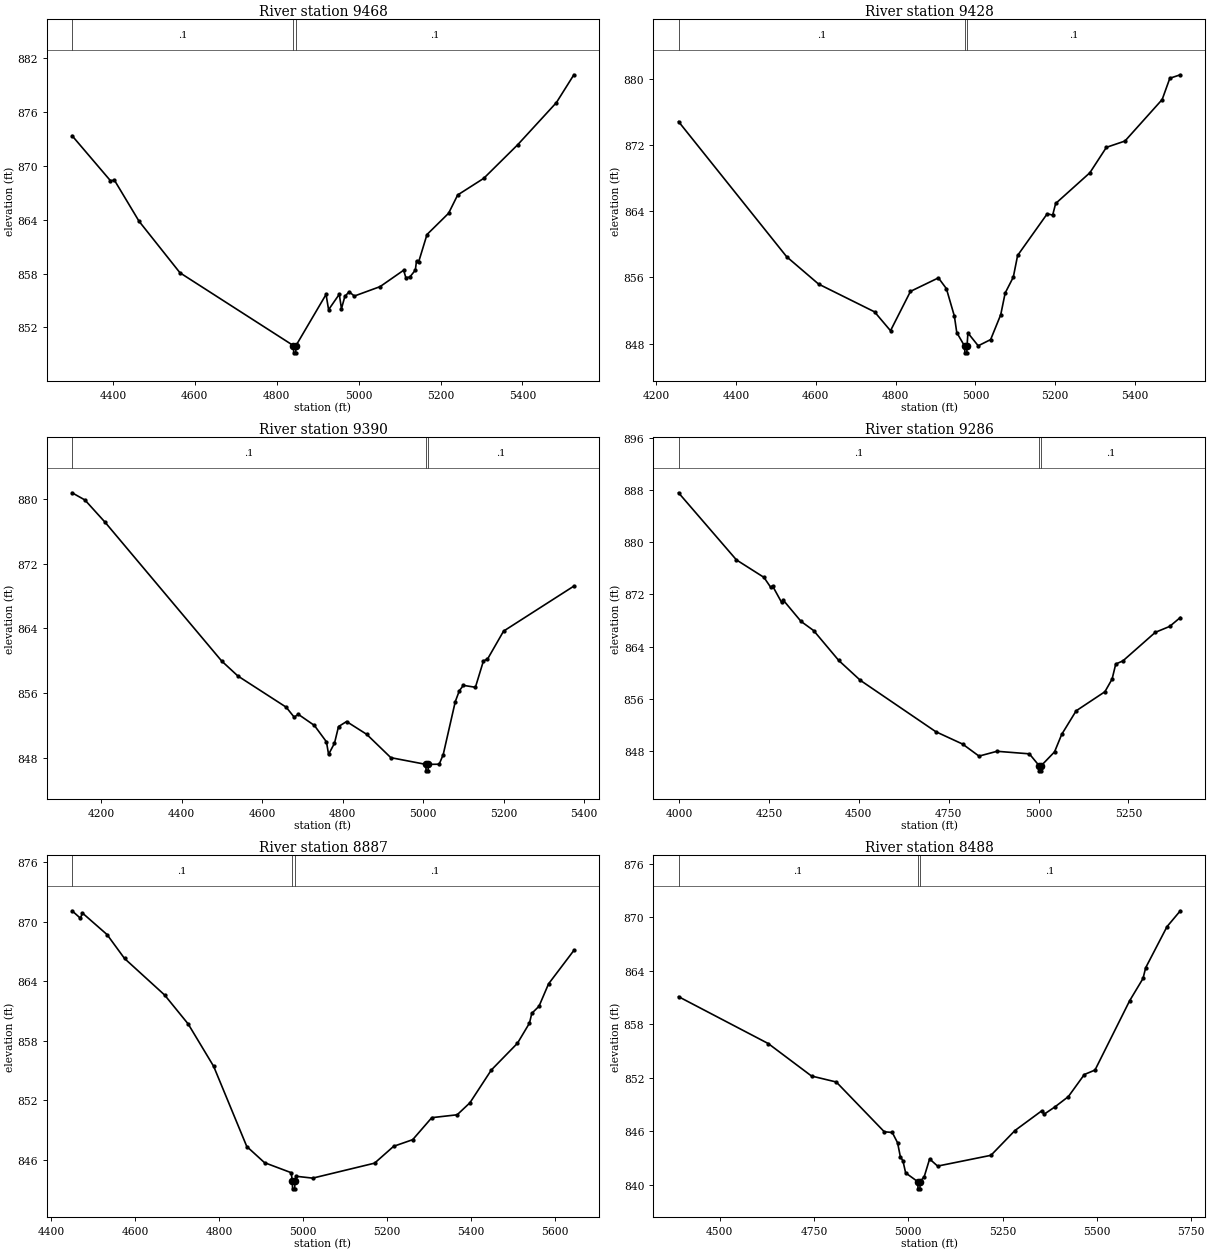
Type RM Length L Ch R = 1,9468,40,40,40
BEGIN DESCRIPTION:
Mapping XS 5b2441f3
END DESCRIPTION:
XS GIS Cut Line= 4
      2002718.51     13661412.85      2002096.98     13661409.38
      2001892.12     13661478.82      2001524.59     13661600.18
#Sta/Elev= 30
  4300.5  873.37  4394.0  868.36  4404.0  868.40  4464.0  863.83  4564.0  858.08
  4841.0  849.96  4841.5  849.16  4846.5  849.16  4847.0  849.96  4920.5  855.67
  4926.7  853.97  4952.8  855.69  4958.1  854.08  4966.4  855.45  4976.9  855.97
  4989.5  855.49  5052.3  856.54  5109.9  858.37  5115.2  857.55  5124.8  857.60
  5138.4  858.38  5141.3  859.41  5146.6  859.31  5166.9  862.35  5219.6  864.72
  5241.8  866.76  5305.3  868.61  5388.1  872.35  5482.8  877.06  5525.4  880.16
#Mann=3,-1,0
  4300.5     0.1       0  4841.0    0.07       0  4847.0     0.1       0
Bank Sta=4841,4847
Exp/Cntr=0.3,0.1

Type RM Length L Ch R = 1,9428,38,38,38
BEGIN DESCRIPTION:
Mapping XS c67c2a5d
END DESCRIPTION:
XS GIS Cut Line= 3
      2002735.90     13661402.44      2002037.95     13661392.02
      2001510.14     13661576.06
#Sta/Elev= 30
  4256.2  874.81  4527.1  858.49  4607.1  855.19  4747.2  851.84  4787.2  849.56
  4837.2  854.31  4907.2  855.94  4927.2  854.64  4947.2  851.32  4953.2  849.34
  4972.9  847.69  4973.4  846.89  4978.4  846.89  4978.9  847.69  4981.1  849.29
  5006.9  847.74  5038.0  848.49  5063.3  851.49  5074.4  854.11  5094.8  856.03
  5105.6  858.65  5179.8  863.68  5193.4  863.52  5200.9  864.92  5286.6  868.63
  5328.0  871.70  5374.5  872.46  5467.7  877.47  5486.9  880.04  5513.2  880.46
#Mann=3,-1,0
  4256.2     0.1       0  4972.9    0.07       0  4978.9     0.1       0
Bank Sta=4972.9,4978.9
Exp/Cntr=0.3,0.1

Type RM Length L Ch R = 1,9390,104,104,104
BEGIN DESCRIPTION:
UNT 085 in HW 18.0
END DESCRIPTION:
XS GIS Cut Line= 3
      2002846.93     13661371.18      2002301.84     13661367.71
      2001600.46     13661385.07
#Sta/Elev= 30
  4127.9  880.79  4159.8  879.90  4209.8  877.15  4499.8  859.96  4539.8  858.12
  4659.8  854.26  4679.8  853.02  4689.8  853.38  4729.9  852.00  4759.9  849.97
  4765.2  848.42  4779.9  849.80  4789.9  851.86  4809.9  852.48  4859.9  850.90
  4919.9  848.01  5006.9  847.18  5007.4  846.38  5012.4  846.38  5012.9  847.18
  5040.0  847.20  5050.0  848.39  5080.0  854.95  5090.0  856.28  5100.0  856.96
  5130.0  856.72  5150.0  859.99  5160.0  860.20  5200.0  863.67  5374.6  869.24
#Mann=3,-1,0
  4127.9     0.1       0  5006.9    0.07       0  5012.9     0.1       0
Bank Sta=5006.9,5012.9
Exp/Cntr=0.3,0.1

Type RM Length L Ch R = 1,9286,399,399,399
BEGIN DESCRIPTION:
UNT 085 in HW 17.0
END DESCRIPTION:
XS GIS Cut Line= 3
      2002924.98     13661125.01      2002579.62     13661260.07
      2001555.34     13661284.38
#Sta/Elev= 30
  3998.9  887.59  4159.9  877.29  4236.4  874.61  4255.5  873.06  4260.8  873.25
  4285.3  870.79  4290.7  871.08  4339.6  867.85  4374.5  866.45  4444.4  861.86
  4504.4  858.81  4714.5  850.92  4788.8  849.03  4834.5  847.18  4884.5  847.92
  4974.5  847.53  5001.5  845.72  5002.0  844.92  5007.1  844.92  5007.6  845.72
  5044.5  847.83  5064.5  850.52  5104.6  854.13  5184.6  857.06  5204.6  859.01
  5214.7  861.31  5234.6  861.79  5324.6  866.17  5364.6  867.08  5394.3  868.45
#Mann=3,-1,0
  3998.9     0.1       0  5001.5    0.07       0  5007.6     0.1       0
Bank Sta=5001.5,5007.6
Exp/Cntr=0.3,0.1

Type RM Length L Ch R = 1,8887,399,399,399
BEGIN DESCRIPTION:
UNT 085 in HW 16.0
END DESCRIPTION:
XS GIS Cut Line= 3
      2002638.62     13660846.88      2002125.00     13660925.00
      2001513.60     13661214.96
#Sta/Elev= 30
  4449.6  871.10  4469.4  870.35  4474.4  870.87  4533.0  868.70  4574.6  866.29
  4670.3  862.60  4726.4  859.68  4787.1  855.41  4866.1  847.32  4908.4  845.69
  4971.9  844.68  4974.7  843.85  4975.2  843.05  4980.3  843.05  4980.8  843.85
  4983.3  844.32  5023.2  844.13  5170.7  845.64  5216.2  847.34  5261.6  848.01
  5307.1  850.23  5367.6  850.52  5398.0  851.73  5449.1  855.04  5511.4  857.74
  5540.0  859.77  5545.5  860.75  5562.7  861.47  5585.5  863.73  5645.8  867.10
#Mann=3,-1,0
  4449.6     0.1       0  4974.7    0.07       0  4980.8     0.1       0
Bank Sta=4974.7,4980.8
Exp/Cntr=0.3,0.1

Type RM Length L Ch R = 1,8488,504,504,504
BEGIN DESCRIPTION:
UNT 085 in HW 15.0
END DESCRIPTION:
XS GIS Cut Line= 3
      2002458.13     13660426.73      2002108.09     13660476.74
      2001425.01     13661174.99
#Sta/Elev= 30
  4391.0  861.07  4628.9  855.81  4743.6  852.17  4809.2  851.50  4936.5  845.92
  4957.7  845.84  4971.8  844.68  4979.0  843.14  4986.0  842.65  4993.1  841.31
  5025.4  840.32  5025.9  839.52  5031.0  839.52  5031.5  840.32  5042.5  840.90
  5056.7  842.87  5077.9  842.07  5219.3  843.28  5283.0  846.06  5353.7  848.26
  5360.7  847.90  5389.0  848.71  5424.5  849.86  5466.9  852.34  5495.2  852.84
  5587.0  860.61  5622.5  863.11  5629.5  864.31  5686.1  868.92  5721.4  870.70
#Mann=3,-1,0
  4391.0     0.1       0  5025.4    0.07       0  5031.5     0.1       0
Bank Sta=5025.4,5031.5
Exp/Cntr=0.3,0.1

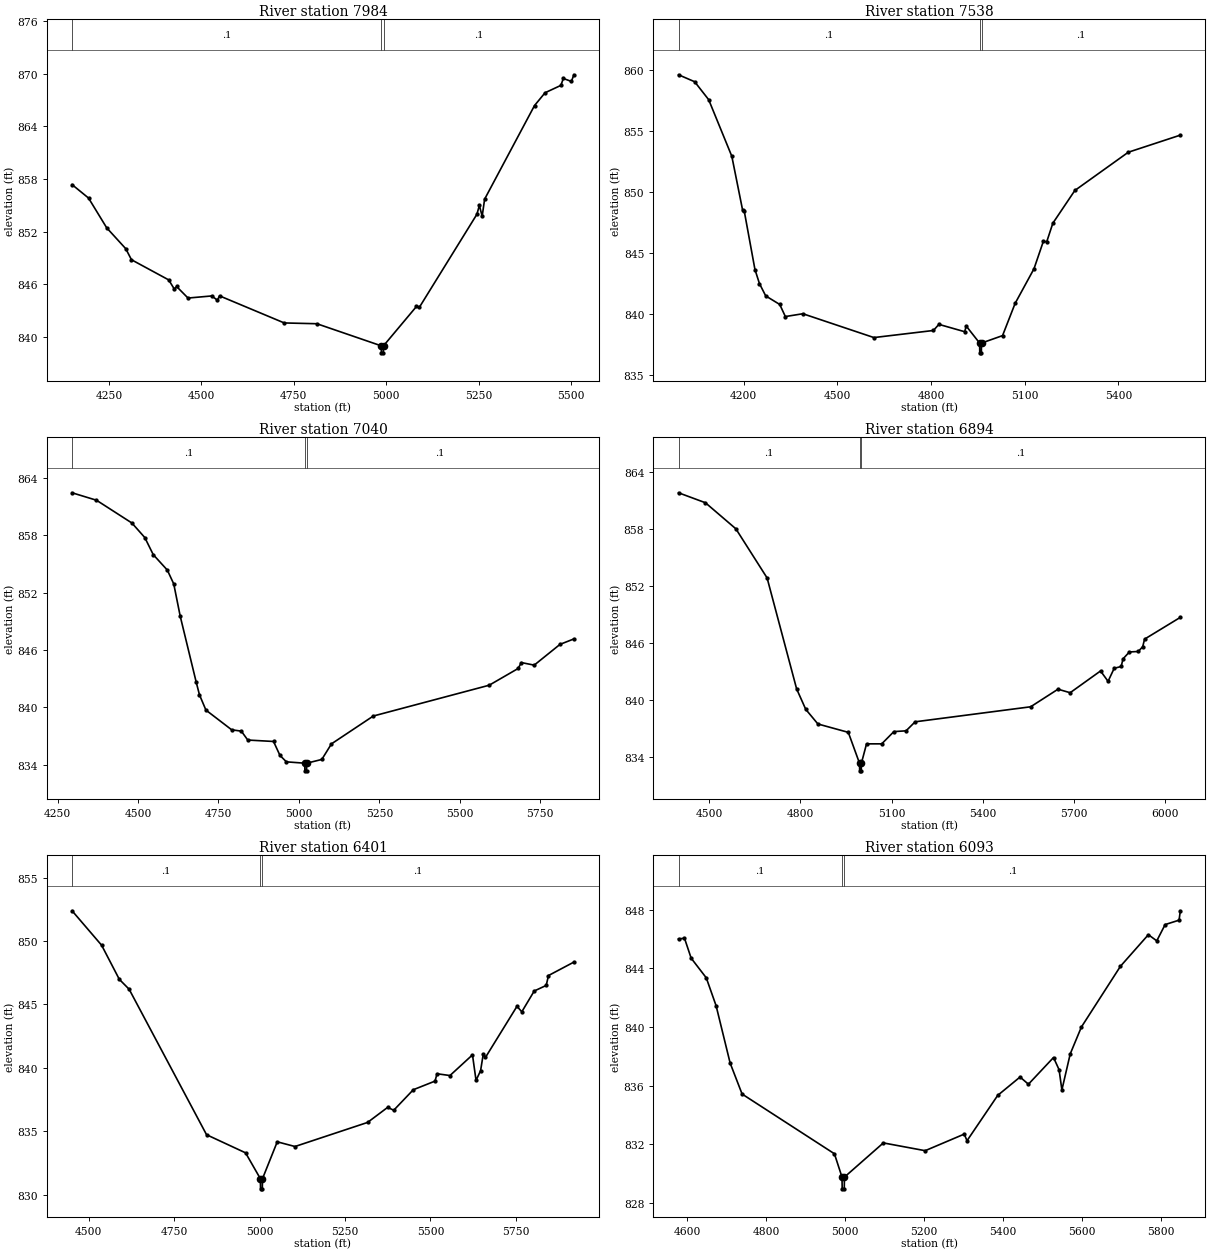
Type RM Length L Ch R = 1,7984,446,446,446
BEGIN DESCRIPTION:
UNT 085 in HW 14.0
END DESCRIPTION:
XS GIS Cut Line= 3
      2002174.99     13660175.01      2001596.98     13660527.43
      2001080.93     13660970.75
#Sta/Elev= 30
  4150.5  857.36  4195.0  855.83  4244.2  852.43  4295.7  850.05  4311.2  848.79
  4411.9  846.49  4427.4  845.42  4433.2  845.74  4464.1  844.42  4528.1  844.66
  4543.6  844.18  4549.4  844.67  4724.4  841.58  4812.7  841.49  4986.8  838.97
  4987.3  838.17  4992.4  838.17  4992.9  838.97  5082.1  843.46  5089.7  843.35
  5245.6  853.98  5252.2  854.99  5259.8  853.75  5266.4  855.70  5401.4  866.38
  5429.9  867.84  5472.7  868.68  5479.3  869.47  5501.2  869.13  5507.8  869.89
#Mann=3,-1,0
  4150.5     0.1       0  4986.8    0.07       0  4992.9     0.1       0
Bank Sta=4986.8,4992.9
Exp/Cntr=0.3,0.1

Type RM Length L Ch R = 1,7538,498,498,498
BEGIN DESCRIPTION:
UNT 085 in HW 13.0
END DESCRIPTION:
XS GIS Cut Line= 3
      2002225.00     13660075.00      2001524.06     13660267.02
      2000649.50     13660371.13
#Sta/Elev= 30
  3990.9  859.57  4042.6  859.00  4087.5  857.53  4161.6  852.90  4196.1  848.50
  4201.3  848.43  4235.7  843.63  4250.1  842.48  4270.2  841.47  4315.1  840.77
  4333.1  839.78  4389.2  840.01  4616.8  838.06  4807.4  838.64  4825.0  839.14
  4907.5  838.54  4912.6  839.00  4955.4  837.61  4955.9  836.81  4961.0  836.81
  4961.5  837.61  5028.9  838.22  5069.2  840.86  5129.6  843.69  5159.8  845.95
  5170.4  845.90  5190.0  847.42  5260.5  850.10  5431.7  853.23  5598.4  854.63
#Mann=3,-1,0
  3990.9     0.1       0  4955.4    0.07       0  4961.5     0.1       0
Bank Sta=4955.4,4961.5
Exp/Cntr=0.3,0.1

Type RM Length L Ch R = 1,7040,146,146,146
BEGIN DESCRIPTION:
UNT 085 in HW 12.0
END DESCRIPTION:
XS GIS Cut Line= 3
      2002360.87     13660027.43      2002107.40     13660034.38
      2000801.86     13660062.16
#Sta/Elev= 30
  4295.1  862.44  4371.0  861.66  4481.0  859.28  4521.1  857.76  4547.4  855.97
  4591.1  854.36  4611.1  852.91  4631.1  849.55  4681.1  842.61  4691.1  841.31
  4711.1  839.72  4791.1  837.66  4821.1  837.52  4841.1  836.59  4921.2  836.44
  4941.2  834.98  4961.2  834.31  5018.1  834.17  5018.6  833.37  5023.8  833.37
  5024.3  834.17  5071.2  834.56  5101.2  836.19  5231.2  839.10  5591.3  842.32
  5681.3  844.07  5691.3  844.69  5731.3  844.42  5811.4  846.59  5854.5  847.16
#Mann=3,-1,0
  4295.1     0.1       0  5018.1    0.07       0  5024.3     0.1       0
Bank Sta=5018.1,5024.3
Exp/Cntr=0.3,0.1

Type RM Length L Ch R = 1,6894,493,493,493
BEGIN DESCRIPTION:
Mapping XS 81669009
END DESCRIPTION:
XS GIS Cut Line= 3
      2002343.54     13659937.16      2000930.31     13659951.05
      2000739.65     13660093.17
#Sta/Elev= 30
  4398.7  861.79  4487.2  860.74  4587.3  858.00  4690.1  852.83  4787.3  841.15
  4817.3  839.00  4857.3  837.46  4957.3  836.58  4994.2  833.33  4994.7  832.53
  4999.9  832.53  5000.4  833.33  5017.3  835.37  5067.3  835.37  5107.3  836.66
  5147.3  836.74  5177.3  837.69  5557.3  839.27  5647.3  841.12  5687.3  840.75
  5787.3  843.04  5812.0  841.95  5832.2  843.32  5855.1  843.51  5861.4  844.32
  5882.2  845.04  5911.4  845.09  5926.0  845.59  5932.2  846.39  6049.8  848.68
#Mann=3,-1,0
  4398.7     0.1       0  4994.2    0.07       0  5000.4     0.1       0
Bank Sta=4994.2,5000.4
Exp/Cntr=0.3,0.1

Type RM Length L Ch R = 1,6401,308,308,308
BEGIN DESCRIPTION:
Mapping XS 083bcafd
END DESCRIPTION:
XS GIS Cut Line= 3
      2002024.07     13659402.43      2000940.73     13659888.55
      2000726.99     13660071.26
#Sta/Elev= 30
  4451.2  852.39  4537.7  849.67  4589.5  846.98  4618.2  846.20  4844.8  834.72
  4959.0  833.29  5002.3  831.25  5002.8  830.45  5008.0  830.45  5008.5  831.25
  5051.7  834.16  5103.6  833.79  5316.1  835.69  5374.9  836.88  5392.6  836.65
  5449.9  838.27  5513.4  838.95  5519.4  839.53  5557.2  839.39  5623.1  841.02
  5633.5  839.01  5646.8  839.77  5654.5  841.06  5661.1  840.82  5753.3  844.85
  5767.5  844.42  5803.8  846.06  5838.9  846.50  5845.5  847.28  5919.8  848.34
#Mann=3,-1,0
  4451.2     0.1       0  5002.3    0.07       0  5008.5     0.1       0
Bank Sta=5002.3,5008.5
Exp/Cntr=0.3,0.1

Type RM Length L Ch R = 1,6093,292,292,292
BEGIN DESCRIPTION:
UNT 085 in HW 11.0
END DESCRIPTION:
XS GIS Cut Line= 3
      2001724.97     13659275.01      2001325.00     13659425.00
      2000725.73     13660020.22
#Sta/Elev= 30
  4577.7  846.00  4592.8  846.05  4609.7  844.69  4648.0  843.35  4672.9  841.45
  4708.5  837.54  4738.8  835.43  4972.8  831.36  4992.0  829.77  4992.5  828.97
  4997.7  828.97  4998.2  829.77  5096.8  832.10  5202.8  831.57  5301.8  832.70
  5308.9  832.25  5386.7  835.34  5443.3  836.59  5464.5  836.10  5528.1  837.92
  5542.2  837.09  5549.3  835.71  5570.5  838.17  5598.8  840.00  5697.8  844.14
  5768.5  846.29  5789.8  845.87  5811.0  846.98  5846.3  847.28  5849.5  847.92
#Mann=3,-1,0
  4577.7     0.1       0  4992.0    0.07       0  4998.2     0.1       0
Bank Sta=4992,4998.2
Exp/Cntr=0.3,0.1

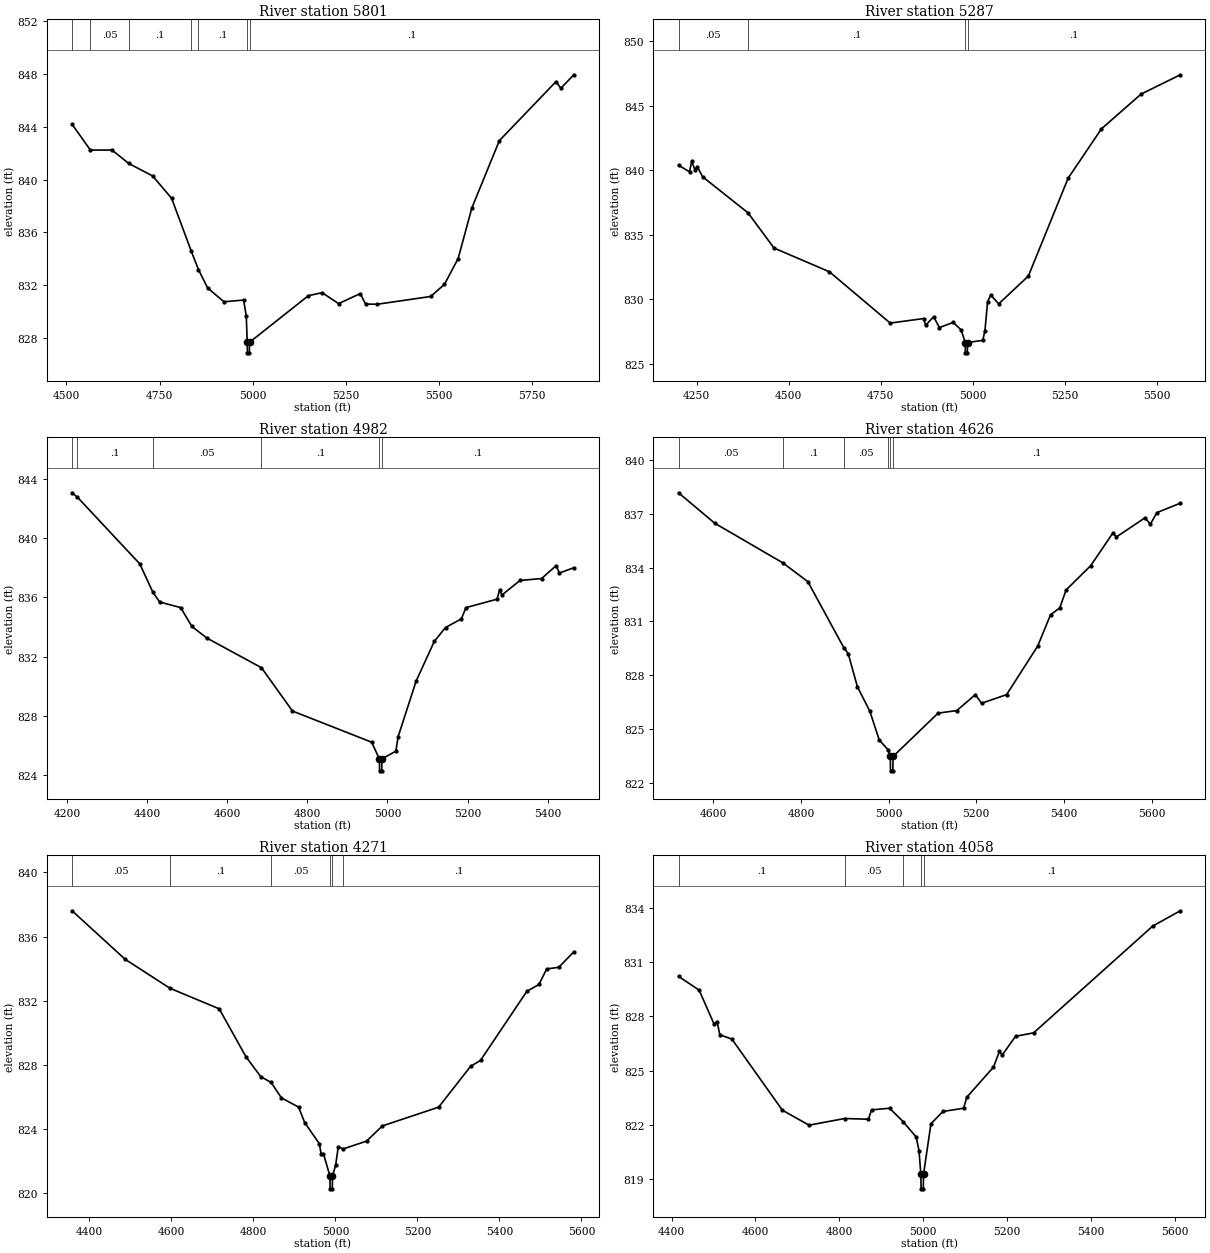
Type RM Length L Ch R = 1,5801,514,514,514
BEGIN DESCRIPTION:
UNT 085 in HW 10.0
END DESCRIPTION:
XS GIS Cut Line= 3
      2001333.09     13658839.93      2001079.62     13659308.68
      2000659.75     13660006.15
#Sta/Elev= 30
  4515.3  844.19  4564.6  842.23  4622.3  842.24  4667.5  841.22  4731.7  840.27
  4782.5  838.58  4834.7  834.62  4854.5  833.18  4879.2  831.79  4923.0  830.74
  4975.8  830.87  4982.9  829.67  4985.5  827.67  4986.0  826.87  4991.2  826.87
  4991.7  827.67  5149.6  831.20  5186.5  831.43  5230.7  830.60  5289.0  831.36
  5303.0  830.57  5334.1  830.55  5477.8  831.14  5514.7  832.05  5551.6  834.01
  5588.5  837.85  5662.3  842.95  5814.3  847.42  5827.4  846.92  5862.3  847.94
#Mann=7,-1,0
  4515.3     0.1       0  4564.6    0.05       0  4667.5     0.1       0
  4834.7    0.16       0  4854.5     0.1       0  4985.5    0.07       0
  4991.7     0.1       0
Bank Sta=4985.5,4991.7
Exp/Cntr=0.3,0.1

Type RM Length L Ch R = 1,5287,305,305,305
BEGIN DESCRIPTION:
Mapping XS 60af70e3
END DESCRIPTION:
XS GIS Cut Line= 3
      2001232.37     13658881.62      2000805.31     13659176.74
      2000385.16     13659909.41
#Sta/Elev= 30
  4200.8  840.39  4230.6  839.88  4236.6  840.70  4245.4  840.02  4251.5  840.29
  4266.4  839.49  4389.5  836.70  4460.4  833.96  4610.9  832.12  4776.0  828.14
  4866.6  828.49  4872.4  827.97  4894.0  828.63  4909.8  827.79  4947.2  828.19
  4968.8  827.61  4979.9  826.63  4980.4  825.83  4985.7  825.83  4986.2  826.63
  5027.7  826.80  5033.5  827.55  5040.7  829.80  5049.3  830.32  5070.9  829.63
  5151.5  831.79  5259.7  839.39  5350.0  843.21  5457.8  845.91  5564.5  847.41
#Mann=4,-1,0
  4200.8    0.05       0  4389.5     0.1       0  4979.9    0.07       0
  4986.2     0.1       0
Bank Sta=4979.9,4986.2
Exp/Cntr=0.3,0.1

Type RM Length L Ch R = 1,4982,356,356,356
BEGIN DESCRIPTION:
UNT 085 in HW 9.0
END DESCRIPTION:
XS GIS Cut Line= 3
      2001224.97     13658775.01      2000525.00     13659175.00
      2000122.50     13659370.59
#Sta/Elev= 30
  4212.0  843.04  4225.5  842.74  4381.1  838.25  4413.7  836.35  4430.8  835.68
  4483.4  835.30  4511.4  834.03  4548.1  833.26  4685.2  831.25  4762.7  828.33
  4960.6  826.23  4979.8  825.10  4980.3  824.30  4985.6  824.30  4986.1  825.10
  5021.0  825.63  5026.7  826.61  5071.8  830.36  5116.9  833.02  5145.0  833.96
  5184.6  834.54  5196.1  835.30  5273.9  835.87  5280.4  836.52  5286.0  836.15
  5331.1  837.13  5385.1  837.26  5421.3  838.13  5429.6  837.63  5465.7  837.99
#Mann=6,-1,0
  4212.0    0.05       0  4225.5     0.1       0  4413.7    0.05       0
  4685.2     0.1       0  4979.8    0.07       0  4986.1     0.1       0
Bank Sta=4979.8,4986.1
Exp/Cntr=0.3,0.1

Type RM Length L Ch R = 1,4626,355,355,355
BEGIN DESCRIPTION:
Mapping XS e683a6d5
END DESCRIPTION:
XS GIS Cut Line= 3
      2000840.03     13658503.14      2000326.15     13658985.77
      2000065.72     13659339.94
#Sta/Elev= 30
  4520.9  838.17  4603.6  836.47  4758.9  834.26  4815.9  833.21  4898.1  829.52
  4907.9  829.20  4928.9  827.35  4957.2  825.99  4978.7  824.38  4999.0  823.83
  5003.9  823.46  5004.4  822.66  5009.7  822.66  5010.2  823.46  5113.0  825.88
  5155.5  826.02  5198.0  826.91  5212.2  826.43  5269.2  826.91  5340.2  829.62
  5369.5  831.37  5390.3  831.74  5405.0  832.75  5461.3  834.11  5511.5  835.92
  5519.9  835.71  5584.7  836.77  5597.3  836.42  5611.8  837.06  5665.5  837.59
#Mann=6,-1,0
  4520.9    0.05       0  4758.9     0.1       0  4898.1    0.05       0
  4999.0     0.1       0  5003.9    0.07       0  5010.2     0.1       0
Bank Sta=5003.9,5010.2
Exp/Cntr=0.3,0.1

Type RM Length L Ch R = 1,4271,213,213,213
BEGIN DESCRIPTION:
UNT 085 in HW 8.0
END DESCRIPTION:
XS GIS Cut Line= 3
      2000725.03     13658274.98      2000225.00     13658625.00
      1999996.29     13659194.09
#Sta/Elev= 30
  4357.8  837.61  4487.3  834.58  4596.7  832.77  4716.6  831.49  4782.0  828.49
  4817.8  827.26  4843.3  826.89  4868.3  825.93  4910.2  825.35  4925.0  824.39
  4960.8  823.07  4965.1  822.44  4970.9  822.44  4986.6  821.05  4987.1  820.25
  4992.4  820.25  4992.9  821.05  5000.5  821.72  5007.1  822.89  5018.6  822.74
  5075.9  823.23  5114.7  824.18  5251.8  825.35  5329.7  827.90  5353.9  828.27
  5466.8  832.58  5496.4  833.01  5515.2  833.98  5544.7  834.08  5581.5  835.05
#Mann=6,-1,0
  4357.8    0.05       0  4596.7     0.1       0  4843.3    0.05       0
  4986.6    0.04       0  4992.9    0.05       0  5018.6     0.1       0
Bank Sta=4986.6,4992.9
Exp/Cntr=0.3,0.1

Type RM Length L Ch R = 1,4058,462,462,462
BEGIN DESCRIPTION:
Mapping XS 1a730097
END DESCRIPTION:
XS GIS Cut Line= 3
      2000423.37     13658114.23      1999895.59     13658721.88
      1999847.02     13659110.40
#Sta/Elev= 30
  4416.7  830.22  4465.8  829.46  4501.0  827.60  4508.6  827.71  4515.2  826.98
  4543.7  826.75  4664.3  822.80  4727.9  821.97  4812.6  822.34  4869.4  822.30
  4877.0  822.82  4919.8  822.91  4952.0  822.17  4983.4  821.31  4990.0  820.56
  4994.5  819.24  4995.0  818.44  5000.3  818.44  5000.8  819.24  5018.5  822.05
  5047.0  822.73  5096.3  822.91  5104.0  823.52  5167.6  825.19  5181.8  826.06
  5188.4  825.86  5220.3  826.90  5263.3  827.09  5547.2  833.01  5613.1  833.86
#Mann=5,-1,0
  4416.7     0.1       0  4812.6    0.05       0  4952.0     0.1       0
  4994.5    0.07       0  5000.8     0.1       0
Bank Sta=4994.5,5000.8
Exp/Cntr=0.3,0.1

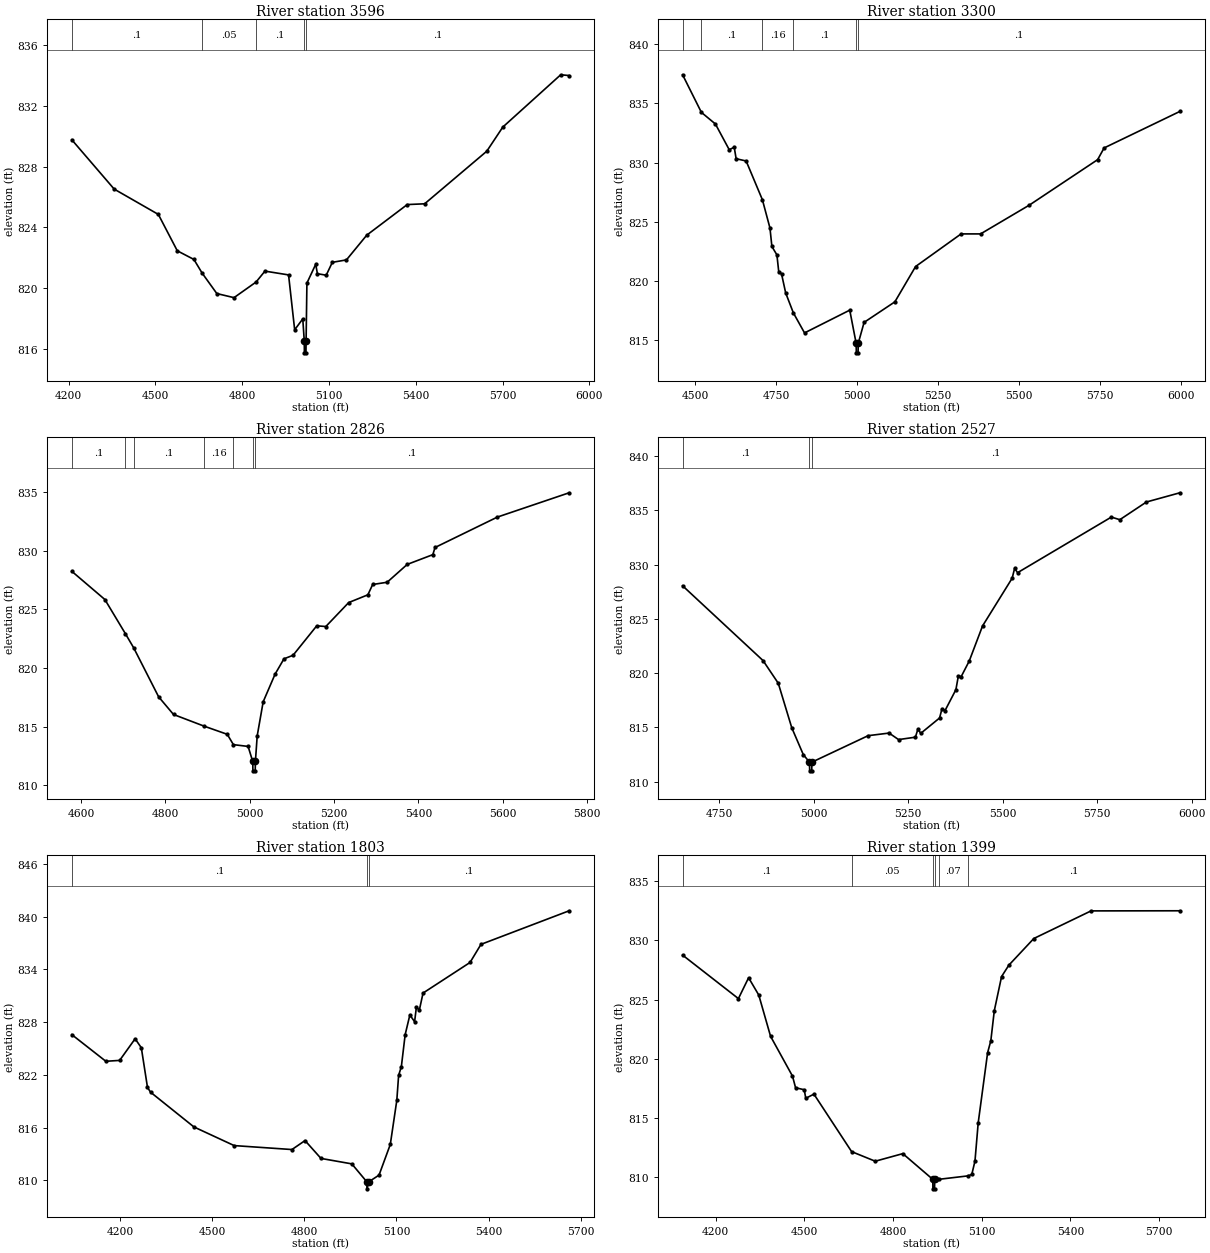
Type RM Length L Ch R = 1,3596,296,296,296
BEGIN DESCRIPTION:
Mapping XS f740e14f
END DESCRIPTION:
XS GIS Cut Line= 3
      2000286.85     13657543.43      1999784.48     13658326.05
      1999808.78     13659114.19
#Sta/Elev= 30
  4211.3  829.77  4357.6  826.52  4510.2  824.85  4575.7  822.45  4633.1  821.88
  4661.5  820.98  4712.3  819.63  4771.7  819.36  4847.9  820.39  4878.6  821.11
  4960.2  820.86  4981.3  817.24  5009.3  817.96  5014.4  816.52  5014.9  815.72
  5020.3  815.72  5020.8  816.52  5023.6  820.32  5054.0  821.56  5059.9  820.94
  5090.3  820.84  5111.4  821.69  5160.2  821.85  5230.3  823.48  5370.3  825.50
  5430.4  825.55  5645.2  829.02  5700.5  830.61  5900.6  834.06  5929.8  834.01
#Mann=5,-1,0
  4211.3     0.1       0  4661.5    0.05       0  4847.9     0.1       0
  5014.4    0.07       0  5020.8     0.1       0
Bank Sta=5014.4,5020.8
Exp/Cntr=0.3,0.1

Type RM Length L Ch R = 1,3300,474,474,474
BEGIN DESCRIPTION:
UNT 085 in HW 7.0
END DESCRIPTION:
XS GIS Cut Line= 3
      1999346.96     13657694.07      1999697.67     13658270.49
      1999770.59     13659128.17
#Sta/Elev= 30
  4461.0  837.40  4519.0  834.23  4562.3  833.25  4605.0  831.08  4620.4  831.29
  4626.3  830.32  4657.2  830.13  4707.4  826.86  4730.8  824.47  4736.7  822.92
  4752.2  822.21  4758.0  820.75  4766.4  820.62  4779.3  819.00  4803.0  817.32
  4837.5  815.63  4977.1  817.55  4996.9  814.75  4997.4  813.95  5002.8  813.95
  5003.3  814.75  5021.4  816.52  5116.4  818.25  5180.4  821.23  5320.9  823.98
  5381.1  823.98  5531.7  826.41  5742.4  830.24  5762.5  831.23  5996.5  834.31
#Mann=6,-1,0
  4461.0    0.05       0  4519.0     0.1       0  4707.4    0.16       0
  4803.0     0.1       0  4996.9    0.07       0  5003.3     0.1       0
Bank Sta=4996.9,5003.3
Exp/Cntr=0.3,0.1

Type RM Length L Ch R = 1,2826,299,299,299
BEGIN DESCRIPTION:
UNT 085 in HW 6.0
END DESCRIPTION:
XS GIS Cut Line= 3
      1999138.63     13658190.61      1999586.56     13658673.27
      1999725.01     13659175.03
#Sta/Elev= 30
  4578.2  828.23  4656.5  825.83  4705.0  822.93  4724.9  821.71  4784.0  817.54
  4819.2  816.04  4892.2  815.04  4946.7  814.35  4961.2  813.47  4996.1  813.32
  5007.0  812.04  5007.5  811.24  5012.9  811.24  5013.4  812.04  5017.6  814.21
  5031.8  817.12  5060.1  819.48  5081.1  820.78  5102.6  821.08  5158.8  823.59
  5180.3  823.53  5234.5  825.57  5280.0  826.23  5291.4  827.11  5325.7  827.30
  5373.3  828.82  5434.0  829.65  5439.2  830.26  5587.0  832.85  5757.2  834.92
#Mann=7,-1,0
  4578.2     0.1       0  4705.0    0.16       0  4724.9     0.1       0
  4892.2    0.16       0  4961.2     0.1       0  5007.0    0.07       0
  5013.4     0.1       0
Bank Sta=5007,5013.4
Exp/Cntr=0.3,0.1

Type RM Length L Ch R = 1,2527,724,724,724
BEGIN DESCRIPTION:
UNT 085 in HW 5.0
END DESCRIPTION:
XS GIS Cut Line= 3
      1999031.02     13658225.38      1999239.34     13658787.85
      1999687.23     13659346.84
#Sta/Elev= 30
  4652.9  828.05  4865.8  821.16  4906.1  819.07  4941.8  814.97  4972.4  812.49
  4988.7  811.80  4989.2  811.00  4994.6  811.00  4995.1  811.80  5143.9  814.24
  5199.4  814.48  5224.4  813.88  5269.0  814.10  5275.4  814.82  5283.4  814.46
  5333.0  815.87  5339.4  816.73  5347.4  816.55  5376.2  818.48  5382.7  819.75
  5390.0  819.67  5411.5  821.12  5446.7  824.35  5525.1  828.75  5531.5  829.65
  5539.5  829.26  5787.6  834.38  5810.0  834.14  5880.4  835.77  5969.0  836.62
#Mann=3,-1,0
  4652.9     0.1       0  4988.7    0.07       0  4995.1     0.1       0
Bank Sta=4988.7,4995.1
Exp/Cntr=0.3,0.1

Type RM Length L Ch R = 1,1803,404,404,404
BEGIN DESCRIPTION:
UNT 085 in HW 4.0
END DESCRIPTION:
XS GIS Cut Line= 3
      1999013.64     13658270.53      1998933.78     13658916.32
      1999444.22     13659739.27
#Sta/Elev= 30
  4043.2  826.58  4153.9  823.55  4198.8  823.65  4249.2  826.11  4269.4  825.09
  4289.5  820.57  4299.6  820.03  4440.7  816.08  4571.7  813.96  4759.8  813.51
  4802.4  814.53  4854.3  812.50  4954.7  811.88  5003.5  809.84  5004.0  809.04
  5010.0  809.84  5043.3  810.60  5080.0  814.09  5101.2  819.11  5107.1  821.95
  5116.0  822.94  5128.4  826.58  5143.7  828.82  5159.1  828.05  5165.0  829.72
  5174.5  829.36  5186.6  831.31  5339.6  834.79  5375.2  836.85  5662.3  840.67
#Mann=3,-1,0
  4043.2     0.1       0  5003.5    0.07       0  5010.0     0.1       0
Bank Sta=5003.5,5010
Exp/Cntr=0.3,0.1

Type RM Length L Ch R = 1,1399,364,364,364
BEGIN DESCRIPTION:
UNT 085 in HW 3.0
END DESCRIPTION:
XS GIS Cut Line= 3
      1998989.33     13658166.37      1998774.06     13658954.52
      1998462.25     13659761.77
#Sta/Elev= 30
  4088.3  828.76  4277.1  825.09  4311.6  826.85  4346.0  825.39  4385.9  821.91
  4460.1  818.55  4470.5  817.57  4499.8  817.40  4505.0  816.68  4532.6  817.03
  4660.1  812.18  4740.0  811.37  4833.3  812.01  4934.7  809.84  4935.2  809.04
  4940.7  809.04  4941.2  809.84  4954.1  809.84  5052.6  810.13  5066.6  810.25
  5077.4  811.38  5088.3  814.60  5120.2  820.53  5131.0  821.53  5142.8  824.07
  5167.4  826.95  5192.0  827.91  5276.5  830.16  5470.1  832.49  5770.7  832.50
#Mann=6,-1,0
  4088.3     0.1       0  4660.1    0.05       0  4934.7    0.07       0
  4941.2    0.05       0  4954.1    0.07       0  5052.6     0.1       0
Bank Sta=4934.7,4941.2
Exp/Cntr=0.3,0.1