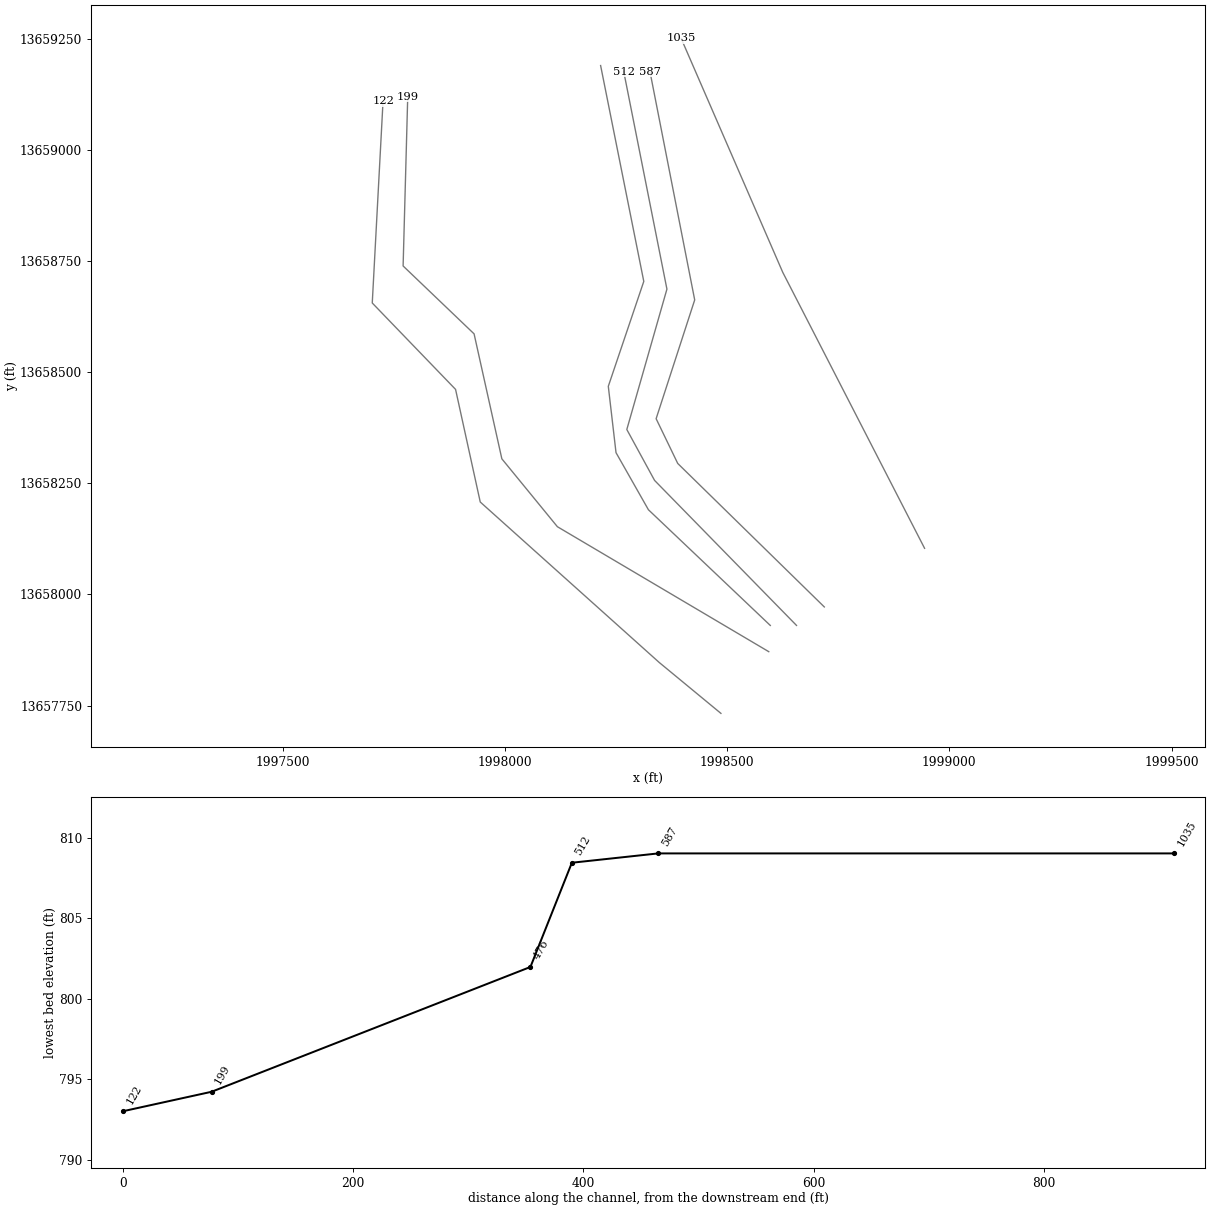
HEC-RAS study UNT 085 in HW.prj: UNT 085 in HW Base Level Engineering

--- UNT 085 in HW.g01 (geometry) --- (continued)

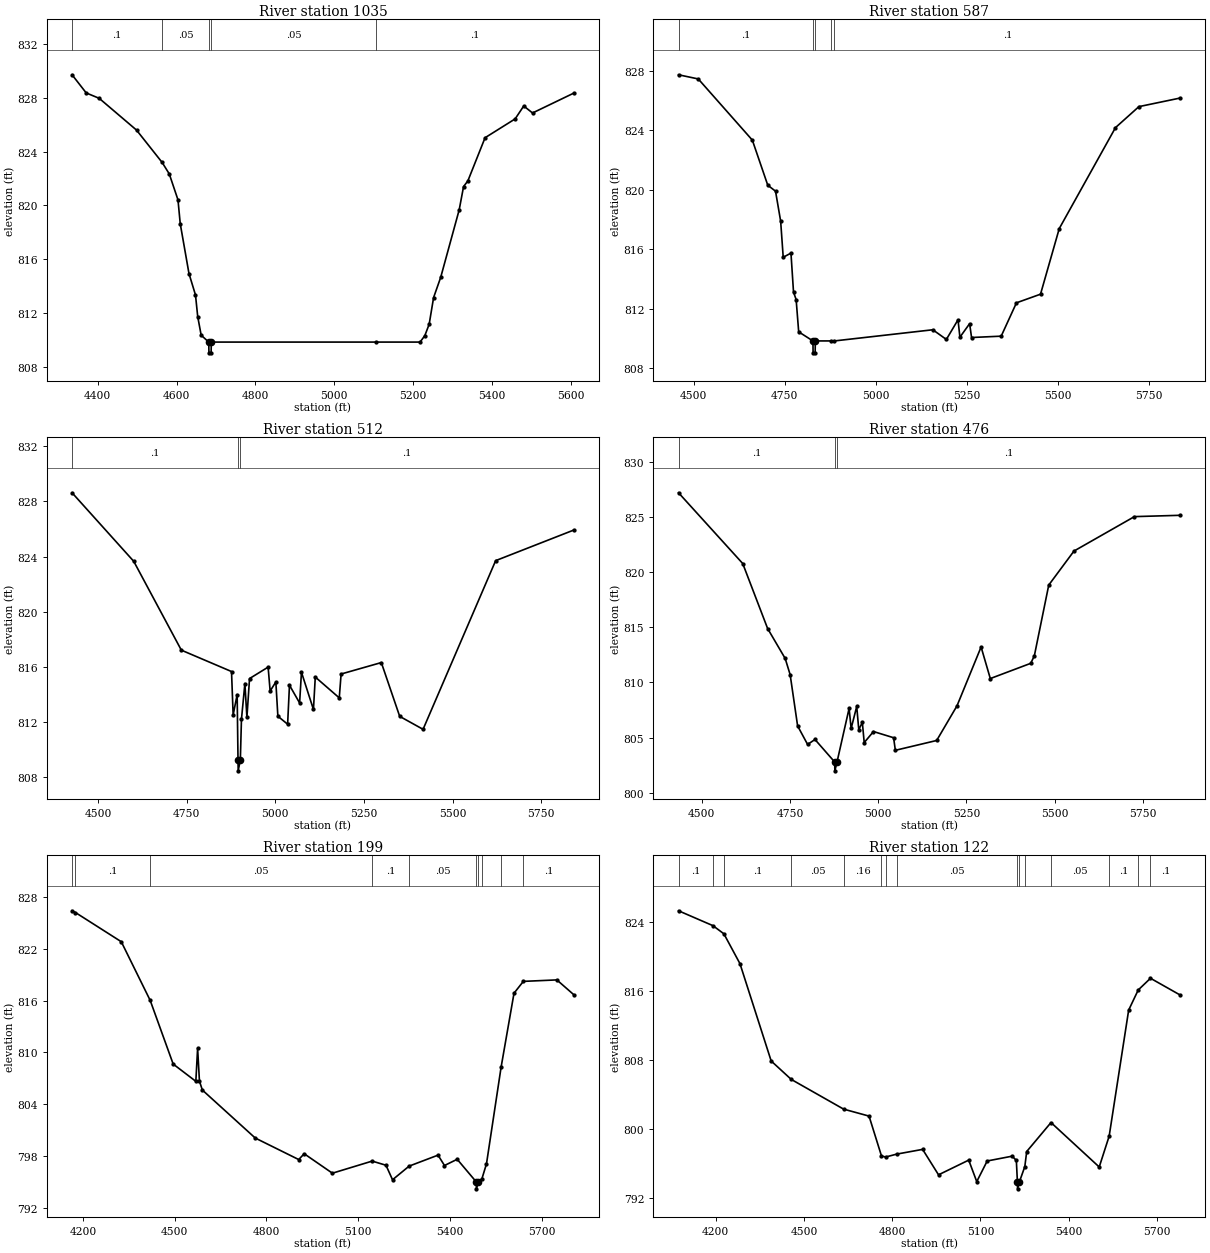
Type RM Length L Ch R = 1,1035,448,448,448
BEGIN DESCRIPTION:
UNT 085 in HW 2.0
END DESCRIPTION:
XS GIS Cut Line= 3
      1998944.21     13658103.82      1998625.00     13658725.00
      1998396.27     13659251.57
#Sta/Elev= 30
  4335.0  829.71  4370.9  828.36  4403.8  827.96  4498.4  825.60  4563.5  823.19
  4581.5  822.34  4603.6  820.41  4609.3  818.64  4631.5  814.93  4648.0  813.34
  4653.6  811.74  4662.4  810.35  4681.6  809.84  4682.1  809.04  4687.6  809.04
  4688.1  809.84  5106.0  809.84  5217.5  809.84  5229.6  810.32  5240.6  811.17
  5251.8  813.15  5269.8  814.65  5316.7  819.67  5327.8  821.40  5338.7  821.82
  5382.3  825.03  5458.6  826.43  5480.4  827.39  5502.7  826.87  5607.5  828.35
#Mann=5,-1,0
  4335.0     0.1       0  4563.5    0.05       0  4681.6   0.033       0
  4688.1    0.05       0  5106.0     0.1       0
Bank Sta=4681.6,4688.1
Exp/Cntr=0.3,0.1

Type RM Length L Ch R = 1,587,75,75,75
BEGIN DESCRIPTION:
Mapping XS 98ac7e3e
END DESCRIPTION:
XS GIS Cut Line= 5
      1998718.54     13657971.85      1998388.65     13658294.80
      1998340.03     13658395.49      1998426.84     13658662.85
      1998326.15     13659176.71
#Sta/Elev= 30
  4458.0  827.72  4512.2  827.44  4660.7  823.33  4703.1  820.30  4724.4  819.90
  4738.5  817.88  4745.5  815.46  4766.8  815.74  4773.8  813.12  4781.0  812.62
  4788.0  810.45  4827.1  809.84  4827.6  809.04  4833.2  809.04  4833.7  809.84
  4875.9  809.84  4886.1  809.84  5156.4  810.59  5193.6  809.94  5225.6  811.26
  5230.8  810.09  5257.5  811.00  5262.8  810.07  5344.2  810.16  5386.1  812.40
  5452.2  812.98  5503.7  817.39  5658.1  824.17  5722.4  825.58  5836.2  826.16
#Mann=5,-1,0
  4458.0     0.1       0  4827.1    0.07       0  4833.7     0.1       0
  4875.9    0.05       0  4886.1     0.1       0
Bank Sta=4827.1,4833.7
Exp/Cntr=0.3,0.1

Type RM Length L Ch R = 1,512,36,36,36
BEGIN DESCRIPTION:
Mapping XS 11efdd0c
END DESCRIPTION:
XS GIS Cut Line= 5
      1998655.99     13657930.23      1998336.56     13658256.60
      1998274.06     13658371.18      1998364.34     13658687.16
      1998267.13     13659176.69
#Sta/Elev= 30
  4427.0  828.62  4600.9  823.65  4735.1  817.21  4876.6  815.66  4881.2  812.51
  4892.5  813.99  4894.9  809.26  4895.4  808.46  4901.5  809.26  4904.6  812.19
  4914.3  814.79  4920.0  812.33  4927.4  815.15  4979.8  815.98  4985.5  814.25
  5001.6  814.90  5007.3  812.42  5034.8  811.84  5040.0  814.67  5068.6  813.38
  5073.8  815.61  5107.6  812.91  5112.8  815.26  5180.4  813.75  5185.6  815.48
  5299.0  816.31  5350.8  812.41  5416.7  811.47  5621.4  823.70  5841.9  825.92
#Mann=3,-1,0
  4427.0     0.1       0  4894.9    0.07       0  4901.5     0.1       0
Bank Sta=4894.9,4901.5
Exp/Cntr=0.3,0.1

Type RM Length L Ch R = 1,476,277,277,277
BEGIN DESCRIPTION:
Mapping XS 1d9701c4
END DESCRIPTION:
XS GIS Cut Line= 6
      1998597.01     13657930.18      1998322.67     13658190.63
      1998249.76     13658319.10      1998232.40     13658468.41
      1998312.26     13658704.52      1998215.09     13659190.33
#Sta/Elev= 30
  4434.7  827.17  4616.5  820.76  4687.0  814.87  4736.7  812.16  4750.8  810.69
  4771.9  806.05  4800.2  804.37  4821.1  804.82  4876.9  802.78  4877.4  801.98
  4883.5  802.78  4917.7  807.63  4923.5  805.82  4939.3  807.81  4945.1  805.71
  4955.2  806.37  4960.5  804.54  4986.8  805.54  5043.7  804.98  5048.7  803.84
  5165.7  804.73  5223.3  807.87  5291.5  813.20  5317.6  810.34  5432.1  811.72
  5442.3  812.40  5483.1  818.81  5554.5  821.89  5725.7  825.01  5855.7  825.13
#Mann=3,-1,0
  4434.7     0.1       0  4876.9    0.07       0  4883.5     0.1       0
Bank Sta=4876.9,4883.5
Exp/Cntr=0.3,0.1

Type RM Length L Ch R = 1,199,77,77,77
BEGIN DESCRIPTION:
Mapping XS 92a93c41
END DESCRIPTION:
XS GIS Cut Line= 6
      1998593.53     13657871.17      1998117.81     13658152.43
      1997992.81     13658305.21      1997930.31     13658586.46
      1997770.59     13658739.24      1997780.99     13659120.62
#Sta/Elev= 30
  4164.3  826.40  4175.2  826.20  4325.2  822.82  4419.7  816.03  4494.9  808.66
  4569.0  806.66  4574.8  810.48  4580.8  806.68  4590.4  805.65  4763.2  800.10
  4905.3  797.61  4923.3  798.28  5015.5  796.03  5145.5  797.43  5190.7  796.95
  5212.1  795.27  5266.4  796.85  5360.9  798.12  5382.0  796.92  5423.5  797.64
  5486.0  795.02  5486.5  794.22  5492.6  795.02  5504.6  795.41  5519.3  797.11
  5567.2  808.32  5609.3  816.86  5639.8  818.23  5749.4  818.40  5805.0  816.68
#Mann=10,-1,0
  4164.3    0.05       0  4175.2     0.1       0  4419.7    0.05       0
  5145.5     0.1       0  5266.4    0.05       0  5486.0    0.04       0
  5492.6    0.05       0  5504.6     0.1       0  5567.2    0.16       0
  5639.8     0.1       0
Bank Sta=5486,5492.6
Exp/Cntr=0.3,0.1

Type RM Length L Ch R = 1,122,0,0,0
BEGIN DESCRIPTION:
UNT 085 in HW 1.0
END DESCRIPTION:
XS GIS Cut Line= 6
      1998485.86     13657732.30      1998346.98     13657846.88
      1997944.20     13658207.99      1997888.65     13658461.46
      1997701.15     13658655.91      1997725.43     13659110.35
#Sta/Elev= 30
  4073.9  825.35  4190.8  823.62  4228.1  822.67  4282.7  819.20  4388.8  807.88
  4456.9  805.74  4635.1  802.28  4721.5  801.47  4763.8  796.83  4777.9  796.71
  4815.7  797.05  4903.6  797.60  4957.7  794.64  5060.3  796.35  5087.6  793.85
  5123.1  796.25  5208.0  796.81  5222.2  796.31  5225.8  793.81  5226.3  793.01
  5232.5  793.81  5251.0  795.60  5257.4  797.35  5340.0  800.72  5503.9  795.55
  5537.7  799.14  5604.0  813.80  5636.5  816.14  5678.2  817.50  5779.6  815.54
#Mann=15,-1,0
  4073.9     0.1       0  4190.8    0.08       0  4228.1     0.1       0
  4456.9    0.05       0  4635.1    0.16       0  4763.8    0.05       0
  4777.9    0.16       0  4815.7    0.05       0  5225.8    0.04       0
  5232.5    0.05       0  5251.0     0.1       0  5340.0    0.05       0
  5537.7     0.1       0  5636.5    0.16       0  5678.2     0.1       0
Bank Sta=5225.8,5232.5
Exp/Cntr=0.3,0.1

Chan Stop Cuts=-1