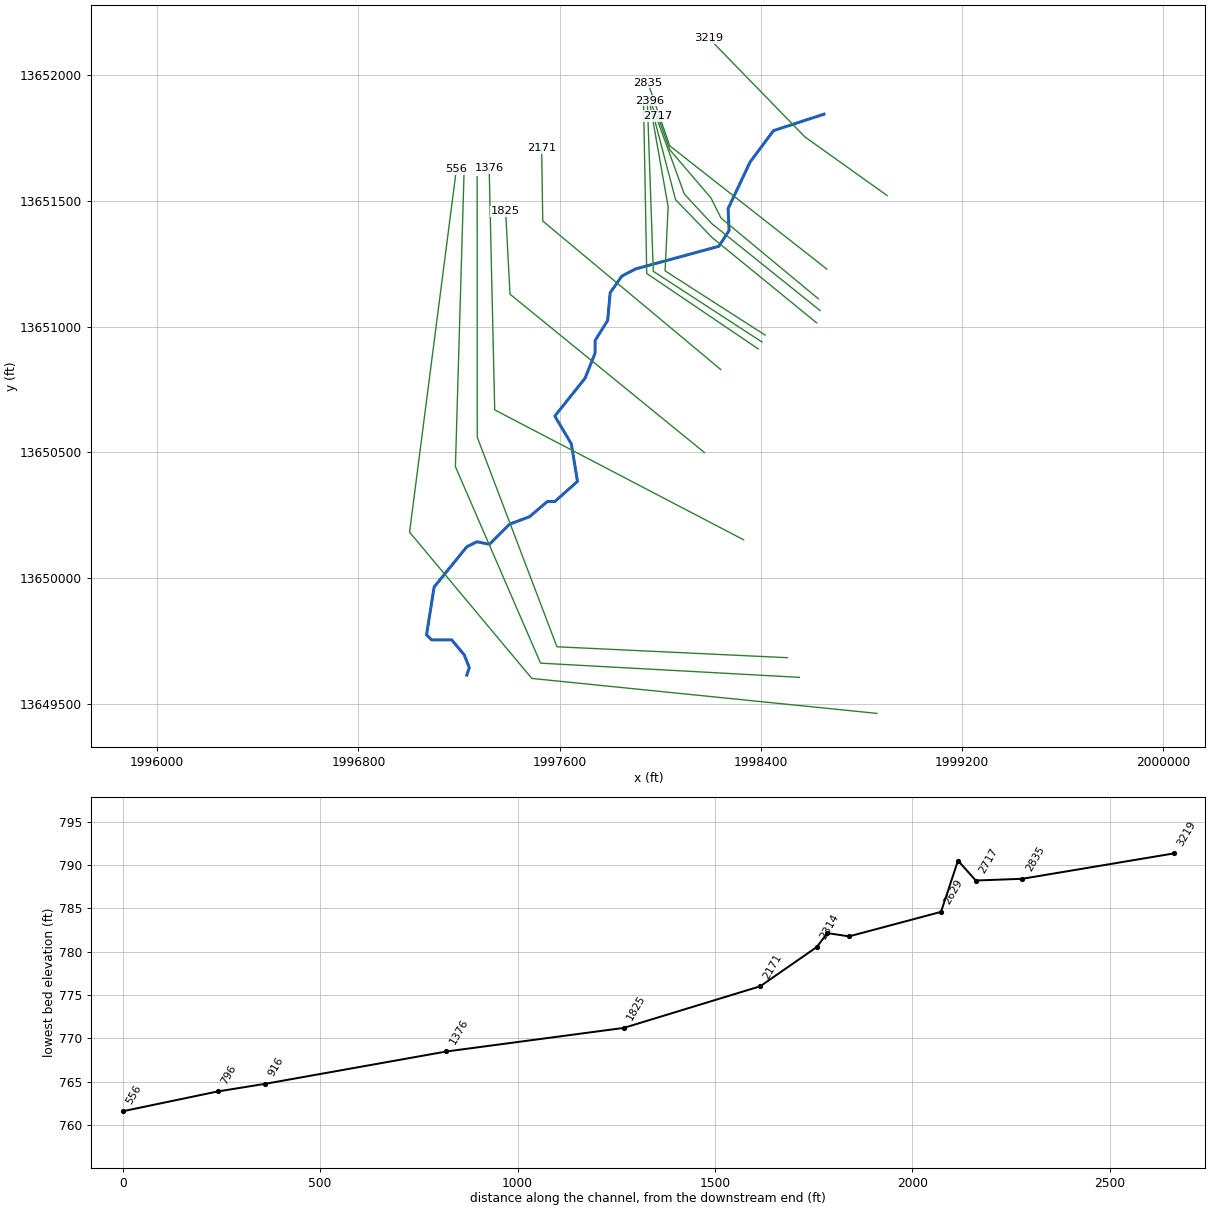
--- UNT 086 in HW.prj (project) ---

Proj Title=UNT 086 in HW Base Level Engineering
Current Plan=p01
Default Exp/Contr=0.3,0.1
English Units
Geom File=g01
Flow File=f01
Plan File=p01
Y Axis Title=Elevation
X Axis Title(PF)=Main Channel Distance
X Axis Title(XS)=Station
BEGIN DESCRIPTION:
UNT 086 in HW
END DESCRIPTION:
DSS Export Rating Curves= 0
DSS Export Rating Curve Sorted= 0
DSS Export Volume Flow Curves= 0
DXF OffsetX= 0
DXF OffsetY= 0
DXF ScaleX= 1
DXF ScaleY= 10

--- UNT 086 in HW.p01 (plan) ---

Plan Title=Multiple Run
Short Identifier=Multiple
Geom File=g01
Flow File=f01
Subcritical Flow
K Sum by GR= 0
Std Step Tol= 0.01
Critical Tol= 0.01
Num of Std Step Trials= 20
Max Error Tol= 0.3
Flow Tol Ratio= 0.001
Split Flow NTrial= 30
Split Flow Tol= 0.02
Split Flow Ratio= 0.02
Log Output Level= 0
Friction Slope Method= 1
Unsteady Friction Slope Method= 2
Unsteady Bridges Friction Slope Method= 1
Parabolic Critical Depth
Global Vel Dist=  1 , 1 , 1
Global Log Level= 0
CheckData=True
Encroach Param= -1, 0, 0, 0
BEGIN DESCRIPTION:
Multiple Run
END DESCRIPTION:

--- UNT 086 in HW.f01 (steady flow) ---

Flow Title=Multiple
Number of Profiles=7
Profile Names=10-year,25-year,50-year,1pct_min,100-year,1pct_plu,500-year
River Rch & RM= UNT 086 in HW,Reach-1,3219
     359     487     591     355     709    1415    1024
Boundary for River Rch & Prof#=UNT 086 in HW,Reach-1,1
Up Type=0
Dn Type=3
Dn Slope=0.005
Boundary for River Rch & Prof#=UNT 086 in HW,Reach-1,2
Up Type=0
Dn Type=3
Dn Slope=0.005
Boundary for River Rch & Prof#=UNT 086 in HW,Reach-1,3
Up Type=0
Dn Type=3
Dn Slope=0.005
Boundary for River Rch & Prof#=UNT 086 in HW,Reach-1,4
Up Type=0
Dn Type=3
Dn Slope=0.005
Boundary for River Rch & Prof#=UNT 086 in HW,Reach-1,5
Up Type=0
Dn Type=3
Dn Slope=0.005
Boundary for River Rch & Prof#=UNT 086 in HW,Reach-1,6
Up Type=0
Dn Type=3
Dn Slope=0.005
Boundary for River Rch & Prof#=UNT 086 in HW,Reach-1,7
Up Type=0
Dn Type=3
Dn Slope=0.005

--- UNT 086 in HW.g01 (geometry) ---

Geom Title=Existing Conditions
Program Version=5.05

River Reach=UNT 086 in HW   ,Reach-1
Reach XY= 30
       1998650.8     13651844.54      1998450.12     13651779.12
      1998357.23     13651654.55      1998269.56     13651468.79
      1998273.64     13651382.16      1998233.02     13651319.31
      1997902.11     13651229.38      1997847.21     13651200.95
       1997800.8     13651134.54       1997790.8     13651024.54
       1997740.8     13650944.54       1997740.8     13650894.54
       1997700.8     13650794.54       1997580.8     13650644.54
      1997646.33     13650533.81       1997670.8     13650384.54
       1997580.8     13650304.54       1997550.8     13650304.54
       1997480.8     13650244.54       1997400.8     13650214.54
       1997320.8     13650134.54       1997270.8     13650144.54
       1997230.8     13650124.54       1997100.8     13649964.54
       1997070.8     13649774.54       1997090.8     13649754.54
       1997170.8     13649754.54       1997220.8     13649694.54
       1997240.8     13649644.54       1997230.8     13649614.54

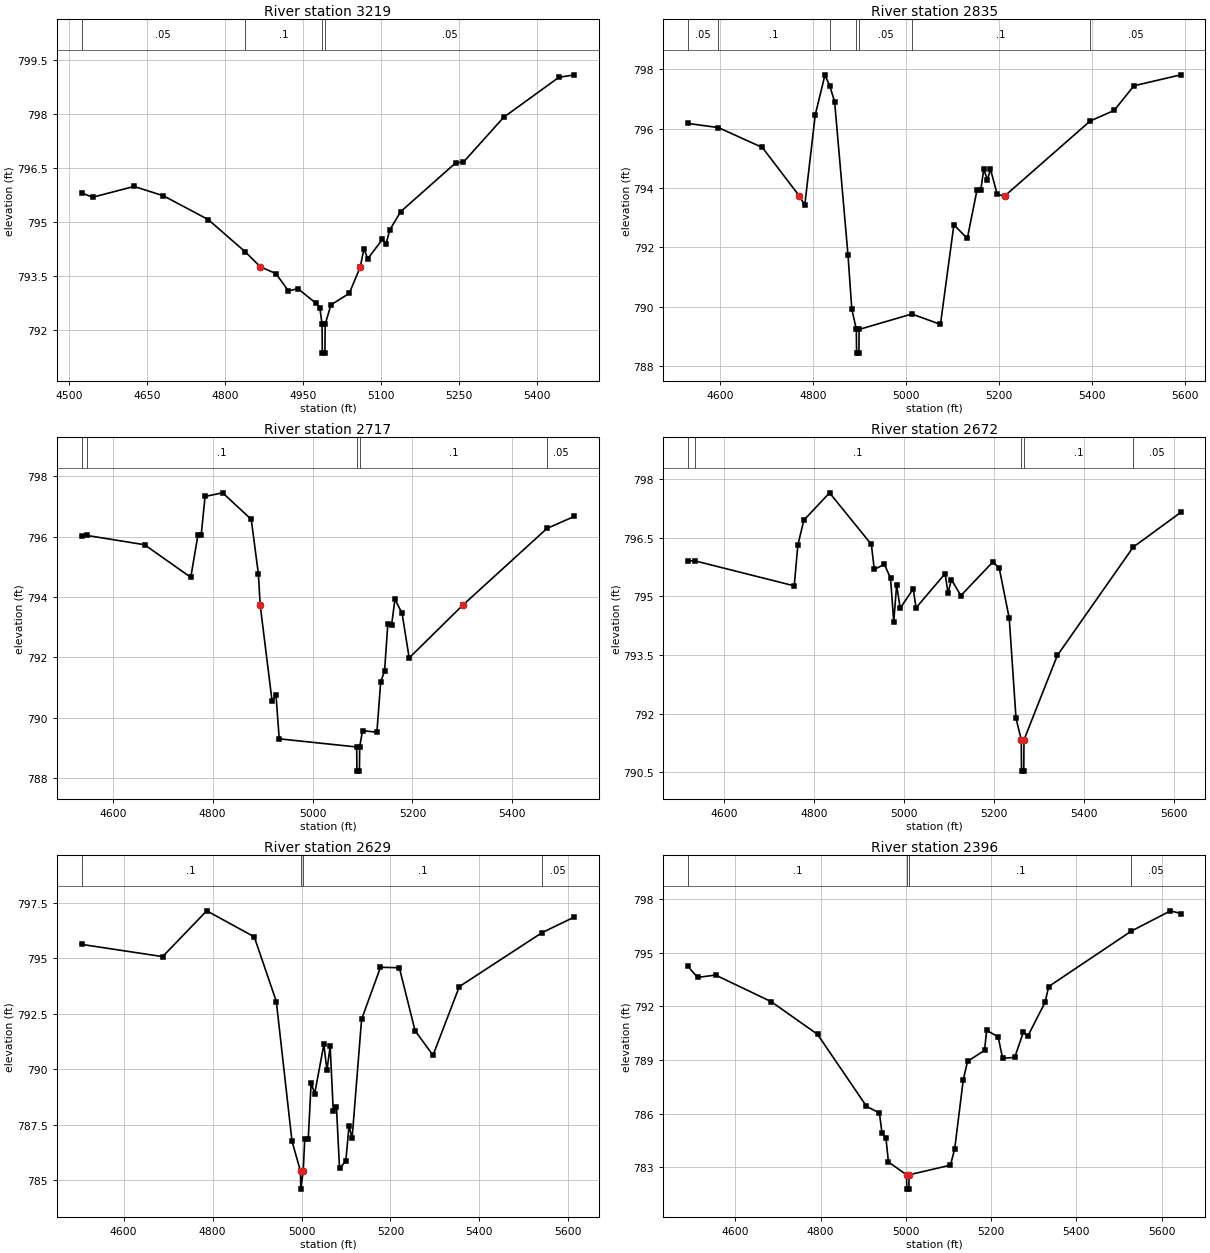
Type RM Length L Ch R = 1 ,3219    ,384,384,384
BEGIN DESCRIPTION:
UNT 086 in HW 2.0
END DESCRIPTION:
XS GIS Cut Line= 3
      1998901.96     13651521.07      1998575.57     13651753.71
      1998193.61     13652146.08
#Sta/Elev= 30
  4523.5  795.81  4544.7  795.69  4624.6  795.99  4681.1  795.73  4767.2  795.07
    4838  794.18 4867.83793.7545  4897.5  793.57  4921.6  793.09  4939.9  793.15
  4975.1  792.74  4982.1  792.62  4986.3  792.16  4986.8  791.36  4991.8  791.36
  4992.3  792.16  5003.4   792.7  5038.7  793.02 5059.83793.7546    5067  794.26
  5074.2  793.98  5102.5  794.52  5109.4  794.39  5116.6  794.78  5137.7  795.29
  5243.9  796.65  5258.1  796.66  5335.8  797.91    5442  799.02  5471.9  799.09
#Mann= 4 ,-1 , 0
  4523.5     .05       0    4838      .1       0  4986.3     .04       0
  4992.3     .05       0
Bank Sta=4867.83,5059.83
XS Rating Curve= 0 ,0
Exp/Cntr=0.3,0.1

Type RM Length L Ch R = 1 ,2835    ,118,118,118
BEGIN DESCRIPTION:
Mapping XS e863c9a1
END DESCRIPTION:
XS GIS Cut Line= 3
      1998662.41      13651228.5      1998037.37     13651718.99
       1997950.7     13651970.35
#Sta/Elev= 30
  4530.4  796.18  4595.8  796.04  4690.4  795.37 4770.23793.7277  4781.7  793.42
  4804.3  796.47  4825.1  797.81  4835.5  797.45  4845.9  796.92  4874.8  791.73
  4882.9  789.92  4892.7  789.23  4893.2  788.43  4898.2  788.43  4898.7  789.23
  5012.1  789.75  5073.7   789.4  5102.6  792.76  5131.5   792.3  5152.3  793.93
  5160.4  793.93  5166.8  794.63  5174.9  794.28  5181.3  794.64  5195.7  793.79
 5211.63793.7277  5395.7  796.26  5447.6  796.62  5489.9  797.45  5590.8  797.82
#Mann= 7 ,-1 , 0
  4530.4     .05       0  4595.8      .1       0  4835.5     .05       0
  4892.7    .033       0  4898.7     .05       0  5012.1      .1       0
  5395.7     .05       0
Bank Sta=4770.23,5211.63
XS Rating Curve= 0 ,0
Exp/Cntr=0.3,0.1

Type RM Length L Ch R = 1 ,2717    ,45,45,45
BEGIN DESCRIPTION:
Mapping XS 01c3da69
END DESCRIPTION:
XS GIS Cut Line= 5
      1998628.48     13651110.51      1998241.37     13651431.66
      1998201.44     13651511.52      1998038.24     13651702.49
      1997989.82     13651837.39
#Sta/Elev= 30
  4537.5  796.03  4547.6  796.04  4663.7  795.73  4756.2  794.65  4770.5  796.05
    4777  796.04  4784.8  797.33    4820  797.45  4877.3  796.57  4891.6  794.76
 4895.23793.7213    4919  790.55  4926.8  790.76  4933.3   789.3  5088.4  789.03
  5088.9  788.23  5093.9  788.23  5094.4  789.03  5100.1  789.57  5128.9  789.52
  5136.5  791.19  5144.2  791.54  5150.7  793.09  5158.4  793.08    5165  793.92
  5179.3  793.46  5193.5  791.98 5300.44793.7213  5469.4  796.27  5524.3  796.67
#Mann= 5 ,-1 , 0
  4537.5     .05       0  4547.6      .1       0  5088.4     .07       0
  5094.4      .1       0  5469.4     .05       0
Bank Sta=4895.23,5300.44
XS Rating Curve= 0 ,0
Exp/Cntr=0.3,0.1

Type RM Length L Ch R = 1 ,2672    ,43,43,43
BEGIN DESCRIPTION:
Mapping XS 3f59c736
END DESCRIPTION:
XS GIS Cut Line= 4
      1998635.44     13651063.62      1998203.17     13651410.83
      1998095.53     13651527.15      1997965.33     13651884.76
#Sta/Elev= 30
  4520.7  795.91  4535.9  795.91  4756.5  795.27  4764.5  796.31  4777.8  796.95
  4834.9  797.65  4927.7  796.33  4934.1  795.69  4956.5  795.82  4970.2  795.47
  4977.3  794.35  4983.7  795.29  4991.7   794.7  5020.5  795.19  5026.9  794.71
  5091.1  795.58  5097.9  795.09  5105.3  795.43  5126.2  795.02  5197.1  795.88
  5211.3  795.73  5233.6  794.44  5248.6  791.88  5260.3  791.33  5260.8  790.53
  5265.8  790.53  5266.3  791.33  5340.3  793.49  5508.6  796.26  5614.2  797.15
#Mann= 5 ,-1 , 0
  4520.7     .05       0  4535.9      .1       0  5260.3     .07       0
  5266.3      .1       0  5508.6     .05       0
Bank Sta=5260.3,5266.3
XS Rating Curve= 0 ,0
Exp/Cntr=0.3,0.1

Type RM Length L Ch R = 1 ,2629    ,233,233,233
BEGIN DESCRIPTION:
Mapping XS f2f9d3d8
END DESCRIPTION:
XS GIS Cut Line= 4
      1998621.54     13651015.02      1998206.64     13651353.53
      1998060.81     13651504.58       1997968.8     13651855.27
#Sta/Elev= 30
  4505.5  795.62  4687.8  795.07  4786.9  797.13  4893.8  795.96  4943.4  793.05
  4978.6  786.77  4997.8  785.41  4998.3  784.61  5003.8  785.41  5007.3  786.86
  5015.2  786.87  5021.7   789.4  5029.6   788.9  5050.3  791.12  5057.2  789.95
  5064.4  791.04  5071.4  788.14  5078.6  788.31  5085.5  785.54  5099.6  785.87
  5106.8  787.44  5113.8  786.91  5135.1  792.25  5177.6  794.59    5220  794.57
  5255.3  791.74  5295.7  790.63  5354.8  793.72  5540.9  796.15  5613.5  796.85
#Mann= 4 ,-1 , 0
  4505.5      .1       0  4997.8     .07       0  5003.8      .1       0
  5540.9     .05       0
Bank Sta=4997.8,5003.8
XS Rating Curve= 0 ,0
Exp/Cntr=0.3,0.1

Type RM Length L Ch R = 1 ,2396    ,55,55,55
BEGIN DESCRIPTION:
Mapping XS a54b6cf7
END DESCRIPTION:
XS GIS Cut Line= 4
      1998416.71     13650966.39      1998019.14     13651221.59
       1998031.3      13651476.8      1997956.64     13651898.72
#Sta/Elev= 30
  4488.6  794.22  4511.1  793.61  4553.4  793.74  4683.6  792.26  4792.6  790.43
  4907.5  786.41  4937.9  786.03  4943.8  784.94  4953.1  784.65    4959   783.3
  5001.5  782.58    5002  781.78    5007  781.78  5007.5  782.58  5104.6  783.12
  5114.6  784.05  5134.6  787.89  5144.6  788.92  5184.5  789.53  5189.5  790.65
  5216.5  790.29  5226.9  789.09  5255.3  789.14  5275.6  790.55  5286.1  790.33
  5326.4  792.21  5335.1   793.1  5529.2   796.2  5620.8  797.33    5645  797.18
#Mann= 4 ,-1 , 0
  4488.6      .1       0  5001.5     .07       0  5007.5      .1       0
  5529.2     .05       0
Bank Sta=5001.5,5007.5
XS Rating Curve= 0 ,0
Exp/Cntr=0.3,0.1

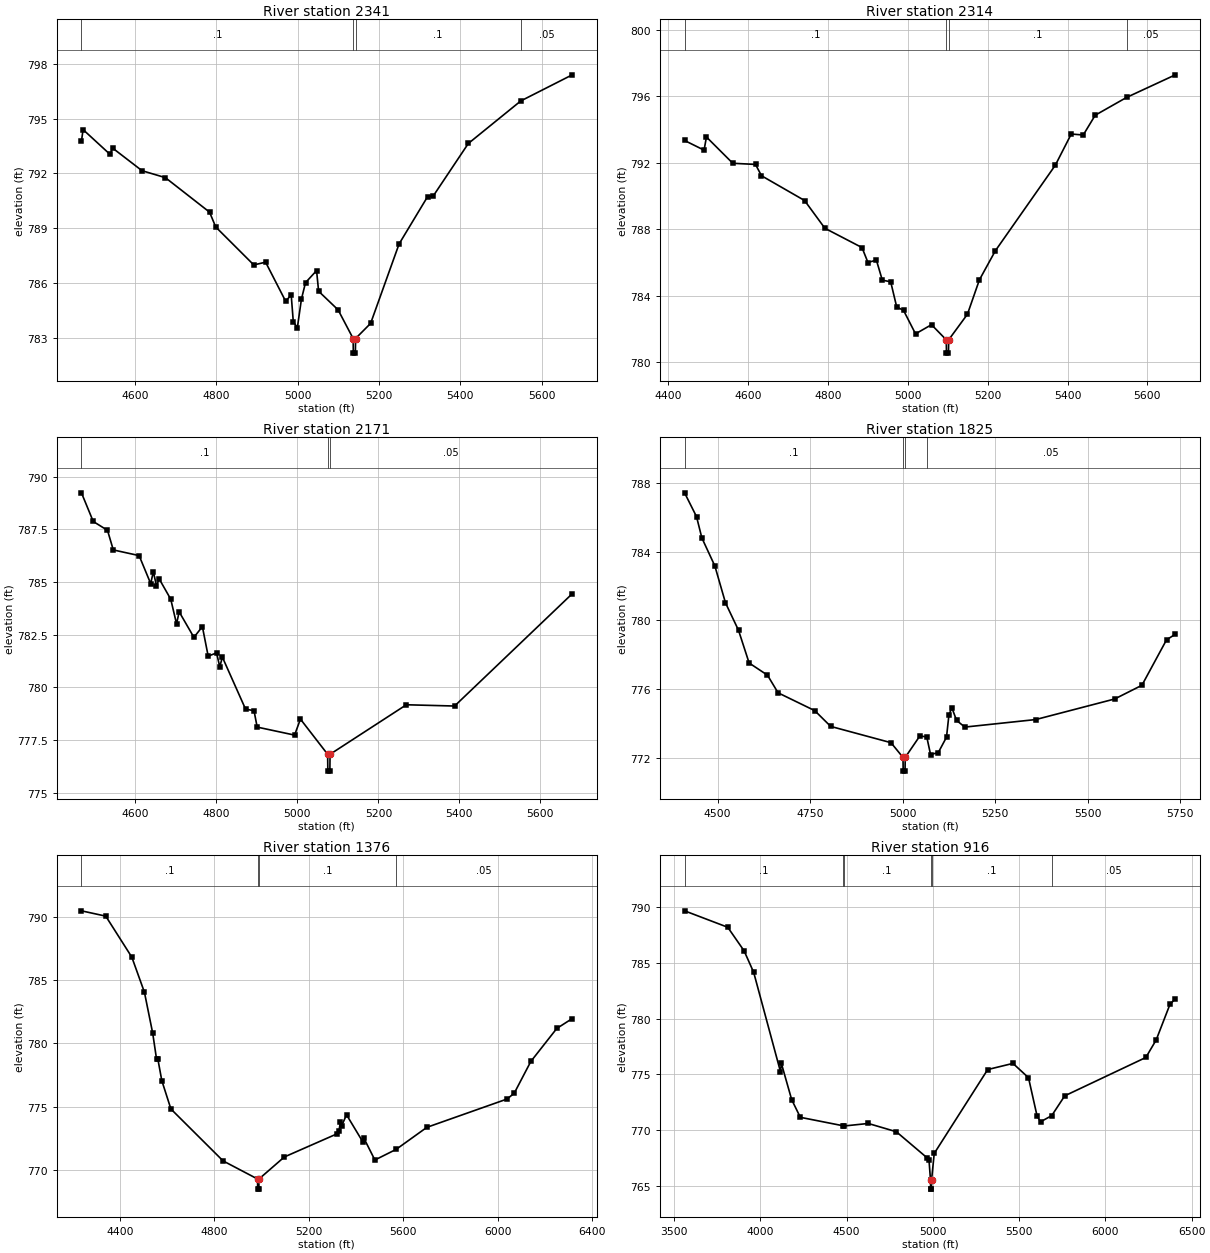
Type RM Length L Ch R = 1 ,2341    ,27,27,27
BEGIN DESCRIPTION:
Mapping XS c435b57d
END DESCRIPTION:
XS GIS Cut Line= 3
      1998404.57      13650938.6      1997972.27     13651219.85
      1997947.98     13651910.39
#Sta/Elev= 30
  4468.5  793.77  4472.5   794.4    4539  793.04    4545  793.39  4617.4  792.15
  4674.8  791.77  4783.5  789.88  4798.6  789.07  4892.2  786.99  4921.3  787.14
  4970.6     785  4984.2  785.35  4989.4  783.87  4999.4  783.56  5009.4  785.12
  5019.4  786.02  5046.6  786.68  5051.6  785.55  5099.5  784.53  5136.5  782.96
    5137  782.16    5142  782.16  5142.5  782.96  5179.5  783.79  5249.5  788.14
  5319.6  790.73  5333.9  790.78  5419.7  793.64  5548.7  795.97  5675.2   797.4
#Mann= 4 ,-1 , 0
  4468.5      .1       0  5136.5     .07       0  5142.5      .1       0
  5548.7     .05       0
Bank Sta=5136.5,5142.5
XS Rating Curve= 0 ,0
Exp/Cntr=0.3,0.1

Type RM Length L Ch R = 1 ,2314    ,143,143,143
BEGIN DESCRIPTION:
Mapping XS b2c7f1be
END DESCRIPTION:
XS GIS Cut Line= 3
      1998388.97     13650911.67      1997946.23     13651211.17
      1997933.21     13651905.62
#Sta/Elev= 30
    4441  793.33  4489.8  792.75  4495.8  793.54  4561.7  791.96  4618.7  791.89
  4633.6  791.21  4741.5  789.72  4792.4  788.05  4885.3  786.89  4900.3  785.99
  4921.3  786.14  4936.2  784.93  4957.2  784.83  4972.2  783.32  4989.4  783.11
  5019.4   781.7  5059.4  782.25  5096.4  781.34  5096.9  780.54  5101.9  780.54
  5102.4  781.34  5149.4  782.88  5179.4  784.95  5219.4   786.7  5369.4  791.84
  5409.4  793.72  5439.4  793.66  5469.4  794.85  5547.9  795.92  5670.1  797.28
#Mann= 4 ,-1 , 0
    4441      .1       0  5096.4     .07       0  5102.4      .1       0
  5547.9     .05       0
Bank Sta=5096.4,5102.4
XS Rating Curve= 0 ,0
Exp/Cntr=0.3,0.1

Type RM Length L Ch R = 1 ,2171    ,346,346,346
BEGIN DESCRIPTION:
Mapping XS 3cd63f9c
END DESCRIPTION:
XS GIS Cut Line= 3
      1998240.21     13650829.52      1997532.74      13651419.8
      1997528.41     13651710.29
#Sta/Elev= 30
  4466.8  789.23  4495.9  787.87  4531.1  787.45  4545.4  786.52  4609.2  786.25
  4637.8  784.92  4644.3  785.49  4652.1  784.81  4658.6  785.15  4687.3  784.18
  4701.6  783.01  4708.1  783.58  4744.5  782.37  4765.4  782.88  4779.7  781.48
  4800.5  781.63  4808.3  780.97  4814.8  781.43  4872.1  778.96  4892.9  778.89
  4900.7  778.11  4993.1  777.73  5007.5  778.49  5074.7  776.82  5075.2  776.02
  5080.2  776.02  5080.7  776.82  5269.1  779.17  5388.2  779.11  5678.7  784.44
#Mann= 3 ,-1 , 0
  4466.8      .1       0  5074.7     .07       0  5080.7     .05       0
Bank Sta=5074.7,5080.7
XS Rating Curve= 0 ,0
Exp/Cntr=0.3,0.1

Type RM Length L Ch R = 1 ,1825    ,449,449,449
BEGIN DESCRIPTION:
Mapping XS b3919f67
END DESCRIPTION:
XS GIS Cut Line= 3
      1998175.12     13650499.64      1997402.53       13651129.
      1997385.17     13651458.86
#Sta/Elev= 30
  4410.6  787.45  4442.9  786.06  4457.3  784.82  4492.5  783.18  4521.2  781.03
  4556.4  779.43  4585.1  777.52  4634.7  776.81  4663.4  775.78  4762.5  774.74
  4805.6  773.82  4968.6  772.87  5001.1  772.01  5001.6  771.21  5006.6  771.21
  5007.1  772.01  5046.9  773.27  5065.4   773.2  5075.6  772.18  5096.4  772.29
  5118.7  773.19  5125.1  774.46    5133  774.92  5145.9  774.17  5168.2  773.78
    5360  774.22  5573.3  775.42    5647  776.22  5713.5  778.87  5737.4   779.2
#Mann= 4 ,-1 , 0
  4410.6      .1       0  5001.1     .07       0  5007.1      .1       0
  5065.4     .05       0
Bank Sta=5001.1,5007.1
XS Rating Curve= 0 ,0
Exp/Cntr=0.3,0.1

Type RM Length L Ch R = 1 ,1376    ,460,460,460
BEGIN DESCRIPTION:
Mapping XS 0d6183e9
END DESCRIPTION:
XS GIS Cut Line= 3
      1998331.32     13650152.45      1997341.77     13650668.93
       1997319.7     13651630.35
#Sta/Elev= 30
    4238  790.47  4340.9  790.05  4451.3  786.81  4504.6  784.04  4539.7   780.8
  4556.1  778.74  4561.8  778.73  4578.2  777.06  4616.7  774.82  4837.6  770.72
  4983.6  769.29  4984.1  768.49  4989.1  768.49  4989.6  769.29    5097  771.03
  5317.9  772.84    5328  773.07  5334.3  773.76  5339.9  773.51  5360.3  774.36
  5428.4  772.25  5433.4  772.53  5480.3  770.79  5570.4  771.63  5700.4  773.37
  6040.5  775.61  6070.5  776.07  6140.5  778.57  6250.5  781.18  6315.9  781.96
#Mann= 4 ,-1 , 0
    4238      .1       0  4983.6     .07       0  4989.6      .1       0
  5570.4     .05       0
Bank Sta=4983.6,4989.6
XS Rating Curve= 0 ,0
Exp/Cntr=0.3,0.1

Type RM Length L Ch R = 1 ,916     ,120,120,120
BEGIN DESCRIPTION:
Mapping XS 18b77112
END DESCRIPTION:
XS GIS Cut Line= 4
      1998504.95     13649683.69      1997589.17     13649727.09
      1997272.33     13650560.42      1997271.95     13651595.98
#Sta/Elev= 30
  3561.7  789.63  3811.9  788.16  3906.7  786.05  3962.1  784.13  4117.4  775.25
  4122.4     776  4182.3  772.75  4232.4  771.17  4478.2  770.42  4483.2  770.39
  4626.1  770.62  4788.8  769.88  4968.4  767.53  4978.2  767.31  4986.8  765.55
  4987.3  764.75  4992.3  764.75  4992.8  765.55  5008.3  767.94  5318.2  775.44
  5464.6  775.99  5554.6  774.71  5604.6  771.27  5624.6  770.77  5689.1  771.32
  5764.6  773.09  6234.6  776.52  6294.6  778.09  6374.6  781.28  6405.6  781.76
#Mann= 6 ,-1 , 0
  3561.7      .1       0  4478.2     .05       0  4483.2      .1       0
  4986.8     .07       0  4992.8      .1       0  5689.1     .05       0
Bank Sta=4986.8,4992.8
XS Rating Curve= 0 ,0
Exp/Cntr=0.3,0.1

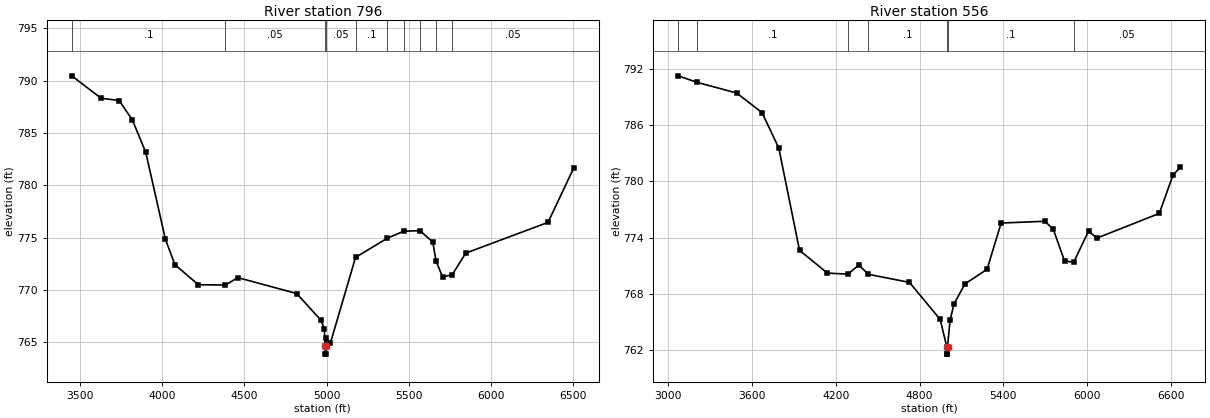
Type RM Length L Ch R = 1 ,796     ,240,240,240
BEGIN DESCRIPTION:
Mapping XS 051f2bb0
END DESCRIPTION:
XS GIS Cut Line= 4
       1998552.7     13649605.56      1997524.06     13649661.98
      1997185.52     13650443.23      1997219.82      13651611.7
#Sta/Elev= 30
  3451.9  790.46  3629.9  788.32    3740   788.1  3820.2  786.24  3901.7  783.14
  4020.5  774.86  4078.1  772.43  4220.8   770.5  4385.1  770.47  4461.1  771.18
  4818.5  769.66  4964.8  767.13  4986.7   766.3  4990.7  764.67  4991.2  763.87
  4996.2  763.87  4996.7  764.67  4999.2  765.41  5022.7  764.89    5176  773.11
  5369.6  774.95  5468.3  775.61  5566.9  775.67  5645.4  774.58  5665.5  772.75
  5705.5  771.23  5764.2  771.47  5845.5  773.52  6345.7  776.46  6502.5  781.68
#Mann= 10 ,-1 , 0
  3451.9      .1       0  4385.1     .05       0  4990.7     .04       0
  4996.7     .05       0    5176      .1       0  5369.6     .08       0
  5468.3     .05       0  5566.9      .1       0  5665.5     .08       0
  5764.2     .05       0
Bank Sta=4990.7,4996.7
XS Rating Curve= 0 ,0
Exp/Cntr=0.3,0.1

Type RM Length L Ch R = 1 ,556     ,0,0,0
BEGIN DESCRIPTION:
UNT 086 in HW 1.0
END DESCRIPTION:
XS GIS Cut Line= 4
      1998860.86     13649462.33      1997489.34     13649601.22
      1997003.23     13650182.82      1997189.48     13651626.32
#Sta/Elev= 30
  3073.5  791.23  3208.8  790.53  3491.5   789.4  3672.4  787.32    3793  783.54
  3941.2  772.64    4141  770.22  4287.6  770.11  4365.9  771.08  4433.5  770.09
  4727.9  769.23  4947.8  765.28  4994.3  762.39  4994.8  761.59  4999.8  761.59
  5000.3  762.39  5018.1  765.18  5046.8  766.95  5124.8  769.07  5282.8  770.62
  5383.6  775.55  5696.2  775.74  5756.7  774.89  5837.4   771.5  5903.3  771.39
  6008.8  774.69  6069.3  773.95  6515.6  776.58  6613.8  780.69  6665.5  781.47
#Mann= 7 ,-1 , 0
  3073.5     .05       0  3208.8      .1       0  4287.6     .05       0
  4433.5      .1       0  4994.3     .07       0  5000.3      .1       0
  5903.3     .05       0
Bank Sta=4994.3,5000.3
XS Rating Curve= 0 ,0
Exp/Cntr=0.3,0.1
LCMann Table=0

Chan Stop Cuts=-1
Use User Specified Reach Order=0
Composite Channel Slope=5