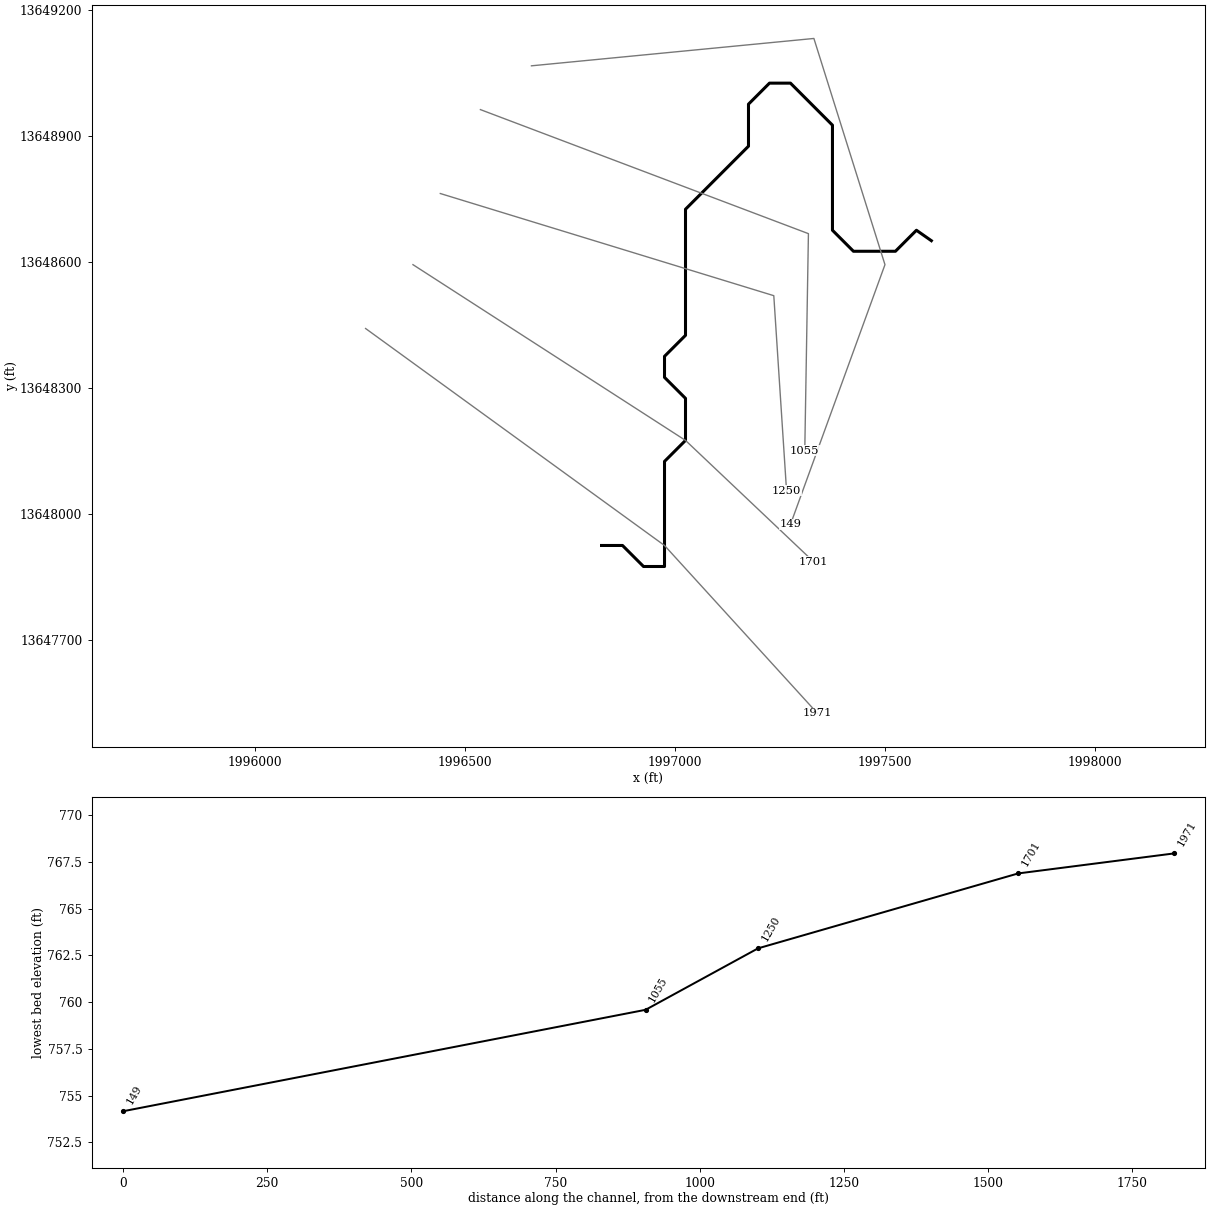
--- UNT 087 in HW.prj (project) ---

Proj Title=UNT 087 in HW Base Level Engineering
Current Plan=p01
Default Exp/Contr=0.3,0.1
English Units
Geom File=g01
Flow File=f01
Plan File=p01
BEGIN DESCRIPTION:
UNT 087 in HW
END DESCRIPTION:

--- UNT 087 in HW.p01 (plan) ---

Plan Title=Multiple Run
Short Identifier=Multiple
Geom File=g01
Flow File=f01
Subcritical Flow
K Sum by GR= 0
Std Step Tol= 0.01
Critical Tol= 0.01
Num of Std Step Trials= 20
Max Error Tol= 0.3
Flow Tol Ratio= 0.001
Split Flow NTrial= 30
Split Flow Tol= 0.02
Split Flow Ratio= 0.02
Log Output Level= 0
Friction Slope Method= 1
Unsteady Friction Slope Method= 2
Unsteady Bridges Friction Slope Method= 1
Parabolic Critical Depth
Global Vel Dist=  1 , 1 , 1
Global Log Level= 0
CheckData=True
Encroach Param= -1, 0, 0, 0
BEGIN DESCRIPTION:
Multiple Run
END DESCRIPTION:

--- UNT 087 in HW.f01 (steady flow) ---

Flow Title=Multiple
Number of Profiles=7
Profile Names=10-year,25-year,50-year,1pct_min,100-year,1pct_plu,500-year
River Rch & RM= UNT 087 in HW,Reach-1,1971
     528     742     920     567    1130    2255    1709
Boundary for River Rch & Prof#=UNT 087 in HW,Reach-1,1
Up Type=0
Dn Type=3
Dn Slope=0.005
Boundary for River Rch & Prof#=UNT 087 in HW,Reach-1,2
Up Type=0
Dn Type=3
Dn Slope=0.005
Boundary for River Rch & Prof#=UNT 087 in HW,Reach-1,3
Up Type=0
Dn Type=3
Dn Slope=0.005
Boundary for River Rch & Prof#=UNT 087 in HW,Reach-1,4
Up Type=0
Dn Type=3
Dn Slope=0.005
Boundary for River Rch & Prof#=UNT 087 in HW,Reach-1,5
Up Type=0
Dn Type=3
Dn Slope=0.005
Boundary for River Rch & Prof#=UNT 087 in HW,Reach-1,6
Up Type=0
Dn Type=3
Dn Slope=0.005
Boundary for River Rch & Prof#=UNT 087 in HW,Reach-1,7
Up Type=0
Dn Type=3
Dn Slope=0.005

--- UNT 087 in HW.g01 (geometry) ---

Geom Title=Existing Conditions

River Reach=UNT 087 in HW,Reach-1
Reach XY= 21
      1996825.00     13647925.00      1996875.00     13647925.00
      1996925.00     13647875.00      1996975.00     13647875.00
      1996975.00     13648125.00      1997025.00     13648175.00
      1997025.00     13648275.00      1996975.00     13648325.00
      1996975.00     13648375.00      1997025.00     13648425.00
      1997025.00     13648725.00      1997175.00     13648875.00
      1997175.00     13648975.00      1997225.00     13649025.00
      1997275.00     13649025.00      1997375.00     13648925.00
      1997375.00     13648675.00      1997425.00     13648625.00
      1997525.00     13648625.00      1997575.00     13648675.00
      1997610.57     13648650.12

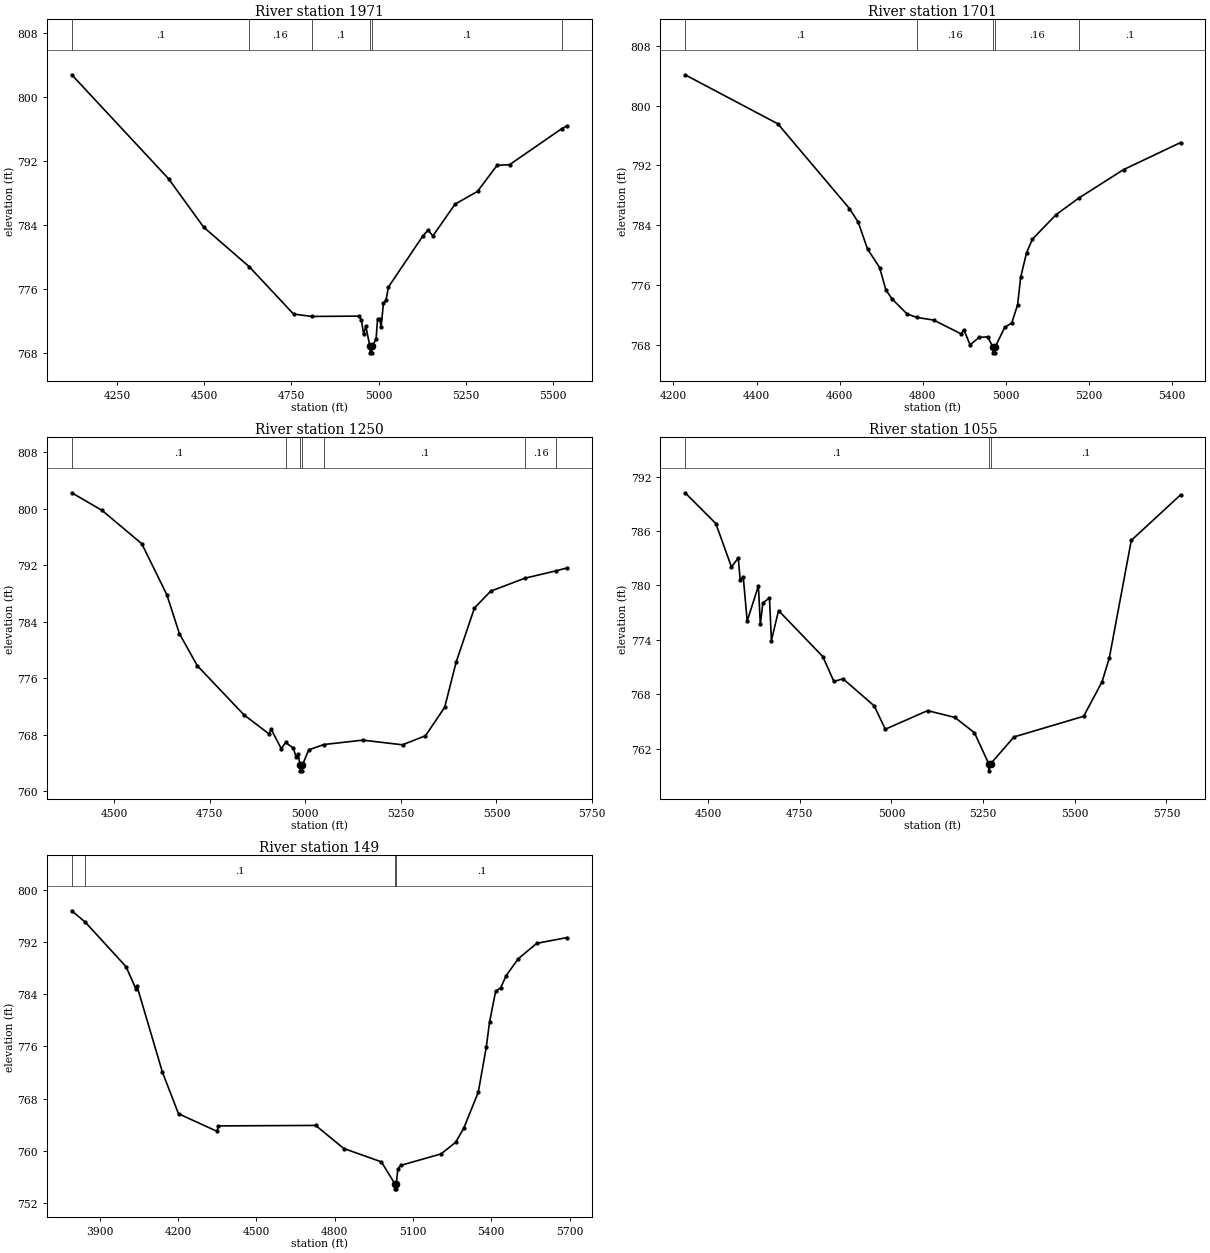
Type RM Length L Ch R = 1,1971,270,270,270
BEGIN DESCRIPTION:
UNT 087 in HW 3.0
END DESCRIPTION:
XS GIS Cut Line= 3
      1996263.06     13648441.22      1996975.00     13647925.00
      1997339.43     13647525.43
#Sta/Elev= 30
  4120.6  802.72  4398.1  789.72  4498.6  783.67  4629.2  778.73  4756.1  772.81
  4808.0  772.51  4942.4  772.55  4950.6  772.10  4957.1  770.26  4963.3  771.29
  4975.0  768.76  4975.5  767.96  4980.5  767.96  4981.0  768.76  4992.7  769.65
  4996.9  772.13  5003.4  772.13  5007.1  771.18  5013.9  774.19  5021.3  774.53
  5028.0  776.18  5127.4  782.61  5141.5  783.28  5155.7  782.59  5219.2  786.55
  5283.4  788.14  5339.5  791.40  5375.3  791.48  5525.4  796.00  5540.8  796.36
#Mann=6,-1,0
  4120.6     0.1       0  4629.2    0.16       0  4808.0     0.1       0
  4975.0    0.07       0  4981.0     0.1       0  5525.4    0.05       0
Bank Sta=4975,4981
Exp/Cntr=0.3,0.1

Type RM Length L Ch R = 1,1701,451,451,451
BEGIN DESCRIPTION:
UNT 087 in HW 2.0
END DESCRIPTION:
XS GIS Cut Line= 3
      1996375.91     13648593.12      1997025.00     13648175.00
      1997330.36     13647886.05
#Sta/Elev= 30
  4227.9  804.15  4451.1  797.58  4623.4  786.23  4644.5  784.40  4666.9  780.81
  4696.0  778.32  4711.2  775.31  4726.4  774.09  4762.1  772.10  4785.4  771.64
  4826.0  771.28  4892.7  769.42  4898.7  769.99  4913.8  767.96  4935.0  768.95
  4956.1  769.04  4968.3  767.69  4968.8  766.89  4973.8  766.89  4974.3  767.69
  4997.0  770.30  5014.0  770.90  5028.1  773.33  5035.4  777.01  5049.6  780.29
  5063.7  782.12  5120.3  785.39  5175.1  787.62  5283.0  791.44  5420.4  795.07
#Mann=5,-1,0
  4227.9     0.1       0  4785.4    0.16       0  4968.3    0.07       0
  4974.3    0.16       0  5175.1     0.1       0
Bank Sta=4968.3,4974.3
Exp/Cntr=0.3,0.1

Type RM Length L Ch R = 1,1250,195,195,195
BEGIN DESCRIPTION:
Mapping XS 5666e948
END DESCRIPTION:
XS GIS Cut Line= 3
      1996441.03     13648762.38      1997235.29     13648519.33
      1997265.67     13648054.94
#Sta/Elev= 30
  4389.3  802.29  4468.8  799.78  4572.4  795.07  4637.9  787.85  4670.7  782.34
  4717.6  777.78  4839.8  770.81  4905.4  768.11  4910.6  768.79  4937.3  766.01
  4948.4  766.90  4968.6  766.11  4976.1  764.83  4981.4  765.25  4986.5  763.68
  4987.0  762.88  4992.0  762.88  4992.5  763.68  5008.9  765.85  5048.7  766.61
  5150.5  767.23  5254.3  766.57  5314.4  767.85  5364.6  771.89  5394.6  778.30
  5442.5  785.97  5484.8  788.34  5574.0  790.18  5656.8  791.24  5685.3  791.65
#Mann=7,-1,0
  4389.3     0.1       0  4948.4    0.16       0  4986.5    0.07       0
  4992.5    0.16       0  5048.7     0.1       0  5574.0    0.16       0
  5656.8     0.1       0
Bank Sta=4986.5,4992.5
Exp/Cntr=0.3,0.1

Type RM Length L Ch R = 1,1055,906,906,906
BEGIN DESCRIPTION:
Mapping XS ba0b496f
END DESCRIPTION:
XS GIS Cut Line= 3
      1996536.53     13648962.03      1997317.75     13648666.90
      1997309.07     13648150.39
#Sta/Elev= 30
  4437.1  790.21  4521.0  786.82  4563.7  782.03  4582.1  783.04  4587.4  780.61
  4595.8  780.93  4606.5  776.08  4637.1  779.95  4642.4  775.73  4649.3  778.10
  4667.3  778.62  4672.6  773.94  4692.0  777.24  4812.8  772.17  4843.0  769.43
  4867.9  769.73  4953.1  766.74  4983.2  764.17  5098.6  766.22  5173.1  765.47
  5226.5  763.78  5265.1  760.39  5265.6  759.59  5271.1  760.39  5334.1  763.32
  5524.2  765.60  5574.2  769.37  5594.2  772.01  5654.2  784.97  5788.8  789.99
#Mann=3,-1,0
  4437.1     0.1       0  5265.1    0.07       0  5271.1     0.1       0
Bank Sta=5265.1,5271.1
Exp/Cntr=0.3,0.1

Type RM Length L Ch R = 1,149,0,0,0
BEGIN DESCRIPTION:
UNT 087 in HW 1.0
END DESCRIPTION:
XS GIS Cut Line= 4
      1996658.08     13649066.21      1997330.78     13649131.31
      1997500.05     13648593.12      1997275.01     13647975.03
#Sta/Elev= 30
  3793.4  796.79  3845.5  795.03  4001.3  788.22  4038.4  784.87  4043.4  785.22
  4140.5  772.06  4202.2  765.67  4349.8  762.98  4354.9  763.81  4727.4  763.88
  4835.4  760.34  4979.0  758.30  5030.3  754.96  5030.8  754.16  5035.8  754.16
  5036.3  754.96  5042.1  757.17  5052.7  757.75  5208.0  759.52  5263.8  761.31
  5294.4  763.44  5350.2  768.97  5380.8  775.86  5393.3  779.71  5416.7  784.46
  5435.8  784.96  5457.1  786.85  5503.1  789.43  5574.2  791.80  5691.2  792.69
#Mann=4,-1,0
  3793.4    0.05       0  3845.5     0.1       0  5030.3    0.07       0
  5036.3     0.1       0
Bank Sta=5030.3,5036.3
Exp/Cntr=0.3,0.1

Chan Stop Cuts=-1