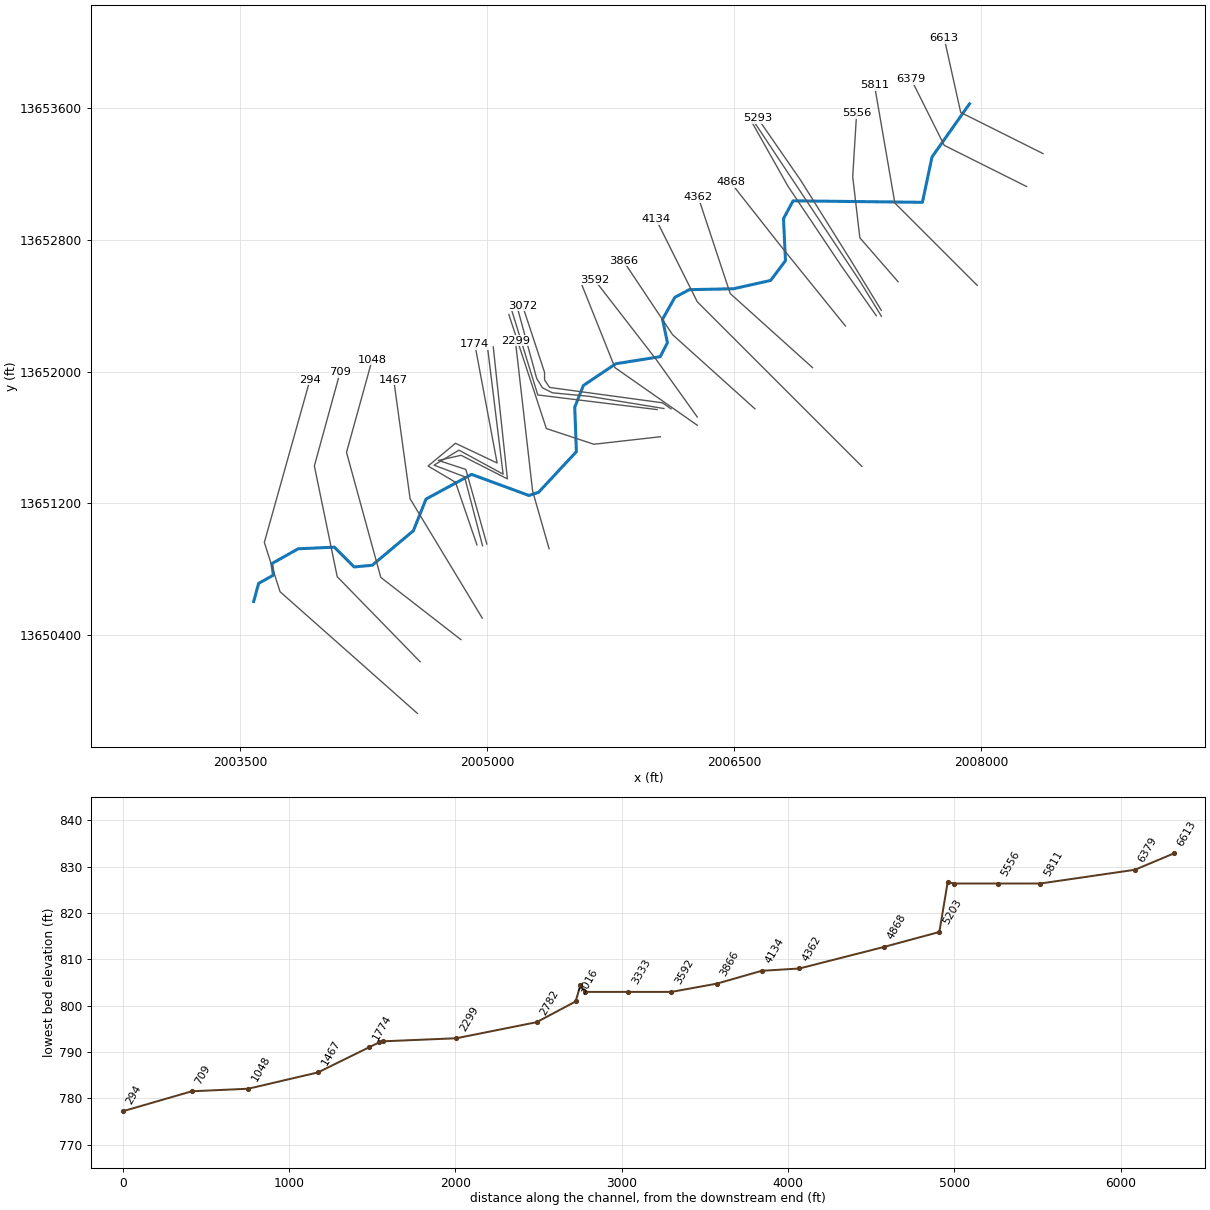
--- UNT 088 in HW.prj (project) ---

Proj Title=UNT 088 in HW Base Level Engineering
Current Plan=p01
Default Exp/Contr=0.3,0.1
English Units
Geom File=g01
Flow File=f01
Plan File=p01
BEGIN DESCRIPTION:
UNT 088 in HW
END DESCRIPTION:

--- UNT 088 in HW.p01 (plan) ---

Plan Title=Multiple Run
Short Identifier=Multiple
Geom File=g01
Flow File=f01
Subcritical Flow
K Sum by GR= 0
Std Step Tol= 0.01
Critical Tol= 0.01
Num of Std Step Trials= 20
Max Error Tol= 0.3
Flow Tol Ratio= 0.001
Split Flow NTrial= 30
Split Flow Tol= 0.02
Split Flow Ratio= 0.02
Log Output Level= 0
Friction Slope Method= 1
Unsteady Friction Slope Method= 2
Unsteady Bridges Friction Slope Method= 1
Parabolic Critical Depth
Global Vel Dist=  1 , 1 , 1
Global Log Level= 0
CheckData=True
Encroach Param= -1, 0, 0, 0
BEGIN DESCRIPTION:
Multiple Run
END DESCRIPTION:

--- UNT 088 in HW.f01 (steady flow) ---

Flow Title=Multiple
Number of Profiles=7
Profile Names=10-year,25-year,50-year,1pct_min,100-year,1pct_plu,500-year
River Rch & RM= UNT 088 in HW,Reach-1,6613
     475     662     817     500     999    1992    1495
River Rch & RM= UNT 088 in HW,Reach-1,2299
     607     858    1069     660    1316    2627    2003
Boundary for River Rch & Prof#=UNT 088 in HW,Reach-1,1
Up Type=0
Dn Type=3
Dn Slope=0.005
Boundary for River Rch & Prof#=UNT 088 in HW,Reach-1,2
Up Type=0
Dn Type=3
Dn Slope=0.005
Boundary for River Rch & Prof#=UNT 088 in HW,Reach-1,3
Up Type=0
Dn Type=3
Dn Slope=0.005
Boundary for River Rch & Prof#=UNT 088 in HW,Reach-1,4
Up Type=0
Dn Type=3
Dn Slope=0.005
Boundary for River Rch & Prof#=UNT 088 in HW,Reach-1,5
Up Type=0
Dn Type=3
Dn Slope=0.005
Boundary for River Rch & Prof#=UNT 088 in HW,Reach-1,6
Up Type=0
Dn Type=3
Dn Slope=0.005
Boundary for River Rch & Prof#=UNT 088 in HW,Reach-1,7
Up Type=0
Dn Type=3
Dn Slope=0.005

--- UNT 088 in HW.g01 (geometry) ---

Geom Title=Existing Conditions

River Reach=UNT 088 in HW,Reach-1
Reach XY= 30
      2007928.69     13653627.42      2007700.80     13653304.54
      2007642.40     13653029.03      2006856.99     13653038.06
      2006798.65     13652929.73      2006810.80     13652674.54
      2006720.80     13652554.54      2006495.18     13652504.03
      2006226.43     13652498.48      2006138.93     13652451.95
      2006063.93     13652318.62      2006093.79     13652176.26
      2006050.04     13652091.53      2005779.90     13652048.48
      2005583.38     13651916.53      2005530.80     13651784.54
      2005540.80     13651514.54      2005311.24     13651267.97
      2005252.65     13651248.43      2004904.34     13651376.47
      2004627.65     13651226.73      2004550.80     13651034.54
      2004300.80     13650824.54      2004190.80     13650814.54
      2004070.80     13650934.54      2003850.80     13650924.54
      2003690.80     13650834.54      2003700.80     13650764.54
      2003610.80     13650714.54      2003580.80     13650604.54

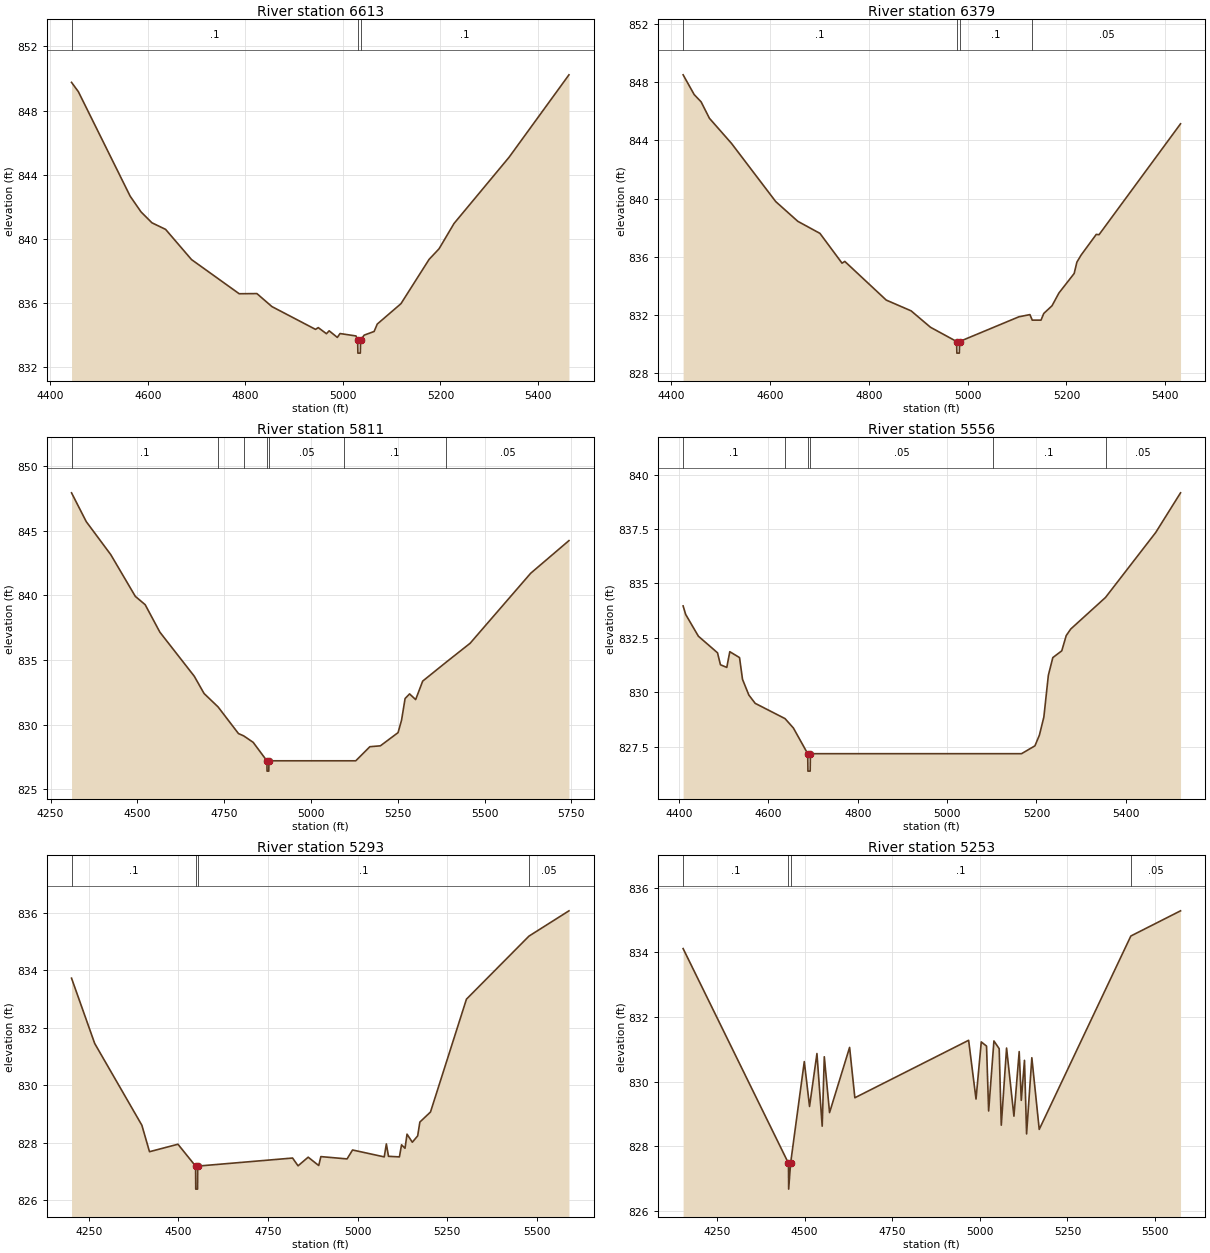
Type RM Length L Ch R = 1,6613,234,234,234
BEGIN DESCRIPTION:
UNT 088 in HW 14.0
END DESCRIPTION:
XS GIS Cut Line= 3
      2008375.00     13653325.00      2007875.00     13653575.00
      2007775.00     13654025.01
#Sta/Elev= 30
  4443.6  849.76  4457.6  849.18  4563.8  842.67  4586.1  841.69  4608.5  841.01
  4636.5  840.60  4689.6  838.72  4787.4  836.59  4823.7  836.60  4854.5  835.79
  4943.9  834.37  4949.5  834.48  4966.3  834.10  4971.9  834.28  4988.6  833.87
  4994.2  834.11  5026.9  833.96  5030.3  833.69  5030.8  832.89  5035.8  832.89
  5036.3  833.69  5043.6  834.01  5064.1  834.24  5070.5  834.70  5119.1  835.97
  5176.8  838.73  5197.2  839.39  5228.0  840.97  5340.7  845.09  5463.6  850.23
#Mann=3,-1,0
  4443.6     0.1       0  5030.3    0.07       0  5036.3     0.1       0
Bank Sta=5030.3,5036.3
Exp/Cntr=0.3,0.1

Type RM Length L Ch R = 1,6379,568,568,568
BEGIN DESCRIPTION:
UNT 088 in HW 13.0
END DESCRIPTION:
XS GIS Cut Line= 3
      2008275.04     13653124.98      2007775.00     13653375.00
      2007574.99     13653775.02
#Sta/Elev= 30
  4424.5  848.51  4446.9  847.15  4460.9  846.65  4477.7  845.52  4522.4  843.79
  4611.8  839.79  4656.5  838.43  4701.3  837.60  4746.0  835.55  4751.6  835.67
  4835.4  833.01  4885.7  832.27  4924.9  831.14  4977.8  830.16  4978.3  829.36
  4983.3  829.36  4983.8  830.16  5103.8  831.86  5126.1  832.01  5130.8  831.63
  5148.5  831.63  5154.1  832.09  5170.8  832.62  5184.8  833.50  5215.6  834.84
  5221.1  835.62  5229.5  836.10  5260.3  837.53  5265.9  837.51  5430.8  845.14
#Mann=4,-1,0
  4424.5     0.1       0  4977.8    0.07       0  4983.8     0.1       0
  5130.8    0.05       0
Bank Sta=4977.8,4983.8
Exp/Cntr=0.3,0.1

Type RM Length L Ch R = 1,5811,255,255,255
BEGIN DESCRIPTION:
UNT 088 in HW 12.0
END DESCRIPTION:
XS GIS Cut Line= 3
      2007974.98     13652525.02      2007475.00     13653025.00
      2007351.46     13653740.13
#Sta/Elev= 30
  4310.4  847.94  4352.8  845.71  4423.5  843.15  4494.2  839.92  4522.5  839.28
  4564.9  837.15  4663.9  833.74  4692.2  832.40  4732.6  831.36  4791.2  829.30
  4806.3  829.12  4833.6  828.62  4873.1  827.19  4873.6  826.39  4878.6  826.39
  4879.1  827.19  5094.8  827.19  5129.1  827.19  5169.7  828.28  5200.1  828.35
  5250.9  829.37  5261.0  830.33  5271.2  832.01  5284.1  832.37  5301.6  831.93
  5321.9  833.36  5388.8  834.81  5458.5  836.29  5632.9  841.71  5743.2  844.24
#Mann=7,-1,0
  4310.4     0.1       0  4732.6    0.08       0  4806.3    0.05       0
  4873.1   0.033       0  4879.1    0.05       0  5094.8     0.1       0
  5388.8    0.05       0
Bank Sta=4873.1,4879.1
Exp/Cntr=0.3,0.1

Type RM Length L Ch R = 1,5556,263,263,263
BEGIN DESCRIPTION:
Mapping XS 284d7fc5
END DESCRIPTION:
XS GIS Cut Line= 4
      2007494.66     13652546.70      2007262.46     13652813.62
      2007219.06     13653184.71      2007242.90     13653570.47
#Sta/Elev= 30
  4408.9  833.97  4414.6  833.58  4443.1  832.58  4485.9  831.82  4492.5  831.27
  4506.7  831.15  4513.4  831.87  4535.2  831.60  4541.9  830.60  4556.1  829.88
  4570.3  829.50  4637.1  828.80  4655.8  828.37  4687.9  827.19  4688.4  826.39
  4693.4  826.39  4693.9  827.19  5102.7  827.19  5166.7  827.19  5196.7  827.55
  5206.7  828.04  5216.7  828.87  5226.8  830.79  5236.8  831.60  5256.8  831.91
  5266.8  832.61  5276.9  832.91  5354.8  834.36  5467.2  837.34  5522.8  839.16
#Mann=6,-1,0
  4408.9     0.1       0  4637.1    0.05       0  4687.9   0.033       0
  4693.9    0.05       0  5102.7     0.1       0  5354.8    0.05       0
Bank Sta=4687.9,4693.9
Exp/Cntr=0.3,0.1

Type RM Length L Ch R = 1,5293,40,40,40
BEGIN DESCRIPTION:
Mapping XS 53e37e6c
END DESCRIPTION:
XS GIS Cut Line= 4
      2007392.67     13652373.08      2007212.55     13652668.22
      2006904.39     13653160.84      2006641.99     13653540.33
#Sta/Elev= 30
  4201.6  833.72  4266.3  831.45  4397.9  828.61  4419.2  827.69  4498.6  827.95
  4547.8  827.19  4548.3  826.39  4553.3  826.39  4553.8  827.19  4818.5  827.47
  4833.8  827.20  4862.0  827.50  4891.5  827.21  4897.4  827.52  4970.5  827.44
  4985.9  827.75  5074.3  827.51  5080.2  827.96  5086.2  827.53  5116.7  827.51
  5122.6  827.93  5132.3  827.81  5137.9  828.30  5152.7  828.02  5167.6  828.24
  5173.7  828.72  5203.4  829.07  5303.7  832.99  5478.1  835.18  5589.8  836.06
#Mann=4,-1,0
  4201.6     0.1       0  4547.8    0.07       0  4553.8     0.1       0
  5478.1    0.05       0
Bank Sta=4547.8,4553.8
Exp/Cntr=0.3,0.1

Type RM Length L Ch R = 1,5253,50,50,50
BEGIN DESCRIPTION:
UNT 088 in HW 11.0
END DESCRIPTION:
XS GIS Cut Line= 3
      2007393.51     13652336.95      2007261.59     13652552.19
      2006615.77     13653524.39
#Sta/Elev= 30
  4153.3  834.12  4454.0  827.47  4454.5  826.67  4460.0  827.47  4499.1  830.62
  4514.1  829.23  4535.2  830.87  4550.2  828.62  4556.2  830.77  4571.2  829.04
  4628.4  831.06  4643.4  829.50  4968.1  831.28  4989.2  829.46  5004.2  831.23
  5019.2  831.10  5025.2  829.09  5040.3  831.26  5055.3  831.02  5061.3  828.65
  5076.4  831.04  5097.4  828.93  5112.4  830.93  5118.4  829.42  5127.5  830.66
  5133.5  828.38  5148.5  830.74  5169.6  828.52  5431.1  834.51  5572.9  835.29
#Mann=4,-1,0
  4153.3     0.1       0  4454.0    0.07       0  4460.0     0.1       0
  5431.1    0.05       0
Bank Sta=4454,4460
Exp/Cntr=0.3,0.1

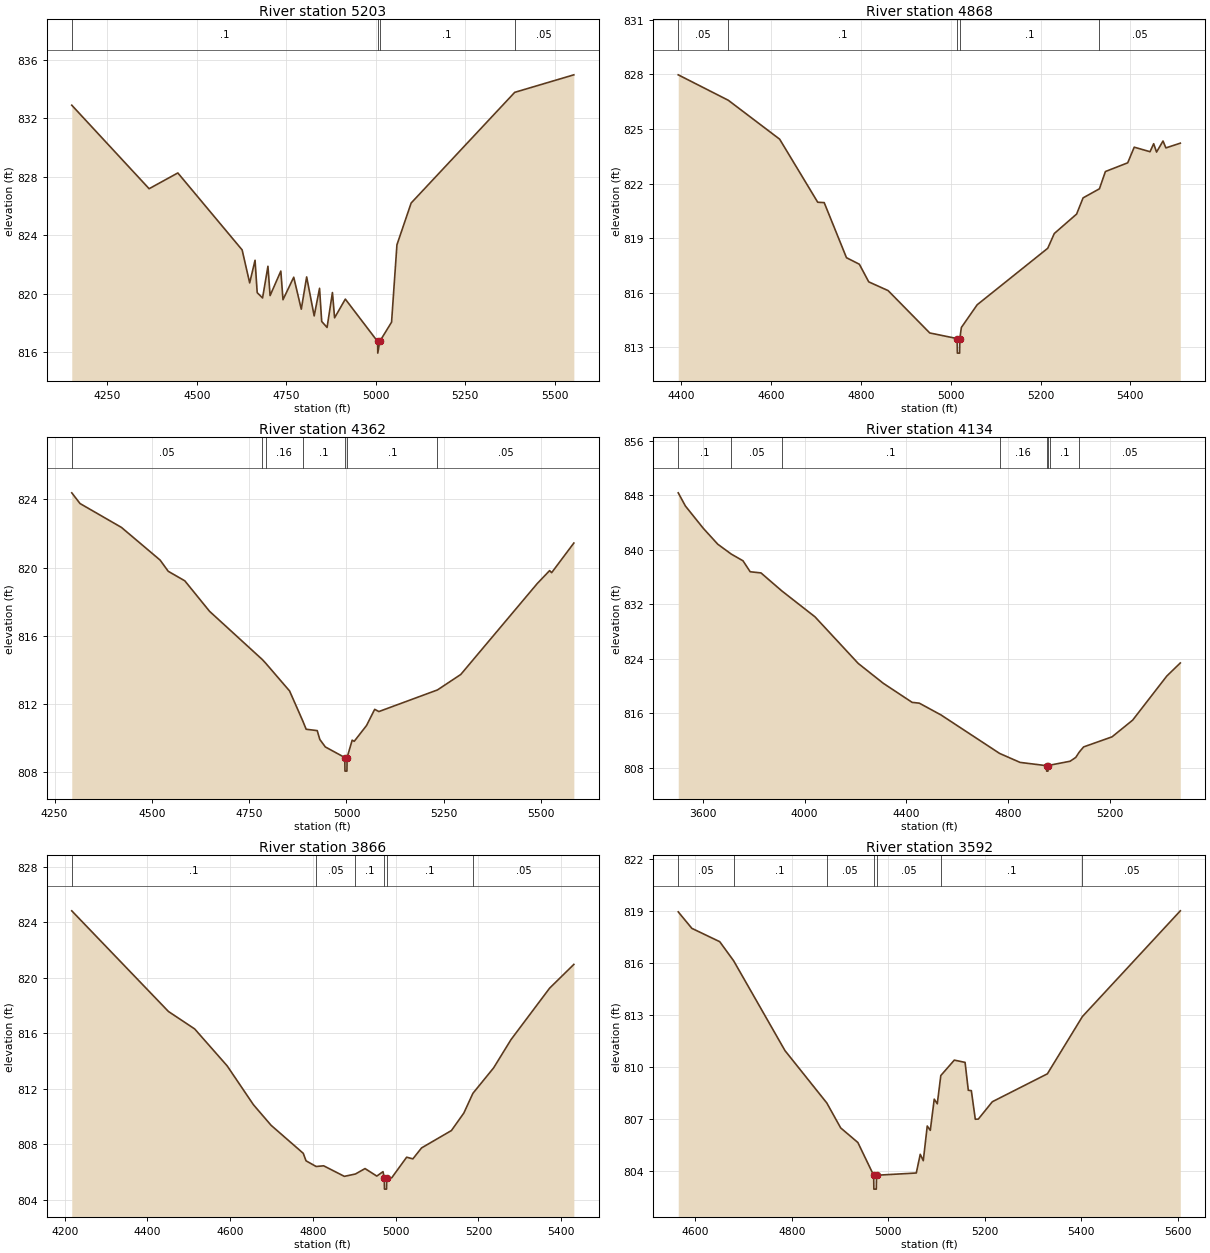
Type RM Length L Ch R = 1,5203,335,335,335
BEGIN DESCRIPTION:
Mapping XS e318a7cc
END DESCRIPTION:
XS GIS Cut Line= 4
      2007362.29     13652340.53      2007147.44     13652646.52
      2006826.26     13653126.12      2006604.89     13653518.94
#Sta/Elev= 30
  4151.1  832.90  4367.1  827.18  4447.3  828.26  4626.8  822.99  4647.9  820.73
  4662.9  822.28  4668.9  820.06  4683.9  819.70  4698.9  821.87  4704.9  819.86
  4734.9  821.54  4740.9  819.58  4770.9  821.12  4792.0  818.93  4807.0  821.14
  4828.0  818.47  4843.0  820.36  4849.0  818.09  4864.0  817.68  4879.0  820.07
  4885.0  818.34  4915.0  819.62  5005.1  816.72  5005.6  815.92  5011.1  816.72
  5044.1  818.04  5059.1  823.34  5098.8  826.20  5388.0  833.78  5553.1  834.98
#Mann=4,-1,0
  4151.1     0.1       0  5005.1    0.07       0  5011.1     0.1       0
  5388.0    0.05       0
Bank Sta=5005.1,5011.1
Exp/Cntr=0.3,0.1

Type RM Length L Ch R = 1,4868,506,506,506
BEGIN DESCRIPTION:
UNT 088 in HW 10.0
END DESCRIPTION:
XS GIS Cut Line= 3
      2007174.79     13652277.88      2006773.31     13652774.84
      2006476.98     13653151.21
#Sta/Elev= 30
  4393.4  827.98  4504.9  826.58  4619.2  824.44  4704.0  820.97  4718.4  820.95
  4768.0  817.92  4796.7  817.56  4817.6  816.59  4860.7  816.11  4953.4  813.78
  5014.4  813.47  5014.9  812.67  5019.9  812.67  5020.4  813.47  5023.8  814.08
  5059.0  815.33  5216.2  818.44  5230.7  819.25  5280.4  820.32  5294.8  821.21
  5331.2  821.71  5344.5  822.66  5394.2  823.14  5408.7  824.00  5443.9  823.75
  5452.0  824.19  5458.4  823.73  5472.8  824.34  5479.2  823.96  5511.3  824.22
#Mann=5,-1,0
  4393.4    0.05       0  4504.9     0.1       0  5014.4    0.07       0
  5020.4     0.1       0  5331.2    0.05       0
Bank Sta=5014.4,5020.4
Exp/Cntr=0.3,0.1

Type RM Length L Ch R = 1,4362,228,228,228
BEGIN DESCRIPTION:
UNT 088 in HW 9.0
END DESCRIPTION:
XS GIS Cut Line= 3
      2006975.03     13652024.97      2006475.00     13652475.00
      2006280.90     13653060.66
#Sta/Elev= 30
  4294.3  824.39  4315.6  823.76  4421.8  822.36  4521.2  820.44  4542.1  819.78
  4584.7  819.22  4648.2  817.43  4784.0  814.59  4792.1  814.39  4853.8  812.75
  4887.7  810.99  4896.4  810.50  4924.8  810.42  4931.5  809.90  4945.7  809.46
  4995.6  808.84  4996.1  808.04  5001.1  808.04  5001.6  808.84  5014.6  809.86
  5019.8  809.79  5051.5  810.72  5072.4  811.67  5083.2  811.54  5233.7  812.81
  5293.6  813.72  5490.0  819.06  5521.7  819.82  5527.0  819.70  5584.0  821.44
#Mann=7,-1,0
  4294.3    0.05       0  4784.0     0.1       0  4792.1    0.16       0
  4887.7     0.1       0  4995.6    0.07       0  5001.6     0.1       0
  5233.7    0.05       0
Bank Sta=4995.6,5001.6
Exp/Cntr=0.3,0.1

Type RM Length L Ch R = 1,4134,268,268,268
BEGIN DESCRIPTION:
UNT 088 in HW 8.0
END DESCRIPTION:
XS GIS Cut Line= 3
      2007274.98     13651425.02      2006275.00     13652425.00
      2006025.00     13652924.99
#Sta/Elev= 30
  3503.1  848.36  3531.4  846.42  3602.1  843.13  3658.6  840.82  3711.2  839.38
  3757.6  838.39  3785.9  836.78  3828.3  836.61  3909.9  833.98  4040.5  830.17
  4210.2  823.34  4309.2  820.41  4422.3  817.62  4450.6  817.50  4535.5  815.78
  4766.0  810.13  4846.6  808.81  4950.6  808.33  4951.1  807.53  4956.1  807.53
  4956.6  808.33  4964.2  808.41  5043.1  808.98  5065.4  809.54  5079.1  810.32
  5096.2  811.08  5208.0  812.56  5289.0  815.01  5423.2  821.48  5476.3  823.40
#Mann=8,-1,0
  3503.1     0.1       0  3711.2    0.05       0  3909.9     0.1       0
  4766.0    0.16       0  4950.6    0.07       0  4956.6    0.16       0
  4964.2     0.1       0  5079.1    0.05       0
Bank Sta=4950.6,4956.6
Exp/Cntr=0.3,0.1

Type RM Length L Ch R = 1,3866,274,274,274
BEGIN DESCRIPTION:
UNT 088 in HW 7.0
END DESCRIPTION:
XS GIS Cut Line= 3
      2006625.02     13651774.98      2006125.00     13652225.00
      2005825.02     13652674.96
#Sta/Elev= 30
  4217.0  824.82  4450.6  817.57  4514.1  816.31  4592.6  813.65  4656.1  810.85
  4698.7  809.37  4776.5  807.35  4783.2  806.81  4807.7  806.40  4825.8  806.45
  4875.9  805.69  4902.6  805.86  4925.8  806.25  4954.3  805.71  4969.3  806.03
  4972.3  805.57  4972.8  804.77  4977.8  804.77  4978.3  805.57  4990.4  805.59
  5026.4  807.07  5041.4  806.95  5062.5  807.74  5134.6  808.99  5164.6  810.25
  5186.5  811.67  5236.7  813.51  5278.8  815.55  5372.0  819.25  5430.5  820.96
#Mann=6,-1,0
  4217.0     0.1       0  4807.7    0.05       0  4902.6     0.1       0
  4972.3    0.07       0  4978.3     0.1       0  5186.5    0.05       0
Bank Sta=4972.3,4978.3
Exp/Cntr=0.3,0.1

Type RM Length L Ch R = 1,3592,259,259,259
BEGIN DESCRIPTION:
UNT 088 in HW 6.0
END DESCRIPTION:
XS GIS Cut Line= 3
      2006274.97     13651725.04      2006025.00     13652075.00
      2005651.35     13652557.83
#Sta/Elev= 30
  4564.6  818.97  4592.8  818.02  4650.6  817.25  4679.4  816.15  4785.8  810.97
  4872.5  807.95  4901.3  806.51  4936.9  805.67  4969.6  803.78  4970.1  802.98
  4975.1  802.98  4975.6  803.78  5058.0  803.91  5066.2  804.99  5072.5  804.62
  5080.7  806.62  5087.0  806.37  5095.2  808.17  5101.5  807.90  5108.8  809.53
  5136.8  810.42  5159.1  810.29  5165.8  808.68  5172.1  808.66  5180.3  807.01
  5186.6  807.02  5215.6  808.02  5329.7  809.63  5402.2  812.93  5605.2  819.03
#Mann=7,-1,0
  4564.6    0.05       0  4679.4     0.1       0  4872.5    0.05       0
  4969.6   0.033       0  4975.6    0.05       0  5108.8     0.1       0
  5402.2    0.05       0
Bank Sta=4969.6,4975.6
Exp/Cntr=0.3,0.1

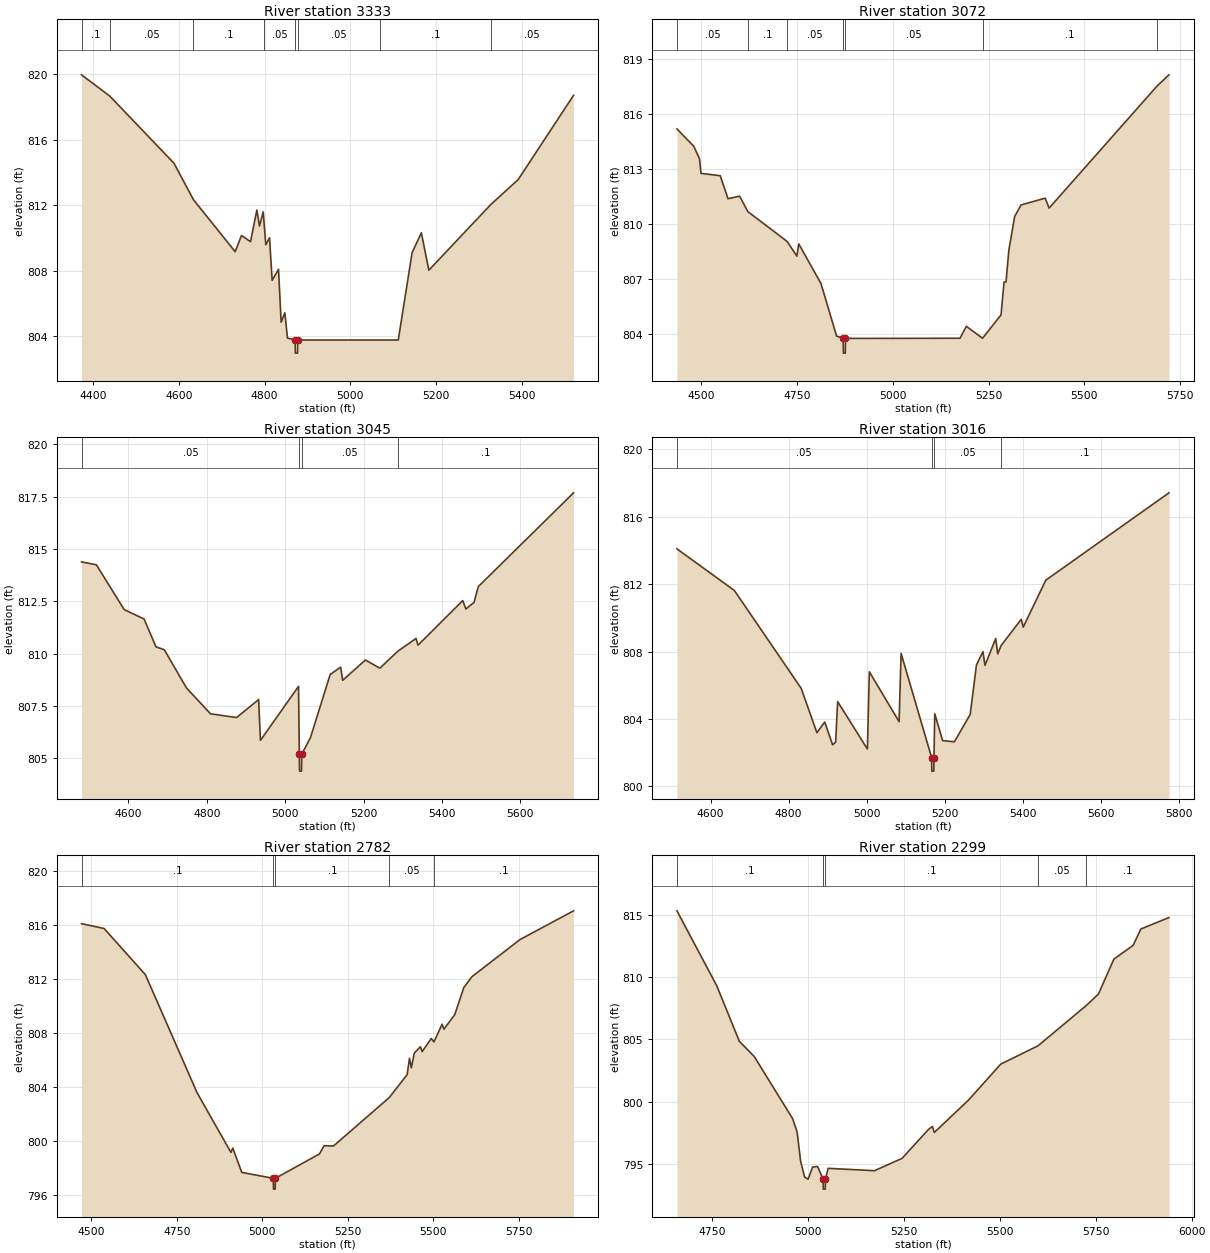
Type RM Length L Ch R = 1,3333,261,261,261
BEGIN DESCRIPTION:
UNT 088 in HW 5.0
END DESCRIPTION:
XS GIS Cut Line= 3
      2006275.03     13651674.98      2005775.00     13652025.00
      2005574.99     13652525.02
#Sta/Elev= 30
  4372.5  819.96  4438.2  818.67  4588.3  814.57  4633.9  812.34  4731.3  809.17
  4746.1  810.16  4767.1  809.78  4781.9  811.71  4788.0  810.73  4796.7  811.60
  4798.8  810.91  4802.8  809.59  4811.5  810.02  4817.6  807.42  4832.5  808.09
  4838.6  804.87  4847.3  805.44  4853.4  803.90  4871.3  803.78  4871.8  802.98
  4876.8  802.98  4877.3  803.78  5069.9  803.78  5112.1  803.78  5144.4  809.11
  5166.0  810.32  5183.5  808.04  5327.9  812.04  5392.1  813.57  5521.4  818.71
#Mann=8,-1,0
  4372.5     0.1       0  4438.2    0.05       0  4633.9     0.1       0
  4798.8    0.05       0  4871.3   0.033       0  4877.3    0.05       0
  5069.9     0.1       0  5327.9    0.05       0
Bank Sta=4871.3,4877.3
Exp/Cntr=0.3,0.1

Type RM Length L Ch R = 1,3072,27,27,27
BEGIN DESCRIPTION:
Mapping XS 34ce99d5
END DESCRIPTION:
XS GIS Cut Line= 6
      2006115.72     13651774.44      2006063.67     13651811.30
      2005377.91     13651904.62      2005347.53     13651950.19
      2005347.53     13651995.77      2005213.59     13652401.91
#Sta/Elev= 30
  4436.7  815.18  4480.7  814.23  4495.5  813.56  4499.4  812.76  4549.7  812.63
  4570.0  811.38  4600.3  811.52  4621.7  810.68  4724.1  809.06  4749.7  808.26
  4754.7  808.92  4812.6  806.77  4853.3  803.91  4870.6  803.78  4871.1  802.98
  4876.1  802.98  4876.6  803.78  5175.6  803.79  5191.9  804.44  5234.3  803.79
  5282.6  805.06  5290.5  806.85  5295.6  806.85  5303.1  808.59  5318.1  810.41
  5334.7  811.04  5397.8  811.41  5408.1  810.87  5690.3  817.52  5721.0  818.12
#Mann=7,-1,0
  4436.7    0.05       0  4621.7     0.1       0  4724.1    0.05       0
  4870.6    0.04       0  4876.6    0.05       0  5234.3     0.1       0
  5690.3    0.05       0
Bank Sta=4870.6,4876.6
Exp/Cntr=0.3,0.1

Type RM Length L Ch R = 1,3045,29,29,29
BEGIN DESCRIPTION:
Mapping XS 46ec8f82
END DESCRIPTION:
XS GIS Cut Line= 6
      2006072.40     13651776.57      2005620.97     13651850.37
      2005395.27     13651872.07      2005334.51     13651902.45
      2005299.79     13651958.87      2005184.76     13652379.89
#Sta/Elev= 30
  4480.7  814.39  4518.6  814.25  4589.5  812.11  4640.2  811.66  4670.6  810.33
  4691.9  810.19  4748.2  808.37  4809.6  807.13  4876.1  806.95  4932.4  807.81
  4937.0  805.86  5034.1  808.44  5036.2  805.19  5036.7  804.39  5041.7  804.39
  5042.2  805.19  5064.7  806.00  5114.9  809.01  5141.6  809.36  5146.7  808.73
  5204.6  809.70  5241.5  809.31  5288.0  810.13  5333.8  810.73  5338.9  810.41
  5452.9  812.54  5460.9  812.14  5481.6  812.45  5492.6  813.21  5735.5  817.69
#Mann=4,-1,0
  4480.7    0.05       0  5036.2    0.04       0  5042.2    0.05       0
  5288.0     0.1       0
Bank Sta=5036.2,5042.2
Exp/Cntr=0.3,0.1

Type RM Length L Ch R = 1,3016,234,234,234
BEGIN DESCRIPTION:
Mapping XS c629043f
END DESCRIPTION:
XS GIS Cut Line= 3
      2006031.11     13651770.07      2005306.30     13651859.05
      2005150.03     13652366.90
#Sta/Elev= 30
  4513.9  814.09  4661.1  811.62  4832.4  805.82  4872.7  803.19  4892.8  803.82
  4913.0  802.47  4920.8  802.63  4925.9  805.03  5002.2  802.22  5007.2  806.80
  5083.5  803.84  5088.6  807.89  5166.9  801.71  5167.4  800.91  5172.4  800.91
  5172.9  801.71  5174.9  804.31  5195.1  802.72  5225.3  802.65  5265.8  804.27
  5281.8  807.20  5298.5  808.00  5303.7  807.18  5331.2  808.77  5336.4  807.86
  5345.2  808.36  5396.6  809.91  5401.8  809.45  5459.6  812.23  5775.5  817.41
#Mann=4,-1,0
  4513.9    0.05       0  5166.9    0.04       0  5172.9    0.05       0
  5345.2     0.1       0
Bank Sta=5166.9,5172.9
Exp/Cntr=0.3,0.1

Type RM Length L Ch R = 1,2782,483,483,483
BEGIN DESCRIPTION:
Mapping XS ada7ec3e
END DESCRIPTION:
XS GIS Cut Line= 4
      2006050.64     13651605.14      2005647.01     13651559.57
      2005358.38     13651655.05      2005130.52     13652347.31
#Sta/Elev= 30
  4471.4  816.11  4537.5  815.75  4658.2  812.33  4809.2  803.59  4908.4  799.16
  4913.7  799.48  4940.1  797.68  5032.3  797.24  5032.8  796.44  5037.8  796.44
  5038.3  797.24  5167.4  799.05  5180.8  799.66  5208.1  799.63  5371.2  803.22
  5423.7  804.92  5430.6  806.14  5435.9  805.43  5444.7  806.52  5462.4  806.99
  5467.7  806.63  5494.2  807.60  5502.2  807.35  5526.0  808.66  5531.2  808.29
  5563.0  809.37  5589.5  811.38  5613.2  812.18  5753.7  814.93  5910.4  817.06
#Mann=5,-1,0
  4471.4     0.1       0  5032.3    0.07       0  5038.3     0.1       0
  5371.2    0.05       0  5502.2     0.1       0
Bank Sta=5032.3,5038.3
Exp/Cntr=0.3,0.1

Type RM Length L Ch R = 1,2299,440,440,440
BEGIN DESCRIPTION:
UNT 088 in HW 4.0
END DESCRIPTION:
XS GIS Cut Line= 3
      2005375.00     13650924.99      2005275.00     13651275.00
      2005170.23     13652187.80
#Sta/Elev= 30
  4658.1  815.32  4762.1  809.29  4820.6  804.85  4859.6  803.62  4959.7  798.63
  4971.4  797.56  4980.5  795.22  4990.9  793.94  5000.0  793.77  5011.7  794.74
  5024.6  794.79  5039.2  793.77  5039.7  792.97  5044.7  792.97  5045.2  793.77
  5052.3  794.64  5173.1  794.45  5245.0  795.44  5314.0  797.77  5324.1  798.00
  5329.1  797.52  5418.2  800.12  5502.3  803.01  5599.4  804.48  5723.5  807.67
  5756.9  808.63  5797.2  811.44  5847.5  812.55  5867.6  813.86  5940.9  814.78
#Mann=5,-1,0
  4658.1     0.1       0  5039.2    0.07       0  5045.2     0.1       0
  5599.4    0.05       0  5723.5     0.1       0
Bank Sta=5039.2,5045.2
Exp/Cntr=0.3,0.1

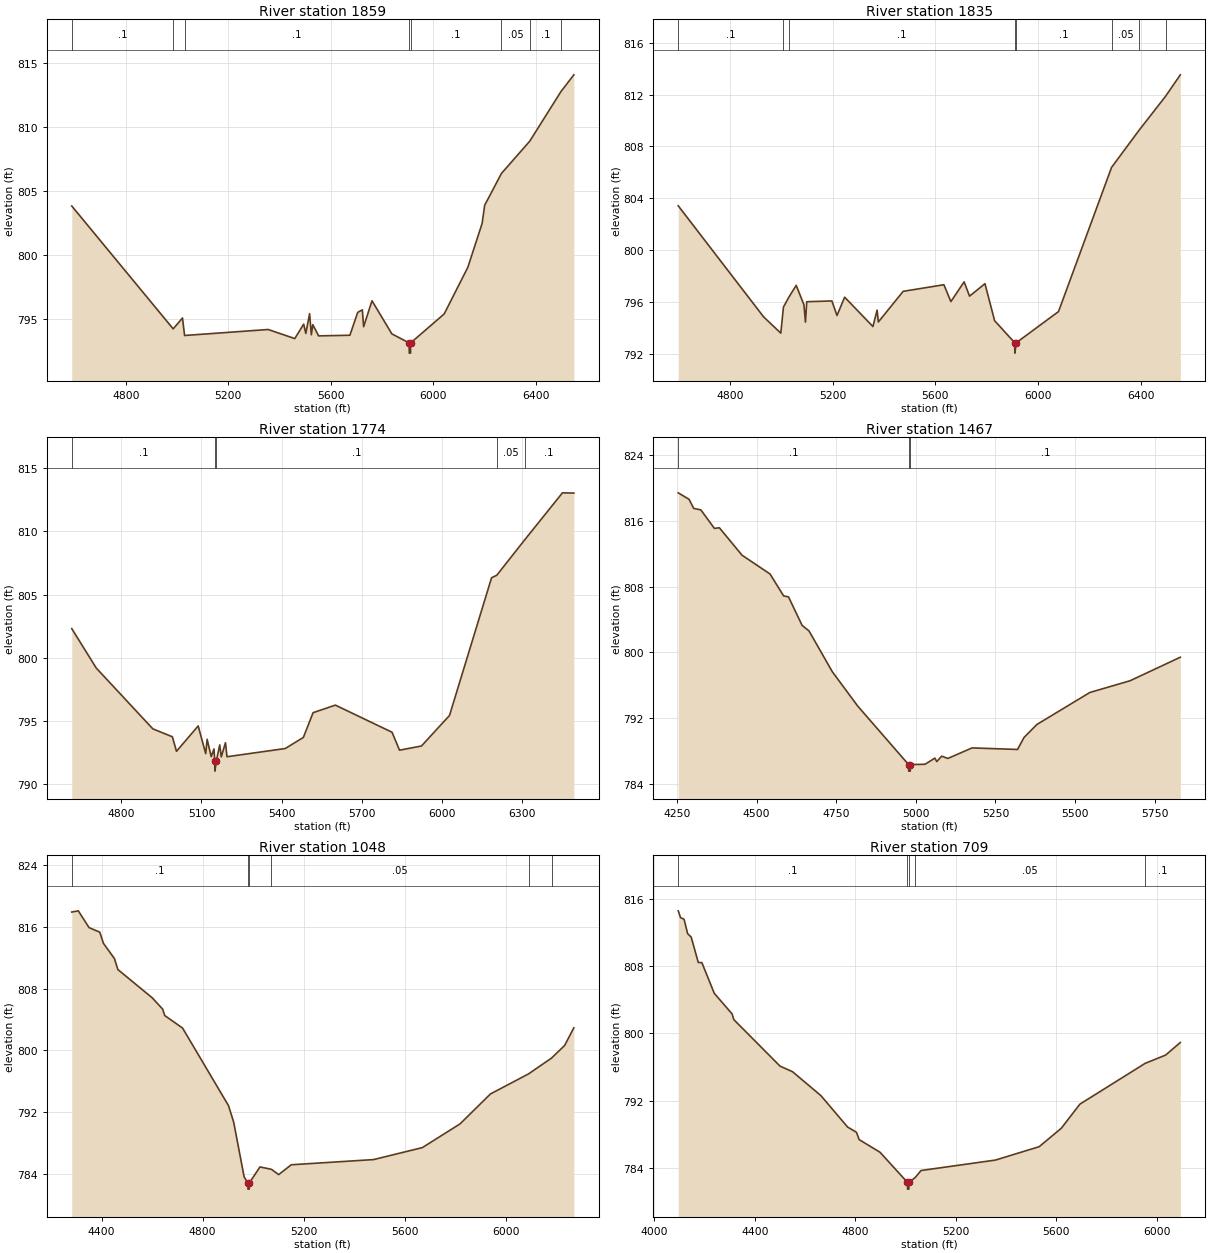
Type RM Length L Ch R = 1,1859,24,24,24
BEGIN DESCRIPTION:
Mapping XS 92bd854c
END DESCRIPTION:
XS GIS Cut Line= 6
      2004996.78     13650953.49      2004869.19     13651406.57
      2004702.52     13651461.26      2004840.54     13651492.51
      2005121.79     13651349.28      2005035.92     13652150.72
#Sta/Elev= 30
  4589.7  803.83  4985.2  794.21  5021.5  795.06  5029.7  793.69  5355.7  794.16
  5459.4  793.45  5494.2  794.58  5502.5  793.85  5517.2  795.40  5524.1  793.75
  5529.8  794.54  5552.4  793.66  5674.4  793.71  5704.9  795.50  5722.9  795.70
  5728.0  794.38  5760.6  796.41  5838.0  793.82  5905.4  793.11  5905.9  792.31
  5910.9  792.31  5911.4  793.11  6042.2  795.38  6134.4  799.03  6190.0  802.46
  6200.1  803.89  6265.5  806.38  6376.0  808.91  6497.2  812.78  6547.8  814.10
#Mann=8,-1,0
  4589.7     0.1       0  4985.2    0.07       0  5029.7     0.1       0
  5905.4    0.07       0  5911.4     0.1       0  6265.5    0.05       0
  6376.0     0.1       0  6497.2    0.05       0
Bank Sta=5905.4,5911.4
Exp/Cntr=0.3,0.1

Type RM Length L Ch R = 1,1835,61,61,61
BEGIN DESCRIPTION:
Mapping XS 679faa56
END DESCRIPTION:
XS GIS Cut Line= 6
      2004970.76     13650943.00      2004861.37     13651362.30
      2004676.48     13651432.61      2004827.52     13651523.76
      2005095.75     13651377.93      2005002.06     13652140.47
#Sta/Elev= 30
  4598.3  803.43  4931.1  794.87  4997.9  793.62  5008.3  795.63  5029.6  796.40
  5058.0  797.30  5088.0  795.81  5094.0  794.47  5099.0  796.04  5196.9  796.10
  5216.9  794.98  5246.7  796.39  5356.9  794.13  5373.1  795.39  5378.0  794.48
  5474.7  796.84  5633.4  797.35  5660.6  796.05  5712.2  797.57  5733.3  796.47
  5793.4  797.43  5831.0  794.58  5909.3  792.88  5909.8  792.08  5915.3  792.88
  6079.9  795.28  6286.7  806.39  6394.6  809.27  6496.8  811.86  6554.5  813.52
#Mann=8,-1,0
  4598.3     0.1       0  5008.3    0.07       0  5029.6     0.1       0
  5909.3    0.07       0  5915.3     0.1       0  6286.7    0.05       0
  6394.6     0.1       0  6496.8    0.05       0
Bank Sta=5909.3,5915.3
Exp/Cntr=0.3,0.1

Type RM Length L Ch R = 1,1774,307,307,307
BEGIN DESCRIPTION:
Mapping XS 5ad1c7e7
END DESCRIPTION:
XS GIS Cut Line= 6
      2004936.90     13650948.23      2004806.69     13651328.45
      2004640.02     13651427.41      2004806.69     13651565.43
      2005059.29     13651445.63      2004923.87     13652167.00
#Sta/Elev= 30
  4614.1  802.30  4705.8  799.18  4917.8  794.36  4991.2  793.73  5006.4  792.58
  5087.8  794.59  5116.0  792.40  5121.3  793.53  5136.6  792.16  5147.0  792.77
  5149.8  791.81  5150.3  791.01  5155.8  791.81  5168.5  793.09  5174.3  792.14
  5190.0  793.26  5195.8  792.15  5413.9  792.80  5481.9  793.68  5518.3  795.64
  5601.7  796.24  5814.3  794.09  5842.2  792.67  5924.4  793.00  6029.5  795.42
  6187.1  806.33  6206.7  806.53  6310.7  809.32  6452.7  813.06  6495.4  813.04
#Mann=5,-1,0
  4614.1     0.1       0  5149.8    0.07       0  5155.8     0.1       0
  6206.7    0.05       0  6310.7     0.1       0
Bank Sta=5149.8,5155.8
Exp/Cntr=0.3,0.1

Type RM Length L Ch R = 1,1467,419,419,419
BEGIN DESCRIPTION:
Mapping XS e411388f
END DESCRIPTION:
XS GIS Cut Line= 3
      2004969.22     13650503.39      2004530.86     13651228.19
      2004431.24     13651951.51
#Sta/Elev= 30
  4253.7  819.38  4287.8  818.59  4302.3  817.49  4324.7  817.31  4367.4  815.06
  4382.9  815.14  4454.3  811.80  4542.0  809.53  4584.7  806.87  4600.2  806.74
  4642.9  803.28  4664.6  802.61  4737.9  797.65  4817.5  793.49  4977.2  786.39
  4977.7  785.59  4982.7  785.59  4983.2  786.39  5028.9  786.42  5059.9  787.17
  5065.8  786.75  5081.3  787.41  5100.7  787.13  5176.8  788.41  5319.6  788.22
  5339.8  789.67  5380.2  791.25  5546.8  795.14  5672.9  796.56  5830.9  799.42
#Mann=3,-1,0
  4253.7     0.1       0  4977.2    0.07       0  4983.2     0.1       0
Bank Sta=4977.2,4983.2
Exp/Cntr=0.3,0.1

Type RM Length L Ch R = 1,1048,339,339,339
BEGIN DESCRIPTION:
Mapping XS 01a61851
END DESCRIPTION:
XS GIS Cut Line= 4
      2004839.03     13650373.14      2004352.91     13650750.76
      2004144.58     13651510.30      2004300.42     13652073.07
#Sta/Elev= 30
  4282.0  817.90  4307.8  818.06  4350.4  815.89  4392.9  815.30  4407.3  813.86
  4450.8  811.89  4464.4  810.47  4600.1  806.82  4641.7  805.35  4649.9  804.52
  4720.5  802.90  4902.3  792.87  4922.7  790.75  4964.2  783.65  4978.9  782.87
  4979.4  782.07  4984.4  782.07  4984.9  782.87  5026.8  784.94  5072.3  784.63
  5100.9  783.95  5150.8  785.22  5476.5  785.89  5669.6  787.44  5818.8  790.51
  5939.1  794.38  6089.7  796.97  6180.9  799.02  6232.4  800.64  6269.1  802.93
#Mann=6,-1,0
  4282.0     0.1       0  4978.9    0.07       0  4984.9     0.1       0
  5072.3    0.05       0  6089.7     0.1       0  6180.9    0.05       0
Bank Sta=4978.9,4984.9
Exp/Cntr=0.3,0.1

Type RM Length L Ch R = 1,709,415,415,415
BEGIN DESCRIPTION:
Mapping XS 8cde3645
END DESCRIPTION:
XS GIS Cut Line= 4
      2004591.62     13650238.61      2004088.15     13650755.10
      2003949.27     13651427.84      2004105.53     13651996.45
#Sta/Elev= 30
  4095.5  814.56  4104.6  813.76  4118.8  813.55  4132.9  811.85  4147.1  811.44
  4175.3  808.43  4189.5  808.41  4239.1  804.76  4309.8  802.32  4316.8  801.64
  4500.7  796.12  4550.3  795.46  4663.3  792.62  4769.5  788.89  4804.7  788.27
  4815.5  787.40  4898.4  785.90  5007.7  782.32  5008.2  781.52  5013.2  781.52
  5013.7  782.32  5037.9  782.88  5061.7  783.73  5357.9  784.97  5531.9  786.56
  5619.9  788.75  5693.9  791.61  5954.0  796.46  6034.8  797.43  6093.4  798.93
#Mann=5,-1,0
  4095.5     0.1       0  5007.7    0.07       0  5013.7     0.1       0
  5037.9    0.05       0  5954.0     0.1       0
Bank Sta=5007.7,5013.7
Exp/Cntr=0.3,0.1

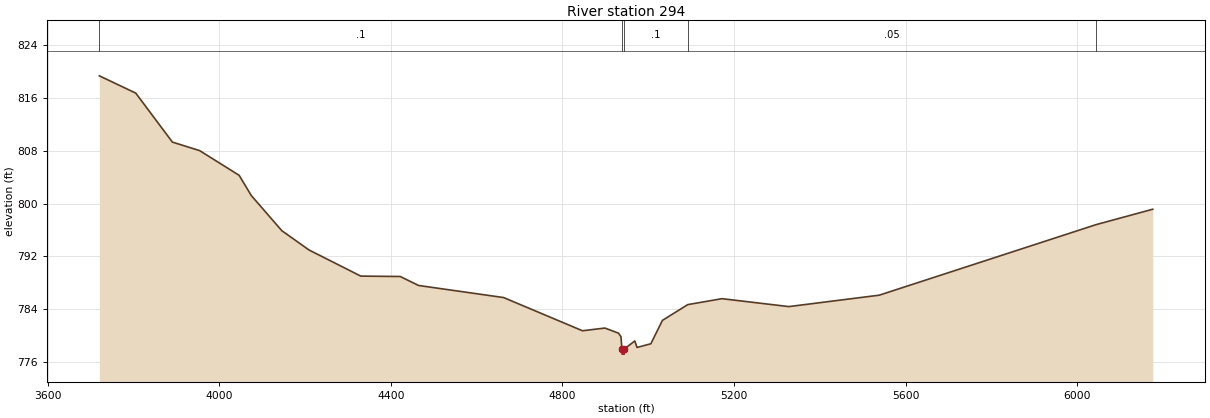
Type RM Length L Ch R = 1,294,0,0,0
BEGIN DESCRIPTION:
UNT 088 in HW 1.0
END DESCRIPTION:
XS GIS Cut Line= 4
      2004575.03     13649924.97      2003740.93     13650663.95
      2003645.45     13650963.43      2003922.81     13651951.54
#Sta/Elev= 30
  3720.6  819.37  3805.5  816.75  3890.9  809.33  3954.4  808.04  4046.4  804.30
  4074.8  801.23  4145.9  795.91  4209.5  792.98  4329.9  789.03  4421.9  788.97
  4464.6  787.61  4662.8  785.78  4846.6  780.75  4898.8  781.16  4930.5  780.39
  4936.3  779.84  4938.5  778.01  4939.0  777.21  4944.0  777.21  4944.5  778.01
  4968.5  779.21  4973.7  778.22  5005.9  778.78  5032.9  782.32  5091.9  784.71
  5171.7  785.61  5327.5  784.41  5538.3  786.14  6043.7  796.83  6175.6  799.16
#Mann=5,-1,0
  3720.6     0.1       0  4938.5    0.07       0  4944.5     0.1       0
  5091.9    0.05       0  6043.7     0.1       0
Bank Sta=4938.5,4944.5
Exp/Cntr=0.3,0.1

Chan Stop Cuts=-1