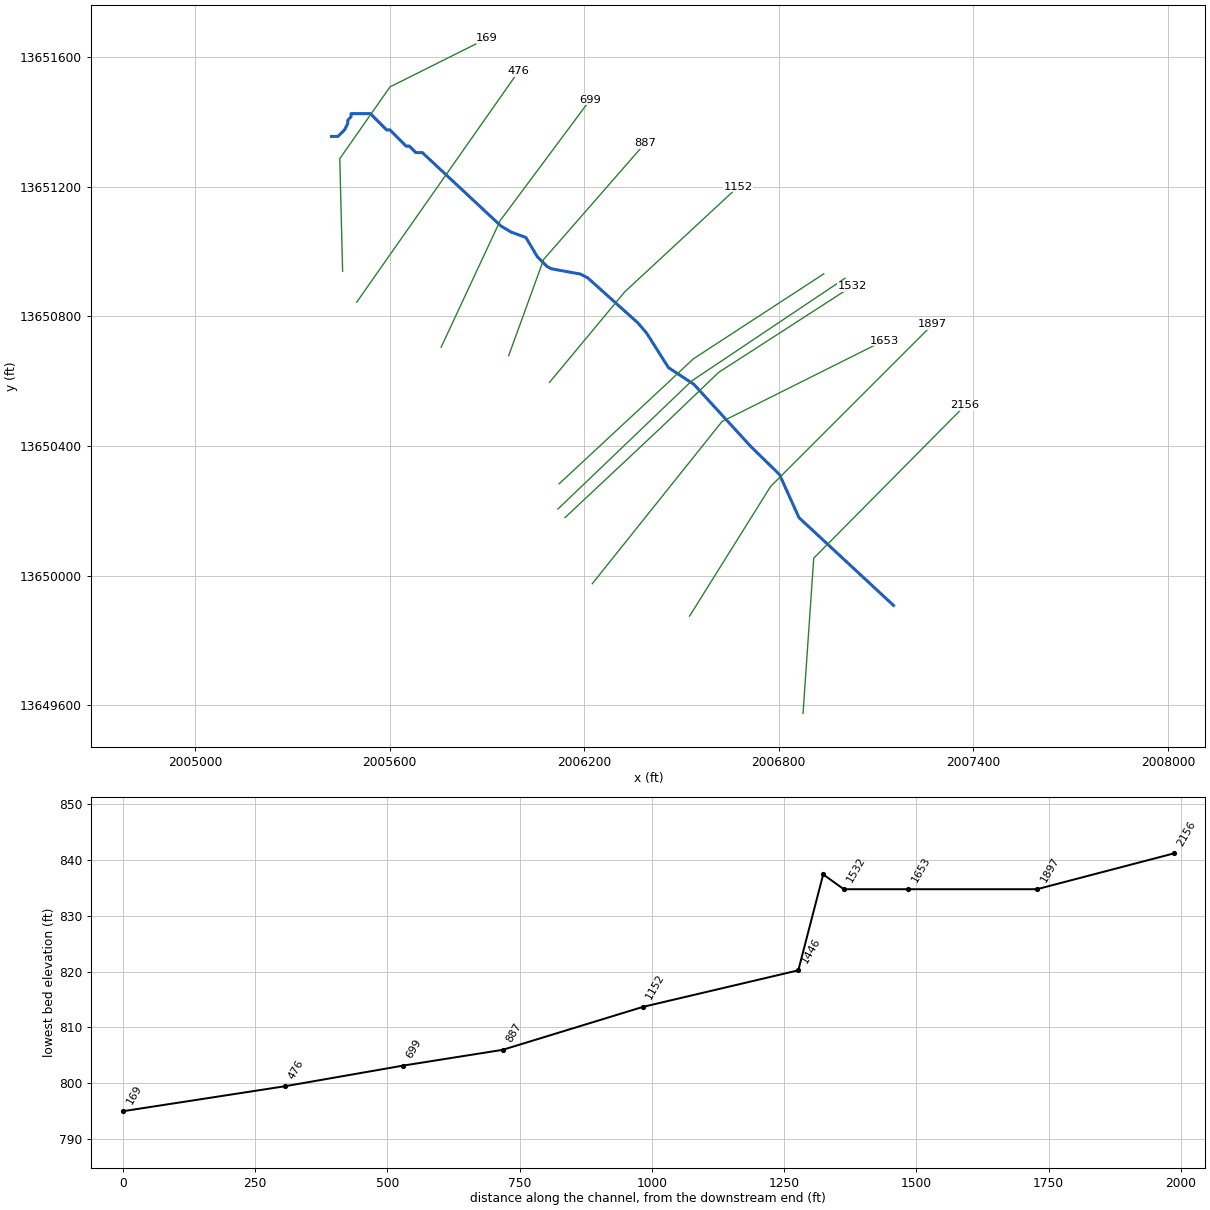
--- UNT 090 in HW.prj (project) ---

Proj Title=UNT 090 in HW Base Level Engineering
Current Plan=p01
Default Exp/Contr=0.3,0.1
English Units
Geom File=g01
Flow File=f01
Plan File=p01
BEGIN DESCRIPTION:
UNT 090 in HW
END DESCRIPTION:

--- UNT 090 in HW.p01 (plan) ---

Plan Title=Multiple Run
Short Identifier=Multiple
Geom File=g01
Flow File=f01
Subcritical Flow
K Sum by GR= 0
Std Step Tol= 0.01
Critical Tol= 0.01
Num of Std Step Trials= 20
Max Error Tol= 0.3
Flow Tol Ratio= 0.001
Split Flow NTrial= 30
Split Flow Tol= 0.02
Split Flow Ratio= 0.02
Log Output Level= 0
Friction Slope Method= 1
Unsteady Friction Slope Method= 2
Unsteady Bridges Friction Slope Method= 1
Parabolic Critical Depth
Global Vel Dist=  1 , 1 , 1
Global Log Level= 0
CheckData=True
Encroach Param= -1, 0, 0, 0
BEGIN DESCRIPTION:
Multiple Run
END DESCRIPTION:

--- UNT 090 in HW.f01 (steady flow) ---

Flow Title=Multiple
Number of Profiles=7
Profile Names=10-year,25-year,50-year,1pct_min,100-year,1pct_plu,500-year
River Rch & RM= UNT 090 in HW,Reach-1,2156
     168     218     257     151     302     602     415
Boundary for River Rch & Prof#=UNT 090 in HW,Reach-1,1
Up Type=0
Dn Type=3
Dn Slope=0.005
Boundary for River Rch & Prof#=UNT 090 in HW,Reach-1,2
Up Type=0
Dn Type=3
Dn Slope=0.005
Boundary for River Rch & Prof#=UNT 090 in HW,Reach-1,3
Up Type=0
Dn Type=3
Dn Slope=0.005
Boundary for River Rch & Prof#=UNT 090 in HW,Reach-1,4
Up Type=0
Dn Type=3
Dn Slope=0.005
Boundary for River Rch & Prof#=UNT 090 in HW,Reach-1,5
Up Type=0
Dn Type=3
Dn Slope=0.005
Boundary for River Rch & Prof#=UNT 090 in HW,Reach-1,6
Up Type=0
Dn Type=3
Dn Slope=0.005
Boundary for River Rch & Prof#=UNT 090 in HW,Reach-1,7
Up Type=0
Dn Type=3
Dn Slope=0.005

--- UNT 090 in HW.g01 (geometry) ---

Geom Title=Existing Conditions

River Reach=UNT 090 in HW,Reach-1
Reach XY= 30
      2007153.95     13649908.09      2006862.29     13650178.92
      2006802.39     13650311.74      2006714.23     13650397.74
      2006538.45     13650589.80      2006459.76     13650641.53
      2006393.10     13650747.09      2006365.32     13650779.73
      2006210.46     13650918.62      2006188.93     13650929.73
      2006098.65     13650946.39      2006084.76     13650954.03
      2006055.60     13650983.20      2006020.07     13651042.78
      2005974.35     13651059.59      2005943.10     13651078.34
      2005700.80     13651304.54      2005680.80     13651304.54
      2005660.80     13651324.54      2005650.80     13651324.54
      2005600.80     13651374.54      2005590.80     13651374.54
      2005540.80     13651424.54      2005480.80     13651424.54
      2005480.80     13651414.54      2005470.80     13651404.54
      2005470.80     13651394.54      2005460.80     13651374.54
      2005440.80     13651354.54      2005420.80     13651354.54

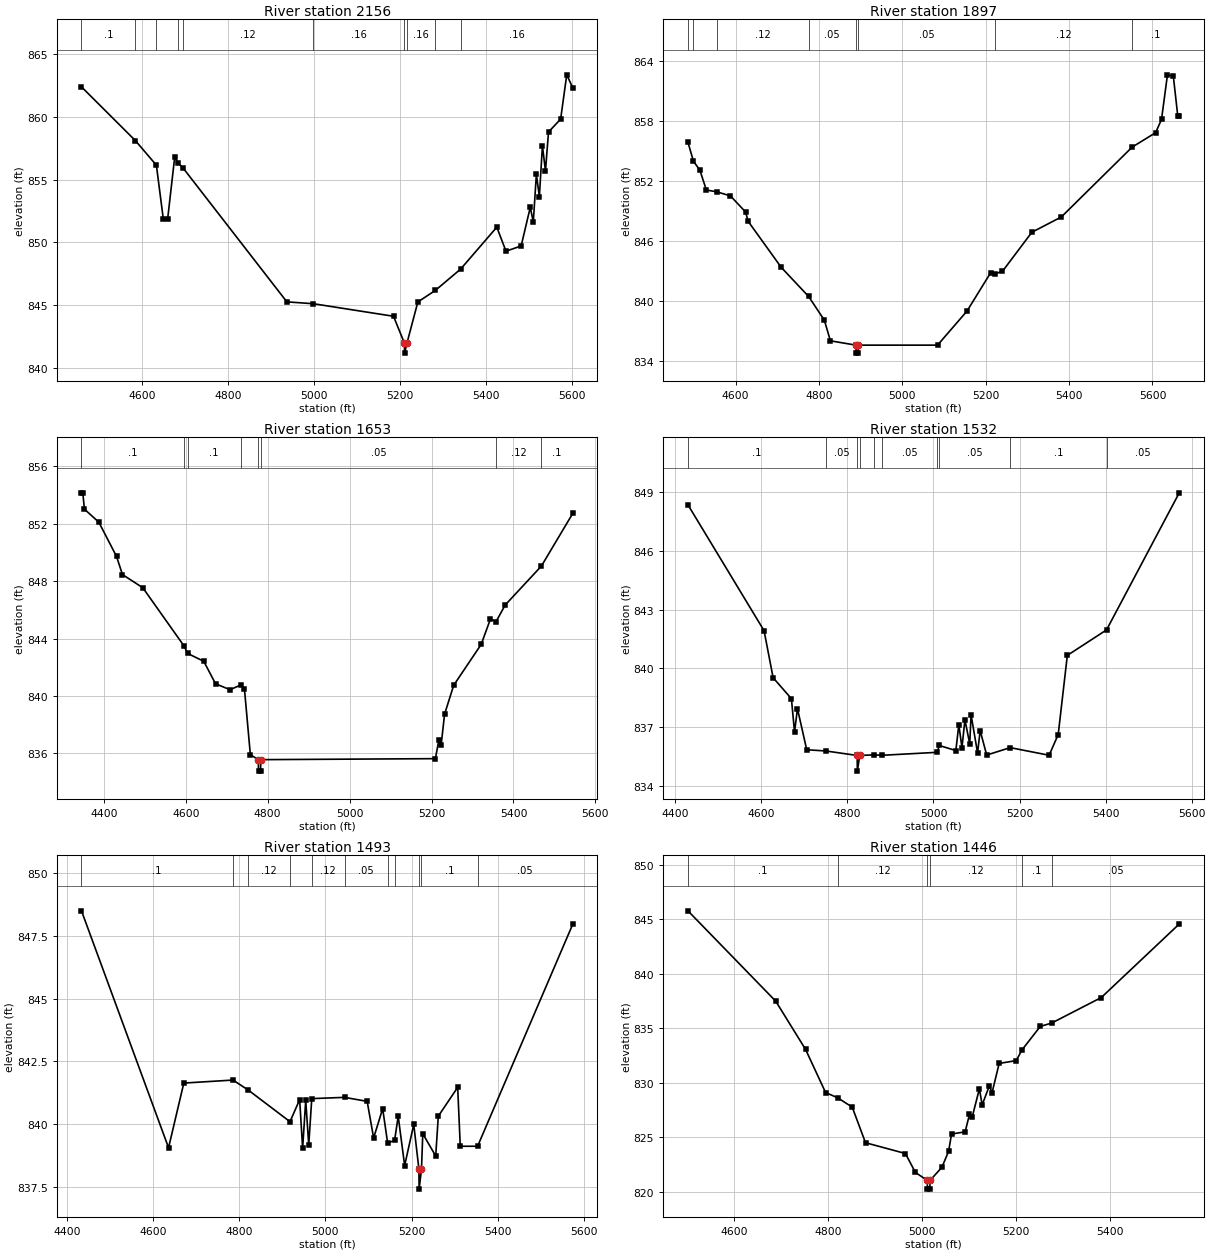
Type RM Length L Ch R = 1,2156,259,259,259
BEGIN DESCRIPTION:
UNT 090 in HW 8.0
END DESCRIPTION:
XS GIS Cut Line= 3
      2006875.00     13649575.05      2006907.94     13650053.66
      2007375.00     13650525.00
#Sta/Elev= 30
  4459.5  862.40  4585.0  858.11  4633.8  856.15  4649.9  851.86  4659.9  851.83
  4676.4  856.79  4683.9  856.34  4696.3  855.91  4937.4  845.25  4999.3  845.10
  5185.6  844.10  5210.9  841.96  5211.4  841.16  5216.9  841.96  5242.2  845.24
  5282.8  846.16  5341.7  847.86  5426.0  851.21  5447.3  849.29  5482.6  849.71
  5503.8  852.79  5510.9  851.63  5518.0  855.41  5525.0  853.65  5532.1  857.69
  5539.2  855.70  5546.3  858.80  5574.5  859.83  5588.7  863.36  5602.8  862.32
#Mann=10,-1,0
  4459.5     0.1       0  4585.0    0.16       0  4633.8     0.1       0
  4683.9    0.16       0  4696.3    0.12       0  4999.3    0.16       0
  5210.9    0.07       0  5216.9    0.16       0  5282.8    0.12       0
  5341.7    0.16       0
Bank Sta=5210.9,5216.9
Exp/Cntr=0.3,0.1

Type RM Length L Ch R = 1,1897,244,244,244
BEGIN DESCRIPTION:
UNT 090 in HW 7.0
END DESCRIPTION:
XS GIS Cut Line= 3
      2006525.02     13649875.04      2006775.00     13650275.00
      2007275.03     13650775.03
#Sta/Elev= 30
  4485.5  855.87  4498.7  853.97  4514.3  853.05  4529.7  851.08  4555.4  850.89
  4587.5  850.49  4624.0  848.87  4629.9  847.95  4709.5  843.33  4775.1  840.42
  4812.7  838.06  4827.4  835.98  4888.7  835.55  4889.2  834.75  4894.2  834.75
  4894.7  835.55  5084.4  835.55  5155.1  838.96  5211.7  842.79  5223.1  842.71
  5240.0  842.93  5310.7  846.85  5381.4  848.38  5551.2  855.37  5607.7  856.82
  5621.8  858.15  5636.0  862.61  5650.1  862.48  5660.7  858.52  5664.3  858.52
#Mann=8,-1,0
  4485.5     0.1       0  4498.7    0.16       0  4555.4    0.12       0
  4775.1    0.05       0  4888.7   0.033       0  4894.7    0.05       0
  5223.1    0.12       0  5551.2     0.1       0
Bank Sta=4888.7,4894.7
Exp/Cntr=0.3,0.1

Type RM Length L Ch R = 1,1653,121,121,121
BEGIN DESCRIPTION:
UNT 090 in HW 6.0
END DESCRIPTION:
XS GIS Cut Line= 3
      2006225.01     13649975.02      2006625.00     13650475.00
      2007124.99     13650725.00
#Sta/Elev= 30
  4345.5  854.16  4348.7  854.16  4352.7  853.02  4387.9  852.11  4431.1  849.72
  4445.5  848.46  4495.2  847.54  4596.3  843.46  4604.4  842.96  4644.0  842.41
  4672.8  840.84  4708.1  840.43  4733.8  840.75  4743.3  840.48  4757.7  835.90
  4777.1  835.55  4777.6  834.75  4782.6  834.75  4783.1  835.55  5209.4  835.62
  5217.8  836.91  5223.4  836.57  5231.8  838.72  5254.1  840.74  5321.2  843.59
  5343.6  845.35  5357.5  845.18  5379.9  846.34  5468.1  849.05  5544.8  852.73
#Mann=8,-1,0
  4345.5     0.1       0  4596.3    0.12       0  4604.4     0.1       0
  4733.8    0.05       0  4777.1   0.033       0  4783.1    0.05       0
  5357.5    0.12       0  5468.1     0.1       0
Bank Sta=4777.1,4783.1
Exp/Cntr=0.3,0.1

Type RM Length L Ch R = 1,1532,39,39,39
BEGIN DESCRIPTION:
Mapping XS abc06da5
END DESCRIPTION:
XS GIS Cut Line= 4
      2006140.94     13650178.94      2006432.60     13650452.36
      2006614.89     13650626.84      2007026.38     13650892.49
#Sta/Elev= 30
  4429.3  848.35  4606.3  841.92  4627.3  839.52  4669.8  838.45  4677.1  836.75
  4683.9  837.94  4705.4  835.84  4749.6  835.78  4822.6  835.55  4823.1  834.75
  4828.6  835.55  4861.6  835.58  4881.1  835.56  5008.9  835.71  5013.4  836.06
  5052.0  835.80  5058.9  837.12  5066.2  835.95  5073.1  837.37  5084.3  836.14
  5087.4  837.62  5102.5  835.68  5108.5  836.82  5123.7  835.57  5178.3  835.95
  5268.8  835.56  5289.9  836.62  5311.1  840.66  5402.2  841.96  5571.2  848.96
#Mann=10,-1,0
  4429.3     0.1       0  4749.6    0.05       0  4822.6   0.035       0
  4828.6    0.05       0  4861.6    0.12       0  4881.1    0.05       0
  5008.9    0.12       0  5013.4    0.05       0  5178.3     0.1       0
  5402.2    0.05       0
Bank Sta=4822.6,4828.6
Exp/Cntr=0.3,0.1

Type RM Length L Ch R = 1,1493,47,47,47
BEGIN DESCRIPTION:
UNT 090 in HW 5.0
END DESCRIPTION:
XS GIS Cut Line= 3
      2006119.02     13650205.19      2006531.34     13650600.15
      2007004.47     13650917.02
#Sta/Elev= 30
  4433.9  848.50  4636.0  839.05  4671.4  841.63  4785.6  841.75  4821.1  841.35
  4917.9  840.09  4940.3  840.97  4947.2  839.03  4954.4  840.94  4961.4  839.16
  4968.4  841.01  5044.6  841.06  5097.0  840.90  5112.0  839.44  5133.0  840.61
  5144.5  839.24  5160.7  839.34  5169.0  840.31  5184.0  838.34  5205.1  839.98
  5217.1  838.20  5217.6  837.40  5223.1  838.20  5226.1  839.61  5256.1  838.72
  5262.1  840.31  5307.1  841.46  5313.1  839.11  5353.3  839.11  5574.3  847.97
#Mann=11,-1,0
  4433.9     0.1       0  4785.6    0.05       0  4821.1    0.12       0
  4917.9    0.05       0  4968.4    0.12       0  5044.6    0.05       0
  5144.5    0.12       0  5160.7     0.1       0  5217.1    0.07       0
  5223.1     0.1       0  5353.3    0.05       0
Bank Sta=5217.1,5223.1
Exp/Cntr=0.3,0.1

Type RM Length L Ch R = 1,1446,294,294,294
BEGIN DESCRIPTION:
Mapping XS 781d91af
END DESCRIPTION:
XS GIS Cut Line= 4
      2006122.68     13650283.07      2006416.97     13650556.53
      2006536.77     13650668.51      2006938.99     13650930.61
#Sta/Elev= 30
  4501.0  845.78  4688.0  837.48  4751.5  833.05  4794.0  829.10  4819.5  828.62
  4850.7  827.76  4879.0  824.49  4964.0  823.50  4985.0  821.77  5010.4  821.03
  5010.9  820.23  5015.9  820.23  5016.4  821.03  5041.7  822.24  5055.9  823.71
  5062.1  825.29  5091.1  825.49  5100.3  827.09  5106.2  826.86  5121.4  829.44
  5127.3  827.96  5142.5  829.70  5148.4  829.09  5163.5  831.77  5199.8  832.03
  5212.4  833.03  5251.1  835.17  5275.4  835.48  5380.9  837.82  5546.8  844.57
#Mann=6,-1,0
  4501.0     0.1       0  4819.5    0.12       0  5010.4    0.07       0
  5016.4    0.12       0  5212.4     0.1       0  5275.4    0.05       0
Bank Sta=5010.4,5016.4
Exp/Cntr=0.3,0.1

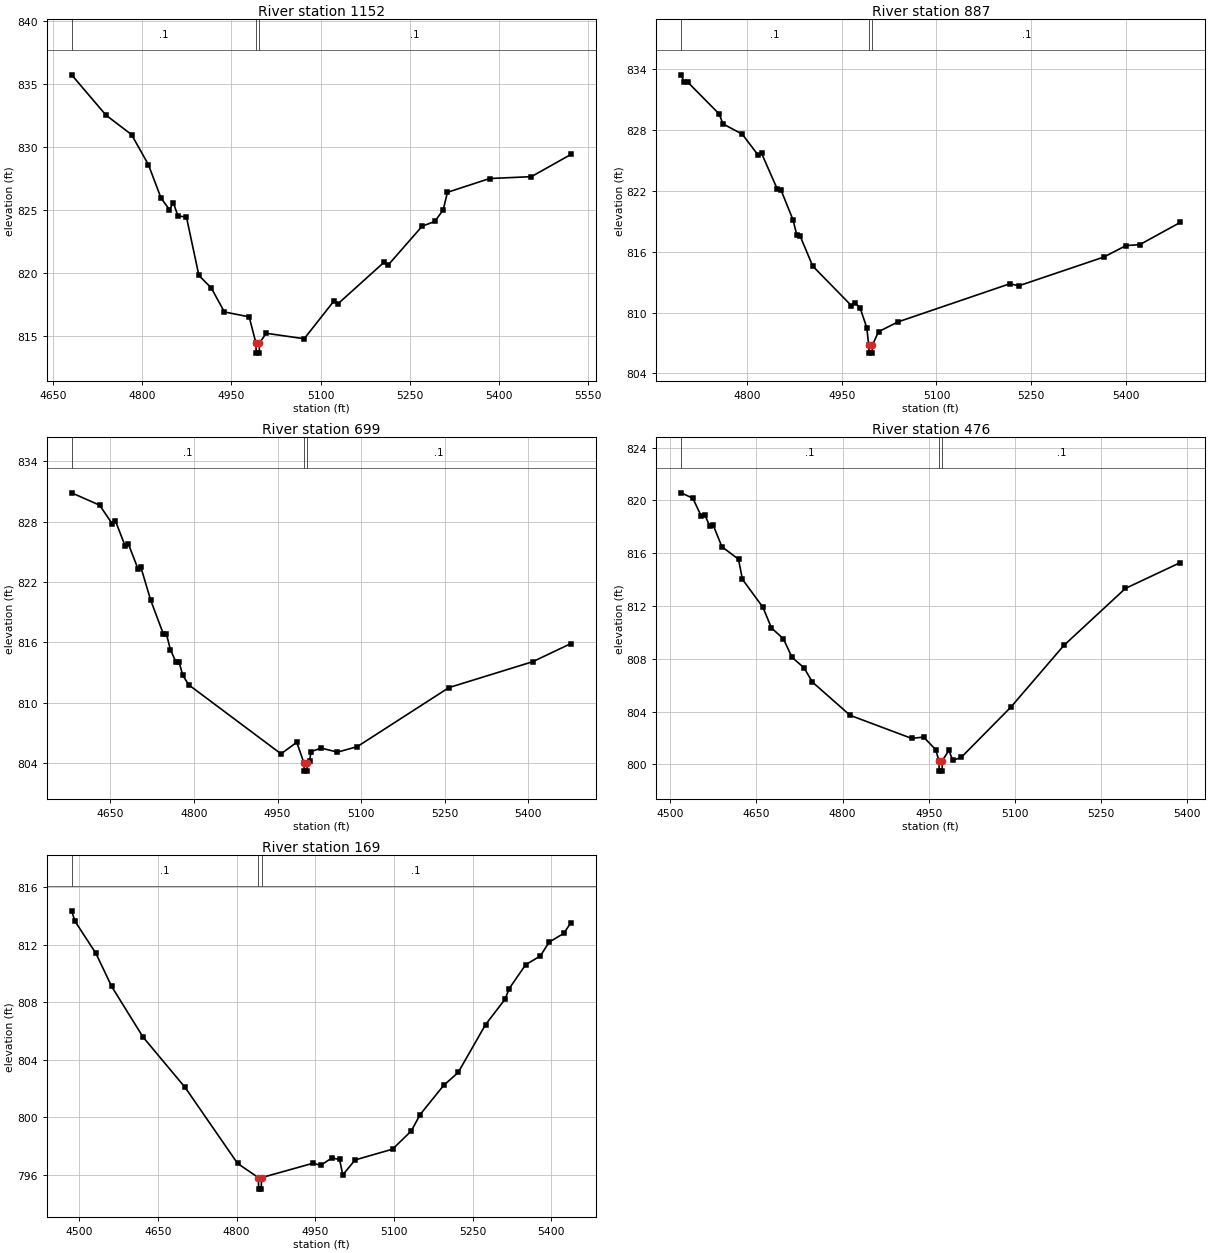
Type RM Length L Ch R = 1,1152,265,265,265
BEGIN DESCRIPTION:
UNT 090 in HW 4.0
END DESCRIPTION:
XS GIS Cut Line= 3
      2006092.97     13650595.80      2006325.00     13650875.00
      2006674.54     13651199.08
#Sta/Elev= 30
  4681.3  835.71  4739.0  832.52  4782.0  830.98  4810.3  828.61  4831.5  825.97
  4845.8  825.03  4852.3  825.59  4860.1  824.54  4874.4  824.45  4895.3  819.83
  4916.1  818.84  4938.2  816.94  4979.9  816.55  4991.2  814.48  4991.7  813.68
  4996.7  813.68  4997.2  814.48  5008.5  815.25  5072.4  814.82  5122.3  817.80
  5129.1  817.58  5207.3  820.90  5214.1  820.68  5270.8  823.73  5291.8  824.10
  5306.0  825.00  5313.3  826.41  5384.2  827.50  5454.5  827.65  5521.0  829.41
#Mann=3,-1,0
  4681.3     0.1       0  4991.2    0.07       0  4997.2     0.1       0
Bank Sta=4991.2,4997.2
Exp/Cntr=0.3,0.1

Type RM Length L Ch R = 1,887,188,188,188
BEGIN DESCRIPTION:
UNT 090 in HW 3.0
END DESCRIPTION:
XS GIS Cut Line= 3
      2005967.10     13650678.27      2006075.00     13650975.00
      2006388.08     13651333.62
#Sta/Elev= 30
  4695.1  833.40  4700.3  832.65  4705.6  832.68  4755.5  829.54  4761.4  828.57
  4792.0  827.56  4817.3  825.49  4822.6  825.68  4847.9  822.11  4853.2  822.10
  4872.5  819.13  4878.5  817.64  4883.8  817.53  4903.8  814.57  4965.0  810.68
  4970.3  810.98  4978.9  810.46  4989.6  808.48  4992.5  806.80  4993.0  806.00
  4998.0  806.00  4998.5  806.80  5008.2  808.11  5038.8  809.07  5216.4  812.83
  5230.6  812.63  5365.4  815.46  5400.5  816.59  5422.4  816.68  5486.9  818.88
#Mann=3,-1,0
  4695.1     0.1       0  4992.5    0.07       0  4998.5     0.1       0
Bank Sta=4992.5,4998.5
Exp/Cntr=0.3,0.1

Type RM Length L Ch R = 1,699,223,223,223
BEGIN DESCRIPTION:
UNT 090 in HW 2.0
END DESCRIPTION:
XS GIS Cut Line= 3
      2005758.76     13650704.30      2005941.06     13651094.94
      2006218.86     13651468.23
#Sta/Elev= 30
  4580.4  830.86  4630.7  829.63  4653.6  827.75  4659.1  828.06  4676.4  825.58
  4682.0  825.81  4699.3  823.33  4704.8  823.45  4722.2  820.20  4745.0  816.83
  4750.5  816.82  4757.7  815.27  4767.9  814.00  4773.4  814.02  4779.8  812.72
  4790.7  811.76  4956.3  804.90  4984.6  806.05  4997.5  803.98  4998.0  803.18
  5003.0  803.18  5003.5  803.98  5007.5  804.19  5010.2  805.12  5028.4  805.47
  5057.6  805.07  5093.0  805.61  5257.8  811.49  5408.0  814.06  5476.8  815.87
#Mann=3,-1,0
  4580.4     0.1       0  4997.5    0.07       0  5003.5     0.1       0
Bank Sta=4997.5,5003.5
Exp/Cntr=0.3,0.1

Type RM Length L Ch R = 1,476,307,307,307
BEGIN DESCRIPTION:
Mapping XS e7e7b93d
END DESCRIPTION:
XS GIS Cut Line= 2
      2005498.37     13650843.23      2005997.46     13651554.98
#Sta/Elev= 30
  4518.9  820.57  4539.3  820.16  4554.1  818.79  4560.2  818.89  4568.9  818.04
  4575.0  818.10  4589.8  816.49  4618.8  815.54  4625.6  814.02  4661.3  811.90
  4676.1  810.34  4697.0  809.51  4711.9  808.11  4732.8  807.32  4747.6  806.23
  4813.0  803.72  4920.2  801.97  4941.1  802.07  4962.0  801.12  4967.7  800.29
  4968.2  799.49  4973.2  799.49  4973.7  800.29  4985.2  801.07  4991.7  800.30
  5006.5  800.53  5092.8  804.33  5185.2  809.01  5292.4  813.33  5388.2  815.29
#Mann=3,-1,0
  4518.9     0.1       0  4967.7    0.07       0  4973.7     0.1       0
Bank Sta=4967.7,4973.7
Exp/Cntr=0.3,0.1

Type RM Length L Ch R = 1,169,0,0,0
BEGIN DESCRIPTION:
UNT 090 in HW 1.0
END DESCRIPTION:
XS GIS Cut Line= 4
      2005454.95     13650938.73      2005446.27     13651285.91
      2005601.22     13651507.29      2005900.58     13651656.97
#Sta/Elev= 30
  4485.3  814.37  4491.6  813.65  4531.6  811.41  4561.6  809.11  4621.6  805.58
  4701.6  802.09  4801.7  796.80  4841.4  795.81  4841.9  795.01  4846.9  795.01
  4847.4  795.81  4945.6  796.81  4960.4  796.67  4981.3  797.17  4996.2  797.08
  5002.4  796.00  5025.8  797.04  5097.3  797.79  5133.1  799.06  5149.9  800.20
  5194.6  802.22  5222.5  803.13  5274.7  806.46  5312.0  808.23  5319.5  808.95
  5351.1  810.62  5379.1  811.23  5395.8  812.19  5423.8  812.80  5437.5  813.55
#Mann=3,-1,0
  4485.3     0.1       0  4841.4    0.07       0  4847.4     0.1       0
Bank Sta=4841.4,4847.4
Exp/Cntr=0.3,0.1

Chan Stop Cuts=-1