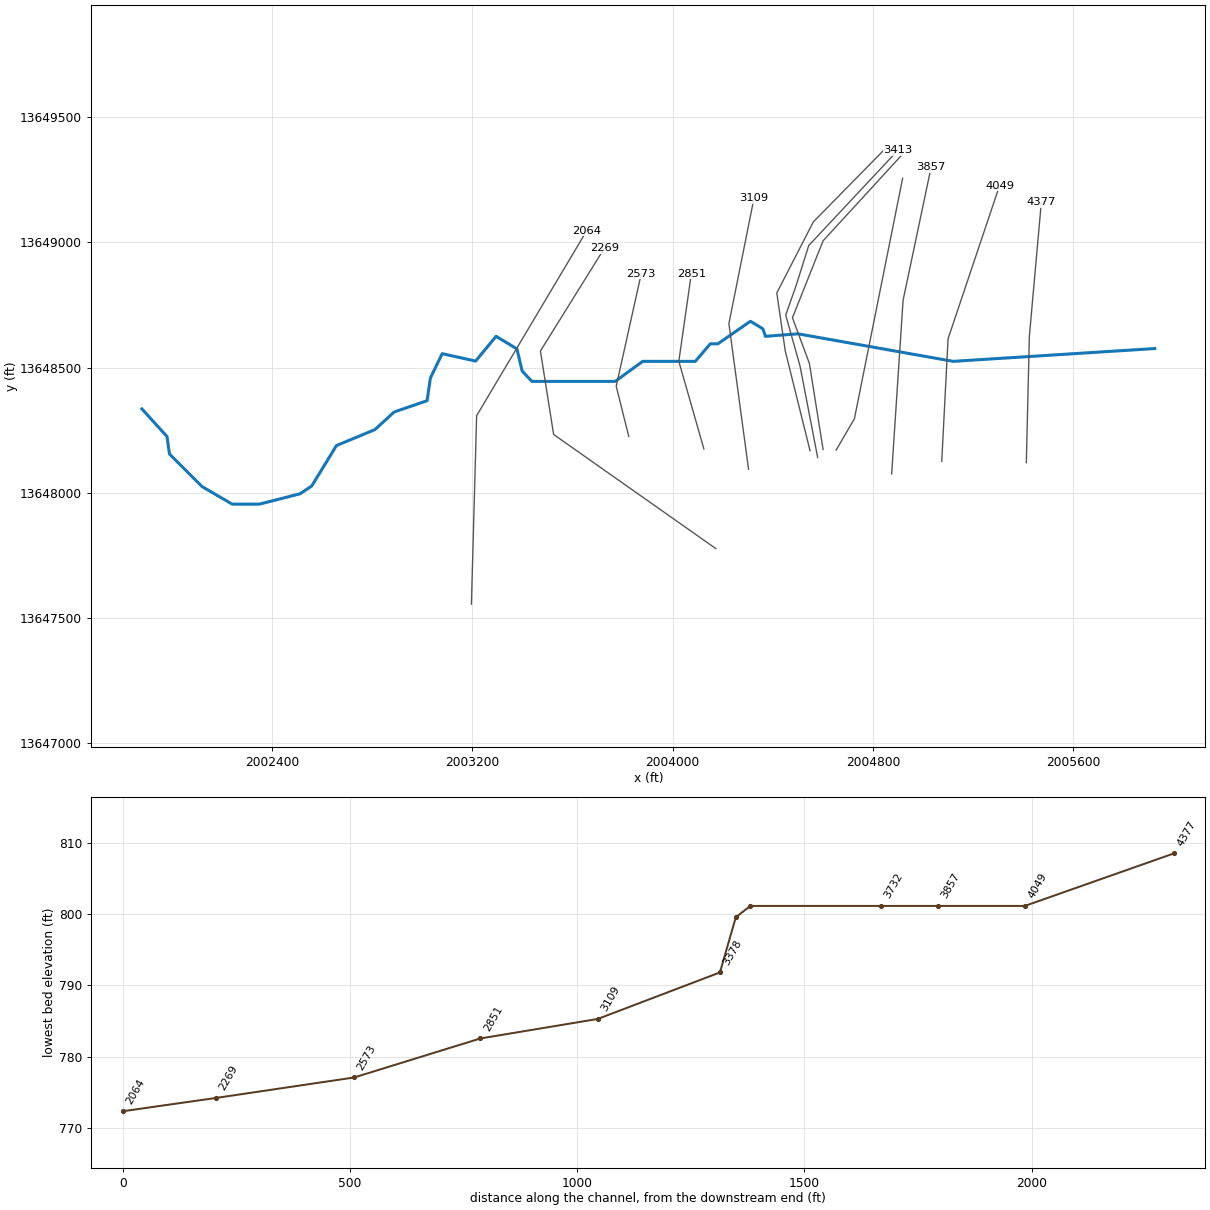
--- UNT 091 in HW.prj (project) ---

Proj Title=UNT 091 in HW Base Level Engineering
Current Plan=p01
Default Exp/Contr=0.3,0.1
English Units
Geom File=g01
Flow File=f01
Plan File=p01
BEGIN DESCRIPTION:
UNT 091 in HW
END DESCRIPTION:

--- UNT 091 in HW.p01 (plan) ---

Plan Title=Multiple Run
Short Identifier=Multiple
Geom File=g01
Flow File=f01
Subcritical Flow
K Sum by GR= 0
Std Step Tol= 0.01
Critical Tol= 0.01
Num of Std Step Trials= 20
Max Error Tol= 0.3
Flow Tol Ratio= 0.001
Split Flow NTrial= 30
Split Flow Tol= 0.02
Split Flow Ratio= 0.02
Log Output Level= 0
Friction Slope Method= 1
Unsteady Friction Slope Method= 2
Unsteady Bridges Friction Slope Method= 1
Parabolic Critical Depth
Global Vel Dist=  1 , 1 , 1
Global Log Level= 0
CheckData=True
Encroach Param= -1, 0, 0, 0
BEGIN DESCRIPTION:
Multiple Run
END DESCRIPTION:

--- UNT 091 in HW.f01 (steady flow) ---

Flow Title=Multiple
Number of Profiles=7
Profile Names=10-year,25-year,50-year,1pct_min,100-year,1pct_plu,500-year
River Rch & RM= UNT 091 in HW,Reach-1,4377
     373     512     626     380     758    1513    1114
Boundary for River Rch & Prof#=UNT 091 in HW,Reach-1,1
Up Type=0
Dn Type=3
Dn Slope=0.005
Boundary for River Rch & Prof#=UNT 091 in HW,Reach-1,2
Up Type=0
Dn Type=3
Dn Slope=0.005
Boundary for River Rch & Prof#=UNT 091 in HW,Reach-1,3
Up Type=0
Dn Type=3
Dn Slope=0.005
Boundary for River Rch & Prof#=UNT 091 in HW,Reach-1,4
Up Type=0
Dn Type=3
Dn Slope=0.005
Boundary for River Rch & Prof#=UNT 091 in HW,Reach-1,5
Up Type=0
Dn Type=3
Dn Slope=0.005
Boundary for River Rch & Prof#=UNT 091 in HW,Reach-1,6
Up Type=0
Dn Type=3
Dn Slope=0.005
Boundary for River Rch & Prof#=UNT 091 in HW,Reach-1,7
Up Type=0
Dn Type=3
Dn Slope=0.005

--- UNT 091 in HW.g01 (geometry) ---

Geom Title=Existing Conditions

River Reach=UNT 091 in HW,Reach-1
Reach XY= 30
      2005925.83     13648575.76      2005120.83     13648524.54
      2004500.80     13648634.54      2004370.80     13648624.54
      2004360.80     13648654.54      2004310.80     13648684.54
      2004180.80     13648594.54      2004150.80     13648594.54
      2004090.80     13648524.54      2003880.80     13648524.54
      2003770.80     13648444.54      2003438.41     13648444.54
      2003399.26     13648485.78      2003378.43     13648574.32
      2003295.10     13648624.66      2003213.50     13648525.71
      2003079.82     13648555.22      2003032.94     13648458.00
      2003019.57     13648367.36      2002888.28     13648322.44
      2002811.46     13648252.12      2002657.81     13648188.32
      2002558.85     13648026.86      2002511.98     13647995.61
      2002350.80     13647954.54      2002240.80     13647954.54
      2002120.80     13648024.54      2001990.80     13648154.54
      2001980.80     13648224.54      2001880.80     13648334.54

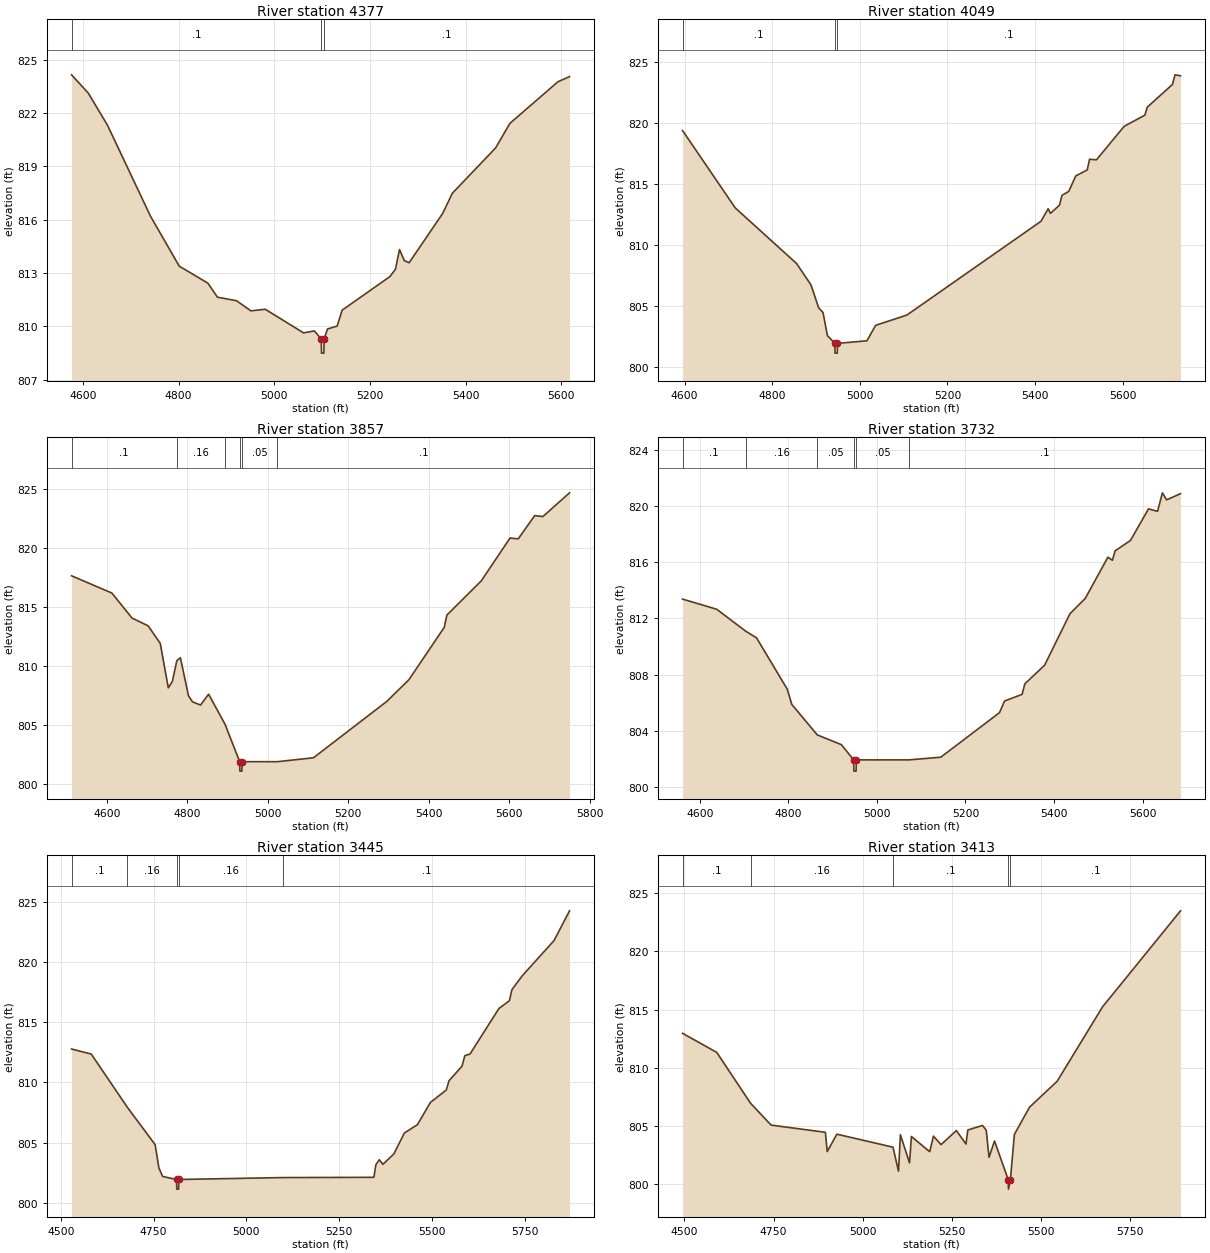
Type RM Length L Ch R = 1,4377,328,328,328
BEGIN DESCRIPTION:
UNT 091 in HW 10.0
END DESCRIPTION:
XS GIS Cut Line= 3
      2005412.81     13648119.99      2005425.00     13648625.00
      2005472.71     13649159.12
#Sta/Elev= 30
  4576.1  824.16  4611.1  823.13  4651.1  821.33  4741.2  816.20  4801.2  813.39
  4861.2  812.43  4881.2  811.64  4921.2  811.44  4951.2  810.87  4981.2  810.96
  5061.3  809.63  5083.8  809.74  5098.3  809.29  5098.8  808.49  5103.8  808.49
  5104.3  809.29  5111.4  809.85  5131.5  810.01  5142.0  810.91  5241.9  812.80
  5253.4  813.21  5262.0  814.32  5272.0  813.70  5282.1  813.58  5352.3  816.36
  5372.4  817.49  5462.8  820.04  5492.9  821.43  5593.3  823.77  5617.5  824.06
#Mann=3,-1,0
  4576.1     0.1       0  5098.3    0.07       0  5104.3     0.1       0
Bank Sta=5098.3,5104.3
Exp/Cntr=0.3,0.1

Type RM Length L Ch R = 1,4049,192,192,192
BEGIN DESCRIPTION:
UNT 091 in HW 9.0
END DESCRIPTION:
XS GIS Cut Line= 3
      2005075.00     13648124.96      2005100.31     13648614.82
      2005306.05     13649226.84
#Sta/Elev= 30
  4595.5  819.38  4715.7  813.04  4855.9  808.47  4888.6  806.72  4906.0  804.85
  4916.0  804.46  4926.0  802.57  4943.0  801.93  4943.5  801.13  4948.5  801.13
  4949.0  801.93  5016.1  802.14  5036.1  803.41  5107.3  804.25  5413.3  811.94
  5429.7  812.97  5434.9  812.59  5455.5  813.26  5461.2  814.07  5476.6  814.39
  5492.7  815.66  5518.8  816.15  5524.2  817.03  5539.9  816.98  5603.2  819.73
  5650.3  820.64  5655.9  821.30  5713.3  823.16  5719.2  823.95  5731.7  823.87
#Mann=3,-1,0
  4595.5     0.1       0  4943.0    0.07       0  4949.0     0.1       0
Bank Sta=4943,4949
Exp/Cntr=0.3,0.1

Type RM Length L Ch R = 1,3857,125,125,125
BEGIN DESCRIPTION:
UNT 091 in HW 8.0
END DESCRIPTION:
XS GIS Cut Line= 3
      2004875.00     13648075.00      2004920.62     13648768.46
      2005032.60     13649299.72
#Sta/Elev= 30
  4511.9  817.68  4612.1  816.22  4662.2  814.10  4702.3  813.44  4732.4  811.95
  4752.4  808.19  4762.4  808.73  4773.6  810.49  4782.5  810.74  4802.5  807.52
  4812.6  807.00  4832.6  806.73  4852.6  807.65  4893.6  805.09  4929.8  801.93
  4930.3  801.13  4935.3  801.13  4935.8  801.93  5023.7  801.93  5113.2  802.26
  5295.3  807.03  5350.4  808.87  5438.4  813.31  5444.9  814.35  5530.4  817.25
  5601.9  820.88  5622.3  820.81  5663.2  822.78  5683.6  822.70  5749.8  824.71
#Mann=6,-1,0
  4511.9     0.1       0  4773.6    0.16       0  4893.6    0.05       0
  4929.8   0.033       0  4935.8    0.05       0  5023.7     0.1       0
Bank Sta=4929.8,4935.8
Exp/Cntr=0.3,0.1

Type RM Length L Ch R = 1,3732,287,287,287
BEGIN DESCRIPTION:
Mapping XS 51e6373f
END DESCRIPTION:
XS GIS Cut Line= 3
      2004653.23     13648169.98      2004726.17     13648295.03
      2004918.88     13649255.93
#Sta/Elev= 30
  4560.9  813.37  4637.9  812.65  4703.4  811.09  4728.1  810.61  4797.4  806.96
  4807.6  805.88  4865.1  803.71  4919.8  803.01  4947.4  801.93  4947.9  801.13
  4952.9  801.13  4953.4  801.93  5072.2  801.93  5144.2  802.12  5276.8  805.29
  5288.3  806.12  5327.8  806.59  5334.1  807.34  5378.8  808.67  5436.0  812.33
  5470.6  813.42  5521.6  816.35  5531.8  816.13  5537.9  816.80  5572.6  817.54
  5613.4  819.79  5633.8  819.61  5644.8  820.93  5654.2  820.43  5685.7  820.87
#Mann=6,-1,0
  4560.9     0.1       0  4703.4    0.16       0  4865.1    0.05       0
  4947.4   0.033       0  4953.4    0.05       0  5072.2     0.1       0
Bank Sta=4947.4,4953.4
Exp/Cntr=0.3,0.1

Type RM Length L Ch R = 1,3445,32,32,32
BEGIN DESCRIPTION:
Mapping XS 1dcbecaf
END DESCRIPTION:
XS GIS Cut Line= 5
      2004601.18     13648172.59      2004546.49     13648516.38
      2004478.78     13648698.67      2004601.17     13649005.96
      2004917.84     13649351.18
#Sta/Elev= 30
  4528.9  812.76  4582.0  812.34  4679.3  807.92  4754.1  804.82  4764.2  802.89
  4774.4  802.18  4811.9  801.93  4812.4  801.13  4817.4  801.13  4817.9  801.93
  5099.6  802.09  5343.5  802.11  5348.9  803.16  5358.2  803.57  5367.8  803.19
  5397.4  804.05  5425.7  805.79  5460.8  806.48  5496.0  808.33  5538.5  809.35
  5545.9  810.12  5581.1  811.34  5588.5  812.20  5602.7  812.35  5680.4  816.12
  5708.7  816.77  5715.5  817.69  5743.9  818.86  5829.0  821.76  5870.7  824.23
#Mann=5,-1,0
  4528.9     0.1       0  4679.3    0.16       0  4811.9    0.07       0
  4817.9    0.16       0  5099.6     0.1       0
Bank Sta=4811.9,4817.9
Exp/Cntr=0.3,0.1

Type RM Length L Ch R = 1,3413,35,35,35
BEGIN DESCRIPTION:
UNT 091 in HW 7.0
END DESCRIPTION:
XS GIS Cut Line= 6
      2004579.48     13648140.85      2004509.16     13648505.44
      2004451.87     13648709.44      2004493.54     13648827.49
      2004543.88     13648987.21      2004900.77     13649368.35
#Sta/Elev= 30
  4494.6  812.96  4590.5  811.32  4685.6  806.94  4743.2  805.06  4895.6  804.44
  4900.8  802.78  4927.8  804.28  5085.4  803.16  5100.9  801.09  5106.2  804.23
  5131.8  801.81  5137.1  804.08  5188.4  802.77  5199.0  804.11  5220.3  803.38
  5263.3  804.59  5290.3  803.43  5295.5  804.64  5336.7  805.03  5347.2  804.62
  5355.0  802.29  5370.5  803.69  5409.0  800.35  5409.5  799.55  5415.0  800.35
  5426.2  804.26  5468.7  806.60  5546.4  808.84  5673.8  815.24  5892.6  823.50
#Mann=5,-1,0
  4494.6     0.1       0  4685.6    0.16       0  5085.4     0.1       0
  5409.0    0.07       0  5415.0     0.1       0
Bank Sta=5409,5415
Exp/Cntr=0.3,0.1

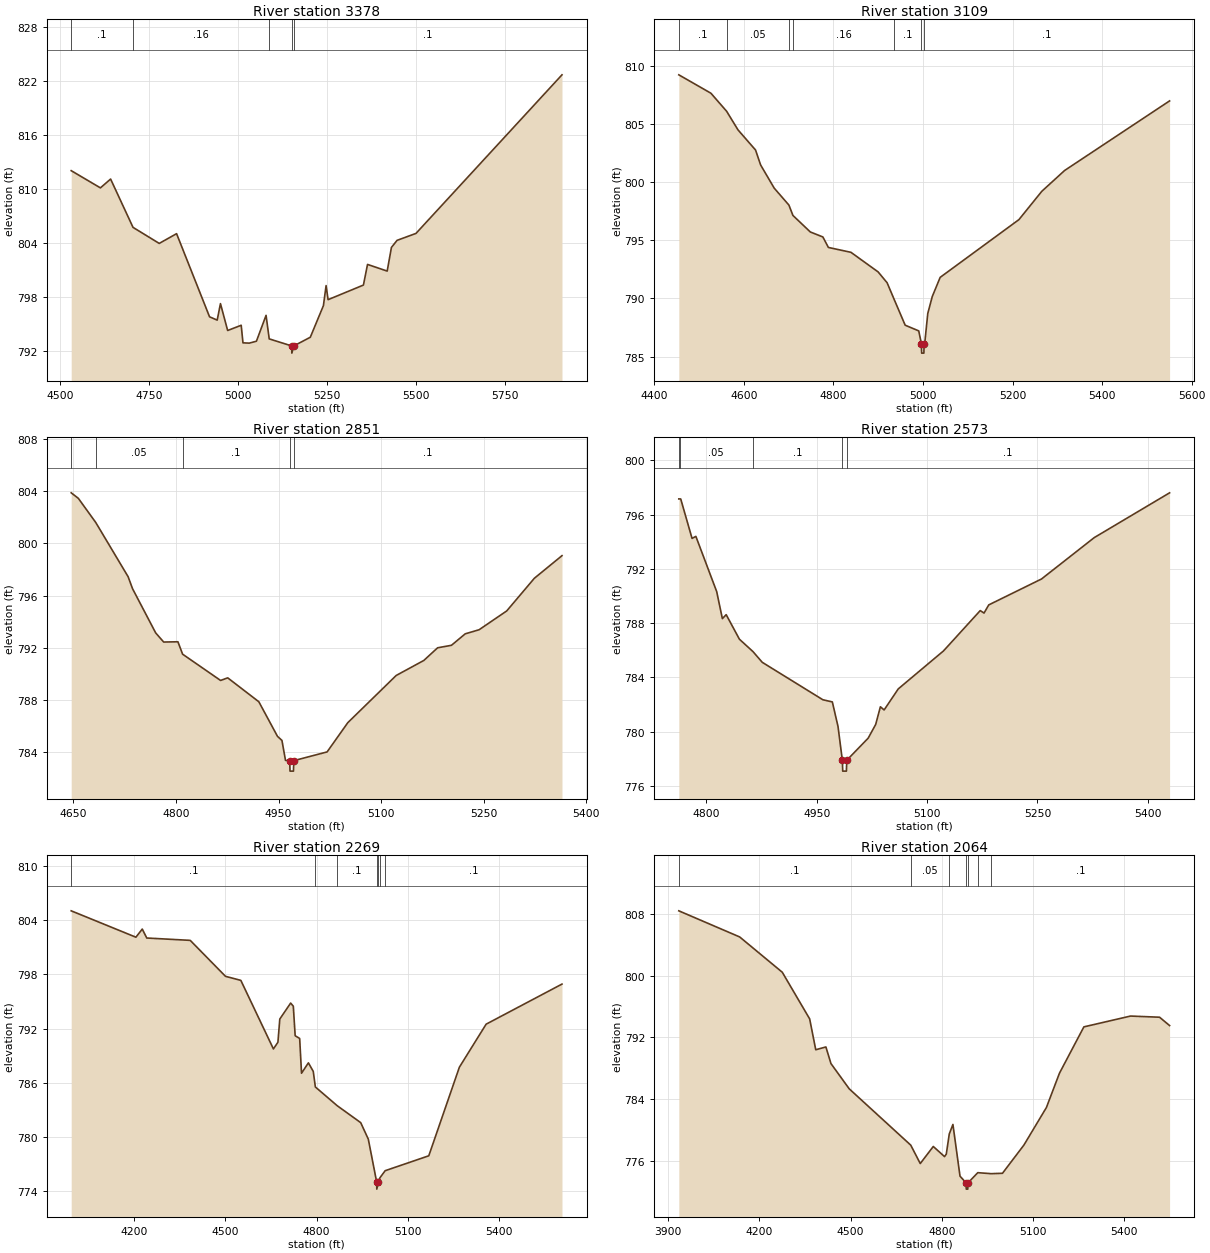
Type RM Length L Ch R = 1,3378,269,269,269
BEGIN DESCRIPTION:
Mapping XS 892fed67
END DESCRIPTION:
XS GIS Cut Line= 5
      2004549.08     13648167.46      2004450.13     13648565.86
      2004416.28     13648797.63      2004562.11     13649081.49
      2004853.76     13649378.34
#Sta/Elev= 30
  4530.2  812.05  4612.3  810.14  4641.0  811.12  4704.0  805.76  4777.7  803.98
  4826.5  805.06  4919.2  795.84  4940.7  795.47  4949.9  797.30  4970.1  794.32
  5008.2  794.90  5013.2  792.95  5030.8  792.92  5051.0  793.13  5078.1  796.00
  5087.0  793.39  5150.1  792.61  5150.6  791.81  5156.1  792.61  5202.5  793.57
  5239.4  797.08  5246.9  799.30  5252.5  797.74  5351.9  799.36  5363.4  801.65
  5418.7  800.91  5430.6  803.53  5446.5  804.32  5499.7  805.09  5910.2  822.68
#Mann=5,-1,0
  4530.2     0.1       0  4704.0    0.16       0  5087.0     0.1       0
  5150.1    0.07       0  5156.1     0.1       0
Bank Sta=5150.1,5156.1
Exp/Cntr=0.3,0.1

Type RM Length L Ch R = 1,3109,258,258,258
BEGIN DESCRIPTION:
UNT 091 in HW 6.0
END DESCRIPTION:
XS GIS Cut Line= 3
      2004303.44     13648093.94      2004225.00     13648675.00
      2004324.99     13649174.97
#Sta/Elev= 30
  4454.5  809.20  4526.2  807.62  4561.3  806.07  4586.7  804.47  4625.9  802.74
  4637.2  801.46  4667.5  799.47  4700.4  798.01  4709.4  797.12  4748.2  795.70
  4776.3  795.27  4788.6  794.37  4839.0  793.95  4899.6  792.27  4919.7  791.34
  4935.9  789.87  4960.1  787.69  4990.4  787.20  4996.4  786.09  4996.9  785.29
  5001.9  785.29  5002.4  786.09  5004.5  786.40  5010.6  788.70  5020.6  790.15
  5038.3  791.80  5214.2  796.76  5265.2  799.19  5316.2  800.98  5550.7  806.96
#Mann=7,-1,0
  4454.5     0.1       0  4561.3    0.05       0  4700.4     0.1       0
  4709.4    0.16       0  4935.9     0.1       0  4996.4    0.07       0
  5002.4     0.1       0
Bank Sta=4996.4,5002.4
Exp/Cntr=0.3,0.1

Type RM Length L Ch R = 1,2851,278,278,278
BEGIN DESCRIPTION:
UNT 091 in HW 5.0
END DESCRIPTION:
XS GIS Cut Line= 3
      2004124.99     13648175.02      2004025.00     13648525.00
      2004075.00     13648874.97
#Sta/Elev= 30
  4646.9  803.86  4657.3  803.44  4682.8  801.59  4730.1  797.44  4736.6  796.52
  4770.4  793.14  4782.1  792.44  4802.9  792.46  4809.8  791.51  4865.3  789.50
  4875.7  789.70  4921.2  787.87  4948.5  785.22  4955.0  784.91  4960.2  783.38
  4966.3  783.36  4966.8  782.56  4971.8  782.56  4972.3  783.36  5021.0  784.03
  5051.3  786.27  5122.0  789.88  5162.4  791.03  5182.6  792.00  5202.8  792.19
  5223.0  793.07  5243.2  793.38  5283.6  794.82  5324.0  797.32  5364.4  799.05
#Mann=5,-1,0
  4646.9     0.1       0  4682.8    0.05       0  4809.8     0.1       0
  4966.3    0.07       0  4972.3     0.1       0
Bank Sta=4966.3,4972.3
Exp/Cntr=0.3,0.1

Type RM Length L Ch R = 1,2573,304,304,304
BEGIN DESCRIPTION:
UNT 091 in HW 4.0
END DESCRIPTION:
XS GIS Cut Line= 3
      2003824.99     13648225.02      2003775.00     13648425.00
      2003875.00     13648874.99
#Sta/Elev= 30
  4762.6  797.15  4763.6  797.15  4765.2  797.15  4780.6  794.24  4785.8  794.39
  4814.1  790.32  4821.8  788.33  4827.0  788.62  4845.0  786.81  4863.4  785.90
  4876.0  785.11  4958.4  782.35  4971.3  782.19  4979.0  780.38  4984.9  777.89
  4985.4  777.09  4990.4  777.09  4990.9  777.89  5020.0  779.52  5030.2  780.53
  5036.6  781.83  5041.7  781.60  5060.9  783.15  5122.4  785.95  5172.3  788.92
  5177.5  788.74  5183.9  789.34  5255.6  791.25  5327.3  794.30  5429.7  797.60
#Mann=5,-1,0
  4762.6     0.1       0  4763.6    0.05       0  4863.4     0.1       0
  4984.9    0.07       0  4990.9     0.1       0
Bank Sta=4984.9,4990.9
Exp/Cntr=0.3,0.1

Type RM Length L Ch R = 1,2269,205,205,205
BEGIN DESCRIPTION:
UNT 091 in HW 3.0
END DESCRIPTION:
XS GIS Cut Line= 4
      2004172.82     13647776.79      2003525.00     13648232.54
      2003472.27     13648565.88      2003727.91     13648976.80
#Sta/Elev= 30
  3993.3  805.03  4206.0  802.11  4226.9  803.01  4241.7  802.02  4384.6  801.76
  4500.5  797.78  4551.0  797.33  4658.1  789.74  4672.9  790.48  4679.1  793.05
  4714.8  794.82  4723.5  794.47  4729.6  791.20  4744.4  790.90  4750.5  787.05
  4773.1  788.20  4789.1  787.25  4796.0  785.53  4867.6  783.46  4945.1  781.58
  4970.1  779.75  4997.5  775.02  4998.0  774.22  5003.5  775.02  5008.4  775.48
  5025.5  776.26  5168.9  777.91  5269.5  787.72  5357.4  792.48  5606.8  796.92
#Mann=7,-1,0
  3993.3     0.1       0  4796.0    0.05       0  4867.6     0.1       0
  4997.5    0.07       0  5003.5     0.1       0  5008.4    0.12       0
  5025.5     0.1       0
Bank Sta=4997.5,5003.5
Exp/Cntr=0.3,0.1

Type RM Length L Ch R = 1,2064,0,0,0
BEGIN DESCRIPTION:
UNT 091 in HW 1.0
END DESCRIPTION:
XS GIS Cut Line= 3
      2003196.66     13647554.96      2003217.49     13648307.53
      2003657.61     13649047.13
#Sta/Elev= 30
  3935.2  808.38  4135.3  805.00  4275.4  800.43  4365.4  794.39  4385.4  790.40
  4418.8  790.76  4435.4  788.61  4495.5  785.34  4697.8  778.05  4729.0  775.67
  4771.8  777.88  4808.8  776.57  4814.6  776.89  4824.4  779.50  4836.4  780.73
  4859.7  774.04  4879.8  773.16  4880.3  772.36  4885.3  772.36  4885.8  773.16
  4918.1  774.49  4961.9  774.36  4999.3  774.41  5069.7  778.06  5143.7  782.92
  5186.6  787.36  5266.9  793.36  5420.3  794.76  5515.7  794.61  5548.7  793.53
#Mann=7,-1,0
  3935.2     0.1       0  4697.8    0.05       0  4824.4    0.12       0
  4879.8    0.07       0  4885.8    0.12       0  4918.1    0.05       0
  4961.9     0.1       0
Bank Sta=4879.8,4885.8
Exp/Cntr=0.3,0.1

Chan Stop Cuts=-1