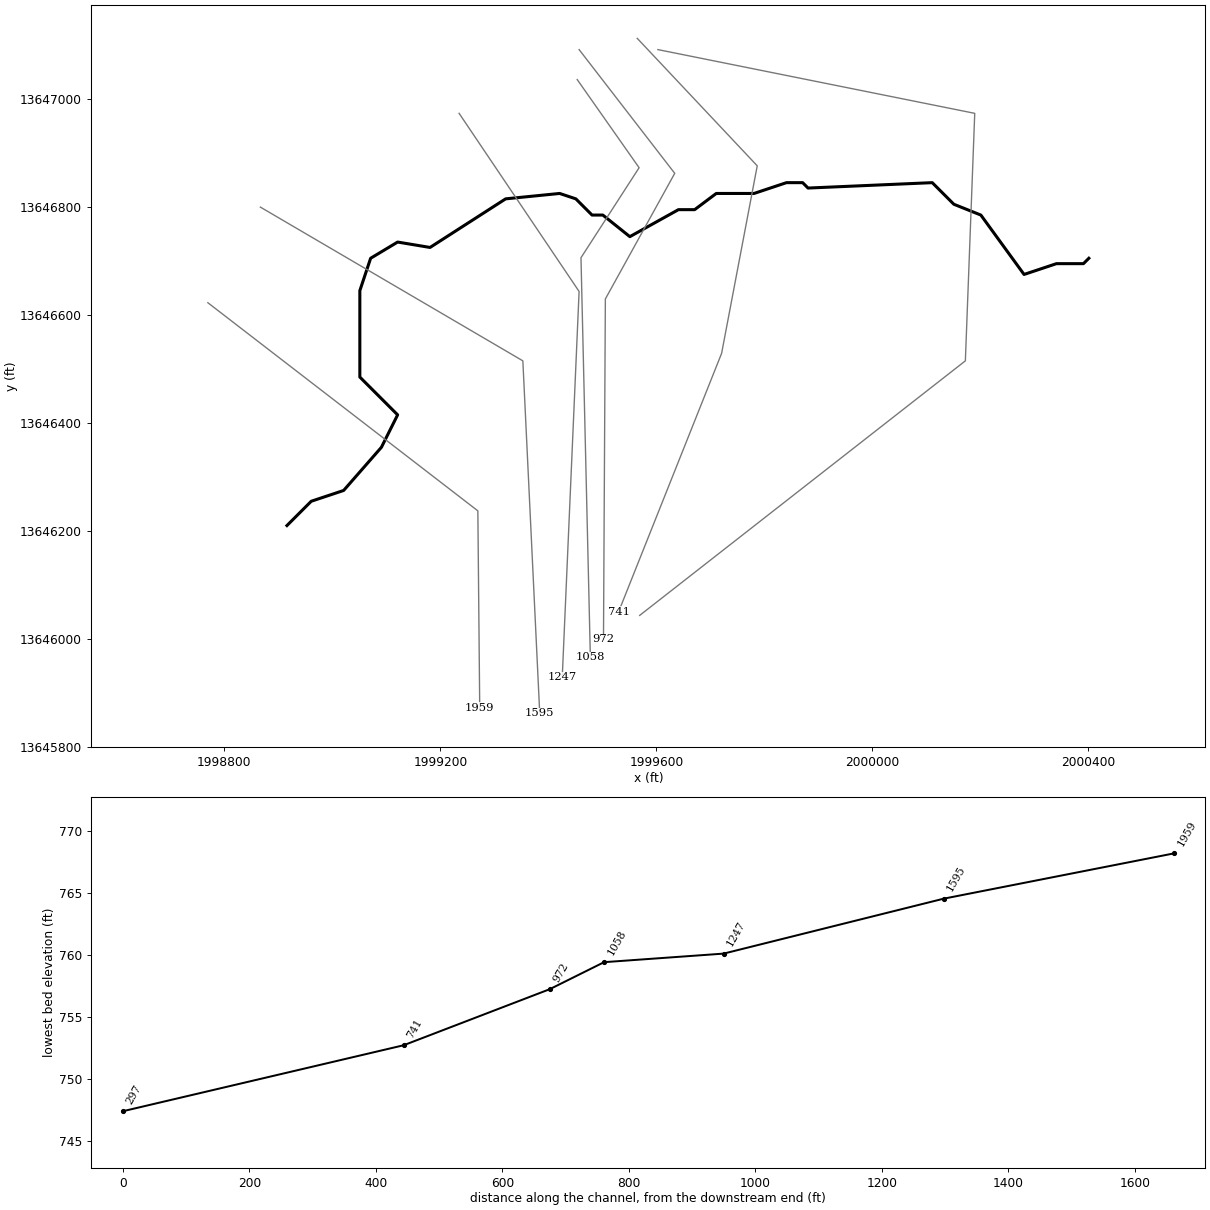
--- UNT 092 in HW.prj (project) ---

Proj Title=UNT 092 in HW Base Level Engineering
Current Plan=p01
Default Exp/Contr=0.3,0.1
English Units
Geom File=g01
Flow File=f01
Plan File=p01
BEGIN DESCRIPTION:
UNT 092 in HW
END DESCRIPTION:

--- UNT 092 in HW.p01 (plan) ---

Plan Title=Multiple Run
Short Identifier=Multiple
Geom File=g01
Flow File=f01
Subcritical Flow
K Sum by GR= 0
Std Step Tol= 0.01
Critical Tol= 0.01
Num of Std Step Trials= 20
Max Error Tol= 0.3
Flow Tol Ratio= 0.001
Split Flow NTrial= 30
Split Flow Tol= 0.02
Split Flow Ratio= 0.02
Log Output Level= 0
Friction Slope Method= 1
Unsteady Friction Slope Method= 2
Unsteady Bridges Friction Slope Method= 1
Parabolic Critical Depth
Global Vel Dist=  1 , 1 , 1
Global Log Level= 0
CheckData=True
Encroach Param= -1, 0, 0, 0
BEGIN DESCRIPTION:
Multiple Run
END DESCRIPTION:

--- UNT 092 in HW.f01 (steady flow) ---

Flow Title=Multiple
Number of Profiles=7
Profile Names=10-year,25-year,50-year,1pct_min,100-year,1pct_plu,500-year
River Rch & RM= UNT 092 in HW,Reach-1,1959
     362     497     608     370     738    1472    1087
Boundary for River Rch & Prof#=UNT 092 in HW,Reach-1,1
Up Type=0
Dn Type=3
Dn Slope=0.005
Boundary for River Rch & Prof#=UNT 092 in HW,Reach-1,2
Up Type=0
Dn Type=3
Dn Slope=0.005
Boundary for River Rch & Prof#=UNT 092 in HW,Reach-1,3
Up Type=0
Dn Type=3
Dn Slope=0.005
Boundary for River Rch & Prof#=UNT 092 in HW,Reach-1,4
Up Type=0
Dn Type=3
Dn Slope=0.005
Boundary for River Rch & Prof#=UNT 092 in HW,Reach-1,5
Up Type=0
Dn Type=3
Dn Slope=0.005
Boundary for River Rch & Prof#=UNT 092 in HW,Reach-1,6
Up Type=0
Dn Type=3
Dn Slope=0.005
Boundary for River Rch & Prof#=UNT 092 in HW,Reach-1,7
Up Type=0
Dn Type=3
Dn Slope=0.005

--- UNT 092 in HW.g01 (geometry) ---

Geom Title=Existing Conditions

River Reach=UNT 092 in HW,Reach-1
Reach XY= 30
      1998915.80     13646209.54      1998960.80     13646254.54
      1999020.80     13646274.54      1999090.80     13646354.54
      1999120.80     13646414.54      1999050.80     13646484.54
      1999050.80     13646644.54      1999070.80     13646704.54
      1999120.80     13646734.54      1999180.80     13646724.54
      1999320.80     13646814.54      1999420.80     13646824.54
      1999450.80     13646814.54      1999480.80     13646784.54
      1999500.80     13646784.54      1999550.80     13646744.54
      1999640.80     13646794.54      1999670.80     13646794.54
      1999710.80     13646824.54      1999780.80     13646824.54
      1999840.80     13646844.54      1999870.80     13646844.54
      1999880.80     13646834.54      2000110.80     13646844.54
      2000150.80     13646804.54      2000200.80     13646784.54
      2000280.80     13646674.54      2000340.80     13646694.54
      2000390.80     13646694.54      2000400.80     13646704.54

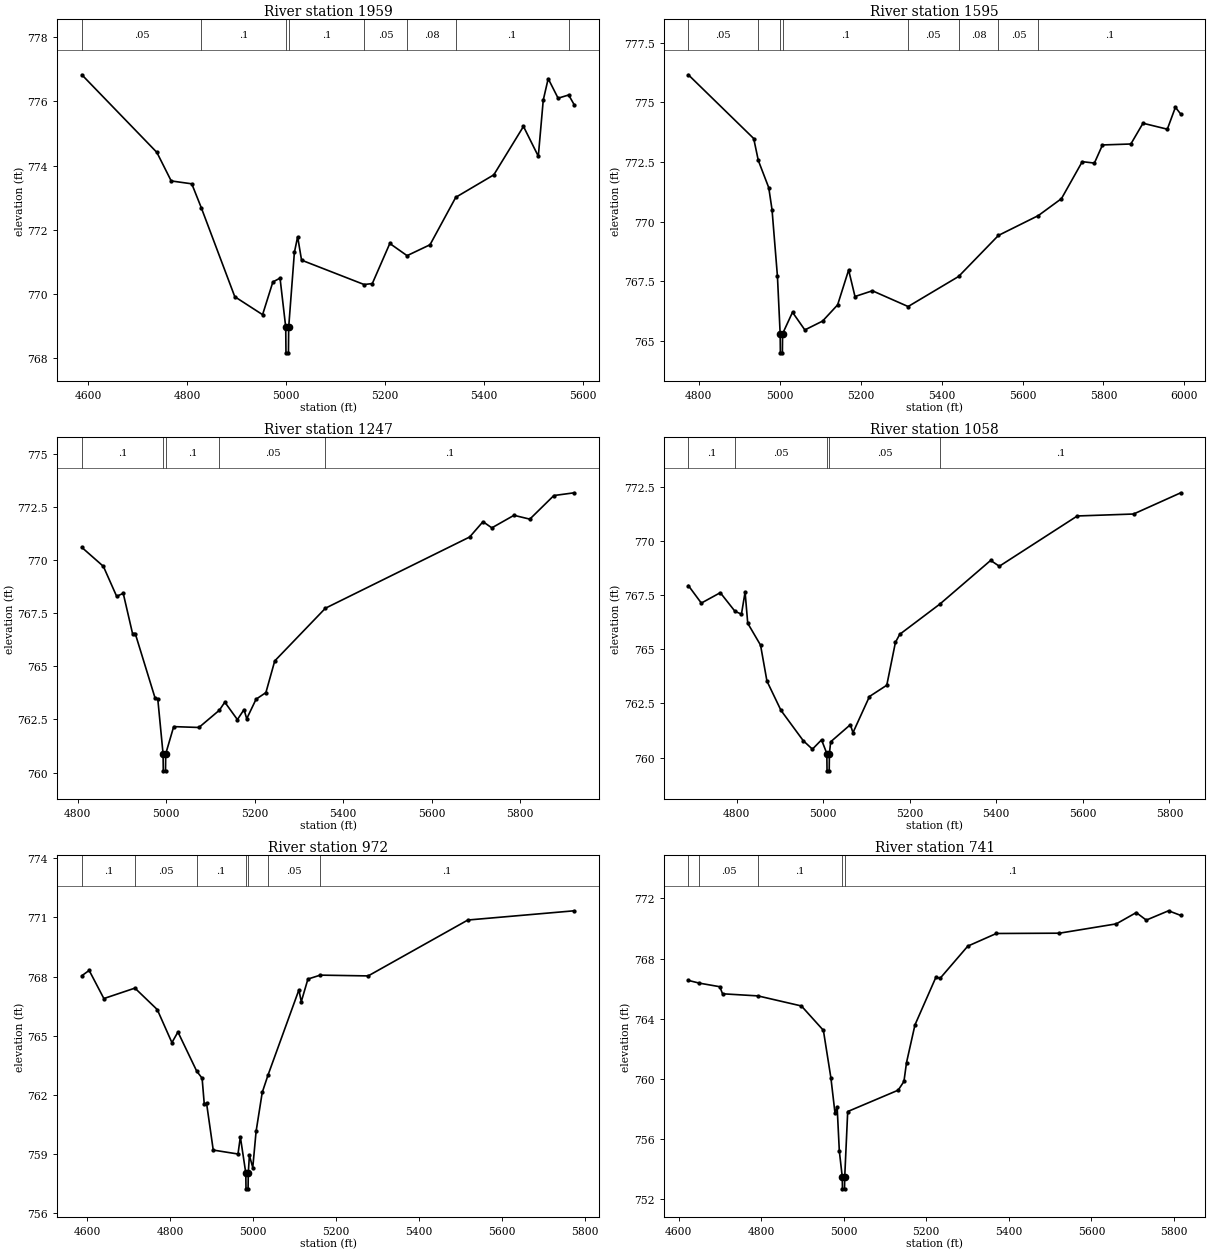
Type RM Length L Ch R = 1,1959,364,364,364
BEGIN DESCRIPTION:
UNT 092 in HW 1.0
END DESCRIPTION:
XS GIS Cut Line= 3
      1998769.36     13646622.20      1999269.34     13646236.79
      1999272.82     13645872.19
#Sta/Elev= 30
  4587.1  776.83  4738.8  774.41  4767.8  773.52  4809.4  773.43  4828.5  772.69
  4896.4  769.91  4952.6  769.35  4973.4  770.37  4987.9  770.49  4999.4  768.96
  4999.9  768.16  5004.9  768.16  5005.4  768.96  5016.9  771.29  5023.5  771.78
  5031.4  771.05  5157.9  770.29  5174.5  770.32  5209.9  771.57  5244.8  771.19
  5291.2  771.53  5343.3  773.01  5420.2  773.71  5480.2  775.22  5510.2  774.29
  5520.2  776.04  5530.2  776.71  5550.2  776.10  5571.6  776.20  5583.0  775.89
#Mann=8,-1,0
  4587.1    0.05       0  4828.5     0.1       0  4999.4    0.07       0
  5005.4     0.1       0  5157.9    0.05       0  5244.8    0.08       0
  5343.3     0.1       0  5571.6    0.05       0
Bank Sta=4999.4,5005.4
Exp/Cntr=0.3,0.1

Type RM Length L Ch R = 1,1595,348,348,348
BEGIN DESCRIPTION:
UNT 092 in HW 2.0
END DESCRIPTION:
XS GIS Cut Line= 3
      1998866.58     13646799.28      1999352.68     13646514.57
      1999383.93     13645861.75
#Sta/Elev= 30
  4774.2  776.16  4935.7  773.49  4947.1  772.57  4972.9  771.43  4981.0  770.51
  4994.4  767.71  5001.1  765.31  5001.6  764.51  5006.6  764.51  5007.1  765.31
  5031.6  766.21  5062.1  765.47  5105.9  765.84  5143.1  766.52  5170.3  767.98
  5186.0  766.87  5229.0  767.11  5317.3  766.45  5442.1  767.71  5540.5  769.43
  5639.0  770.26  5696.2  770.97  5747.6  772.52  5777.6  772.46  5797.6  773.22
  5867.7  773.26  5897.7  774.13  5957.8  773.88  5977.8  774.80  5991.1  774.51
#Mann=8,-1,0
  4774.2    0.05       0  4947.1     0.1       0  5001.1    0.07       0
  5007.1     0.1       0  5317.3    0.05       0  5442.1    0.08       0
  5540.5    0.05       0  5639.0     0.1       0
Bank Sta=5001.1,5007.1
Exp/Cntr=0.3,0.1

Type RM Length L Ch R = 1,1247,189,189,189
BEGIN DESCRIPTION:
UNT 092 in HW 3.0
END DESCRIPTION:
XS GIS Cut Line= 3
      1999234.61     13646972.92      1999456.84     13646643.04
      1999425.64     13645928.87
#Sta/Elev= 30
  4809.4  770.59  4858.0  769.70  4888.0  768.29  4902.9  768.43  4923.9  766.54
  4930.0  766.54  4974.9  763.50  4980.9  763.47  4992.9  760.88  4993.4  760.08
  4998.4  760.08  4998.9  760.88  5016.9  762.16  5073.9  762.12  5120.0  762.93
  5132.4  763.31  5160.8  762.49  5175.8  762.96  5181.9  762.53  5203.0  763.45
  5225.2  763.76  5245.2  765.25  5359.7  767.73  5685.6  771.08  5715.7  771.80
  5735.7  771.51  5785.7  772.10  5821.5  771.92  5875.8  773.03  5922.0  773.16
#Mann=5,-1,0
  4809.4     0.1       0  4992.9    0.07       0  4998.9     0.1       0
  5120.0    0.05       0  5359.7     0.1       0
Bank Sta=4992.9,4998.9
Exp/Cntr=0.3,0.1

Type RM Length L Ch R = 1,1058,86,86,86
BEGIN DESCRIPTION:
UNT 092 in HW 4.0
END DESCRIPTION:
XS GIS Cut Line= 4
      1999453.36     13647035.41      1999567.96     13646872.20
      1999460.32     13646705.54      1999477.68     13645965.96
#Sta/Elev= 30
  4688.6  767.94  4718.6  767.13  4762.4  767.61  4796.4  766.75  4811.3  766.62
  4819.7  767.64  4825.8  766.20  4855.4  765.19  4870.2  763.53  4902.6  762.18
  4954.1  760.78  4975.2  760.39  4996.3  760.82  5008.5  760.19  5009.0  759.39
  5014.0  759.39  5014.5  760.19  5017.4  760.73  5062.9  761.52  5068.9  761.15
  5107.0  762.82  5147.0  763.34  5167.0  765.32  5177.0  765.69  5270.0  767.09
  5387.0  769.10  5407.0  768.83  5587.1  771.15  5717.1  771.24  5826.2  772.22
#Mann=5,-1,0
  4688.6     0.1       0  4796.4    0.05       0  5008.5    0.04       0
  5014.5    0.05       0  5270.0     0.1       0
Bank Sta=5008.5,5014.5
Exp/Cntr=0.3,0.1

Type RM Length L Ch R = 1,972,231,231,231
BEGIN DESCRIPTION:
UNT 092 in HW 5.0
END DESCRIPTION:
XS GIS Cut Line= 4
      1999456.86     13647090.93      1999633.93     13646861.79
      1999505.46     13646629.15      1999501.99     13645998.60
#Sta/Elev= 30
  4587.9  768.04  4605.5  768.31  4640.9  766.88  4715.7  767.41  4769.5  766.32
  4804.8  764.64  4819.3  765.18  4864.5  763.19  4877.5  762.83  4882.6  761.54
  4888.3  761.55  4904.3  759.18  4963.9  758.98  4969.6  759.85  4982.7  758.01
  4983.2  757.21  4988.2  757.21  4988.7  758.01  4991.4  758.91  4999.5  758.29
  5007.5  760.13  5022.3  762.11  5036.2  762.99  5110.6  767.32  5116.3  766.72
  5132.3  767.87  5162.0  768.07  5277.4  768.03  5517.4  770.87  5773.8  771.34
#Mann=7,-1,0
  4587.9     0.1       0  4715.7    0.05       0  4864.5     0.1       0
  4982.7    0.07       0  4988.7     0.1       0  5036.2    0.05       0
  5162.0     0.1       0
Bank Sta=4982.7,4988.7
Exp/Cntr=0.3,0.1

Type RM Length L Ch R = 1,741,444,444,444
BEGIN DESCRIPTION:
UNT 092 in HW 6.0
END DESCRIPTION:
XS GIS Cut Line= 4
      1999564.48     13647111.79      1999786.71     13646875.68
      1999720.73     13646528.45      1999530.02     13646049.94
#Sta/Elev= 30
  4623.7  766.55  4650.1  766.37  4699.8  766.13  4706.6  765.66  4792.2  765.52
  4897.6  764.85  4950.8  763.23  4969.0  760.07  4979.0  757.71  4984.1  758.15
  4989.4  755.21  4996.5  753.49  4997.0  752.69  5002.0  752.69  5002.5  753.49
  5009.7  757.83  5131.9  759.25  5145.9  759.83  5152.2  761.09  5172.6  763.59
  5223.5  766.77  5233.6  766.69  5300.6  768.83  5369.7  769.67  5522.6  769.69
  5660.3  770.31  5708.6  771.06  5732.9  770.56  5786.8  771.18  5816.5  770.87
#Mann=5,-1,0
  4623.7     0.1       0  4650.1    0.05       0  4792.2     0.1       0
  4996.5    0.07       0  5002.5     0.1       0
Bank Sta=4996.5,5002.5
Exp/Cntr=0.3,0.1

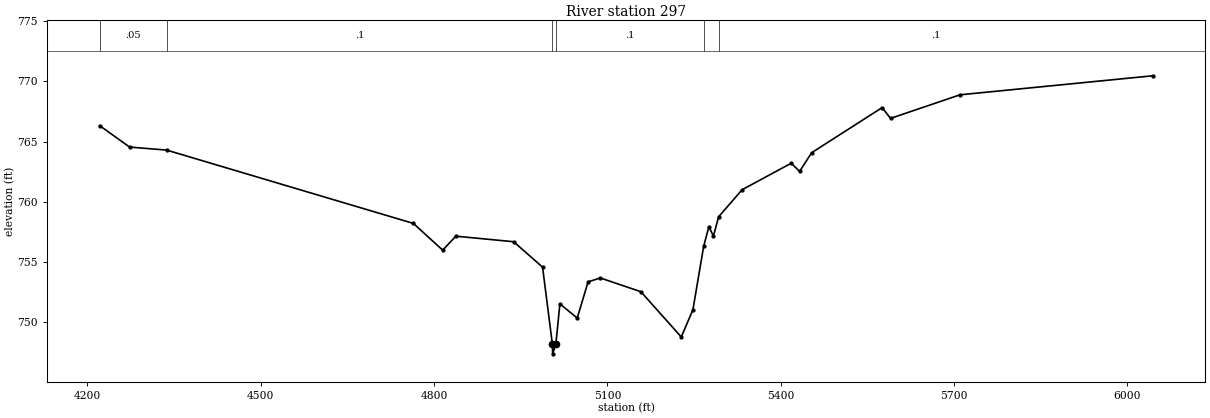
Type RM Length L Ch R = 1,297,0,0,0
BEGIN DESCRIPTION:
UNT 092 in HW 7.0
END DESCRIPTION:
XS GIS Cut Line= 4
      1999602.69     13647090.95      2000189.48     13646972.90
      2000172.12     13646514.57      1999569.00     13646043.16
#Sta/Elev= 30
  4221.1  766.32  4273.0  764.54  4337.0  764.29  4764.1  758.20  4814.8  755.98
  4837.6  757.14  4937.6  756.68  4987.7  754.57  5004.7  748.17  5005.2  747.37
  5010.7  748.17  5017.7  751.52  5047.7  750.34  5066.5  753.35  5087.7  753.67
  5157.8  752.53  5227.8  748.77  5247.9  751.03  5266.5  756.29  5275.6  757.94
  5283.4  757.14  5292.4  758.75  5333.1  761.00  5418.1  763.20  5432.6  762.52
  5453.4  764.07  5575.5  767.82  5589.9  766.92  5710.2  768.88  6043.8  770.46
#Mann=6,-1,0
  4221.1    0.05       0  4337.0     0.1       0  5004.7    0.07       0
  5010.7     0.1       0  5266.5    0.16       0  5292.4     0.1       0
Bank Sta=5004.7,5010.7
Exp/Cntr=0.3,0.1

Chan Stop Cuts=-1