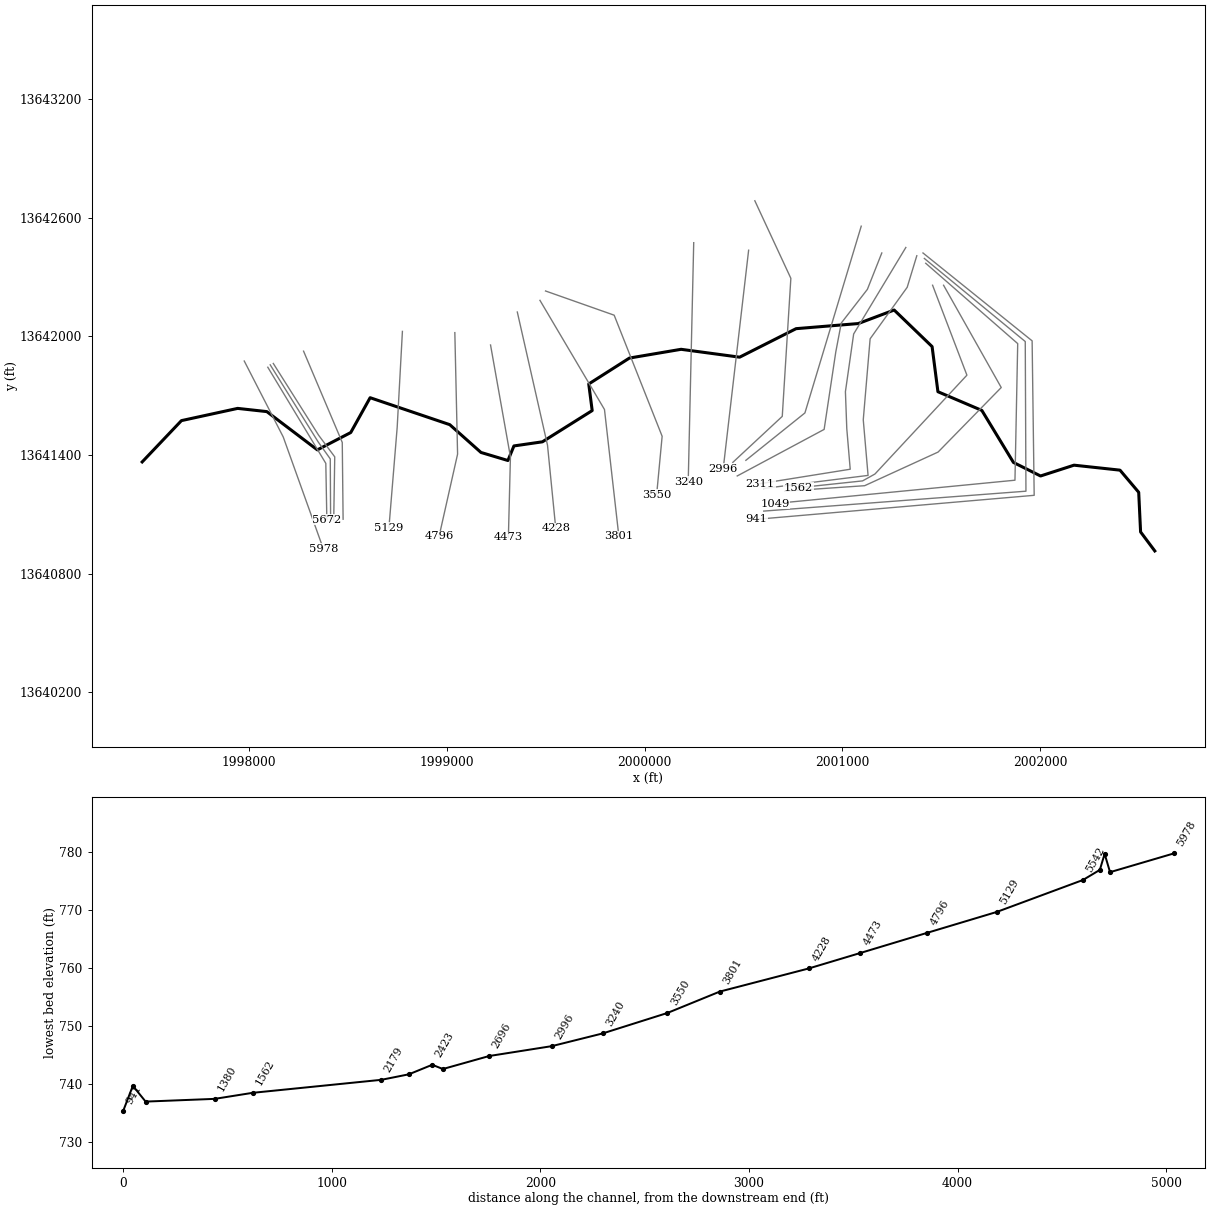
--- UNT 093 in HW.prj (project) ---

Proj Title=UNT 093 in HW Base Level Engineering
Current Plan=p01
Default Exp/Contr=0.3,0.1
English Units
Geom File=g01
Flow File=f01
Plan File=p01
BEGIN DESCRIPTION:
UNT 093 in HW
END DESCRIPTION:

--- UNT 093 in HW.p01 (plan) ---

Plan Title=Multiple Run
Short Identifier=Multiple
Geom File=g01
Flow File=f01
Subcritical Flow
K Sum by GR= 0
Std Step Tol= 0.01
Critical Tol= 0.01
Num of Std Step Trials= 20
Max Error Tol= 0.3
Flow Tol Ratio= 0.001
Split Flow NTrial= 30
Split Flow Tol= 0.02
Split Flow Ratio= 0.02
Log Output Level= 0
Friction Slope Method= 1
Unsteady Friction Slope Method= 2
Unsteady Bridges Friction Slope Method= 1
Parabolic Critical Depth
Global Vel Dist=  1 , 1 , 1
Global Log Level= 0
CheckData=True
Encroach Param= -1, 0, 0, 0
BEGIN DESCRIPTION:
Multiple Run
END DESCRIPTION:

--- UNT 093 in HW.f01 (steady flow) ---

Flow Title=Multiple
Number of Profiles=7
Profile Names=10-year,25-year,50-year,1pct_min,100-year,1pct_plu,500-year
River Rch & RM= UNT 093 in HW,Reach-1,5978
     704    1008    1266     789    1573    3139    2437
Boundary for River Rch & Prof#=UNT 093 in HW,Reach-1,1
Up Type=0
Dn Type=3
Dn Slope=0.005
Boundary for River Rch & Prof#=UNT 093 in HW,Reach-1,2
Up Type=0
Dn Type=3
Dn Slope=0.005
Boundary for River Rch & Prof#=UNT 093 in HW,Reach-1,3
Up Type=0
Dn Type=3
Dn Slope=0.005
Boundary for River Rch & Prof#=UNT 093 in HW,Reach-1,4
Up Type=0
Dn Type=3
Dn Slope=0.005
Boundary for River Rch & Prof#=UNT 093 in HW,Reach-1,5
Up Type=0
Dn Type=3
Dn Slope=0.005
Boundary for River Rch & Prof#=UNT 093 in HW,Reach-1,6
Up Type=0
Dn Type=3
Dn Slope=0.005
Boundary for River Rch & Prof#=UNT 093 in HW,Reach-1,7
Up Type=0
Dn Type=3
Dn Slope=0.005

--- UNT 093 in HW.g01 (geometry) ---

Geom Title=Existing Conditions

River Reach=UNT 093 in HW,Reach-1
Reach XY= 30
      1997458.60     13641364.64      1997657.25     13641573.65
      1997941.54     13641635.50      1998089.11     13641619.22
      1998344.75     13641425.65      1998513.59     13641513.32
      1998611.68     13641689.54      1999014.46     13641553.25
      1999172.44     13641412.63      1999308.73     13641371.83
      1999339.11     13641445.61      1999483.21     13641466.45
      1999734.94     13641624.43      1999717.58     13641758.98
      1999923.31     13641890.06      2000184.60     13641934.33
      2000480.80     13641894.54      2000766.30     13642038.72
      2001080.80     13642064.54      2001262.48     13642133.01
      2001454.32     13641948.11      2001483.84     13641719.82
      2001706.06     13641625.20      2001865.78     13641362.18
      2002002.93     13641293.60      2002172.21     13641348.29
      2002404.84     13641323.11      2002499.46     13641211.14
      2002509.01     13641010.61      2002580.80     13640914.54

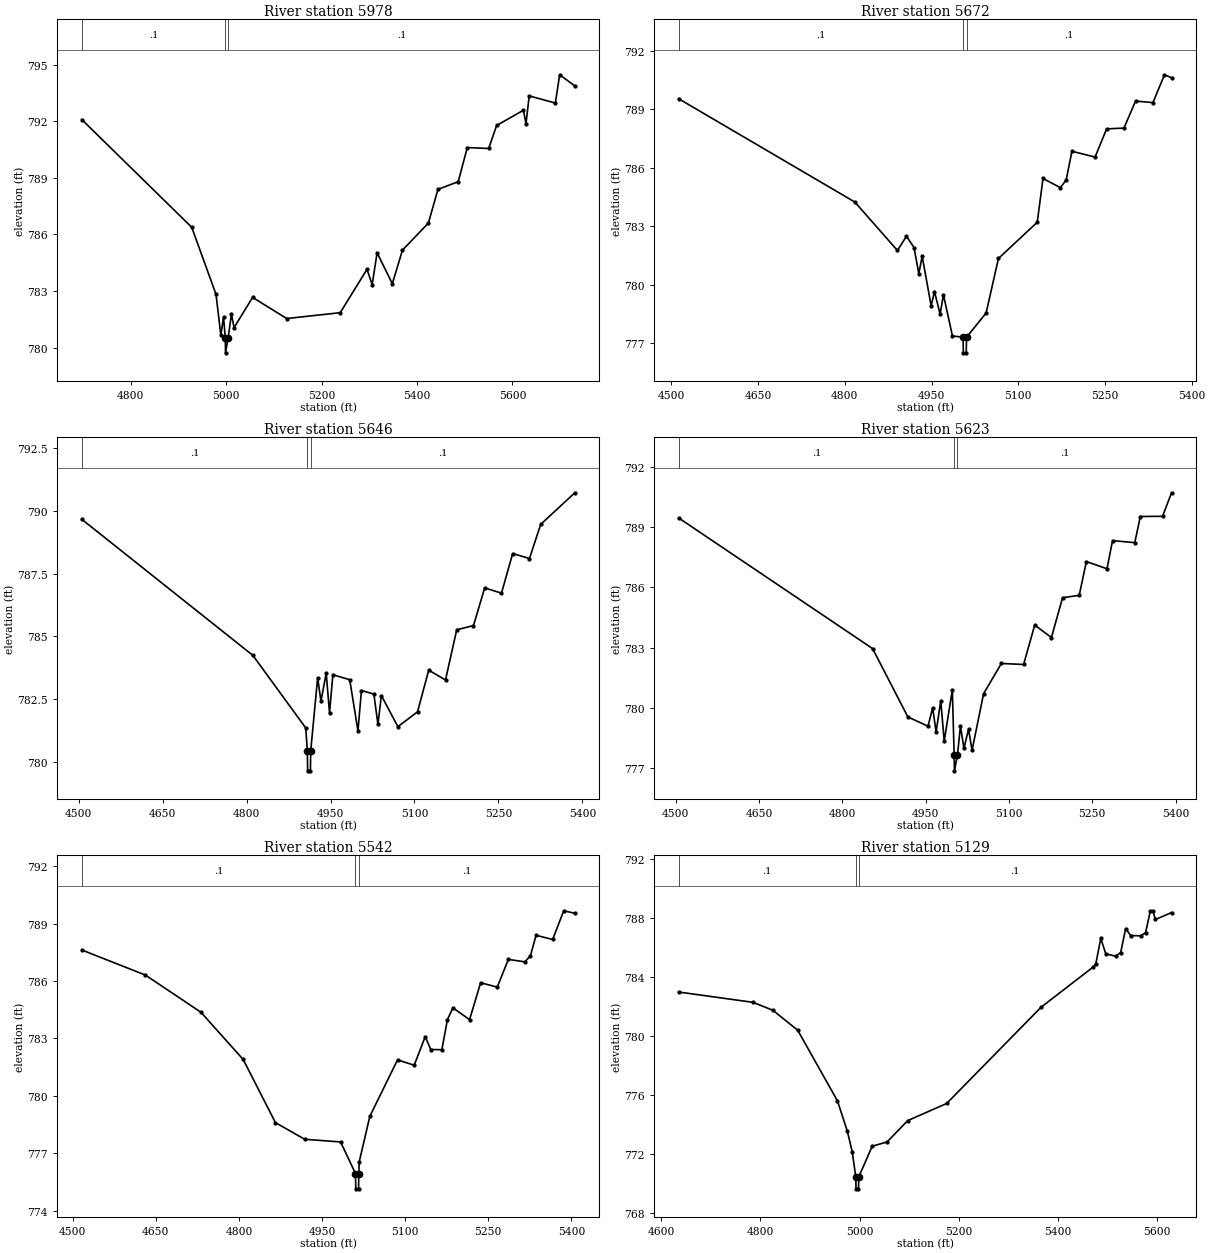
Type RM Length L Ch R = 1,5978,306,306,306
BEGIN DESCRIPTION:
UNT 093 in HW 10.0
END DESCRIPTION:
XS GIS Cut Line= 3
      1997974.98     13641875.03      1998172.14     13641491.01
      1998374.99     13640925.04
#Sta/Elev= 30
  4697.8  792.09  4928.0  786.38  4978.9  782.82  4989.0  780.65  4994.6  781.63
  4998.3  780.52  4998.8  779.72  5004.3  780.52  5011.1  781.76  5016.8  781.06
  5055.5  782.66  5127.1  781.54  5239.2  781.85  5295.2  784.15  5306.1  783.34
  5316.4  785.03  5348.3  783.39  5369.6  785.17  5423.8  786.60  5443.9  788.39
  5486.4  788.80  5505.4  790.61  5550.2  790.56  5566.9  791.78  5623.1  792.59
  5628.4  791.87  5635.1  793.35  5689.9  792.97  5698.9  794.47  5730.7  793.88
#Mann=3,-1,0
  4697.8     0.1       0  4998.3    0.07       0  5004.3     0.1       0
Bank Sta=4998.3,5004.3
Exp/Cntr=0.3,0.1

Type RM Length L Ch R = 1,5672,26,26,26
BEGIN DESCRIPTION:
Mapping XS 954ea281
END DESCRIPTION:
XS GIS Cut Line= 3
      1998094.12     13641843.63      1998387.54     13641357.48
      1998392.75     13641072.76
#Sta/Elev= 30
  4512.5  789.55  4817.3  784.24  4891.0  781.75  4906.6  782.48  4919.7  781.90
  4927.9  780.56  4933.8  781.45  4949.3  778.91  4955.1  779.64  4964.8  778.48
  4970.6  779.47  4986.1  777.36  5004.5  777.29  5005.0  776.49  5010.0  776.49
  5010.5  777.29  5044.4  778.54  5065.7  781.34  5132.8  783.20  5142.8  785.45
  5172.8  784.98  5182.8  785.37  5192.8  786.85  5232.8  786.55  5252.8  788.00
  5282.8  788.04  5302.9  789.43  5332.9  789.35  5352.9  790.78  5365.1  790.63
#Mann=3,-1,0
  4512.5     0.1       0  5004.5    0.07       0  5010.5     0.1       0
Bank Sta=5004.5,5010.5
Exp/Cntr=0.3,0.1

Type RM Length L Ch R = 1,5646,23,23,23
BEGIN DESCRIPTION:
Mapping XS d094f166
END DESCRIPTION:
XS GIS Cut Line= 4
      1998106.31     13641855.71      1998349.35     13641465.12
      1998410.11     13641380.05      1998411.85     13641064.03
#Sta/Elev= 30
  4505.8  789.66  4811.3  784.24  4905.7  781.35  4908.6  780.44  4909.1  779.64
  4914.1  779.64  4914.6  780.44  4927.0  783.35  4932.9  782.42  4942.3  783.53
  4948.2  781.95  4954.2  783.47  4984.3  783.27  4999.0  781.23  5005.2  782.84
  5027.4  782.70  5034.7  781.49  5040.8  782.64  5070.3  781.40  5105.4  781.99
  5125.4  783.65  5155.4  783.26  5175.4  785.26  5205.4  785.43  5225.4  786.93
  5255.4  786.72  5275.4  788.30  5305.4  788.10  5325.4  789.46  5386.4  790.72
#Mann=3,-1,0
  4505.8     0.1       0  4908.6    0.07       0  4914.6     0.1       0
Bank Sta=4908.6,4914.6
Exp/Cntr=0.3,0.1

Type RM Length L Ch R = 1,5623,81,81,81
BEGIN DESCRIPTION:
Mapping XS c5e0df5d
END DESCRIPTION:
XS GIS Cut Line= 4
      1998121.94     13641862.65      1998351.09     13641499.84
      1998432.68     13641390.46      1998427.49     13641068.78
#Sta/Elev= 30
  4505.4  789.46  4854.6  782.96  4918.1  779.56  4954.3  779.10  4962.7  780.01
  4968.9  778.82  4977.3  780.36  4983.5  778.36  4998.1  780.91  5001.4  777.68
  5001.9  776.88  5007.4  777.68  5012.7  779.10  5019.0  778.00  5027.3  778.95
  5033.6  777.90  5054.4  780.72  5086.4  782.22  5126.4  782.17  5146.4  784.13
  5176.5  783.51  5196.5  785.49  5226.5  785.61  5239.4  787.29  5276.5  786.93
  5286.5  788.33  5326.5  788.23  5336.5  789.53  5376.5  789.54  5392.7  790.71
#Mann=3,-1,0
  4505.4     0.1       0  5001.4    0.07       0  5007.4     0.1       0
Bank Sta=5001.4,5007.4
Exp/Cntr=0.3,0.1

Type RM Length L Ch R = 1,5542,413,413,413
BEGIN DESCRIPTION:
UNT 093 in HW 9.0
END DESCRIPTION:
XS GIS Cut Line= 3
      1998275.01     13641924.98      1998470.75     13641463.23
      1998475.00     13641074.98
#Sta/Elev= 30
  4516.5  787.62  4631.2  786.31  4731.3  784.37  4807.7  781.90  4865.9  778.60
  4918.7  777.73  4983.5  777.59  5010.4  775.94  5010.9  775.14  5015.9  775.14
  5016.4  775.94  5017.1  776.55  5036.3  778.93  5086.3  781.88  5116.3  781.60
  5136.3  783.09  5146.3  782.42  5166.3  782.41  5176.3  783.98  5186.3  784.60
  5216.3  783.98  5236.3  785.91  5266.3  785.68  5286.3  787.13  5316.3  787.00
  5326.3  787.33  5336.3  788.39  5366.3  788.17  5386.3  789.67  5406.3  789.54
#Mann=3,-1,0
  4516.5     0.1       0  5010.4    0.07       0  5016.4     0.1       0
Bank Sta=5010.4,5016.4
Exp/Cntr=0.3,0.1

Type RM Length L Ch R = 1,5129,333,333,333
BEGIN DESCRIPTION:
UNT 093 in HW 8.0
END DESCRIPTION:
XS GIS Cut Line= 3
      1998775.00     13642024.99      1998748.53     13641539.62
      1998706.86     13641032.72
#Sta/Elev= 30
  4634.8  782.99  4785.0  782.29  4825.1  781.75  4875.1  780.40  4955.3  775.61
  4975.3  773.55  4985.3  772.13  4992.3  770.44  4992.8  769.64  4997.8  769.64
  4998.3  770.44  5025.4  772.53  5055.4  772.82  5097.2  774.27  5175.7  775.43
  5366.3  781.96  5470.4  784.66  5476.7  784.90  5486.7  786.63  5496.8  785.58
  5516.8  785.42  5526.9  785.67  5536.9  787.29  5546.9  786.82  5567.0  786.80
  5577.0  787.01  5586.6  788.47  5591.7  788.50  5597.1  787.91  5629.5  788.38
#Mann=3,-1,0
  4634.8     0.1       0  4992.3    0.07       0  4998.3     0.1       0
Bank Sta=4992.3,4998.3
Exp/Cntr=0.3,0.1

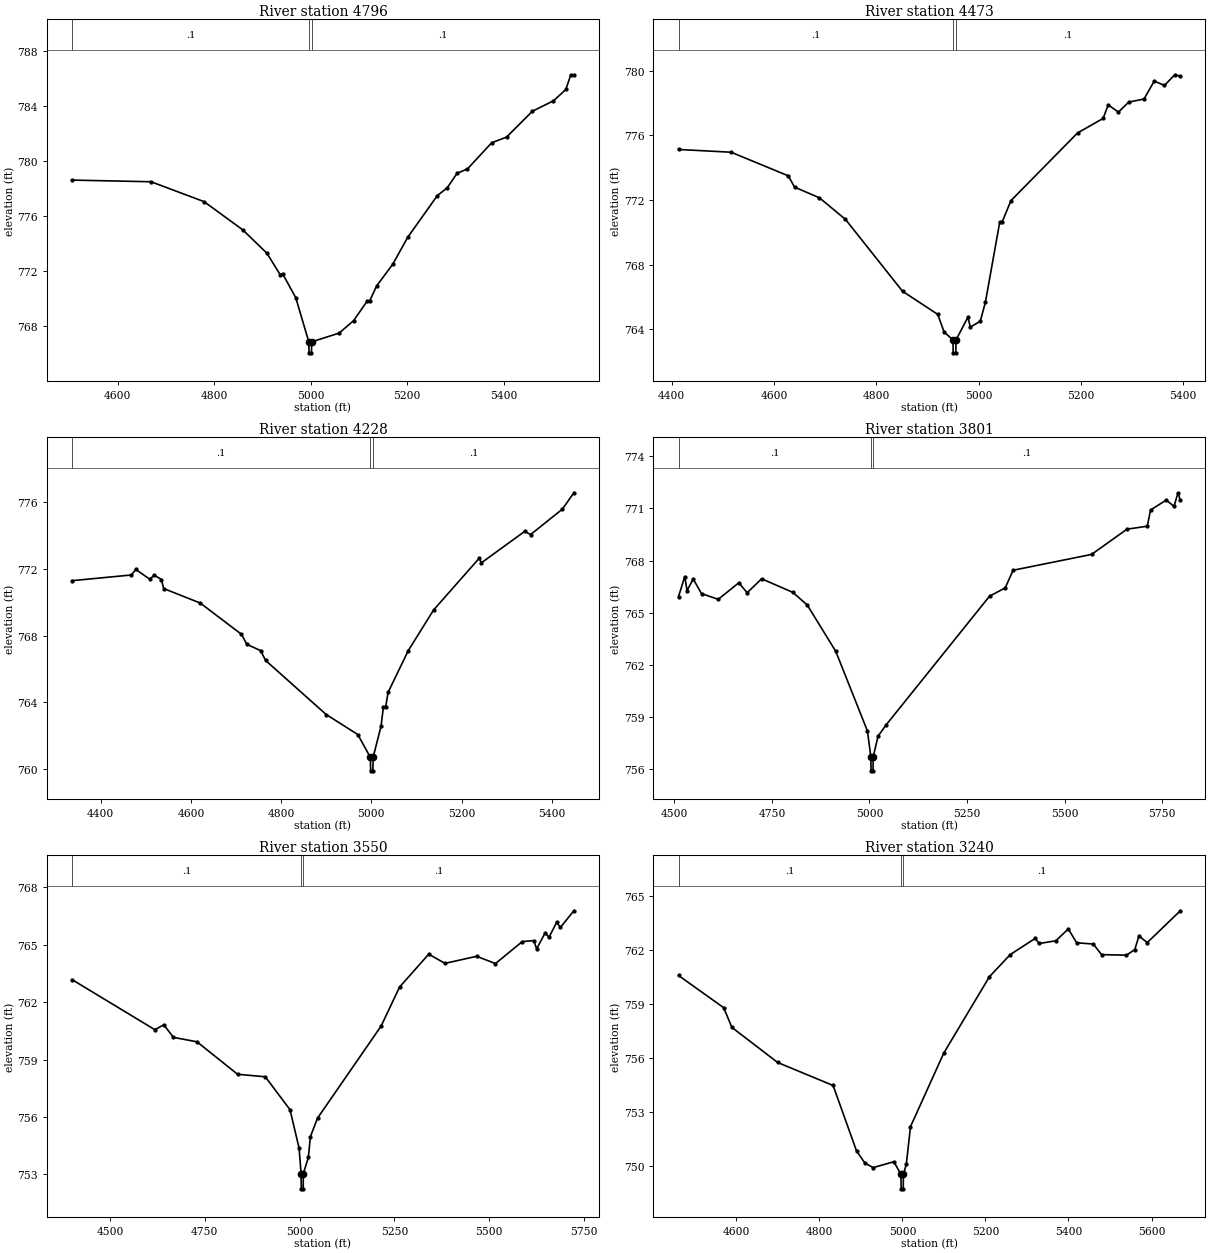
Type RM Length L Ch R = 1,4796,323,323,323
BEGIN DESCRIPTION:
UNT 093 in HW 7.0
END DESCRIPTION:
XS GIS Cut Line= 3
      1999040.19     13642018.75      1999054.08     13641404.20
      1998960.62     13640988.79
#Sta/Elev= 30
  4505.3  778.63  4669.1  778.51  4779.1  777.06  4859.1  775.01  4909.2  773.31
  4936.7  771.75  4941.7  771.82  4969.2  770.06  4996.2  766.85  4996.7  766.05
  5001.7  766.05  5002.2  766.85  5059.2  767.49  5089.2  768.40  5117.1  769.81
  5122.2  769.81  5136.6  770.91  5170.4  772.51  5201.2  774.46  5262.7  777.50
  5283.2  778.07  5303.7  779.13  5325.1  779.44  5375.4  781.35  5406.2  781.76
  5460.0  783.65  5503.3  784.40  5529.2  785.23  5539.4  786.30  5545.8  786.26
#Mann=3,-1,0
  4505.3     0.1       0  4996.2    0.07       0  5002.2     0.1       0
Bank Sta=4996.2,5002.2
Exp/Cntr=0.3,0.1

Type RM Length L Ch R = 1,4473,245,245,245
BEGIN DESCRIPTION:
UNT 093 in HW 6.0
END DESCRIPTION:
XS GIS Cut Line= 3
      1999220.76     13641956.24      1999321.44     13641390.31
      1999311.03     13640984.06
#Sta/Elev= 30
  4413.2  775.13  4516.0  774.96  4627.8  773.50  4640.1  772.80  4688.7  772.14
  4739.5  770.81  4851.2  766.36  4920.0  764.93  4932.5  763.84  4949.8  763.35
  4950.3  762.55  4955.3  762.55  4955.8  763.35  4979.0  764.75  4983.9  764.14
  5003.3  764.51  5013.3  765.69  5041.3  770.64  5046.3  770.67  5063.3  771.97
  5193.4  776.15  5243.4  777.05  5253.4  777.89  5273.4  777.44  5293.4  778.06
  5323.4  778.25  5343.4  779.36  5363.4  779.09  5383.5  779.75  5394.4  779.66
#Mann=3,-1,0
  4413.2     0.1       0  4949.8    0.07       0  4955.8     0.1       0
Bank Sta=4949.8,4955.8
Exp/Cntr=0.3,0.1

Type RM Length L Ch R = 1,4228,427,427,427
BEGIN DESCRIPTION:
UNT 093 in HW 5.0
END DESCRIPTION:
XS GIS Cut Line= 3
      1999356.17     13642122.93      1999508.94     13641449.34
      1999550.57     13641029.59
#Sta/Elev= 30
  4336.6  771.29  4467.8  771.63  4478.0  771.96  4508.8  771.38  4519.0  771.62
  4534.6  771.36  4539.7  770.82  4620.8  769.95  4712.2  768.08  4724.1  767.48
  4754.9  767.10  4765.5  766.52  4900.0  763.28  4970.2  762.08  4998.0  760.71
  4998.5  759.91  5003.5  759.91  5004.0  760.71  5021.5  762.57  5027.0  763.75
  5032.0  763.75  5037.3  764.61  5081.9  767.10  5138.2  769.54  5239.2  772.63
  5244.2  772.36  5340.1  774.24  5353.2  774.05  5423.6  775.57  5449.1  776.55
#Mann=3,-1,0
  4336.6     0.1       0  4998.0    0.07       0  5004.0     0.1       0
Bank Sta=4998,5004
Exp/Cntr=0.3,0.1

Type RM Length L Ch R = 1,3801,251,251,251
BEGIN DESCRIPTION:
UNT 093 in HW 4.0
END DESCRIPTION:
XS GIS Cut Line= 3
      1999470.76     13642181.97      1999797.14     13641629.89
      1999869.88     13640989.04
#Sta/Elev= 30
  4510.6  765.93  4526.6  767.08  4532.4  766.27  4548.1  766.94  4569.5  766.10
  4612.4  765.77  4665.1  766.72  4686.5  766.15  4723.6  766.95  4803.6  766.17
  4840.7  765.44  4913.7  762.78  4994.8  758.21  5003.6  756.72  5004.1  755.92
  5009.1  755.92  5009.6  756.72  5022.0  757.91  5043.5  758.58  5307.8  765.95
  5348.1  766.43  5368.2  767.44  5569.5  768.35  5660.1  769.80  5712.3  769.97
  5720.5  770.90  5760.7  771.47  5780.8  771.11  5790.9  771.89  5796.9  771.46
#Mann=3,-1,0
  4510.6     0.1       0  5003.6    0.07       0  5009.6     0.1       0
Bank Sta=5003.6,5009.6
Exp/Cntr=0.3,0.1

Type RM Length L Ch R = 1,3550,310,310,310
BEGIN DESCRIPTION:
Mapping XS 25d353d4
END DESCRIPTION:
XS GIS Cut Line= 4
      1999499.03     13642229.31      1999846.15     13642106.90
      2000088.81     13641494.48      2000061.06     13641199.69
#Sta/Elev= 30
  4400.0  763.18  4618.4  760.56  4641.7  760.82  4667.3  760.16  4729.2  759.93
  4836.4  758.23  4909.4  758.10  4974.5  756.38  4998.5  754.37  5003.8  753.04
  5004.3  752.24  5009.3  752.24  5009.8  753.04  5022.9  753.88  5028.3  754.97
  5047.2  755.94  5214.7  760.75  5263.4  762.79  5340.2  764.51  5383.2  764.03
  5466.5  764.40  5516.2  764.02  5587.0  765.17  5617.1  765.22  5624.8  764.79
  5647.3  765.63  5657.3  765.39  5677.4  766.17  5687.4  765.91  5722.9  766.78
#Mann=3,-1,0
  4400.0     0.1       0  5003.8    0.07       0  5009.8     0.1       0
Bank Sta=5003.8,5009.8
Exp/Cntr=0.3,0.1

Type RM Length L Ch R = 1,3240,244,244,244
BEGIN DESCRIPTION:
Mapping XS 9ac3e81c
END DESCRIPTION:
XS GIS Cut Line= 2
      2000248.53     13642473.60      2000220.75     13641265.31
#Sta/Elev= 30
  4460.8  760.59  4569.4  758.80  4589.4  757.70  4699.5  755.75  4833.1  754.47
  4889.5  750.83  4909.5  750.16  4929.5  749.90  4979.5  750.23  4996.5  749.52
  4997.0  748.72  5002.0  748.72  5002.5  749.52  5009.5  750.10  5019.5  752.18
  5099.6  756.27  5209.6  760.52  5259.6  761.75  5319.6  762.65  5329.6  762.37
  5369.6  762.52  5399.6  763.18  5419.6  762.41  5459.7  762.34  5479.7  761.75
  5539.7  761.72  5559.7  762.03  5569.7  762.79  5589.7  762.42  5669.4  764.19
#Mann=3,-1,0
  4460.8     0.1       0  4996.5    0.07       0  5002.5     0.1       0
Bank Sta=4996.5,5002.5
Exp/Cntr=0.3,0.1

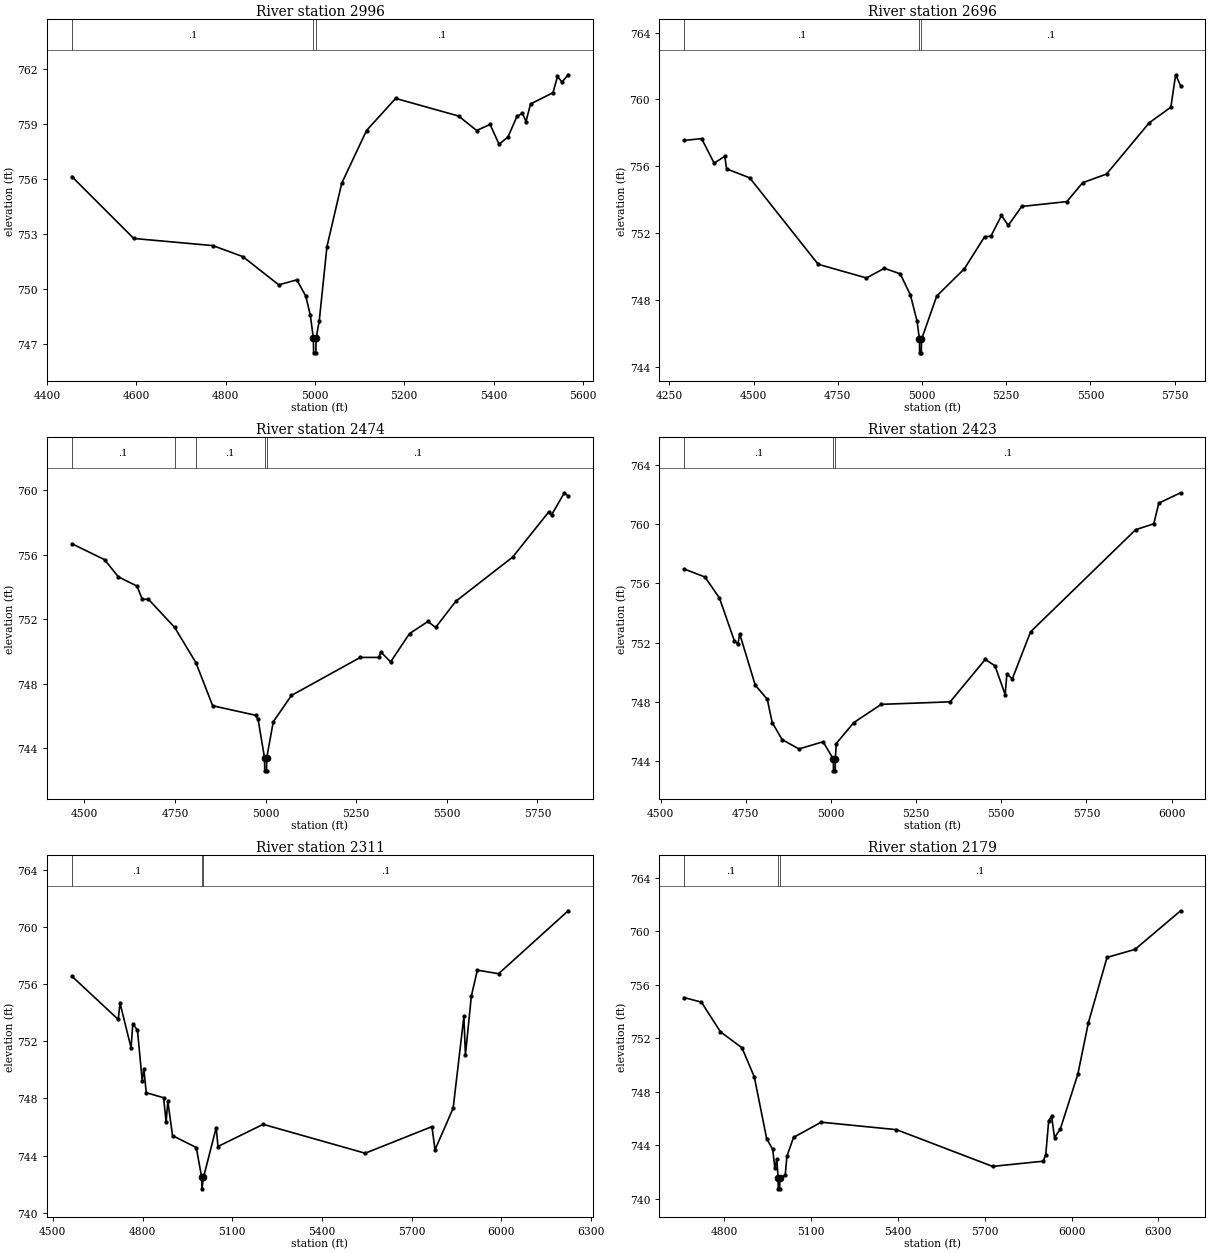
Type RM Length L Ch R = 1,2996,300,300,300
BEGIN DESCRIPTION:
Mapping XS 4e948e33
END DESCRIPTION:
XS GIS Cut Line= 2
      2000526.31     13642435.49      2000397.83     13641331.24
#Sta/Elev= 30
  4455.4  756.15  4594.2  752.77  4771.3  752.38  4838.5  751.78  4919.0  750.24
  4959.3  750.51  4979.4  749.63  4989.5  748.60  4996.5  747.33  4997.0  746.53
  5002.0  746.53  5002.5  747.33  5009.6  748.27  5026.9  752.33  5059.9  755.78
  5115.5  758.66  5180.7  760.41  5321.7  759.45  5362.0  758.66  5392.2  758.99
  5412.3  757.91  5432.4  758.31  5452.6  759.44  5464.7  759.59  5472.7  759.15
  5482.8  760.11  5533.1  760.72  5543.2  761.61  5553.3  761.30  5567.1  761.70
#Mann=3,-1,0
  4455.4     0.1       0  4996.5    0.07       0  5002.5     0.1       0
Bank Sta=4996.5,5002.5
Exp/Cntr=0.3,0.1

Type RM Length L Ch R = 1,2696,222,222,222
BEGIN DESCRIPTION:
Mapping XS bc29fa59
END DESCRIPTION:
XS GIS Cut Line= 4
      2000557.70     13642685.58      2000739.90     13642293.35
      2000696.44     13641595.17      2000446.45     13641362.54
#Sta/Elev= 30
  4294.0  757.54  4345.6  757.65  4382.8  756.18  4414.3  756.59  4419.8  755.84
  4488.5  755.30  4691.6  750.13  4835.0  749.31  4888.0  749.89  4935.2  749.56
  4965.3  748.30  4985.3  746.72  4992.3  745.63  4992.8  744.83  4997.8  744.83
  4998.3  745.63  5043.6  748.23  5125.6  749.86  5185.7  751.78  5204.3  751.81
  5235.8  753.05  5255.9  752.46  5295.9  753.59  5429.8  753.88  5476.7  755.01
  5547.6  755.53  5674.6  758.60  5738.6  759.53  5752.8  761.47  5767.5  760.82
#Mann=3,-1,0
  4294.0     0.1       0  4992.3    0.07       0  4998.3     0.1       0
Bank Sta=4992.3,4998.3
Exp/Cntr=0.3,0.1

Type RM Length L Ch R = 1,2474,51,51,51
BEGIN DESCRIPTION:
Mapping XS ca25554a
END DESCRIPTION:
XS GIS Cut Line= 3
      2001095.88     13642557.13      2000811.03     13641612.53
      2000512.38     13641372.92
#Sta/Elev= 30
  4465.4  756.69  4555.7  755.70  4593.9  754.63  4645.2  754.06  4659.9  753.23
  4676.5  753.25  4749.3  751.49  4807.9  749.30  4854.1  746.63  4972.4  746.04
  4979.4  745.78  4997.2  743.39  4997.7  742.59  5002.7  742.59  5003.2  743.39
  5021.2  745.63  5071.4  747.27  5261.4  749.63  5312.7  749.63  5318.0  749.97
  5345.0  749.35  5397.2  751.11  5448.1  751.86  5469.1  751.49  5525.1  753.12
  5681.9  755.86  5781.2  758.66  5789.2  758.48  5824.4  759.85  5834.9  759.66
#Mann=5,-1,0
  4465.4     0.1       0  4749.3    0.12       0  4807.9     0.1       0
  4997.2    0.07       0  5003.2     0.1       0
Bank Sta=4997.2,5003.2
Exp/Cntr=0.3,0.1

Type RM Length L Ch R = 1,2423,112,112,112
BEGIN DESCRIPTION:
UNT 093 in HW 3.0
END DESCRIPTION:
XS GIS Cut Line= 6
      2001199.93     13642421.59      2001127.00     13642237.53
      2000995.06     13642067.39      2000967.28     13641921.56
      2000908.25     13641529.20      2000468.62     13641293.81
#Sta/Elev= 30
  4569.1  756.98  4630.0  756.44  4672.6  755.01  4716.0  752.14  4726.6  751.88
  4732.0  752.59  4777.6  749.12  4812.9  748.16  4827.3  746.59  4856.3  745.44
  4906.1  744.80  4976.7  745.29  5006.8  744.12  5007.3  743.32  5012.3  743.32
  5012.8  744.12  5015.4  745.17  5067.1  746.59  5147.6  747.82  5349.8  747.99
  5452.8  750.86  5481.3  750.43  5511.3  748.48  5516.3  749.87  5532.3  749.55
  5585.9  752.73  5894.3  759.64  5947.5  760.04  5962.3  761.44  6026.3  762.14
#Mann=3,-1,0
  4569.1     0.1       0  5006.8    0.07       0  5012.8     0.1       0
Bank Sta=5006.8,5012.8
Exp/Cntr=0.3,0.1

Type RM Length L Ch R = 1,2311,132,132,132
BEGIN DESCRIPTION:
UNT 093 in HW 2.0
END DESCRIPTION:
XS GIS Cut Line= 6
      2001321.45     13642449.35      2001057.56     13642011.84
      2001015.89     13641720.17      2001022.83     13641532.67
      2001040.19     13641327.81      2000585.37     13641254.90
#Sta/Elev= 30
  4563.6  756.55  4718.9  753.52  4724.7  754.67  4761.8  751.54  4767.6  753.23
  4783.2  752.76  4798.9  749.25  4804.7  750.06  4812.4  748.40  4870.5  748.05
  4878.9  746.36  4884.7  747.80  4900.4  745.40  4979.7  744.57  4997.9  742.48
  4998.4  741.68  5003.9  742.48  5046.4  745.96  5052.3  744.64  5203.3  746.19
  5544.5  744.17  5767.7  746.03  5777.9  744.41  5838.6  747.32  5874.5  753.74
  5879.6  751.04  5899.4  755.16  5919.6  756.97  5990.5  756.72  6223.1  761.12
#Mann=3,-1,0
  4563.6     0.1       0  4997.9    0.07       0  5003.9     0.1       0
Bank Sta=4997.9,5003.9
Exp/Cntr=0.3,0.1

Type RM Length L Ch R = 1,2179,617,617,617
BEGIN DESCRIPTION:
Mapping XS d8165c34
END DESCRIPTION:
XS GIS Cut Line= 6
      2001376.99     13642407.65      2001328.39     13642247.95
      2001140.89     13641987.53      2001106.17     13641577.81
      2001130.47     13641296.56      2000602.72     13641230.59
#Sta/Elev= 30
  4661.7  755.05  4721.0  754.71  4786.7  752.49  4861.2  751.29  4903.8  749.11
  4946.5  744.49  4967.4  743.68  4974.9  742.28  4981.6  742.96  4986.1  741.53
  4986.6  740.73  4991.6  740.73  4992.1  741.53  5010.7  741.76  5016.5  743.17
  5039.4  744.58  5134.9  745.72  5395.1  745.16  5727.1  742.41  5901.8  742.80
  5910.8  743.28  5920.9  745.82  5931.0  746.17  5941.1  744.57  5961.2  745.21
  6021.7  749.32  6058.0  753.16  6122.5  758.06  6219.2  758.66  6376.7  761.55
#Mann=3,-1,0
  4661.7     0.1       0  4986.1    0.07       0  4992.1     0.1       0
Bank Sta=4986.1,4992.1
Exp/Cntr=0.3,0.1

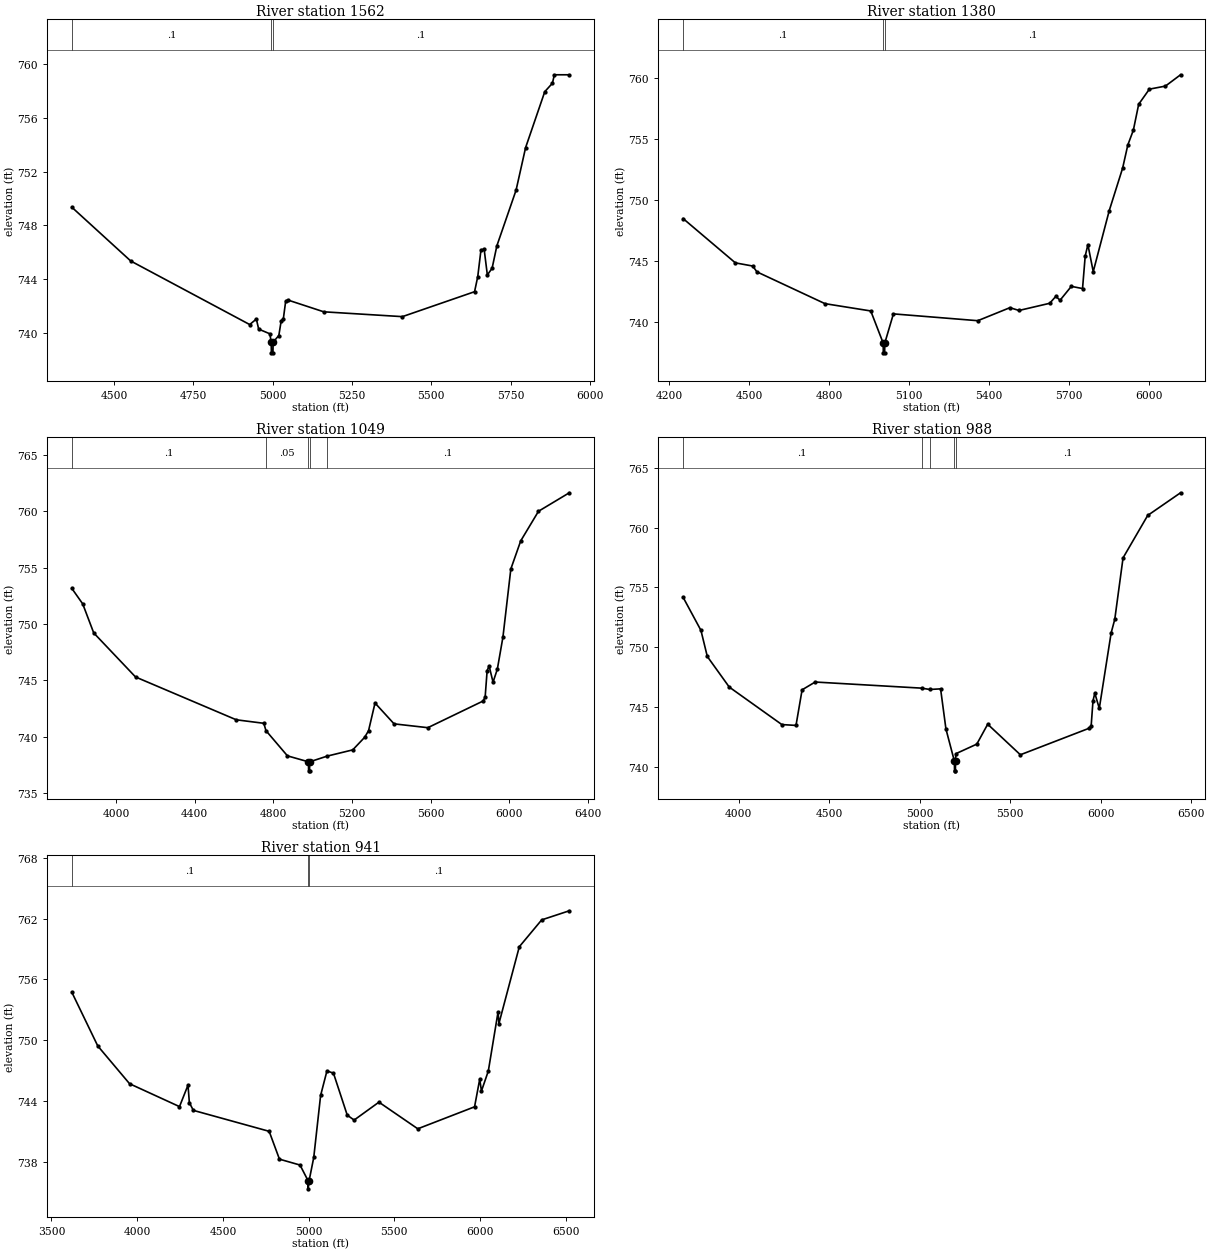
Type RM Length L Ch R = 1,1562,182,182,182
BEGIN DESCRIPTION:
Mapping XS a2039189
END DESCRIPTION:
XS GIS Cut Line= 5
      2001456.85     13642258.40      2001630.47     13641803.51
      2001165.19     13641303.51      2001102.69     13641268.78
      2000778.12     13641234.25
#Sta/Elev= 30
  4367.1  749.35  4552.7  745.34  4927.6  740.60  4948.6  741.01  4955.9  740.26
  4991.1  739.91  4995.4  739.29  4995.9  738.49  5000.9  738.49  5001.4  739.29
  5019.4  739.78  5026.8  740.87  5033.6  741.02  5040.9  742.32  5047.8  742.43
  5161.1  741.55  5408.8  741.19  5636.3  743.05  5646.4  744.18  5656.5  746.17
  5666.5  746.22  5676.6  744.30  5691.6  744.80  5706.7  746.48  5767.1  750.62
  5797.2  753.80  5857.6  757.97  5881.7  758.60  5887.8  759.23  5934.9  759.23
#Mann=3,-1,0
  4367.1     0.1       0  4995.4    0.07       0  5001.4     0.1       0
Bank Sta=4995.4,5001.4
Exp/Cntr=0.3,0.1

Type RM Length L Ch R = 1,1380,331,331,331
BEGIN DESCRIPTION:
Mapping XS abbdd6e6
END DESCRIPTION:
XS GIS Cut Line= 5
      2001512.43     13642258.34      2001804.08     13641741.01
      2001484.64     13641414.62      2001113.11     13641244.48
      2000708.47     13641216.81
#Sta/Elev= 30
  4253.0  748.48  4449.0  744.84  4513.9  744.58  4529.9  744.10  4784.9  741.49
  4956.5  740.89  5003.1  738.25  5003.6  737.45  5008.6  737.45  5009.1  738.25
  5041.4  740.65  5357.7  740.09  5478.2  741.16  5512.2  740.93  5627.3  741.52
  5650.3  742.09  5666.1  741.77  5708.4  742.91  5750.4  742.73  5760.4  745.40
  5770.5  746.34  5790.5  744.12  5850.6  749.14  5900.8  752.63  5920.1  754.52
  5940.9  755.74  5960.9  757.87  6001.0  759.11  6061.1  759.36  6117.8  760.29
#Mann=3,-1,0
  4253.0     0.1       0  5003.1    0.07       0  5009.1     0.1       0
Bank Sta=5003.1,5009.1
Exp/Cntr=0.3,0.1

Type RM Length L Ch R = 1,1049,61,61,61
BEGIN DESCRIPTION:
Mapping XS c09cc1fd
END DESCRIPTION:
XS GIS Cut Line= 4
      2001422.12     13642369.50      2001887.42     13641963.23
      2001873.53     13641272.26      2000659.16     13641154.29
#Sta/Elev= 30
  3775.9  753.17  3831.1  751.80  3887.1  749.22  4099.7  745.31  4611.9  741.51
  4751.9  741.20  4762.6  740.55  4871.9  738.31  4978.9  737.78  4979.4  736.98
  4984.4  736.98  4984.9  737.78  5074.5  738.29  5203.8  738.84  5264.1  739.95
  5284.2  740.54  5317.1  743.00  5414.0  741.15  5585.6  740.81  5866.9  743.18
  5877.0  743.53  5887.0  745.86  5897.0  746.30  5917.1  744.85  5938.9  746.00
  5967.4  748.85  6007.6  754.90  6057.8  757.39  6148.2  760.02  6304.8  761.66
#Mann=5,-1,0
  3775.9     0.1       0  4762.6    0.05       0  4978.9   0.033       0
  4984.9    0.05       0  5074.5     0.1       0
Bank Sta=4978.9,4984.9
Exp/Cntr=0.3,0.1

Type RM Length L Ch R = 1,988,47,47,47
BEGIN DESCRIPTION:
Mapping XS 2b7d93e2
END DESCRIPTION:
XS GIS Cut Line= 4
      2001415.18     13642393.80      2001925.61     13641973.64
      2001929.08     13641216.70      2000602.66     13641116.00
#Sta/Elev= 30
  3692.7  754.18  3791.3  751.42  3826.5  749.24  3947.7  746.69  4238.3  743.56
  4316.5  743.49  4350.2  746.46  4422.5  747.11  5009.9  746.60  5055.8  746.49
  5115.3  746.54  5144.9  743.19  5191.7  740.50  5192.2  739.70  5197.2  739.70
  5197.7  740.50  5199.7  741.13  5315.4  741.93  5375.6  743.59  5556.1  741.04
  5937.2  743.26  5947.2  743.46  5957.3  745.54  5967.3  746.18  5992.1  744.91
  6057.6  751.21  6077.6  752.34  6123.4  757.47  6259.6  761.01  6441.0  762.90
#Mann=5,-1,0
  3692.7     0.1       0  5009.9    0.05       0  5055.8     0.1       0
  5191.7    0.07       0  5197.7     0.1       0
Bank Sta=5191.7,5197.7
Exp/Cntr=0.3,0.1

Type RM Length L Ch R = 1,941,0,0,0
BEGIN DESCRIPTION:
UNT 093 in HW 1.0
END DESCRIPTION:
XS GIS Cut Line= 4
      2001408.23     13642421.58      2001960.33     13641977.12
      2001970.75     13641195.87      2000564.48     13641074.34
#Sta/Elev= 30
  3619.0  754.73  3770.2  749.43  3955.7  745.70  4246.9  743.44  4296.5  745.56
  4304.4  743.83  4327.6  743.07  4769.9  741.00  4829.9  738.25  4949.9  737.67
  4996.9  736.12  4997.4  735.32  5002.9  736.12  5030.0  738.42  5070.0  744.54
  5107.0  746.97  5145.0  746.74  5225.3  742.60  5265.4  742.11  5410.2  743.88
  5636.8  741.25  5968.0  743.42  5998.1  746.15  6008.2  744.98  6048.3  746.96
  6105.0  752.79  6110.0  751.64  6229.0  759.23  6359.5  761.88  6520.6  762.78
#Mann=3,-1,0
  3619.0     0.1       0  4996.9    0.07       0  5002.9     0.1       0
Bank Sta=4996.9,5002.9
Exp/Cntr=0.3,0.1

Chan Stop Cuts=-1