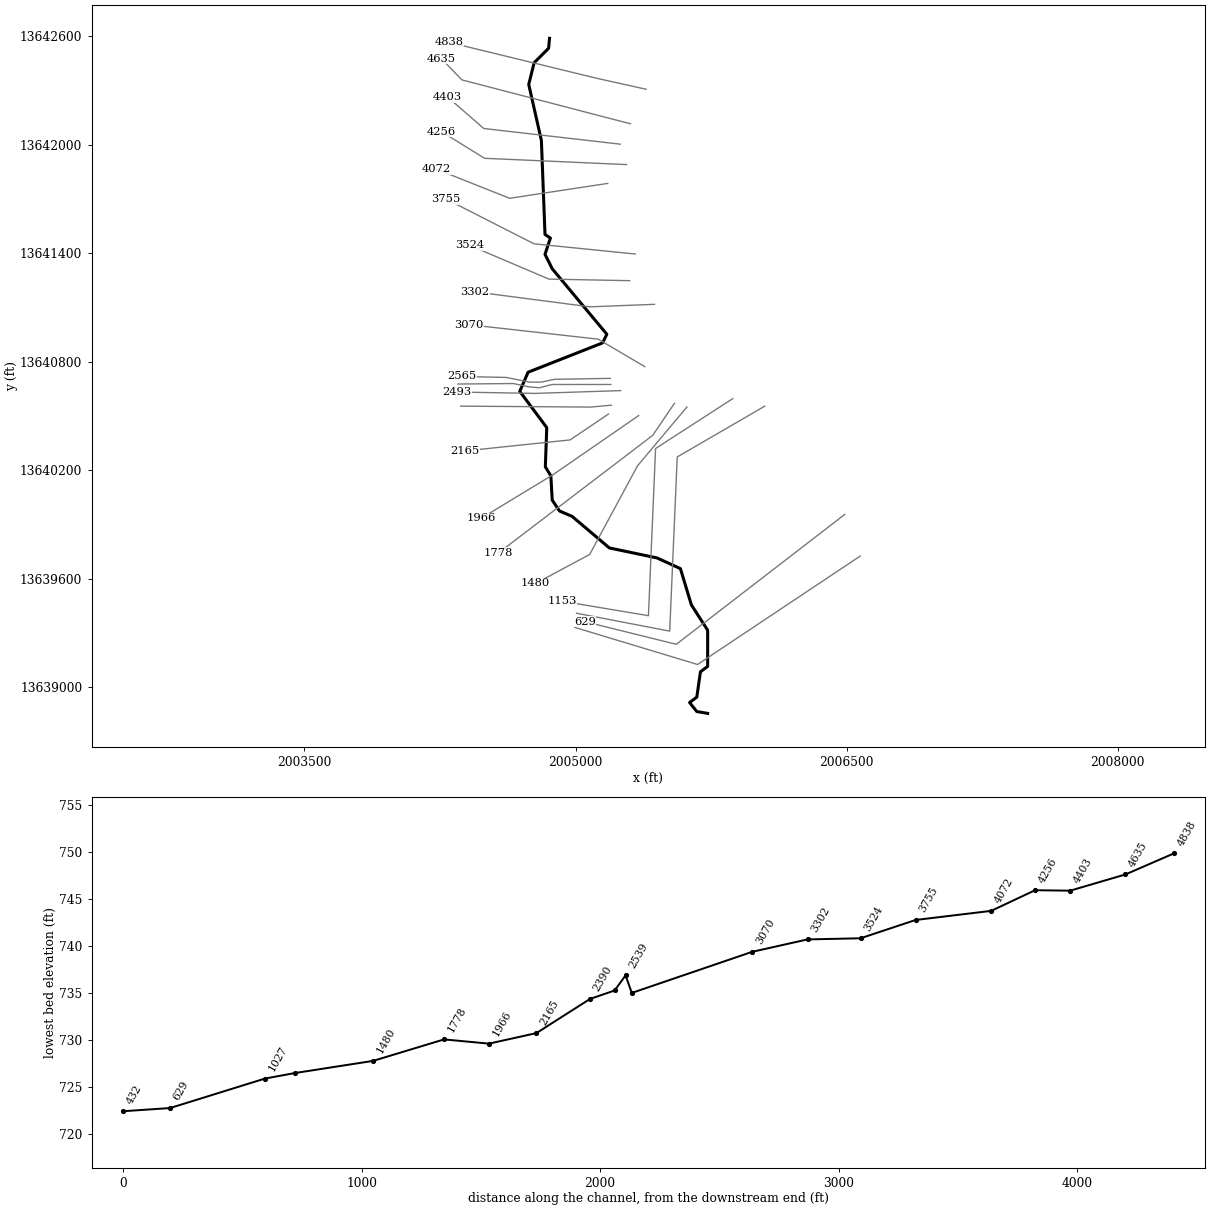
--- UNT 094 in HW.prj (project) ---

Proj Title=UNT 094 in HW Base Level Engineering
Current Plan=p01
Default Exp/Contr=0.3,0.1
English Units
Geom File=g01
Flow File=f01
Plan File=p01
BEGIN DESCRIPTION:
UNT 094 in HW
END DESCRIPTION:

--- UNT 094 in HW.p01 (plan) ---

Plan Title=Multiple Run
Short Identifier=Multiple
Geom File=g01
Flow File=f01
Subcritical Flow
K Sum by GR= 0
Std Step Tol= 0.01
Critical Tol= 0.01
Num of Std Step Trials= 20
Max Error Tol= 0.3
Flow Tol Ratio= 0.001
Split Flow NTrial= 30
Split Flow Tol= 0.02
Split Flow Ratio= 0.02
Log Output Level= 0
Friction Slope Method= 1
Unsteady Friction Slope Method= 2
Unsteady Bridges Friction Slope Method= 1
Parabolic Critical Depth
Global Vel Dist=  1 , 1 , 1
Global Log Level= 0
CheckData=True
Encroach Param= -1, 0, 0, 0
BEGIN DESCRIPTION:
Multiple Run
END DESCRIPTION:

--- UNT 094 in HW.f01 (steady flow) ---

Flow Title=Multiple
Number of Profiles=7
Profile Names=10-year,25-year,50-year,1pct_min,100-year,1pct_plu,500-year
River Rch & RM= UNT 094 in HW,Reach-1,4838
     608     857    1066     657    1312    2617    1991
Boundary for River Rch & Prof#=UNT 094 in HW,Reach-1,1
Up Type=0
Dn Type=3
Dn Slope=0.005
Boundary for River Rch & Prof#=UNT 094 in HW,Reach-1,2
Up Type=0
Dn Type=3
Dn Slope=0.005
Boundary for River Rch & Prof#=UNT 094 in HW,Reach-1,3
Up Type=0
Dn Type=3
Dn Slope=0.005
Boundary for River Rch & Prof#=UNT 094 in HW,Reach-1,4
Up Type=0
Dn Type=3
Dn Slope=0.005
Boundary for River Rch & Prof#=UNT 094 in HW,Reach-1,5
Up Type=0
Dn Type=3
Dn Slope=0.005
Boundary for River Rch & Prof#=UNT 094 in HW,Reach-1,6
Up Type=0
Dn Type=3
Dn Slope=0.005
Boundary for River Rch & Prof#=UNT 094 in HW,Reach-1,7
Up Type=0
Dn Type=3
Dn Slope=0.005

--- UNT 094 in HW.g01 (geometry) ---

Geom Title=Existing Conditions

River Reach=UNT 094 in HW,Reach-1
Reach XY= 30
      2004855.80     13642589.54      2004850.80     13642534.54
      2004770.80     13642454.54      2004740.80     13642334.54
      2004810.80     13642024.54      2004830.80     13641504.54
      2004860.80     13641484.54      2004830.80     13641394.54
      2004870.80     13641314.54      2005172.95     13640952.22
      2005149.51     13640904.48      2004737.19     13640742.15
      2004691.18     13640636.25      2004840.49     13640435.73
      2004832.67     13640218.71      2004863.06     13640169.23
      2004870.80     13640034.54      2004910.80     13639974.54
      2004980.80     13639944.54      2005186.84     13639769.93
      2005450.80     13639714.54      2005580.07     13639655.34
      2005640.80     13639454.54      2005730.80     13639314.54
      2005730.80     13639114.54      2005690.80     13639084.54
      2005670.80     13638944.54      2005630.80     13638914.54
      2005670.80     13638864.54      2005730.80     13638854.54

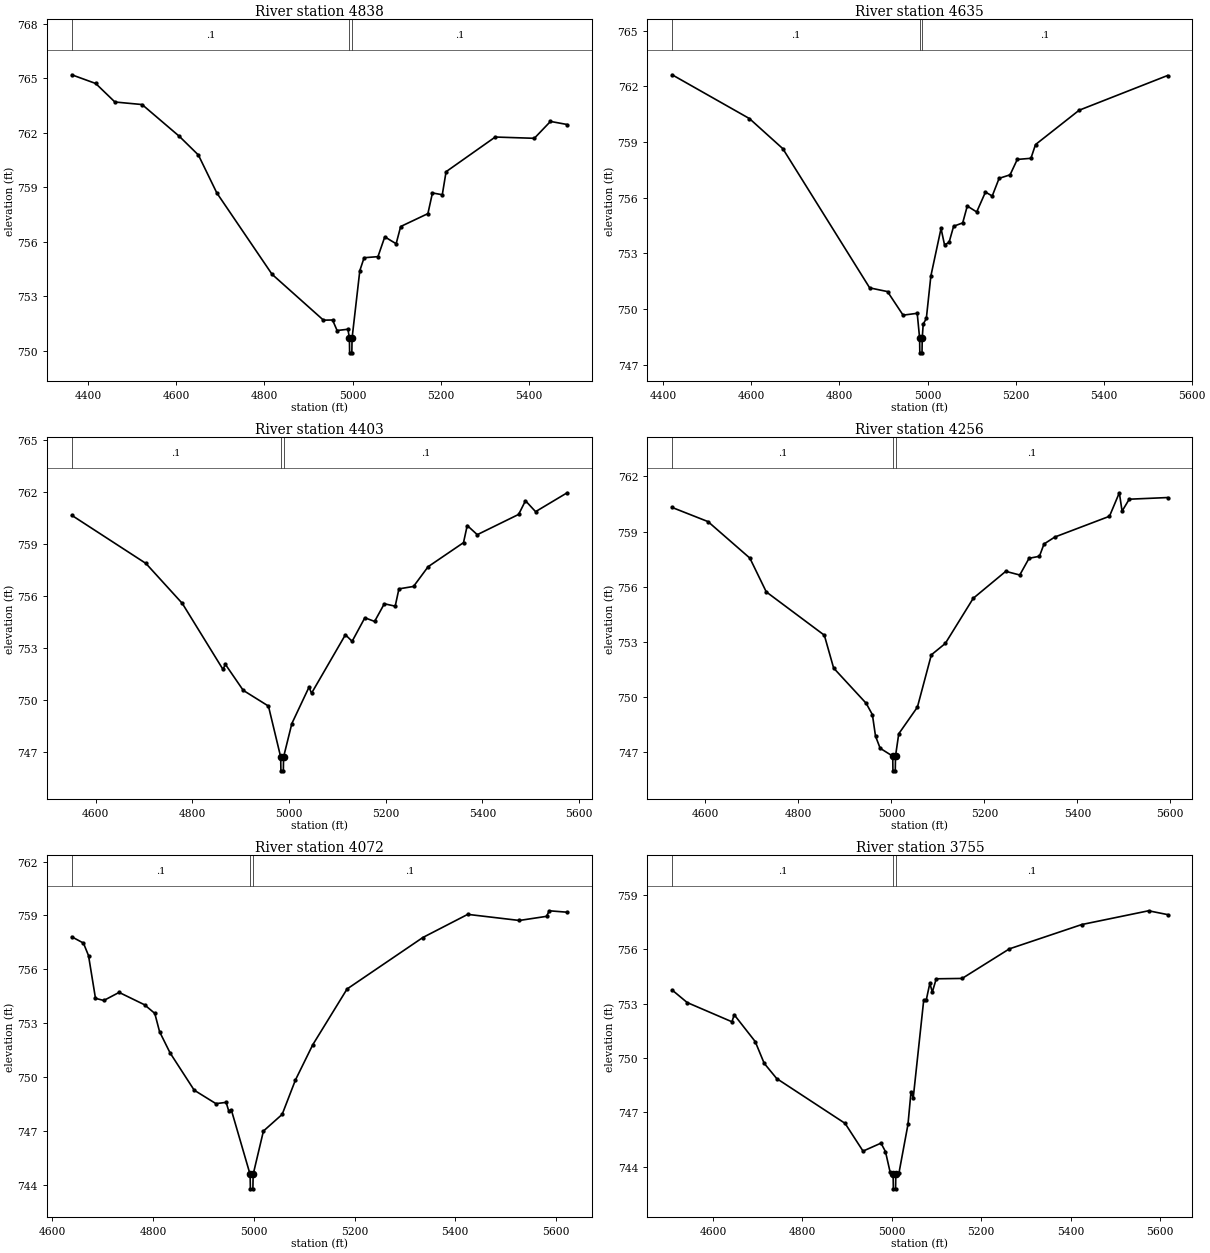
Type RM Length L Ch R = 1,4838,203,203,203
BEGIN DESCRIPTION:
UNT 094 in HW 9.0
END DESCRIPTION:
XS GIS Cut Line= 3
      2005390.62     13642307.71      2005117.15     13642368.48
      2004298.39     13642567.75
#Sta/Elev= 30
  4363.4  765.20  4417.7  764.72  4461.2  763.70  4522.8  763.56  4607.2  761.81
  4650.4  760.78  4692.2  758.69  4817.3  754.21  4933.9  751.68  4954.5  751.69
  4964.8  751.11  4989.4  751.18  4992.7  750.68  4993.2  749.88  4998.2  749.88
  4998.7  750.68  5016.3  754.41  5026.0  755.12  5057.4  755.18  5072.9  756.27
  5098.6  755.89  5108.9  756.84  5170.6  757.55  5180.9  758.69  5203.2  758.59
  5211.8  759.86  5323.2  761.77  5411.8  761.70  5448.4  762.63  5486.2  762.46
#Mann=3,-1,0
  4363.4     0.1       0  4992.7    0.07       0  4998.7     0.1       0
Bank Sta=4992.7,4998.7
Exp/Cntr=0.3,0.1

Type RM Length L Ch R = 1,4635,232,232,232
BEGIN DESCRIPTION:
Mapping XS f6100599
END DESCRIPTION:
XS GIS Cut Line= 3
      2005303.73     13642116.75      2004370.62     13642359.80
      2004258.91     13642475.81
#Sta/Elev= 30
  4419.9  762.62  4595.5  760.26  4671.3  758.64  4868.6  751.14  4909.1  750.94
  4944.5  749.67  4976.6  749.77  4982.0  748.44  4982.5  747.64  4987.5  747.64
  4988.0  748.44  4990.2  749.19  4997.3  749.49  5007.6  751.78  5030.7  754.34
  5038.6  753.46  5048.9  753.59  5059.3  754.46  5079.9  754.64  5090.3  755.55
  5111.7  755.23  5131.6  756.30  5147.0  756.09  5162.6  757.04  5187.5  757.23
  5203.9  758.06  5234.9  758.12  5245.3  758.86  5344.4  760.71  5545.2  762.58
#Mann=3,-1,0
  4419.9     0.1       0  4982.0    0.07       0  4988.0     0.1       0
Bank Sta=4982,4988
Exp/Cntr=0.3,0.1

Type RM Length L Ch R = 1,4403,147,147,147
BEGIN DESCRIPTION:
Mapping XS 4bf140ff
END DESCRIPTION:
XS GIS Cut Line= 3
      2005247.36     13642003.90      2004492.15     13642090.70
      2004292.47     13642264.34
#Sta/Elev= 30
  4550.5  760.67  4703.9  757.89  4779.2  755.58  4863.3  751.77  4868.3  752.06
  4905.2  750.56  4957.4  749.65  4982.7  746.71  4983.2  745.91  4988.2  745.91
  4988.7  746.71  5005.8  748.64  5041.4  750.75  5046.5  750.39  5116.6  753.77
  5130.5  753.39  5156.8  754.75  5177.0  754.54  5197.1  755.56  5219.6  755.42
  5227.3  756.42  5257.5  756.56  5287.7  757.70  5360.9  759.09  5368.6  760.08
  5389.4  759.55  5474.9  760.72  5489.1  761.51  5510.0  760.88  5575.3  761.97
#Mann=3,-1,0
  4550.5     0.1       0  4982.7    0.07       0  4988.7     0.1       0
Bank Sta=4982.7,4988.7
Exp/Cntr=0.3,0.1

Type RM Length L Ch R = 1,4256,184,184,184
BEGIN DESCRIPTION:
Mapping XS d8a2ac5e
END DESCRIPTION:
XS GIS Cut Line= 3
      2005282.04     13641891.05      2004496.49     13641925.77
      2004258.85     13642072.68
#Sta/Elev= 30
  4528.3  760.31  4605.4  759.54  4695.5  757.55  4730.8  755.71  4855.7  753.35
  4875.7  751.56  4945.7  749.64  4959.1  749.02  4965.8  747.85  4975.8  747.19
  5002.8  746.76  5003.3  745.96  5008.3  745.96  5008.8  746.76  5015.8  747.98
  5055.9  749.43  5085.9  752.28  5115.9  752.90  5176.0  755.36  5246.0  756.83
  5276.1  756.63  5296.1  757.54  5318.4  757.65  5328.3  758.32  5351.6  758.70
  5469.1  759.83  5490.3  761.11  5496.2  760.11  5511.6  760.76  5594.0  760.85
#Mann=3,-1,0
  4528.3     0.1       0  5002.8    0.07       0  5008.8     0.1       0
Bank Sta=5002.8,5008.8
Exp/Cntr=0.3,0.1

Type RM Length L Ch R = 1,4072,317,317,317
BEGIN DESCRIPTION:
Mapping XS c8a0fbe5
END DESCRIPTION:
XS GIS Cut Line= 3
      2005177.90     13641786.88      2004635.38     13641704.42
      2004231.70     13641865.02
#Sta/Elev= 30
  4638.8  757.81  4662.0  757.46  4672.1  756.76  4685.9  754.38  4702.4  754.26
  4732.8  754.71  4783.3  754.02  4803.6  753.54  4813.1  752.52  4833.9  751.34
  4881.8  749.26  4924.9  748.51  4945.2  748.58  4950.5  748.09  4955.6  748.15
  4992.8  744.56  4993.3  743.76  4998.3  743.76  4998.8  744.56  5019.2  746.98
  5056.4  747.91  5082.8  749.83  5117.1  751.79  5185.2  754.90  5335.6  757.77
  5424.7  759.06  5527.1  758.72  5581.1  758.95  5586.5  759.26  5622.0  759.18
#Mann=3,-1,0
  4638.8     0.1       0  4992.8    0.07       0  4998.8     0.1       0
Bank Sta=4992.8,4998.8
Exp/Cntr=0.3,0.1

Type RM Length L Ch R = 1,3755,231,231,231
BEGIN DESCRIPTION:
Mapping XS f0d41e67
END DESCRIPTION:
XS GIS Cut Line= 3
      2005329.82     13641396.26      2004769.92     13641452.68
      2004283.88     13641700.04
#Sta/Elev= 30
  4508.5  753.75  4542.2  753.06  4642.3  752.00  4647.3  752.39  4694.3  750.91
  4714.4  749.71  4742.4  748.87  4895.3  746.40  4935.5  744.87  4975.7  745.31
  4985.7  744.84  4995.8  743.74  5002.8  743.59  5003.3  742.79  5008.3  742.79
  5008.8  743.59  5015.9  743.67  5036.0  746.34  5042.7  748.11  5047.8  747.81
  5071.2  753.19  5076.8  753.19  5084.9  754.12  5090.5  753.64  5099.2  754.37
  5157.2  754.39  5262.8  756.02  5424.6  757.36  5574.2  758.12  5616.6  757.91
#Mann=3,-1,0
  4508.5     0.1       0  5002.8    0.07       0  5008.8     0.1       0
Bank Sta=5002.8,5008.8
Exp/Cntr=0.3,0.1

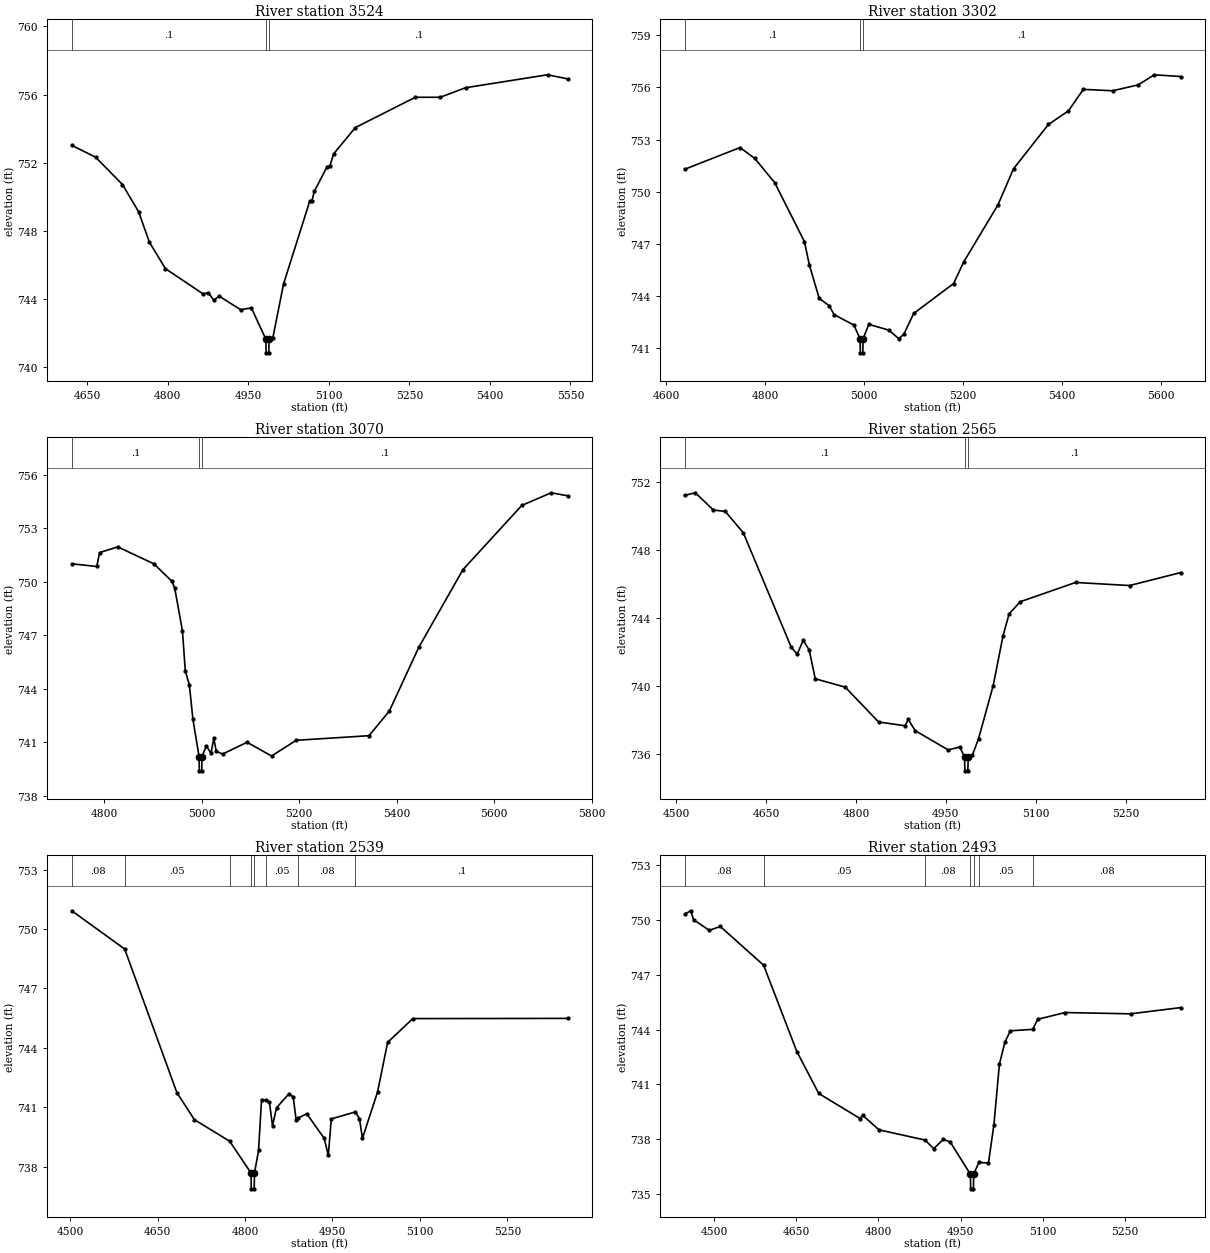
Type RM Length L Ch R = 1,3524,222,222,222
BEGIN DESCRIPTION:
Mapping XS 28c2d58e
END DESCRIPTION:
XS GIS Cut Line= 3
      2005299.43     13641248.69      2004852.39     13641257.37
      2004413.99     13641444.01
#Sta/Elev= 30
  4621.3  753.02  4665.7  752.32  4715.7  750.72  4745.8  749.12  4765.8  747.34
  4795.8  745.78  4865.8  744.30  4875.8  744.37  4885.8  743.92  4895.8  744.17
  4935.8  743.37  4955.8  743.48  4982.8  741.64  4983.3  740.84  4988.3  740.84
  4988.8  741.64  4995.8  741.72  5015.8  744.89  5064.6  749.75  5068.4  749.75
  5073.1  750.32  5096.7  751.76  5102.1  751.82  5109.1  752.52  5149.4  754.06
  5261.2  755.84  5307.5  755.84  5354.8  756.40  5507.4  757.16  5544.9  756.92
#Mann=3,-1,0
  4621.3     0.1       0  4982.8    0.07       0  4988.8     0.1       0
Bank Sta=4982.8,4988.8
Exp/Cntr=0.3,0.1

Type RM Length L Ch R = 1,3302,232,232,232
BEGIN DESCRIPTION:
UNT 094 in HW 8.0
END DESCRIPTION:
XS GIS Cut Line= 3
      2005436.61     13641117.83      2005078.95     13641103.94
      2004440.10     13641187.27
#Sta/Elev= 30
  4637.0  751.29  4748.7  752.54  4778.7  751.91  4818.8  750.52  4878.8  747.13
  4888.8  745.79  4908.8  743.85  4928.8  743.44  4938.8  742.92  4978.9  742.32
  4991.4  741.52  4991.9  740.72  4996.9  740.72  4997.4  741.52  5009.0  742.36
  5049.3  742.03  5069.5  741.54  5079.6  741.78  5099.8  742.99  5180.4  744.71
  5201.0  745.96  5270.0  749.24  5301.5  751.32  5372.1  753.87  5412.4  754.65
  5442.6  755.89  5501.9  755.81  5553.6  756.15  5585.9  756.73  5639.2  756.63
#Mann=3,-1,0
  4637.0     0.1       0  4991.4    0.07       0  4997.4     0.1       0
Bank Sta=4991.4,4997.4
Exp/Cntr=0.3,0.1

Type RM Length L Ch R = 1,3070,505,505,505
BEGIN DESCRIPTION:
UNT 094 in HW 7.0
END DESCRIPTION:
XS GIS Cut Line= 3
      2005382.81     13640773.19      2005125.00     13640925.00
      2004411.46     13641004.98
#Sta/Elev= 30
  4733.5  751.00  4784.8  750.85  4790.6  751.63  4827.7  751.95  4901.9  751.00
  4939.0  750.02  4944.8  749.62  4960.5  747.24  4966.3  745.02  4974.7  744.21
  4981.9  742.31  4994.6  740.20  4995.1  739.40  5000.1  739.40  5000.6  740.20
  5009.5  740.79  5019.1  740.39  5024.9  741.22  5029.8  740.50  5042.8  740.34
  5093.1  741.00  5143.4  740.23  5193.7  741.11  5343.3  741.37  5384.9  742.75
  5445.3  746.32  5535.8  750.67  5656.6  754.27  5716.9  754.98  5750.7  754.81
#Mann=3,-1,0
  4733.5     0.1       0  4994.6    0.07       0  5000.6     0.1       0
Bank Sta=4994.6,5000.6
Exp/Cntr=0.3,0.1

Type RM Length L Ch R = 1,2565,26,26,26
BEGIN DESCRIPTION:
Mapping XS df7752f8
END DESCRIPTION:
XS GIS Cut Line= 6
      2005192.70     13640708.11      2004882.77     13640702.90
      2004809.86     13640687.27      2004744.75     13640687.27
      2004617.15     13640713.31      2004369.88     13640718.52
#Sta/Elev= 30
  4514.4  751.21  4532.1  751.36  4562.1  750.35  4582.1  750.26  4612.1  749.01
  4692.1  742.28  4702.1  741.88  4712.1  742.70  4722.1  742.11  4732.1  740.43
  4782.1  739.94  4837.8  737.89  4882.1  737.67  4887.2  738.04  4898.9  737.38
  4953.8  736.25  4973.3  736.42  4981.2  735.82  4981.7  735.02  4986.7  735.02
  4987.2  735.82  4994.4  735.96  5004.6  736.92  5028.9  740.02  5045.4  742.96
  5055.6  744.25  5074.3  744.96  5166.4  746.09  5256.5  745.91  5341.6  746.67
#Mann=3,-1,0
  4514.4     0.1       0  4981.2    0.07       0  4987.2     0.1       0
Bank Sta=4981.2,4987.2
Exp/Cntr=0.3,0.1

Type RM Length L Ch R = 1,2539,46,46,46
BEGIN DESCRIPTION:
Mapping XS fab6cb72
END DESCRIPTION:
XS GIS Cut Line= 6
      2005195.29     13640674.25      2004869.75     13640674.25
      2004799.44     13640656.02      2004742.15     13640661.23
      2004656.21     13640679.46      2004349.48     13640676.86
#Sta/Elev= 30
  4503.0  750.92  4593.7  748.99  4683.3  741.74  4713.3  740.38  4773.8  739.29
  4810.3  737.69  4810.8  736.89  4815.8  736.89  4816.3  737.69  4823.3  738.83
  4828.4  741.39  4836.3  741.35  4842.0  741.25  4847.2  740.07  4854.1  740.98
  4874.8  741.67  4882.6  741.54  4887.8  740.35  4890.5  740.45  4905.9  740.68
  4935.8  739.44  4942.9  738.58  4948.0  740.42  4989.3  740.77  4996.3  740.43
  5001.4  739.44  5027.3  741.77  5044.6  744.28  5087.8  745.48  5353.3  745.49
#Mann=8,-1,0
  4503.0    0.08       0  4593.7    0.05       0  4773.8     0.1       0
  4810.3    0.07       0  4816.3     0.1       0  4836.3    0.05       0
  4890.5    0.08       0  4989.3     0.1       0
Bank Sta=4810.3,4816.3
Exp/Cntr=0.3,0.1

Type RM Length L Ch R = 1,2493,103,103,103
BEGIN DESCRIPTION:
UNT 094 in HW 6.0
END DESCRIPTION:
XS GIS Cut Line= 3
      2005249.92     13640640.40      2004775.00     13640625.00
      2004343.73     13640632.58
#Sta/Elev= 30
  4445.8  750.32  4456.9  750.50  4461.9  750.01  4490.7  749.43  4510.8  749.64
  4590.0  747.52  4650.8  742.79  4690.8  740.50  4766.3  739.13  4771.3  739.30
  4800.9  738.51  4885.1  737.95  4901.0  737.48  4918.5  737.99  4931.0  737.85
  4968.0  736.08  4968.5  735.28  4973.5  735.28  4974.0  736.08  4983.5  736.73
  5001.0  736.69  5011.0  738.79  5021.0  742.10  5031.0  743.30  5041.0  743.93
  5082.0  744.01  5091.0  744.56  5141.0  744.93  5261.0  744.86  5352.3  745.20
#Mann=7,-1,0
  4445.8    0.08       0  4590.0    0.05       0  4885.1    0.08       0
  4968.0    0.04       0  4974.0    0.08       0  4983.5    0.05       0
  5082.0    0.08       0
Bank Sta=4968,4974
Exp/Cntr=0.3,0.1

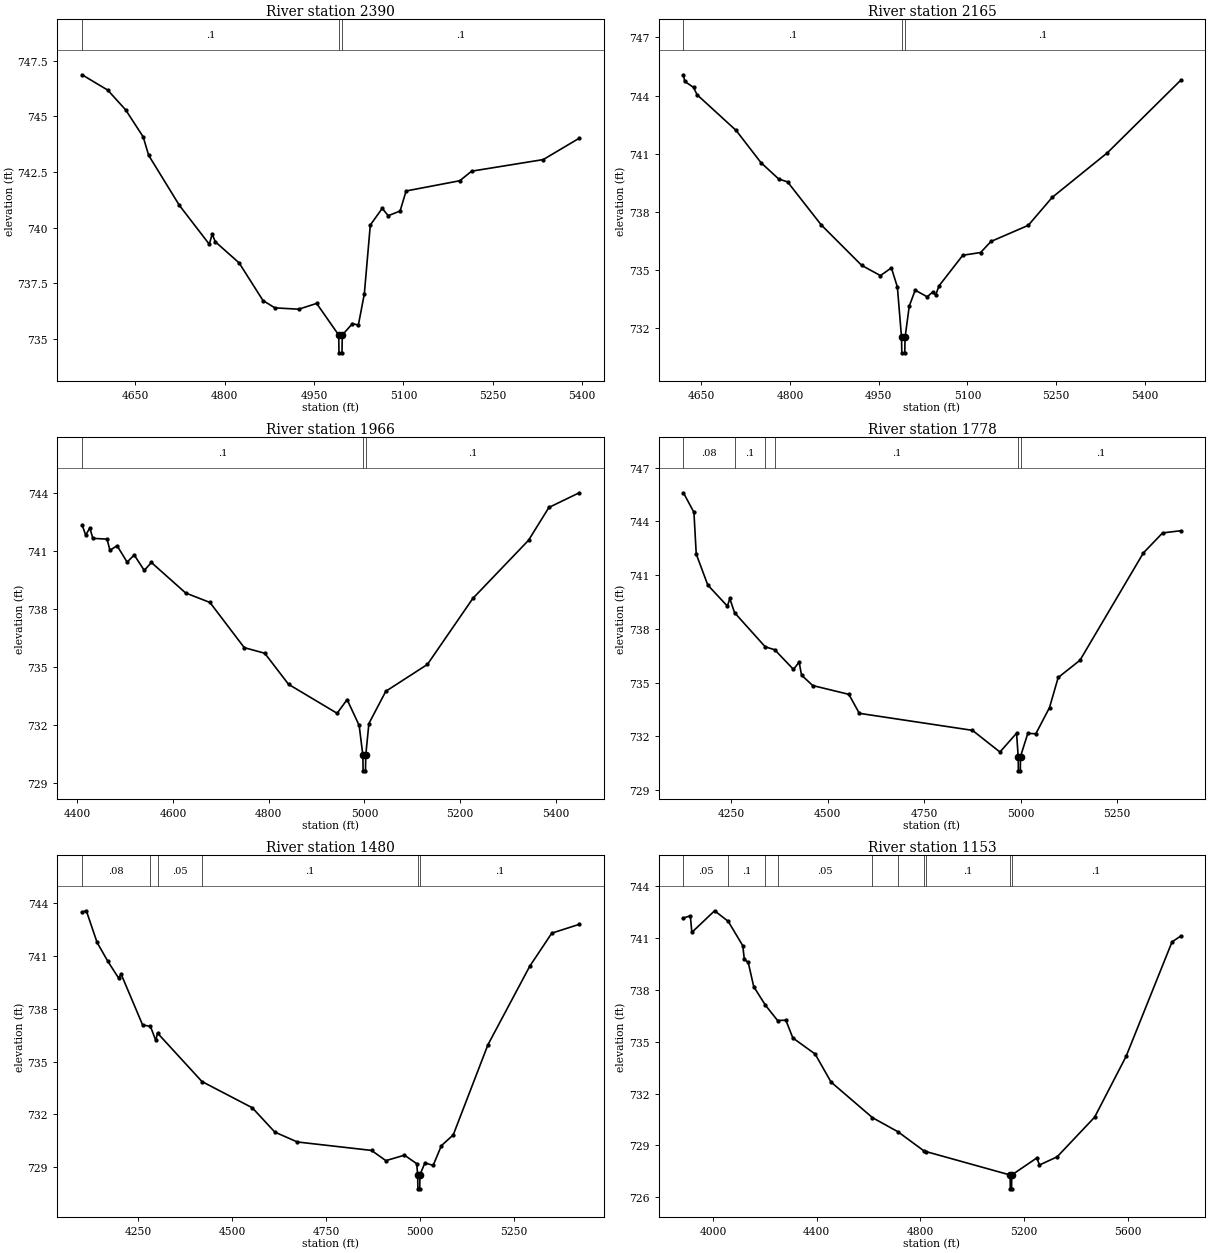
Type RM Length L Ch R = 1,2390,225,225,225
BEGIN DESCRIPTION:
UNT 094 in HW 5.0
END DESCRIPTION:
XS GIS Cut Line= 3
      2005197.87     13640559.67      2005083.29     13640549.25
      2004364.57     13640554.46
#Sta/Elev= 30
  4561.1  746.87  4604.2  746.18  4634.3  745.29  4663.6  744.08  4672.8  743.25
  4724.4  741.00  4774.4  739.26  4779.4  739.71  4784.5  739.37  4824.5  738.42
  4864.5  736.73  4884.5  736.40  4924.5  736.34  4954.5  736.60  4991.5  735.18
  4992.0  734.38  4997.0  734.38  4997.5  735.18  5014.5  735.69  5024.5  735.63
  5034.5  737.03  5044.5  740.12  5064.5  740.87  5074.5  740.54  5094.5  740.75
  5104.5  741.65  5194.5  742.11  5214.5  742.54  5334.5  743.06  5394.9  744.02
#Mann=3,-1,0
  4561.1     0.1       0  4991.5    0.07       0  4997.5     0.1       0
Bank Sta=4991.5,4997.5
Exp/Cntr=0.3,0.1

Type RM Length L Ch R = 1,2165,199,199,199
BEGIN DESCRIPTION:
Mapping XS 4f7e4c57
END DESCRIPTION:
XS GIS Cut Line= 3
      2005182.26     13640510.85      2004969.58     13640367.61
      2004388.95     13640306.95
#Sta/Elev= 30
  4619.9  745.07  4622.0  744.73  4637.0  744.42  4643.0  744.04  4709.0  742.20
  4751.0  740.54  4780.9  739.70  4795.9  739.55  4852.9  737.33  4921.1  735.25
  4952.9  734.72  4971.4  735.12  4981.5  734.13  4988.5  731.54  4989.0  730.74
  4994.0  730.74  4994.5  731.54  5001.6  733.15  5011.6  733.97  5031.7  733.63
  5041.3  733.87  5046.3  733.72  5051.8  734.19  5092.1  735.77  5122.2  735.91
  5139.7  736.48  5202.7  737.31  5243.1  738.75  5336.4  741.05  5460.1  744.78
#Mann=3,-1,0
  4619.9     0.1       0  4988.5    0.07       0  4994.5     0.1       0
Bank Sta=4988.5,4994.5
Exp/Cntr=0.3,0.1

Type RM Length L Ch R = 1,1966,188,188,188
BEGIN DESCRIPTION:
UNT 094 in HW 4.0
END DESCRIPTION:
XS GIS Cut Line= 3
      2005348.94     13640502.39      2004875.00     13640175.00
      2004479.58     13639934.95
#Sta/Elev= 30
  4410.2  742.36  4417.7  741.83  4426.5  742.20  4432.6  741.66  4462.4  741.62
  4468.4  741.04  4483.3  741.28  4504.3  740.43  4519.1  740.80  4540.1  740.00
  4555.0  740.41  4626.6  738.83  4677.3  738.34  4749.0  736.00  4791.8  735.71
  4841.6  734.10  4943.0  732.60  4963.9  733.31  4989.1  731.97  4996.8  730.42
  4997.3  729.62  5002.3  729.62  5002.8  730.42  5009.4  732.07  5044.7  733.74
  5131.6  735.13  5226.6  738.55  5342.9  741.56  5385.5  743.26  5448.8  744.02
#Mann=3,-1,0
  4410.2     0.1       0  4996.8    0.07       0  5002.8     0.1       0
Bank Sta=4996.8,5002.8
Exp/Cntr=0.3,0.1

Type RM Length L Ch R = 1,1778,298,298,298
BEGIN DESCRIPTION:
UNT 094 in HW 3.0
END DESCRIPTION:
XS GIS Cut Line= 3
      2005546.84     13640570.09      2005427.04     13640393.00
      2004572.87     13639741.96
#Sta/Elev= 30
  4126.4  745.59  4153.6  744.50  4159.6  742.17  4189.5  740.44  4240.4  739.26
  4246.5  739.69  4258.8  738.90  4338.4  736.99  4362.9  736.83  4411.5  735.73
  4426.1  736.14  4432.4  735.41  4461.4  734.83  4554.9  734.34  4582.0  733.28
  4875.1  732.33  4946.3  731.12  4989.4  732.17  4993.6  730.87  4994.1  730.07
  4999.1  730.07  4999.6  730.87  5018.5  732.16  5039.3  732.14  5074.7  733.60
  5097.2  735.28  5153.6  736.24  5317.8  742.23  5367.7  743.35  5414.2  743.47
#Mann=6,-1,0
  4126.4    0.08       0  4258.8     0.1       0  4338.4    0.05       0
  4362.9     0.1       0  4993.6    0.07       0  4999.6     0.1       0
Bank Sta=4993.6,4999.6
Exp/Cntr=0.3,0.1

Type RM Length L Ch R = 1,1480,327,327,327
BEGIN DESCRIPTION:
Mapping XS ce27a910
END DESCRIPTION:
XS GIS Cut Line= 4
      2005616.25     13640549.87      2005342.84     13640224.38
      2005078.08     13639733.93      2004779.27     13639573.69
#Sta/Elev= 30
  4101.2  743.49  4112.5  743.56  4141.1  741.76  4169.7  740.69  4198.3  739.74
  4204.9  739.97  4262.1  737.08  4282.8  737.00  4297.2  736.20  4301.7  736.62
  4419.8  733.87  4553.7  732.38  4613.6  731.00  4673.3  730.44  4870.6  729.96
  4908.7  729.38  4958.2  729.69  4990.6  729.21  4993.3  728.58  4993.8  727.78
  4998.8  727.78  4999.3  728.58  5012.5  729.25  5034.4  729.11  5056.3  730.23
  5087.8  730.84  5180.1  735.96  5291.4  740.42  5349.8  742.29  5422.7  742.79
#Mann=6,-1,0
  4101.2    0.08       0  4282.8     0.1       0  4301.7    0.05       0
  4419.8     0.1       0  4993.3    0.07       0  4999.3     0.1       0
Bank Sta=4993.3,4999.3
Exp/Cntr=0.3,0.1

Type RM Length L Ch R = 1,1153,126,126,126
BEGIN DESCRIPTION:
UNT 094 in HW 2.0
END DESCRIPTION:
XS GIS Cut Line= 4
      2005869.73     13640596.11      2005442.67     13640320.09
      2005403.08     13639395.09      2004924.96     13639475.01
#Sta/Elev= 30
  3885.4  742.16  3912.0  742.29  3917.9  741.33  4005.7  742.58  4058.2  741.97
  4114.5  740.56  4120.5  739.77  4135.6  739.59  4156.8  738.19  4201.3  737.13
  4248.9  736.23  4280.8  736.25  4307.8  735.22  4393.9  734.29  4455.2  732.67
  4615.1  730.61  4713.8  729.79  4812.5  728.70  4823.4  728.64  5146.7  727.29
  5147.2  726.49  5152.2  726.49  5152.7  727.29  5249.8  728.28  5259.8  727.87
  5327.9  728.34  5472.9  730.64  5594.4  734.16  5771.6  740.78  5804.5  741.11
#Mann=10,-1,0
  3885.4    0.05       0  4058.2     0.1       0  4201.3    0.08       0
  4248.9    0.05       0  4615.1    0.08       0  4713.8    0.05       0
  4812.5    0.08       0  4823.4     0.1       0  5146.7    0.07       0
  5152.7     0.1       0
Bank Sta=5146.7,5152.7
Exp/Cntr=0.3,0.1

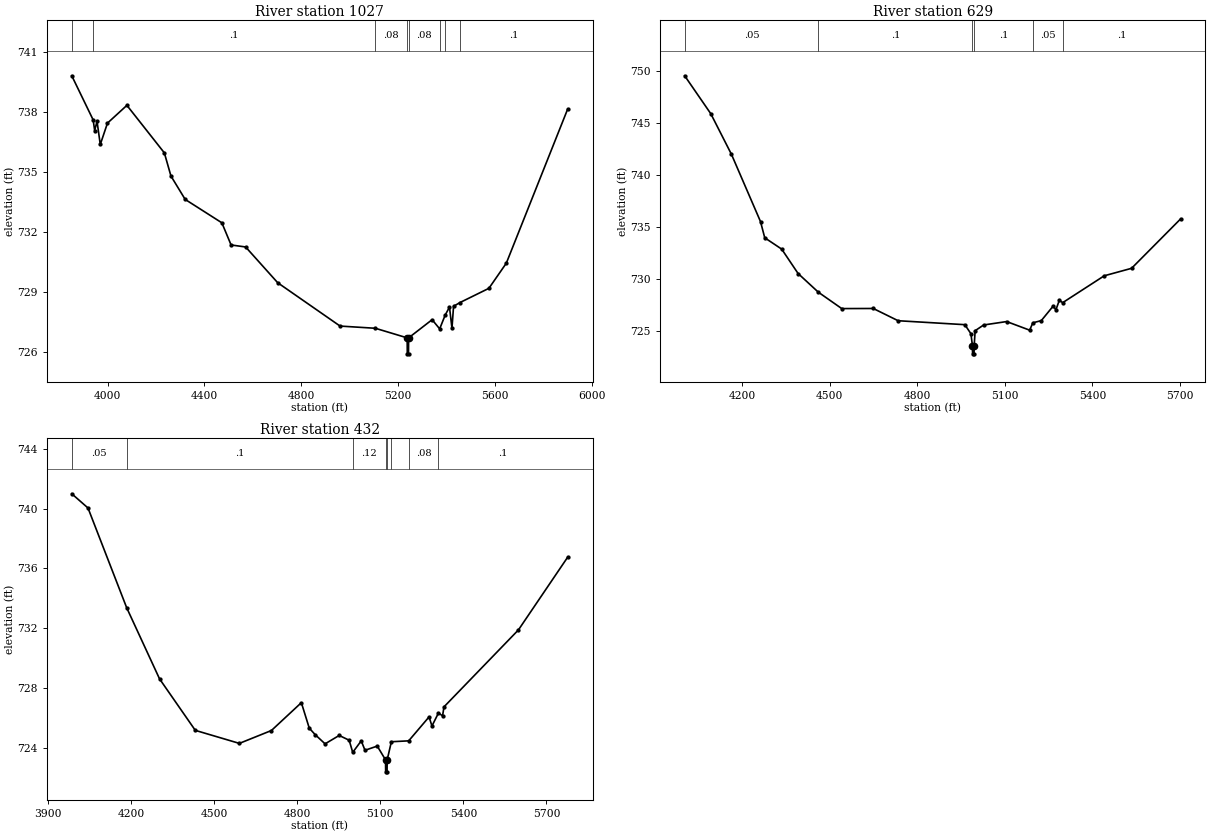
Type RM Length L Ch R = 1,1027,398,398,398
BEGIN DESCRIPTION:
Mapping XS 63a0d545
END DESCRIPTION:
XS GIS Cut Line= 4
      2006046.83     13640554.46      2005562.46     13640273.21
      2005520.79     13639309.67      2005005.15     13639408.63
#Sta/Elev= 30
  3851.6  739.82  3940.0  737.61  3946.2  737.08  3956.0  737.54  3969.4  736.38
  3999.1  737.45  4079.4  738.34  4234.2  735.96  4261.5  734.80  4320.3  733.63
  4471.8  732.46  4510.0  731.35  4570.1  731.25  4702.6  729.46  4960.4  727.29
  5106.1  727.18  5237.7  726.70  5238.2  725.90  5243.2  725.90  5243.7  726.70
  5340.8  727.61  5372.0  727.15  5394.8  727.84  5412.6  728.24  5422.8  727.18
  5429.4  728.28  5456.3  728.47  5575.5  729.18  5647.5  730.44  5901.2  738.16
#Mann=8,-1,0
  3851.6    0.05       0  3940.0     0.1       0  5106.1    0.08       0
  5237.7    0.07       0  5243.7    0.08       0  5372.0    0.05       0
  5394.8    0.08       0  5456.3     0.1       0
Bank Sta=5237.7,5243.7
Exp/Cntr=0.3,0.1

Type RM Length L Ch R = 1,629,197,197,197
BEGIN DESCRIPTION:
Mapping XS e8b6c39a
END DESCRIPTION:
XS GIS Cut Line= 3
      2006489.52     13639955.48      2005557.25     13639236.75
      2005052.04     13639361.75
#Sta/Elev= 30
  4004.1  749.55  4093.4  745.90  4164.1  741.99  4263.7  735.50  4278.2  733.94
  4336.2  732.85  4392.3  730.50  4461.6  728.70  4541.8  727.12  4649.6  727.13
  4734.8  725.95  4963.1  725.57  4983.9  724.70  4989.1  723.56  4989.6  722.76
  4994.6  722.76  4995.1  723.56  4998.4  724.99  5027.4  725.54  5106.2  725.87
  5185.0  725.04  5195.8  725.75  5224.8  725.96  5266.0  727.38  5274.6  726.99
  5286.6  727.92  5298.0  727.69  5440.3  730.28  5533.8  731.00  5701.7  735.76
#Mann=6,-1,0
  4004.1    0.05       0  4461.6     0.1       0  4989.1    0.07       0
  4995.1     0.1       0  5195.8    0.05       0  5298.0     0.1       0
Bank Sta=4989.1,4995.1
Exp/Cntr=0.3,0.1

Type RM Length L Ch R = 1,432,0,0,0
BEGIN DESCRIPTION:
UNT 094 in HW 1.0
END DESCRIPTION:
XS GIS Cut Line= 3
      2006575.00     13639725.00      2005675.00     13639125.00
      2004995.59     13639330.25
#Sta/Elev= 30
  3985.4  740.99  4044.0  740.04  4183.7  733.38  4302.4  728.63  4431.6  725.19
  4590.8  724.32  4706.5  725.18  4814.7  727.04  4843.2  725.34  4864.2  724.91
  4900.3  724.29  4951.4  724.85  4987.4  724.53  5000.2  723.72  5031.0  724.49
  5044.5  723.86  5088.8  724.14  5118.7  723.22  5119.2  722.42  5124.2  722.42
  5124.7  723.22  5139.8  724.43  5202.4  724.49  5276.0  726.09  5286.4  725.48
  5309.9  726.35  5324.7  726.16  5329.9  726.76  5598.8  731.90  5776.8  736.76
#Mann=8,-1,0
  3985.4    0.05       0  4183.7     0.1       0  5000.2    0.12       0
  5118.7    0.07       0  5124.7    0.12       0  5139.8     0.1       0
  5202.4    0.08       0  5309.9     0.1       0
Bank Sta=5118.7,5124.7
Exp/Cntr=0.3,0.1

Chan Stop Cuts=-1