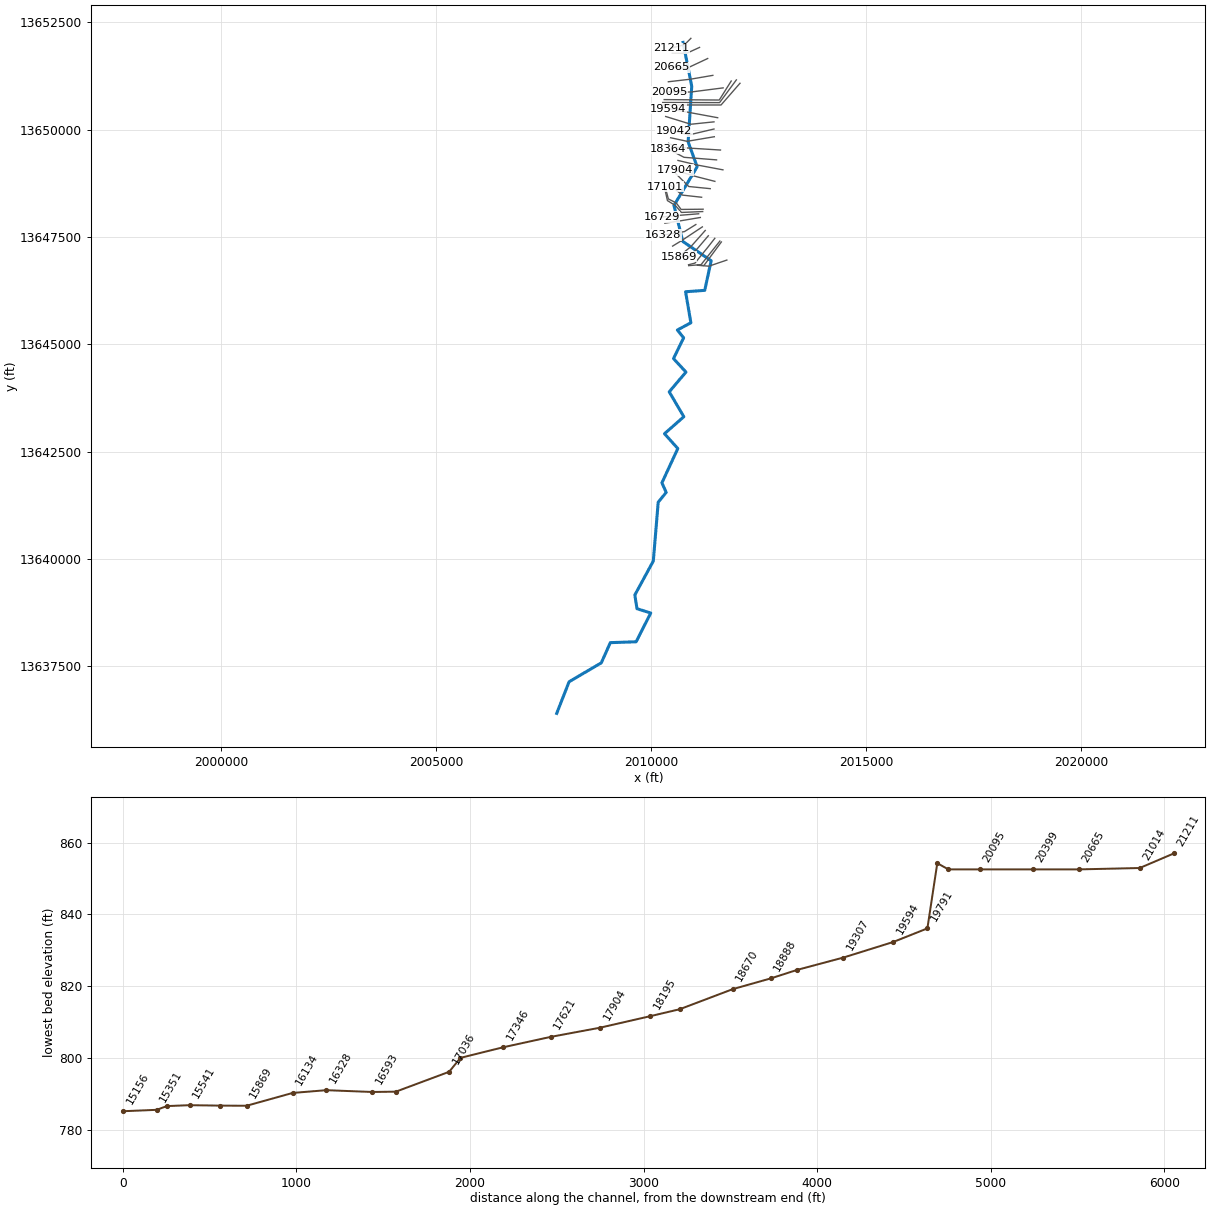
--- UNT 095 in HW.prj (project) ---

Proj Title=UNT 095 in HW Base Level Engineering
Current Plan=p01
Default Exp/Contr=0.3,0.1
English Units
Geom File=g01
Flow File=f01
Plan File=p01
BEGIN DESCRIPTION:
UNT 095 in HW
END DESCRIPTION:

--- UNT 095 in HW.p01 (plan) ---

Plan Title=Multiple Run
Short Identifier=Multiple
Geom File=g01
Flow File=f01
Subcritical Flow
K Sum by GR= 0
Std Step Tol= 0.01
Critical Tol= 0.01
Num of Std Step Trials= 20
Max Error Tol= 0.3
Flow Tol Ratio= 0.001
Split Flow NTrial= 30
Split Flow Tol= 0.02
Split Flow Ratio= 0.02
Log Output Level= 0
Friction Slope Method= 1
Unsteady Friction Slope Method= 2
Unsteady Bridges Friction Slope Method= 1
Parabolic Critical Depth
Global Vel Dist=  1 , 1 , 1
Global Log Level= 0
CheckData=True
Encroach Param= -1, 0, 0, 0
BEGIN DESCRIPTION:
Multiple Run
END DESCRIPTION:

--- UNT 095 in HW.f01 (steady flow) ---

Flow Title=Multiple
Number of Profiles=7
Profile Names=10-year,25-year,50-year,1pct_min,100-year,1pct_plu,500-year
River Rch & RM= UNT 095 in HW,Reach-1,21211
     593     836    1039     640    1277    2548    1935
River Rch & RM= UNT 095 in HW,Reach-1,11651
     841    1203    1511     938    1872    3734    2884
Boundary for River Rch & Prof#=UNT 095 in HW,Reach-1,1
Up Type=0
Dn Type=3
Dn Slope=0.005
Boundary for River Rch & Prof#=UNT 095 in HW,Reach-1,2
Up Type=0
Dn Type=3
Dn Slope=0.005
Boundary for River Rch & Prof#=UNT 095 in HW,Reach-1,3
Up Type=0
Dn Type=3
Dn Slope=0.005
Boundary for River Rch & Prof#=UNT 095 in HW,Reach-1,4
Up Type=0
Dn Type=3
Dn Slope=0.005
Boundary for River Rch & Prof#=UNT 095 in HW,Reach-1,5
Up Type=0
Dn Type=3
Dn Slope=0.005
Boundary for River Rch & Prof#=UNT 095 in HW,Reach-1,6
Up Type=0
Dn Type=3
Dn Slope=0.005
Boundary for River Rch & Prof#=UNT 095 in HW,Reach-1,7
Up Type=0
Dn Type=3
Dn Slope=0.005

--- UNT 095 in HW.g01 (geometry) ---

Geom Title=Existing Conditions

River Reach=UNT 095 in HW,Reach-1
Reach XY= 30
      2010743.32     13652031.25      2010944.71     13651006.94
      2010860.80     13649714.54      2011070.80     13649134.54
      2010530.80     13648234.54      2010736.55     13647396.00
      2011396.88     13646947.20      2011247.15     13646257.09
      2010801.83     13646224.76      2010924.23     13645502.10
      2010609.99     13645332.83      2010755.83     13645152.28
      2010520.58     13644667.90      2010810.80     13644354.54
      2010420.80     13643894.54      2010760.80     13643314.54
      2010310.79     13642919.16      2010620.80     13642574.54
      2010250.80     13641774.54      2010351.07     13641552.50
      2010164.96     13641325.41      2010050.80     13639954.54
      2009620.80     13639164.54      2009670.80     13638844.54
      2009990.80     13638744.54      2009650.80     13638074.54
      2009050.80     13638054.54      2008840.80     13637584.54
      2008090.80     13637143.76      2007802.88     13636407.64

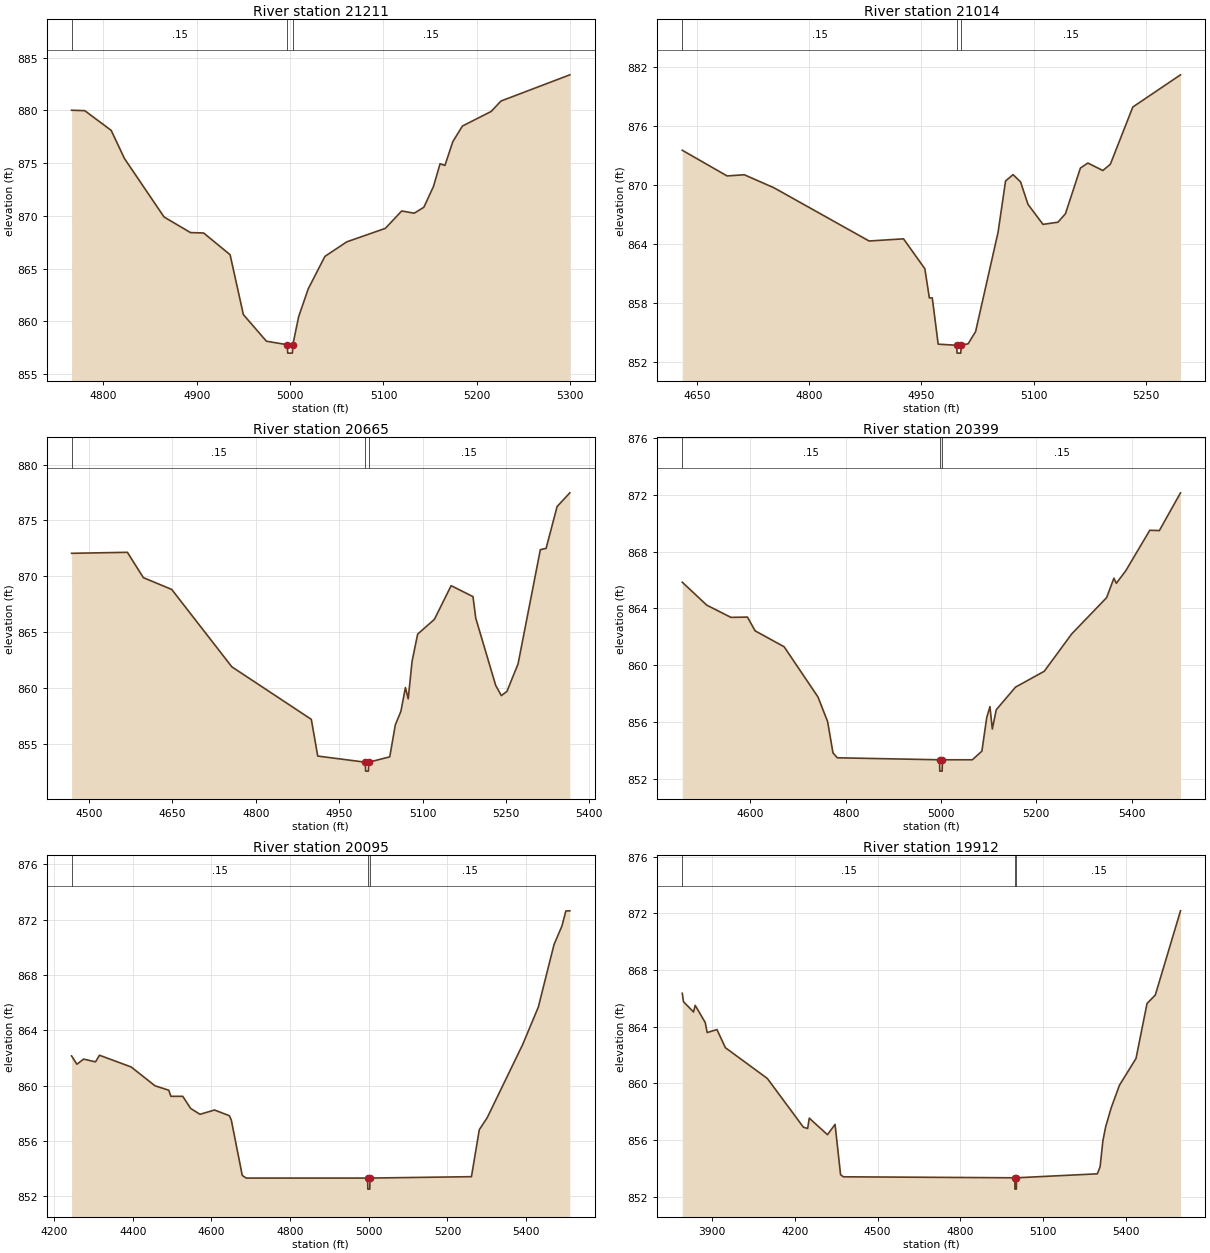
Type RM Length L Ch R = 1,21211,197,197,197
BEGIN DESCRIPTION:
UNT 095 in HW 51.0
END DESCRIPTION:
XS GIS Cut Line= 3
      2010925.00     13652125.00      2010775.00     13651975.00
      2010463.46     13651896.57
#Sta/Elev= 30
  4766.1  880.02  4780.2  879.98  4808.5  878.11  4822.7  875.44  4865.1  869.89
  4893.4  868.41  4907.5  868.37  4935.8  866.31  4950.0  860.63  4974.7  858.10
  4997.0  857.77  4997.5  856.97  5002.5  856.97  5003.0  857.77  5009.2  860.43
  5019.5  863.08  5037.3  866.15  5060.7  867.53  5102.0  868.81  5119.5  870.46
  5132.9  870.25  5143.2  870.81  5153.5  872.78  5160.6  874.94  5165.8  874.78
  5174.2  877.03  5184.5  878.52  5215.4  879.91  5225.7  880.89  5299.5  883.38
#Mann=3,-1,0
  4766.1    0.15       0  4997.0    0.05       0  5003.0    0.15       0
Bank Sta=4997,5003
Exp/Cntr=0.3,0.1

Type RM Length L Ch R = 1,21014,349,349,349
BEGIN DESCRIPTION:
UNT 095 in HW 50.0
END DESCRIPTION:
XS GIS Cut Line= 3
      2011126.63     13651913.92      2010822.85     13651775.05
      2010491.29     13651778.52
#Sta/Elev= 30
  4630.4  873.52  4690.3  870.91  4713.3  871.03  4753.1  869.70  4880.0  864.30
  4926.0  864.52  4954.5  861.48  4960.5  858.52  4964.4  858.52  4972.3  853.82
  4997.0  853.71  4997.5  852.91  5002.5  852.91  5003.0  853.71  5012.3  853.86
  5022.3  855.10  5052.3  865.19  5062.3  870.40  5072.3  871.04  5082.3  870.31
  5092.3  868.02  5112.3  865.99  5132.3  866.21  5142.3  867.07  5162.3  871.71
  5172.3  872.22  5192.3  871.46  5202.3  872.10  5232.3  877.91  5296.0  881.18
#Mann=3,-1,0
  4630.4    0.15       0  4997.0    0.05       0  5003.0    0.15       0
Bank Sta=4997,5003
Exp/Cntr=0.3,0.1

Type RM Length L Ch R = 1,20665,266,266,266
BEGIN DESCRIPTION:
UNT 095 in HW 49.0
END DESCRIPTION:
XS GIS Cut Line= 3
      2011315.89     13651655.25      2010825.00     13651425.00
      2010472.18     13651453.87
#Sta/Elev= 30
  4468.6  872.05  4569.0  872.14  4597.7  869.87  4648.8  868.81  4756.8  861.88
  4899.8  857.17  4911.4  853.88  4997.0  853.33  4997.5  852.53  5002.5  852.53
  5003.0  853.33  5040.9  853.81  5050.9  856.67  5061.0  857.90  5069.1  860.02
  5074.1  859.01  5081.0  862.36  5091.1  864.81  5121.2  866.13  5151.3  869.15
  5190.6  868.17  5195.6  866.24  5231.5  860.21  5241.6  859.30  5251.6  859.67
  5271.7  862.14  5311.8  872.38  5322.1  872.49  5341.9  876.24  5364.8  877.47
#Mann=3,-1,0
  4468.6    0.15       0  4997.0    0.05       0  5003.0    0.15       0
Bank Sta=4997,5003
Exp/Cntr=0.3,0.1

Type RM Length L Ch R = 1,20399,304,304,304
BEGIN DESCRIPTION:
UNT 095 in HW 48.0
END DESCRIPTION:
XS GIS Cut Line= 3
      2011435.73     13651263.14      2010925.00     13651175.00
      2010400.94     13651113.82
#Sta/Elev= 30
  4456.9  865.85  4508.4  864.23  4559.1  863.37  4593.8  863.39  4609.9  862.42
  4670.7  861.30  4741.8  857.76  4762.1  856.02  4773.3  853.82  4782.4  853.47
  4997.0  853.33  4997.5  852.53  5002.5  852.53  5003.0  853.33  5065.8  853.33
  5085.9  853.94  5096.0  856.30  5102.8  857.08  5107.8  855.50  5116.1  856.86
  5156.4  858.45  5216.8  859.57  5274.6  862.21  5347.7  864.76  5363.0  866.13
  5368.1  865.77  5388.0  866.66  5438.3  869.51  5458.4  869.49  5502.8  872.15
#Mann=3,-1,0
  4456.9    0.15       0  4997.0    0.05       0  5003.0    0.15       0
Bank Sta=4997,5003
Exp/Cntr=0.3,0.1

Type RM Length L Ch R = 1,20095,183,183,183
BEGIN DESCRIPTION:
UNT 095 in HW 47.0
END DESCRIPTION:
XS GIS Cut Line= 3
      2011675.32     13650971.47      2010925.00     13650875.00
      2010414.91     13650877.71
#Sta/Elev= 30
  4244.4  862.16  4257.9  861.56  4275.0  861.93  4305.2  861.73  4315.3  862.21
  4396.0  861.36  4456.5  860.00  4491.5  859.68  4496.8  859.24  4527.0  859.24
  4547.2  858.36  4571.0  857.94  4607.7  858.25  4645.5  857.84  4650.5  857.52
  4678.3  853.52  4688.3  853.33  4997.0  853.33  4997.5  852.53  5002.5  852.53
  5003.0  853.33  5260.9  853.43  5280.9  856.83  5300.9  857.69  5390.9  862.97
  5430.9  865.69  5470.9  870.22  5490.9  871.55  5500.9  872.64  5511.0  872.65
#Mann=3,-1,0
  4244.4    0.15       0  4997.0    0.05       0  5003.0    0.15       0
Bank Sta=4997,5003
Exp/Cntr=0.3,0.1

Type RM Length L Ch R = 1,19912,64,64,64
BEGIN DESCRIPTION:
Mapping XS 73ef12d6
END DESCRIPTION:
XS GIS Cut Line= 3
      2011863.79     13651131.38      2011585.01     13650688.25
      2010303.78     13650698.66
#Sta/Elev= 30
  3792.3  866.35  3796.7  865.76  3833.2  865.03  3839.1  865.50  3875.6  864.29
  3882.5  863.58  3918.0  863.79  3948.6  862.51  4100.5  860.34  4231.2  856.90
  4246.5  856.81  4252.4  857.54  4318.3  856.37  4345.8  857.10  4365.8  853.55
  4375.8  853.40  4997.0  853.33  4997.5  852.53  5002.5  852.53  5003.0  853.33
  5295.9  853.61  5305.9  854.11  5315.9  855.93  5325.9  856.92  5345.9  858.26
  5375.9  859.86  5435.9  861.75  5475.9  865.63  5505.9  866.23  5597.1  872.17
#Mann=3,-1,0
  3792.3    0.15       0  4997.0    0.05       0  5003.0    0.15       0
Bank Sta=4997,5003
Exp/Cntr=0.3,0.1

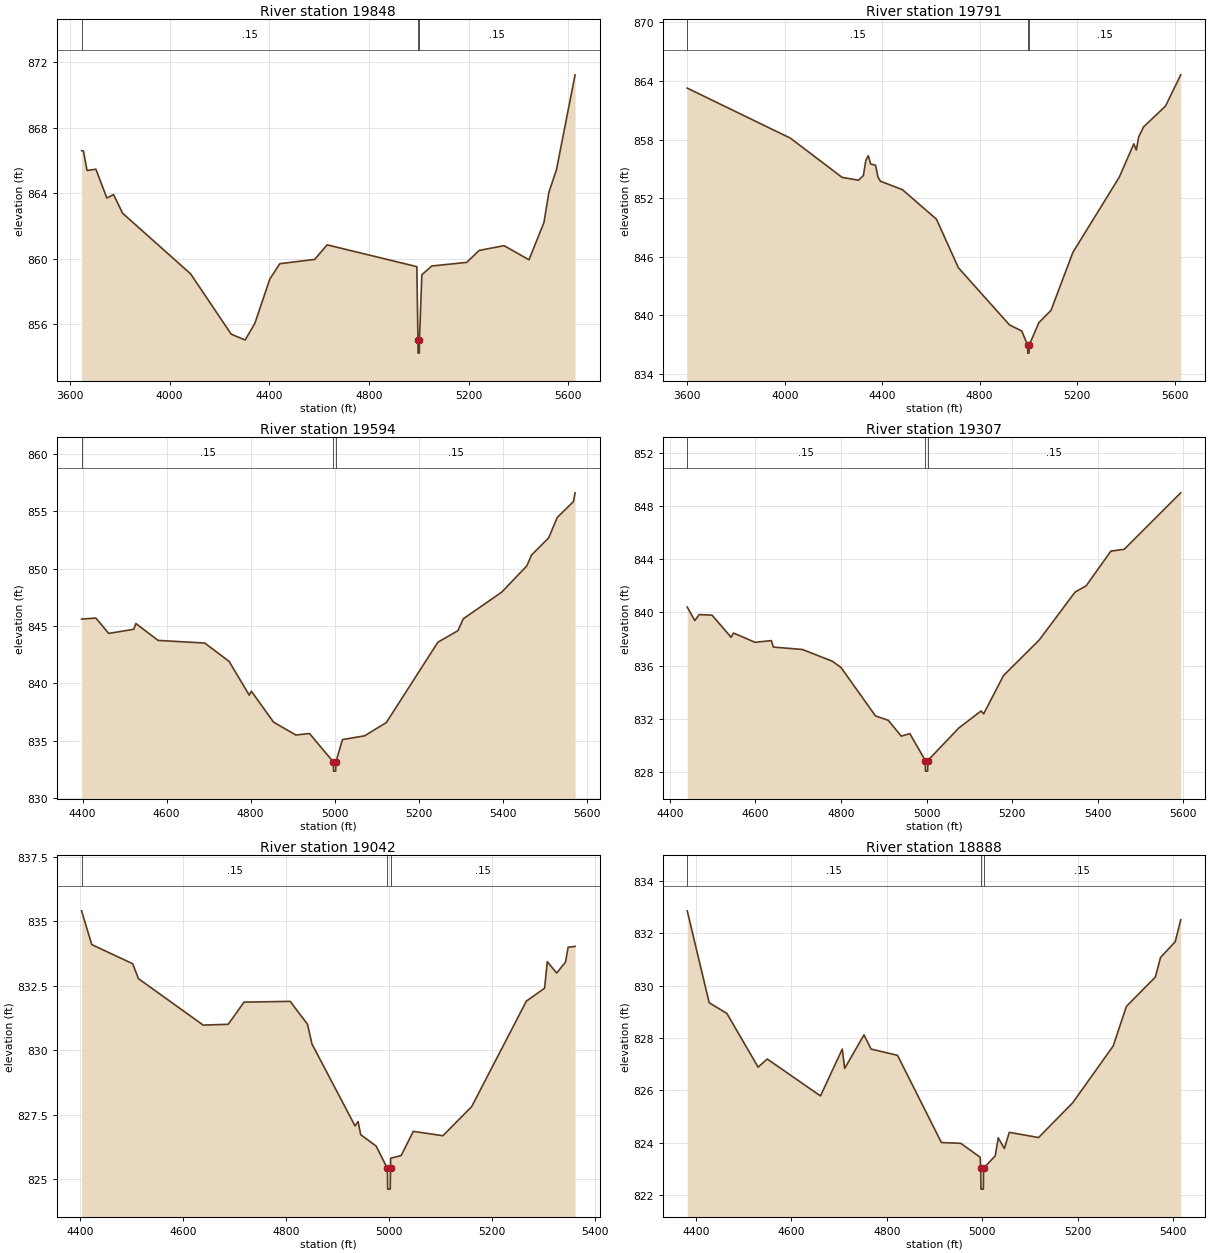
Type RM Length L Ch R = 1,19848,57,57,57
BEGIN DESCRIPTION:
UNT 095 in HW 46.0
END DESCRIPTION:
XS GIS Cut Line= 3
      2011983.15     13651157.42      2011592.82     13650628.35
      2010269.99     13650630.95
#Sta/Elev= 30
  3647.2  866.61  3654.5  866.60  3669.1  865.40  3704.6  865.48  3748.5  863.72
  3775.5  863.93  3811.8  862.79  4084.7  859.09  4247.5  855.41  4303.6  855.05
  4342.5  856.07  4402.5  858.77  4442.5  859.71  4582.5  859.97  4632.5  860.86
  4992.5  859.53  4997.0  855.05  4997.5  854.25  5002.5  854.25  5003.0  855.05
  5012.5  859.03  5052.5  859.57  5192.5  859.79  5242.5  860.52  5342.5  860.81
  5442.5  859.95  5502.5  862.22  5522.5  864.08  5552.5  865.43  5627.5  871.24
#Mann=3,-1,0
  3647.2    0.15       0  4997.0    0.05       0  5003.0    0.15       0
Bank Sta=4997,5003
Exp/Cntr=0.3,0.1

Type RM Length L Ch R = 1,19791,197,197,197
BEGIN DESCRIPTION:
Mapping XS 52ec41fb
END DESCRIPTION:
XS GIS Cut Line= 3
      2012067.79     13651079.30      2011627.23     13650573.63
      2010272.50     13650573.66
#Sta/Elev= 30
  3599.8  863.27  4023.0  858.15  4235.6  854.13  4302.7  853.84  4322.7  854.32
  4332.7  855.86  4342.7  856.35  4352.7  855.50  4372.7  855.37  4382.7  854.15
  4392.7  853.74  4482.7  852.88  4622.7  849.85  4712.7  844.88  4922.7  839.02
  4972.7  838.41  4997.0  836.94  4997.5  836.14  5002.5  836.14  5003.0  836.94
  5042.7  839.25  5092.7  840.52  5182.7  846.46  5372.7  854.14  5432.7  857.57
  5442.7  856.93  5452.7  858.28  5472.7  859.30  5562.7  861.43  5625.2  864.63
#Mann=3,-1,0
  3599.8    0.15       0  4997.0    0.05       0  5003.0    0.15       0
Bank Sta=4997,5003
Exp/Cntr=0.3,0.1

Type RM Length L Ch R = 1,19594,287,287,287
BEGIN DESCRIPTION:
Mapping XS b6d18310
END DESCRIPTION:
XS GIS Cut Line= 2
      2011548.53     13650276.79      2010393.17     13650490.17
#Sta/Elev= 30
  4397.6  845.61  4431.7  845.70  4462.2  844.36  4521.8  844.72  4526.9  845.22
  4579.8  843.75  4690.8  843.52  4748.8  841.92  4796.7  838.98  4801.8  839.32
  4854.7  836.62  4907.7  835.50  4940.2  835.63  4997.0  833.15  4997.5  832.35
  5002.5  832.35  5003.0  833.15  5018.7  835.10  5071.6  835.43  5123.2  836.59
  5245.8  843.59  5293.6  844.60  5306.2  845.63  5397.8  847.96  5457.6  850.25
  5468.9  851.20  5509.6  852.69  5530.0  854.47  5568.6  855.86  5572.5  856.62
#Mann=3,-1,0
  4397.6    0.15       0  4997.0    0.05       0  5003.0    0.15       0
Bank Sta=4997,5003
Exp/Cntr=0.3,0.1

Type RM Length L Ch R = 1,19307,265,265,265
BEGIN DESCRIPTION:
UNT 095 in HW 45.0
END DESCRIPTION:
XS GIS Cut Line= 3
      2011462.65     13650180.44      2010925.00     13650125.00
      2010338.83     13650305.06
#Sta/Elev= 30
  4440.5  840.41  4458.2  839.39  4468.3  839.84  4498.5  839.80  4543.0  838.13
  4548.7  838.45  4599.0  837.75  4637.0  837.88  4642.0  837.39  4709.6  837.21
  4779.9  836.32  4800.0  835.85  4880.5  832.20  4910.6  831.86  4940.8  830.67
  4960.9  830.86  4997.0  828.83  4997.5  828.03  5002.5  828.03  5003.0  828.83
  5075.2  831.28  5127.5  832.57  5133.5  832.35  5179.8  835.24  5263.5  837.93
  5347.1  841.54  5373.0  842.01  5430.8  844.63  5462.2  844.77  5594.2  849.03
#Mann=3,-1,0
  4440.5    0.15       0  4997.0    0.05       0  5003.0    0.15       0
Bank Sta=4997,5003
Exp/Cntr=0.3,0.1

Type RM Length L Ch R = 1,19042,154,154,154
BEGIN DESCRIPTION:
UNT 095 in HW 44.0
END DESCRIPTION:
XS GIS Cut Line= 3
      2011462.60     13650013.76      2010875.00     13649875.00
      2010530.33     13649964.28
#Sta/Elev= 30
  4402.2  835.41  4422.0  834.10  4501.5  833.36  4512.8  832.78  4638.7  830.98
  4687.4  831.01  4718.1  831.87  4807.9  831.90  4841.6  831.01  4850.2  830.25
  4934.0  827.07  4939.9  827.24  4945.1  826.73  4975.1  826.29  4997.0  825.42
  4997.5  824.62  5002.5  824.62  5003.0  825.42  5003.4  825.82  5023.7  825.92
  5047.3  826.86  5104.9  826.69  5160.9  827.82  5267.3  831.91  5302.7  832.41
  5307.9  833.44  5326.2  833.00  5343.3  833.42  5348.5  834.00  5362.0  834.03
#Mann=3,-1,0
  4402.2    0.15       0  4997.0    0.05       0  5003.0    0.15       0
Bank Sta=4997,5003
Exp/Cntr=0.3,0.1

Type RM Length L Ch R = 1,18888,218,218,218
BEGIN DESCRIPTION:
Mapping XS fbe85f75
END DESCRIPTION:
XS GIS Cut Line= 3
      2011470.38     13649834.07      2010837.61     13649727.31
      2010453.70     13649810.32
#Sta/Elev= 30
  4381.8  832.86  4427.8  829.35  4464.9  828.94  4530.4  826.89  4549.5  827.20
  4661.1  825.79  4706.8  827.58  4711.8  826.84  4752.3  828.12  4767.2  827.58
  4822.6  827.34  4914.6  824.01  4955.2  823.98  4995.7  823.45  4997.0  823.03
  4997.5  822.23  5002.5  822.23  5003.0  823.03  5027.4  823.50  5033.8  824.19
  5046.6  823.78  5056.9  824.40  5118.3  824.20  5189.9  825.53  5274.8  827.70
  5302.4  829.21  5363.1  830.33  5374.0  831.08  5404.7  831.68  5416.3  832.52
#Mann=3,-1,0
  4381.8    0.15       0  4997.0    0.05       0  5003.0    0.15       0
Bank Sta=4997,5003
Exp/Cntr=0.3,0.1

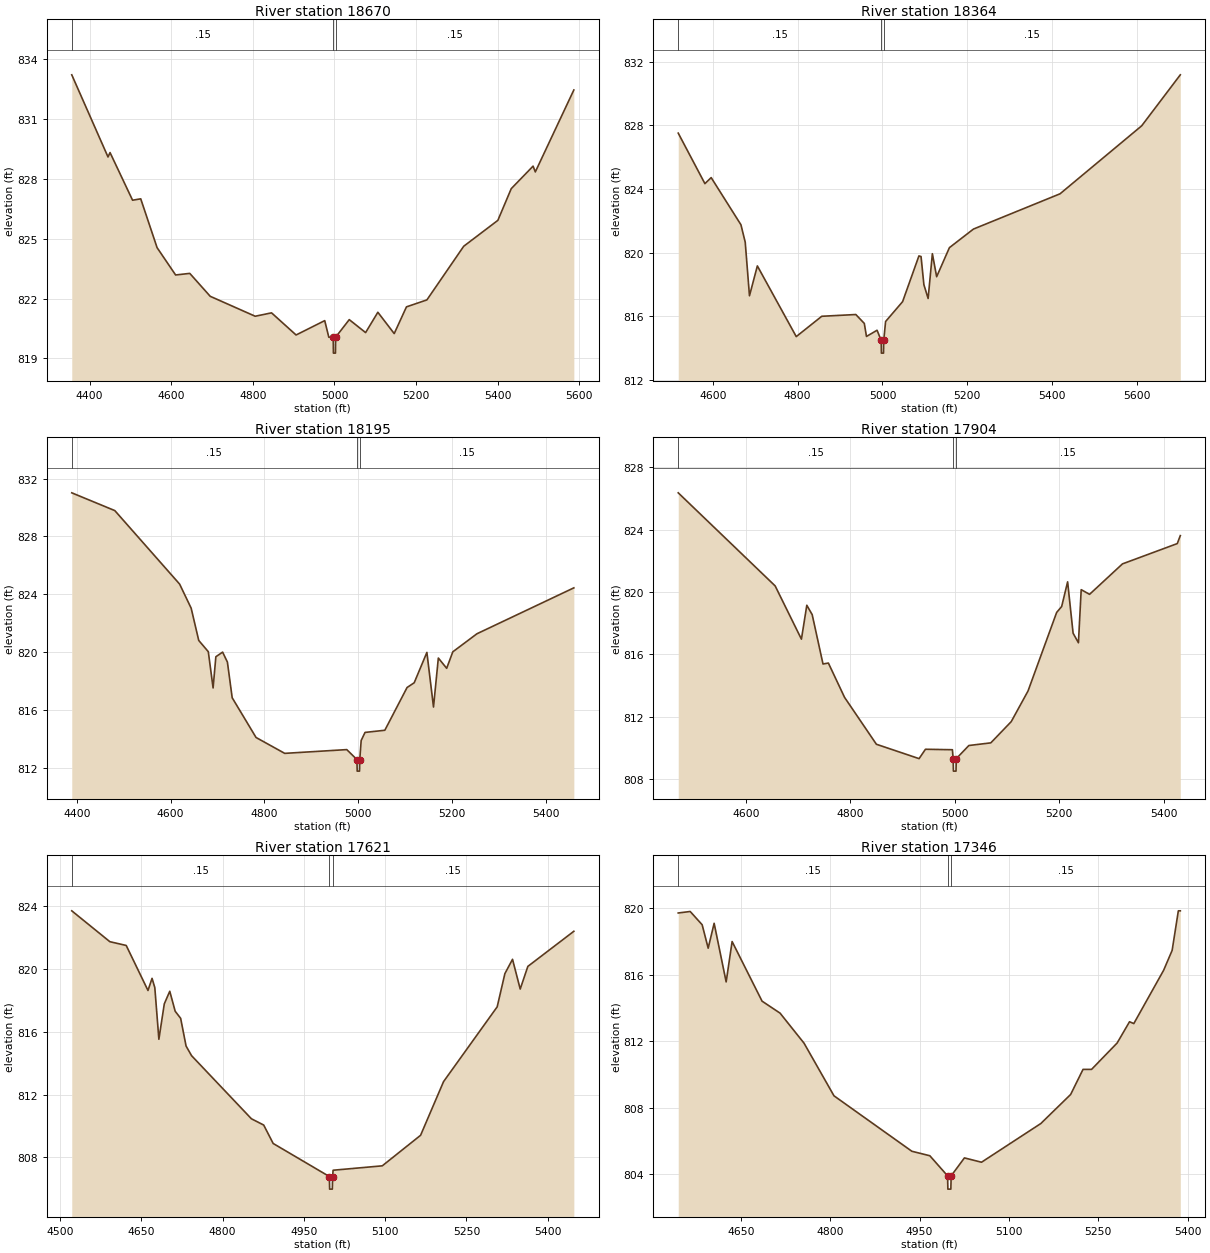
Type RM Length L Ch R = 1,18670,306,306,306
BEGIN DESCRIPTION:
Mapping XS 7c0e900f
END DESCRIPTION:
XS GIS Cut Line= 3
      2011613.67     13649524.18      2010608.44     13649586.68
      2010405.75     13649680.23
#Sta/Elev= 30
  4356.3  833.22  4445.1  829.10  4450.1  829.32  4505.3  826.93  4525.3  827.00
  4565.4  824.55  4610.8  823.18  4645.5  823.26  4695.6  822.11  4805.8  821.11
  4845.9  821.28  4906.0  820.17  4976.2  820.89  4986.2  820.06  4997.0  820.06
  4997.5  819.26  5002.5  819.26  5003.0  820.06  5036.3  820.94  5076.4  820.29
  5106.4  821.31  5146.5  820.24  5176.5  821.58  5226.6  821.93  5316.8  824.62
  5400.5  825.92  5433.3  827.51  5486.8  828.64  5492.3  828.35  5586.7  832.46
#Mann=3,-1,0
  4356.3    0.15       0  4997.0    0.05       0  5003.0    0.15       0
Bank Sta=4997,5003
Exp/Cntr=0.3,0.1

Type RM Length L Ch R = 1,18364,169,169,169
BEGIN DESCRIPTION:
Mapping XS 72a6c1ac
END DESCRIPTION:
XS GIS Cut Line= 3
      2011522.47     13649295.02      2010764.69     13649354.91
      2010389.84     13649552.75
#Sta/Elev= 30
  4518.4  827.52  4581.3  824.34  4596.1  824.72  4666.3  821.75  4676.4  820.65
  4686.4  817.28  4705.0  819.16  4796.7  814.71  4856.9  815.99  4937.2  816.10
  4957.2  815.54  4962.3  814.72  4987.3  815.11  4997.0  814.47  4997.5  813.67
  5002.5  813.67  5003.0  814.47  5007.4  815.66  5047.5  816.91  5086.0  819.79
  5091.0  819.75  5097.7  817.98  5107.7  817.11  5117.7  819.93  5127.8  818.48
  5157.9  820.31  5214.6  821.48  5418.8  823.70  5611.3  827.98  5702.4  831.19
#Mann=3,-1,0
  4518.4    0.15       0  4997.0    0.05       0  5003.0    0.15       0
Bank Sta=4997,5003
Exp/Cntr=0.3,0.1

Type RM Length L Ch R = 1,18195,291,291,291
BEGIN DESCRIPTION:
UNT 095 in HW 43.0
END DESCRIPTION:
XS GIS Cut Line= 3
      2011670.90     13649063.26      2011075.00     13649175.00
      2010624.10     13649281.99
#Sta/Elev= 30
  4389.4  831.02  4481.1  829.79  4619.2  824.70  4643.8  823.03  4659.9  820.80
  4680.3  820.02  4690.5  817.51  4696.4  819.67  4710.8  819.99  4721.0  819.30
  4731.2  816.83  4782.0  814.08  4843.1  812.98  4975.3  813.24  4997.0  812.55
  4997.5  811.75  5002.5  811.75  5003.0  812.55  5006.0  813.87  5014.2  814.43
  5056.4  814.58  5103.8  817.54  5119.0  817.87  5146.0  819.97  5160.1  816.19
  5170.4  819.58  5188.2  818.87  5201.2  820.01  5252.6  821.26  5459.1  824.44
#Mann=3,-1,0
  4389.4    0.15       0  4997.0    0.05       0  5003.0    0.15       0
Bank Sta=4997,5003
Exp/Cntr=0.3,0.1

Type RM Length L Ch R = 1,17904,283,283,283
BEGIN DESCRIPTION:
UNT 095 in HW 42.0
END DESCRIPTION:
XS GIS Cut Line= 3
      2011483.44     13648795.02      2010975.00     13648925.00
      2010559.51     13649057.86
#Sta/Elev= 30
  4470.8  826.35  4656.3  820.39  4706.6  816.98  4716.9  819.15  4727.2  818.55
  4747.9  815.39  4758.2  815.45  4789.2  813.25  4850.1  810.25  4931.8  809.33
  4944.0  809.93  4995.6  809.90  4997.0  809.33  4997.5  808.53  5002.5  808.53
  5003.0  809.33  5027.1  810.17  5069.1  810.34  5108.2  811.70  5140.3  813.66
  5195.1  818.69  5204.7  819.07  5216.1  820.65  5226.6  817.36  5236.8  816.75
  5242.1  820.15  5258.1  819.85  5321.1  821.80  5426.0  823.10  5431.8  823.61
#Mann=3,-1,0
  4470.8    0.15       0  4997.0    0.05       0  5003.0    0.15       0
Bank Sta=4997,5003
Exp/Cntr=0.3,0.1

Type RM Length L Ch R = 1,17621,275,275,275
BEGIN DESCRIPTION:
UNT 095 in HW 41.0
END DESCRIPTION:
XS GIS Cut Line= 3
      2011375.00     13648625.00      2010875.00     13648675.00
      2010574.97     13648975.03
#Sta/Elev= 30
  4521.5  823.67  4591.8  821.71  4622.0  821.47  4662.2  818.61  4669.7  819.38
  4674.8  818.79  4682.3  815.51  4692.3  817.76  4702.4  818.56  4712.4  817.29
  4722.5  816.84  4732.5  815.08  4742.6  814.47  4853.1  810.46  4875.8  810.06
  4893.3  808.89  4997.0  806.79  4997.5  805.99  5002.5  805.99  5003.0  806.79
  5003.9  807.19  5094.7  807.47  5165.4  809.41  5207.8  812.82  5306.8  817.57
  5321.0  819.68  5335.1  820.59  5349.3  818.70  5363.4  820.14  5448.3  822.37
#Mann=3,-1,0
  4521.5    0.15       0  4997.0    0.05       0  5003.0    0.15       0
Bank Sta=4997,5003
Exp/Cntr=0.3,0.1

Type RM Length L Ch R = 1,17346,245,245,245
BEGIN DESCRIPTION:
UNT 095 in HW 40.0
END DESCRIPTION:
XS GIS Cut Line= 3
      2011174.98     13648425.00      2010725.00     13648475.00
      2010424.97     13648725.03
#Sta/Elev= 30
  4544.6  819.72  4564.7  819.81  4584.8  819.01  4594.9  817.60  4604.9  819.10
  4625.1  815.57  4635.1  818.00  4685.4  814.41  4715.6  813.69  4755.9  811.88
  4806.2  808.71  4937.0  805.37  4967.2  805.10  4997.0  803.89  4997.5  803.09
  5002.5  803.09  5003.0  803.89  5025.3  804.97  5054.0  804.71  5153.6  807.04
  5203.7  808.79  5224.5  810.30  5238.8  810.30  5281.8  811.89  5302.6  813.17
  5309.8  813.06  5359.9  816.27  5374.2  817.47  5384.6  819.85  5387.9  819.85
#Mann=3,-1,0
  4544.6    0.15       0  4997.0    0.05       0  5003.0    0.15       0
Bank Sta=4997,5003
Exp/Cntr=0.3,0.1

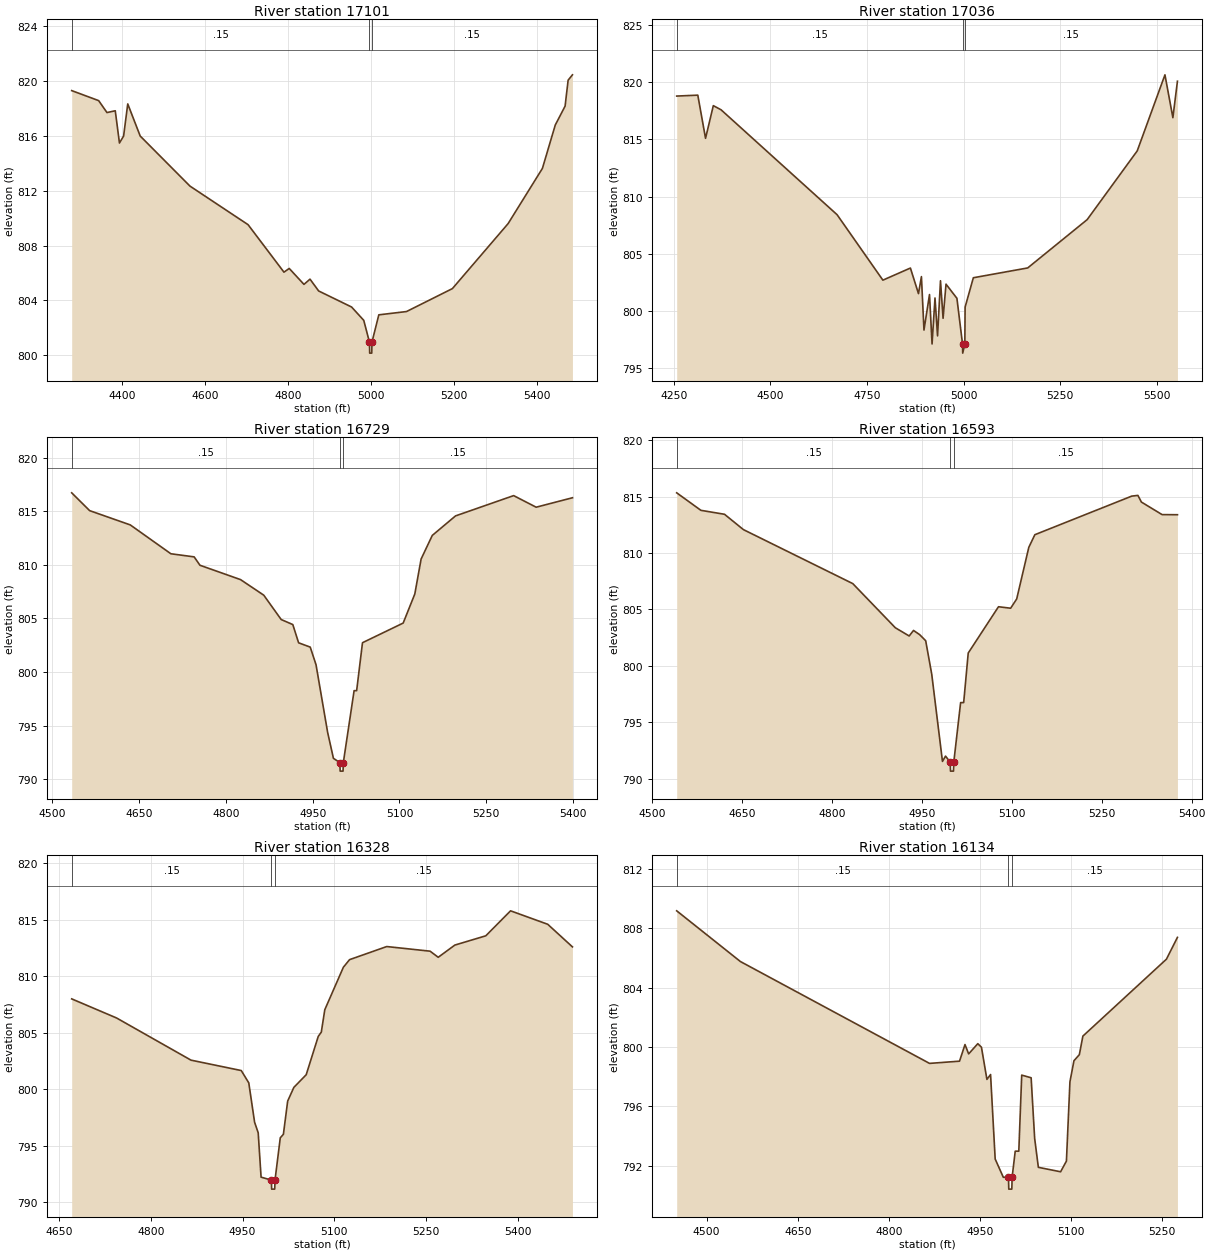
Type RM Length L Ch R = 1,17101,65,65,65
BEGIN DESCRIPTION:
UNT 095 in HW 39.0
END DESCRIPTION:
XS GIS Cut Line= 5
      2011210.04     13648146.58      2010696.98     13648141.37
      2010585.01     13648292.41      2010400.11     13648386.16
      2010324.99     13648675.04
#Sta/Elev= 30
  4279.3  819.29  4344.3  818.56  4364.3  817.69  4384.3  817.82  4394.4  815.47
  4404.4  815.98  4414.4  818.32  4444.4  815.98  4564.4  812.33  4704.4  809.52
  4790.9  806.06  4803.6  806.33  4839.1  805.17  4853.7  805.55  4874.5  804.69
  4953.9  803.52  4983.2  802.55  4997.0  800.96  4997.5  800.16  5002.5  800.16
  5003.0  800.96  5019.5  802.95  5086.3  803.19  5196.8  804.86  5331.2  809.60
  5413.8  813.62  5444.8  816.78  5468.5  818.16  5475.8  820.05  5486.2  820.44
#Mann=3,-1,0
  4279.3    0.15       0  4997.0    0.05       0  5003.0    0.15       0
Bank Sta=4997,5003
Exp/Cntr=0.3,0.1

Type RM Length L Ch R = 1,17036,307,307,307
BEGIN DESCRIPTION:
Mapping XS c19c7df9
END DESCRIPTION:
XS GIS Cut Line= 5
      2011199.57     13648091.89      2010704.80     13648071.06
      2010564.17     13648232.52      2010379.28     13648347.10
      2010298.54     13648706.49
#Sta/Elev= 30
  4257.7  818.80  4312.3  818.88  4332.3  815.10  4352.4  817.96  4372.4  817.60
  4672.6  808.41  4791.0  802.68  4862.2  803.74  4883.1  801.50  4890.7  802.99
  4897.3  798.31  4911.6  801.42  4918.2  797.09  4925.8  801.12  4932.4  797.80
  4940.0  802.63  4946.7  799.34  4954.3  802.33  4982.5  801.09  4997.0  797.09
  4997.5  796.29  5003.0  797.09  5003.7  800.32  5025.0  802.89  5165.6  803.75
  5319.4  807.98  5448.9  814.00  5520.6  820.66  5541.1  816.91  5552.9  820.10
#Mann=3,-1,0
  4257.7    0.15       0  4997.0    0.05       0  5003.0    0.15       0
Bank Sta=4997,5003
Exp/Cntr=0.3,0.1

Type RM Length L Ch R = 1,16729,136,136,136
BEGIN DESCRIPTION:
UNT 095 in HW 38.0
END DESCRIPTION:
XS GIS Cut Line= 3
      2011105.88     13648039.81      2010618.86     13648000.75
      2010243.91     13647964.29
#Sta/Elev= 30
  4533.6  816.71  4564.6  815.05  4634.8  813.72  4705.0  811.03  4745.2  810.74
  4755.2  809.96  4825.4  808.62  4865.5  807.17  4895.6  804.90  4915.7  804.43
  4925.7  802.73  4945.8  802.33  4955.8  800.69  4975.9  794.37  4985.9  791.96
  4997.0  791.57  4997.5  790.77  5002.5  790.77  5003.0  791.57  5021.6  798.27
  5026.0  798.27  5036.1  802.74  5106.4  804.57  5126.5  807.28  5137.4  810.54
  5156.7  812.74  5196.9  814.56  5297.3  816.45  5336.2  815.37  5398.9  816.25
#Mann=3,-1,0
  4533.6    0.15       0  4997.0    0.05       0  5003.0    0.15       0
Bank Sta=4997,5003
Exp/Cntr=0.3,0.1

Type RM Length L Ch R = 1,16593,265,265,265
BEGIN DESCRIPTION:
UNT 095 in HW 37.0
END DESCRIPTION:
XS GIS Cut Line= 3
      2011144.87     13647953.87      2010675.00     13647875.00
      2010319.70     13647821.11
#Sta/Elev= 30
  4540.5  815.33  4580.9  813.78  4620.3  813.43  4651.9  812.07  4834.4  807.29
  4905.4  803.38  4928.5  802.65  4935.8  803.14  4946.0  802.77  4956.1  802.23
  4966.2  799.26  4984.1  791.54  4989.2  792.01  4997.0  791.48  4997.5  790.68
  5002.5  790.68  5003.0  791.48  5014.4  796.75  5019.5  796.75  5027.1  801.14
  5077.6  805.24  5097.9  805.11  5108.0  805.93  5128.2  810.50  5138.3  811.62
  5300.1  815.04  5310.3  815.10  5316.2  814.51  5350.7  813.40  5376.3  813.39
#Mann=3,-1,0
  4540.5    0.15       0  4997.0    0.05       0  5003.0    0.15       0
Bank Sta=4997,5003
Exp/Cntr=0.3,0.1

Type RM Length L Ch R = 1,16328,194,194,194
BEGIN DESCRIPTION:
UNT 095 in HW 36.0
END DESCRIPTION:
XS GIS Cut Line= 3
      2011040.69     13647789.78      2010775.00     13647625.00
      2010275.10     13647545.02
#Sta/Elev= 30
  4670.5  808.01  4743.9  806.32  4865.6  802.59  4947.8  801.67  4960.1  800.58
  4969.6  797.10  4975.5  796.16  4980.2  792.24  4997.0  791.98  4997.5  791.18
  5002.5  791.18  5003.0  791.98  5011.6  795.72  5016.7  796.03  5023.7  798.97
  5033.8  800.18  5054.0  801.30  5073.7  804.69  5078.7  805.07  5084.4  807.05
  5114.8  810.81  5124.9  811.48  5185.7  812.64  5256.6  812.23  5269.9  811.69
  5297.1  812.77  5347.7  813.59  5388.2  815.80  5449.0  814.61  5489.4  812.61
#Mann=3,-1,0
  4670.5    0.15       0  4997.0    0.05       0  5003.0    0.15       0
Bank Sta=4997,5003
Exp/Cntr=0.3,0.1

Type RM Length L Ch R = 1,16134,265,265,265
BEGIN DESCRIPTION:
UNT 095 in HW 35.0
END DESCRIPTION:
XS GIS Cut Line= 3
      2011191.77     13647735.11      2010725.00     13647425.00
      2010499.52     13647287.48
#Sta/Elev= 30
  4450.7  809.18  4555.6  805.76  4867.0  798.89  4916.4  799.04  4925.4  800.16
  4931.4  799.53  4946.5  800.22  4952.5  799.98  4961.5  797.81  4967.5  798.14
  4975.1  792.44  4988.5  791.21  4997.0  791.21  4997.5  790.41  5002.5  790.41
  5003.0  791.21  5008.1  792.97  5014.0  792.97  5018.8  798.10  5034.3  797.92
  5040.1  793.83  5046.2  791.88  5082.8  791.58  5092.4  792.30  5098.2  797.65
  5104.8  799.07  5113.7  799.48  5119.5  800.73  5257.1  805.92  5275.2  807.39
#Mann=3,-1,0
  4450.7    0.15       0  4997.0    0.05       0  5003.0    0.15       0
Bank Sta=4997,5003
Exp/Cntr=0.3,0.1

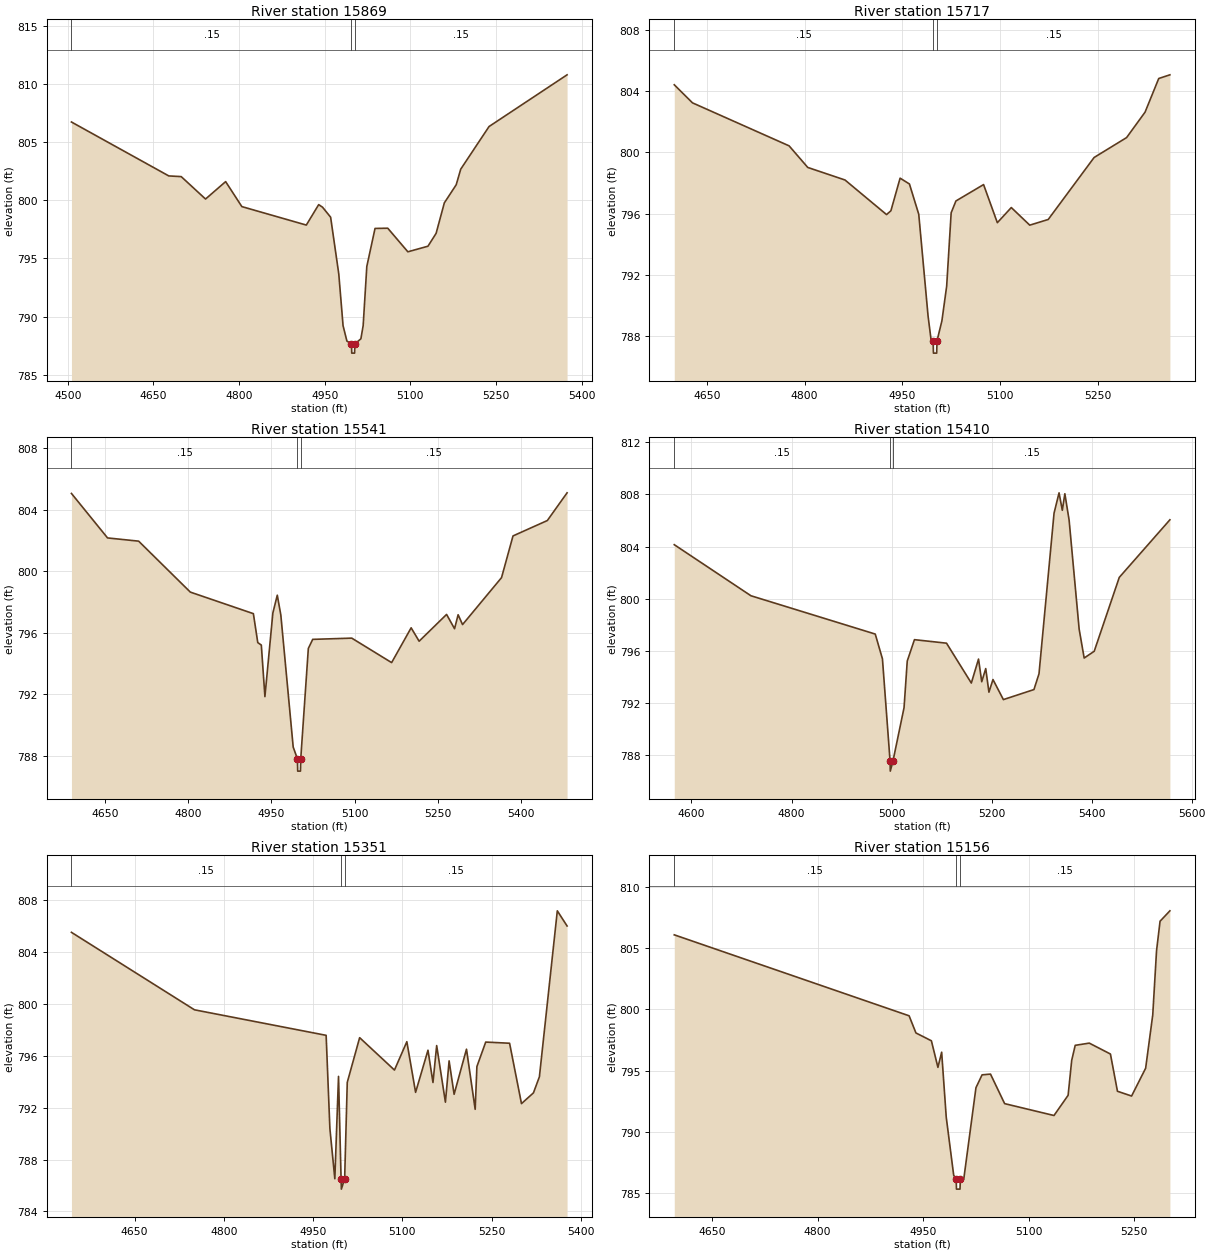
Type RM Length L Ch R = 1,15869,152,152,152
BEGIN DESCRIPTION:
UNT 095 in HW 34.0
END DESCRIPTION:
XS GIS Cut Line= 3
      2011259.47     13647651.77      2010925.00     13647275.00
      2010642.33     13647045.05
#Sta/Elev= 30
  4506.5  806.74  4677.0  802.10  4698.8  802.04  4741.4  800.11  4776.6  801.61
  4805.0  799.46  4917.9  797.87  4939.6  799.63  4946.3  799.41  4960.5  798.55
  4974.8  793.66  4982.3  789.21  4989.0  787.89  4997.0  787.65  4997.5  786.85
  5002.5  786.85  5003.0  787.65  5013.5  788.08  5017.5  789.22  5023.9  794.31
  5038.3  797.58  5060.6  797.60  5095.8  795.57  5131.0  796.05  5145.3  797.16
  5159.7  799.78  5180.5  801.34  5188.4  802.68  5238.0  806.35  5374.7  810.80
#Mann=3,-1,0
  4506.5    0.15       0  4997.0    0.05       0  5003.0    0.15       0
Bank Sta=4997,5003
Exp/Cntr=0.3,0.1

Type RM Length L Ch R = 1,15717,176,176,176
BEGIN DESCRIPTION:
UNT 095 in HW 33.0
END DESCRIPTION:
XS GIS Cut Line= 3
      2011330.73     13647528.08      2011073.81     13647226.02
      2010809.96     13646976.06
#Sta/Elev= 30
  4600.1  804.42  4628.0  803.24  4776.2  800.43  4804.8  799.02  4861.9  798.20
  4925.6  795.94  4932.3  796.19  4946.4  798.32  4960.7  797.94  4975.0  795.96
  4989.3  789.31  4994.0  787.72  4997.0  787.69  4997.5  786.89  5002.5  786.89
  5003.0  787.69  5010.5  789.00  5017.8  791.26  5024.7  796.06  5032.0  796.83
  5074.4  797.90  5095.5  795.41  5116.9  796.40  5145.2  795.25  5173.5  795.62
  5243.9  799.67  5293.7  800.97  5322.0  802.63  5343.0  804.83  5360.1  805.07
#Mann=3,-1,0
  4600.1    0.15       0  4997.0    0.05       0  5003.0    0.15       0
Bank Sta=4997,5003
Exp/Cntr=0.3,0.1

Type RM Length L Ch R = 1,15541,131,131,131
BEGIN DESCRIPTION:
UNT 095 in HW 32.0
END DESCRIPTION:
XS GIS Cut Line= 4
      2011481.79     13647469.07      2011329.02     13647272.90
      2011019.92     13646891.50      2010870.51     13646853.23
#Sta/Elev= 30
  4589.5  805.05  4654.6  802.16  4710.7  801.95  4803.9  798.64  4917.6  797.24
  4925.5  795.36  4931.9  795.20  4938.4  791.85  4952.7  797.28  4960.7  798.44
  4967.1  797.15  4989.4  788.57  4997.0  787.81  4997.5  787.01  5002.5  787.01
  5003.0  787.81  5016.7  794.98  5024.6  795.57  5095.0  795.65  5166.9  794.06
  5202.1  796.32  5216.5  795.45  5266.0  797.19  5280.4  796.26  5286.8  797.17
  5294.8  796.53  5365.1  799.58  5385.8  802.29  5447.7  803.29  5483.3  805.09
#Mann=3,-1,0
  4589.5    0.15       0  4997.0    0.05       0  5003.0    0.15       0
Bank Sta=4997,5003
Exp/Cntr=0.3,0.1

Type RM Length L Ch R = 1,15410,59,59,59
BEGIN DESCRIPTION:
Mapping XS 8f8c806a
END DESCRIPTION:
XS GIS Cut Line= 3
      2011599.88     13647404.87      2011162.35     13646856.23
      2010874.17     13646832.40
#Sta/Elev= 30
  4565.6  804.14  4718.9  800.22  4967.4  797.28  4981.8  795.38  4997.0  787.56
  4997.5  786.76  5003.0  787.56  5025.0  791.63  5031.4  795.21  5045.8  796.85
  5109.9  796.58  5159.5  793.52  5173.9  795.36  5180.3  793.62  5188.3  794.63
  5194.7  792.82  5202.8  793.79  5223.6  792.25  5284.7  793.02  5294.8  794.23
  5324.9  806.56  5334.9  808.12  5341.4  806.78  5346.5  808.05  5355.0  806.03
  5375.1  797.65  5385.1  795.44  5405.2  795.96  5455.3  801.63  5556.5  806.05
#Mann=3,-1,0
  4565.6    0.15       0  4997.0    0.05       0  5003.0    0.15       0
Bank Sta=4997,5003
Exp/Cntr=0.3,0.1

Type RM Length L Ch R = 1,15351,195,195,195
BEGIN DESCRIPTION:
Mapping XS 7a32d375
END DESCRIPTION:
XS GIS Cut Line= 3
      2011634.55     13647383.98      2011228.33     13646835.40
      2011078.59     13646845.73
#Sta/Elev= 30
  4544.0  805.54  4750.7  799.56  4971.9  797.59  4978.2  790.40  4986.5  786.52
  4992.7  794.42  4997.0  786.52  4997.5  785.72  5003.0  786.52  5007.4  793.96
  5028.2  797.41  5086.7  794.91  5107.5  797.10  5122.2  793.19  5143.0  796.44
  5151.4  793.95  5157.6  796.80  5172.3  792.43  5178.5  795.62  5186.9  793.04
  5207.7  796.52  5222.3  791.88  5225.2  795.18  5240.0  797.07  5280.1  796.98
  5300.1  792.32  5320.2  793.15  5330.2  794.39  5360.3  807.20  5376.7  806.03
#Mann=3,-1,0
  4544.0    0.15       0  4997.0    0.05       0  5003.0    0.15       0
Bank Sta=4997,5003
Exp/Cntr=0.3,0.1

Type RM Length L Ch R = 1,15156,57,57,57
BEGIN DESCRIPTION:
Mapping XS 51bd3f4b
END DESCRIPTION:
XS GIS Cut Line= 3
      2011761.30     13646962.13      2011342.91     13646819.77
      2011080.66     13646841.55
#Sta/Elev= 30
  4596.0  806.09  4930.1  799.48  4939.8  798.08  4961.8  797.44  4971.1  795.27
  4976.4  796.51  4982.9  791.21  4993.5  786.47  4997.0  786.13  4997.5  785.33
  5002.5  785.33  5003.0  786.13  5007.8  786.13  5025.2  793.61  5033.9  794.66
  5045.9  794.72  5066.0  792.31  5136.2  791.34  5156.3  792.99  5161.4  795.84
  5166.4  797.07  5186.4  797.25  5216.5  796.36  5226.5  793.32  5246.6  792.93
  5266.6  795.20  5276.7  799.55  5282.1  804.79  5287.1  807.20  5301.1  808.05
#Mann=3,-1,0
  4596.0    0.15       0  4997.0    0.05       0  5003.0    0.15       0
Bank Sta=4997,5003
Exp/Cntr=0.3,0.1