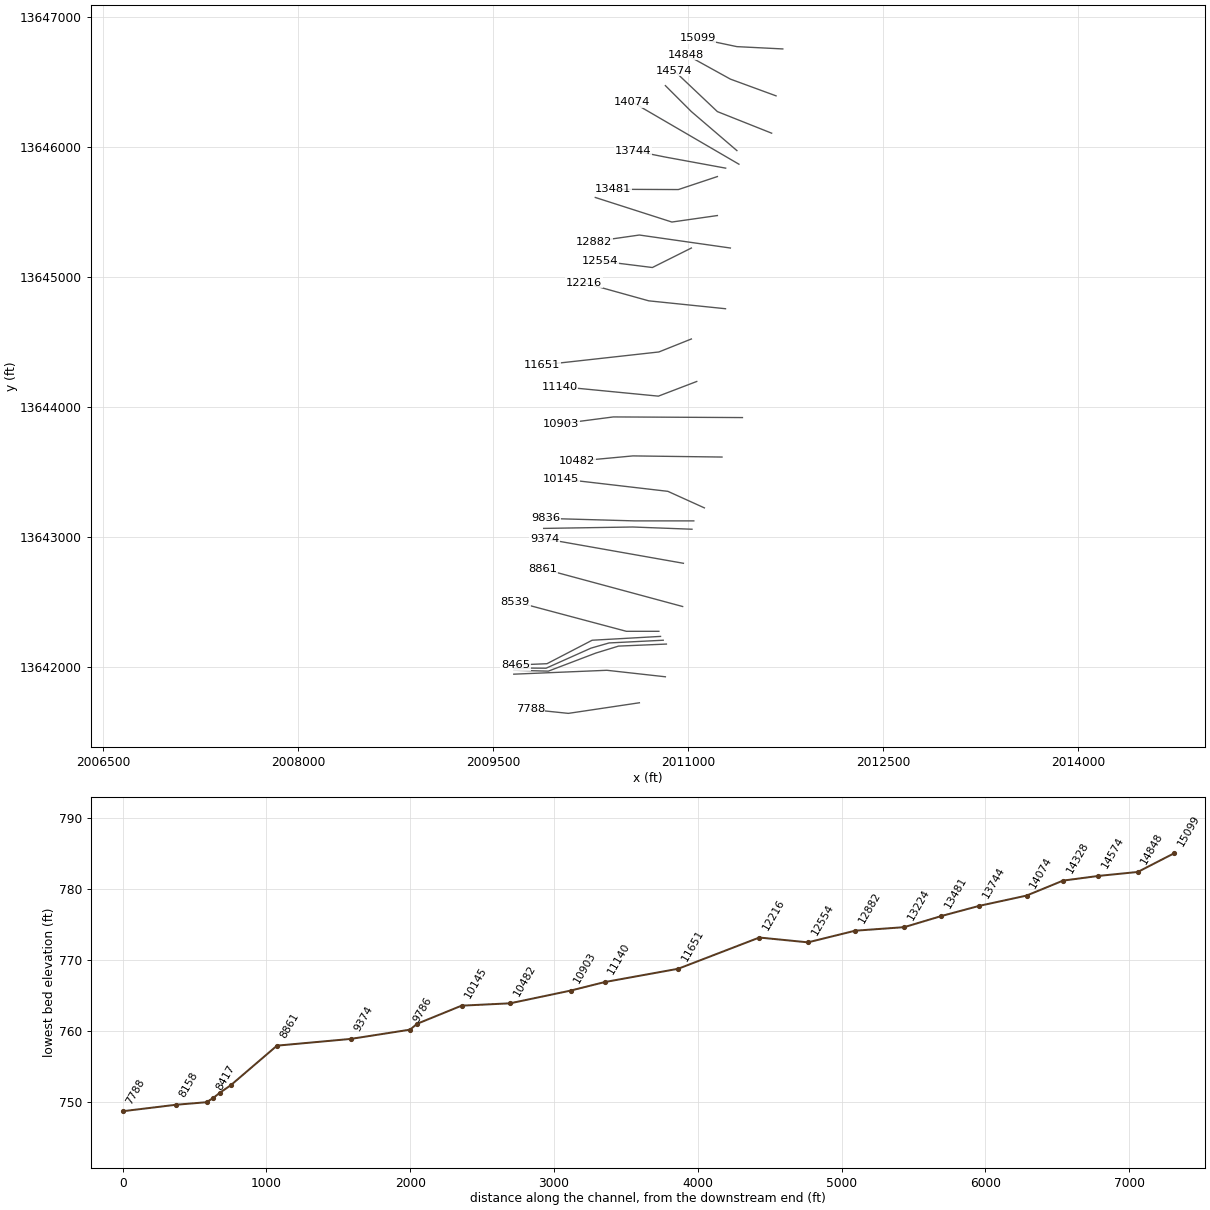
HEC-RAS study UNT 095 in HW.prj: UNT 095 in HW Base Level Engineering

--- UNT 095 in HW.g01 (geometry) --- (continued)

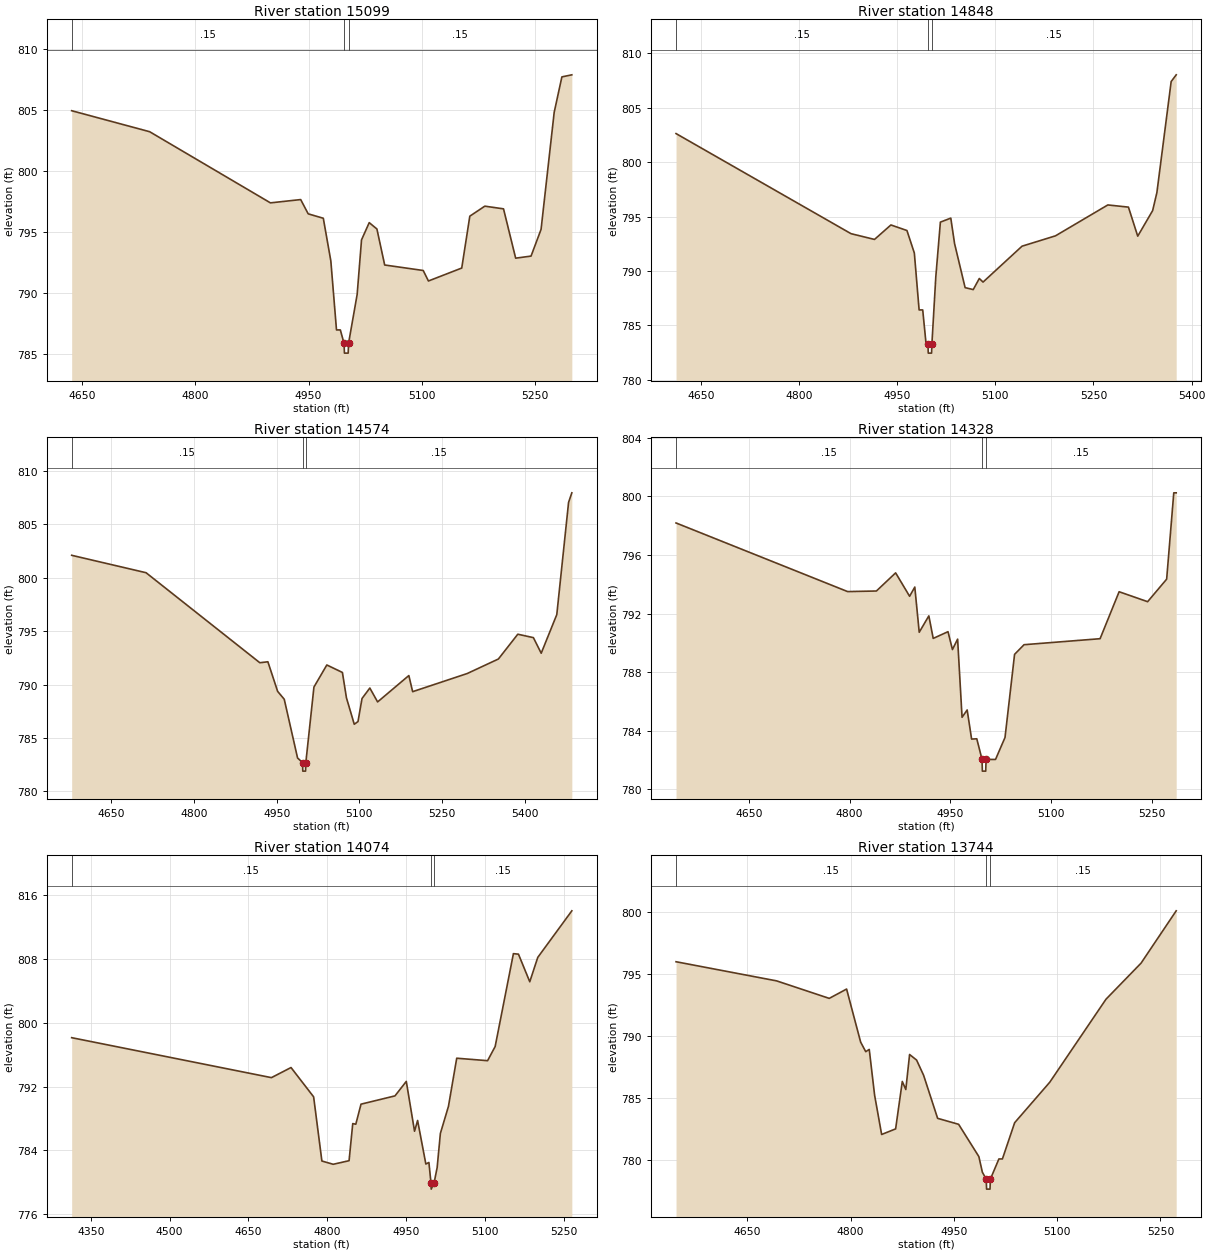
Type RM Length L Ch R = 1,15099,251,251,251
BEGIN DESCRIPTION:
UNT 095 in HW 31.0
END DESCRIPTION:
XS GIS Cut Line= 3
      2011728.30     13646757.28      2011375.00     13646775.00
      2011072.11     13646838.87
#Sta/Elev= 30
  4635.8  804.92  4739.2  803.20  4899.4  797.37  4939.5  797.64  4949.5  796.47
  4969.5  796.11  4979.5  792.61  4987.0  786.96  4992.1  786.96  4997.0  785.86
  4997.5  785.06  5002.5  785.06  5003.0  785.86  5014.4  789.87  5020.2  794.34
  5030.4  795.75  5040.6  795.23  5050.9  792.28  5102.0  791.83  5108.9  790.97
  5153.1  792.03  5163.8  796.28  5183.7  797.10  5208.5  796.88  5224.6  792.84
  5245.0  793.01  5258.3  795.20  5275.7  804.79  5285.9  807.69  5299.1  807.86
#Mann=3,-1,0
  4635.8    0.15       0  4997.0    0.05       0  5003.0    0.15       0
Bank Sta=4997,5003
Exp/Cntr=0.3,0.1

Type RM Length L Ch R = 1,14848,274,274,274
BEGIN DESCRIPTION:
UNT 095 in HW 30.0
END DESCRIPTION:
XS GIS Cut Line= 3
      2011676.28     13646396.15      2011325.00     13646525.00
      2010983.53     13646713.88
#Sta/Elev= 30
  4612.0  802.63  4879.4  793.43  4915.3  792.90  4940.4  794.23  4964.9  793.72
  4976.2  791.65  4983.5  786.42  4989.0  786.42  4994.2  783.25  4997.0  783.25
  4997.5  782.45  5002.5  782.45  5003.0  783.25  5009.0  789.46  5016.0  794.49
  5031.9  794.86  5037.7  792.51  5053.8  788.47  5066.2  788.29  5075.5  789.31
  5081.2  788.98  5140.8  792.28  5191.9  793.23  5271.9  796.07  5303.4  795.87
  5317.6  793.20  5340.4  795.55  5346.9  797.21  5368.7  807.41  5376.4  808.03
#Mann=3,-1,0
  4612.0    0.15       0  4997.0    0.05       0  5003.0    0.15       0
Bank Sta=4997,5003
Exp/Cntr=0.3,0.1

Type RM Length L Ch R = 1,14574,246,246,246
BEGIN DESCRIPTION:
UNT 095 in HW 29.0
END DESCRIPTION:
XS GIS Cut Line= 3
      2011642.39     13646108.84      2011225.00     13646275.00
      2010891.81     13646590.34
#Sta/Elev= 30
  4577.9  802.10  4712.9  800.47  4919.5  792.04  4934.1  792.13  4951.8  789.36
  4963.8  788.62  4988.0  783.12  4997.0  782.69  4997.5  781.89  5002.5  781.89
  5003.0  782.69  5017.7  789.76  5041.1  791.83  5069.4  791.13  5076.7  788.76
  5090.9  786.28  5097.7  786.53  5105.0  788.69  5119.2  789.67  5133.3  788.37
  5190.0  790.84  5196.9  789.33  5296.0  791.03  5352.6  792.39  5387.8  794.71
  5416.1  794.39  5430.3  792.93  5458.6  796.55  5480.0  807.06  5485.9  807.95
#Mann=3,-1,0
  4577.9    0.15       0  4997.0    0.05       0  5003.0    0.15       0
Bank Sta=4997,5003
Exp/Cntr=0.3,0.1

Type RM Length L Ch R = 1,14328,254,254,254
BEGIN DESCRIPTION:
UNT 095 in HW 28.0
END DESCRIPTION:
XS GIS Cut Line= 3
      2011375.04     13645974.97      2011025.00     13646275.00
      2010824.98     13646475.02
#Sta/Elev= 30
  4541.9  798.19  4797.1  793.50  4839.9  793.54  4868.5  794.78  4889.3  793.18
  4897.0  793.81  4903.6  790.72  4917.9  791.84  4924.4  790.30  4946.4  790.76
  4953.0  789.54  4960.7  790.25  4967.3  784.91  4974.9  785.41  4981.5  783.42
  4989.2  783.44  4997.0  782.03  4997.5  781.23  5002.5  781.23  5003.0  782.03
  5017.1  782.03  5031.2  783.53  5045.4  789.21  5059.5  789.87  5172.6  790.28
  5200.9  793.49  5243.3  792.81  5271.6  794.35  5282.2  800.25  5285.8  800.25
#Mann=3,-1,0
  4541.9    0.15       0  4997.0    0.05       0  5003.0    0.15       0
Bank Sta=4997,5003
Exp/Cntr=0.3,0.1

Type RM Length L Ch R = 1,14074,330,330,330
BEGIN DESCRIPTION:
Mapping XS cbe8a341
END DESCRIPTION:
XS GIS Cut Line= 2
      2011390.68     13645870.11      2010569.06     13646349.20
#Sta/Elev= 30
  4313.8  798.14  4693.7  793.12  4730.9  794.39  4773.9  790.71  4789.6  782.65
  4811.1  782.24  4841.3  782.69  4848.3  787.35  4854.1  787.27  4864.0  789.79
  4928.6  790.83  4950.1  792.65  4965.8  786.39  4971.6  787.74  4987.3  782.27
  4993.1  782.47  4997.0  779.92  4997.5  779.12  5003.0  779.92  5008.8  781.83
  5014.9  786.11  5030.3  789.52  5046.0  795.56  5104.7  795.25  5119.1  797.03
  5153.8  808.69  5163.4  808.63  5184.9  805.16  5200.1  808.22  5264.9  814.07
#Mann=3,-1,0
  4313.8    0.15       0  4997.0    0.05       0  5003.0    0.15       0
Bank Sta=4997,5003
Exp/Cntr=0.3,0.1

Type RM Length L Ch R = 1,13744,263,263,263
BEGIN DESCRIPTION:
UNT 095 in HW 27.0
END DESCRIPTION:
XS GIS Cut Line= 3
      2011288.64     13645839.74      2010825.00     13645925.00
      2010574.97     13645975.01
#Sta/Elev= 30
  4546.5  795.98  4692.5  794.44  4769.0  793.03  4794.2  793.78  4814.6  789.51
  4822.0  788.74  4827.1  788.92  4834.9  785.23  4845.1  782.07  4865.4  782.52
  4875.1  786.34  4880.2  785.69  4885.7  788.51  4895.9  788.06  4906.1  786.83
  4926.4  783.37  4956.9  782.89  4986.3  780.29  4991.4  779.03  4997.0  778.47
  4997.5  777.67  5002.5  777.67  5003.0  778.47  5015.4  780.10  5020.5  780.10
  5038.3  783.02  5089.3  786.28  5170.9  792.96  5221.9  795.87  5272.9  800.08
#Mann=3,-1,0
  4546.5    0.15       0  4997.0    0.05       0  5003.0    0.15       0
Bank Sta=4997,5003
Exp/Cntr=0.3,0.1

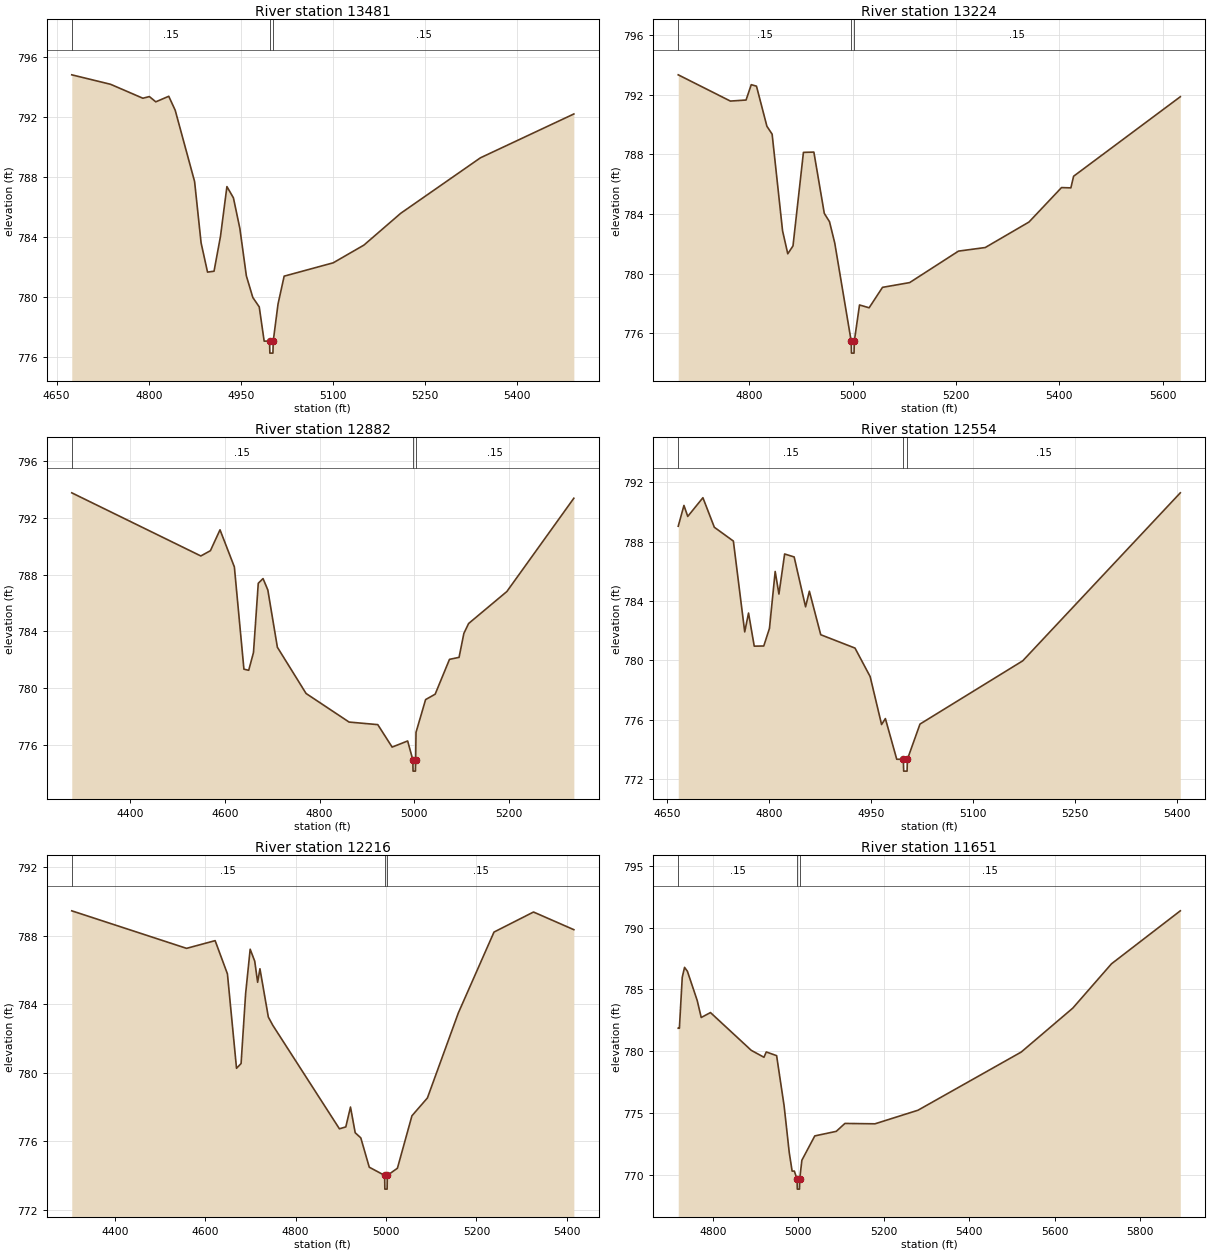
Type RM Length L Ch R = 1,13481,257,257,257
BEGIN DESCRIPTION:
UNT 095 in HW 26.0
END DESCRIPTION:
XS GIS Cut Line= 3
      2011224.96     13645774.99      2010925.00     13645675.00
      2010422.79     13645676.98
#Sta/Elev= 30
  4674.6  794.79  4737.8  794.16  4790.5  793.23  4801.1  793.34  4811.6  792.99
  4832.7  793.36  4843.2  792.43  4874.8  787.68  4885.4  783.59  4895.9  781.64
  4906.5  781.70  4917.0  784.02  4927.5  787.34  4938.1  786.59  4948.6  784.55
  4959.2  781.39  4969.7  779.95  4980.2  779.32  4988.2  777.04  4997.0  777.04
  4997.5  776.24  5002.5  776.24  5003.0  777.04  5010.8  779.51  5020.8  781.37
  5100.8  782.26  5150.8  783.44  5210.8  785.56  5340.8  789.26  5493.0  792.18
#Mann=3,-1,0
  4674.6    0.15       0  4997.0    0.05       0  5003.0    0.15       0
Bank Sta=4997,5003
Exp/Cntr=0.3,0.1

Type RM Length L Ch R = 1,13224,342,342,342
BEGIN DESCRIPTION:
UNT 095 in HW 25.0
END DESCRIPTION:
XS GIS Cut Line= 3
      2011224.98     13645475.00      2010875.00     13645425.00
      2010286.03     13645614.05
#Sta/Elev= 30
  4662.1  793.34  4763.1  791.58  4793.4  791.65  4803.5  792.68  4813.6  792.58
  4833.8  789.89  4843.9  789.36  4864.1  782.88  4874.2  781.34  4884.3  781.87
  4904.5  788.14  4924.7  788.16  4944.9  784.05  4955.0  783.49  4965.1  782.07
  4997.0  775.48  4997.5  774.68  5002.5  774.68  5003.0  775.48  5013.1  777.91
  5031.7  777.72  5057.6  779.09  5110.2  779.41  5204.7  781.52  5256.5  781.76
  5341.2  783.47  5404.2  785.78  5422.3  785.76  5427.6  786.54  5634.2  791.87
#Mann=3,-1,0
  4662.1    0.15       0  4997.0    0.05       0  5003.0    0.15       0
Bank Sta=4997,5003
Exp/Cntr=0.3,0.1

Type RM Length L Ch R = 1,12882,328,328,328
BEGIN DESCRIPTION:
UNT 095 in HW 24.0
END DESCRIPTION:
XS GIS Cut Line= 3
      2011325.00     13645225.00      2010625.00     13645325.00
      2010274.96     13645274.99
#Sta/Elev= 30
  4276.5  793.75  4549.2  789.31  4569.4  789.68  4589.7  791.15  4620.0  788.54
  4640.2  781.35  4650.3  781.27  4660.4  782.52  4670.5  787.39  4680.6  787.72
  4690.7  786.92  4710.9  782.89  4771.5  779.64  4862.4  777.63  4923.0  777.45
  4953.3  775.87  4986.1  776.30  4997.0  774.98  4997.5  774.18  5002.5  774.18
  5003.0  774.98  5003.8  776.91  5024.0  779.21  5044.2  779.59  5074.5  782.04
  5094.7  782.18  5104.8  783.86  5114.9  784.56  5195.7  786.81  5337.2  793.37
#Mann=3,-1,0
  4276.5    0.15       0  4997.0    0.05       0  5003.0    0.15       0
Bank Sta=4997,5003
Exp/Cntr=0.3,0.1

Type RM Length L Ch R = 1,12554,338,338,338
BEGIN DESCRIPTION:
UNT 095 in HW 23.0
END DESCRIPTION:
XS GIS Cut Line= 3
      2011025.01     13645225.00      2010725.00     13645075.00
      2010325.03     13645125.00
#Sta/Elev= 30
  4665.9  789.04  4674.3  790.44  4679.9  789.70  4702.2  790.96  4719.0  788.97
  4747.0  788.04  4763.7  781.92  4769.3  783.19  4777.7  780.96  4791.7  780.97
  4800.1  782.16  4808.5  785.99  4814.0  784.47  4822.4  787.17  4836.4  786.97
  4853.2  783.61  4858.8  784.66  4875.5  781.73  4925.9  780.83  4948.2  778.91
  4965.0  775.68  4970.6  776.08  4987.3  773.34  4997.0  773.34  4997.5  772.54
  5002.5  772.54  5003.0  773.34  5021.5  775.71  5172.6  779.97  5404.4  791.29
#Mann=3,-1,0
  4665.9    0.15       0  4997.0    0.05       0  5003.0    0.15       0
Bank Sta=4997,5003
Exp/Cntr=0.3,0.1

Type RM Length L Ch R = 1,12216,565,565,565
BEGIN DESCRIPTION:
UNT 095 in HW 22.0
END DESCRIPTION:
XS GIS Cut Line= 3
      2011287.53     13644757.75      2010697.29     13644818.51
      2010199.08     13644957.14
#Sta/Elev= 30
  4305.0  789.46  4558.9  787.27  4622.1  787.72  4649.3  785.78  4669.4  780.27
  4679.5  780.55  4689.5  784.62  4699.6  787.22  4709.7  786.52  4716.1  785.29
  4721.2  786.08  4739.8  783.26  4749.9  782.77  4897.0  776.74  4911.1  776.85
  4921.5  778.01  4931.9  776.51  4944.3  776.21  4963.0  774.50  4997.0  774.02
  4997.5  773.22  5002.5  773.22  5003.0  774.02  5025.3  774.44  5057.4  777.50
  5091.6  778.54  5160.0  783.50  5238.9  788.22  5326.3  789.39  5415.5  788.36
#Mann=3,-1,0
  4305.0    0.15       0  4997.0    0.05       0  5003.0    0.15       0
Bank Sta=4997,5003
Exp/Cntr=0.3,0.1

Type RM Length L Ch R = 1,11651,511,511,511
BEGIN DESCRIPTION:
UNT 095 in HW 21.0
END DESCRIPTION:
XS GIS Cut Line= 3
      2011024.97     13644524.99      2010775.00     13644425.00
      2009874.97     13644325.00
#Sta/Elev= 30
  4718.9  781.85  4721.6  781.85  4728.3  785.98  4733.7  786.78  4740.4  786.46
  4763.3  784.10  4772.7  782.72  4794.3  783.12  4889.8  780.06  4919.5  779.50
  4924.9  779.93  4949.1  779.63  4966.6  775.58  4978.7  771.77  4985.4  770.28
  4990.6  770.28  4997.0  769.62  4997.5  768.82  5002.6  768.82  5003.1  769.62
  5008.2  771.16  5038.4  773.13  5088.7  773.50  5108.9  774.14  5179.3  774.11
  5279.9  775.21  5521.4  779.92  5642.1  783.48  5732.7  787.07  5893.7  791.36
#Mann=3,-1,0
  4718.9    0.15       0  4997.0    0.05       0  5003.1    0.15       0
Bank Sta=4997,5003.1
Exp/Cntr=0.3,0.1

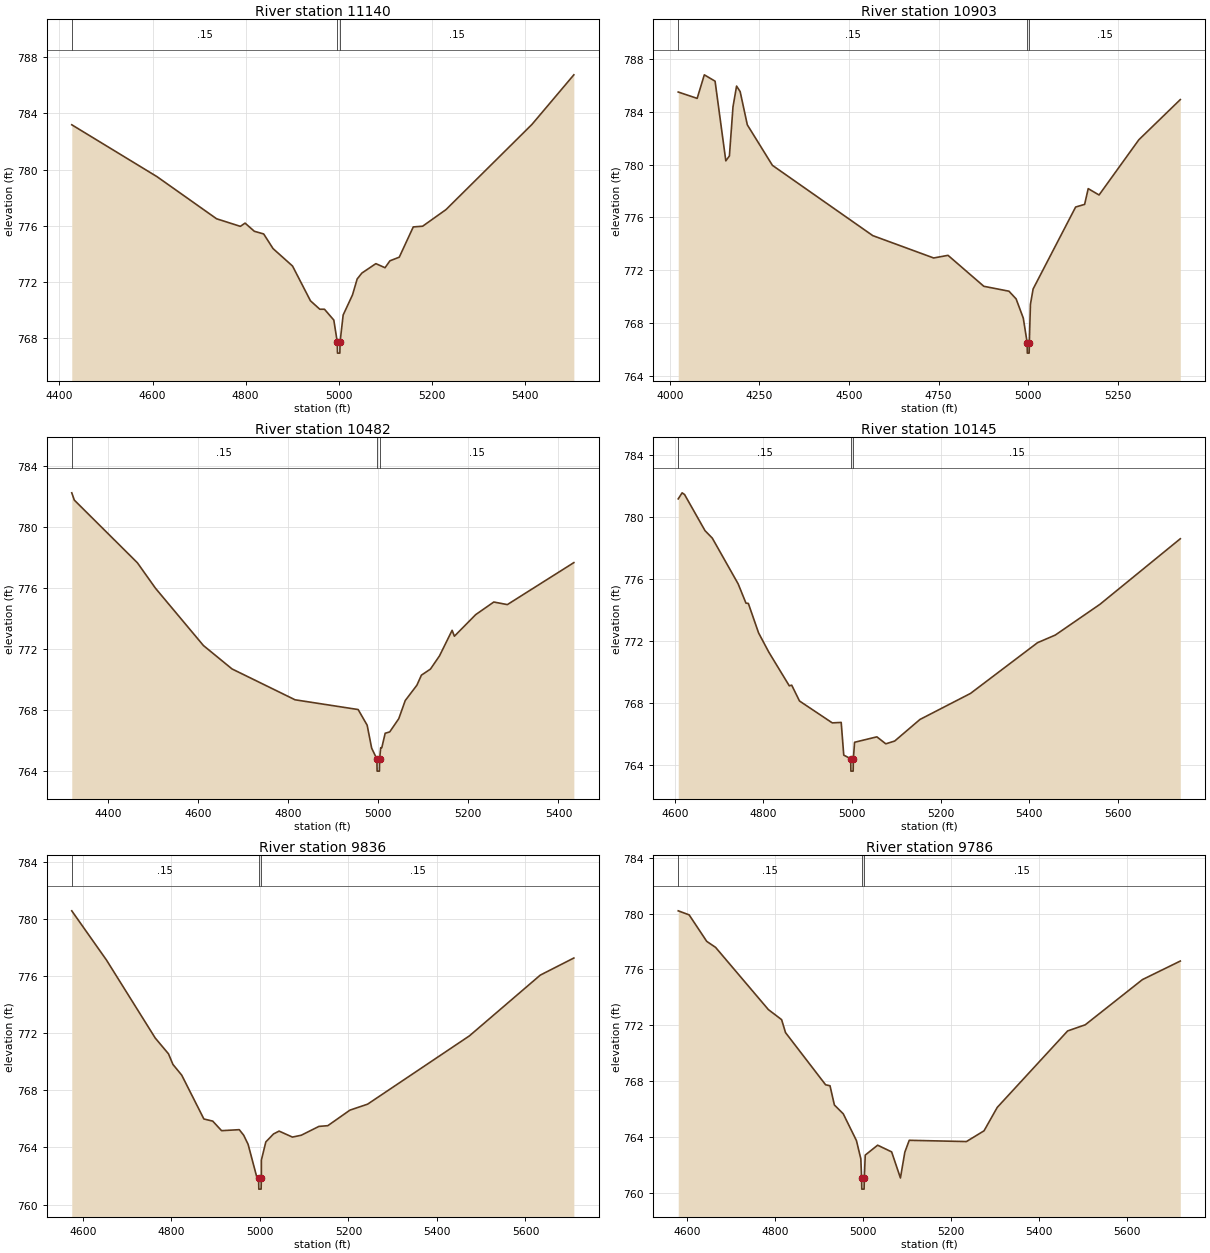
Type RM Length L Ch R = 1,11140,237,237,237
BEGIN DESCRIPTION:
Mapping XS 7be4677d
END DESCRIPTION:
XS GIS Cut Line= 3
      2011066.22     13644197.85      2010771.08     13644085.00
      2010011.53     13644158.79
#Sta/Elev= 30
  4426.4  783.18  4609.7  779.49  4737.6  776.50  4788.7  775.96  4798.9  776.19
  4818.8  775.61  4838.9  775.42  4859.0  774.38  4900.9  773.14  4939.4  770.67
  4959.5  770.07  4969.5  770.07  4989.6  769.30  4997.0  767.75  4997.5  766.95
  5002.6  766.95  5003.1  767.75  5009.7  769.66  5029.8  771.09  5039.8  772.22
  5049.9  772.64  5080.0  773.31  5099.7  773.02  5110.2  773.51  5130.3  773.77
  5160.4  775.92  5180.5  775.97  5230.7  777.15  5415.6  783.21  5505.5  786.73
#Mann=3,-1,0
  4426.4    0.15       0  4997.0    0.05       0  5003.1    0.15       0
Bank Sta=4997,5003.1
Exp/Cntr=0.3,0.1

Type RM Length L Ch R = 1,10903,421,421,421
BEGIN DESCRIPTION:
UNT 095 in HW 20.0
END DESCRIPTION:
XS GIS Cut Line= 3
      2011417.77     13643920.07      2010425.00     13643925.00
      2010020.19     13643872.33
#Sta/Elev= 30
  4023.4  785.48  4076.2  785.00  4096.2  786.78  4126.2  786.30  4156.2  780.28
  4166.2  780.65  4176.2  784.36  4186.2  785.93  4196.2  785.51  4216.2  783.00
  4286.2  779.94  4566.2  774.63  4736.2  772.94  4776.2  773.14  4876.2  770.80
  4946.2  770.43  4966.2  769.85  4986.2  768.40  4997.0  766.55  4997.5  765.75
  5002.6  765.75  5003.1  766.55  5006.2  769.44  5013.7  770.60  5132.3  776.79
  5157.4  776.99  5167.4  778.18  5197.7  777.70  5308.6  781.87  5424.4  784.91
#Mann=3,-1,0
  4023.4    0.15       0  4997.0    0.05       0  5003.1    0.15       0
Bank Sta=4997,5003.1
Exp/Cntr=0.3,0.1

Type RM Length L Ch R = 1,10482,337,337,337
BEGIN DESCRIPTION:
UNT 095 in HW 19.0
END DESCRIPTION:
XS GIS Cut Line= 3
      2011260.65     13643616.25      2010575.00     13643625.00
      2010148.06     13643585.19
#Sta/Elev= 30
  4319.7  782.26  4325.4  781.78  4465.4  777.66  4505.4  775.99  4611.9  772.22
  4675.4  770.68  4815.4  768.65  4955.4  768.01  4975.4  766.98  4985.4  765.47
  4997.0  764.76  4997.5  763.96  5002.6  763.96  5003.1  764.76  5005.4  765.50
  5007.9  765.50  5015.4  766.45  5025.5  766.54  5045.6  767.41  5059.9  768.60
  5085.8  769.61  5095.8  770.27  5115.9  770.67  5136.0  771.54  5164.0  773.22
  5169.0  772.83  5216.3  774.25  5256.5  775.08  5286.6  774.91  5434.2  777.67
#Mann=3,-1,0
  4319.7    0.15       0  4997.0    0.05       0  5003.1    0.15       0
Bank Sta=4997,5003.1
Exp/Cntr=0.3,0.1

Type RM Length L Ch R = 1,10145,309,309,309
BEGIN DESCRIPTION:
UNT 095 in HW 18.0
END DESCRIPTION:
XS GIS Cut Line= 3
      2011125.02     13643224.99      2010844.00     13643352.36
      2010024.58     13643447.85
#Sta/Elev= 30
  4607.7  781.18  4616.5  781.57  4622.0  781.46  4668.2  779.13  4684.6  778.65
  4743.0  775.70  4760.6  774.46  4766.0  774.44  4789.1  772.54  4812.2  771.30
  4858.4  769.13  4863.9  769.17  4881.5  768.15  4955.5  766.74  4975.6  766.77
  4981.4  764.66  4997.0  764.43  4997.5  763.63  5002.6  763.63  5003.1  764.43
  5005.8  765.49  5056.2  765.84  5076.3  765.39  5096.4  765.57  5153.4  766.96
  5267.6  768.64  5418.9  771.91  5458.9  772.40  5559.6  774.38  5741.2  778.61
#Mann=3,-1,0
  4607.7    0.15       0  4997.0    0.05       0  5003.1    0.15       0
Bank Sta=4997,5003.1
Exp/Cntr=0.3,0.1

Type RM Length L Ch R = 1,9836,50,50,50
BEGIN DESCRIPTION:
UNT 095 in HW 17.0
END DESCRIPTION:
XS GIS Cut Line= 3
      2011043.63     13643124.93      2010585.31     13643124.93
      2009909.10     13643144.00
#Sta/Elev= 30
  4574.6  780.60  4653.2  777.14  4763.2  771.68  4793.2  770.57  4803.2  769.83
  4823.2  769.07  4873.2  766.00  4893.2  765.85  4913.2  765.18  4953.2  765.25
  4963.2  764.86  4973.2  764.22  4993.2  761.88  4996.9  761.88  4997.4  761.08
  5002.6  761.08  5003.1  761.88  5003.2  763.12  5013.2  764.39  5030.6  764.95
  5043.2  765.15  5073.3  764.73  5093.3  764.86  5133.3  765.48  5153.3  765.53
  5203.3  766.62  5243.3  767.04  5473.4  771.83  5633.5  776.09  5709.4  777.29
#Mann=3,-1,0
  4574.6    0.15       0  4996.9    0.05       0  5003.1    0.15       0
Bank Sta=4996.9,5003.1
Exp/Cntr=0.3,0.1

Type RM Length L Ch R = 1,9786,412,412,412
BEGIN DESCRIPTION:
UNT 095 in HW 16.0
END DESCRIPTION:
XS GIS Cut Line= 3
      2011029.79     13643060.69      2010573.61     13643077.84
      2009888.90     13643067.01
#Sta/Elev= 30
  4580.1  780.20  4604.9  779.91  4644.9  778.01  4665.0  777.58  4785.0  773.12
  4815.1  772.40  4824.0  771.47  4915.1  767.73  4925.1  767.66  4935.1  766.28
  4955.2  765.65  4985.2  763.73  4995.2  762.42  4996.9  761.05  4997.4  760.25
  5002.6  760.25  5003.1  761.05  5005.2  762.69  5033.4  763.40  5065.2  762.92
  5085.2  761.05  5095.2  762.90  5105.2  763.75  5235.2  763.66  5275.2  764.43
  5305.3  766.11  5465.3  771.59  5505.3  772.03  5635.3  775.27  5721.4  776.60
#Mann=3,-1,0
  4580.1    0.15       0  4996.9    0.05       0  5003.1    0.15       0
Bank Sta=4996.9,5003.1
Exp/Cntr=0.3,0.1

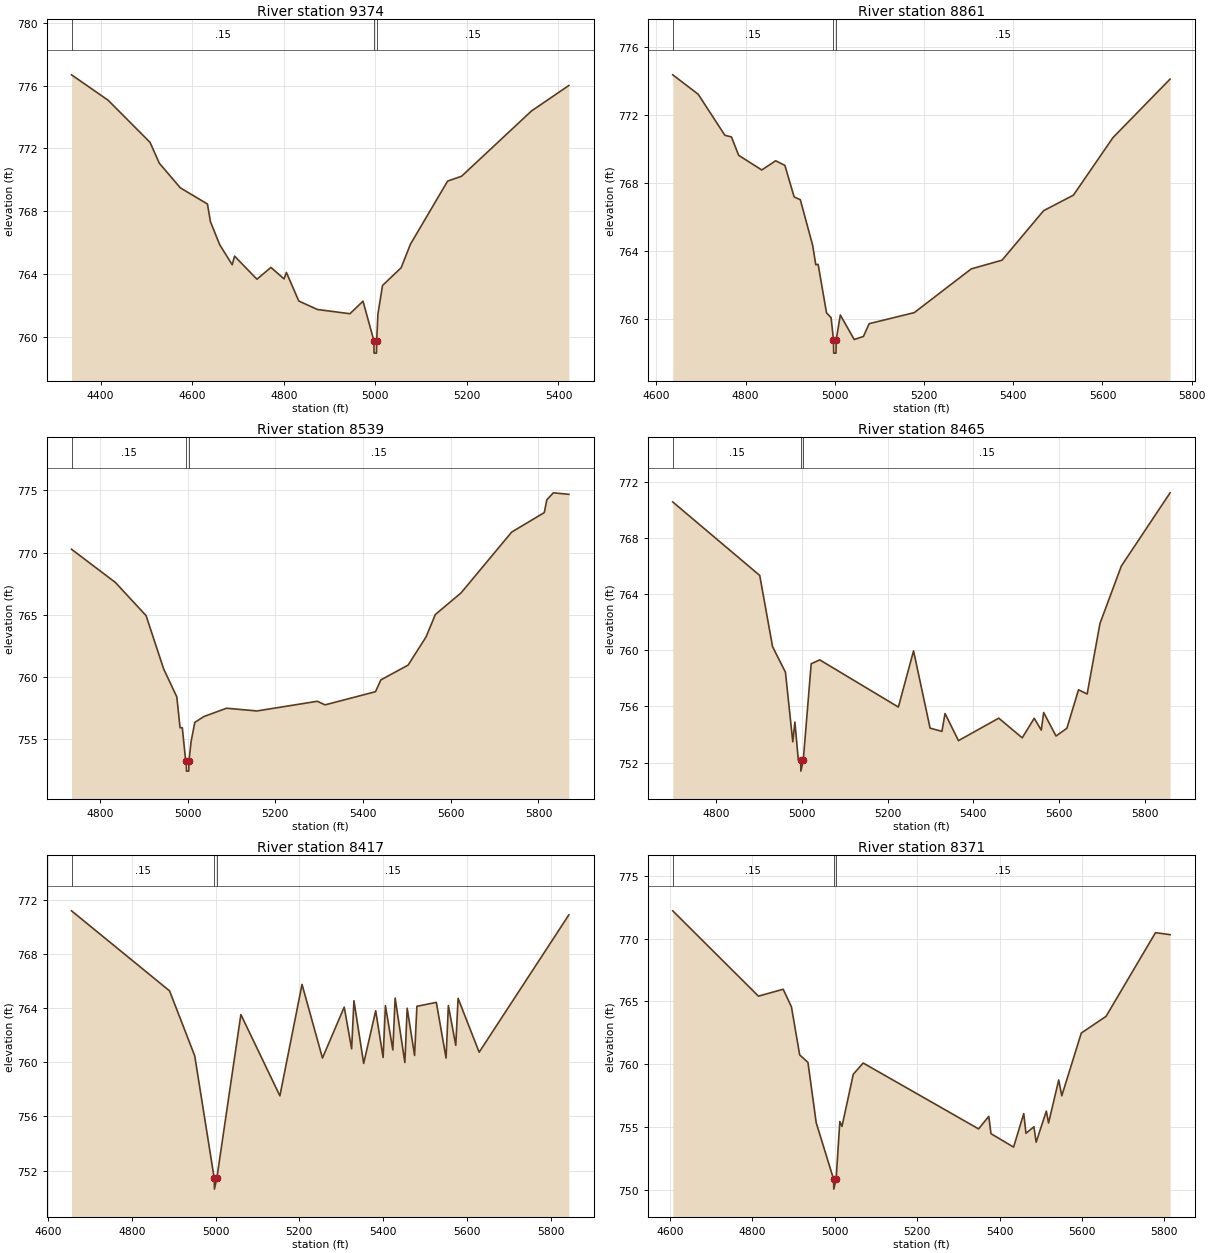
Type RM Length L Ch R = 1,9374,513,513,513
BEGIN DESCRIPTION:
Mapping XS cd58cfbb
END DESCRIPTION:
XS GIS Cut Line= 2
      2010963.74     13642798.55      2009894.35     13642987.78
#Sta/Elev= 30
  4336.7  776.68  4416.7  775.06  4508.1  772.38  4528.4  771.05  4574.3  769.48
  4633.5  768.45  4640.1  767.32  4660.4  765.85  4687.6  764.58  4692.7  765.13
  4741.6  763.66  4772.1  764.41  4800.8  763.68  4805.9  764.09  4833.0  762.27
  4873.7  761.73  4944.7  761.46  4973.2  762.26  4996.9  759.75  4997.4  758.95
  5002.6  758.95  5003.1  759.75  5005.7  761.42  5015.8  763.26  5056.5  764.39
  5076.8  765.89  5158.0  769.91  5188.5  770.22  5340.8  774.37  5422.7  776.00
#Mann=3,-1,0
  4336.7    0.15       0  4996.9    0.05       0  5003.1    0.15       0
Bank Sta=4996.9,5003.1
Exp/Cntr=0.3,0.1

Type RM Length L Ch R = 1,8861,322,322,322
BEGIN DESCRIPTION:
Mapping XS 01d7a11f
END DESCRIPTION:
XS GIS Cut Line= 2
      2010957.72     13642465.86      2009881.31     13642756.67
#Sta/Elev= 30
  4636.6  774.35  4693.6  773.21  4753.4  770.80  4768.2  770.70  4784.4  769.62
  4836.2  768.76  4867.3  769.30  4888.0  769.03  4908.7  767.18  4922.6  767.01
  4950.2  764.34  4957.3  763.19  4962.5  763.22  4981.3  760.37  4991.6  760.08
  4996.9  758.80  4997.4  758.00  5002.6  758.00  5003.1  758.80  5012.3  760.24
  5043.4  758.80  5064.1  758.98  5076.9  759.73  5178.1  760.38  5305.9  762.95
  5374.9  763.46  5468.1  766.37  5534.9  767.28  5623.5  770.66  5751.6  774.10
#Mann=3,-1,0
  4636.6    0.15       0  4996.9    0.05       0  5003.1    0.15       0
Bank Sta=4996.9,5003.1
Exp/Cntr=0.3,0.1

Type RM Length L Ch R = 1,8539,74,74,74
BEGIN DESCRIPTION:
UNT 095 in HW 15.0
END DESCRIPTION:
XS GIS Cut Line= 3
      2010775.00     13642275.00      2010525.00     13642275.00
      2009670.84     13642502.75
#Sta/Elev= 30
  4735.3  770.27  4835.3  767.60  4905.3  764.93  4945.3  760.65  4975.3  758.40
  4982.8  755.91  4987.9  755.91  4995.7  753.22  4996.9  753.22  4997.4  752.42
  5002.6  752.42  5003.1  753.22  5007.9  754.80  5016.4  756.34  5037.0  756.81
  5088.8  757.48  5158.0  757.26  5295.8  758.04  5313.3  757.75  5428.4  758.81
  5440.7  759.76  5502.8  760.95  5543.6  763.21  5564.9  765.02  5623.8  766.77
  5738.9  771.65  5813.3  773.22  5819.1  774.25  5834.0  774.81  5869.3  774.69
#Mann=3,-1,0
  4735.3    0.15       0  4996.9    0.05       0  5003.1    0.15       0
Bank Sta=4996.9,5003.1
Exp/Cntr=0.3,0.1

Type RM Length L Ch R = 1,8465,48,48,48
BEGIN DESCRIPTION:
Mapping XS ade9ea11
END DESCRIPTION:
XS GIS Cut Line= 4
      2010787.74     13642235.82      2010261.71     13642206.31
      2009914.49     13642025.75      2009671.43     13642015.34
#Sta/Elev= 30
  4698.2  770.55  4901.3  765.32  4931.3  760.25  4961.4  758.43  4978.5  753.48
  4983.5  754.88  4991.4  752.19  4996.9  752.19  4997.4  751.39  5003.1  752.19
  5021.5  759.03  5041.5  759.31  5225.1  755.95  5260.6  759.95  5299.2  754.45
  5326.9  754.22  5334.1  755.49  5365.5  753.56  5459.6  755.16  5514.4  753.76
  5542.4  755.15  5558.9  754.31  5564.5  755.56  5593.3  753.89  5618.7  754.44
  5645.9  757.18  5666.0  756.88  5696.0  761.90  5745.9  765.99  5859.7  771.20
#Mann=3,-1,0
  4698.2    0.15       0  4996.9    0.05       0  5003.1    0.15       0
Bank Sta=4996.9,5003.1
Exp/Cntr=0.3,0.1

Type RM Length L Ch R = 1,8417,46,46,46
BEGIN DESCRIPTION:
Mapping XS 49e6d05e
END DESCRIPTION:
XS GIS Cut Line= 5
      2010808.58     13642206.31      2010391.92     13642185.48
      2010253.03     13642145.55      2009907.54     13641991.03
      2009661.01     13641992.77
#Sta/Elev= 30
  4656.4  771.18  4890.3  765.27  4950.4  760.47  4996.9  751.43  4997.4  750.63
  5003.1  751.43  5060.5  763.52  5153.6  757.52  5206.4  765.75  5255.2  760.31
  5307.1  764.07  5324.8  760.99  5330.3  764.54  5353.5  759.91  5382.2  763.80
  5399.9  760.35  5405.4  764.18  5423.1  760.91  5428.6  764.74  5451.8  759.98
  5457.3  763.99  5475.0  760.50  5480.5  764.13  5526.9  764.42  5550.1  760.31
  5555.6  764.18  5573.3  761.25  5578.8  764.72  5629.1  760.74  5843.1  770.88
#Mann=3,-1,0
  4656.4    0.15       0  4996.9    0.05       0  5003.1    0.15       0
Bank Sta=4996.9,5003.1
Exp/Cntr=0.3,0.1

Type RM Length L Ch R = 1,8371,213,213,213
BEGIN DESCRIPTION:
Mapping XS cca78848
END DESCRIPTION:
XS GIS Cut Line= 5
      2010832.86     13642176.80      2010464.83     13642161.17
      2010289.49     13642107.35      2009924.90     13641968.46
      2009659.62     13641975.40
#Sta/Elev= 30
  4606.5  772.22  4814.5  765.42  4874.6  765.97  4894.6  764.57  4914.6  760.74
  4934.7  760.14  4954.7  755.34  4996.9  750.84  4997.4  750.04  5003.1  750.84
  5012.1  755.43  5017.3  755.04  5044.8  759.20  5068.8  760.09  5348.9  754.84
  5373.7  755.84  5379.0  754.46  5433.9  753.39  5458.6  756.06  5463.9  754.49
  5483.3  755.01  5488.7  753.78  5513.4  756.26  5518.8  755.31  5543.5  758.74
  5550.9  757.48  5598.3  762.48  5658.4  763.81  5778.4  770.48  5813.8  770.32
#Mann=3,-1,0
  4606.5    0.15       0  4996.9    0.05       0  5003.1    0.15       0
Bank Sta=4996.9,5003.1
Exp/Cntr=0.3,0.1

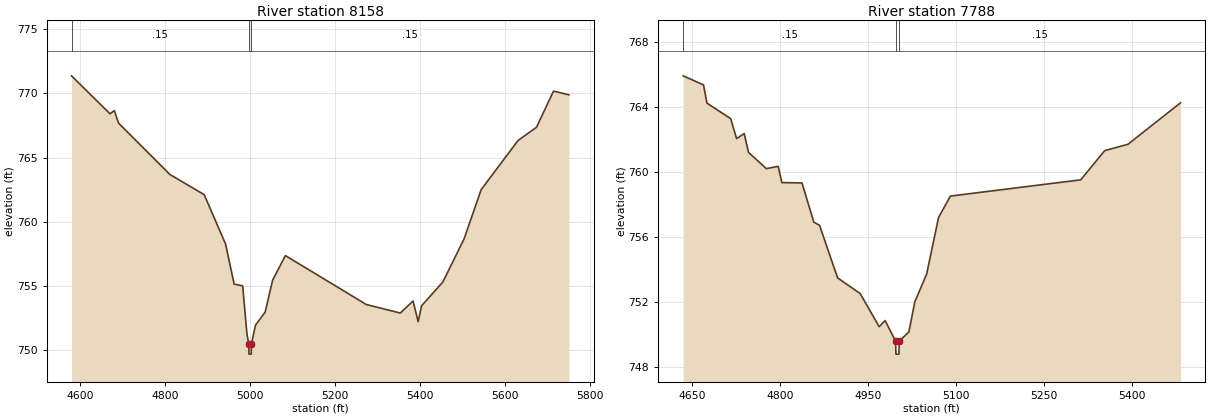
Type RM Length L Ch R = 1,8158,370,370,370
BEGIN DESCRIPTION:
UNT 095 in HW 14.0
END DESCRIPTION:
XS GIS Cut Line= 3
      2010824.97     13641925.00      2010375.00     13641975.00
      2009658.86     13641945.07
#Sta/Elev= 30
  4580.1  771.37  4670.6  768.41  4680.7  768.66  4690.7  767.68  4811.5  763.68
  4892.0  762.11  4942.3  758.26  4962.4  755.14  4982.5  755.00  4992.6  751.23
  4996.9  750.48  4997.4  749.68  5002.6  749.68  5003.1  750.48  5012.7  751.94
  5035.3  752.95  5052.9  755.44  5082.9  757.36  5273.0  753.55  5353.1  752.88
  5383.1  753.82  5395.1  752.21  5403.2  753.45  5453.2  755.30  5503.2  758.67
  5543.3  762.50  5630.0  766.33  5673.4  767.36  5713.4  770.18  5749.6  769.89
#Mann=3,-1,0
  4580.1    0.15       0  4996.9    0.05       0  5003.1    0.15       0
Bank Sta=4996.9,5003.1
Exp/Cntr=0.3,0.1

Type RM Length L Ch R = 1,7788,339,339,339
BEGIN DESCRIPTION:
UNT 095 in HW 13.0
END DESCRIPTION:
XS GIS Cut Line= 3
      2010625.04     13641725.01      2010078.82     13641643.38
      2009785.88     13641673.76
#Sta/Elev= 30
  4635.2  765.92  4669.9  765.36  4675.7  764.24  4716.1  763.28  4726.2  762.05
  4739.1  762.36  4746.5  761.20  4776.8  760.20  4797.0  760.34  4803.2  759.34
  4837.5  759.32  4857.7  756.90  4867.4  756.71  4898.1  753.47  4936.6  752.50
  4968.9  750.46  4979.0  750.84  4996.9  749.57  4997.4  748.77  5002.6  748.77
  5003.1  749.57  5019.5  750.14  5029.6  751.99  5049.8  753.71  5070.0  757.19
  5090.2  758.51  5312.0  759.51  5352.9  761.31  5392.4  761.70  5482.0  764.26
#Mann=3,-1,0
  4635.2    0.15       0  4996.9    0.05       0  5003.1    0.15       0
Bank Sta=4996.9,5003.1
Exp/Cntr=0.3,0.1