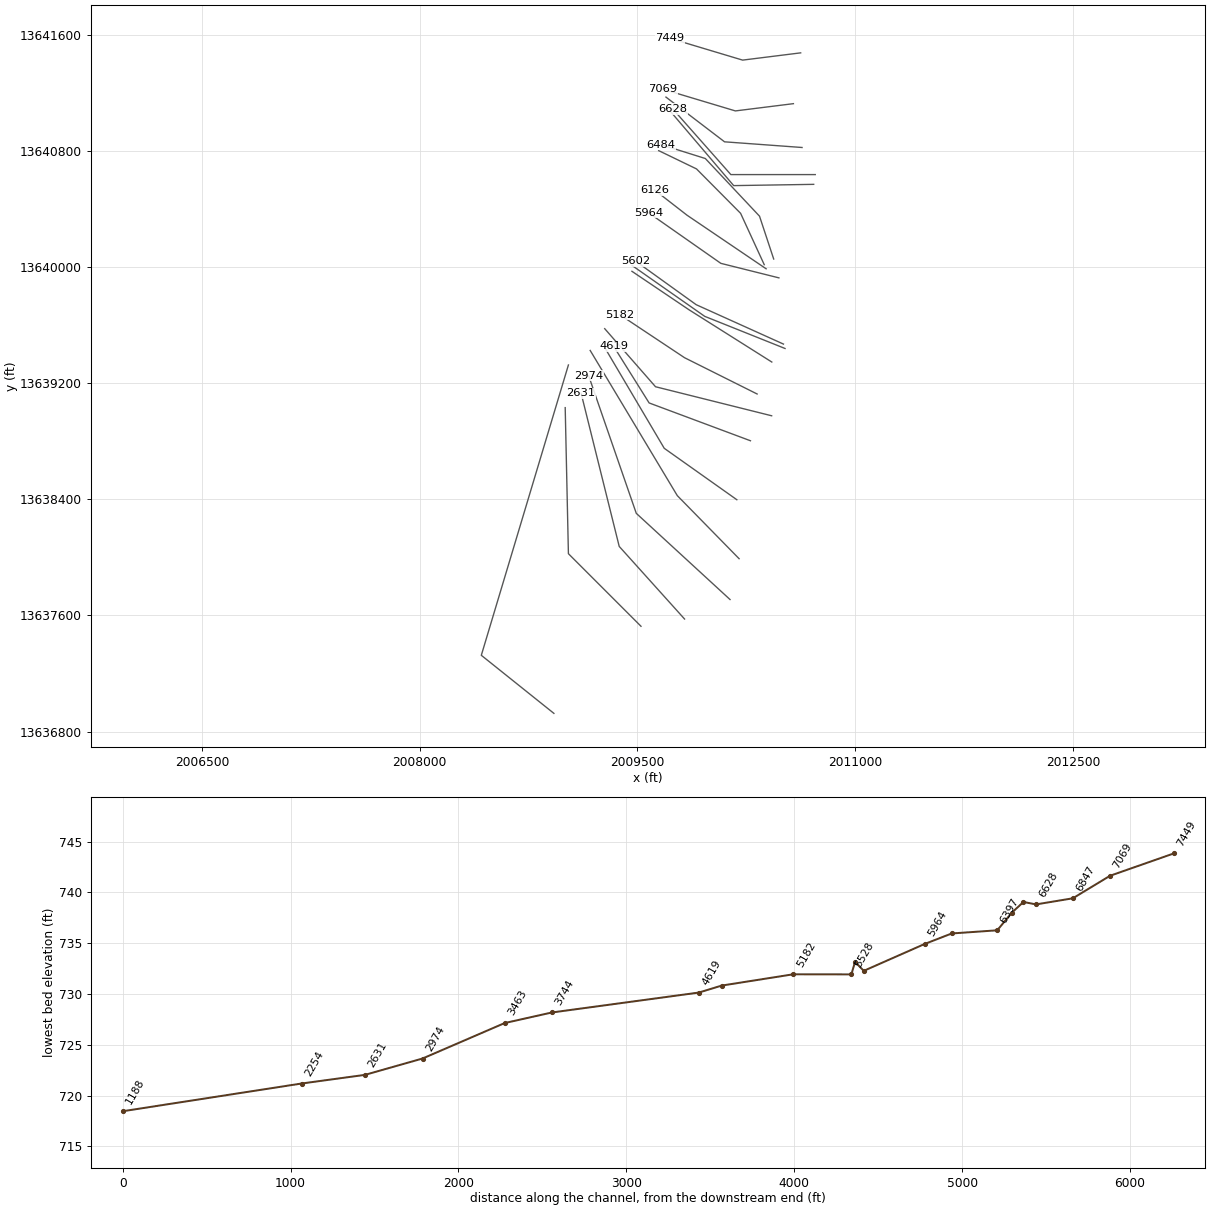
HEC-RAS study UNT 095 in HW.prj: UNT 095 in HW Base Level Engineering

--- UNT 095 in HW.g01 (geometry) --- (continued)

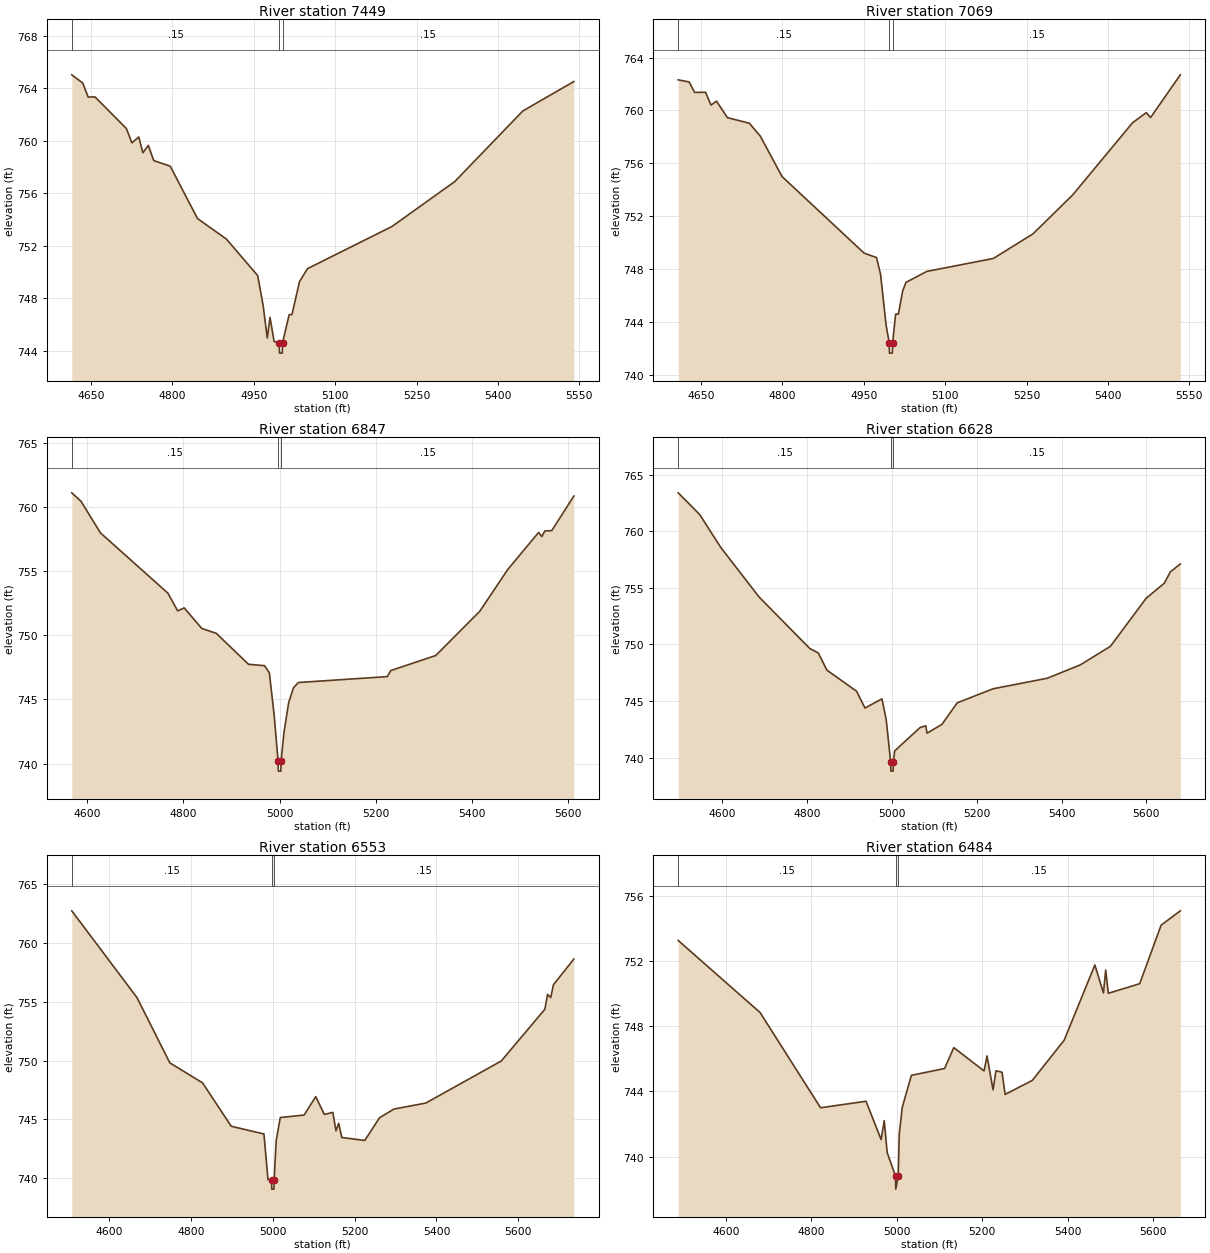
Type RM Length L Ch R = 1,7449,380,380,380
BEGIN DESCRIPTION:
UNT 095 in HW 12.0
END DESCRIPTION:
XS GIS Cut Line= 3
      2010624.96     13641474.99      2010225.00     13641425.00
      2009724.99     13641575.00
#Sta/Elev= 30
  4614.7  765.02  4634.8  764.40  4644.9  763.33  4657.5  763.34  4715.4  760.93
  4725.5  759.84  4738.1  760.29  4745.7  759.09  4755.7  759.65  4765.8  758.49
  4796.1  758.07  4846.4  754.08  4899.4  752.53  4957.3  749.74  4967.4  747.45
  4974.9  744.99  4980.0  746.56  4987.5  744.73  4996.9  744.64  4997.4  743.84
  5002.6  743.84  5003.1  744.64  5015.3  746.77  5020.4  746.77  5034.3  749.28
  5049.1  750.27  5204.8  753.48  5320.5  756.90  5445.8  762.27  5539.8  764.51
#Mann=3,-1,0
  4614.7    0.15       0  4996.9    0.05       0  5003.1    0.15       0
Bank Sta=4996.9,5003.1
Exp/Cntr=0.3,0.1

Type RM Length L Ch R = 1,7069,222,222,222
BEGIN DESCRIPTION:
UNT 095 in HW 11.0
END DESCRIPTION:
XS GIS Cut Line= 3
      2010574.96     13641125.00      2010175.00     13641075.00
      2009674.99     13641225.00
#Sta/Elev= 30
  4608.2  762.31  4628.3  762.15  4638.4  761.36  4658.6  761.37  4668.6  760.40
  4678.7  760.70  4698.9  759.45  4739.2  759.03  4759.3  758.06  4799.6  754.99
  4950.8  749.20  4973.5  748.87  4981.0  747.60  4991.1  743.79  4996.9  742.44
  4997.4  741.64  5002.7  741.64  5003.2  742.44  5008.8  744.59  5013.9  744.59
  5021.7  746.34  5027.8  746.99  5066.1  747.82  5188.8  748.80  5261.8  750.66
  5334.9  753.60  5445.4  759.07  5470.6  759.83  5478.5  759.46  5533.3  762.69
#Mann=3,-1,0
  4608.2    0.15       0  4996.9    0.05       0  5003.2    0.15       0
Bank Sta=4996.9,5003.2
Exp/Cntr=0.3,0.1

Type RM Length L Ch R = 1,6847,219,219,219
BEGIN DESCRIPTION:
Mapping XS 16a8254f
END DESCRIPTION:
XS GIS Cut Line= 3
      2010634.40     13640823.06      2010100.52     13640862.13
      2009696.90     13641170.27
#Sta/Elev= 30
  4568.3  761.09  4587.7  760.42  4627.9  757.97  4768.2  753.27  4788.3  751.90
  4801.9  752.13  4838.4  750.53  4868.5  750.15  4935.5  747.74  4968.8  747.63
  4978.8  747.07  4988.8  743.79  4996.9  740.22  4997.4  739.42  5002.7  739.42
  5003.2  740.22  5008.9  742.36  5018.9  744.75  5028.9  745.91  5039.0  746.32
  5223.8  746.78  5231.0  747.25  5324.4  748.42  5416.0  751.87  5474.1  755.12
  5538.3  758.01  5544.8  757.68  5551.1  758.12  5565.6  758.15  5611.4  760.84
#Mann=3,-1,0
  4568.3    0.15       0  4996.9    0.05       0  5003.2    0.15       0
Bank Sta=4996.9,5003.2
Exp/Cntr=0.3,0.1

Type RM Length L Ch R = 1,6628,75,75,75
BEGIN DESCRIPTION:
Mapping XS d32f9762
END DESCRIPTION:
XS GIS Cut Line= 3
      2010725.48     13640636.43      2010143.93     13640636.43
      2009744.63     13641087.81
#Sta/Elev= 30
  4495.8  763.39  4546.3  761.48  4596.3  758.56  4686.3  754.20  4806.3  749.64
  4826.3  749.25  4846.3  747.74  4916.3  745.88  4936.3  744.39  4976.3  745.20
  4986.3  743.38  4996.9  739.62  4997.4  738.82  5002.7  738.82  5003.2  739.62
  5006.3  740.60  5016.3  740.95  5066.3  742.67  5079.7  742.82  5082.7  742.17
  5117.8  742.95  5153.8  744.85  5238.3  746.09  5366.3  747.02  5444.1  748.20
  5515.2  749.84  5599.6  754.09  5642.3  755.41  5656.5  756.41  5680.0  757.11
#Mann=3,-1,0
  4495.8    0.15       0  4996.9    0.05       0  5003.2    0.15       0
Bank Sta=4996.9,5003.2
Exp/Cntr=0.3,0.1

Type RM Length L Ch R = 1,6553,69,69,69
BEGIN DESCRIPTION:
UNT 095 in HW 10.0
END DESCRIPTION:
XS GIS Cut Line= 3
      2010714.63     13640569.16      2010163.46     13640560.48
      2009725.03     13641074.97
#Sta/Elev= 30
  4508.6  762.73  4668.2  755.34  4748.3  749.80  4828.3  748.10  4898.3  744.41
  4978.3  743.75  4988.3  739.86  4996.9  739.86  4997.4  739.06  5002.7  739.06
  5003.2  739.86  5008.3  743.20  5018.3  745.15  5076.5  745.36  5105.0  746.93
  5125.9  745.41  5146.7  745.59  5154.4  744.02  5161.0  744.66  5168.7  743.45
  5224.7  743.20  5260.9  745.13  5296.1  745.87  5374.0  746.38  5558.5  749.96
  5665.0  754.36  5671.6  755.62  5679.3  755.35  5685.9  756.44  5735.8  758.63
#Mann=3,-1,0
  4508.6    0.15       0  4996.9    0.05       0  5003.2    0.15       0
Bank Sta=4996.9,5003.2
Exp/Cntr=0.3,0.1

Type RM Length L Ch R = 1,6484,87,87,87
BEGIN DESCRIPTION:
Mapping XS e8e93bb8
END DESCRIPTION:
XS GIS Cut Line= 4
      2010439.05     13640054.87      2010341.41     13640349.98
      2009968.15     13640747.11      2009664.35     13640842.59
#Sta/Elev= 30
  4488.7  753.26  4680.2  748.84  4821.6  743.00  4928.0  743.40  4963.2  741.05
  4970.5  742.21  4977.4  740.25  4996.9  738.81  4997.4  738.01  5003.2  738.81
  5005.7  741.39  5012.6  743.02  5034.0  744.99  5111.7  745.41  5133.2  746.69
  5204.0  745.26  5210.9  746.18  5225.0  744.10  5231.9  745.27  5246.0  745.18
  5253.3  743.82  5316.9  744.68  5391.3  747.14  5463.2  751.76  5483.2  750.04
  5488.5  751.45  5494.6  750.02  5568.0  750.61  5618.1  754.20  5663.0  755.08
#Mann=3,-1,0
  4488.7    0.15       0  4996.9    0.05       0  5003.2    0.15       0
Bank Sta=4996.9,5003.2
Exp/Cntr=0.3,0.1

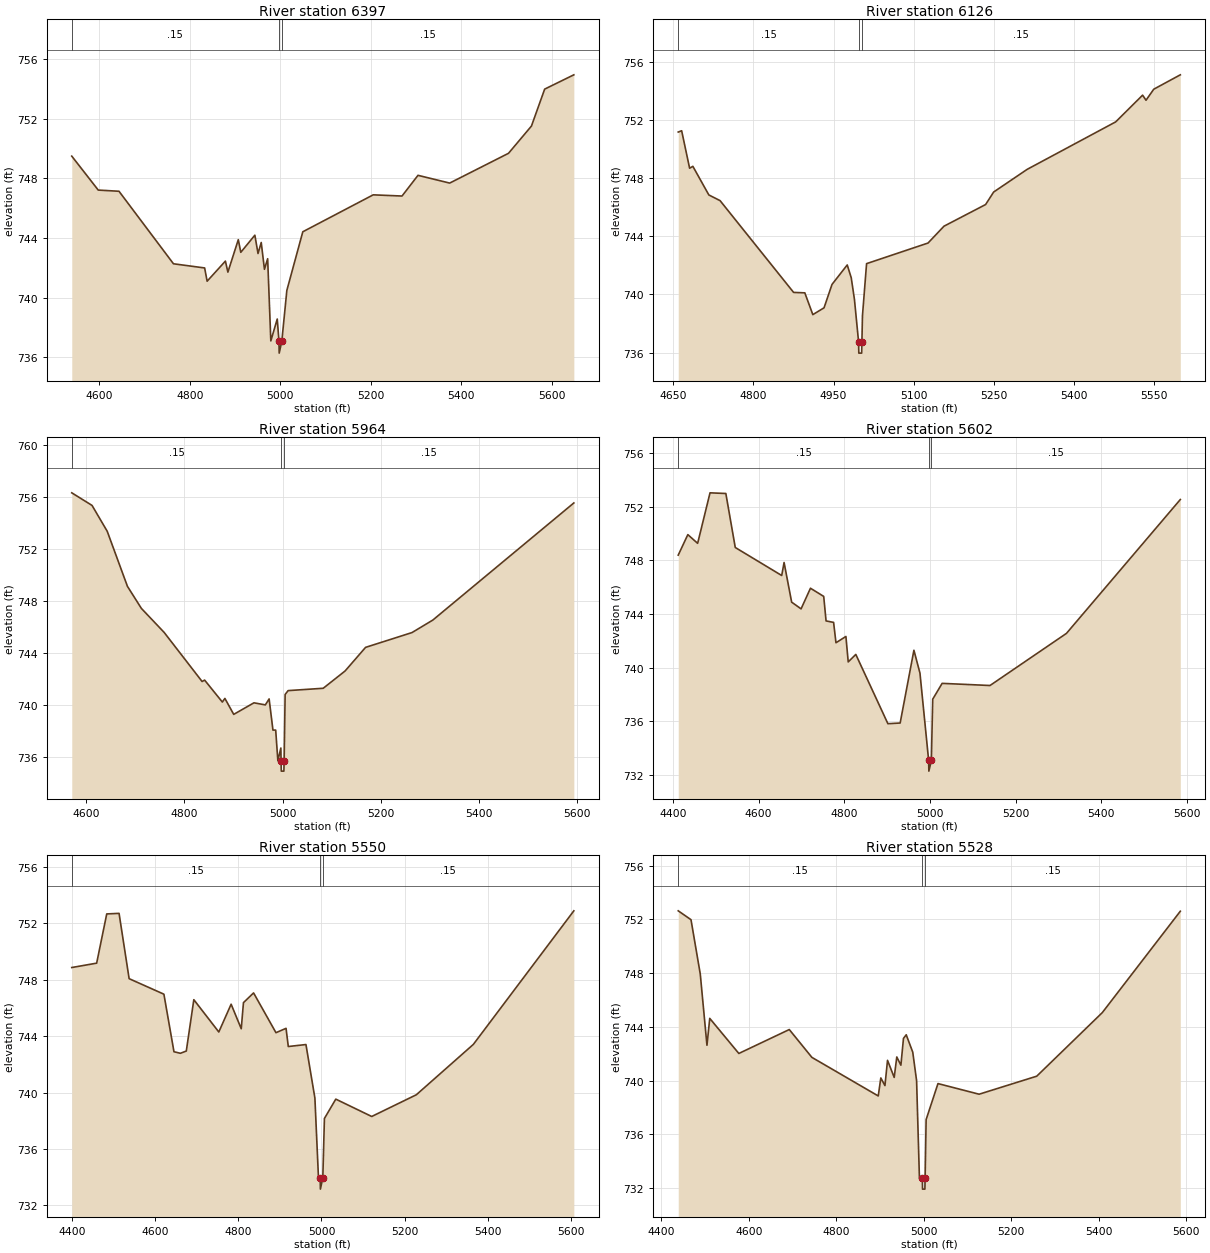
Type RM Length L Ch R = 1,6397,271,271,271
BEGIN DESCRIPTION:
UNT 095 in HW 9.0
END DESCRIPTION:
XS GIS Cut Line= 4
      2010373.94     13640015.82      2010211.20     13640369.51
      2009907.38     13640675.50      2009646.94     13640801.37
#Sta/Elev= 30
  4538.9  749.50  4597.4  747.22  4643.3  747.14  4763.7  742.27  4832.6  741.99
  4838.1  741.10  4878.5  742.45  4884.0  741.71  4907.0  743.89  4912.5  743.04
  4943.6  744.19  4950.6  742.96  4957.7  743.70  4964.8  741.90  4971.9  742.61
  4978.9  737.09  4993.1  738.56  4996.9  737.07  4997.4  736.27  5003.2  737.07
  5014.3  740.48  5049.6  744.42  5205.2  746.90  5268.9  746.82  5304.2  748.21
  5374.3  747.69  5504.3  749.69  5555.0  751.52  5584.2  754.00  5648.7  754.96
#Mann=3,-1,0
  4538.9    0.15       0  4996.9    0.05       0  5003.2    0.15       0
Bank Sta=4996.9,5003.2
Exp/Cntr=0.3,0.1

Type RM Length L Ch R = 1,6126,162,162,162
BEGIN DESCRIPTION:
Mapping XS a76d6395
END DESCRIPTION:
XS GIS Cut Line= 3
      2010386.97     13639987.57      2009842.28     13640356.49
      2009619.46     13640529.55
#Sta/Elev= 30
  4659.3  751.18  4665.7  751.27  4680.6  748.69  4686.7  748.82  4716.6  746.85
  4737.6  746.46  4875.3  740.14  4896.3  740.11  4911.3  738.61  4932.3  739.08
  4947.2  740.69  4975.7  742.03  4983.2  741.15  4989.2  739.66  4996.9  736.76
  4997.4  735.96  5002.7  735.96  5003.2  736.76  5004.2  738.52  5011.9  742.12
  5127.0  743.54  5156.9  744.70  5234.8  746.19  5249.8  747.05  5312.5  748.61
  5478.3  751.88  5528.7  753.72  5535.1  753.37  5549.6  754.13  5599.3  755.12
#Mann=3,-1,0
  4659.3    0.15       0  4996.9    0.05       0  5003.2    0.15       0
Bank Sta=4996.9,5003.2
Exp/Cntr=0.3,0.1

Type RM Length L Ch R = 1,5964,362,362,362
BEGIN DESCRIPTION:
UNT 095 in HW 8.0
END DESCRIPTION:
XS GIS Cut Line= 3
      2010475.04     13639924.99      2010075.00     13640025.00
      2009574.99     13640375.01
#Sta/Elev= 30
  4570.6  756.35  4611.9  755.38  4642.8  753.39  4684.0  749.15  4712.4  747.45
  4758.8  745.60  4836.1  741.82  4841.2  741.93  4877.3  740.24  4882.5  740.52
  4900.5  739.29  4941.7  740.18  4964.9  740.02  4972.6  740.48  4980.4  738.08
  4986.0  738.08  4990.4  735.72  4996.5  736.70  4996.9  735.72  4997.4  734.92
  5002.7  734.92  5003.2  735.72  5005.2  740.82  5011.3  741.12  5082.8  741.30
  5127.3  742.63  5169.1  744.45  5263.7  745.59  5306.0  746.55  5593.3  755.57
#Mann=3,-1,0
  4570.6    0.15       0  4996.9    0.05       0  5003.2    0.15       0
Bank Sta=4996.9,5003.2
Exp/Cntr=0.3,0.1

Type RM Length L Ch R = 1,5602,52,52,52
BEGIN DESCRIPTION:
Mapping XS a943208c
END DESCRIPTION:
XS GIS Cut Line= 3
      2010506.30     13639468.92      2009905.21     13639740.17
      2009489.26     13640039.13
#Sta/Elev= 30
  4412.5  748.40  4434.9  749.93  4457.8  749.28  4486.7  753.05  4523.6  753.00
  4545.6  748.97  4654.0  746.88  4659.5  747.85  4677.2  744.89  4699.2  744.39
  4721.1  745.93  4752.0  745.32  4757.5  743.49  4775.1  743.38  4780.6  741.86
  4803.8  742.33  4809.2  740.43  4826.9  740.99  4901.8  735.82  4930.4  735.87
  4962.5  741.30  4976.6  739.60  4996.9  733.08  4997.4  732.28  5003.2  733.08
  5006.4  737.65  5028.4  738.83  5140.1  738.67  5318.5  742.56  5584.2  752.55
#Mann=3,-1,0
  4412.5    0.15       0  4996.9    0.05       0  5003.2    0.15       0
Bank Sta=4996.9,5003.2
Exp/Cntr=0.3,0.1

Type RM Length L Ch R = 1,5550,22,22,22
BEGIN DESCRIPTION:
UNT 095 in HW 7.0
END DESCRIPTION:
XS GIS Cut Line= 3
      2010517.23     13639438.50      2009964.15     13639659.81
      2009464.18     13640009.79
#Sta/Elev= 30
  4400.2  748.87  4460.0  749.18  4484.2  752.67  4513.8  752.71  4538.0  748.08
  4621.5  746.98  4645.7  742.90  4661.1  742.79  4675.3  742.95  4693.4  746.59
  4753.4  744.30  4783.0  746.27  4807.3  744.53  4812.6  746.38  4836.9  747.07
  4890.7  744.25  4914.9  744.56  4920.3  743.27  4962.7  743.41  4984.2  739.62
  4992.8  733.96  4996.9  733.96  4997.4  733.16  5003.2  733.96  5007.1  738.17
  5034.4  739.54  5120.7  738.31  5227.9  739.85  5364.8  743.42  5606.2  752.89
#Mann=3,-1,0
  4400.2    0.15       0  4996.9    0.05       0  5003.2    0.15       0
Bank Sta=4996.9,5003.2
Exp/Cntr=0.3,0.1

Type RM Length L Ch R = 1,5528,346,346,346
BEGIN DESCRIPTION:
Mapping XS 557ac0cd
END DESCRIPTION:
XS GIS Cut Line= 3
      2010426.01     13639345.22      2009855.30     13639705.44
      2009462.65     13639970.10
#Sta/Elev= 30
  4438.5  752.63  4467.7  751.97  4488.9  747.93  4504.2  742.63  4510.6  744.63
  4577.1  742.02  4692.5  743.80  4744.2  741.73  4896.0  738.86  4901.9  740.20
  4911.3  739.63  4917.2  741.51  4932.5  740.24  4938.4  741.76  4947.8  741.15
  4953.7  743.14  4960.0  743.41  4974.9  742.12  4983.7  740.00  4990.2  732.73
  4996.8  732.73  4997.3  731.93  5002.7  731.93  5003.2  732.73  5005.5  737.10
  5032.6  739.78  5126.7  738.99  5258.5  740.33  5408.5  745.06  5586.9  752.60
#Mann=3,-1,0
  4438.5    0.15       0  4996.8    0.05       0  5003.2    0.15       0
Bank Sta=4996.8,5003.2
Exp/Cntr=0.3,0.1

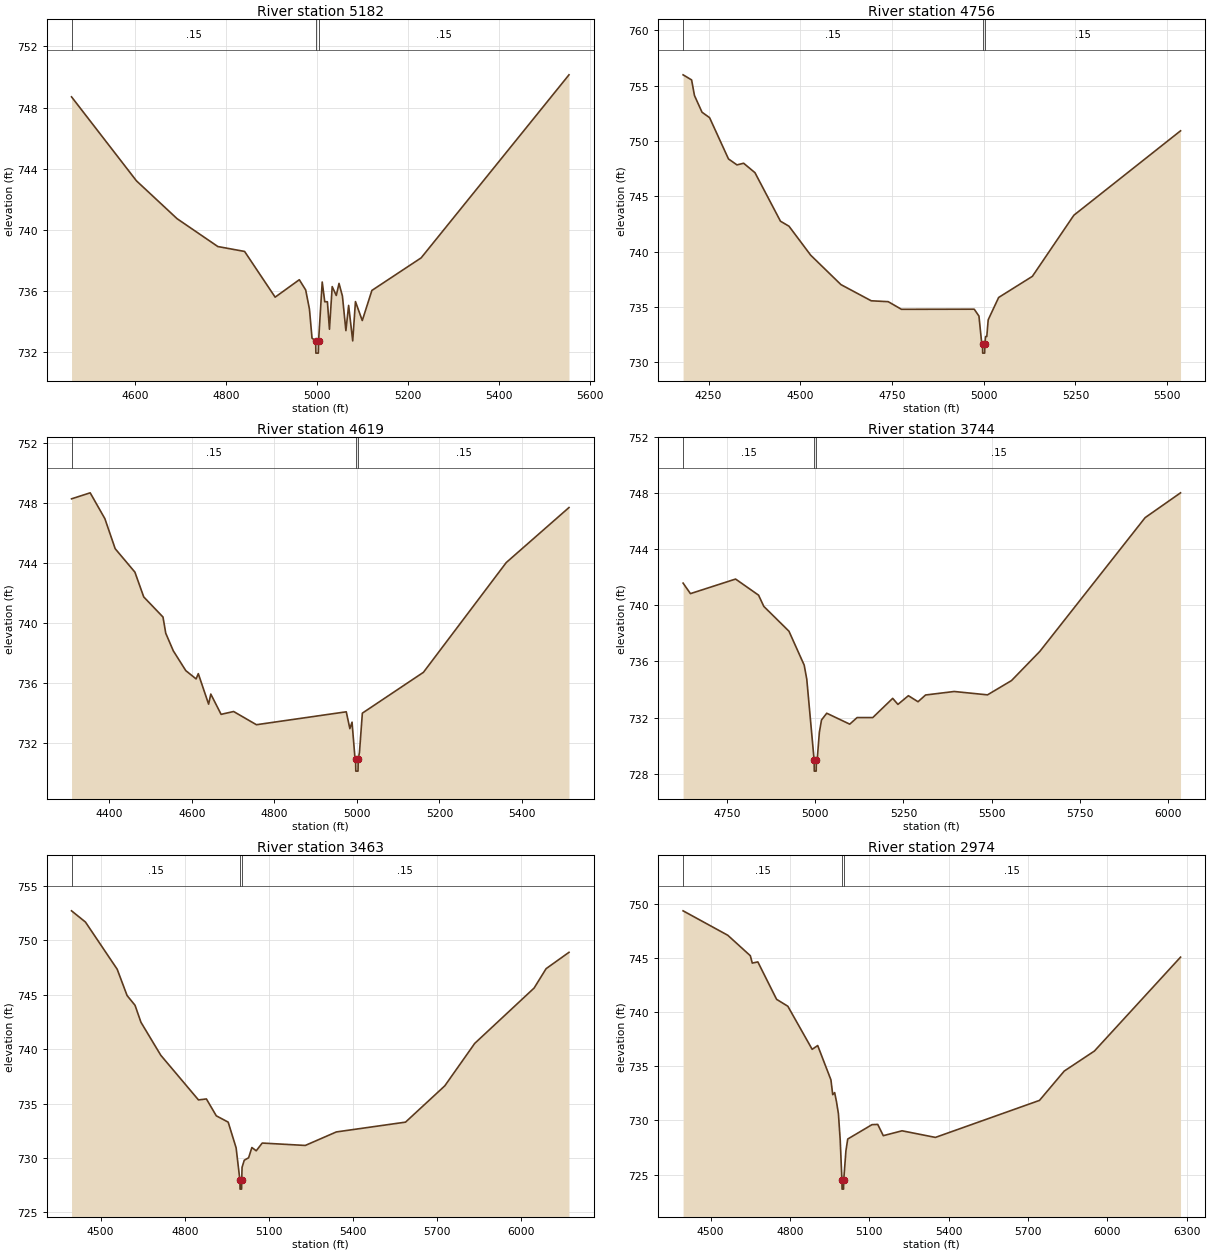
Type RM Length L Ch R = 1,5182,426,426,426
BEGIN DESCRIPTION:
UNT 095 in HW 6.0
END DESCRIPTION:
XS GIS Cut Line= 3
      2010324.96     13639125.02      2009825.00     13639375.00
      2009380.57     13639670.37
#Sta/Elev= 30
  4460.6  748.70  4603.1  743.21  4692.5  740.73  4782.0  738.91  4840.7  738.59
  4907.8  735.60  4960.9  736.74  4974.9  736.07  4983.2  734.81  4988.8  732.92
  4996.8  732.74  4997.3  731.94  5002.7  731.94  5003.2  732.74  5011.2  736.59
  5016.8  735.30  5022.6  735.30  5027.1  733.50  5033.1  736.29  5042.1  735.71
  5048.1  736.50  5055.6  735.67  5063.2  733.41  5069.2  735.06  5078.2  732.74
  5084.2  735.31  5099.2  734.07  5120.3  736.04  5228.5  738.17  5553.2  750.14
#Mann=3,-1,0
  4460.6    0.15       0  4996.8    0.05       0  5003.2    0.15       0
Bank Sta=4996.8,5003.2
Exp/Cntr=0.3,0.1

Type RM Length L Ch R = 1,4756,137,137,137
BEGIN DESCRIPTION:
UNT 095 in HW 5.0
END DESCRIPTION:
XS GIS Cut Line= 3
      2010425.04     13638974.99      2009625.00     13639175.00
      2009274.98     13639575.02
#Sta/Elev= 30
  4180.5  755.98  4203.7  755.52  4211.5  754.11  4232.1  752.60  4252.7  752.11
  4304.2  748.38  4327.4  747.84  4345.5  747.99  4376.4  747.14  4446.0  742.75
  4469.2  742.30  4528.4  739.68  4610.9  737.02  4693.4  735.56  4739.7  735.48
  4775.8  734.79  4974.2  734.80  4987.1  734.18  4994.9  731.63  4996.8  731.63
  4997.3  730.83  5002.7  730.83  5003.2  731.63  5005.2  732.33  5008.5  732.33
  5012.3  733.84  5040.8  735.86  5132.8  737.77  5245.8  743.29  5536.7  750.92
#Mann=3,-1,0
  4180.5    0.15       0  4996.8    0.05       0  5003.2    0.15       0
Bank Sta=4996.8,5003.2
Exp/Cntr=0.3,0.1

Type RM Length L Ch R = 1,4619,875,875,875
BEGIN DESCRIPTION:
Mapping XS 121bd756
END DESCRIPTION:
XS GIS Cut Line= 3
      2010278.95     13638802.94      2009580.99     13639063.37
      2009336.23     13639453.96
#Sta/Elev= 30
  4308.2  748.27  4353.4  748.67  4389.0  746.95  4414.0  744.95  4461.8  743.39
  4483.2  741.74  4529.9  740.40  4536.6  739.32  4554.9  738.15  4585.2  736.83
  4610.2  736.28  4615.5  736.63  4640.5  734.60  4645.8  735.27  4670.8  733.92
  4701.1  734.11  4756.4  733.23  4974.2  734.09  4982.9  732.97  4988.2  733.40
  4995.5  730.94  4996.8  730.94  4997.3  730.14  5002.7  730.14  5003.2  730.94
  5006.2  731.39  5013.2  734.00  5161.3  736.72  5362.1  744.03  5514.1  747.69
#Mann=3,-1,0
  4308.2    0.15       0  4996.8    0.05       0  5003.2    0.15       0
Bank Sta=4996.8,5003.2
Exp/Cntr=0.3,0.1

Type RM Length L Ch R = 1,3744,281,281,281
BEGIN DESCRIPTION:
Mapping XS 75142bce
END DESCRIPTION:
XS GIS Cut Line= 3
      2010185.17     13638396.70      2009685.16     13638750.87
      2009279.47     13639437.43
#Sta/Elev= 30
  4625.4  741.59  4646.2  740.84  4774.2  741.88  4839.4  740.73  4854.2  739.93
  4925.5  738.16  4968.7  735.74  4976.0  734.74  4996.8  728.98  4997.3  728.18
  5002.7  728.18  5003.2  728.98  5005.5  728.98  5011.7  730.95  5017.8  731.83
  5032.6  732.31  5097.8  731.53  5118.7  732.00  5163.1  732.00  5219.6  733.37
  5234.4  732.94  5264.1  733.56  5291.4  733.13  5312.8  733.61  5393.9  733.86
  5488.4  733.62  5556.5  734.64  5636.7  736.72  5935.2  746.26  6035.6  748.03
#Mann=3,-1,0
  4625.4    0.15       0  4996.8    0.05       0  5003.2    0.15       0
Bank Sta=4996.8,5003.2
Exp/Cntr=0.3,0.1

Type RM Length L Ch R = 1,3463,489,489,489
BEGIN DESCRIPTION:
UNT 095 in HW 4.0
END DESCRIPTION:
XS GIS Cut Line= 3
      2010200.75     13637990.49      2009775.00     13638425.00
      2009175.01     13639424.98
#Sta/Elev= 30
  4396.1  752.69  4445.7  751.66  4558.9  747.33  4594.3  744.91  4622.6  744.02
  4643.7  742.46  4714.5  739.43  4848.9  735.33  4877.2  735.42  4912.5  733.87
  4954.9  733.29  4983.2  730.93  4996.8  727.94  4997.3  727.14  5002.7  727.14
  5003.2  727.94  5004.4  729.14  5012.2  729.79  5027.8  730.02  5039.4  730.96
  5055.0  730.66  5076.3  731.37  5229.9  731.15  5340.7  732.39  5587.5  733.29
  5727.5  736.62  5834.4  740.52  6046.2  745.60  6089.0  747.38  6170.6  748.88
#Mann=3,-1,0
  4396.1    0.15       0  4996.8    0.05       0  5003.2    0.15       0
Bank Sta=4996.8,5003.2
Exp/Cntr=0.3,0.1

Type RM Length L Ch R = 1,2974,343,343,343
BEGIN DESCRIPTION:
Mapping XS 0ea5bc99
END DESCRIPTION:
XS GIS Cut Line= 3
      2010138.31     13637709.18      2009492.45     13638302.96
      2009164.47     13639250.47
#Sta/Elev= 30
  4396.4  749.37  4565.4  747.11  4650.5  745.22  4657.9  744.54  4678.9  744.65
  4749.8  741.19  4792.3  740.55  4884.2  736.57  4905.1  736.92  4955.1  733.75
  4961.9  732.38  4969.2  732.57  4976.0  731.74  4983.4  730.63  4990.2  728.17
  4996.7  724.45  4997.2  723.65  5002.8  723.65  5003.3  724.45  5011.8  727.20
  5018.6  728.28  5110.4  729.61  5132.0  729.63  5153.0  728.59  5223.9  729.04
  5350.0  728.43  5743.3  731.85  5836.8  734.56  5950.8  736.41  6276.4  745.09
#Mann=3,-1,0
  4396.4    0.15       0  4996.7    0.05       0  5003.3    0.15       0
Bank Sta=4996.7,5003.3
Exp/Cntr=0.3,0.1

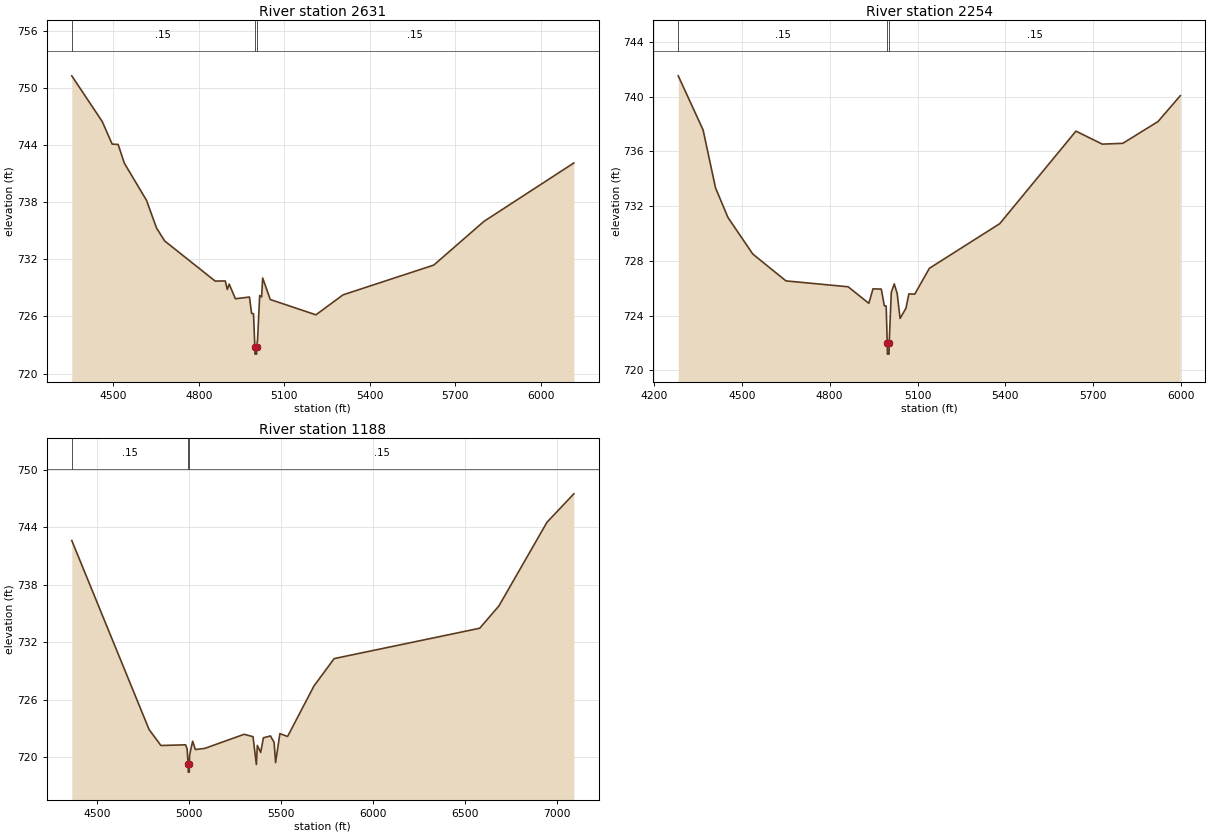
Type RM Length L Ch R = 1,2631,377,377,377
BEGIN DESCRIPTION:
UNT 095 in HW 3.0
END DESCRIPTION:
XS GIS Cut Line= 3
      2009825.03     13637574.96      2009375.00     13638075.00
      2009112.39     13639130.49
#Sta/Elev= 30
  4354.8  751.29  4461.4  746.50  4496.5  744.11  4517.4  744.08  4539.1  742.11
  4616.8  738.21  4651.9  735.30  4680.4  733.94  4857.5  729.72  4893.0  729.73
  4900.1  728.84  4906.8  729.40  4928.5  727.86  4977.8  728.04  4985.3  726.33
  4992.0  726.28  4996.7  722.84  4997.2  722.04  5002.8  722.04  5003.3  722.84
  5006.2  723.55  5013.7  728.20  5020.4  728.05  5024.2  730.04  5050.8  727.78
  5210.9  726.17  5305.8  728.27  5624.1  731.40  5800.4  736.00  6115.2  742.13
#Mann=3,-1,0
  4354.8    0.15       0  4996.7    0.05       0  5003.3    0.15       0
Bank Sta=4996.7,5003.3
Exp/Cntr=0.3,0.1

Type RM Length L Ch R = 1,2254,1066,1066,1066
BEGIN DESCRIPTION:
UNT 095 in HW 2.0
END DESCRIPTION:
XS GIS Cut Line= 3
      2009524.97     13637525.03      2009025.00     13638025.00
      2009002.89     13639031.10
#Sta/Elev= 30
  4283.4  741.52  4368.2  737.57  4410.6  733.34  4453.1  731.17  4537.9  728.50
  4651.0  726.54  4863.2  726.11  4933.9  724.90  4948.0  725.96  4976.3  725.94
  4986.9  724.71  4993.0  724.71  4996.7  721.99  4997.2  721.19  5002.8  721.19
  5003.3  721.99  5010.5  725.70  5020.5  726.32  5030.5  725.63  5040.5  723.80
  5060.5  724.54  5070.5  725.59  5090.5  725.57  5140.5  727.46  5380.6  730.72
  5640.6  737.48  5730.6  736.53  5800.7  736.59  5920.7  738.18  5996.8  740.07
#Mann=3,-1,0
  4283.4    0.15       0  4996.7    0.05       0  5003.3    0.15       0
Bank Sta=4996.7,5003.3
Exp/Cntr=0.3,0.1

Type RM Length L Ch R = 1,1188,0,0,0
BEGIN DESCRIPTION:
UNT 095 in HW 1.0
END DESCRIPTION:
XS GIS Cut Line= 3
      2008925.03     13636924.97      2008425.00     13637325.00
      2009025.00     13639324.98
#Sta/Elev= 30
  4364.1  742.64  4784.3  722.91  4848.4  721.24  4982.8  721.31  4990.8  720.90
  4996.7  719.26  4997.2  718.46  5002.9  718.46  5003.4  719.26  5004.5  720.25
  5021.0  721.69  5035.8  720.82  5087.1  720.94  5301.1  722.41  5349.0  722.16
  5367.3  719.26  5372.5  721.25  5390.7  720.52  5405.5  722.04  5443.8  722.24
  5463.8  721.56  5471.7  719.46  5495.1  722.48  5536.9  722.18  5680.5  727.46
  5790.1  730.31  6580.9  733.48  6685.3  735.81  6946.4  744.54  7092.5  747.51
#Mann=3,-1,0
  4364.1    0.15       0  4996.7    0.05       0  5003.4    0.15       0
Bank Sta=4996.7,5003.4
Exp/Cntr=0.3,0.1

Chan Stop Cuts=-1