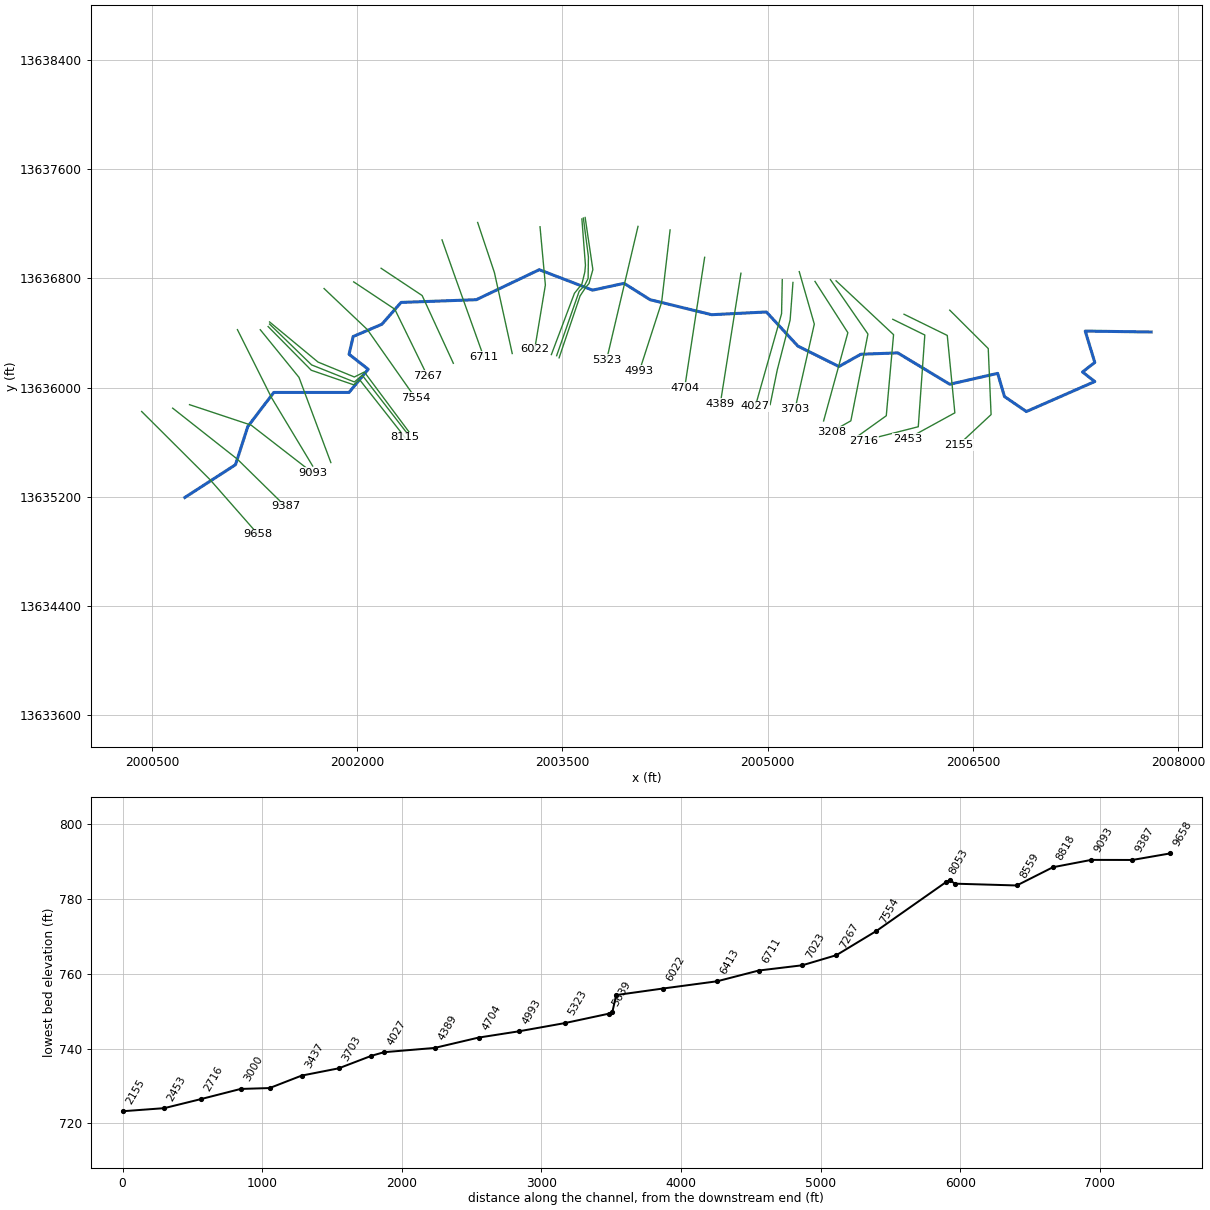
--- UNT 096 in HW.prj (project) ---

Proj Title=UNT 096 in HW Base Level Engineering
Current Plan=p01
Default Exp/Contr=0.3,0.1
English Units
Geom File=g01
Flow File=f01
Plan File=p01
BEGIN DESCRIPTION:
UNT 096 in HW
END DESCRIPTION:

--- UNT 096 in HW.p01 (plan) ---

Plan Title=Multiple Run
Short Identifier=Multiple
Geom File=g01
Flow File=f01
Subcritical Flow
K Sum by GR= 0
Std Step Tol= 0.01
Critical Tol= 0.01
Num of Std Step Trials= 20
Max Error Tol= 0.3
Flow Tol Ratio= 0.001
Split Flow NTrial= 30
Split Flow Tol= 0.02
Split Flow Ratio= 0.02
Log Output Level= 0
Friction Slope Method= 1
Unsteady Friction Slope Method= 2
Unsteady Bridges Friction Slope Method= 1
Parabolic Critical Depth
Global Vel Dist=  1 , 1 , 1
Global Log Level= 0
CheckData=True
Encroach Param= -1, 0, 0, 0
BEGIN DESCRIPTION:
Multiple Run
END DESCRIPTION:

--- UNT 096 in HW.f01 (steady flow) ---

Flow Title=Multiple
Number of Profiles=7
Profile Names=10-year,25-year,50-year,1pct_min,100-year,1pct_plu,500-year
River Rch & RM= UNT 096 in HW,Reach-1,9658
     569     803     999     616    1229    2452    1866
Boundary for River Rch & Prof#=UNT 096 in HW,Reach-1,1
Up Type=0
Dn Type=3
Dn Slope=0.005
Boundary for River Rch & Prof#=UNT 096 in HW,Reach-1,2
Up Type=0
Dn Type=3
Dn Slope=0.005
Boundary for River Rch & Prof#=UNT 096 in HW,Reach-1,3
Up Type=0
Dn Type=3
Dn Slope=0.005
Boundary for River Rch & Prof#=UNT 096 in HW,Reach-1,4
Up Type=0
Dn Type=3
Dn Slope=0.005
Boundary for River Rch & Prof#=UNT 096 in HW,Reach-1,5
Up Type=0
Dn Type=3
Dn Slope=0.005
Boundary for River Rch & Prof#=UNT 096 in HW,Reach-1,6
Up Type=0
Dn Type=3
Dn Slope=0.005
Boundary for River Rch & Prof#=UNT 096 in HW,Reach-1,7
Up Type=0
Dn Type=3
Dn Slope=0.005

--- UNT 096 in HW.g01 (geometry) ---

Geom Title=Existing Conditions
Program Version=5.05

River Reach=UNT 096 in HW   ,Reach-1
Reach XY= 30
       2000740.8     13635194.54       2001110.8     13635434.54
       2001200.8     13635714.54       2001390.8     13635964.54
       2001940.8     13635964.54       2002080.8     13636134.54
       2001940.8     13636244.54       2001970.8     13636374.54
       2002180.8     13636464.54       2002320.8     13636624.54
       2002870.8     13636644.54       2003330.8     13636864.54
       2003720.8     13636714.54       2003950.8     13636764.54
       2004140.8     13636644.54       2004590.8     13636534.54
       2004990.8     13636554.54       2005220.8     13636304.54
       2005520.8     13636154.54       2005680.8     13636244.54
       2005950.8     13636254.54       2006330.8     13636024.54
       2006680.8     13636104.54       2006730.8     13635934.54
       2006890.8     13635824.54       2007390.8     13636044.54
       2007300.8     13636114.54       2007390.8     13636184.54
       2007320.8     13636414.54      2007802.88     13636407.64

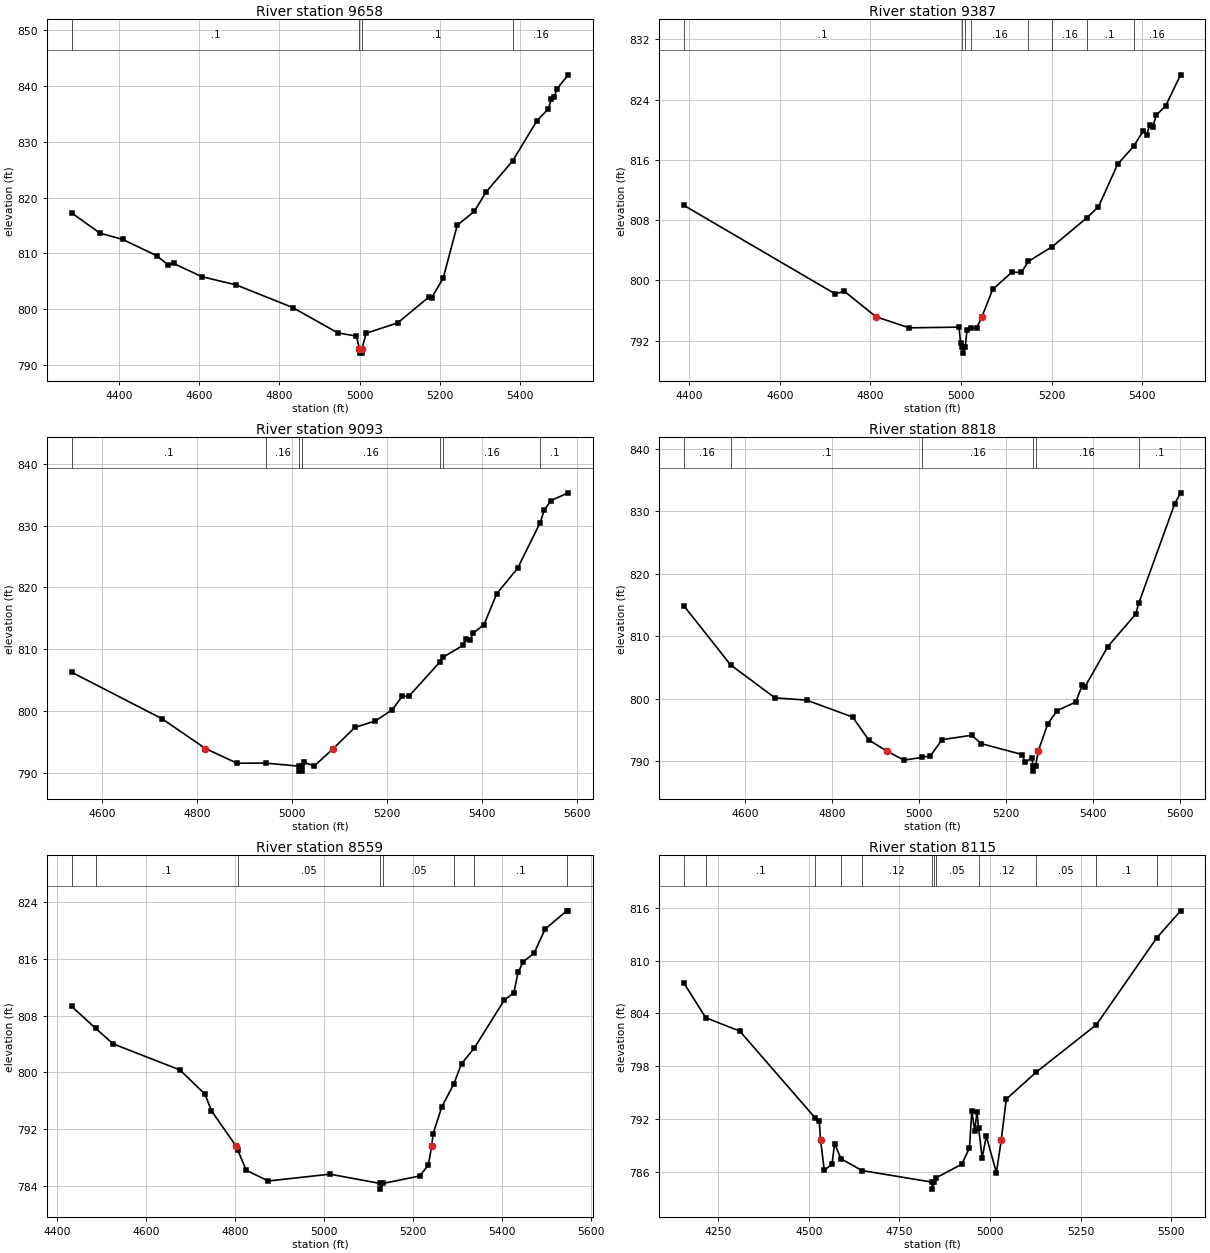
Type RM Length L Ch R = 1 ,9658    ,271,271,271
BEGIN DESCRIPTION:
UNT 096 in HW 17.0
END DESCRIPTION:
XS GIS Cut Line= 3
      2000425.02     13635824.98        2000925.       13635325.
      2001275.01     13634924.99
#Sta/Elev= 30
  4281.4  817.27  4352.1  813.62  4408.6   812.5  4493.5  809.59  4521.8  807.95
  4535.9  808.18  4606.6   805.8  4691.5  804.34  4832.9  800.27    4946   795.7
  4991.8  795.16  4999.2  792.89  4999.7  792.09  5004.7  792.09  5005.2  792.89
  5016.5  795.67  5094.8  797.52  5173.1   802.2  5179.7  802.05  5208.2  805.55
  5243.3  815.06    5286  817.52  5314.5  820.95  5381.2  826.56  5441.7  833.76
  5470.2   835.9  5477.7   837.6  5484.4  837.99    5492  839.51    5520  842.02
#Mann= 4 ,-1 , 0
  4281.4      .1       0  4999.2     .07       0  5005.2      .1       0
  5381.2     .16       0
Bank Sta=4999.2,5005.2
XS Rating Curve= 0 ,0
Exp/Cntr=0.3,0.1

Type RM Length L Ch R = 1 ,9387    ,294,294,294
BEGIN DESCRIPTION:
UNT 096 in HW 16.0
END DESCRIPTION:
XS GIS Cut Line= 3
      2000651.59     13635849.55        2001125.       13635475.
      2001475.77     13635129.52
#Sta/Elev= 30
  4388.2  809.96  4721.8  798.22  4742.6  798.54 4812.23795.1678  4885.3   793.7
  4995.4  793.79  4998.9  791.65    5003  791.14  5003.5  790.34    5009  791.14
  5013.1  793.43    5021  793.64  5034.2  793.68 5045.97795.1677  5069.6   798.8
  5112.1  801.09  5133.2  801.05  5148.1  802.51  5201.4  804.49  5276.7  808.27
    5303  809.76  5345.4  815.43  5380.4  817.78    5402  819.86  5409.1  819.27
  5416.1  820.63  5423.2  820.37  5430.3  821.91  5451.5   823.2  5484.2  827.29
#Mann= 8 ,-1 , 0
  4388.2      .1       0    5003     .07       0    5009      .1       0
    5021     .16       0  5148.1      .1       0  5201.4     .16       0
  5276.7      .1       0  5380.4     .16       0
Bank Sta=4812.23,5045.97
XS Rating Curve= 0 ,0
Exp/Cntr=0.3,0.1

Type RM Length L Ch R = 1 ,9093    ,275,275,275
BEGIN DESCRIPTION:
UNT 096 in HW 15.0
END DESCRIPTION:
XS GIS Cut Line= 3
      2000774.98     13635875.01        2001225.       13635725.
      2001674.96     13635375.03
#Sta/Elev= 30
  4536.5  806.33  4726.3  798.84  4818.2794.0039  4884.4  791.64    4945  791.65
  5015.1  791.16  5015.6  790.36  5020.6  790.36  5021.1  791.16  5024.4   791.8
  5047.1   791.2 5086.96794.0039  5132.1  797.41  5175.6  798.47  5210.8  800.28
  5231.7  802.42  5246.1  802.47  5311.8  808.04    5317  808.72  5360.2  810.69
  5366.5   811.7  5374.6  811.55    5381  812.64  5403.6  813.98  5430.7  819.03
  5474.2  823.07    5522  830.49  5530.3  832.48  5544.8  834.04  5580.9  835.28
#Mann= 7 ,-1 , 0
  4536.5      .1       0    4945     .16       0  5015.1     .07       0
  5021.1     .16       0  5311.8      .1       0    5317     .16       0
    5522      .1       0
Bank Sta=4818.2,5086.96
XS Rating Curve= 0 ,0
Exp/Cntr=0.3,0.1

Type RM Length L Ch R = 1 ,8818    ,259,259,259
BEGIN DESCRIPTION:
UNT 096 in HW 14.0
END DESCRIPTION:
XS GIS Cut Line= 3
      2001125.01     13636424.98        2001375.       13635925.
      2001675.01     13635424.99
#Sta/Elev= 30
  4458.7  814.86  4566.4  805.39  4668.3  800.12    4741  799.76  4847.2  797.04
  4883.5  793.41 4924.82791.6378  4964.6  790.16  5006.9   790.6  5025.5  790.85
  5052.7  793.44  5120.7  794.14  5142.1  792.81  5237.3  791.04  5243.2  789.79
  5258.7  790.53  5261.5   789.2    5262   788.4  5267.5   789.2 5273.66 791.637
  5295.6  795.98    5317  798.09  5359.8  799.45  5375.3  802.24  5381.2  801.92
  5433.6  808.34  5497.8  813.54  5504.5  815.24  5587.2  831.17  5600.8  832.93
#Mann= 6 ,-1 , 0
  4458.7     .16       0  4566.4      .1       0  5006.9     .16       0
  5261.5     .07       0  5267.5     .16       0  5504.5      .1       0
Bank Sta=4924.82,5273.66
XS Rating Curve= 0 ,0
Exp/Cntr=0.3,0.1

Type RM Length L Ch R = 1 ,8559    ,444,444,444
BEGIN DESCRIPTION:
UNT 096 in HW 13.0
END DESCRIPTION:
XS GIS Cut Line= 3
      2001292.16     13636424.25        2001575.       13636075.
       2001807.8     13635450.28
#Sta/Elev= 30
  4432.7  809.34  4487.3  806.21  4526.4  804.03  4676.2  800.36  4732.7  796.93
    4747   794.6  4802.2789.6285  4805.7  789.12  4825.4  786.19  4874.9  784.68
  5013.2  785.64  5126.2  784.33  5126.7  783.53  5132.2  784.33  5214.9  785.38
  5234.3  786.92 5242.01789.6264  5245.2  791.36  5264.8  795.16  5291.9  798.41
    5309  801.24  5337.5  803.43    5405  810.22  5426.4  811.23  5436.1  814.14
  5447.7  815.65  5471.8  816.81  5496.8  820.24  5545.3  822.82  5548.8  822.82
#Mann= 8 ,-1 , 0
  4432.7     .16       0  4487.3      .1       0  4805.7     .05       0
  5126.2    .033       0  5132.2     .05       0  5291.9     .07       0
  5337.5      .1       0  5545.3     .16       0
Bank Sta=4802.2,5242.01
XS Rating Curve= 0 ,0
Exp/Cntr=0.3,0.1

Type RM Length L Ch R = 1 ,8115    ,35,35,35
BEGIN DESCRIPTION:
Mapping XS 99887a78
END DESCRIPTION:
XS GIS Cut Line= 5
      2001349.48     13636447.65      2001664.58     13636127.35
      2001974.47     13636020.58      2002018.74     13636057.04
      2002349.48     13635635.16
#Sta/Elev= 30
  4155.2  807.45  4215.8  803.49  4309.5  801.98  4518.3  792.07  4528.7  791.81
 4532.37789.6131  4542.8  786.14  4564.1  786.85  4571.1  789.19    4589  787.45
  4647.1  786.12  4839.5  784.81    4840  784.01  4845.5  784.81  4849.7  785.26
  4922.3  786.85  4943.3  788.71  4949.7  792.91  4957.6  790.66  4964.1  792.78
  4968.3  791.01  4978.4  787.55  4989.6  790.03  5017.6  785.89 5031.06789.6157
  5044.8  794.24  5127.2   797.3  5293.4   802.7  5459.5  812.55  5525.7  815.65
#Mann= 12 ,-1 , 0
  4155.2     .16       0  4215.8      .1       0  4518.3     .12       0
    4589     .05       0  4647.1     .12       0  4839.5     .07       0
  4845.5     .12       0  4849.7     .05       0  4968.3     .12       0
  5127.2     .05       0  5293.4      .1       0  5459.5     .16       0
Bank Sta=4532.37,5031.06
XS Rating Curve= 0 ,0
Exp/Cntr=0.3,0.1

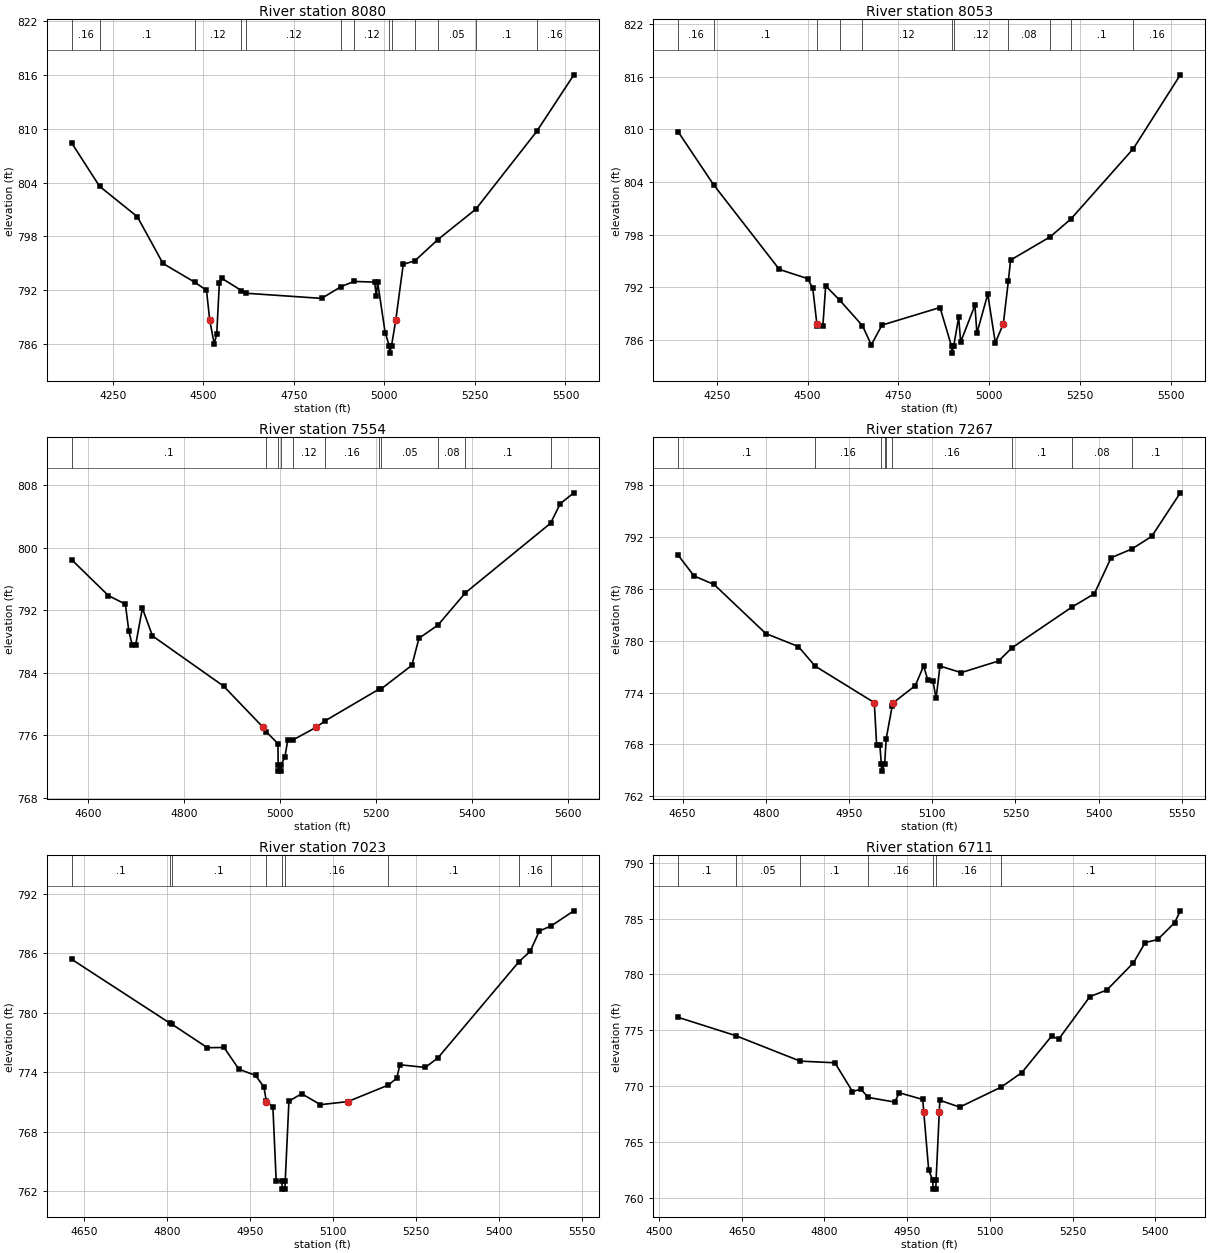
Type RM Length L Ch R = 1 ,8080    ,27,27,27
BEGIN DESCRIPTION:
Mapping XS 10647ca1
END DESCRIPTION:
XS GIS Cut Line= 5
      2001359.88     13636465.91      2001667.18     13636166.42
      2001979.68     13636041.42      2002036.97      13636090.9
       2002369.6     13635659.52
#Sta/Elev= 30
  4137.1  808.39  4213.8  803.58  4318.1  800.19  4388.9  794.98  4476.3   792.9
    4509  791.99 4518.09788.6379  4530.3  786.03  4537.3   787.1  4544.5  792.75
  4551.5  793.32  4605.5  791.96  4619.2  791.66  4826.8  791.09  4881.1  792.41
  4916.6  792.98  4973.2   792.9  4977.8  791.33  4981.5   792.9  5002.3  787.26
  5013.8  785.79  5014.3  784.99  5019.8  785.79 5031.46788.6366  5052.2  794.88
  5084.7  795.29    5148  797.65  5252.6  801.03  5420.6  809.69  5523.2     816
#Mann= 13 ,-1 , 0
  4137.1     .16       0  4213.8      .1       0  4476.3     .12       0
  4605.5     .07       0  4619.2     .12       0  4881.1     .05       0
  4916.6     .12       0  5013.8     .07       0  5019.8     .12       0
  5084.7     .08       0    5148     .05       0  5252.6      .1       0
  5420.6     .16       0
Bank Sta=4518.09,5031.46
XS Rating Curve= 0 ,0
Exp/Cntr=0.3,0.1

Type RM Length L Ch R = 1 ,8053    ,499,499,499
BEGIN DESCRIPTION:
UNT 096 in HW 12.0
END DESCRIPTION:
XS GIS Cut Line= 5
       2001359.9     13636481.51      2001714.06     13636187.25
      2001979.68     13636077.88       2002052.6     13636114.33
      2002382.95     13635669.53
#Sta/Elev= 30
  4143.6  809.72  4240.9  803.69  4422.2  794.01  4500.3  792.96  4514.3  791.86
 4525.48787.8107  4526.3  787.53    4542   787.5  4549.8  792.13  4588.7  790.49
  4651.2  787.58  4675.5   785.4  4704.9  787.65  4864.8  789.66  4896.5  785.25
    4897  784.45  4902.5  785.25  4916.2  788.53  4921.8  785.73    4961  789.91
  4966.5  786.73  4996.4  791.18  5017.2  785.63 5039.35787.8134  5053.1  792.67
  5059.2  795.08  5168.2  797.73  5225.4  799.77  5397.7  807.82  5526.9  816.24
#Mann= 11 ,-1 , 0
  4143.6     .16       0  4240.9      .1       0  4526.3     .12       0
  4588.7     .07       0  4651.2     .12       0  4896.5     .07       0
  4902.5     .12       0  5053.1     .08       0  5168.2     .05       0
  5225.4      .1       0  5397.7     .16       0
Bank Sta=4525.48,5039.35
XS Rating Curve= 0 ,0
Exp/Cntr=0.3,0.1

Type RM Length L Ch R = 1 ,7554    ,287,287,287
BEGIN DESCRIPTION:
UNT 096 in HW 11.0
END DESCRIPTION:
XS GIS Cut Line= 3
      2001758.31     13636726.33        2002075.       13636425.
      2002425.02     13635924.98
#Sta/Elev= 30
  4565.5  798.44    4642  793.86  4677.3  792.77  4684.5  789.34  4691.4  787.59
  4698.7  787.51  4712.8  792.25  4733.9   788.7  4882.3  782.27 4965.03776.9771
  4971.5  776.42  4995.6   774.9  4996.2  772.19  4996.7  771.39  5001.7  771.39
  5002.2  772.19  5010.1  773.19  5016.2  775.38  5027.7  775.41  5074.7776.9774
  5093.8  777.82  5207.3  781.91  5211.5  781.94  5275.1  784.94  5289.9   788.4
  5329.2  790.07  5386.9  794.23  5564.5  803.13  5584.6  805.63    5613  807.02
#Mann= 11 ,-1 , 0
  4565.5      .1       0  4971.5     .16       0  4996.2     .07       0
  5002.2     .16       0  5027.7     .12       0  5093.8     .16       0
  5207.3      .1       0  5211.5     .05       0  5329.2     .08       0
  5386.9      .1       0  5564.5     .16       0
Bank Sta=4965.03,5074.7
XS Rating Curve= 0 ,0
Exp/Cntr=0.3,0.1

Type RM Length L Ch R = 1 ,7267    ,244,244,244
BEGIN DESCRIPTION:
UNT 096 in HW 10.0
END DESCRIPTION:
XS GIS Cut Line= 3
      2001974.97     13636775.02        2002275.       13636575.
      2002513.56     13636085.65
#Sta/Elev= 30
  4642.1  789.86  4670.7  787.47  4706.7  786.49  4799.9  780.82  4858.5  779.32
    4889  777.05 4995.52772.8376  4999.7  767.97  5005.5  767.97  5008.2  765.72
  5008.7  764.92  5014.2  765.72  5016.9  768.65  5027.9  772.49 5030.09772.8411
  5069.4   774.8  5084.4  777.07  5091.7   775.5  5101.3  775.29  5106.9  773.33
  5113.9  777.07    5152   776.3  5219.6  777.65  5243.8  779.18  5351.8  783.88
  5392.1  785.42  5422.4  789.58  5459.7  790.59  5495.6  792.05  5547.1  797.08
#Mann= 9 ,-1 , 0
  4642.1      .1       0    4889     .16       0  5008.2     .07       0
  5014.2     .16       0  5016.9     .12       0  5027.9     .16       0
  5243.8      .1       0  5351.8     .08       0  5459.7      .1       0
Bank Sta=4995.52,5030.09
XS Rating Curve= 0 ,0
Exp/Cntr=0.3,0.1

Type RM Length L Ch R = 1 ,7023    ,312,312,312
BEGIN DESCRIPTION:
UNT 096 in HW 9.0
END DESCRIPTION:
XS GIS Cut Line= 3
      2002174.97     13636875.02        2002475.       13636675.
      2002702.92     13636178.39
#Sta/Elev= 30
  4627.9  785.37  4805.8  778.92  4808.2  778.86  4872.8  776.47  4902.9  776.49
  4929.9   774.3  4959.9  773.68    4975  772.51  4979.4  771.08 4979.53771.0378
  4991.2  770.53  4997.2  763.04  5007.5  763.02    5008  762.22    5013  762.22
  5013.5  763.02  5020.2  771.08  5043.2  771.83  5077.2  770.73  5126.5771.0375
  5199.6   772.7  5215.1   773.4  5220.6  774.75  5266.6  774.48  5289.6  775.46
  5435.7  785.13    5456  786.17  5472.6  788.23  5493.6  788.73  5534.9  790.26
#Mann= 9 ,-1 , 0
  4627.9      .1       0  4805.8     .16       0  4808.2      .1       0
  4979.4     .16       0  5007.5     .07       0  5013.5     .16       0
  5199.6      .1       0  5435.7     .16       0  5493.6     .08       0
Bank Sta=4979.53,5126.5
XS Rating Curve= 0 ,0
Exp/Cntr=0.3,0.1

Type RM Length L Ch R = 1 ,6711    ,298,298,298
BEGIN DESCRIPTION:
UNT 096 in HW 8.0
END DESCRIPTION:
XS GIS Cut Line= 3
      2002620.32     13637083.04      2002706.24     13636838.29
      2002924.99     13636225.03
#Sta/Elev= 30
  4534.9  776.17  4638.8  774.54    4756  772.26    4819  772.11  4850.9  769.54
  4865.9  769.75  4879.8  769.01  4927.5   768.6  4935.8  769.43  4978.3  768.83
 4980.09767.7463  4989.1  762.52  4996.5  761.62    4997  760.82    5002  760.82
  5002.5  761.62 5008.33767.7418  5009.3  768.76  5045.4  768.15  5120.7  769.94
  5158.1  771.24  5211.9  774.49    5225  774.23  5281.3  778.02  5312.1  778.61
  5360.5  781.05  5381.7  782.85  5404.5  783.13  5435.3  784.64  5445.4  785.69
#Mann= 7 ,-1 , 0
  4534.9      .1       0  4638.8     .05       0    4756      .1       0
  4879.8     .16       0  4996.5     .07       0  5002.5     .16       0
  5120.7      .1       0
Bank Sta=4980.09,5008.33
XS Rating Curve= 0 ,0
Exp/Cntr=0.3,0.1

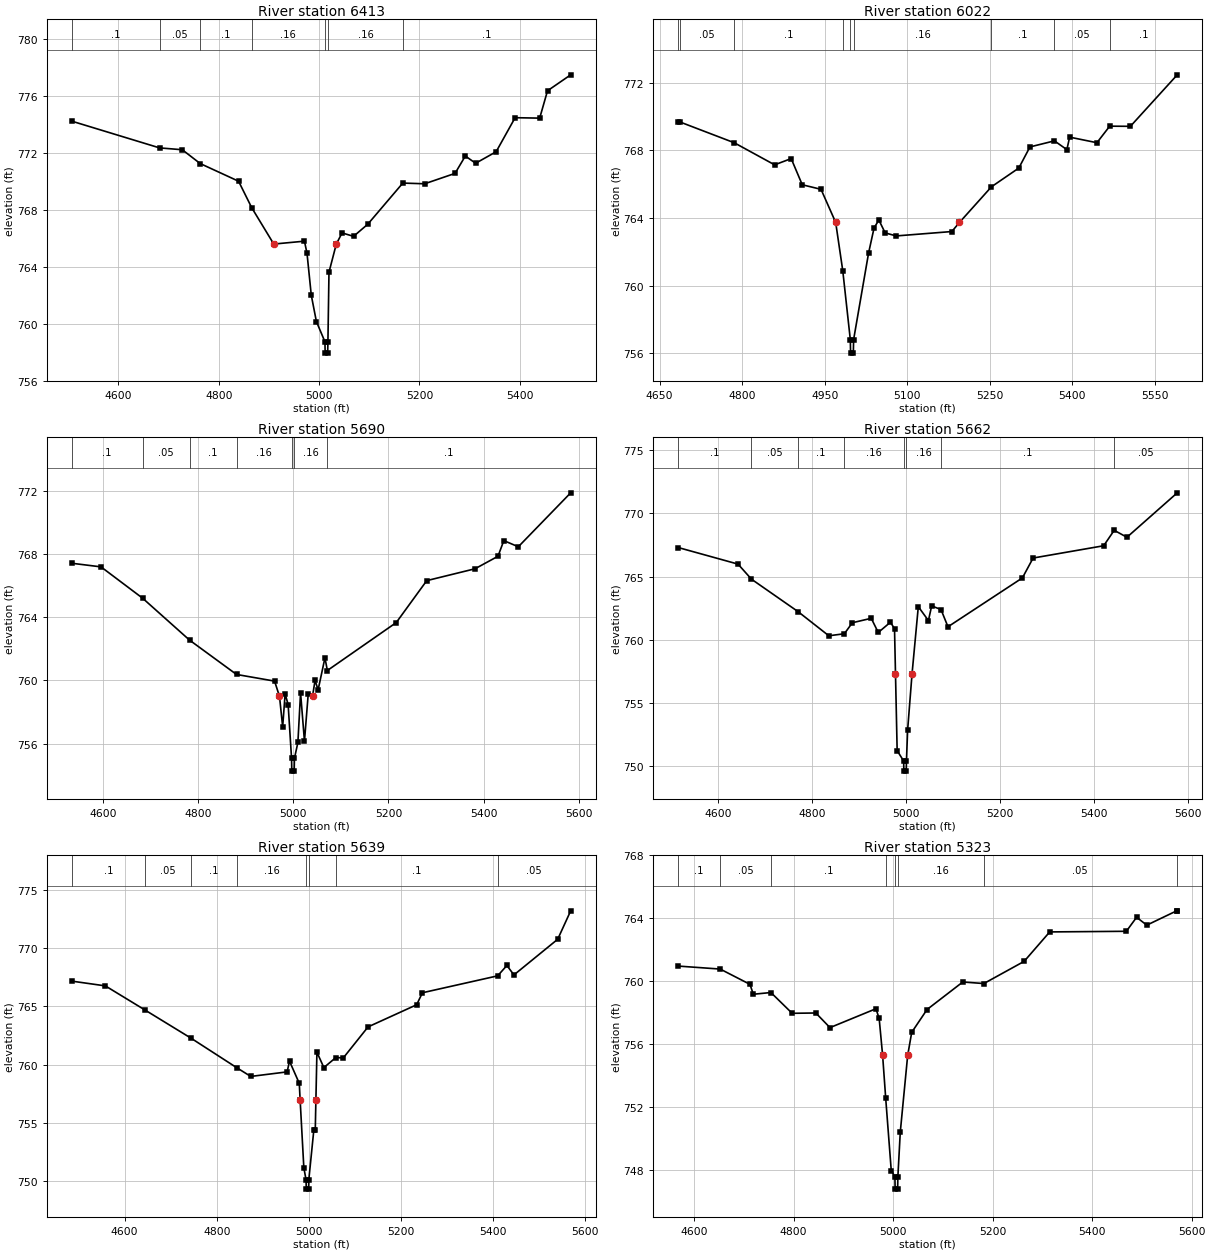
Type RM Length L Ch R = 1 ,6413    ,391,391,391
BEGIN DESCRIPTION:
UNT 096 in HW 7.0
END DESCRIPTION:
XS GIS Cut Line= 3
      2002880.72      13637210.7      2003003.12      13636843.5
       2003133.3     13636249.87
#Sta/Elev= 30
  4506.6  774.24  4681.9  772.36  4727.2  772.23  4762.9  771.26  4839.4  770.02
  4865.6  768.16 4909.54 765.608  4970.7  765.81  4975.8  764.96  4984.3  762.02
  4994.5  760.17  5011.5  758.75    5012  757.95    5017  757.95  5017.5  758.75
  5019.6  763.63 5034.19 765.608  5045.7  766.39  5068.6  766.15  5096.9     767
  5166.8  769.89  5210.3  769.84  5270.9  770.57  5291.4  771.79  5311.9  771.28
  5352.8  772.09  5390.6  774.48  5439.6  774.45  5455.2  776.37  5501.4  777.49
#Mann= 7 ,-1 , 0
  4506.6      .1       0  4681.9     .05       0  4762.9      .1       0
  4865.6     .16       0  5011.5     .07       0  5017.5     .16       0
  5166.8      .1       0
Bank Sta=4909.54,5034.19
XS Rating Curve= 0 ,0
Exp/Cntr=0.3,0.1

Type RM Length L Ch R = 1 ,6022    ,332,332,332
BEGIN DESCRIPTION:
UNT 096 in HW 6.0
END DESCRIPTION:
XS GIS Cut Line= 3
      2003336.45     13637179.42      2003375.51     13636752.35
       2003297.4     13636281.04
#Sta/Elev= 30
  4683.8  769.69  4686.8  769.69  4785.5  768.46    4859  767.15  4889.1  767.52
  4909.2  765.97  4943.3   765.7 4969.93763.7392  4982.8  760.88  4996.5   756.8
    4997     756    5002     756  5002.5   756.8  5029.7  761.93  5039.7  763.42
  5048.4  763.88  5059.8  763.12  5079.9  762.94  5180.9   763.2 5194.78763.7385
  5252.9  765.85  5302.6  766.96  5322.8  768.21  5367.3  768.57  5389.9  768.05
  5394.9  768.79  5444.5  768.46  5467.7  769.44  5505.3  769.43  5590.4  772.48
#Mann= 9 ,-1 , 0
  4683.8      .1       0  4686.8     .05       0  4785.5      .1       0
  4982.8     .16       0  4996.5     .07       0  5002.5     .16       0
  5252.9      .1       0  5367.3     .05       0  5467.7      .1       0
Bank Sta=4969.93,5194.78
XS Rating Curve= 0 ,0
Exp/Cntr=0.3,0.1

Type RM Length L Ch R = 1 ,5690    ,28,28,28
BEGIN DESCRIPTION:
Mapping XS d7d6f641
END DESCRIPTION:
XS GIS Cut Line= 6
      2003642.35     13637236.53      2003668.39     13636897.99
      2003664.05     13636848.08      2003642.35      13636759.1
       2003588.1     13636691.83      2003419.41     13636241.99
#Sta/Elev= 30
  4534.6  767.41  4596.3  767.18  4683.7   765.2  4782.3  762.55  4880.9  760.38
  4960.8  759.96 4971.17758.9935  4977.8  757.07    4983  759.15  4989.3  758.48
  4996.5  755.07    4997  754.27    5002  754.27  5002.5  755.07  5009.8  756.08
  5015.4  759.23  5023.6  756.16  5031.5  759.15  5040.5758.9937  5045.8     760
  5052.3  759.41  5066.6  761.43  5071.7  760.63  5216.4  763.66  5280.4  766.31
  5381.8  767.06    5430  767.85  5442.3  768.84  5472.7  768.45  5582.7  771.86
#Mann= 7 ,-1 , 0
  4534.6      .1       0  4683.7     .05       0  4782.3      .1       0
  4880.9     .16       0  4996.5     .07       0  5002.5     .16       0
  5071.7      .1       0
Bank Sta=4971.17,5040.5
XS Rating Curve= 0 ,0
Exp/Cntr=0.3,0.1

Type RM Length L Ch R = 1 ,5662    ,23,23,23
BEGIN DESCRIPTION:
Mapping XS 5b1e911d
END DESCRIPTION:
XS GIS Cut Line= 6
       2003653.2     13637243.07      2003690.09     13636958.76
      2003687.92     13636800.34      2003661.88     13636748.25
      2003622.82     13636707.02      2003457.89     13636233.93
#Sta/Elev= 30
    4515  767.29  4642.3  765.98  4670.9  764.79  4769.9  762.23  4835.5  760.32
  4868.5  760.48  4885.5  761.35  4925.7   761.7  4940.6  760.58  4966.5  761.39
  4975.2  760.88 4977.28757.3036  4980.8  751.25  4994.6  750.43  4995.1  749.63
  5000.1  749.63  5000.6  750.43  5003.1  752.89 5012.45757.3038  5025.8  762.62
  5047.3  761.52  5054.2  762.68  5074.1  762.39  5088.9  761.03  5247.2  764.89
    5270  766.46  5420.1  767.43  5442.5  768.65  5469.6   768.1  5576.6  771.61
#Mann= 8 ,-1 , 0
    4515      .1       0  4670.9     .05       0  4769.9      .1       0
  4868.5     .16       0  4994.6     .07       0  5000.6     .16       0
  5074.1      .1       0  5442.5     .05       0
Bank Sta=4977.28,5012.45
XS Rating Curve= 0 ,0
Exp/Cntr=0.3,0.1

Type RM Length L Ch R = 1 ,5639    ,316,316,316
BEGIN DESCRIPTION:
Mapping XS 70a8ad30
END DESCRIPTION:
XS GIS Cut Line= 6
      2003666.22     13637247.38      2003722.65     13636865.44
      2003694.43     13636763.44      2003670.56     13636735.23
      2003629.33      13636672.3      2003475.82     13636218.25
#Sta/Elev= 30
    4485  767.16  4558.2  766.75  4645.1  764.66  4744.3  762.26  4843.4  759.73
  4873.9  758.98  4952.8  759.37    4958  760.29  4979.2  758.39 4981.04 756.983
  4989.1  751.15  4993.9  750.11  4994.4  749.31  4999.4  749.31  4999.9  750.11
  5010.7  754.35  5013.9  754.35 5015.31756.9783  5017.5  761.06  5032.6  759.74
  5058.6   760.6  5074.8  760.57  5128.5  763.23    5234  765.13  5246.5  766.16
  5409.8  767.61  5429.9   768.5  5445.2  767.69  5540.2  770.75  5568.4  773.19
#Mann= 8 ,-1 , 0
    4485      .1       0  4645.1     .05       0  4744.3      .1       0
  4843.4     .16       0  4993.9     .07       0  4999.9     .16       0
  5058.6      .1       0  5409.8     .05       0
Bank Sta=4981.04,5015.31
XS Rating Curve= 0 ,0
Exp/Cntr=0.3,0.1

Type RM Length L Ch R = 1 ,5323    ,330,330,330
BEGIN DESCRIPTION:
Mapping XS f51613bc
END DESCRIPTION:
XS GIS Cut Line= 2
      2004052.59     13637182.01      2003823.42     13636205.44
#Sta/Elev= 30
    4568  760.96  4652.5  760.77  4712.3   759.8    4719  759.17  4754.4  759.28
  4797.1  757.96  4844.7  757.98  4873.1  757.05  4965.5  758.25    4972  757.63
 4978.94755.2805  4985.1  752.57  4996.3  747.96  5003.6  747.59  5004.1  746.79
  5009.1  746.79  5009.6  747.59  5014.4  750.41 5029.26755.2816  5037.4  756.75
  5068.2   758.2  5140.1  759.95  5182.4  759.85  5263.4  761.26  5314.8  763.13
  5468.8  763.17  5489.4  764.06  5509.9  763.56    5570  764.47  5571.1  764.47
#Mann= 8 ,-1 , 0
    4568      .1       0  4652.5     .05       0  4754.4      .1       0
  4985.1     .16       0  5003.6     .07       0  5009.6     .16       0
  5182.4     .05       0    5570      .1       0
Bank Sta=4978.94,5029.26
XS Rating Curve= 0 ,0
Exp/Cntr=0.3,0.1

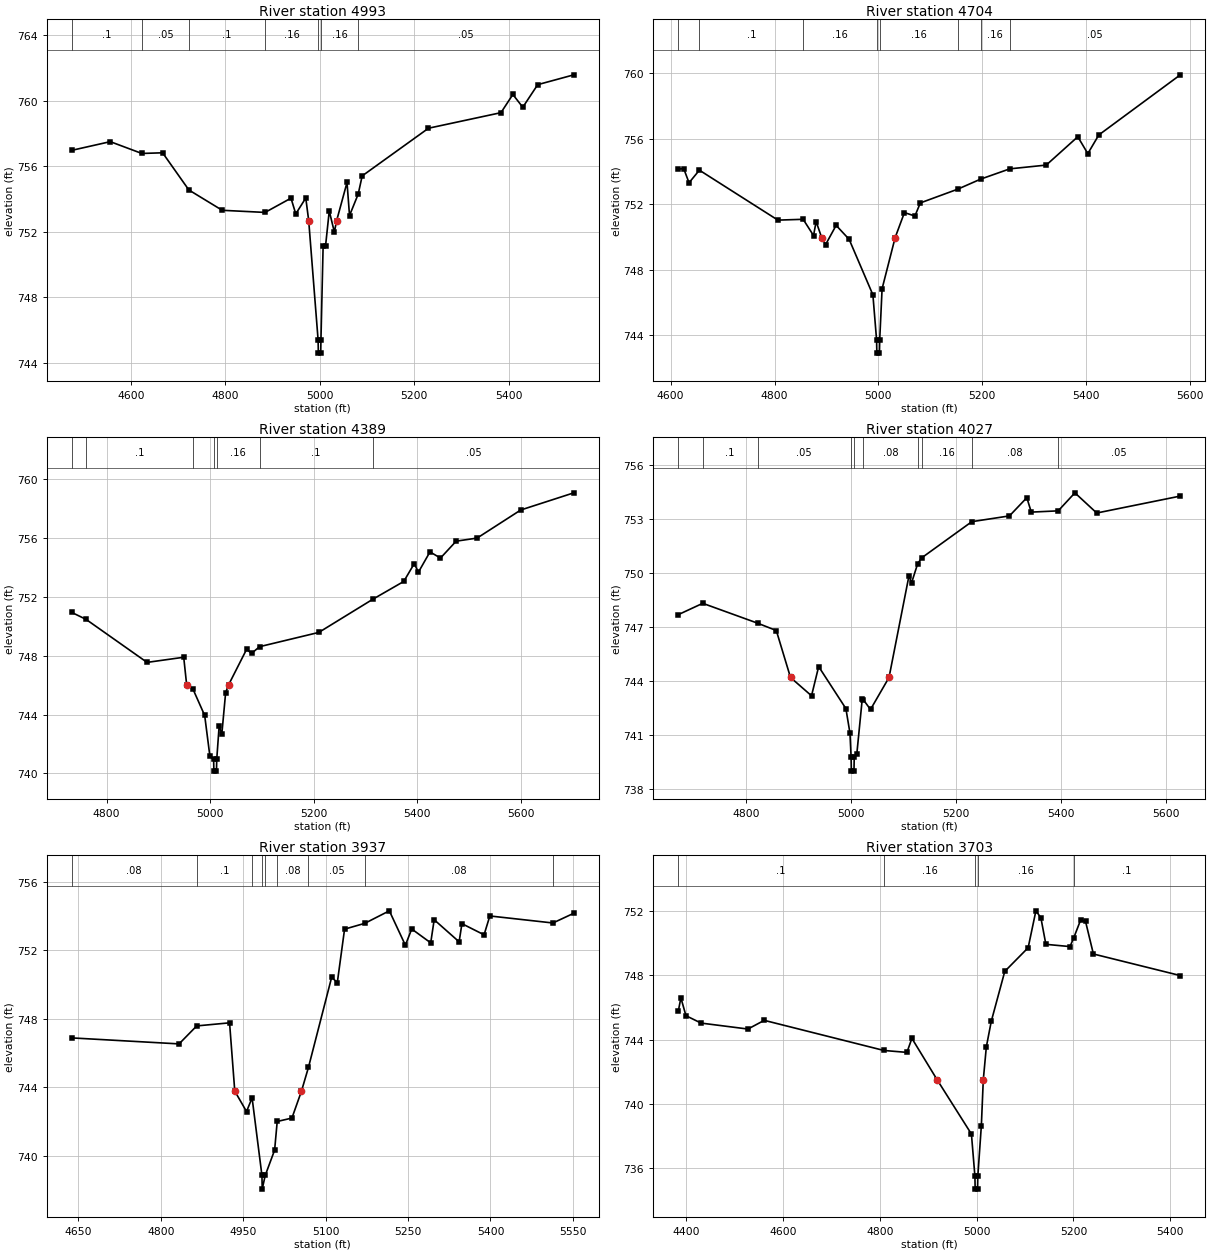
Type RM Length L Ch R = 1 ,4993    ,289,289,289
BEGIN DESCRIPTION:
UNT 096 in HW 4.0
END DESCRIPTION:
XS GIS Cut Line= 3
      2004286.97       13637156.        2004225.       13636625.
      2004063.02     13636122.15
#Sta/Elev= 30
    4475  756.97  4556.5   757.5  4623.3  756.78  4667.3  756.82  4722.9  754.55
  4793.5  753.31  4884.2  753.18  4939.1  754.05  4949.2  753.09  4970.4  754.06
 4976.58752.6797  4996.5  745.39    4997  744.59    5002  744.59  5002.5  745.39
  5007.1  751.12  5012.2  751.12  5020.1  753.27  5030.9  751.98 5035.76752.6804
  5057.7  755.01    5063  752.99  5081.4   754.3  5089.8  755.41  5230.2  758.32
  5383.6  759.27  5408.8  760.38  5429.8   759.6  5461.4  760.98  5537.9  761.58
#Mann= 7 ,-1 , 0
    4475      .1       0  4623.3     .05       0  4722.9      .1       0
  4884.2     .16       0  4996.5     .07       0  5002.5     .16       0
  5081.4     .05       0
Bank Sta=4976.58,5035.76
XS Rating Curve= 0 ,0
Exp/Cntr=0.3,0.1

Type RM Length L Ch R = 1 ,4704    ,315,315,315
BEGIN DESCRIPTION:
Mapping XS aeb2cf96
END DESCRIPTION:
XS GIS Cut Line= 2
      2004539.58     13636955.53      2004393.76     13635999.89
#Sta/Elev= 30
  4614.6  754.15  4625.2  754.17  4635.4  753.31  4655.3  754.08  4806.5  751.03
  4855.1  751.08  4875.1  750.09  4880.1  750.94 4890.79749.9619  4898.4  749.54
  4918.6  750.71  4943.6  749.86  4989.4  746.47  4996.5  743.71    4997  742.91
    5002  742.91  5002.5  743.71  5007.1  746.84 5032.24749.9628  5050.1  751.49
  5070.3  751.28  5080.7  752.08  5152.8  752.92  5196.6  753.53  5252.9  754.16
  5323.2  754.39  5383.9  756.12  5403.2  755.09  5424.4  756.23  5581.3   759.9
#Mann= 8 ,-1 , 0
  4614.6     .05       0  4655.3      .1       0  4855.1     .16       0
  4996.5     .07       0  5002.5     .16       0  5152.8     .05       0
  5196.6     .16       0  5252.9     .05       0
Bank Sta=4890.79,5032.24
XS Rating Curve= 0 ,0
Exp/Cntr=0.3,0.1

Type RM Length L Ch R = 1 ,4389    ,362,362,362
BEGIN DESCRIPTION:
Mapping XS 5841ba34
END DESCRIPTION:
XS GIS Cut Line= 2
      2004804.76     13636838.68      2004653.73     13635880.41
#Sta/Elev= 30
  4732.6  750.95  4760.1  750.48  4878.1  747.55  4948.9   747.9 4954.58746.0255
  4966.3  745.77  4989.4  743.94  4999.5  741.16  5006.7  740.95  5007.2  740.15
  5012.2  740.15  5012.7  740.95  5017.4  743.24  5022.5  742.66  5029.9  745.49
 5035.66746.0261  5070.4  748.44  5079.9  748.16  5095.5  748.62  5209.9  749.59
  5314.4  751.85  5374.1  753.06  5394.3  754.27  5402.4  753.69  5424.7  755.07
    5445  754.65  5475.3   755.8  5515.8  756.01    5600  757.92  5702.7  759.09
#Mann= 7 ,-1 , 0
  4732.6     .05       0  4760.1      .1       0  4966.3     .16       0
  5006.7     .07       0  5012.7     .16       0  5095.5      .1       0
  5314.4     .05       0
Bank Sta=4954.58,5035.66
XS Rating Curve= 0 ,0
Exp/Cntr=0.3,0.1

Type RM Length L Ch R = 1 ,4027    ,90,90,90
BEGIN DESCRIPTION:
Mapping XS 30b5ead4
END DESCRIPTION:
XS GIS Cut Line= 4
      2005106.85     13636791.85      2005101.64     13636541.85
      2005044.35     13636338.73      2004909.54     13635861.71
#Sta/Elev= 30
  4670.4  747.69  4717.1  748.32  4821.5  747.22  4857.3  746.81 4884.34744.2068
  4924.4  743.19    4938  744.81  4989.9  742.48  4997.6  741.13  4999.8  739.81
  5000.3  739.01  5005.3  739.01  5005.8  739.81  5010.7  739.96  5021.1  743.02
  5023.4  742.96  5036.8  742.43  5072.1744.2075    5110  749.83  5115.2  749.47
  5126.6  750.51  5134.2  750.84  5229.9  752.85  5301.6  753.17  5334.7  754.18
  5343.2  753.38  5394.5  753.45  5426.3  754.45  5467.9  753.33  5627.2  754.27
#Mann= 10 ,-1 , 0
  4670.4     .05       0  4717.1      .1       0  4821.5     .05       0
  4999.8     .04       0  5005.8     .05       0  5023.4     .08       0
  5126.6     .05       0  5134.2     .16       0  5229.9     .08       0
  5394.5     .05       0
Bank Sta=4884.34,5072.1
XS Rating Curve= 0 ,0
Exp/Cntr=0.3,0.1

Type RM Length L Ch R = 1 ,3937    ,234,234,234
BEGIN DESCRIPTION:
Mapping XS 2037168a
END DESCRIPTION:
XS GIS Cut Line= 4
      2005184.98     13636771.05      2005164.14     13636494.98
      2005070.39     13636130.39       2005018.3     13635875.16
#Sta/Elev= 30
  4637.9  746.88  4833.2  746.53  4865.3  747.58  4925.1  747.76 4934.57743.7725
    4956  742.58  4966.1  743.38    4984  738.85  4984.5  738.05    4990  738.85
  5007.1  740.33  5011.8     742  5038.6   742.2 5055.97743.7726  5068.7  745.16
  5110.9  750.42  5121.2  750.11  5134.4  753.23  5171.2  753.57  5215.9   754.3
  5245.1  752.29  5256.6  753.24  5291.2  752.43  5297.5  753.78  5342.9  752.49
    5348  753.55  5388.3   752.9  5398.8     754  5513.6  753.59  5551.7  754.16
#Mann= 9 ,-1 , 0
  4637.9     .08       0  4865.3      .1       0  4966.1     .16       0
    4984     .07       0    4990     .16       0  5011.8     .08       0
  5068.7     .05       0  5171.2     .08       0  5513.6     .05       0
Bank Sta=4934.57,5055.97
XS Rating Curve= 0 ,0
Exp/Cntr=0.3,0.1

Type RM Length L Ch R = 1 ,3703    ,266,266,266
BEGIN DESCRIPTION:
Mapping XS d1c7a867
END DESCRIPTION:
XS GIS Cut Line= 3
      2005230.89     13636850.26      2005341.02     13636465.77
      2005200.61     13635843.97
#Sta/Elev= 30
  4383.5  745.74    4389  746.59  4399.4  745.48  4430.6  745.02  4527.5  744.65
  4561.2  745.19  4808.4  743.32    4856   743.2  4866.3  744.07 4918.53741.4965
  4989.3  738.13  4996.5  735.51    4997  734.71    5002  734.71  5002.5  735.51
  5009.8  738.65  5013.8 741.496  5020.1  743.54  5030.3  745.13  5058.2  748.23
  5106.5   749.7  5122.5  751.99  5132.8  751.56  5143.1  749.91  5192.9  749.77
  5200.8  750.32  5214.8  751.41  5225.1  751.33  5241.3  749.31  5420.9  747.97
#Mann= 5 ,-1 , 0
  4383.5      .1       0  4808.4     .16       0  4996.5     .07       0
  5002.5     .16       0  5200.8      .1       0
Bank Sta=4918.53,5013.8
XS Rating Curve= 0 ,0
Exp/Cntr=0.3,0.1

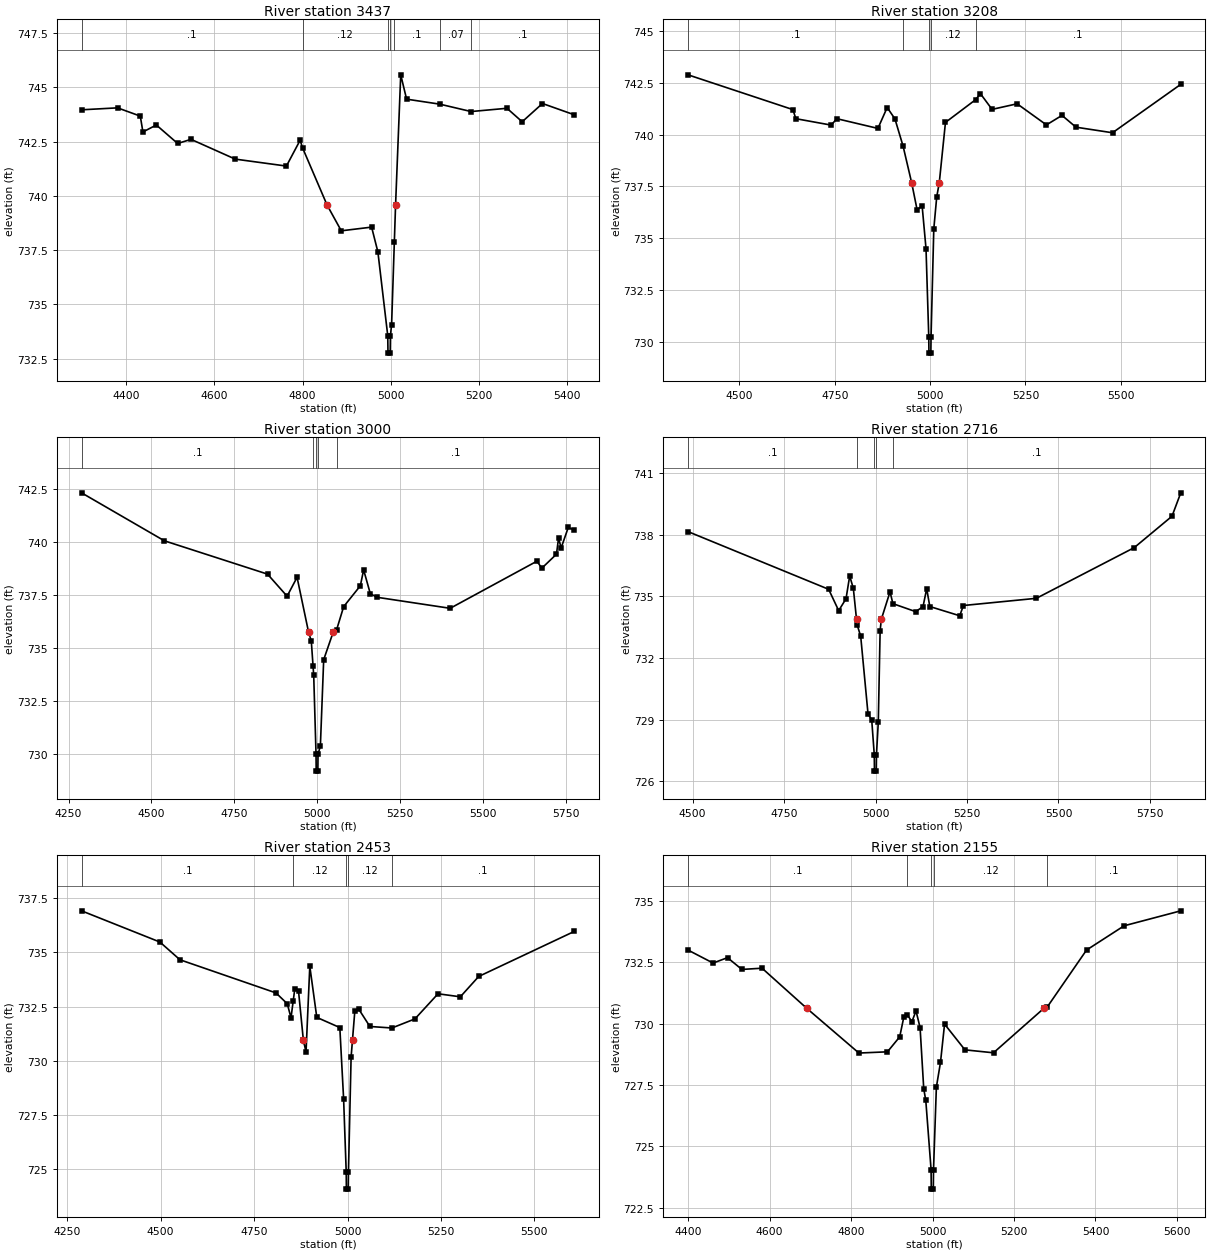
Type RM Length L Ch R = 1 ,3437    ,229,229,229
BEGIN DESCRIPTION:
Mapping XS a3b84456
END DESCRIPTION:
XS GIS Cut Line= 3
      2005345.93     13636778.61      2005586.24     13636402.76
      2005408.94     13635755.41
#Sta/Elev= 30
  4298.6  743.96  4380.2  744.05  4431.8  743.67  4437.7  742.94  4468.2  743.26
  4516.5  742.41  4546.8   742.6  4647.1  741.69  4763.1  741.37  4794.2  742.56
  4799.7  742.21 4855.32739.5757  4887.5  738.39  4956.3  738.56  4970.5  737.42
  4992.9  733.56  4993.4  732.76  4998.4  732.76  4998.9  733.56  5001.6  734.07
  5007.8  737.86  5010.6739.5734  5022.3  745.57  5035.6  744.45  5110.9  744.22
  5181.8  743.88  5263.2  744.03  5297.7  743.41  5343.7  744.25  5415.9  743.73
#Mann= 7 ,-1 , 0
  4298.6      .1       0  4799.7     .12       0  4992.9     .07       0
  4998.9     .12       0  5007.8      .1       0  5110.9     .07       0
  5181.8      .1       0
Bank Sta=4855.32,5010.6
XS Rating Curve= 0 ,0
Exp/Cntr=0.3,0.1

Type RM Length L Ch R = 1 ,3208    ,208,208,208
BEGIN DESCRIPTION:
Mapping XS b005f2aa
END DESCRIPTION:
XS GIS Cut Line= 4
      2005458.78     13636791.62       2005732.9     13636392.64
      2005608.08     13635756.45      2005468.59     13635677.65
#Sta/Elev= 30
    4365  742.89    4640  741.21  4647.9  740.77  4740.5  740.46  4755.4  740.77
  4863.1   740.3  4887.4  741.31  4907.8  740.76  4929.2  739.44 4951.63737.6753
  4965.9  736.37  4979.1  736.56  4989.3  734.49  4996.5  730.24    4997  729.44
    5002  729.44  5002.5  730.24  5009.7  735.44  5017.4  736.99 5024.09737.6757
  5040.3  740.59  5119.5  741.69    5132  741.98  5162.6  741.22  5228.3  741.49
  5305.2  740.47    5346  740.93  5382.6  740.36  5478.5  740.09  5657.6  742.43
#Mann= 5 ,-1 , 0
    4365      .1       0  4929.2     .12       0  4996.5     .07       0
  5002.5     .12       0  5119.5      .1       0
Bank Sta=4951.63,5024.09
XS Rating Curve= 0 ,0
Exp/Cntr=0.3,0.1

Type RM Length L Ch R = 1 ,3000    ,284,284,284
BEGIN DESCRIPTION:
Mapping XS 8a52cf8c
END DESCRIPTION:
XS GIS Cut Line= 4
      2005499.98     13636782.98       2005920.2     13636388.27
      2005866.88     13635793.57      2005612.84      13635611.1
#Sta/Elev= 30
  4289.2  742.31    4539  740.05  4850.2  738.48  4909.2  737.44  4939.3  738.33
 4974.18735.7327  4982.2  735.33  4987.6  734.13  4989.5  733.71  4996.5     730
    4997   729.2    5002   729.2  5002.5     730  5009.6  730.38  5019.6  734.45
 5047.95735.7327  5058.4  735.85  5079.9  736.95  5130.1  737.93  5140.1  738.68
  5160.2  737.56  5180.3  737.39  5401.1  736.87  5662.9  739.09  5677.6  738.76
  5721.8  739.42    5728  740.17    5736  739.72  5757.4  740.68  5775.6  740.55
#Mann= 5 ,-1 , 0
  4289.2      .1       0  4987.6     .12       0  4996.5     .07       0
  5002.5     .12       0  5058.4      .1       0
Bank Sta=4974.18,5047.95
XS Rating Curve= 0 ,0
Exp/Cntr=0.3,0.1

Type RM Length L Ch R = 1 ,2716    ,263,263,263
BEGIN DESCRIPTION:
Mapping XS a406377b
END DESCRIPTION:
XS GIS Cut Line= 4
      2005914.53     13636500.83      2006148.58     13636385.55
      2006100.83     13635713.12      2005701.79     13635611.09
#Sta/Elev= 30
  4487.5  738.16  4871.9  735.35  4899.3  734.31  4919.4  734.89  4929.4     736
  4939.4  735.39 4948.05733.8913  4949.6  733.63  4959.5  733.06  4979.5  729.28
  4989.6  728.99  4996.6  727.29  4997.1  726.49  5002.1  726.49  5002.6  727.29
  5007.6  728.89  5012.6  733.33 5015.93733.8914  5039.7  735.23  5047.5  734.65
  5109.9  734.26  5129.9  734.51  5139.9  735.38  5148.4  734.51  5230.2  734.06
  5240.2  734.56  5439.6  734.91  5707.2  737.38  5810.4  738.91  5834.4  740.05
#Mann= 5 ,-1 , 0
  4487.5      .1       0  4949.6     .12       0  4996.6     .07       0
  5002.6     .12       0  5047.5      .1       0
Bank Sta=4948.05,5015.93
XS Rating Curve= 0 ,0
Exp/Cntr=0.3,0.1

Type RM Length L Ch R = 1 ,2453    ,298,298,298
BEGIN DESCRIPTION:
Mapping XS 347576cb
END DESCRIPTION:
XS GIS Cut Line= 4
      2005996.98     13636537.73      2006312.72     13636382.51
      2006368.05     13635815.09      2006020.83     13635624.13
#Sta/Elev= 30
  4288.5  736.92    4498  735.48  4551.8  734.66  4808.6  733.13  4838.8  732.63
  4848.8  731.98  4854.7  732.76  4858.9  733.31  4868.9  733.22 4881.76730.9648
    4889   730.4  4899.1  734.36  4917.8     732  4979.4  731.53  4989.5  728.25
  4996.5  724.87    4997  724.07    5002  724.07  5002.5  724.87  5009.6  730.17
 5013.32 730.966  5019.6  732.31  5029.7  732.39  5059.8  731.58  5118.7  731.51
  5180.4  731.93  5242.1  733.09  5301.8  732.95    5351  733.89  5606.7  735.97
#Mann= 5 ,-1 , 0
  4288.5      .1       0  4854.7     .12       0  4996.5     .07       0
  5002.5     .12       0  5118.7      .1       0
Bank Sta=4881.76,5013.32
XS Rating Curve= 0 ,0
Exp/Cntr=0.3,0.1

Type RM Length L Ch R = 1 ,2155    ,508,508,508
BEGIN DESCRIPTION:
Mapping XS 5e40ba42
END DESCRIPTION:
XS GIS Cut Line= 4
      2006330.84     13636567.86      2006612.06     13636286.64
      2006632.89     13635802.27      2006394.18     13635579.12
#Sta/Elev= 30
    4400     733  4461.5  732.47  4496.9  732.69  4532.2  732.21  4581.7  732.26
 4691.62730.6208  4819.4   728.8  4889.4  728.85  4919.5  729.46  4929.5  730.26
  4937.7  730.37  4949.5  730.08  4959.5  730.52  4969.5  729.84  4978.5  727.34
  4983.5  726.87  4996.5  724.05    4997  723.25    5002  723.25  5002.5  724.05
  5009.5  727.41  5019.6  728.42  5029.6  729.98  5079.6  728.93  5149.7  728.81
 5273.11730.6209  5282.1  730.69    5378     733  5470.3  733.99  5609.3   734.6
#Mann= 5 ,-1 , 0
    4400      .1       0  4937.7     .12       0  4996.5     .07       0
  5002.5     .12       0  5282.1      .1       0
Bank Sta=4691.62,5273.11
XS Rating Curve= 0 ,0
Exp/Cntr=0.3,0.1