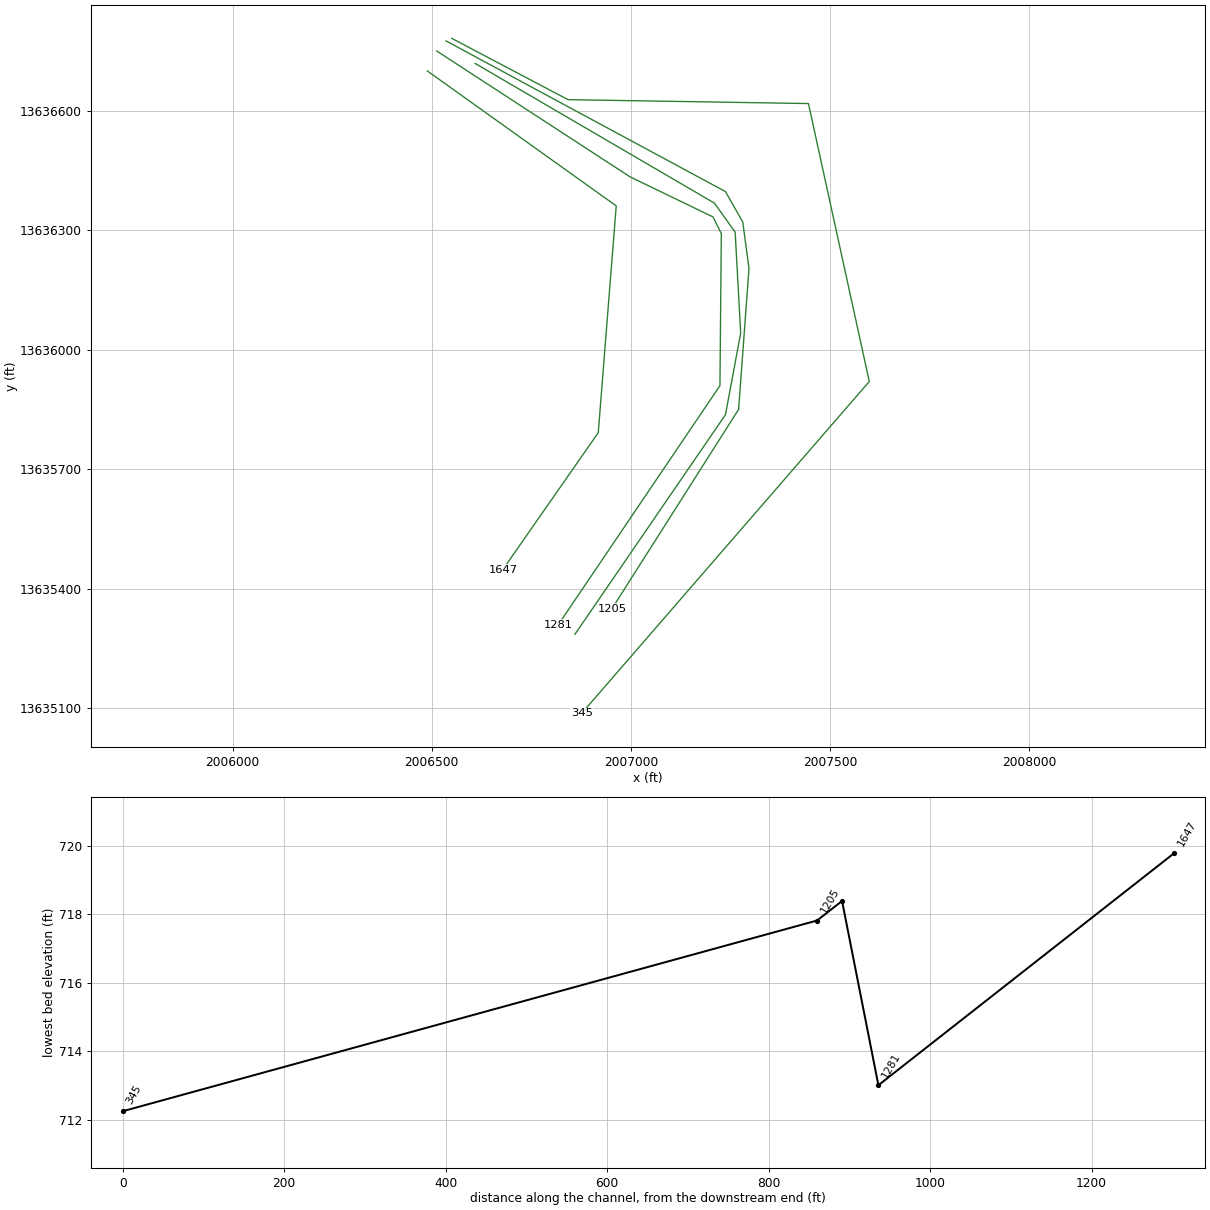
HEC-RAS study UNT 096 in HW.prj: UNT 096 in HW Base Level Engineering

--- UNT 096 in HW.g01 (geometry) --- (continued)

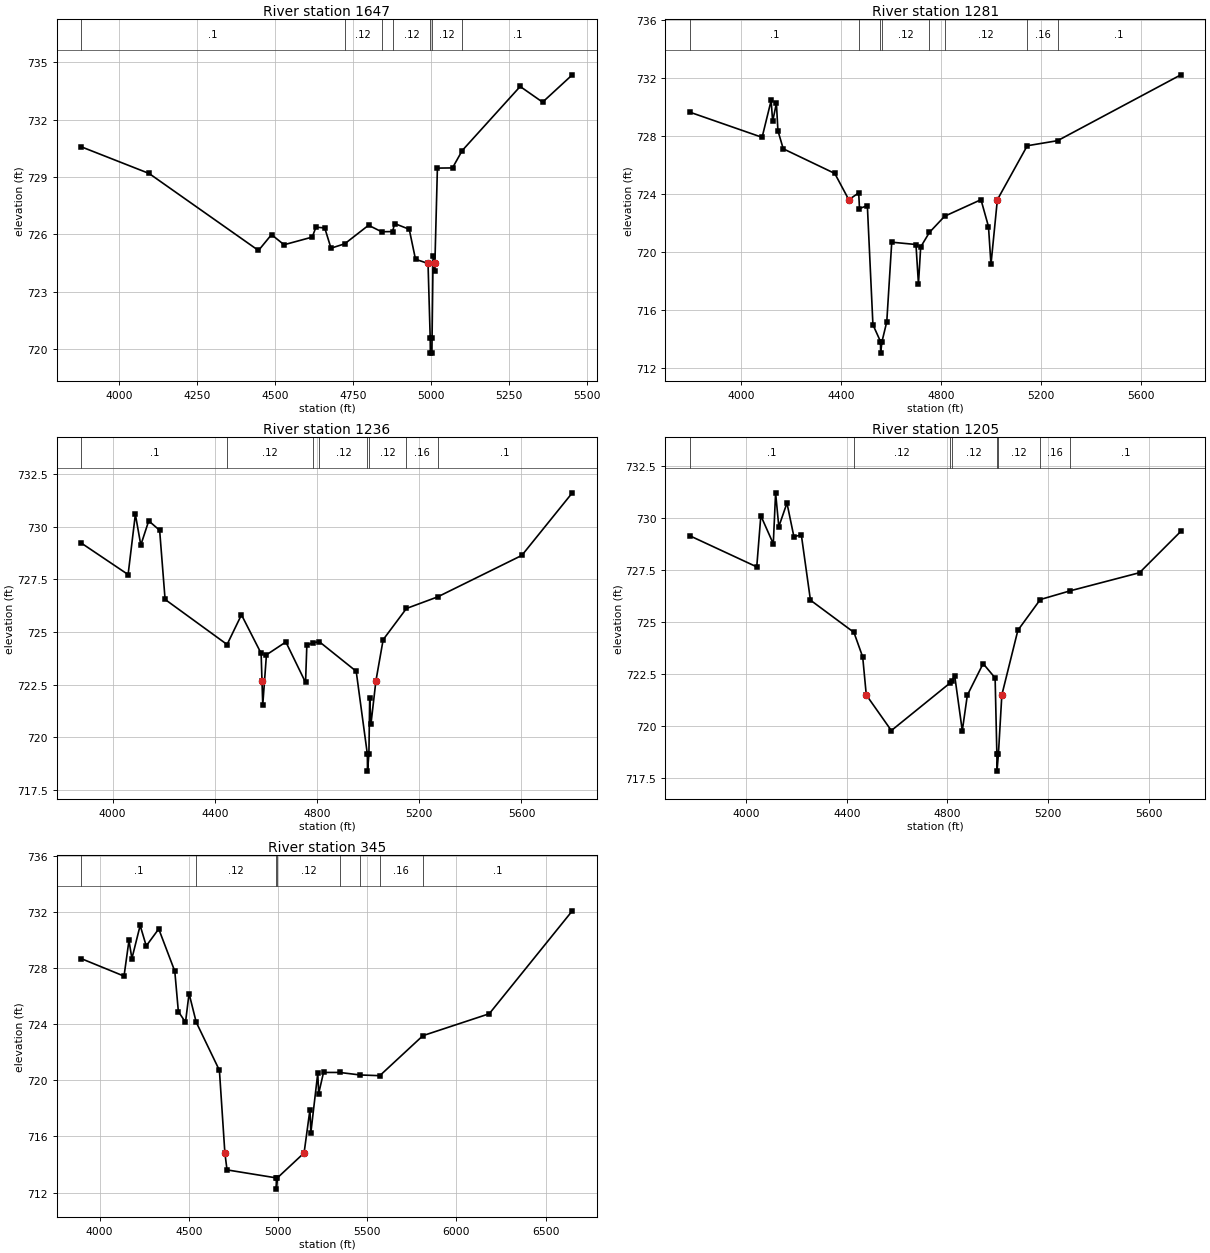
Type RM Length L Ch R = 1 ,1647    ,366,366,366
BEGIN DESCRIPTION:
Mapping XS de973b37
END DESCRIPTION:
XS GIS Cut Line= 4
      2006488.67     13636700.03       2006963.1      13636361.1
      2006917.96     13635791.65      2006678.37      13635447.9
#Sta/Elev= 30
  3878.7  730.57  4095.4  729.18  4446.1  725.15  4487.9  725.98  4528.1  725.45
  4618.3  725.85  4630.4  726.37  4658.5  726.33  4678.5  725.27  4722.6   725.5
  4798.9  726.47  4840.7  726.13    4876  726.14  4882.4  726.56  4929.3  726.26
  4949.4  724.69 4989.55724.4721  4996.5  720.58    4997  719.78    5002  719.78
  5002.5  720.58  5005.8  724.85  5010.9  724.08 5011.53724.4695  5019.6  729.46
    5068  729.47  5099.2  730.38  5284.9  733.73  5356.8  732.91    5452  734.34
#Mann= 7 ,-1 , 0
  3878.7      .1       0  4722.6     .12       0  4840.7     .16       0
    4876     .12       0  4996.5     .07       0  5002.5     .12       0
  5099.2      .1       0
Bank Sta=4989.55,5011.53
XS Rating Curve= 0 ,0
Exp/Cntr=0.3,0.1

Type RM Length L Ch R = 1 ,1281    ,45,45,45
BEGIN DESCRIPTION:
Mapping XS 62264f92
END DESCRIPTION:
XS GIS Cut Line= 6
      2006512.41       13636750.      2006997.82     13636434.02
      2007206.15     13636333.32      2007226.99     13636291.65
      2007223.51     13635909.71      2006817.61     13635309.52
#Sta/Elev= 30
  3795.2  729.62  4083.6  727.89  4119.8  730.43  4125.8  728.99  4140.9  730.24
  4146.9  728.35  4168.2   727.1  4374.4   725.4 4430.61723.5873  4470.2  724.06
  4473.3  722.98  4504.8  723.18  4527.1  714.97  4557.4  713.81  4557.9  713.01
  4563.4  713.81  4582.5  715.17  4602.4  720.66  4699.3   720.5  4709.3  717.78
  4718.3  720.33    4753  721.33  4814.1  722.45  4959.5  723.59  4989.5  721.74
  4999.5  719.13 5025.06723.5873  5144.7  727.31  5266.2  727.66  5759.4   732.2
#Mann= 8 ,-1 , 0
  3795.2      .1       0  4473.3     .12       0  4557.4     .07       0
  4563.4     .12       0    4753      .1       0  4814.1     .12       0
  5144.7     .16       0  5266.2      .1       0
Bank Sta=4430.61,5025.06
XS Rating Curve= 0 ,0
Exp/Cntr=0.3,0.1

Type RM Length L Ch R = 1 ,1236    ,31,31,31
BEGIN DESCRIPTION:
Mapping XS 9a70938f
END DESCRIPTION:
XS GIS Cut Line= 6
       2006608.9     13636718.76      2007209.63     13636368.04
      2007261.71     13636295.13       2007275.6     13636041.65
       2007237.4     13635836.79      2006859.46     13635285.48
#Sta/Elev= 30
  3878.5  729.21    4061  727.72  4089.4  730.58  4110.7  729.12  4141.7  730.27
  4184.4  729.82  4205.7  726.54  4448.3   724.4  4504.5  725.81  4581.4  723.98
  4584.8722.6785  4587.8  721.53  4602.2  723.91  4678.2  724.52  4755.2   722.6
  4760.3  724.36  4784.3  724.49  4809.4  724.53  4953.4  723.13  4997.1  719.19
  4997.6  718.39  5003.1  719.19  5006.2  721.86  5011.2  720.63 5030.57722.6782
  5058.9  724.63  5149.9  726.11    5272  726.66  5601.4  728.63  5798.9   731.6
#Mann= 8 ,-1 , 0
  3878.5      .1       0  4448.3     .12       0  4784.3      .1       0
  4809.4     .12       0  4997.1     .07       0  5003.1     .12       0
  5149.9     .16       0    5272      .1       0
Bank Sta=4584.8,5030.57
XS Rating Curve= 0 ,0
Exp/Cntr=0.3,0.1

Type RM Length L Ch R = 1 ,1205    ,860,860,860
BEGIN DESCRIPTION:
Mapping XS c133d4b3
END DESCRIPTION:
XS GIS Cut Line= 6
      2006535.77     13636775.33       2007237.4     13636396.98
      2007280.81     13636320.59      2007296.43     13636204.27
      2007270.39      13635850.1      2006952.69     13635350.12
#Sta/Elev= 30
  3777.4  729.13  4042.5  727.64  4058.7   730.1  4108.2  728.75  4117.4   731.2
  4130.1  729.57  4162.5  730.71  4190.1  729.09  4219.6  729.18  4255.8  726.04
  4428.6  724.49  4463.4  723.31 4477.65721.4819  4577.2  719.77  4811.8  722.07
  4817.1  722.16  4829.1  722.39  4859.1  719.76  4879.1  721.47  4941.9  722.99
  4989.5   722.3  4996.5  718.62    4997  717.82  5002.5  718.62  5016.2721.4808
  5079.9  724.59    5169  726.07  5288.1  726.49  5563.2  727.36  5727.5  729.35
#Mann= 8 ,-1 , 0
  3777.4      .1       0  4428.6     .12       0  4811.8      .1       0
  4817.1     .12       0  4996.5     .07       0  5002.5     .12       0
    5169     .16       0  5288.1      .1       0
Bank Sta=4477.65,5016.2
XS Rating Curve= 0 ,0
Exp/Cntr=0.3,0.1

Type RM Length L Ch R = 1 ,345     ,0,0,0
BEGIN DESCRIPTION:
UNT 096 in HW 1.0
END DESCRIPTION:
XS GIS Cut Line= 5
      2006549.99     13636781.83      2006842.09     13636627.86
      2007445.74     13636618.04      2007598.51     13635920.13
       2006876.3      13635086.8
#Sta/Elev= 30
  3898.7  728.66  4137.3  727.42    4165  729.96  4181.4  728.67  4227.7  731.03
  4261.8  729.57  4331.8  730.78  4421.8  727.77  4441.8   724.9  4481.8  724.13
  4501.8  726.18  4541.8  724.14  4671.9  720.71 4702.51714.8262  4714.5  713.62
  4990.6  713.05  4991.1  712.25  4996.6  713.05  5146.5714.8268  5179.3  717.91
  5184.4  716.27  5223.1   720.5  5228.3  719.06  5255.4  720.56  5345.5  720.56
  5460.5  720.38  5570.7  720.33  5812.6  723.18  6184.3  724.74  6649.8  732.07
#Mann= 8 ,-1 , 0
  3898.7      .1       0  4541.8     .12       0  4990.6     .07       0
  4996.6     .12       0  5345.5     .16       0  5460.5     .12       0
  5570.7     .16       0  5812.6      .1       0
Bank Sta=4702.51,5146.5
XS Rating Curve= 0 ,0
Exp/Cntr=0.3,0.1
LCMann Table=0

Chan Stop Cuts=-1
Use User Specified Reach Order=0
Composite Channel Slope=5