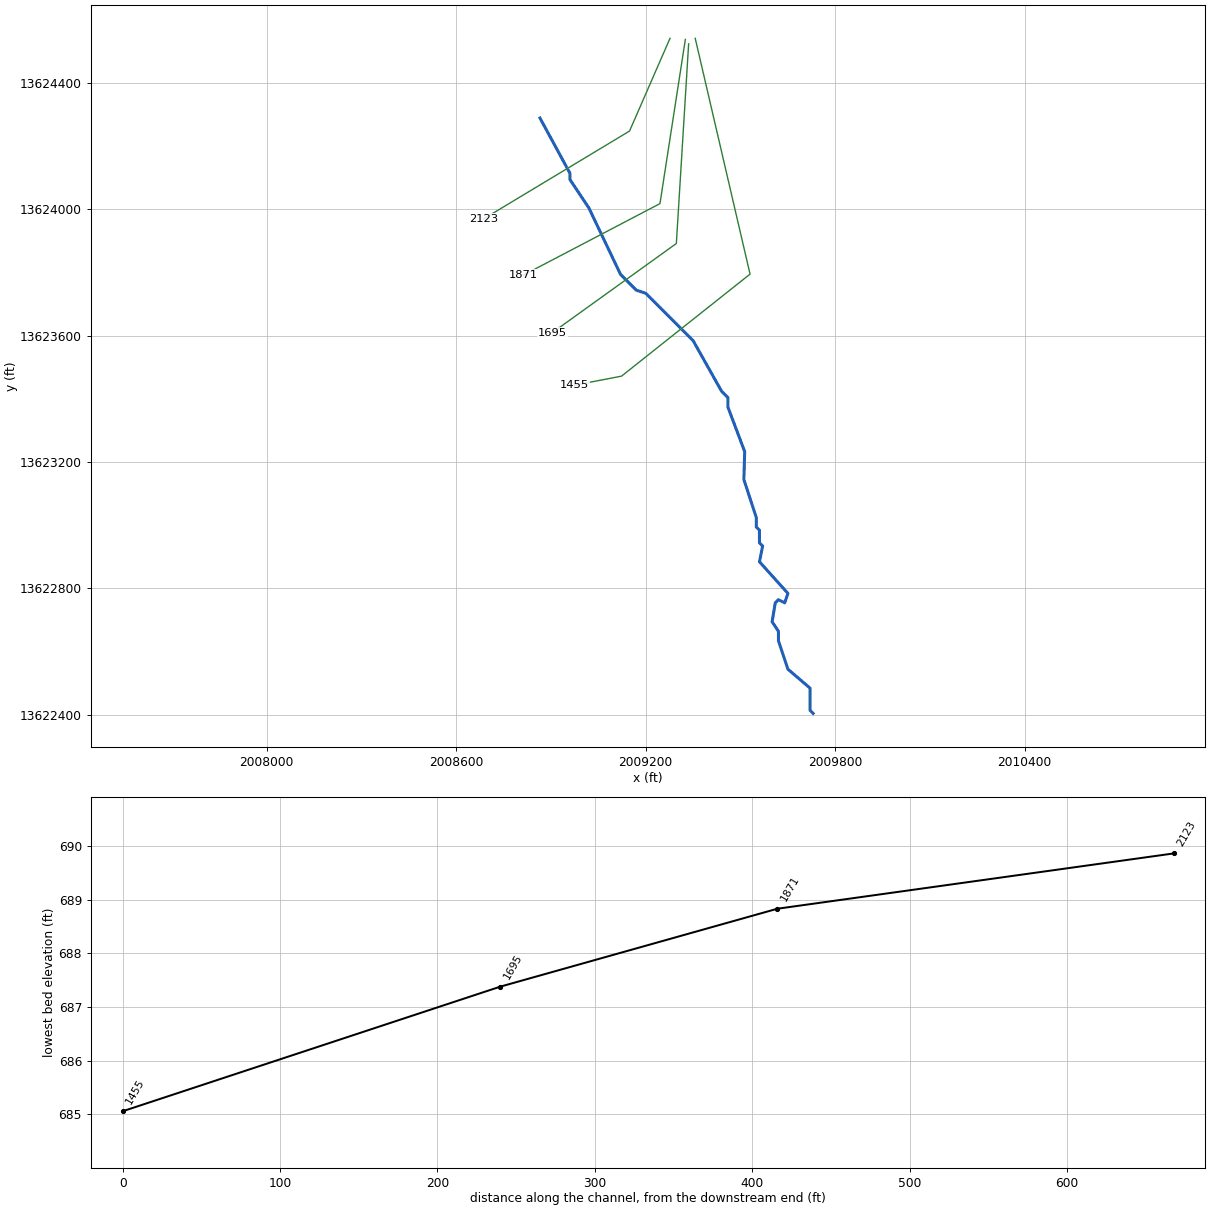
--- UNT 097 in HW.prj (project) ---

Proj Title=UNT 097 in HW Base Level Engineering
Current Plan=p01
Default Exp/Contr=0.3,0.1
English Units
Geom File=g01
Flow File=f01
Plan File=p01
BEGIN DESCRIPTION:
UNT 097 in HW
END DESCRIPTION:

--- UNT 097 in HW.p01 (plan) ---

Plan Title=Multiple Run
Short Identifier=Multiple
Geom File=g01
Flow File=f01
Subcritical Flow
K Sum by GR= 0
Std Step Tol= 0.01
Critical Tol= 0.01
Num of Std Step Trials= 20
Max Error Tol= 0.3
Flow Tol Ratio= 0.001
Split Flow NTrial= 30
Split Flow Tol= 0.02
Split Flow Ratio= 0.02
Log Output Level= 0
Friction Slope Method= 1
Unsteady Friction Slope Method= 2
Unsteady Bridges Friction Slope Method= 1
Parabolic Critical Depth
Global Vel Dist=  1 , 1 , 1
Global Log Level= 0
CheckData=True
Encroach Param= -1, 0, 0, 0
BEGIN DESCRIPTION:
Multiple Run
END DESCRIPTION:

--- UNT 097 in HW.f01 (steady flow) ---

Flow Title=Multiple
Number of Profiles=7
Profile Names=10-year,25-year,50-year,1pct_min,100-year,1pct_plu,500-year
River Rch & RM= UNT 097 in HW,Reach-1,2123
     458     633     776     471     940    1876    1385
River Rch & RM= UNT 097 in HW,Reach-1,1871
     555     776     960     587    1171    2337    1752
Boundary for River Rch & Prof#=UNT 097 in HW,Reach-1,1
Up Type=0
Dn Type=3
Dn Slope=0.005
Boundary for River Rch & Prof#=UNT 097 in HW,Reach-1,2
Up Type=0
Dn Type=3
Dn Slope=0.005
Boundary for River Rch & Prof#=UNT 097 in HW,Reach-1,3
Up Type=0
Dn Type=3
Dn Slope=0.005
Boundary for River Rch & Prof#=UNT 097 in HW,Reach-1,4
Up Type=0
Dn Type=3
Dn Slope=0.005
Boundary for River Rch & Prof#=UNT 097 in HW,Reach-1,5
Up Type=0
Dn Type=3
Dn Slope=0.005
Boundary for River Rch & Prof#=UNT 097 in HW,Reach-1,6
Up Type=0
Dn Type=3
Dn Slope=0.005
Boundary for River Rch & Prof#=UNT 097 in HW,Reach-1,7
Up Type=0
Dn Type=3
Dn Slope=0.005

--- UNT 097 in HW.g01 (geometry) ---

Geom Title=Existing Conditions

River Reach=UNT 097 in HW,Reach-1
Reach XY= 30
      2008865.80     13624289.54      2008960.80     13624114.54
      2008960.80     13624094.54      2009020.80     13624004.54
      2009120.80     13623794.54      2009170.80     13623744.54
      2009200.80     13623734.54      2009350.80     13623584.54
      2009440.80     13623424.54      2009460.80     13623404.54
      2009460.80     13623374.54      2009514.01     13623233.32
      2009511.40     13623144.78      2009550.80     13623024.54
      2009550.80     13622994.54      2009560.80     13622984.54
      2009560.80     13622944.54      2009570.80     13622934.54
      2009560.80     13622884.54      2009650.80     13622784.54
      2009640.80     13622754.54      2009620.80     13622764.54
      2009610.80     13622754.54      2009600.80     13622694.54
      2009620.80     13622664.54      2009620.80     13622634.54
      2009650.80     13622544.54      2009720.80     13622484.54
      2009720.80     13622414.54      2009730.80     13622404.54

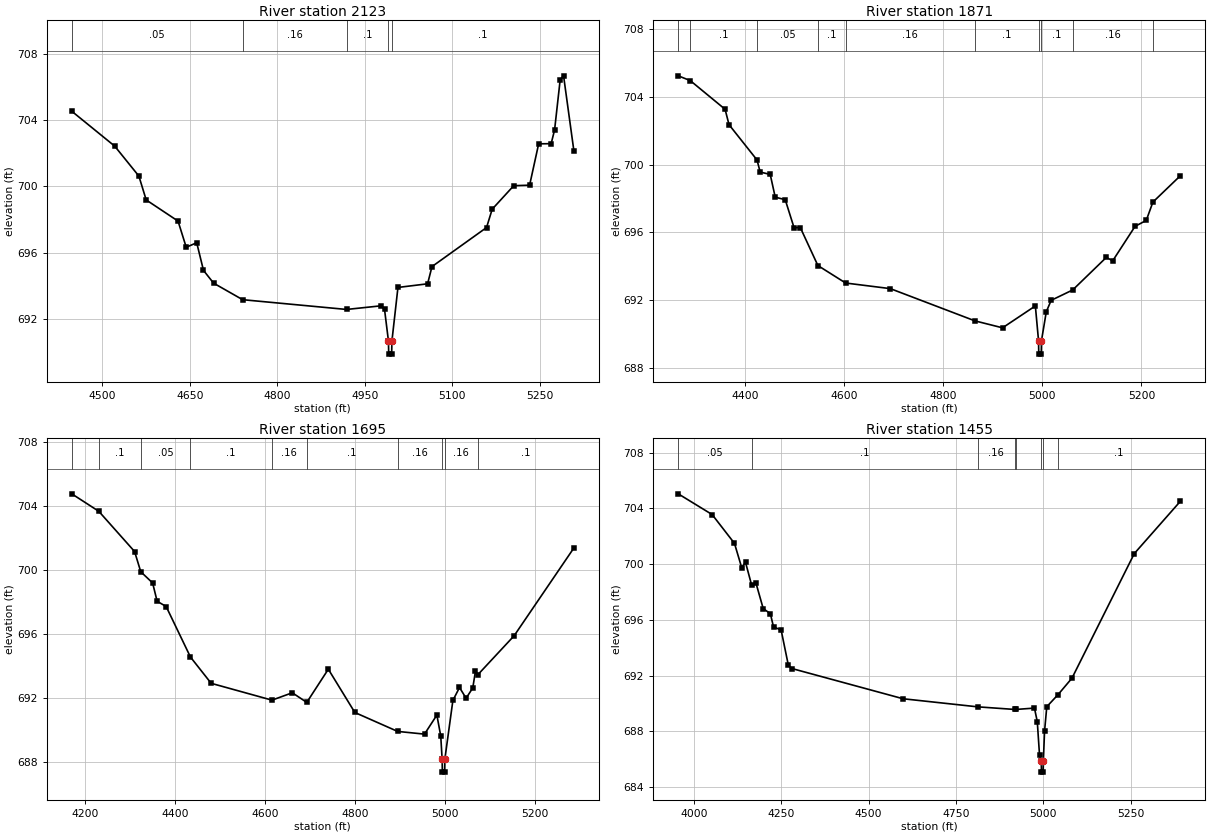
Type RM Length L Ch R = 1,2123,252,252,252
BEGIN DESCRIPTION:
UNT 097 in HW 1.0
END DESCRIPTION:
XS GIS Cut Line= 3
      2009277.51     13624541.90      2009149.42     13624248.36
      2008686.75     13623969.84
#Sta/Elev= 30
  4447.9  704.54  4521.5  702.43  4562.9  700.62  4575.4  699.18  4630.0  697.90
  4644.0  696.32  4662.0  696.59  4673.6  694.92  4690.9  694.15  4740.7  693.15
  4918.7  692.56  4977.9  692.78  4983.8  692.57  4990.5  690.66  4991.0  689.86
  4996.0  689.86  4996.5  690.66  5006.8  693.89  5057.6  694.11  5065.1  695.15
  5158.6  697.51  5168.3  698.62  5205.2  700.04  5232.4  700.07  5247.9  702.57
  5269.3  702.58  5275.2  703.41  5284.8  706.45  5290.6  706.68  5308.2  702.16
#Mann=5,-1,0
  4447.9    0.05       0  4740.7    0.16       0  4918.7     0.1       0
  4990.5    0.07       0  4996.5     0.1       0
Bank Sta=4990.5,4996.5
Exp/Cntr=0.3,0.1

Type RM Length L Ch R = 1,1871,176,176,176
BEGIN DESCRIPTION:
UNT 097 in HW 2.0
END DESCRIPTION:
XS GIS Cut Line= 3
      2009326.11     13624538.38      2009245.71     13624018.58
      2008814.16     13623792.64
#Sta/Elev= 30
  4265.3  705.23  4289.5  704.95  4359.8  703.26  4367.8  702.35  4424.3  700.27
  4430.6  699.56  4450.9  699.42  4461.0  698.08  4481.2  697.93  4499.0  696.28
  4511.6  696.29  4547.1  694.05  4603.1  693.02  4693.2  692.69  4864.0  690.79
  4919.7  690.38  4985.9  691.67  4992.3  689.63  4992.8  688.83  4997.8  688.83
  4998.3  689.63  5008.0  691.33  5017.8  692.00  5061.2  692.61  5129.1  694.53
  5142.0  694.33  5187.1  696.36  5209.7  696.71  5223.1  697.79  5278.4  699.34
#Mann=10,-1,0
  4265.3    0.05       0  4289.5     0.1       0  4424.3    0.05       0
  4547.1     0.1       0  4603.1    0.16       0  4864.0     0.1       0
  4992.3    0.07       0  4998.3     0.1       0  5061.2    0.16       0
  5223.1     0.1       0
Bank Sta=4992.3,4998.3
Exp/Cntr=0.3,0.1

Type RM Length L Ch R = 1,1695,240,240,240
BEGIN DESCRIPTION:
UNT 097 in HW 3.0
END DESCRIPTION:
XS GIS Cut Line= 3
      2009336.52     13624524.46      2009297.59     13623892.23
      2008905.29     13623610.34
#Sta/Elev= 30
  4169.9  704.74  4230.0  703.65  4309.6  701.14  4323.3  699.88  4349.7  699.18
  4359.7  698.04  4379.8  697.71  4433.8  694.56  4479.9  692.92  4615.1  691.87
  4660.3  692.33  4692.5  691.73  4740.4  693.80  4799.4  691.10  4894.5  689.92
  4954.3  689.75  4981.8  690.94  4990.4  689.64  4993.5  688.18  4994.0  687.38
  4999.0  687.38  4999.5  688.18  5017.4  691.85  5032.1  692.66  5046.8  691.99
  5061.6  692.63  5067.7  693.69  5072.7  693.45  5153.7  695.89  5286.4  701.36
#Mann=10,-1,0
  4169.9    0.05       0  4230.0     0.1       0  4323.3    0.05       0
  4433.8     0.1       0  4615.1    0.16       0  4692.5     0.1       0
  4894.5    0.16       0  4993.5    0.07       0  4999.5    0.16       0
  5072.7     0.1       0
Bank Sta=4993.5,4999.5
Exp/Cntr=0.3,0.1

Type RM Length L Ch R = 1,1455,0,0,0
BEGIN DESCRIPTION:
UNT 097 in HW 4.0
END DESCRIPTION:
XS GIS Cut Line= 4
      2009357.36     13624541.84      2009530.97     13623795.34
      2009124.07     13623472.33      2008975.65     13623443.69
#Sta/Elev= 30
  3955.3  705.05  4052.4  703.56  4116.3  701.49  4136.9  699.75  4147.9  700.13
  4165.1  698.52  4177.9  698.63  4198.5  696.81  4219.0  696.44  4228.0  695.49
  4249.8  695.27  4270.3  692.76  4280.8  692.50  4598.9  690.33  4812.2  689.75
  4919.6  689.56  4920.7  689.56  4974.9  689.66  4983.0  688.69  4989.4  686.29
  4994.4  685.86  4994.9  685.06  4999.9  685.06  5000.4  685.86  5003.8  687.99
  5010.2  689.76  5042.2  690.62  5082.3  691.81  5260.7  700.76  5392.4  704.51
#Mann=8,-1,0
  3955.3    0.05       0  4165.1     0.1       0  4812.2    0.16       0
  4919.6    0.12       0  4920.7    0.16       0  4994.4    0.07       0
  5000.4    0.16       0  5042.2     0.1       0
Bank Sta=4994.4,5000.4
Exp/Cntr=0.3,0.1

Chan Stop Cuts=-1