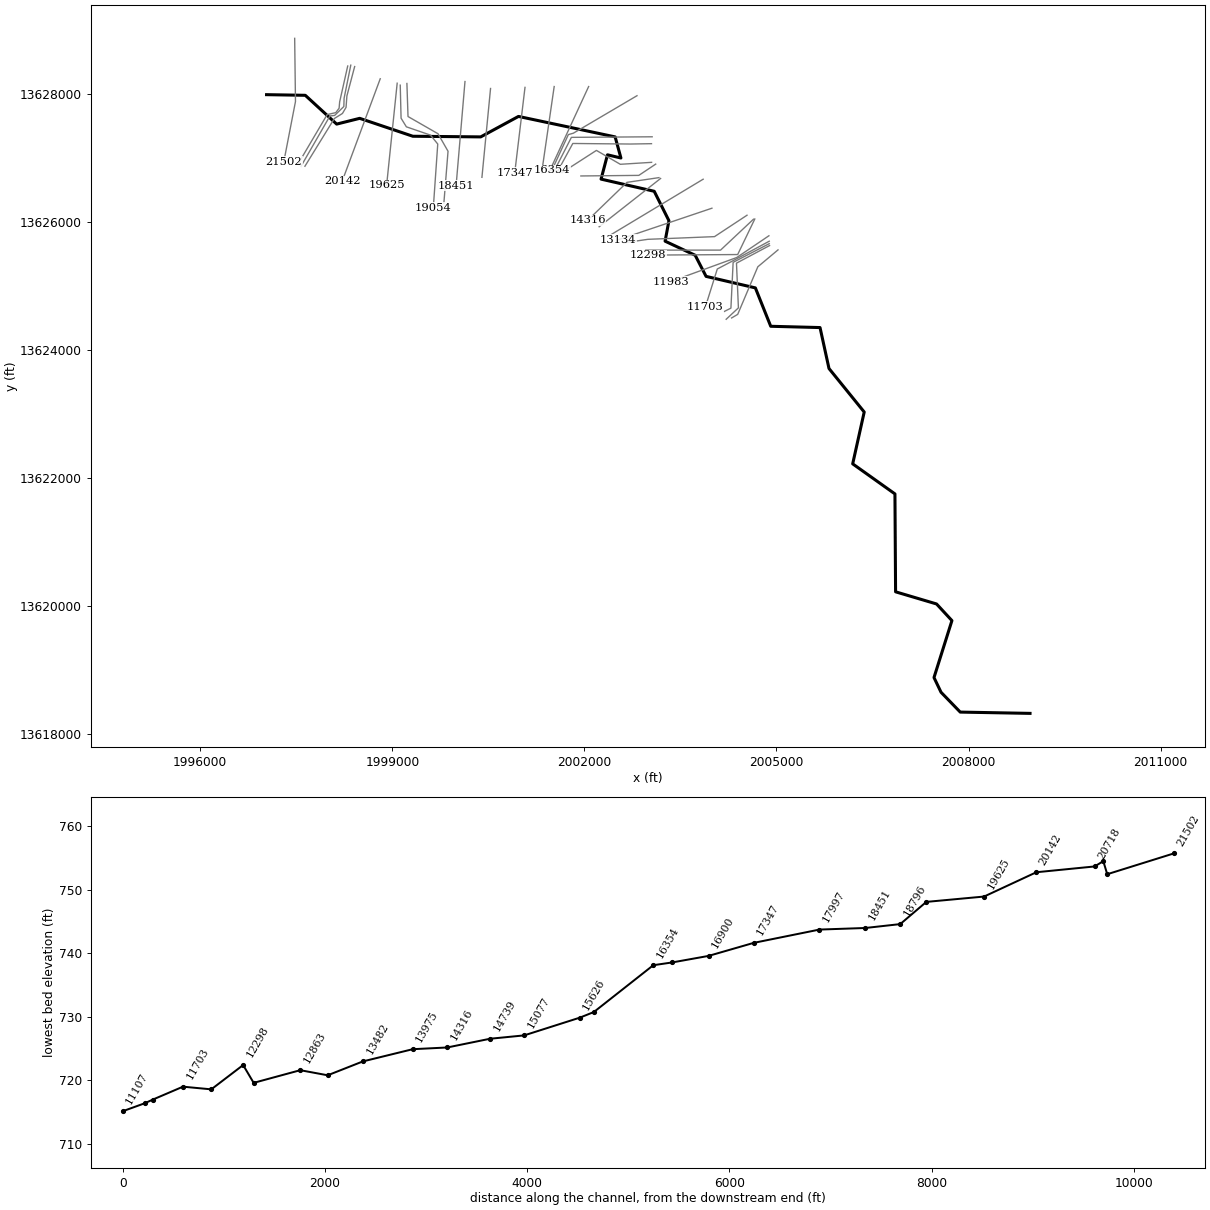
--- UNT 098 in HW.prj (project) ---

Proj Title=UNT 098 in HW Base Level Engineering
Current Plan=p01
Default Exp/Contr=0.3,0.1
English Units
Geom File=g01
Flow File=f01
Plan File=p01
Y Axis Title=Elevation
X Axis Title(PF)=Main Channel Distance
X Axis Title(XS)=Station
BEGIN DESCRIPTION:
UNT 098 in HW
END DESCRIPTION:
DSS Export Rating Curves= 0
DSS Export Rating Curve Sorted= 0
DSS Export Volume Flow Curves= 0
DXF OffsetX= 0
DXF OffsetY= 0
DXF ScaleX= 1
DXF ScaleY= 10

--- UNT 098 in HW.p01 (plan) ---

Plan Title=Multiple Run
Short Identifier=Multiple
Geom File=g01
Flow File=f01
Subcritical Flow
K Sum by GR= 0
Std Step Tol= 0.01
Critical Tol= 0.01
Num of Std Step Trials= 20
Max Error Tol= 0.3
Flow Tol Ratio= 0.001
Split Flow NTrial= 30
Split Flow Tol= 0.02
Split Flow Ratio= 0.02
Log Output Level= 0
Friction Slope Method= 1
Unsteady Friction Slope Method= 2
Unsteady Bridges Friction Slope Method= 1
Parabolic Critical Depth
Global Vel Dist=  1 , 1 , 1
Global Log Level= 0
CheckData=True
Encroach Param= -1, 0, 0, 0
BEGIN DESCRIPTION:
Multiple Run
END DESCRIPTION:

--- UNT 098 in HW.f01 (steady flow) ---

Flow Title=Multiple
Number of Profiles=7
Profile Names=10-year,25-year,50-year,1pct_min,100-year,1pct_plu,500-year
River Rch & RM= UNT 098 in HW,Reach-1,21502
     488     684     848     521    1040    2074    1569
River Rch & RM= UNT 098 in HW,Reach-1,20142
    1082    1583    2017    1271    2536    5060    4025
River Rch & RM= UNT 098 in HW,Reach-1,15766
    1247    1827    2329    1467    2927    5839    4641
River Rch & RM= UNT 098 in HW,Reach-1,4445
    1532    2263    2901    1836    3662    7307    5866
River Rch & RM= UNT 098 in HW,Reach-1,144
    5777    8792   11504    7397   14759   29449   24394
Boundary for River Rch & Prof#=UNT 098 in HW,Reach-1,1
Up Type=0
Dn Type=3
Dn Slope=0.005
Boundary for River Rch & Prof#=UNT 098 in HW,Reach-1,2
Up Type=0
Dn Type=3
Dn Slope=0.005
Boundary for River Rch & Prof#=UNT 098 in HW,Reach-1,3
Up Type=0
Dn Type=3
Dn Slope=0.005
Boundary for River Rch & Prof#=UNT 098 in HW,Reach-1,4
Up Type=0
Dn Type=3
Dn Slope=0.005
Boundary for River Rch & Prof#=UNT 098 in HW,Reach-1,5
Up Type=0
Dn Type=3
Dn Slope=0.005
Boundary for River Rch & Prof#=UNT 098 in HW,Reach-1,6
Up Type=0
Dn Type=3
Dn Slope=0.005
Boundary for River Rch & Prof#=UNT 098 in HW,Reach-1,7
Up Type=0
Dn Type=3
Dn Slope=0.005

--- UNT 098 in HW.g01 (geometry) ---

Geom Title=Existing Conditions
Program Version=5.05

River Reach=UNT 098 in HW   ,Reach-1
Reach XY= 30
       1997035.8     13627994.54       1997640.8     13627984.54
       1998130.8     13627534.54       1998490.8     13627624.54
       1999320.8     13627344.54       2000380.8     13627334.54
       2000970.8     13627654.54       2002480.8     13627334.54
       2002570.8     13627004.54       2002360.8     13627054.54
       2002260.8     13626674.54       2003090.8     13626484.54
       2003320.8     13626024.54       2003260.8     13625704.54
       2003730.8     13625484.54       2003900.8     13625154.54
       2004670.8     13624974.54       2004910.8     13624374.54
       2005680.8     13624354.54       2005820.8     13623714.54
       2006370.8     13623034.54       2006190.8     13622224.54
       2006850.8     13621754.54       2006860.8     13620224.54
       2007500.8     13620034.54       2007740.8     13619774.54
       2007460.8     13618884.54       2007570.8     13618654.54
       2007870.8     13618344.54       2008960.8     13618324.54

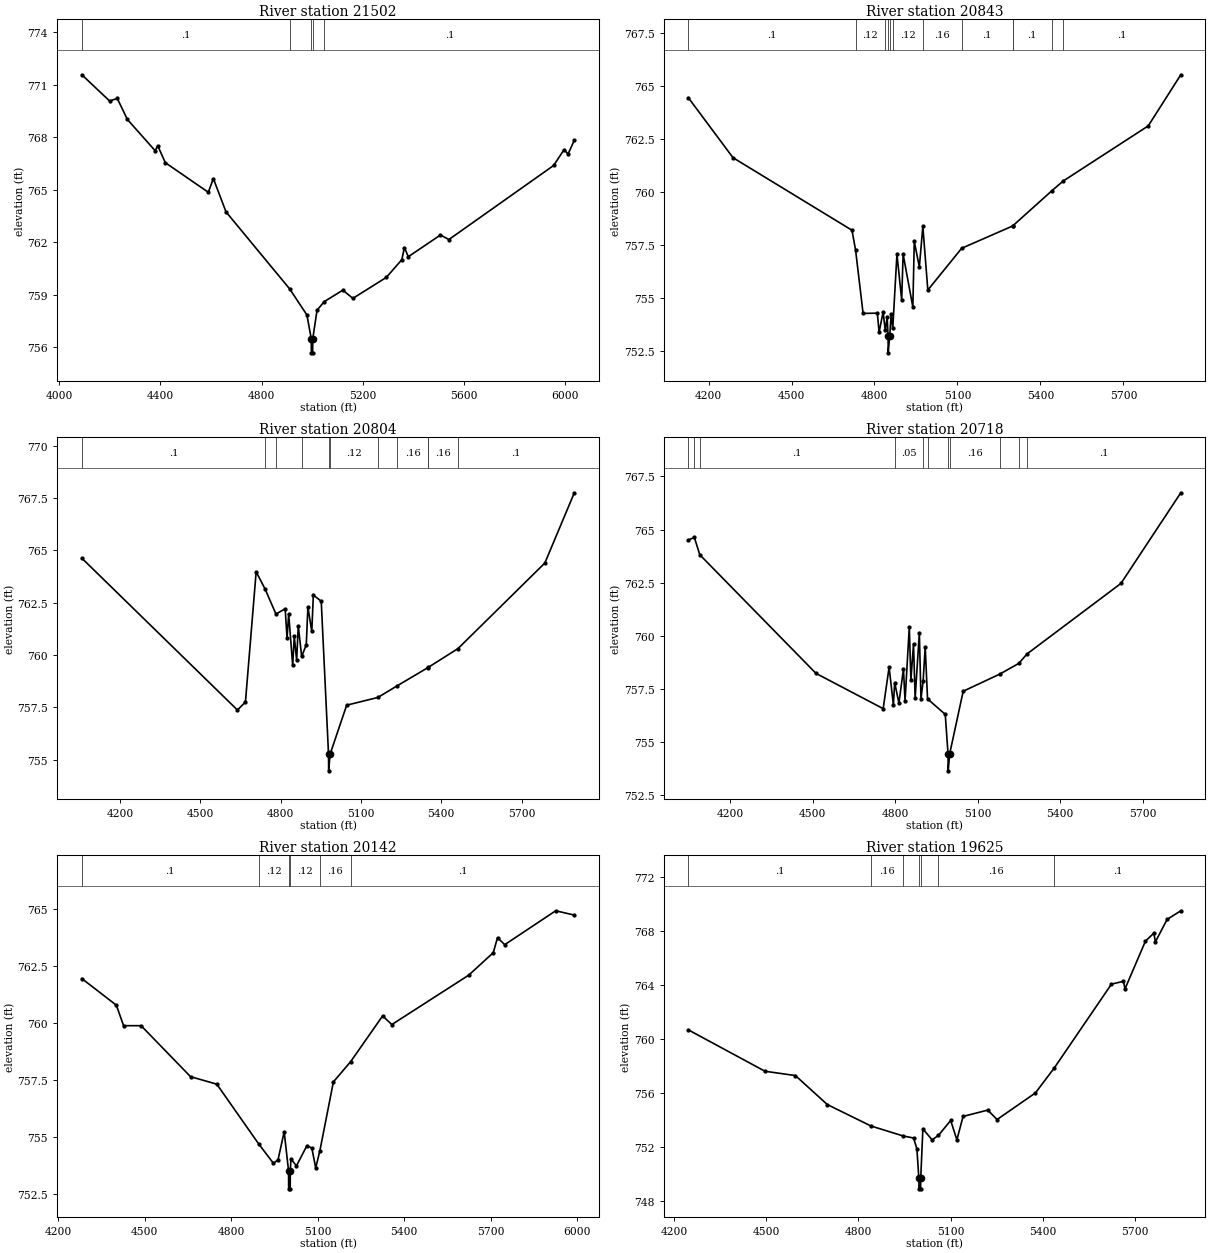
Type RM Length L Ch R = 1 ,21502   ,659,659,659
BEGIN DESCRIPTION:
UNT 098 in HW 46.0
END DESCRIPTION:
XS GIS Cut Line= 3
        1997475.     13628874.96      1997487.59     13627887.13
       1997305.3     13626945.32
#Sta/Elev= 30
  4089.5  771.56  4199.5  770.06  4229.5  770.21  4269.5  769.01  4379.5  767.22
  4389.5  767.51  4419.5  766.54  4589.5  764.85  4609.5  765.63  4659.5  763.73
  4911.2  759.33  4979.5  757.84  4996.5  756.48    4997  755.68    5002  755.68
  5002.5  756.48  5019.5  758.12  5048.4  758.61  5121.4  759.26  5161.1  758.79
  5293.5  759.99  5354.6     761  5364.8  761.69  5380.3  761.17  5507.4  762.41
  5540.7  762.15  5954.9  766.38  5996.3  767.29  6011.8  767.03  6036.7  767.82
#Mann= 5 ,-1 , 0
  4089.5      .1       0  4911.2     .12       0  4996.5     .07       0
  5002.5     .12       0  5048.4      .1       0
Bank Sta=4996.5,5002.5
XS Rating Curve= 0 ,0
Exp/Cntr=0.3,0.1

Type RM Length L Ch R = 1 ,20843   ,39,39,39
BEGIN DESCRIPTION:
Mapping XS a0d8be5d
END DESCRIPTION:
XS GIS Cut Line= 6
      1998303.55     13628442.65      1998177.69     13627882.79
      1998169.01     13627782.97      1998116.93     13627713.52
      1997982.38     13627683.14      1997535.31     13626923.55
#Sta/Elev= 30
    4127  764.44  4288.6  761.61  4718.7  758.19  4731.7  757.25  4758.8  754.27
  4810.4  754.28  4816.6  753.38  4831.2  754.33    4839  753.47  4845.8  754.09
  4849.1  753.21  4849.6  752.41  4855.1  753.21  4860.4  754.24  4866.1  753.58
  4881.2  757.06  4898.3  754.91  4903.5  757.06  4938.7  754.57  4943.8  757.66
  4962.2  756.46  4974.8  758.37  4992.8  755.37  5115.2  757.34  5299.3  758.39
  5299.4  758.39    5441  760.05  5482.1  760.51  5789.6  763.11  5907.3  765.52
#Mann= 12 ,-1 , 0
    4127      .1       0  4731.7     .12       0    4839     .05       0
  4849.1     .07       0  4855.1     .05       0  4866.1     .12       0
  4974.8     .16       0  5115.2      .1       0  5299.3     .16       0
  5299.4      .1       0    5441     .16       0  5482.1      .1       0
Bank Sta=4849.1,4855.1
XS Rating Curve= 0 ,0
Exp/Cntr=0.3,0.1

Type RM Length L Ch R = 1 ,20804   ,86,86,86
BEGIN DESCRIPTION:
Mapping XS 4b0c5460
END DESCRIPTION:
XS GIS Cut Line= 6
       1998351.3     13628455.68      1998247.14     13627939.22
       1998242.8     13627809.01      1998099.57     13627670.12
      1998025.78     13627661.44      1997574.41     13626875.88
#Sta/Elev= 30
  4057.5  764.63  4638.6  757.37  4668.6  757.75  4708.7  763.98  4741.9  763.16
  4782.6  761.96  4817.1  762.21  4824.1  760.81  4830.2  761.96  4845.1  759.51
  4851.1  760.89    4860  759.74    4866   761.4  4878.7  759.93  4895.9  760.49
  4901.9   762.3  4916.5  761.13  4922.3  762.87  4951.8  762.57    4979  755.26
  4979.5  754.46    4985  755.26  5046.8   757.6  5163.4  757.97  5235.9  758.53
  5350.7   759.4  5351.8  759.41  5462.9  760.31  5787.2   764.4  5897.3  767.76
#Mann= 11 ,-1 , 0
  4057.5      .1       0  4741.9     .12       0  4782.6     .05       0
  4878.7     .12       0    4979     .07       0    4985     .12       0
  5163.4      .1       0  5235.9     .16       0  5350.7      .1       0
  5351.8     .16       0  5462.9      .1       0
Bank Sta=4979,4985
XS Rating Curve= 0 ,0
Exp/Cntr=0.3,0.1

Type RM Length L Ch R = 1 ,20718   ,576,576,576
BEGIN DESCRIPTION:
Mapping XS 224d782e
END DESCRIPTION:
XS GIS Cut Line= 6
      1998412.06     13628433.99      1998290.54     13627973.94
      1998277.52     13627795.99      1998221.09      13627700.5
      1998095.23     13627622.38      1997635.17     13626875.87
#Sta/Elev= 30
  4048.1   764.5    4070  764.63  4089.8  763.81  4512.5  758.22  4756.7  756.56
  4778.2  758.51  4793.8  756.74  4798.5  757.79  4813.9  756.82  4830.4  758.43
  4836.2  756.93  4851.6   760.4  4857.5  757.92    4867  759.61  4872.9  757.05
  4888.2  760.14  4894.1  757.02    4902  757.87  4909.5  759.46    4918  757.02
  4982.4  756.29  4992.5  754.43    4993  753.63  4998.5  754.43  5047.6  757.38
  5181.1  758.19  5249.7  758.69    5280  759.14  5621.3  762.46  5838.9  766.73
#Mann= 11 ,-1 , 0
  4048.1      .1       0    4070     .05       0  4089.8      .1       0
  4798.5     .05       0    4902     .12       0    4918     .16       0
  4992.5     .07       0  4998.5     .16       0  5181.1      .1       0
  5249.7     .16       0    5280      .1       0
Bank Sta=4992.5,4998.5
XS Rating Curve= 0 ,0
Exp/Cntr=0.3,0.1

Type RM Length L Ch R = 1 ,20142   ,517,517,517
BEGIN DESCRIPTION:
Mapping XS 4d1fe525
END DESCRIPTION:
XS GIS Cut Line= 2
      1998811.38     13628243.05      1998216.75     13626641.47
#Sta/Elev= 30
  4281.5  761.96  4401.2  760.79  4426.3  759.89    4487  759.89  4658.5  757.65
  4749.6  757.32  4894.6   754.7  4946.2  753.84  4962.1     754  4983.4  755.23
  4998.5  753.52    4999  752.72  5004.2  752.72  5004.7  753.52  5006.9  754.03
  5026.1  753.73  5062.3  754.62  5079.4  754.51  5092.7  753.64  5107.3   754.4
  5154.1  757.42    5214  758.31  5324.9  760.32  5356.8  759.94  5623.5  762.11
  5708.8   763.1  5723.4  763.76  5748.4  763.45  5925.3  764.94  5989.9  764.75
#Mann= 6 ,-1 , 0
  4281.5      .1       0  4894.6     .12       0  4998.5     .07       0
  5004.7     .12       0  5107.3     .16       0    5214      .1       0
Bank Sta=4998.5,5004.7
XS Rating Curve= 0 ,0
Exp/Cntr=0.3,0.1

Type RM Length L Ch R = 1 ,19625   ,571,571,571
BEGIN DESCRIPTION:
Mapping XS 9095a06b
END DESCRIPTION:
XS GIS Cut Line= 2
      1999076.13     13628173.63       1998911.2     13626580.75
#Sta/Elev= 30
  4246.9  760.69  4496.2  757.62  4595.1   757.3  4698.9  755.15  4840.9  753.56
  4945.7  752.82  4979.4  752.67  4990.3  751.85  4996.4   749.7  4996.9   748.9
  5002.2   748.9  5002.7   749.7  5009.6  753.35  5039.7  752.53  5060.4  752.87
  5100.1  753.97  5120.2  752.53  5140.3  754.27  5220.7  754.74  5250.9  754.04
  5375.5  756.01  5437.1  757.87  5622.8  764.08  5661.9  764.29  5666.9  763.73
  5733.4  767.27  5760.7  767.86  5765.8  767.22  5803.8  768.88  5848.3  769.52
#Mann= 7 ,-1 , 0
  4246.9      .1       0  4840.9     .16       0  4945.7      .1       0
  4996.4     .07       0  5002.7      .1       0  5060.4     .16       0
  5437.1      .1       0
Bank Sta=4996.4,5002.7
XS Rating Curve= 0 ,0
Exp/Cntr=0.3,0.1

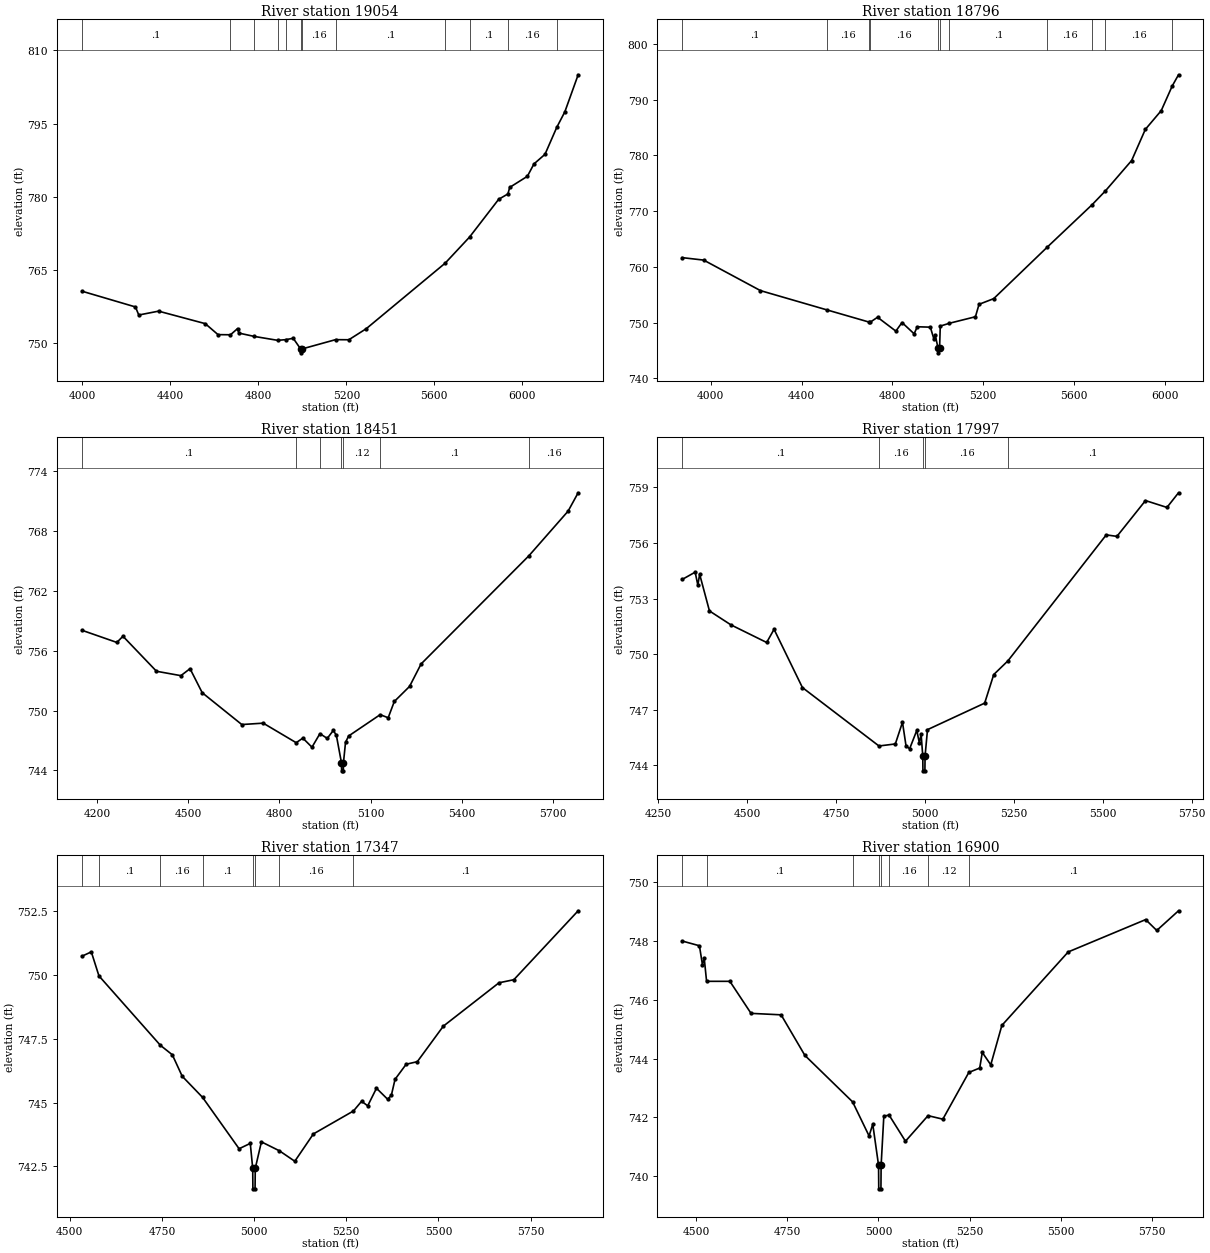
Type RM Length L Ch R = 1 ,19054   ,258,258,258
BEGIN DESCRIPTION:
Mapping XS 2db0c87c
END DESCRIPTION:
XS GIS Cut Line= 6
      1999123.87     13628143.19      1999136.89     13627626.72
      1999219.36     13627492.17      1999596.96     13627361.96
      1999709.81     13627223.07      1999640.36     13626224.78
#Sta/Elev= 30
  3998.8  760.69    4242  757.46  4257.1  755.81  4347.1   756.6  4559.1  754.04
  4617.1  751.79  4673.8  751.76  4706.2  753.04  4711.6  752.11    4781  751.43
  4888.2  750.62  4924.5  750.76  4958.8  751.04  4992.3  748.86  4992.8  748.06
  4998.8  748.86  5151.1  750.76  5211.5  750.74  5290.7  753.01  5649.1  766.43
  5759.9  771.78  5892.1  779.51    5934  780.61  5942.2  781.95  6022.4  784.22
  6052.5  786.76  6102.6  788.73  6155.8  794.23  6192.8  797.44  6253.2  805.02
#Mann= 12 ,-1 , 0
  3998.8      .1       0  4673.8     .12       0    4781     .16       0
  4888.2     .12       0  4924.5     .16       0  4992.3     .07       0
  4998.8     .16       0  5151.1      .1       0  5649.1     .16       0
  5759.9      .1       0    5934     .16       0  6155.8      .1       0
Bank Sta=4992.3,4998.8
XS Rating Curve= 0 ,0
Exp/Cntr=0.3,0.1

Type RM Length L Ch R = 1 ,18796   ,345,345,345
BEGIN DESCRIPTION:
Mapping XS d8d654e2
END DESCRIPTION:
XS GIS Cut Line= 5
      1999228.04     13628169.27       1999245.4     13627652.76
      1999714.15     13627383.66       1999870.4     13627110.22
      1999805.35     13626299.26
#Sta/Elev= 30
  3874.6  761.66  3968.9  761.22  4219.1  755.74  4510.8  752.29  4698.4  750.08
  4702.1  750.06  4734.7  750.96  4815.3  748.47  4842.6  750.01  4895.8  747.99
  4909.8  749.25  4967.3  749.18  4983.1  747.03  4988.9  747.76  5001.4  745.37
  5001.9  744.57  5007.9  745.37    5011  749.37  5051.2  749.88  5165.9  751.05
  5181.8  753.28  5246.4   754.3  5483.1  763.58  5680.2  771.18  5738.6  773.65
    5854   779.1  5914.2  784.68  5984.4  788.06  6032.6  792.47  6060.4  794.49
#Mann= 11 ,-1 , 0
  3874.6      .1       0  4510.8     .16       0  4698.4     .12       0
  4702.1     .16       0  5001.4     .07       0  5007.9     .16       0
  5051.2      .1       0  5483.1     .16       0  5680.2      .1       0
  5738.6     .16       0  6032.6      .1       0
Bank Sta=5001.4,5007.9
XS Rating Curve= 0 ,0
Exp/Cntr=0.3,0.1

Type RM Length L Ch R = 1 ,18451   ,454,454,454
BEGIN DESCRIPTION:
Mapping XS 77486a54
END DESCRIPTION:
XS GIS Cut Line= 2
      2000135.15     13628199.59      1999996.27     13626572.01
#Sta/Elev= 30
  4149.8  758.05  4264.8  756.83  4284.9  757.45  4395.3  753.94  4475.6   753.5
  4505.7   754.2  4545.8  751.79  4676.1   748.6  4746.6  748.74  4855.2  746.78
    4877  747.24  4907.1  746.33  4933.3  747.69  4957.3  747.21  4977.4  748.01
  4987.4  747.52  5004.2  744.76  5004.7  743.96  5010.2  743.96  5010.7  744.76
  5017.5  746.81  5027.6  747.45  5131.6  749.59    5158  749.28  5178.1  750.91
  5228.3  752.42  5266.2  754.67    5621  765.51  5750.2  769.99  5783.3  771.83
#Mann= 7 ,-1 , 0
  4149.8      .1       0  4855.2     .16       0  4933.3     .12       0
  5004.2     .07       0  5010.7     .12       0  5131.6      .1       0
    5621     .16       0
Bank Sta=5004.2,5010.7
XS Rating Curve= 0 ,0
Exp/Cntr=0.3,0.1

Type RM Length L Ch R = 1 ,17997   ,650,650,650
BEGIN DESCRIPTION:
Mapping XS 39ff786e
END DESCRIPTION:
XS GIS Cut Line= 2
      2000534.46     13628091.08      2000399.96     13626702.68
#Sta/Elev= 30
  4318.2  754.03  4354.4  754.42    4362  753.72    4367  754.31  4394.6  752.33
  4454.9  751.58  4555.4  750.63  4576.2  751.34  4655.9   748.2  4871.1  745.05
  4917.1  745.16  4937.2  746.33  4947.2  745.05  4957.3   744.9  4977.4  745.89
  4984.5  745.23  4989.6  745.68  4994.2  744.51  4994.7  743.71  5000.2  743.71
  5000.7  744.51  5007.5  745.93  5168.2  747.36  5193.7   748.9  5233.6  749.64
    5510  756.43    5540  756.35  5620.3  758.28  5680.6  757.91  5713.1   758.7
#Mann= 5 ,-1 , 0
  4318.2      .1       0  4871.1     .16       0  4994.2     .07       0
  5000.7     .16       0  5233.6      .1       0
Bank Sta=4994.2,5000.7
XS Rating Curve= 0 ,0
Exp/Cntr=0.3,0.1

Type RM Length L Ch R = 1 ,17347   ,447,447,447
BEGIN DESCRIPTION:
Mapping XS 1563152e
END DESCRIPTION:
XS GIS Cut Line= 2
      2001072.66      13628108.5      2000912.07     13626771.71
#Sta/Elev= 30
  4532.7  750.73  4558.2   750.9  4578.9  749.96  4745.7  747.24    4778  746.87
  4804.8  746.03  4860.2   745.2  4959.2  743.19  4989.5   743.4  4996.1  742.42
  4996.6  741.62  5002.5  741.62    5003  742.42  5019.7  743.46  5068.5  743.11
  5110.3   742.7  5160.7  743.77  5269.5  744.67  5291.6  745.05  5308.1  744.87
  5331.9  745.56  5362.1  745.13  5372.2  745.28  5382.3  745.91  5412.5   746.5
  5442.7   746.6  5513.2  747.99  5664.3  749.69  5704.6  749.81  5879.1  752.51
#Mann= 8 ,-1 , 0
  4532.7     .05       0  4578.9      .1       0  4745.7     .16       0
  4860.2      .1       0  4996.1     .07       0    5003      .1       0
  5068.5     .16       0  5269.5      .1       0
Bank Sta=4996.1,5003
XS Rating Curve= 0 ,0
Exp/Cntr=0.3,0.1

Type RM Length L Ch R = 1 ,16900   ,361,361,361
BEGIN DESCRIPTION:
Mapping XS bb25c7ab
END DESCRIPTION:
XS GIS Cut Line= 2
      2001528.38     13628121.48      2001333.07     13626775.98
#Sta/Elev= 30
  4462.7     748  4509.7  747.84  4517.9   747.2  4522.9  747.41  4529.3  746.63
  4593.1  746.63  4651.1  745.54  4733.5  745.49  4798.6  744.11  4929.3  742.53
  4974.5  741.37  4984.6  741.77  5000.5  740.37    5001  739.57    5007  739.57
  5007.5  740.37  5014.9  742.04  5029.3  742.08  5074.2  741.19  5136.1  742.06
  5176.6  741.94  5247.8  743.53  5277.6  743.68  5284.7  744.21  5307.9  743.79
  5338.3  745.13  5520.1  747.63  5732.3  748.73  5762.7  748.36  5822.3  749.03
#Mann= 8 ,-1 , 0
  4462.7     .08       0  4529.3      .1       0  4929.3     .07       0
  5000.5     .07       0  5007.5     .07       0  5029.3     .16       0
  5136.1     .12       0  5247.8      .1       0
Bank Sta=5000.5,5007.5
XS Rating Curve= 0 ,0
Exp/Cntr=0.3,0.1

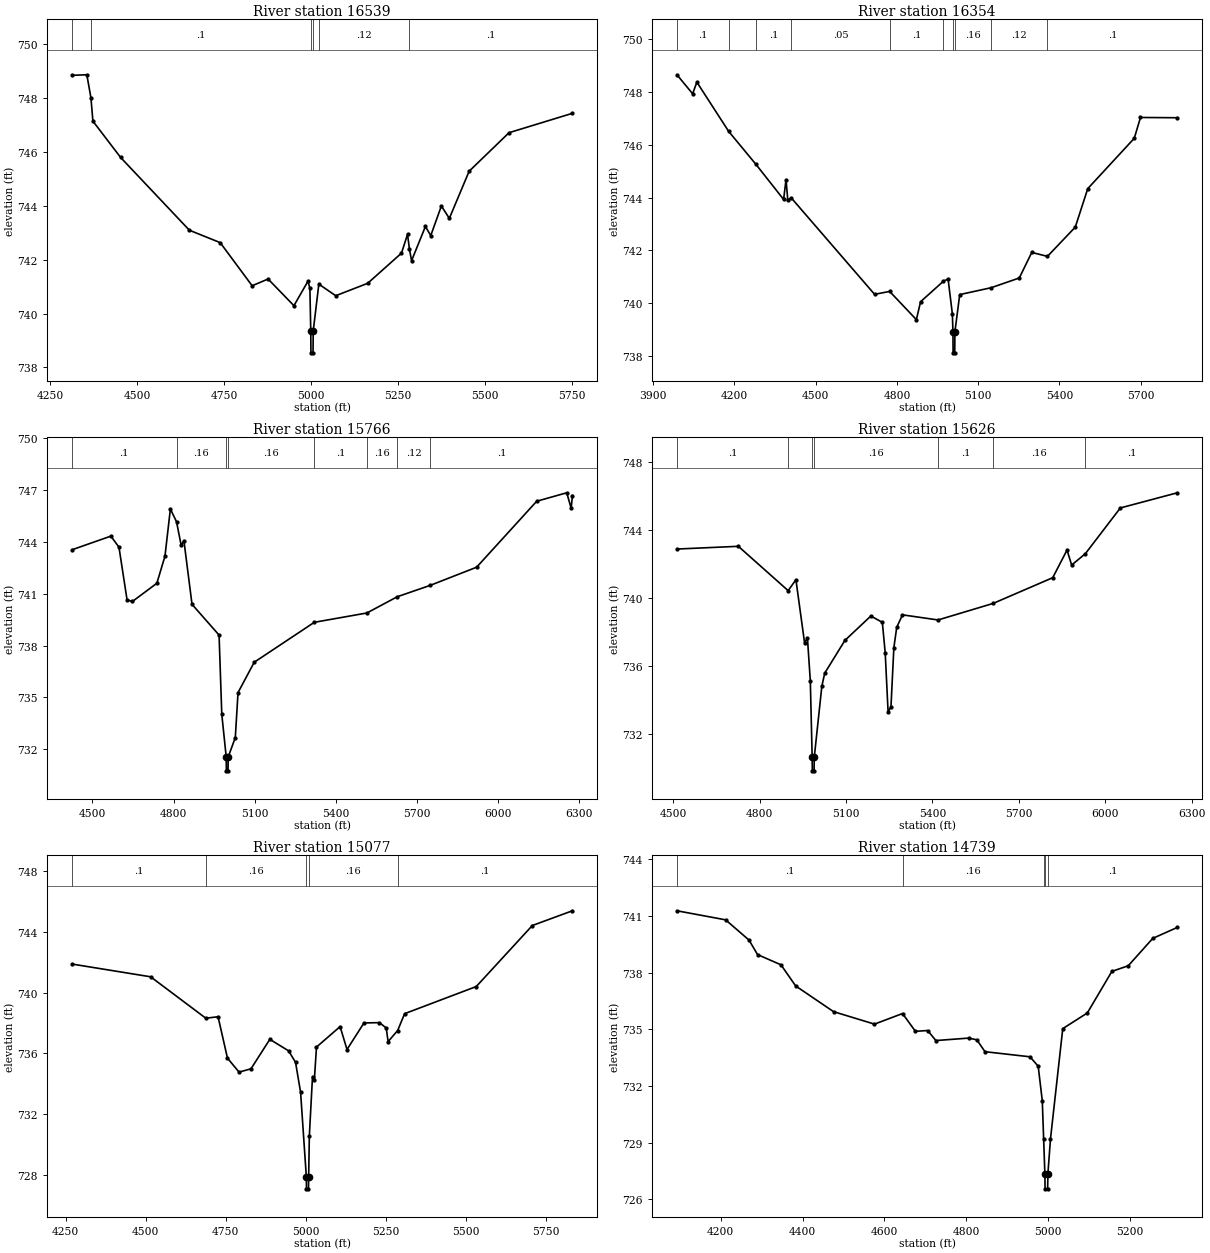
Type RM Length L Ch R = 1 ,16539   ,185,185,185
BEGIN DESCRIPTION:
Mapping XS 7802aeea
END DESCRIPTION:
XS GIS Cut Line= 2
      2002066.59     13628121.54      2001463.29     13626815.11
#Sta/Elev= 30
  4312.2  748.84  4354.9  748.86  4366.7     748  4372.3  747.14  4452.1  745.79
  4649.8  743.09  4738.4  742.63  4830.2  741.03  4876.1  741.28  4950.4  740.29
  4990.8   741.2  4996.3  740.93  4998.8  739.34  4999.3  738.54  5005.3  738.54
  5005.8  739.34    5022  741.09  5070.6  740.66  5162.4  741.12  5259.7  742.24
  5277.1  742.94  5282.3  742.41  5288.7  741.96  5328.5  743.23  5343.8  742.89
  5374.4  743.99  5397.3  743.53  5454.2  745.28  5568.9  746.71  5751.2  747.43
#Mann= 6 ,-1 , 0
  4312.2     .05       0  4366.7      .1       0  4998.8     .07       0
  5005.8      .1       0    5022     .12       0  5282.3      .1       0
Bank Sta=4998.8,5005.8
XS Rating Curve= 0 ,0
Exp/Cntr=0.3,0.1

Type RM Length L Ch R = 1 ,16354   ,588,588,588
BEGIN DESCRIPTION:
Mapping XS dfe07b01
END DESCRIPTION:
XS GIS Cut Line= 4
      2002821.77     13627978.27      2001827.87     13627392.34
      2001749.74     13627370.64      2001493.65     13626815.06
#Sta/Elev= 30
  3988.4  748.66  4046.3  747.94  4061.9  748.38  4179.4  746.51  4279.2  745.27
    4382  743.93  4390.9  744.68  4397.6  743.89  4410.1  743.99  4717.7  740.33
  4773.3  740.44  4871.9  739.37  4887.5  740.05    4972  740.83    4989  740.91
  5004.7  739.59  5006.9  738.91  5007.4  738.11  5013.5  738.11  5014.1  738.91
  5031.9  740.32  5147.6  740.58  5251.7  740.95  5297.7  741.92  5355.6  741.77
  5458.3  742.88  5504.3  744.34    5676  746.25  5698.9  747.04    5835  747.03
#Mann= 10 ,-1 , 0
  3988.4      .1       0  4179.4     .16       0  4279.2      .1       0
  4410.1     .05       0  4773.3      .1       0    4972     .16       0
  5006.9     .07       0  5014.1     .16       0  5147.6     .12       0
  5355.6      .1       0
Bank Sta=5006.9,5014.1
XS Rating Curve= 0 ,0
Exp/Cntr=0.3,0.1

Type RM Length L Ch R = 1 ,15766   ,140,140,140
BEGIN DESCRIPTION:
Mapping XS 92a2162f
END DESCRIPTION:
XS GIS Cut Line= 3
      2003058.61     13627336.19      2001797.48     13627327.24
      2001529.19     13626803.64
#Sta/Elev= 30
  4424.6  743.55  4568.2  744.34  4598.2   743.7  4628.2  740.64  4648.2  740.56
  4738.2  741.61  4768.2  743.18  4788.2  745.91    4811  745.17  4828.2   743.8
  4838.2  744.08  4868.2  740.39  4968.2  738.61  4978.2  734.02  4994.6  731.55
  4995.1  730.75  5001.3  730.75  5001.9  731.55  5028.2  732.68  5038.2  735.28
  5098.2  737.04  5320.2  739.35  5514.5  739.89  5626.7  740.83  5748.7  741.49
    5920  742.54  6142.1  746.36  6253.1  746.85  6269.6  745.95  6274.1  746.69
#Mann= 8 ,-1 , 0
  4424.6      .1       0    4811     .16       0  4994.6     .07       0
  5001.9     .16       0  5320.2      .1       0  5514.5     .16       0
  5626.7     .12       0  5748.7      .1       0
Bank Sta=4994.6,5001.9
XS Rating Curve= 0 ,0
Exp/Cntr=0.3,0.1

Type RM Length L Ch R = 1 ,15626   ,549,549,549
BEGIN DESCRIPTION:
Mapping XS 2ff17d0c
END DESCRIPTION:
XS GIS Cut Line= 4
       2003048.2     13627228.55      2002717.62     13627223.07
      2001819.18     13627231.75      2001576.15     13626784.75
#Sta/Elev= 30
  4512.5  742.87  4725.7  743.03  4898.7  740.43  4925.7  741.07  4955.7  737.37
  4965.7  737.65  4975.7  735.13  4982.1  730.66  4982.6  729.86  4988.8  729.86
  4989.4  730.66  5015.7  734.82  5025.7  735.59  5095.8  737.51  5185.8  738.94
  5225.8  738.57  5235.8  736.78  5245.8  733.31  5255.8  733.62  5265.8  737.08
  5275.8  738.28  5295.8  739.01  5419.2  738.71  5610.6  739.68  5817.6  741.19
  5867.2  742.81  5883.3  741.93    5931   742.6  6052.4  745.28  6250.4  746.17
#Mann= 7 ,-1 , 0
  4512.5      .1       0  4898.7     .16       0  4982.1     .07       0
  4989.4     .16       0  5419.2      .1       0  5610.6     .16       0
    5931      .1       0
Bank Sta=4982.1,4989.4
XS Rating Curve= 0 ,0
Exp/Cntr=0.3,0.1

Type RM Length L Ch R = 1 ,15077   ,338,338,338
BEGIN DESCRIPTION:
Mapping XS b3f0f70f
END DESCRIPTION:
XS GIS Cut Line= 4
      2003049.95     13626936.88      2002561.37     13626906.23
      2002188.11     13627123.25      2001649.98     13626776.07
#Sta/Elev= 30
  4269.9  741.89  4515.3  741.05  4687.6  738.32  4725.7  738.42  4755.1  735.69
  4791.3  734.77  4828.5  734.99  4887.3  736.93    4946  736.17  4967.6  735.41
  4983.3  733.44  5001.2  727.88  5001.7  727.08  5007.9  727.08  5008.5  727.88
  5010.6  730.57  5020.5  734.48  5026.3  734.28  5032.9  736.42  5106.6  737.77
  5128.1  736.26  5181.1  738.01  5229.4  738.03  5250.5  737.68  5256.4  736.78
  5286.2  737.51  5307.9  738.62  5531.6  740.41  5706.6  744.43  5831.6   745.4
#Mann= 5 ,-1 , 0
  4269.9      .1       0  4687.6     .16       0  5001.2     .07       0
  5008.5     .16       0  5286.2      .1       0
Bank Sta=5001.2,5008.5
XS Rating Curve= 0 ,0
Exp/Cntr=0.3,0.1

Type RM Length L Ch R = 1 ,14739   ,423,423,423
BEGIN DESCRIPTION:
Mapping XS 43e6b6d5
END DESCRIPTION:
XS GIS Cut Line= 3
      2003114.22     13626909.11       2002850.3     13626733.02
      2001945.01     13626723.94
#Sta/Elev= 30
  4093.2  741.27  4212.1  740.79  4269.2  739.72  4290.2  738.95  4347.3  738.41
  4383.3  737.29  4475.8  735.93  4575.8  735.27  4644.3  735.83  4675.8  734.89
  4705.8  734.93  4725.8   734.4  4805.8  734.53  4825.8  734.44  4845.8  733.81
  4955.8  733.54  4975.8  733.04  4985.8  731.21  4989.1  729.19  4992.1  727.35
  4992.6  726.55  4998.9  726.55  4999.5  727.35  5005.8  729.19  5035.8  735.03
  5095.8  735.86  5155.8  738.06  5195.8  738.36  5255.8  739.81  5315.8  740.39
#Mann= 5 ,-1 , 0
  4093.2      .1       0  4644.3     .16       0  4989.1      .1       0
  4992.1     .07       0  4999.5      .1       0
Bank Sta=4992.1,4999.5
XS Rating Curve= 0 ,0
Exp/Cntr=0.3,0.1

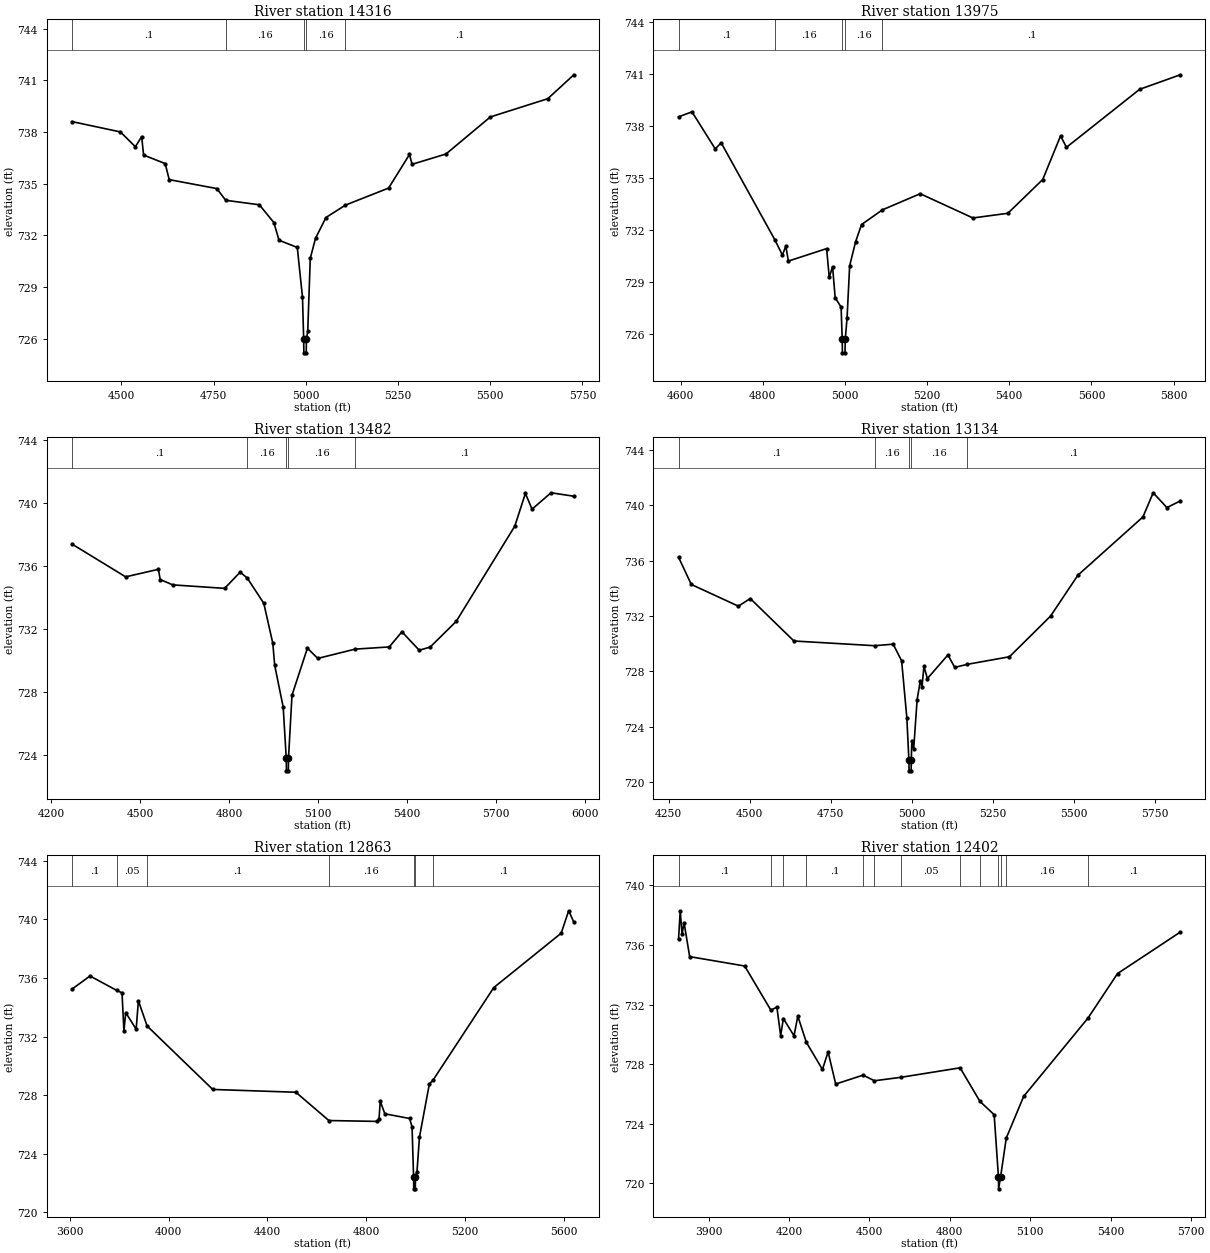
Type RM Length L Ch R = 1 ,14316   ,341,341,341
BEGIN DESCRIPTION:
Mapping XS aa49a68b
END DESCRIPTION:
XS GIS Cut Line= 3
      2003164.65      13626697.9      2002665.54     13626624.11
      2002050.56     13626029.46
#Sta/Elev= 30
  4366.6  738.61  4497.7  738.01  4538.1  737.15  4555.3  737.74  4560.4  736.67
    4619  736.17  4629.9  735.24    4759  734.72  4782.9  734.04  4874.1  733.78
  4913.4  732.75  4927.5  731.72    4977   731.3  4991.1  728.41  4994.3  725.98
  4994.9  725.18  5001.2  725.18  5001.8  725.98  5005.3  726.42  5012.2  730.67
  5026.4  731.83  5054.7  733.04  5107.5  733.76  5224.5  734.75  5281.1   736.7
  5288.2  736.13  5380.1  736.73  5500.2  738.88  5655.9  739.94  5726.6  741.33
#Mann= 5 ,-1 , 0
  4366.6      .1       0  4782.9     .16       0  4994.3     .07       0
  5001.8     .16       0  5107.5      .1       0
Bank Sta=4994.3,5001.8
XS Rating Curve= 0 ,0
Exp/Cntr=0.3,0.1

Type RM Length L Ch R = 1 ,13975   ,493,493,493
BEGIN DESCRIPTION:
Mapping XS 0ac6d1b7
END DESCRIPTION:
XS GIS Cut Line= 2
      2003190.69     13626684.86      2002230.61       13625930.
#Sta/Elev= 30
    4595  738.54  4627.7  738.83  4684.3  736.69  4698.8  737.04  4830.1  731.41
  4847.9  730.55    4856  731.08  4862.4  730.21  4955.4  730.93  4961.8  729.27
  4969.9  729.89  4976.2   728.1  4990.7  727.55  4993.3  725.71  4993.9  724.91
  5000.2  724.91  5000.8  725.71  5005.1   726.9  5011.5  729.94    5026  731.33
  5040.4  732.32  5091.3  733.17  5183.2   734.1  5311.5   732.7  5396.5  732.97
  5481.4  734.92  5524.8  737.44  5539.2  736.78  5717.3  740.13  5816.3  740.97
#Mann= 5 ,-1 , 0
    4595      .1       0  4830.1     .16       0  4993.3     .07       0
  5000.8     .16       0  5091.3      .1       0
Bank Sta=4993.3,5000.8
XS Rating Curve= 0 ,0
Exp/Cntr=0.3,0.1

Type RM Length L Ch R = 1 ,13482   ,348,348,348
BEGIN DESCRIPTION:
Mapping XS 2c634433
END DESCRIPTION:
XS GIS Cut Line= 2
      2003855.11       13626673.      2002404.92     13625799.77
#Sta/Elev= 30
  4269.4  737.39  4450.1  735.31  4560.8  735.79  4566.6  735.14  4609.3   734.8
  4784.1  734.58  4836.5  735.61  4860.6  735.23  4916.2  733.63  4946.6  731.09
    4953  729.69  4981.6  727.04    4992  723.79  4992.6  722.99    4999  722.99
  4999.5  723.79  5011.3  727.79  5063.3  730.78  5098.3  730.13  5224.2  730.72
  5339.5  730.86  5382.2  731.82  5440.5  730.65  5477.4  730.85  5565.2  732.48
  5762.9  738.53  5798.7  740.61  5821.1  739.61  5885.2  740.65  5962.2  740.43
#Mann= 5 ,-1 , 0
  4269.4      .1       0  4860.6     .16       0    4992     .07       0
  4999.5     .16       0  5224.2      .1       0
Bank Sta=4992,4999.5
XS Rating Curve= 0 ,0
Exp/Cntr=0.3,0.1

Type RM Length L Ch R = 1 ,13134   ,271,271,271
BEGIN DESCRIPTION:
Mapping XS 860df112
END DESCRIPTION:
XS GIS Cut Line= 2
      2003992.26     13626219.87      2002525.68     13625725.08
#Sta/Elev= 30
  4280.8  736.26  4320.1  734.29  4465.3  732.72  4502.1  733.27  4636.7   730.2
  4885.7  729.86  4942.8  729.97  4968.9  728.77    4985  724.65  4991.3  721.61
  4991.9  720.81  4998.3  720.81  4998.8  721.61  5000.4     723  5006.1  722.37
  5016.7  725.95  5026.6  727.33  5031.8  726.87  5037.8  728.38  5048.3  727.48
  5111.7  729.19  5132.8  728.29  5170.6  728.51  5301.6  729.06  5428.3     732
  5512.7  734.96  5713.2  739.17  5744.9  740.92  5787.2  739.85  5828.6  740.33
#Mann= 5 ,-1 , 0
  4280.8      .1       0  4885.7     .16       0  4991.3     .07       0
  4998.8     .16       0  5170.6      .1       0
Bank Sta=4991.3,4998.8
XS Rating Curve= 0 ,0
Exp/Cntr=0.3,0.1

Type RM Length L Ch R = 1 ,12863   ,461,461,461
BEGIN DESCRIPTION:
Mapping XS 39dc048e
END DESCRIPTION:
XS GIS Cut Line= 4
      2004540.27     13626110.35      2004032.91     13625775.77
      2002991.03     13625733.53      2002614.25     13625678.21
#Sta/Elev= 30
  3609.5  735.24  3682.2  736.13    3790  735.15  3811.7  734.98  3819.4  732.39
  3826.8  733.63  3868.9   732.5    3878  734.44  3913.3  732.72    4179  728.39
  4515.4   728.2  4649.1  726.27  4845.7  726.21  4852.1   726.4  4857.1  727.58
  4875.7  726.73  4975.8  726.41  4985.8  725.84    4992  722.41  4992.6  721.61
    4999  721.61  4999.6  722.41  5005.8  722.79  5015.8  725.14  5055.8  728.76
  5070.5  729.02  5316.6  735.34  5589.5  739.05  5619.8  740.58  5640.8   739.8
#Mann= 7 ,-1 , 0
  3609.5      .1       0    3790     .05       0  3913.3      .1       0
  4649.1     .16       0    4992     .07       0  4999.6     .16       0
  5070.5      .1       0
Bank Sta=4992,4999.6
XS Rating Curve= 0 ,0
Exp/Cntr=0.3,0.1

Type RM Length L Ch R = 1 ,12402   ,104,104,104
BEGIN DESCRIPTION:
Mapping XS a13a4222
END DESCRIPTION:
XS GIS Cut Line= 3
      2004640.89     13626047.79      2004127.03     13625565.09
      2002960.65     13625565.09
#Sta/Elev= 30
  3788.2  736.39  3794.5   738.3  3801.4  736.72  3808.7  737.51  3829.7  735.22
  4034.8  734.59  4132.3  731.63    4155  731.82  4169.1  729.91  4179.1  731.06
  4218.9   729.9  4233.1  731.22  4264.7  729.47  4324.9  727.64    4346  728.82
  4374.3  726.66  4476.8  727.26  4518.5  726.88  4616.9  727.11  4838.3  727.75
  4912.1   725.5  4965.3   724.6  4981.3  720.42    4982  719.62  4989.2  720.42
  5010.5  723.03  5075.3  725.83  5315.6   731.1  5425.3  734.08  5659.6  736.87
#Mann= 13 ,-1 , 0
  3788.2      .1       0  4132.3     .05       0  4179.1     .08       0
  4264.7      .1       0  4476.8     .05       0  4518.5     .08       0
  4616.9     .05       0  4838.3     .16       0  4912.1      .1       0
  4981.3     .07       0  4989.2      .1       0  5010.5     .16       0
  5315.6      .1       0
Bank Sta=4981.3,4989.2
XS Rating Curve= 0 ,0
Exp/Cntr=0.3,0.1

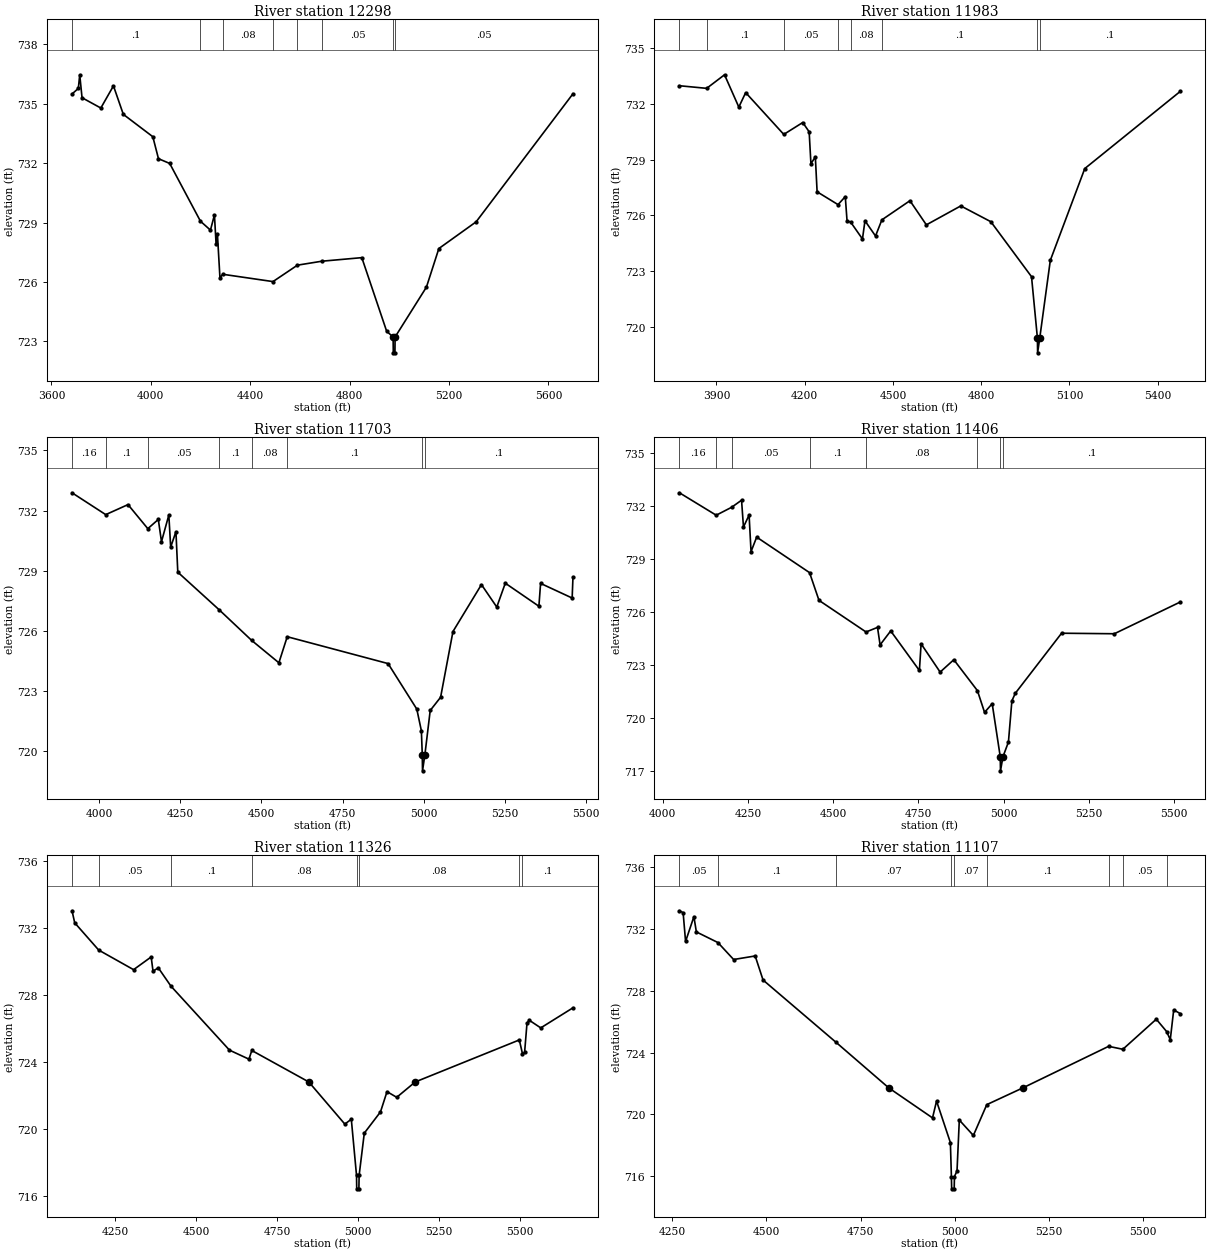
Type RM Length L Ch R = 1 ,12298   ,315,315,315
BEGIN DESCRIPTION:
Mapping XS c062f7f2
END DESCRIPTION:
XS GIS Cut Line= 3
      2004661.77     13626051.33      2004394.39     13625495.74
       2002995.4     13625486.96
#Sta/Elev= 30
    3683   735.5  3708.4  735.78    3714  736.47  3723.3  735.31  3798.9  734.79
  3849.7  735.91  3889.4  734.47  4008.1  733.34  4030.8  732.23    4076  731.99
  4199.8  729.07    4240  728.62    4256  729.39  4262.6  727.93  4268.1   728.4
  4278.2  726.21  4289.4  726.39  4491.6  726.02    4590  726.85  4688.4  727.05
    4849  727.23    4949  723.51    4975  723.22  4975.7  722.42  4982.3  722.42
  4982.9  723.22    5109  725.74    5159  727.69    5309  729.04  5698.6  735.51
#Mann= 8 ,-1 , 0
    3683      .1       0  4199.8     .05       0  4289.4     .08       0
  4491.6     .05       0    4590     .08       0  4688.4     .05       0
    4975     .04       0  4982.9     .05       0
Bank Sta=4975,4982.9
XS Rating Curve= 0 ,0
Exp/Cntr=0.3,0.1

Type RM Length L Ch R = 1 ,11983   ,280,280,280
BEGIN DESCRIPTION:
Mapping XS 77bc92c3
END DESCRIPTION:
XS GIS Cut Line= 3
       2004882.2     13625789.12      2004380.09     13625449.49
       2003349.6     13625074.17
#Sta/Elev= 30
  3774.2  732.98  3866.8  732.84  3927.5  733.57  3976.1  731.83  3999.4  732.61
  4128.9  730.36  4193.4     731  4215.2   730.5  4221.2  728.78  4236.2  729.15
  4242.2  727.27  4313.3  726.58    4338  727.01    4344   725.7  4356.2  725.64
  4396.4  724.73  4404.9  725.71  4440.8  724.89  4462.4  725.76  4557.8  726.79
  4613.6  725.49  4730.6  726.51  4832.8  725.66  4971.1   722.7  4991.1   719.4
  4991.8   718.6  4999.1   719.4    5035  723.58  5152.1  728.52  5477.1  732.68
#Mann= 8 ,-1 , 0
  3774.2     .16       0  3866.8      .1       0  4128.9     .05       0
  4313.3      .1       0  4356.2     .08       0  4462.4      .1       0
  4991.1     .07       0  4999.1      .1       0
Bank Sta=4991.1,4999.1
XS Rating Curve= 0 ,0
Exp/Cntr=0.3,0.1

Type RM Length L Ch R = 1 ,11703   ,297,297,297
BEGIN DESCRIPTION:
Mapping XS d4cf4896
END DESCRIPTION:
XS GIS Cut Line= 4
      2004887.48     13625704.09      2004323.53     13625400.16
      2004076.13     13625269.95      2003889.75     13624676.13
#Sta/Elev= 30
  3916.9  732.89  4020.7   731.8  4089.3   732.3  4150.3   731.1  4182.6  731.56
  4192.4  730.45    4215  731.78  4220.7  730.18  4236.9  730.95  4242.6  728.93
  4370.9  727.04  4469.8  725.53  4553.9  724.41  4579.6  725.71  4890.2  724.37
  4978.6   722.1  4992.7  721.02  4995.5  719.82  4996.2  719.02  5003.5  719.82
  5019.9  722.03  5051.9  722.69    5090  725.97  5177.7  728.31  5224.9  727.19
  5251.1  728.38  5354.6  727.23  5359.8  728.37    5457  727.64  5459.5  728.67
#Mann= 8 ,-1 , 0
  3916.9     .16       0  4020.7      .1       0  4150.3     .05       0
  4370.9      .1       0  4469.8     .08       0  4579.6      .1       0
  4995.5     .07       0  5003.5      .1       0
Bank Sta=4995.5,5003.5
XS Rating Curve= 0 ,0
Exp/Cntr=0.3,0.1

Type RM Length L Ch R = 1 ,11406   ,80,80,80
BEGIN DESCRIPTION:
Mapping XS 4ea5c1d3
END DESCRIPTION:
XS GIS Cut Line= 4
      2004887.46     13625665.88      2004323.53     13625374.11
       2004288.8     13624657.97      2004184.63     13624605.88
#Sta/Elev= 30
  4049.3  732.74  4157.1  731.47  4202.4  731.92  4231.4  732.32    4237   730.8
  4253.5  731.48  4259.2  729.41  4275.7  730.23  4430.7  728.22  4458.4  726.65
  4596.3  724.86  4629.9  725.12  4637.5  724.13  4668.6  724.92  4752.7  722.68
  4757.7  724.19  4813.5  722.59  4853.6  723.29  4922.8  721.54  4943.7  720.31
  4966.1   720.8  4989.7   717.8  4990.4     717  4997.7   717.8  5013.7  718.63
  5023.8  720.96  5033.8  721.39  5169.5  724.79  5324.1  724.76  5517.7  726.56
#Mann= 8 ,-1 , 0
  4049.3     .16       0  4157.1      .1       0  4202.4     .05       0
  4430.7      .1       0  4596.3     .08       0  4922.8      .1       0
  4989.7     .07       0  4997.7      .1       0
Bank Sta=4989.7,4997.7
XS Rating Curve= 0 ,0
Exp/Cntr=0.3,0.1

Type RM Length L Ch R = 1 ,11326   ,219,219,219
BEGIN DESCRIPTION:
Mapping XS c23417b5
END DESCRIPTION:
XS GIS Cut Line= 4
      2004892.69     13625636.38      2004375.61     13625361.09
      2004405.99     13624662.31        2004215.     13624484.34
#Sta/Elev= 30
  4117.3  733.04  4125.6  732.32  4199.7  730.69  4307.3  729.52  4361.6  730.28
  4367.3  729.43  4383.6  729.63  4422.5  728.54  4603.3  724.71  4663.5  724.17
  4672.2  724.69 4848.24 722.808  4959.4  720.29  4979.4  720.58  4995.5  717.22
  4996.1  716.42  5002.8  716.42  5003.5  717.22  5019.5  719.75  5069.5  721.02
  5089.6  722.23  5119.6  721.89 5176.64722.8078    5498  725.32  5507.7   724.5
  5514.3  724.57  5521.7  726.32  5528.5   726.5  5564.2  726.04  5663.6  727.24
#Mann= 8 ,-1 , 0
  4117.3     .16       0  4199.7     .05       0  4422.5      .1       0
  4672.2     .08       0  4995.5     .07       0  5003.5     .08       0
    5498     .05       0  5507.7      .1       0
Bank Sta=4848.24,5176.64
XS Rating Curve= 0 ,0
Exp/Cntr=0.3,0.1

Type RM Length L Ch R = 1 ,11107   ,318,318,318
BEGIN DESCRIPTION:
Mapping XS b884be64
END DESCRIPTION:
XS GIS Cut Line= 4
      2005024.63     13625568.68      2004709.07     13625304.32
      2004395.02     13624560.95      2004299.76     13624504.65
#Sta/Elev= 30
  4269.3  733.19  4279.1  733.07  4285.6   731.2  4307.7  732.81  4314.2  731.82
  4371.4  731.13  4413.1  730.03  4470.3  730.26  4491.2   728.7  4684.9  724.66
 4824.72721.7077  4940.9  719.76  4951.6  720.85  4988.3  718.16    4991  715.96
  4991.7  715.16  4998.4  715.16  4999.1  715.96  5005.9  716.32    5012  719.62
  5049.3  718.62  5084.9  720.62 5180.78721.7077  5408.2   724.4    5446  724.21
  5534.7  726.16  5562.1  725.36  5571.8  724.83  5580.9  726.76  5598.6  726.52
#Mann= 9 ,-1 , 0
  4269.3     .05       0  4371.4      .1       0  4684.9     .07       0
    4991     .07       0  4999.1     .07       0  5084.9      .1       0
  5408.2     .08       0    5446     .05       0  5562.1      .1       0
Bank Sta=4824.72,5180.78
XS Rating Curve= 0 ,0
Exp/Cntr=0.3,0.1