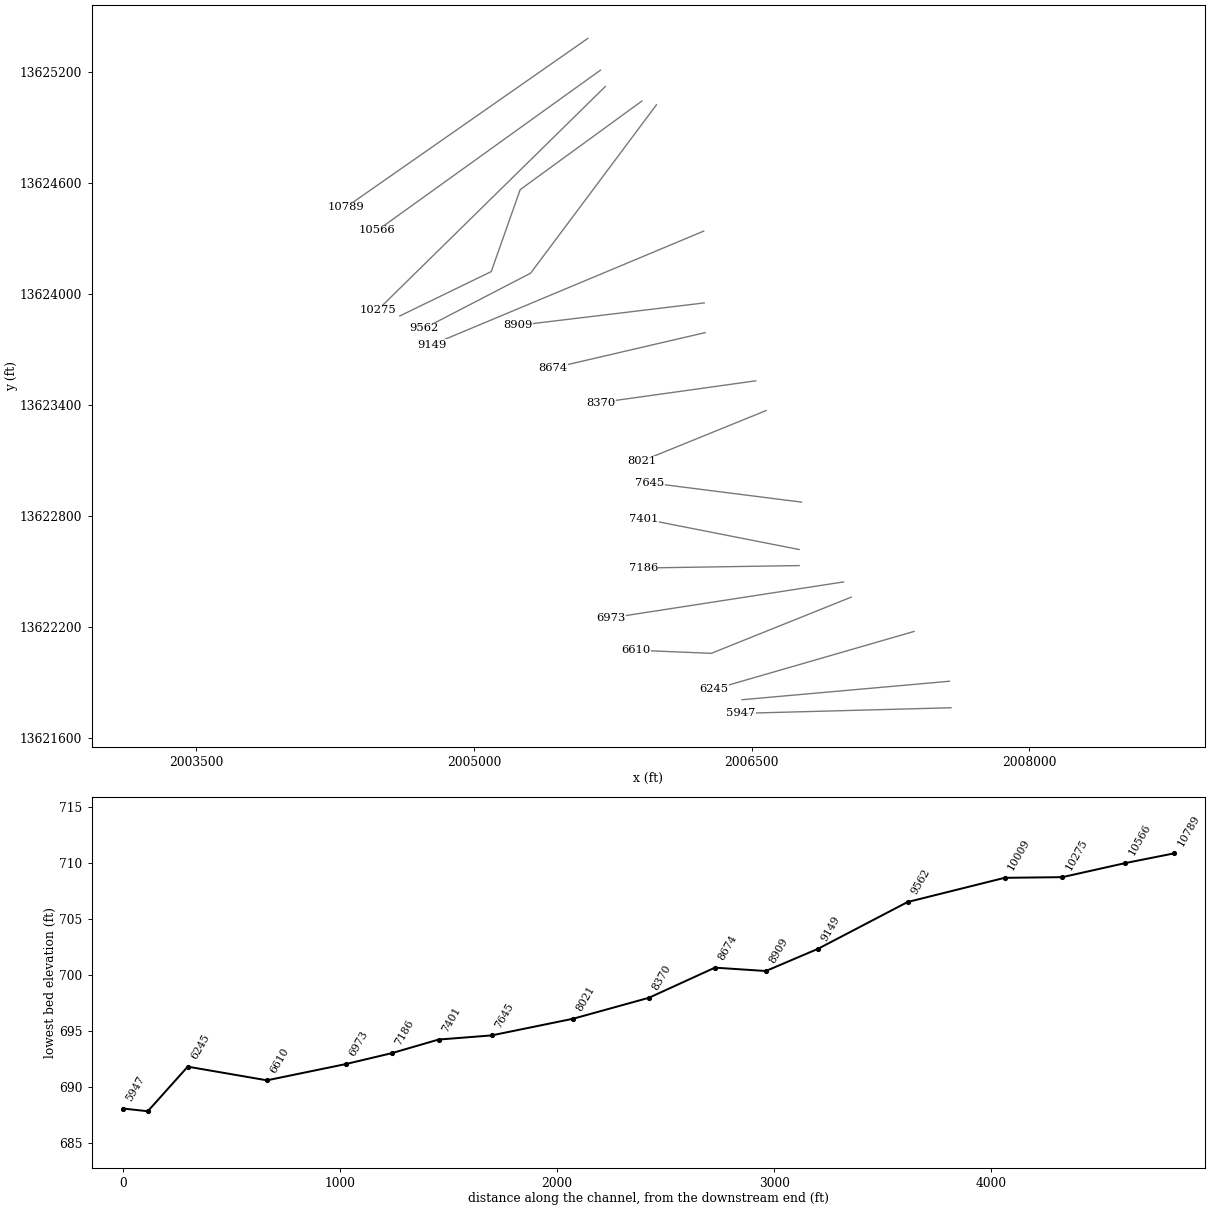
HEC-RAS study UNT 098 in HW.prj: UNT 098 in HW Base Level Engineering

--- UNT 098 in HW.g01 (geometry) --- (continued)

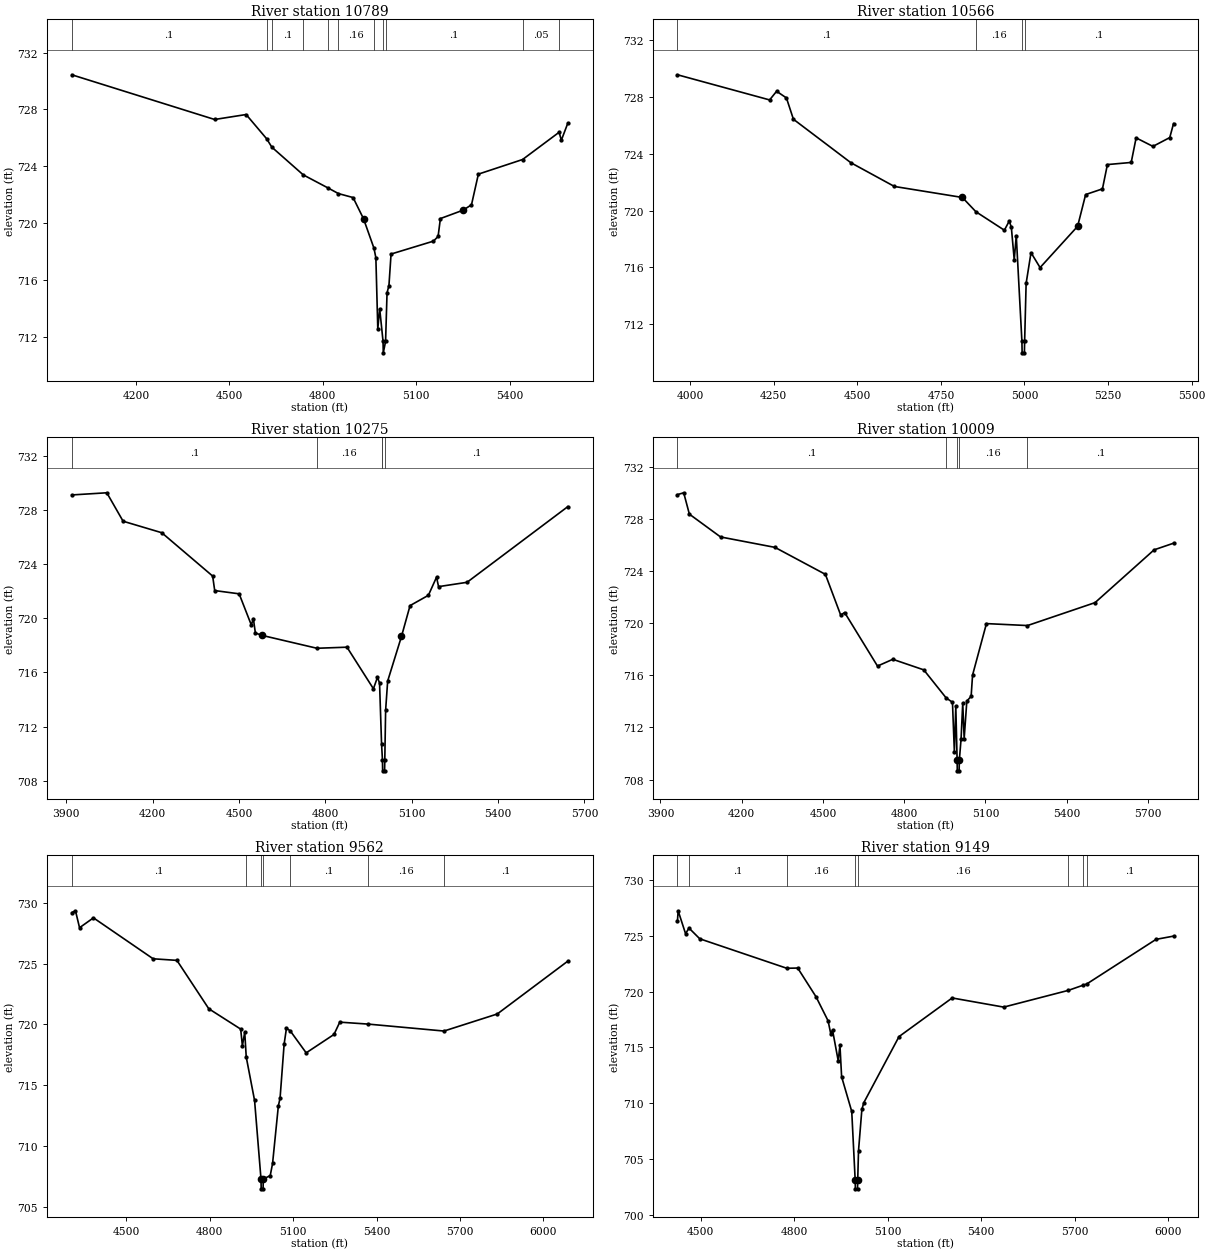
Type RM Length L Ch R = 1 ,10789   ,223,223,223
BEGIN DESCRIPTION:
Mapping XS 84b33884
END DESCRIPTION:
XS GIS Cut Line= 2
      2005615.96     13625382.92      2004309.27     13624470.53
#Sta/Elev= 30
  3993.6  730.44  4452.5  727.29  4553.7  727.64  4619.7  725.93  4636.3  725.34
  4737.1  723.39  4816.5  722.47  4850.3  722.07  4897.3  721.79 4930.94720.2919
  4964.4  718.22  4970.5  717.55  4976.7  712.55  4982.8  713.95  4993.6  711.65
  4994.3  710.85  5001.7  711.65  5006.4  715.08  5012.5  715.59  5019.3  717.81
  5155.5  718.72  5170.4  719.05  5177.8  720.31 5250.72720.9006  5277.7  721.28
  5299.8  723.44  5441.8  724.47  5559.2  726.39  5566.4  725.83  5587.3  727.04
#Mann= 11 ,-1 , 0
  3993.6      .1       0  4619.7     .07       0  4636.3      .1       0
  4737.1     .07       0  4816.5      .1       0  4850.3     .16       0
  4964.4      .1       0  4993.6     .07       0  5001.7      .1       0
  5441.8     .05       0  5559.2      .1       0
Bank Sta=4930.94,5250.72
XS Rating Curve= 0 ,0
Exp/Cntr=0.3,0.1

Type RM Length L Ch R = 1 ,10566   ,291,291,291
BEGIN DESCRIPTION:
Mapping XS cab0d497
END DESCRIPTION:
XS GIS Cut Line= 2
      2005683.61     13625211.01      2004478.75     13624344.84
#Sta/Elev= 30
    3962  729.56  4237.6  727.79  4258.5   728.4  4287.9  727.93  4308.8  726.43
  4480.7  723.37  4610.8   721.7 4814.23720.9253  4854.7  719.92  4939.8  718.62
  4954.5  719.27  4960.7  718.82  4969.3  716.54  4975.4  718.24  4992.3  710.79
  4992.9  709.99  4999.7  709.99  5000.4  710.79  5004.9  714.88  5019.5  717.04
  5046.6  715.99 5158.89718.8939  5182.9  721.13  5233.2  721.53    5248  723.24
  5319.2  723.39  5333.9  725.12  5384.2  724.52  5434.5  725.14  5445.9  726.13
#Mann= 4 ,-1 , 0
    3962      .1       0  4854.7     .16       0  4992.3     .07       0
  5000.4      .1       0
Bank Sta=4814.23,5158.89
XS Rating Curve= 0 ,0
Exp/Cntr=0.3,0.1

Type RM Length L Ch R = 1 ,10275   ,266,266,266
BEGIN DESCRIPTION:
Mapping XS c060da9f
END DESCRIPTION:
XS GIS Cut Line= 2
       2005709.7      13625122.5      2004480.48     13623914.12
#Sta/Elev= 30
  3918.8   729.1  4040.5  729.26  4097.1  727.16  4231.5  726.31  4408.3  723.11
  4415.4  722.04  4500.3   721.8  4542.6   719.5  4549.7  719.97  4556.7  718.91
 4579.13718.7345  4770.6  717.78    4875  717.86  4966.9  714.79    4981  715.64
  4988.2  715.21  4995.2   710.7  4998.3  709.53  4998.9  708.73  5005.7  708.73
  5006.4  709.53  5009.3  713.21  5016.4  715.36 5064.38718.6528  5094.2  720.93
  5157.9  721.69  5186.2  723.03  5193.2  722.33  5292.2  722.65  5642.5  728.24
#Mann= 5 ,-1 , 0
  3918.8      .1       0  4770.6     .16       0  4995.2      .1       0
  4998.3     .07       0  5006.4      .1       0
Bank Sta=4579.13,5064.38
XS Rating Curve= 0 ,0
Exp/Cntr=0.3,0.1

Type RM Length L Ch R = 1 ,10009   ,447,447,447
BEGIN DESCRIPTION:
Mapping XS 1ea50aac
END DESCRIPTION:
XS GIS Cut Line= 4
      2005907.56     13625044.33      2005250.06     13624565.29
      2005093.81     13624122.58      2004600.31      13623882.9
#Sta/Elev= 30
    3963  729.87    3986  730.01  4006.9  728.37    4122  726.62  4322.9  725.82
  4509.1  723.75  4565.5  720.63  4580.2  720.82  4701.5  716.71    4758  717.23
  4872.3  716.42  4954.8  714.27  4978.3  713.93  4985.3  710.13  4990.6  713.61
  4995.5  709.47  4996.1  708.67  5002.9  708.67  5003.6  709.47  5010.1  711.13
  5016.2  713.87  5021.5  711.15  5031.3  714.02  5047.2  714.39  5052.5  716.02
  5103.7  719.97  5255.3  719.82  5504.8  721.58  5722.7  725.63  5794.6  726.14
#Mann= 5 ,-1 , 0
    3963      .1       0  4954.8     .16       0  4995.5     .07       0
  5003.6     .16       0  5255.3      .1       0
Bank Sta=4995.5,5003.6
XS Rating Curve= 0 ,0
Exp/Cntr=0.3,0.1

Type RM Length L Ch R = 1 ,9562    ,413,413,413
BEGIN DESCRIPTION:
Mapping XS 79ed1cd5
END DESCRIPTION:
XS GIS Cut Line= 3
      2005985.74     13625023.56      2005306.48      13624113.9
      2004730.52     13623815.19
#Sta/Elev= 30
  4304.1  729.18  4317.4  729.33    4332  727.94    4382  728.75  4596.7  725.39
  4682.2  725.26  4796.8  721.29  4911.5  719.62  4917.7  718.25  4926.1  719.37
  4931.5  717.33  4961.5  713.76  4984.6  707.31  4985.3  706.51  4992.1  706.51
  4992.8  707.31  5017.8   707.6  5026.2  708.59    5047  713.31  5053.2  713.96
  5067.8  718.39  5076.1  719.68  5089.3  719.49  5147.1  717.67  5247.1  719.18
  5267.9  720.19  5370.1  720.03  5642.7  719.46  5834.3  720.86  6088.2   725.2
#Mann= 7 ,-1 , 0
  4304.1      .1       0  4931.5     .16       0  4984.6     .07       0
  4992.8     .16       0  5089.3      .1       0  5370.1     .16       0
  5642.7      .1       0
Bank Sta=4984.6,4992.8
XS Rating Curve= 0 ,0
Exp/Cntr=0.3,0.1

Type RM Length L Ch R = 1 ,9149    ,240,240,240
BEGIN DESCRIPTION:
Mapping XS 41e62bc6
END DESCRIPTION:
XS GIS Cut Line= 2
      2006240.96     13624341.24      2004772.16     13623726.64
#Sta/Elev= 30
  4425.3  726.36  4427.4  727.24  4451.2  725.19  4462.3  725.69  4496.8  724.73
  4776.1  722.09  4811.2  722.11  4869.9  719.54  4908.7  717.38  4917.4   716.2
  4922.9  716.56  4941.2   713.8  4946.7   715.2  4952.1  712.37  4984.6  709.26
  4995.6  703.13  4996.3  702.33  5003.1  702.33  5003.8  703.13  5006.3  705.73
  5017.1  709.44  5023.5  710.06  5136.4  715.97  5306.9  719.43  5472.4  718.61
  5679.9  720.11  5727.9  720.58  5738.7  720.68  5961.3  724.68  6017.5  724.97
#Mann= 8 ,-1 , 0
  4425.3     .05       0  4462.3      .1       0  4776.1     .16       0
  4995.6     .07       0  5003.8     .16       0  5679.9      .1       0
  5727.9     .16       0  5738.7      .1       0
Bank Sta=4995.6,5003.8
XS Rating Curve= 0 ,0
Exp/Cntr=0.3,0.1

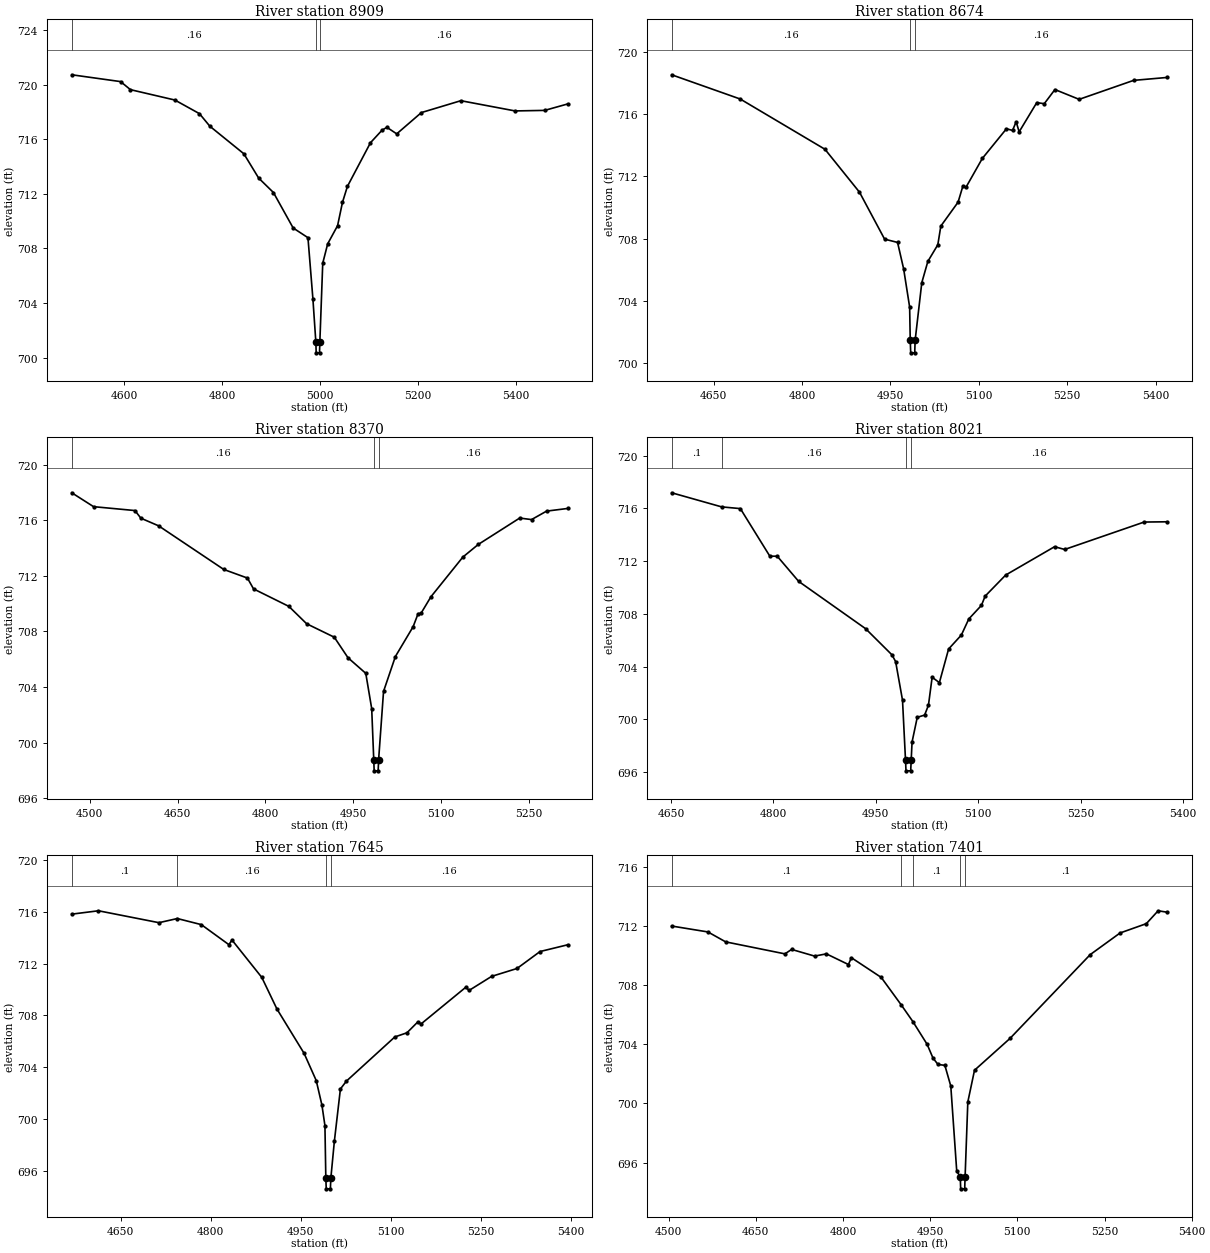
Type RM Length L Ch R = 1 ,8909    ,235,235,235
BEGIN DESCRIPTION:
Mapping XS 68f00360
END DESCRIPTION:
XS GIS Cut Line= 2
      2006243.95      13623953.3      2005238.54     13623831.96
#Sta/Elev= 30
  4493.2  720.73  4592.9  720.23    4613  719.64  4703.7  718.88    4754  717.88
  4775.2  716.96  4844.7  714.94  4874.9  713.16  4905.1   712.1  4945.4   709.5
  4975.6  708.79  4985.7  704.31  4991.7  701.15  4992.4  700.35  4999.2  700.35
  4999.9  701.15  5005.8  706.92  5015.9  708.34  5036.1  709.67  5046.1  711.38
  5056.2  712.55  5103.3  715.75  5126.7  716.66  5136.8  716.88  5156.9   716.4
  5207.3  717.96  5287.9  718.83  5398.7  718.08  5459.1  718.12  5505.9  718.59
#Mann= 3 ,-1 , 0
  4493.2     .16       0  4991.7     .07       0  4999.9     .16       0
Bank Sta=4991.7,4999.9
XS Rating Curve= 0 ,0
Exp/Cntr=0.3,0.1

Type RM Length L Ch R = 1 ,8674    ,304,304,304
BEGIN DESCRIPTION:
Mapping XS 79f43241
END DESCRIPTION:
XS GIS Cut Line= 2
      2006248.35     13623792.72      2005428.96     13623601.97
#Sta/Elev= 30
  4578.8  718.53  4695.2  716.97  4838.9  713.74  4897.5  710.98  4940.1  707.96
  4962.1  707.75  4972.4  706.05  4982.6  703.59  4983.6  701.45  4984.4  700.65
  4991.2  700.65  4991.9  701.45  5003.2  705.16  5013.5  706.53  5030.4   707.6
  5035.5   708.8  5064.8  710.34  5072.9  711.37  5078.1  711.29  5105.9  713.15
  5146.9  715.06  5157.2  714.95  5163.3  715.51  5168.4  714.86  5198.3  716.74
    5211  716.67  5229.1  717.58  5270.2  716.95  5362.6  718.17  5420.1  718.36
#Mann= 3 ,-1 , 0
  4578.8     .16       0  4983.6     .07       0  4991.9     .16       0
Bank Sta=4983.6,4991.9
XS Rating Curve= 0 ,0
Exp/Cntr=0.3,0.1

Type RM Length L Ch R = 1 ,8370    ,349,349,349
BEGIN DESCRIPTION:
Mapping XS 4a921b0b
END DESCRIPTION:
XS GIS Cut Line= 2
       2006521.8     13623532.31      2005684.06     13623415.11
#Sta/Elev= 30
  4469.6  717.98  4506.8  716.98  4577.4   716.7  4587.5  716.15  4617.8   715.6
  4728.9  712.46  4769.3  711.84  4779.7  711.06    4840   709.8  4870.3  708.55
  4917.5  707.58  4940.9   706.1  4971.2  704.98  4981.3  702.44  4984.8  698.76
  4985.5  697.96  4992.3  697.96  4993.1  698.76  5001.5  703.68  5021.7  706.19
    5052  708.34  5060.4  709.27  5065.4   709.3  5082.3  710.49  5136.8  713.35
  5163.1  714.26  5233.8  716.16    5254  716.05  5279.7  716.66  5315.5  716.85
#Mann= 3 ,-1 , 0
  4469.6     .16       0  4984.8     .07       0  4993.1     .16       0
Bank Sta=4984.8,4993.1
XS Rating Curve= 0 ,0
Exp/Cntr=0.3,0.1

Type RM Length L Ch R = 1 ,8021    ,376,376,376
BEGIN DESCRIPTION:
Mapping XS 4ce8c0a9
END DESCRIPTION:
XS GIS Cut Line= 2
      2006578.21     13623371.72      2005905.46     13623098.28
#Sta/Elev= 30
  4651.1  717.18  4724.3  716.11  4751.7  715.98  4794.9  712.37  4805.7  712.37
  4837.1  710.46  4935.2  706.87  4973.7  704.89  4979.1  704.38  4989.2  701.45
  4993.6  696.89  4994.3  696.09  5001.2  696.09  5001.9  696.89  5003.2  698.28
  5010.8  700.15  5021.6  700.32  5027.2  701.07  5032.6  703.19  5043.2  702.78
  5056.7  705.33  5075.4  706.39  5086.3  707.61  5104.8  708.64  5110.2  709.34
  5140.3  710.94  5211.9  713.09  5226.7  712.88  5343.1  714.96  5377.3  714.98
#Mann= 4 ,-1 , 0
  4651.1      .1       0  4724.3     .16       0  4993.6     .07       0
  5001.9     .16       0
Bank Sta=4993.6,5001.9
XS Rating Curve= 0 ,0
Exp/Cntr=0.3,0.1

Type RM Length L Ch R = 1 ,7645    ,244,244,244
BEGIN DESCRIPTION:
Mapping XS 1924c3a0
END DESCRIPTION:
XS GIS Cut Line= 2
      2006769.16     13622876.92      2005949.44     13622981.01
#Sta/Elev= 30
  4568.2  715.83  4612.7  716.09  4713.5  715.17  4744.1  715.49  4784.1  715.02
  4830.1  713.47  4835.2  713.83  4884.9  710.94  4910.1   708.5  4955.4  705.07
  4975.6  702.97  4985.1  701.07  4990.1  699.49  4991.6   695.4  4992.3   694.6
  4999.2   694.6  4999.9   695.4  5005.8  698.27  5015.9  702.32    5026  702.93
  5106.6  706.34  5126.8  706.66  5145.1  707.51  5150.2  707.34  5225.1  710.19
  5230.2  709.93  5267.9  711.02  5310.2  711.63  5348.6  712.94  5394.5  713.46
#Mann= 4 ,-1 , 0
  4568.2      .1       0  4744.1     .16       0  4991.6     .07       0
  4999.9     .16       0
Bank Sta=4991.6,4999.9
XS Rating Curve= 0 ,0
Exp/Cntr=0.3,0.1

Type RM Length L Ch R = 1 ,7401    ,215,215,215
BEGIN DESCRIPTION:
Mapping XS a94844f2
END DESCRIPTION:
XS GIS Cut Line= 2
      2006756.18     13622620.84      2005919.25     13622785.62
#Sta/Elev= 30
  4505.3  711.98  4567.7  711.58  4598.2  710.91  4700.1   710.1  4711.7   710.4
  4751.1  709.95  4771.5   710.1  4809.4  709.38  4814.5  709.84  4865.8  708.51
  4900.3  706.65  4920.2  705.53  4944.8  703.99  4954.9  703.06  4963.5  702.63
  4975.3  702.57  4985.5  701.17  4995.7  695.44  5001.8  695.03  5002.5  694.23
  5009.4  694.23  5010.1  695.03  5014.8   700.1  5026.3  702.24  5087.4  704.39
  5225.4  710.05  5276.7  711.51  5321.9  712.14  5342.2  713.01  5358.3  712.91
#Mann= 5 ,-1 , 0
  4505.3      .1       0  4900.3     .16       0  4920.2      .1       0
  5001.8     .07       0  5010.1      .1       0
Bank Sta=5001.8,5010.1
XS Rating Curve= 0 ,0
Exp/Cntr=0.3,0.1

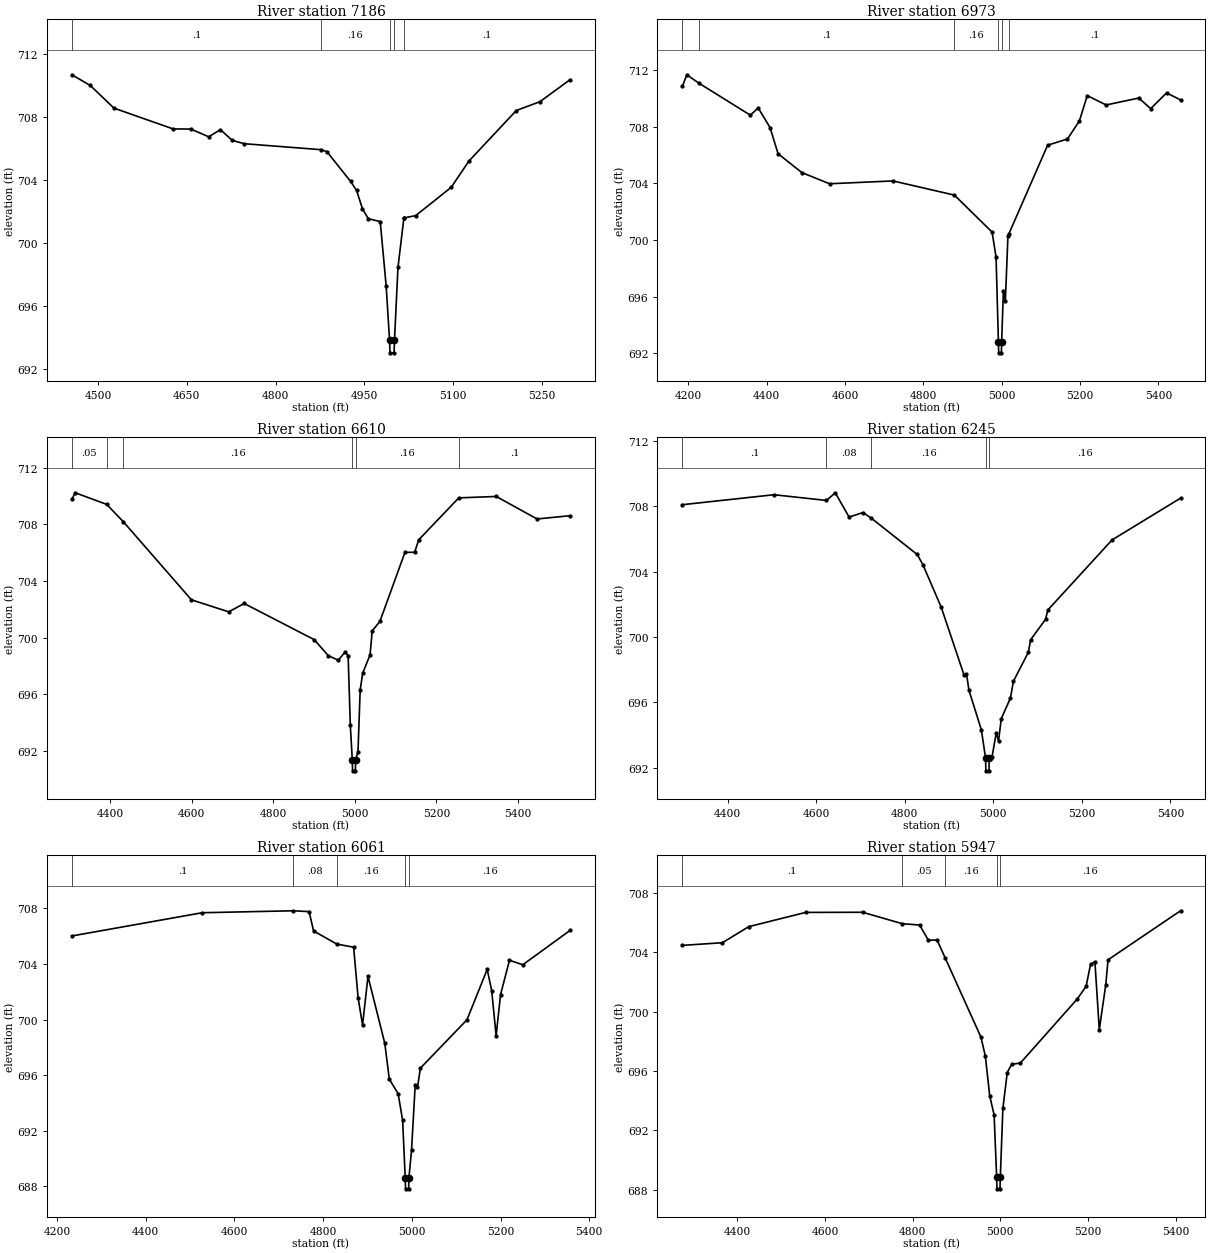
Type RM Length L Ch R = 1 ,7186    ,213,213,213
BEGIN DESCRIPTION:
Mapping XS 9ebc8d52
END DESCRIPTION:
XS GIS Cut Line= 2
      2006756.12     13622534.04      2005914.12     13622521.02
#Sta/Elev= 30
  4455.7  710.69  4486.8  710.01  4526.8  708.57  4626.8  707.25  4656.8  707.24
  4686.8  706.75  4706.8   707.2  4726.9  706.52  4746.9  706.31  4876.9  705.93
  4886.9   705.8  4926.9  703.91  4936.9  703.34  4946.9  702.17  4956.9  701.54
  4976.9  701.36  4986.9  697.29  4992.7  693.82  4993.4  693.02  5000.3  693.02
    5001  693.82  5006.9  698.46  5016.9  701.59  5017.8   701.6  5036.9  701.74
  5096.9  703.54  5126.9  705.21  5206.9  708.42  5246.9  708.98  5297.8  710.38
#Mann= 5 ,-1 , 0
  4455.7      .1       0  4876.9     .16       0  4992.7     .07       0
    5001     .16       0  5017.8      .1       0
Bank Sta=4992.7,5001
XS Rating Curve= 0 ,0
Exp/Cntr=0.3,0.1

Type RM Length L Ch R = 1 ,6973    ,363,363,363
BEGIN DESCRIPTION:
Mapping XS bb52a963
END DESCRIPTION:
XS GIS Cut Line= 2
      2006996.42      13622445.8      2005739.76      13622251.4
#Sta/Elev= 30
  4184.8  710.84  4196.4  711.66    4227  711.07  4358.4  708.81  4378.5  709.32
  4408.8  707.93  4429.1  706.09  4489.8  704.76  4560.6  703.97  4722.5  704.17
  4879.2  703.17  4975.5  700.56  4985.6  698.79  4991.6  692.84  4992.3  692.04
  4999.2  692.04  4999.9  692.84  5004.3  696.42  5009.3  695.69    5016  700.31
  5018.2  700.43  5117.2  706.69  5167.8  707.13  5198.1  708.39  5218.4  710.19
  5266.6  709.53  5349.9  710.02  5380.3  709.27  5420.7  710.38  5456.4  709.89
#Mann= 6 ,-1 , 0
  4184.8     .05       0    4227      .1       0  4879.2     .16       0
  4991.6     .07       0  4999.9     .16       0  5018.2      .1       0
Bank Sta=4991.6,4999.9
XS Rating Curve= 0 ,0
Exp/Cntr=0.3,0.1

Type RM Length L Ch R = 1 ,6610    ,365,365,365
BEGIN DESCRIPTION:
Mapping XS c43c0567
END DESCRIPTION:
XS GIS Cut Line= 3
      2007037.19     13622363.33      2006281.85     13622059.82
      2005874.04     13622076.87
#Sta/Elev= 30
  4305.9  709.78  4314.2  710.23  4391.2  709.41    4432  708.19  4599.2  702.67
  4690.6  701.82  4728.6  702.41  4900.2  699.86  4935.2  698.72  4959.4  698.41
  4976.4  698.98  4983.6  698.73    4989   693.8  4993.8  691.39  4994.5  690.59
  5001.4  690.59  5002.1  691.39  5007.8  691.94  5013.2  696.32  5019.5   697.5
  5037.4  698.78  5042.7  700.48  5061.5  701.14    5123  706.02  5146.8  706.03
  5156.8  706.91  5255.1  709.87    5347  709.97  5447.1  708.38  5528.1  708.61
#Mann= 6 ,-1 , 0
  4305.9     .05       0  4391.2      .1       0    4432     .16       0
  4993.8     .07       0  5002.1     .16       0  5255.1      .1       0
Bank Sta=4993.8,5002.1
XS Rating Curve= 0 ,0
Exp/Cntr=0.3,0.1

Type RM Length L Ch R = 1 ,6245    ,184,184,184
BEGIN DESCRIPTION:
Mapping XS 07fad95f
END DESCRIPTION:
XS GIS Cut Line= 2
      2007376.82     13622178.14      2006296.09     13621865.64
#Sta/Elev= 30
  4297.8  708.11  4504.9  708.72  4623.3  708.37  4643.2  708.84  4674.4  707.35
  4705.7  707.63  4724.8  707.28  4828.2  705.06    4841  704.44  4882.6  701.82
  4934.3  697.65  4939.5  697.75  4945.1  696.74  4973.1  694.32  4982.5  692.61
  4983.3  691.81  4990.2  691.81  4990.9  692.61  4997.1  692.65  5006.7  694.13
  5011.9  693.64    5018     695  5038.8  696.27  5045.5   697.3  5079.2  699.07
  5084.4  699.84    5118  701.09  5123.2  701.66  5268.1  705.95  5422.8  708.51
#Mann= 5 ,-1 , 0
  4297.8      .1       0  4623.3     .08       0  4724.8     .16       0
  4982.5     .07       0  4990.9     .16       0
Bank Sta=4982.5,4990.9
XS Rating Curve= 0 ,0
Exp/Cntr=0.3,0.1

Type RM Length L Ch R = 1 ,6061    ,114,114,114
BEGIN DESCRIPTION:
Mapping XS a8f2a8aa
END DESCRIPTION:
XS GIS Cut Line= 2
      2007567.73     13621909.03      2006448.96      13621809.3
#Sta/Elev= 30
  4233.6  706.01  4527.5  707.68  4732.2  707.82  4768.4  707.76  4778.5  706.37
  4830.7  705.43  4868.8   705.2  4878.9  701.57  4888.9  699.61  4901.2   703.1
  4939.1  698.29  4949.2  695.72  4969.2  694.67  4979.3  692.75  4985.1  688.63
  4985.9  687.83  4992.8  687.83  4993.5  688.63  4999.4  690.61  5007.7  695.33
  5012.7  695.12  5019.4  696.51  5124.3  699.98    5170  703.61  5180.1  702.07
  5190.1  698.84  5200.1   701.8  5220.2  704.26  5250.3  703.94  5356.8  706.41
#Mann= 5 ,-1 , 0
  4233.6      .1       0  4732.2     .08       0  4830.7     .16       0
  4985.1     .07       0  4993.5     .16       0
Bank Sta=4985.1,4993.5
XS Rating Curve= 0 ,0
Exp/Cntr=0.3,0.1

Type RM Length L Ch R = 1 ,5947    ,318,318,318
BEGIN DESCRIPTION:
Mapping XS b07597cb
END DESCRIPTION:
XS GIS Cut Line= 2
      2007576.44     13621765.81      2006439.65     13621735.44
#Sta/Elev= 30
  4274.1  704.46  4365.6  704.64  4425.6  705.72  4555.6  706.68  4685.7  706.69
  4776.1  705.92  4815.7  705.83  4835.7  704.81  4855.7  704.82  4874.5  703.59
  4955.8  698.28  4965.8     697  4975.8  694.33  4985.8  693.05  4991.6  688.87
  4992.3  688.07  4999.2  688.07    5000  688.87  5005.8  693.48  5015.8   695.9
  5025.8  696.45  5045.8  696.54  5175.9  700.86  5195.9  701.71  5205.9  703.18
  5215.9  703.36  5225.9  698.79  5240.7  701.81  5245.9  703.49  5411.3  706.79
#Mann= 5 ,-1 , 0
  4274.1      .1       0  4776.1     .05       0  4874.5     .16       0
  4991.6     .07       0    5000     .16       0
Bank Sta=4991.6,5000
XS Rating Curve= 0 ,0
Exp/Cntr=0.3,0.1