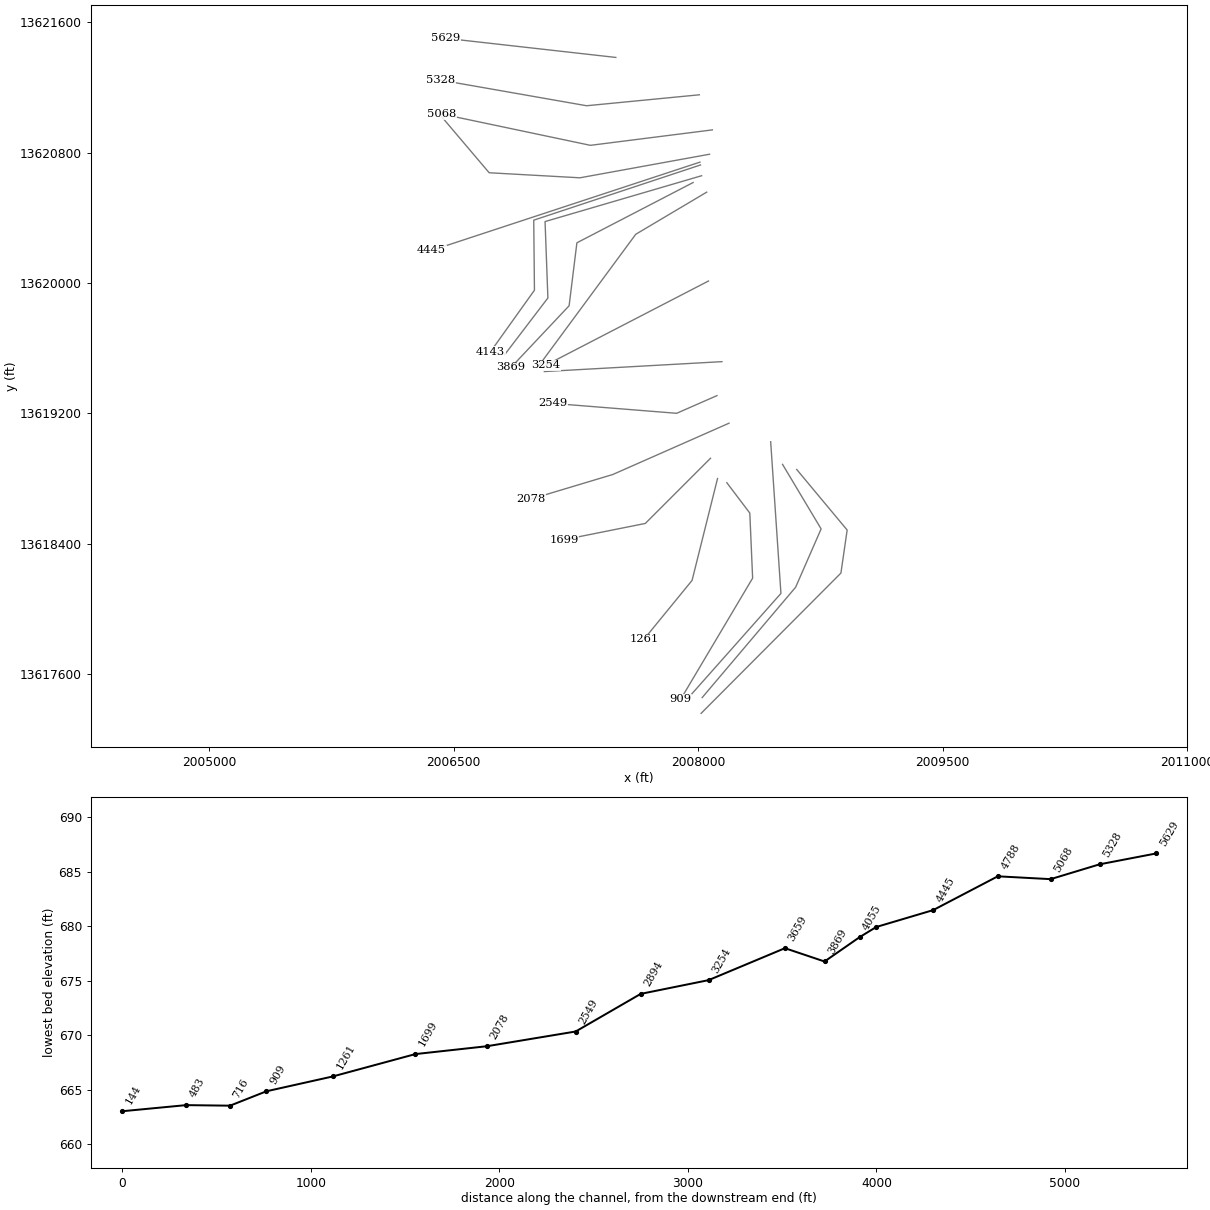
HEC-RAS study UNT 098 in HW.prj: UNT 098 in HW Base Level Engineering

--- UNT 098 in HW.g01 (geometry) --- (continued)

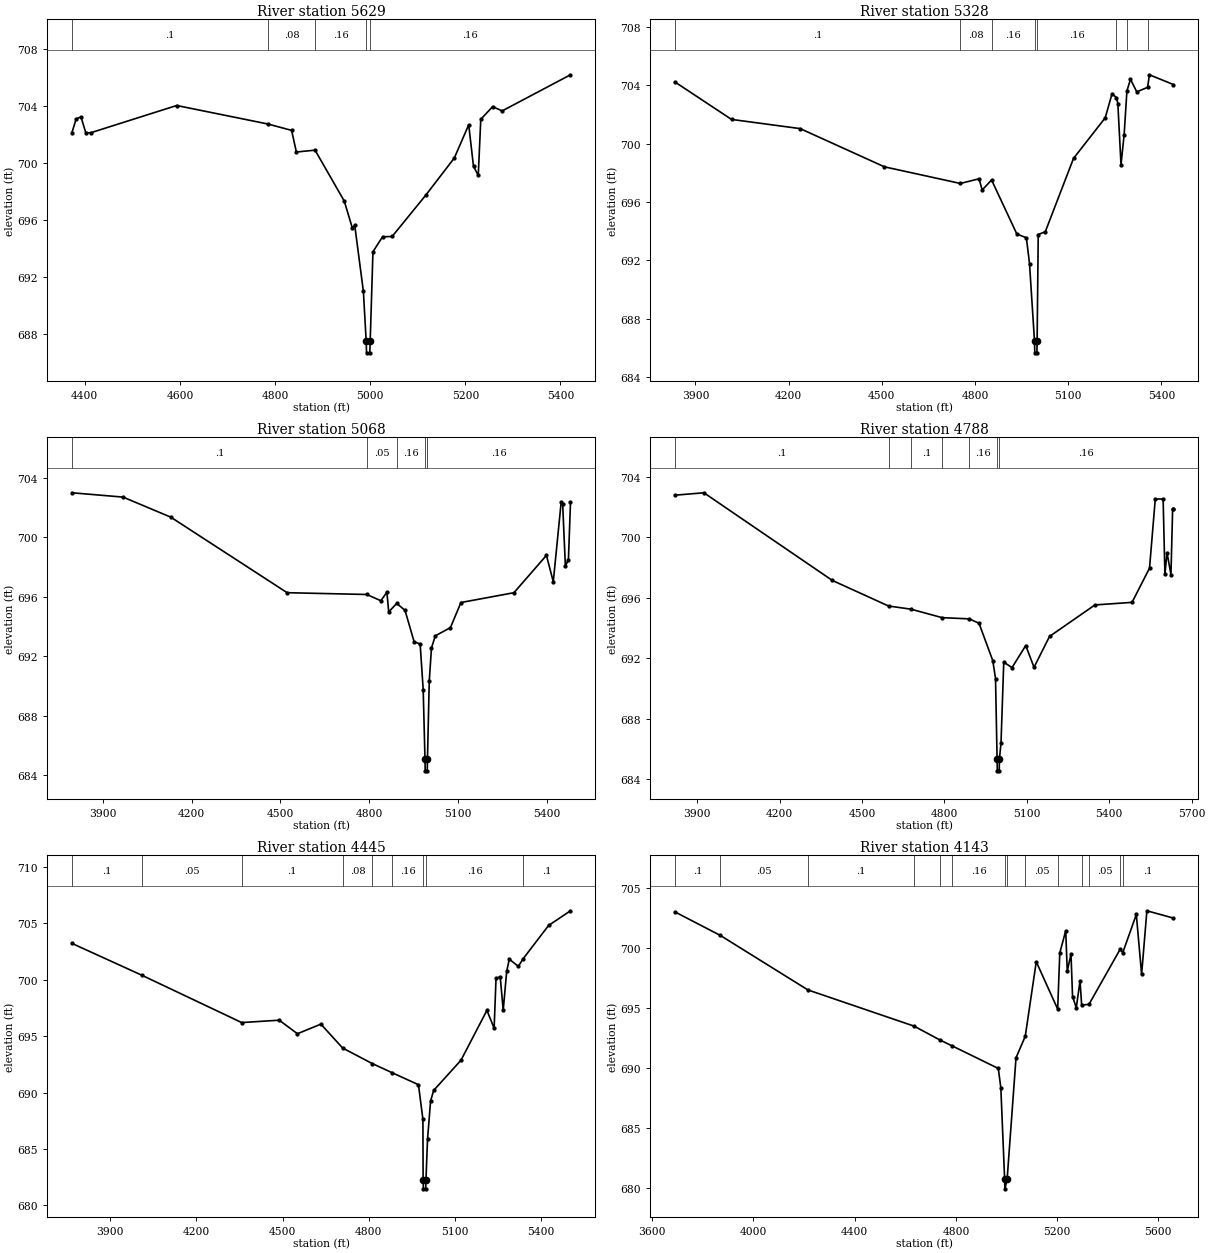
Type RM Length L Ch R = 1 ,5629    ,301,301,301
BEGIN DESCRIPTION:
Mapping XS 8d921d26
END DESCRIPTION:
XS GIS Cut Line= 2
      2007493.97     13621383.87      2006452.34     13621501.05
#Sta/Elev= 30
  4372.9  702.14  4381.9  703.11    4392  703.25    4402  702.14  4412.1  702.13
  4593.2  704.05  4784.8  702.75  4834.8   702.3  4844.8  700.78  4884.1  700.91
  4945.5  697.33  4962.5  695.43  4967.5  695.63  4985.7  690.98  4991.6  687.46
  4992.3  686.66  4999.2  686.66    5000  687.46  5005.8  693.77    5026  694.82
  5046.1  694.84  5116.5  697.73  5176.9  700.36  5207.1  702.69  5217.2  699.77
  5227.2  699.14  5232.5  703.08  5257.4  703.97  5277.5  703.67  5421.1  706.21
#Mann= 5 ,-1 , 0
  4372.9      .1       0  4784.8     .08       0  4884.1     .16       0
  4991.6     .07       0    5000     .16       0
Bank Sta=4991.6,5000
XS Rating Curve= 0 ,0
Exp/Cntr=0.3,0.1

Type RM Length L Ch R = 1 ,5328    ,260,260,260
BEGIN DESCRIPTION:
Mapping XS 3b9e0a2f
END DESCRIPTION:
XS GIS Cut Line= 3
      2008006.55     13621154.68      2007314.76     13621087.51
       2006418.8     13621244.76
#Sta/Elev= 30
  3833.9  704.23  4016.3  701.66  4237.3  701.03  4508.6  698.41  4752.9  697.27
    4813  697.59  4823.1  696.82  4853.3  697.51  4934.8   693.8  4965.3  693.55
  4975.4  691.78  4991.5  686.46  4992.3  685.66  4999.2  685.66  4999.9  686.46
  5003.5  693.77  5026.2  693.96  5117.1  698.99  5219.1  701.77    5241  703.42
  5255.1  703.16  5259.7  702.75  5269.9  698.56    5280  700.62  5288.9  703.61
  5300.4  704.41  5320.6  703.55  5355.6  703.86  5361.2  704.72  5438.6  704.05
#Mann= 8 ,-1 , 0
  3833.9      .1       0  4752.9     .08       0  4853.3     .16       0
  4991.5     .07       0  4999.9     .16       0  5255.1      .1       0
  5288.9     .16       0  5355.6      .1       0
Bank Sta=4991.5,4999.9
XS Rating Curve= 0 ,0
Exp/Cntr=0.3,0.1

Type RM Length L Ch R = 1 ,5068    ,280,280,280
BEGIN DESCRIPTION:
Mapping XS 7a14a626
END DESCRIPTION:
XS GIS Cut Line= 3
      2008086.38      13620939.4      2007338.21     13620844.66
      2006428.11     13621036.26
#Sta/Elev= 30
    3796     703  3968.7  702.71    4130  701.36  4523.1  696.28  4792.1  696.16
  4839.6  695.74    4860  696.31  4866.2  694.99  4893.3  695.56  4921.3  695.09
    4952  692.98  4972.4  692.83  4982.6  689.77  4988.7   685.1  4989.4   684.3
  4996.3   684.3  4997.1   685.1  5003.1  690.33  5010.6  692.56  5023.5  693.38
  5074.6  693.93  5110.2  695.62  5289.2  696.28  5398.9  698.79  5422.1  697.02
  5448.7  702.37  5453.8  702.23  5462.9  698.08  5473.2  698.49  5480.2  702.35
#Mann= 5 ,-1 , 0
    3796      .1       0  4792.1     .05       0  4893.3     .16       0
  4988.7     .07       0  4997.1     .16       0
Bank Sta=4988.7,4997.1
XS Rating Curve= 0 ,0
Exp/Cntr=0.3,0.1

Type RM Length L Ch R = 1 ,4788    ,343,343,343
BEGIN DESCRIPTION:
Mapping XS 1a7e056b
END DESCRIPTION:
XS GIS Cut Line= 4
      2008069.08      13620790.1      2007273.78     13620645.47
      2006717.07      13620676.4      2006426.27     13621019.28
#Sta/Elev= 30
  3818.1  702.77  3923.9  702.93  4391.4  697.14  4596.2  695.45  4677.9  695.24
  4791.5  694.68  4890.2   694.6  4925.7  694.31  4975.8  691.84  4985.8  690.66
  4991.5  685.36  4992.3  684.56  4999.3  684.56  5000.1  685.36  5005.8  686.41
  5015.8  691.74  5045.9  691.38  5095.9  692.84    5126   691.4  5182.5  693.44
  5347.8  695.52  5482.9  695.69  5546.6  697.95  5567.5  702.52  5596.1  702.52
  5602.6  697.54  5610.3  698.97  5624.6  697.53  5630.7  701.83  5633.6  701.83
#Mann= 7 ,-1 , 0
  3818.1      .1       0  4596.2     .05       0  4677.9      .1       0
  4791.5     .05       0  4890.2     .16       0  4991.5     .07       0
  5000.1     .16       0
Bank Sta=4991.5,5000.1
XS Rating Curve= 0 ,0
Exp/Cntr=0.3,0.1

Type RM Length L Ch R = 1 ,4445    ,302,302,302
BEGIN DESCRIPTION:
Mapping XS be246fa1
END DESCRIPTION:
XS GIS Cut Line= 2
      2008010.06      13620741.5      2006362.73     13620199.48
#Sta/Elev= 30
  3767.3  703.22  4009.4  700.41  4357.9   696.2  4488.5  696.41  4551.7  695.21
  4633.3  696.06  4709.1  693.94  4811.6  692.57  4882.4  691.74  4972.7  690.69
  4988.2  687.62  4988.9  682.26  4989.9  681.46  4997.8  681.46  4998.8  682.26
  5004.3  685.88  5014.8  689.23  5025.4  690.18  5120.6  692.86  5210.8  697.28
  5235.9   695.7  5242.5  700.11    5257  700.27  5267.5   697.3  5279.6  700.74
  5288.6  701.82  5320.1  701.18  5336.3  701.84  5425.4  704.81  5501.5  706.11
#Mann= 9 ,-1 , 0
  3767.3      .1       0  4009.4     .05       0  4357.9      .1       0
  4709.1     .08       0  4811.6     .05       0  4882.4     .16       0
  4988.9     .07       0  4998.8     .16       0  5336.3      .1       0
Bank Sta=4988.9,4998.8
XS Rating Curve= 0 ,0
Exp/Cntr=0.3,0.1

Type RM Length L Ch R = 1 ,4143    ,88,88,88
BEGIN DESCRIPTION:
Mapping XS b78dbd6f
END DESCRIPTION:
XS GIS Cut Line= 4
      2008013.51     13620724.13      2006990.51      13620385.6
      2006994.85     13619955.91      2006725.89     13619579.13
#Sta/Elev= 30
  3689.3  703.01  3868.6  701.05    4215   696.5  4634.6  693.48  4737.2  692.32
  4786.3  691.82  4967.5  689.95  4977.5  688.34  4992.5  680.71  4993.5  679.91
  5002.4  680.71  5037.5  690.84    5074  692.63  5117.5  698.85  5202.1   694.9
  5210.5  699.59  5233.9  701.43    5240  698.07  5254.8  699.49  5260.9  695.94
  5275.7  695.02  5290.4  697.25  5296.9  695.23  5325.9   695.3  5449.8  699.92
  5459.1  699.59  5512.9  702.79  5533.8  697.79  5554.6   703.1  5659.5  702.49
#Mann= 14 ,-1 , 0
  3689.3      .1       0  3868.6     .05       0    4215      .1       0
  4634.6     .08       0  4737.2     .05       0  4786.3     .16       0
  4992.5     .07       0  5002.4     .16       0    5074     .05       0
  5202.1      .1       0  5296.9     .16       0  5325.9     .05       0
  5449.8     .08       0  5459.1      .1       0
Bank Sta=4992.5,5002.4
XS Rating Curve= 0 ,0
Exp/Cntr=0.3,0.1

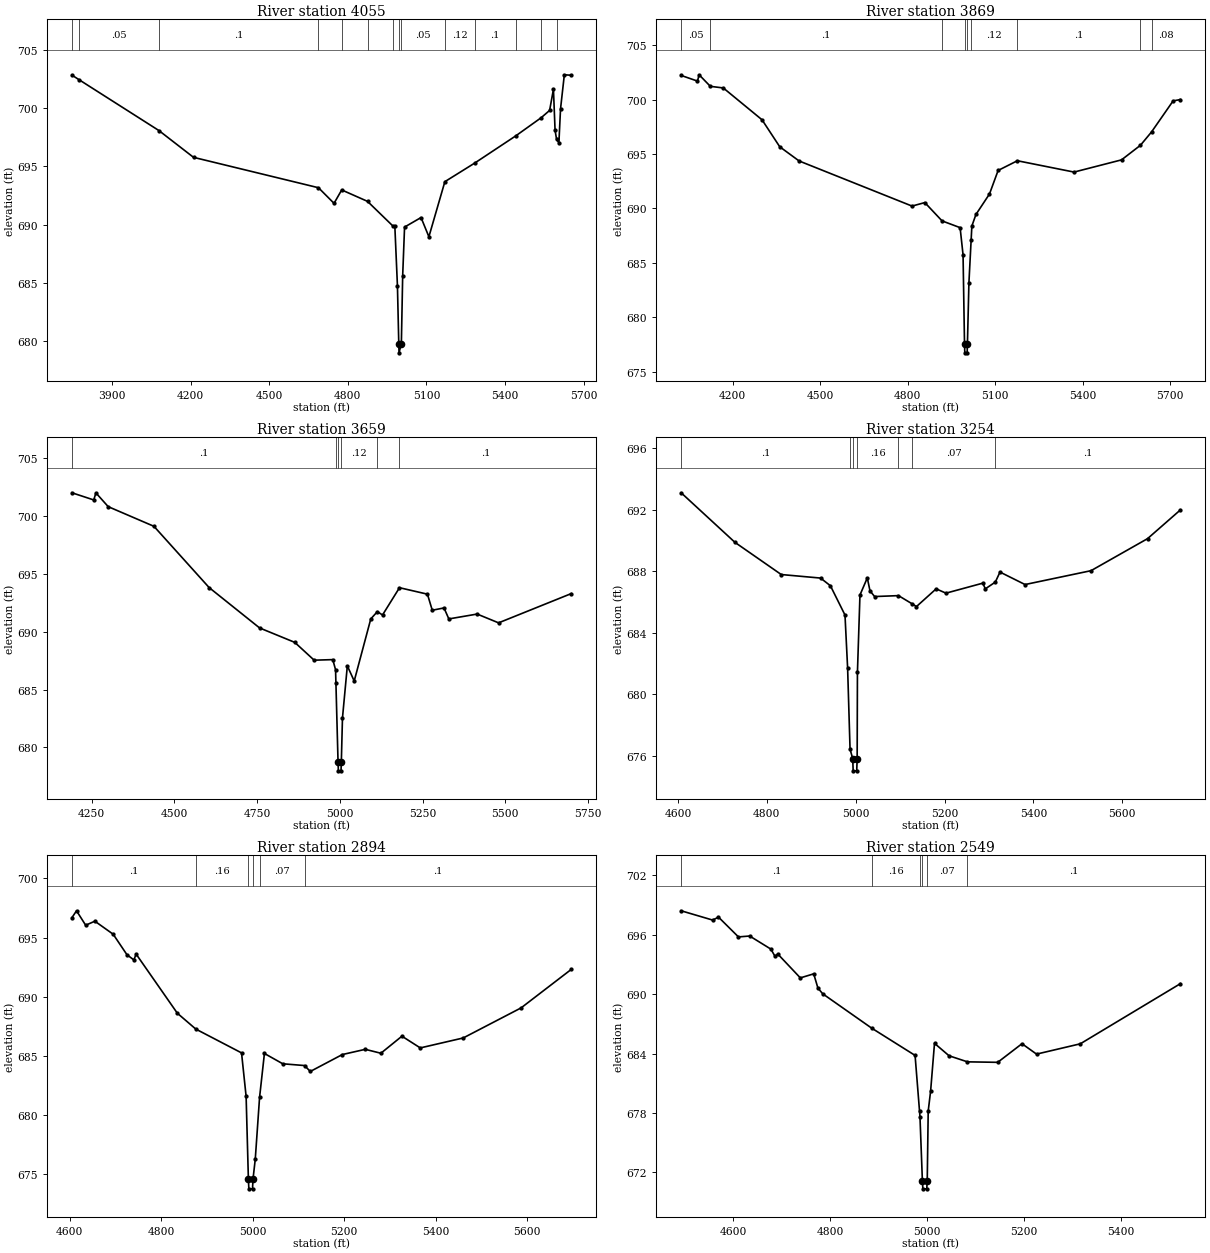
Type RM Length L Ch R = 1 ,4055    ,186,186,186
BEGIN DESCRIPTION:
Mapping XS 9184cb64
END DESCRIPTION:
XS GIS Cut Line= 4
      2008020.47     13620658.16      2007059.95     13620376.92
      2007077.32     13619908.17      2006812.54     13619560.92
#Sta/Elev= 30
  3746.6  702.83  3773.5  702.44  4078.7  698.07  4210.8  695.77  4687.9  693.16
  4747.4  691.82  4776.7  692.97  4875.2  691.99  4973.7  689.84  4979.5  689.89
  4989.5  684.74  4994.6  679.78  4995.6  678.98  5004.5  679.78  5009.5   685.6
  5016.7  689.78  5079.6   690.6  5109.6  688.95  5170.6  693.68  5284.1  695.27
  5441.1  697.61  5538.2  699.17  5570.6   699.8  5585.2  701.62  5591.4   698.1
    5597  697.33    5606  697.02  5612.3  699.94  5626.8  702.86  5653.2  702.82
#Mann= 14 ,-1 , 0
  3746.6     .08       0  3773.5     .05       0  4078.7      .1       0
  4687.9     .08       0  4776.7     .05       0  4875.2     .08       0
  4973.7     .05       0  4994.6     .04       0  5004.5     .05       0
  5170.6     .12       0  5284.1      .1       0  5441.1     .08       0
  5538.2     .05       0    5597      .1       0
Bank Sta=4994.6,5004.5
XS Rating Curve= 0 ,0
Exp/Cntr=0.3,0.1

Type RM Length L Ch R = 1 ,3869    ,210,210,210
BEGIN DESCRIPTION:
Mapping XS 66d19eca
END DESCRIPTION:
XS GIS Cut Line= 4
      2007968.31     13620616.47      2007255.27     13620246.71
      2007207.52     13619860.43      2006851.64     13619482.85
#Sta/Elev= 30
  4023.3  702.21  4079.3  701.69  4084.9  702.27  4123.3  701.21  4167.8  701.06
  4300.5  698.14  4361.3  695.66  4427.6  694.36  4814.6  690.22  4858.5  690.54
  4917.5  688.86  4979.4  688.24  4989.5  685.75  4994.5  677.55  4995.5  676.75
  5003.5  676.75  5004.5  677.55  5009.6  683.18  5017.2   687.1  5019.7  688.39
  5033.7  689.45  5080.1  691.33  5109.7  693.49  5175.7  694.38    5370  693.34
  5532.6  694.46  5597.5   695.8  5635.4  697.02  5709.4  699.87  5734.6     700
#Mann= 9 ,-1 , 0
  4023.3     .05       0  4123.3      .1       0  4917.5     .07       0
  4994.5     .07       0  5004.5     .07       0  5017.2     .12       0
  5175.7      .1       0  5597.5     .05       0  5635.4     .08       0
Bank Sta=4994.5,5004.5
XS Rating Curve= 0 ,0
Exp/Cntr=0.3,0.1

Type RM Length L Ch R = 1 ,3659    ,405,405,405
BEGIN DESCRIPTION:
Mapping XS 4c80bf6f
END DESCRIPTION:
XS GIS Cut Line= 3
      2008051.65     13620557.44      2007616.29     13620298.96
      2007020.86     13619491.46
#Sta/Elev= 30
    4190  702.02  4255.9   701.4  4262.5  702.01  4299.6  700.82  4437.9  699.12
  4604.8  693.82  4757.3  690.33  4863.8  689.08  4922.3  687.54  4978.6  687.59
    4987  686.72  4988.1  685.57  4994.5  678.77  4995.5  677.97  5003.5  677.97
  5004.5  678.77  5007.9  682.54  5022.6  687.05  5043.4  685.74  5093.5  691.11
  5113.4  691.74    5129  691.45  5180.3  693.81  5264.8  693.25  5279.4  691.86
  5314.9  692.06  5329.5  691.11  5415.1  691.53  5479.9  690.77  5699.6   693.3
#Mann= 6 ,-1 , 0
    4190      .1       0  4988.1     .12       0  4994.5     .07       0
  5004.5     .12       0  5113.4     .07       0  5180.3      .1       0
Bank Sta=4994.5,5004.5
XS Rating Curve= 0 ,0
Exp/Cntr=0.3,0.1

Type RM Length L Ch R = 1 ,3254    ,360,360,360
BEGIN DESCRIPTION:
Mapping XS 5a90ad8f
END DESCRIPTION:
XS GIS Cut Line= 2
      2008062.52     13620012.32      2007064.32     13619495.86
#Sta/Elev= 30
  4607.1   693.1  4728.2  689.88  4832.4  687.79    4921  687.56  4943.1  687.06
  4975.9  685.16  4981.8  681.73  4987.3  676.44  4993.3  675.84  4994.3  675.04
  5002.3  675.04  5003.3  675.84  5003.9  681.43  5009.6  686.46  5026.1  687.57
  5032.2  686.73  5042.6  686.36  5096.3  686.42  5126.9  685.89  5136.8  685.71
  5181.1  686.86  5203.2  686.58  5286.1  687.23  5291.8  686.86  5314.3   687.3
  5324.8  687.95  5381.2  687.14  5529.7  688.04  5656.9  690.12    5731  691.99
#Mann= 7 ,-1 , 0
  4607.1      .1       0  4987.3     .16       0  4993.3     .07       0
  5003.3     .16       0  5096.3     .12       0  5126.9     .07       0
  5314.3      .1       0
Bank Sta=4993.3,5003.3
XS Rating Curve= 0 ,0
Exp/Cntr=0.3,0.1

Type RM Length L Ch R = 1 ,2894    ,345,345,345
BEGIN DESCRIPTION:
Mapping XS 63056c9f
END DESCRIPTION:
XS GIS Cut Line= 2
      2008144.99     13619517.54      2007055.58     13619456.78
#Sta/Elev= 30
  4605.2  696.68  4615.2  697.26  4635.2  696.04  4655.3  696.38  4695.3  695.28
  4725.4  693.55  4740.5  693.11  4745.5   693.6  4835.5  688.61  4875.9  687.27
  4975.8  685.26  4985.8  681.59  4990.8  674.58  4991.8  673.78  4999.8  673.78
  5000.8  674.58  5005.8  676.28  5015.2   681.5  5025.8  685.21  5065.9  684.34
  5113.6  684.19    5126  683.69  5196.1  685.12  5246.2  685.56  5280.3  685.23
  5326.3  686.67  5366.4  685.68  5460.2  686.52  5586.7  689.06  5696.3  692.31
#Mann= 6 ,-1 , 0
  4605.2      .1       0  4875.9     .16       0  4990.8     .07       0
  5000.8     .16       0  5015.2     .07       0  5113.6      .1       0
Bank Sta=4990.8,5000.8
XS Rating Curve= 0 ,0
Exp/Cntr=0.3,0.1

Type RM Length L Ch R = 1 ,2549    ,471,471,471
BEGIN DESCRIPTION:
Mapping XS d76d01ee
END DESCRIPTION:
XS GIS Cut Line= 3
       2008114.6     13619309.19      2007867.25     13619200.71
      2007108.87     13619261.38
#Sta/Elev= 30
  4492.7  698.42  4557.8  697.48  4569.8  697.78    4611  695.78  4634.2  695.87
  4677.9  694.55  4686.6  693.81  4692.1  694.06  4738.8  691.64  4766.4  692.05
  4775.1  690.61  4785.1  690.03  4885.9  686.57  4975.7  683.81  4984.9  678.17
  4985.8  677.62  4990.8  671.13  4991.8  670.33  4999.8  670.33  5000.8  671.13
  5002.8  678.18  5007.8  680.22  5015.8  685.03  5045.9  683.77  5083.8  683.16
  5146.3  683.11  5196.4  684.99  5226.5  683.94  5316.8  684.98  5523.6  691.06
#Mann= 6 ,-1 , 0
  4492.7      .1       0  4885.9     .16       0  4984.9     .07       0
  4990.8     .07       0  5000.8     .07       0  5083.8      .1       0
Bank Sta=4990.8,5000.8
XS Rating Curve= 0 ,0
Exp/Cntr=0.3,0.1

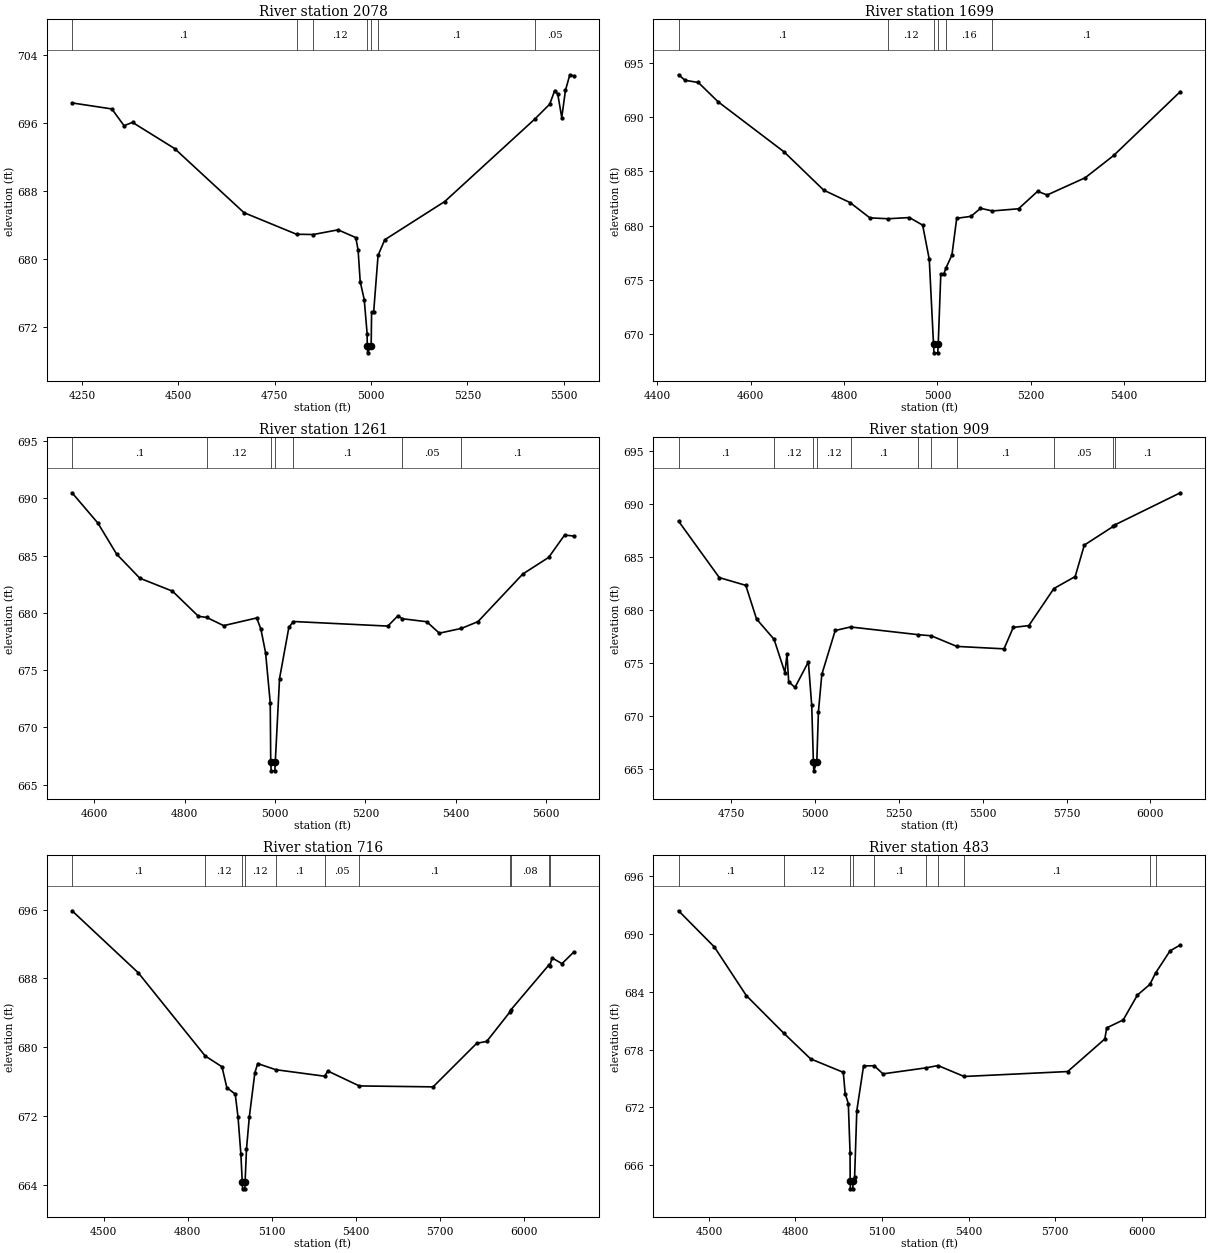
Type RM Length L Ch R = 1 ,2078    ,379,379,379
BEGIN DESCRIPTION:
UNT 098 in HW 5.0
END DESCRIPTION:
XS GIS Cut Line= 3
      2008188.42     13619139.94        2007475.       13618825.
      2006974.96     13618674.99
#Sta/Elev= 30
  4224.2  698.38  4327.4  697.67  4359.1   695.7    4381  696.09  4490.3  693.01
  4670.2  685.47  4806.5  682.93    4850   682.9  4914.3  683.45  4960.3  682.54
  4966.3  681.07  4971.8  677.35  4982.2  675.25  4989.7  671.25  4990.1  669.78
  4991.1  668.98  5000.2  669.78  5001.3  673.78  5006.7  673.78  5018.1  680.44
  5035.4  682.28  5191.1  686.78  5425.2   696.5  5463.4  698.23  5476.5  699.84
  5484.3  699.42  5494.7  696.66  5504.3  699.86  5515.6  701.69  5526.1  701.56
#Mann= 7 ,-1 , 0
  4224.2      .1       0  4806.5     .16       0    4850     .12       0
  4990.1     .07       0  5000.2     .12       0  5018.1      .1       0
  5425.2     .05       0
Bank Sta=4990.1,5000.2
XS Rating Curve= 0 ,0
Exp/Cntr=0.3,0.1

Type RM Length L Ch R = 1 ,1699    ,438,438,438
BEGIN DESCRIPTION:
UNT 098 in HW 4.0
END DESCRIPTION:
XS GIS Cut Line= 3
      2008074.97     13618924.97        2007675.       13618525.
      2007175.05     13618425.01
#Sta/Elev= 30
  4445.2  693.91  4459.3   693.4  4487.6   693.2    4530  691.42  4671.4   686.8
  4756.3  683.27  4812.9  682.12  4855.3  680.71    4894  680.63  4940.1  680.74
  4968.4  680.04  4982.6  676.89  4991.7  669.06  4992.7  668.26  5000.8  668.26
  5001.8  669.06  5007.3  675.49  5013.4  675.49  5018.4  676.09  5031.2  677.29
  5041.4  680.67    5072  680.85  5092.4  681.59  5118.1  681.35    5174  681.55
  5214.8  683.16  5235.2  682.82  5316.8  684.41    5378  686.47  5520.7  692.36
#Mann= 6 ,-1 , 0
  4445.2      .1       0    4894     .12       0  4991.7     .07       0
  5001.8     .12       0  5018.4     .16       0  5118.1      .1       0
Bank Sta=4991.7,5001.8
XS Rating Curve= 0 ,0
Exp/Cntr=0.3,0.1

Type RM Length L Ch R = 1 ,1261    ,352,352,352
BEGIN DESCRIPTION:
UNT 098 in HW 3.0
END DESCRIPTION:
XS GIS Cut Line= 3
      2008118.11     13618800.52      2007961.86     13618175.53
      2007666.73     13617814.42
#Sta/Elev= 30
  4550.6  690.49  4607.8  687.84  4649.1  685.14  4700.6  683.03  4772.8   681.9
  4830.4   679.7  4848.3  679.61  4886.1  678.89  4959.3  679.56  4968.6  678.57
  4978.9  676.52  4989.2  672.15  4990.3  667.01  4991.3  666.21  4999.4  666.21
  5000.4  667.01  5009.8  674.27  5030.4  678.73  5040.3  679.25  5249.4  678.85
  5271.7  679.74  5281.9  679.49  5335.6  679.23  5363.4  678.23  5412.5  678.65
    5449  679.24    5548  683.39  5605.5  684.85  5640.7   686.8  5661.2  686.71
#Mann= 7 ,-1 , 0
  4550.6      .1       0  4848.3     .12       0  4990.3     .07       0
  5000.4     .12       0  5040.3      .1       0  5281.9     .05       0
  5412.5      .1       0
Bank Sta=4990.3,5000.4
XS Rating Curve= 0 ,0
Exp/Cntr=0.3,0.1

Type RM Length L Ch R = 1 ,909     ,193,193,193
BEGIN DESCRIPTION:
UNT 098 in HW 2.0
END DESCRIPTION:
XS GIS Cut Line= 4
        2008175.     13618775.01      2008316.03     13618588.73
      2008333.39     13618189.42      2007891.98     13617446.37
#Sta/Elev= 30
    4592  688.37  4713.7  683.05  4792.7  682.32  4824.8  679.15  4877.1  677.24
  4909.5  674.11  4915.7  675.84  4920.7  673.25  4939.5   672.7  4979.5  675.11
  4989.5  671.01  4994.5  665.65  4995.5  664.85  5004.6  665.65  5009.5  670.41
  5019.6  673.93  5059.6  678.07  5105.4   678.4  5305.8  677.68  5346.2  677.57
  5422.6  676.57  5563.4  676.34    5591  678.36  5637.5  678.53  5712.2  682.02
  5775.8  683.15    5803  686.11  5889.7  687.88  5895.2  688.03  6089.6  691.04
#Mann= 11 ,-1 , 0
    4592      .1       0  4877.1     .12       0  4994.5     .07       0
  5004.6     .12       0  5105.4      .1       0  5305.8     .05       0
  5346.2     .08       0  5422.6      .1       0  5712.2     .05       0
  5889.7     .08       0  5895.2      .1       0
Bank Sta=4994.5,5004.6
XS Rating Curve= 0 ,0
Exp/Cntr=0.3,0.1

Type RM Length L Ch R = 1 ,716     ,233,233,233
BEGIN DESCRIPTION:
Mapping XS 38475ca6
END DESCRIPTION:
XS GIS Cut Line= 3
      2008444.05     13619026.24        2008507.     13618095.67
      2007937.13     13617453.32
#Sta/Elev= 30
  4386.9  695.87  4623.5  688.65    4862  678.99    4922  677.73  4939.4  675.31
  4969.5  674.54  4979.5  671.83  4989.5  667.57  4994.5  664.33  4995.5  663.53
  5003.6  663.53  5004.6  664.33  5009.6  668.17  5019.6  671.87  5039.6  677.06
  5049.7   678.1  5113.6  677.39  5288.3  676.63  5300.2  677.23  5412.1   675.5
  5675.7  675.39  5831.3  680.45  5867.3  680.68    5949  684.06    5954  684.37
  6089.5  689.58  6092.2  689.46  6100.6  690.39  6135.9  689.72  6178.3  691.08
#Mann= 11 ,-1 , 0
  4386.9      .1       0    4862     .12       0  4994.5     .07       0
  5004.6     .12       0  5113.6      .1       0  5288.3     .05       0
  5412.1      .1       0    5949     .05       0    5954     .08       0
  6089.5     .05       0  6092.2      .1       0
Bank Sta=4994.5,5004.6
XS Rating Curve= 0 ,0
Exp/Cntr=0.3,0.1

Type RM Length L Ch R = 1 ,483     ,339,339,339
BEGIN DESCRIPTION:
Mapping XS 6525fc13
END DESCRIPTION:
XS GIS Cut Line= 4
      2008516.96     13618887.33      2008753.53      13618491.5
      2008597.28     13618133.86      2008023.89     13617456.74
#Sta/Elev= 30
  4394.8  692.36  4518.8  688.62  4629.7  683.58  4760.2  679.67  4852.5  677.03
  4965.7  675.64  4972.2  673.43  4983.1  672.41  4989.1  667.33  4989.5  664.38
  4990.5  663.58  4998.6  663.58  4999.6  664.38  5004.9  664.81  5012.5  671.67
  5035.9   676.3    5073  676.32  5103.1  675.48  5251.7   676.1  5293.9  676.34
  5384.4  675.21  5743.2  675.72  5871.8  679.09  5878.4  680.24  5935.5  681.06
  5984.9  683.64    6028  684.74  6047.5  685.91  6098.1  688.22  6133.5  688.82
#Mann= 10 ,-1 , 0
  4394.8      .1       0  4760.2     .12       0  4989.5     .07       0
  4999.6     .12       0    5073      .1       0  5251.7     .08       0
  5293.9     .05       0  5384.4      .1       0    6028     .08       0
  6047.5     .05       0
Bank Sta=4989.5,4999.6
XS Rating Curve= 0 ,0
Exp/Cntr=0.3,0.1

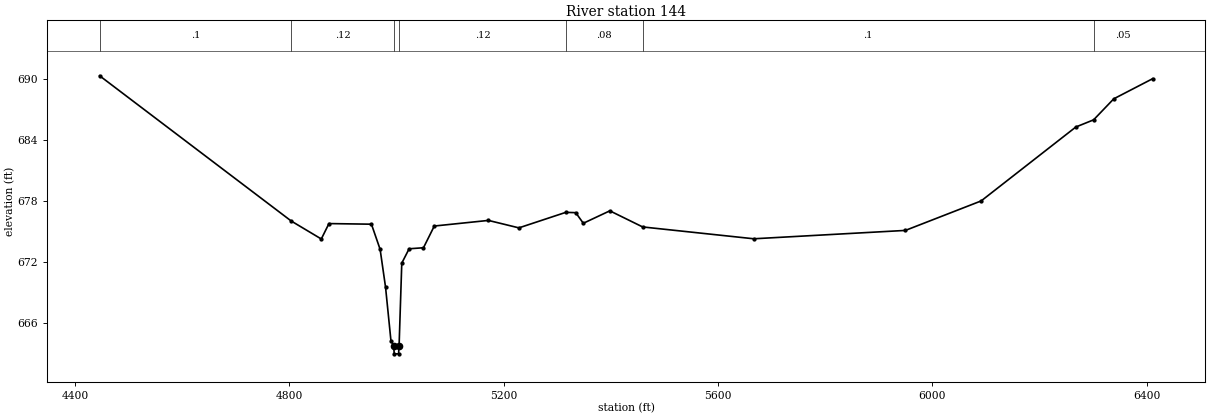
Type RM Length L Ch R = 1 ,144     ,0,0,0
BEGIN DESCRIPTION:
UNT 098 in HW 1.0
END DESCRIPTION:
XS GIS Cut Line= 4
      2008603.76     13618856.09      2008913.25     13618484.56
      2008875.06     13618220.67      2008017.22      13617359.8
#Sta/Elev= 30
  4445.7  690.28  4803.3  676.04  4859.4  674.28  4873.7  675.79    4953  675.73
  4969.2  673.26  4979.3  669.56  4989.4   664.3  4994.5  663.82  4995.5  663.02
  5003.6  663.02  5004.6  663.82  5009.6  671.91  5023.3  673.32  5050.1  673.42
  5070.3  675.55  5171.3   676.1  5228.2  675.37  5315.7  676.89  5334.3  676.86
  5348.4  675.82  5397.9  677.04  5459.2  675.46  5666.6   674.3  5949.5  675.12
  6090.9  678.01  6267.7  685.26  6300.8  685.96  6338.4  688.02  6411.2     690
#Mann= 7 ,-1 , 0
  4445.7      .1       0  4803.3     .12       0  4994.5     .07       0
  5004.6     .12       0  5315.7     .08       0  5459.2      .1       0
  6300.8     .05       0
Bank Sta=4994.5,5004.6
XS Rating Curve= 0 ,0
Exp/Cntr=0.3,0.1
LCMann Table=0

Chan Stop Cuts=-1
Use User Specified Reach Order=0
Composite Channel Slope=5