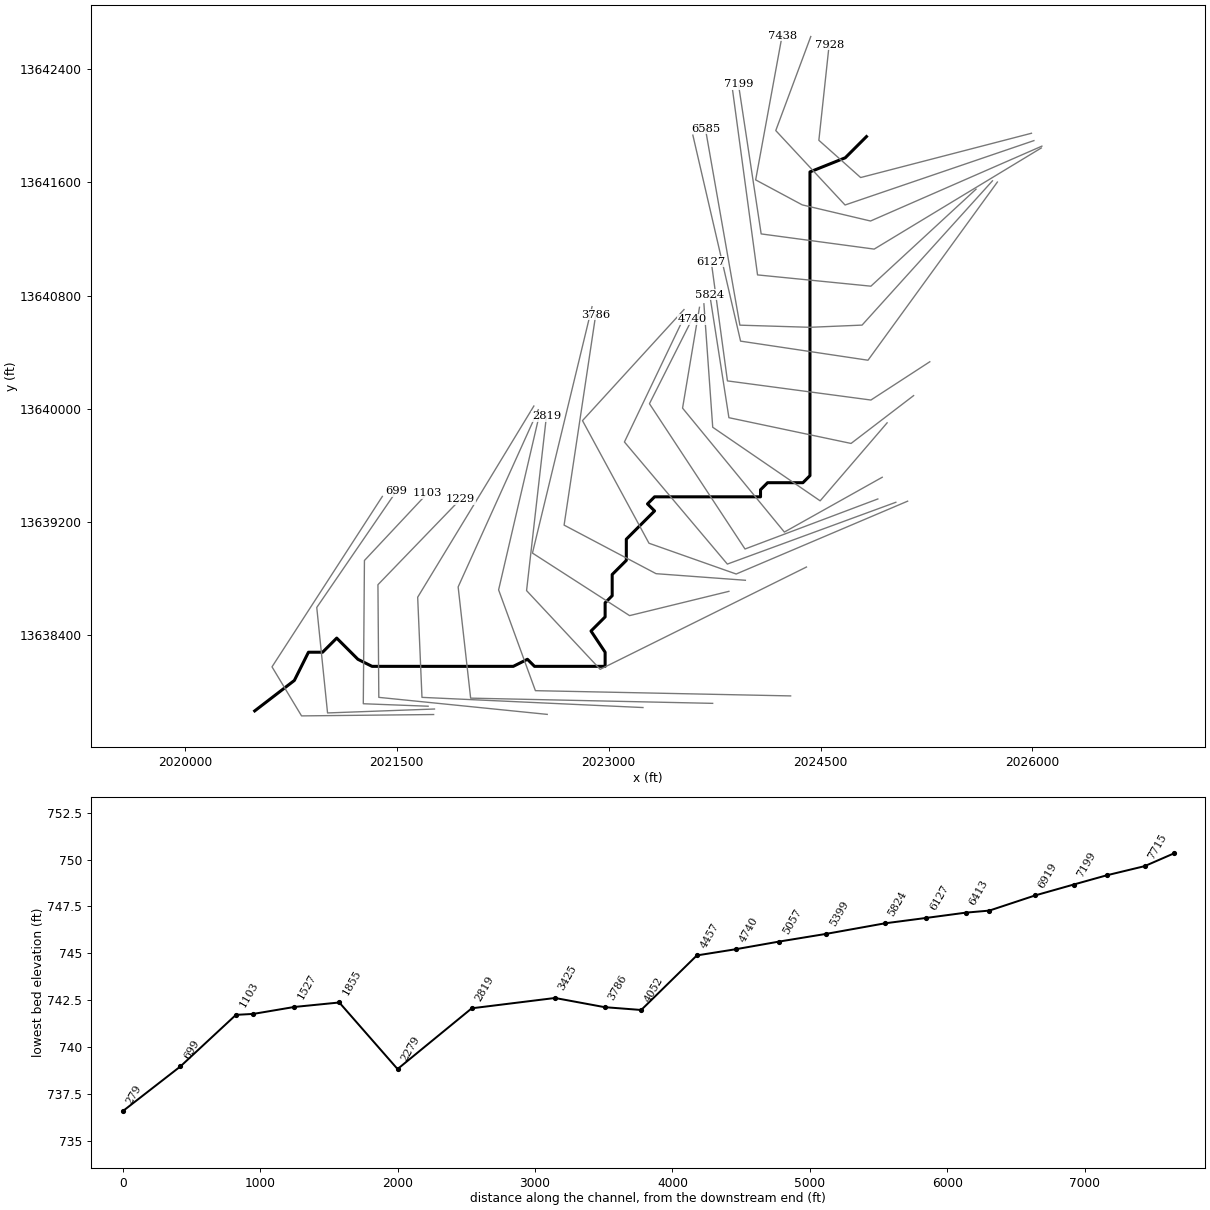
--- UNT 100 in HW.prj (project) ---

Proj Title=UNT 100 in HW Base Level Engineering
Current Plan=p01
Default Exp/Contr=0.3,0.1
English Units
Geom File=g01
Flow File=f01
Plan File=p01
BEGIN DESCRIPTION:
UNT 100 in HW
END DESCRIPTION:

--- UNT 100 in HW.p01 (plan) ---

Plan Title=Multiple Run
Short Identifier=Multiple
Geom File=g01
Flow File=f01
Subcritical Flow
K Sum by GR= 0
Std Step Tol= 0.01
Critical Tol= 0.01
Num of Std Step Trials= 20
Max Error Tol= 0.3
Flow Tol Ratio= 0.001
Split Flow NTrial= 30
Split Flow Tol= 0.02
Split Flow Ratio= 0.02
Log Output Level= 0
Friction Slope Method= 1
Unsteady Friction Slope Method= 2
Unsteady Bridges Friction Slope Method= 1
Parabolic Critical Depth
Global Vel Dist=  1 , 1 , 1
Global Log Level= 0
CheckData=True
Encroach Param= -1, 0, 0, 0
BEGIN DESCRIPTION:
Multiple Run
END DESCRIPTION:

--- UNT 100 in HW.f01 (steady flow) ---

Flow Title=Multiple
Number of Profiles=7
Profile Names=10-year,25-year,50-year,1pct_min,100-year,1pct_plu,500-year
River Rch & RM= UNT 100 in HW,Reach-1,7928
     293     383     451     263     525    1047     713
River Rch & RM= UNT 100 in HW,Reach-1,7438
     396     526     628     370     739    1474    1026
Boundary for River Rch & Prof#=UNT 100 in HW,Reach-1,1
Up Type=0
Dn Type=3
Dn Slope=0.005
Boundary for River Rch & Prof#=UNT 100 in HW,Reach-1,2
Up Type=0
Dn Type=3
Dn Slope=0.005
Boundary for River Rch & Prof#=UNT 100 in HW,Reach-1,3
Up Type=0
Dn Type=3
Dn Slope=0.005
Boundary for River Rch & Prof#=UNT 100 in HW,Reach-1,4
Up Type=0
Dn Type=3
Dn Slope=0.005
Boundary for River Rch & Prof#=UNT 100 in HW,Reach-1,5
Up Type=0
Dn Type=3
Dn Slope=0.005
Boundary for River Rch & Prof#=UNT 100 in HW,Reach-1,6
Up Type=0
Dn Type=3
Dn Slope=0.005
Boundary for River Rch & Prof#=UNT 100 in HW,Reach-1,7
Up Type=0
Dn Type=3
Dn Slope=0.005

--- UNT 100 in HW.g01 (geometry) ---

Geom Title=Existing Conditions

River Reach=UNT 100 in HW,Reach-1
Reach XY= 30
      2024825.00     13641925.00      2024675.00     13641775.00
      2024425.00     13641675.00      2024425.00     13639525.00
      2024375.00     13639475.00      2024125.00     13639475.00
      2024075.00     13639425.00      2024075.00     13639375.00
      2023325.00     13639375.00      2023275.00     13639325.00
      2023325.00     13639275.00      2023125.00     13639075.00
      2023125.00     13638925.00      2023025.00     13638825.00
      2023025.00     13638675.00      2022975.00     13638625.00
      2022975.00     13638525.00      2022875.00     13638425.00
      2022975.00     13638275.00      2022975.00     13638175.00
      2022475.00     13638175.00      2022425.00     13638225.00
      2022325.00     13638175.00      2021325.00     13638175.00
      2021225.00     13638225.00      2021075.00     13638375.00
      2020975.00     13638275.00      2020875.00     13638275.00
      2020775.00     13638075.00      2020494.51     13637859.57

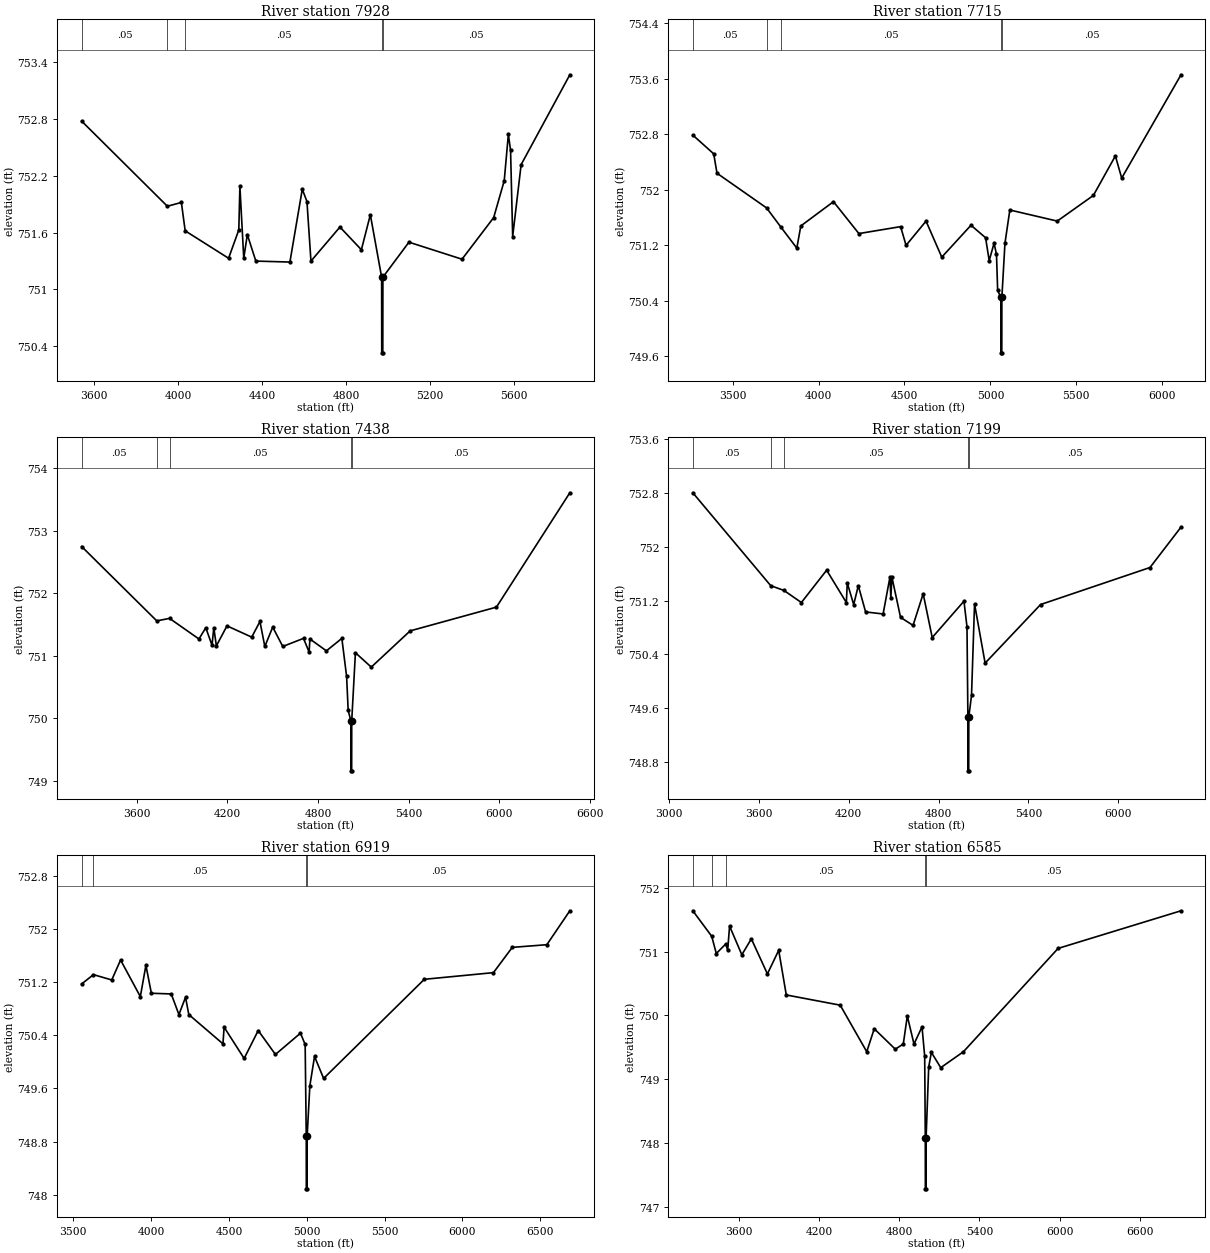
Type RM Length L Ch R = 1,7928,213,213,213
BEGIN DESCRIPTION:
UNT 100 in HW 4.0
END DESCRIPTION:
XS GIS Cut Line= 4
      2025992.78     13641948.52      2024783.65     13641635.05
      2024487.94     13641898.69      2024560.86     13642575.81
#Sta/Elev= 30
  3540.6  752.78  3949.1  751.88  4015.8  751.92  4034.0  751.62  4240.8  751.33
  4289.5  751.63  4294.7  752.09  4313.1  751.33  4330.1  751.58  4370.7  751.30
  4533.0  751.29  4592.0  752.06  4614.2  751.93  4633.3  751.30  4771.4  751.66
  4873.6  751.42  4916.3  751.79  4970.1  751.13  4970.6  750.33  4975.6  750.33
  4976.1  751.13  5100.2  751.50  5353.1  751.32  5504.0  751.76  5554.3  752.15
  5574.0  752.64  5584.5  752.47  5594.5  751.56  5634.8  752.32  5866.9  753.27
#Mann=5,-1,0
  3540.6    0.05       0  3949.1     0.1       0  4034.0    0.05       0
  4970.1   0.035       0  4976.1    0.05       0
Bank Sta=4970.1,4976.1
Exp/Cntr=0.3,0.1

Type RM Length L Ch R = 1,7715,277,277,277
BEGIN DESCRIPTION:
Mapping XS f14a80fd
END DESCRIPTION:
XS GIS Cut Line= 4
      2026010.20     13641896.45      2024673.36     13641440.71
      2024182.87     13641967.53      2024430.67     13642633.11
#Sta/Elev= 30
  3267.5  752.79  3389.2  752.52  3408.3  752.24  3697.0  751.74  3781.4  751.46
  3873.1  751.16  3896.3  751.48  4086.5  751.83  4234.4  751.37  4477.4  751.47
  4509.1  751.20  4625.4  751.55  4717.0  751.03  4887.1  751.49  4972.1  751.31
  4993.1  750.98  5021.4  751.23  5035.6  751.07  5042.4  750.55  5060.9  750.45
  5061.4  749.65  5066.4  749.65  5066.9  750.45  5084.9  751.23  5113.3  751.71
  5389.3  751.55  5599.7  751.92  5727.8  752.49  5764.6  752.17  6109.9  753.66
#Mann=5,-1,0
  3267.5    0.05       0  3697.0     0.1       0  3781.4    0.05       0
  5060.9   0.035       0  5066.9    0.05       0
Bank Sta=5060.9,5066.9
Exp/Cntr=0.3,0.1

Type RM Length L Ch R = 1,7438,239,239,239
BEGIN DESCRIPTION:
Mapping XS fb18851c
END DESCRIPTION:
XS GIS Cut Line= 5
      2026066.57     13641857.37      2024853.59     13641327.36
      2024370.37     13641441.49      2024040.57     13641618.45
      2024227.52     13642638.25
#Sta/Elev= 30
  3235.9  752.75  3733.2  751.56  3817.7  751.60  4012.4  751.27  4057.5  751.45
  4098.9  751.17  4110.6  751.45  4127.7  751.16  4197.9  751.48  4361.6  751.30
  4416.2  751.55  4448.3  751.15  4500.6  751.46  4567.2  751.15  4704.4  751.28
  4741.6  751.06  4746.7  751.27  4856.1  751.08  4958.2  751.28  4989.7  750.67
  5000.0  750.13  5017.6  749.96  5018.1  749.16  5023.1  749.16  5023.6  749.96
  5048.0  751.05  5153.0  750.82  5410.4  751.40  5981.4  751.78  6467.2  753.61
#Mann=5,-1,0
  3235.9    0.05       0  3733.2     0.1       0  3817.7    0.05       0
  5017.6   0.035       0  5023.6    0.05       0
Bank Sta=5017.6,5023.6
Exp/Cntr=0.3,0.1

Type RM Length L Ch R = 1,7199,280,280,280
BEGIN DESCRIPTION:
Mapping XS 8712b536
END DESCRIPTION:
XS GIS Cut Line= 4
      2026062.23     13641844.34      2024879.61     13641128.49
      2024079.53     13641236.02      2023918.93     13642294.53
#Sta/Elev= 30
  3158.9  752.80  3679.4  751.42  3767.0  751.35  3884.0  751.17  4052.7  751.65
  4184.3  751.17  4190.5  751.46  4233.2  751.14  4264.2  751.42  4312.9  751.03
  4429.8  751.00  4475.6  751.55  4481.4  751.23  4488.2  751.55  4546.2  750.95
  4629.7  750.83  4697.3  751.30  4757.8  750.65  4969.7  751.19  4989.9  750.81
  4996.0  749.47  4996.5  748.67  5001.5  748.67  5002.0  749.47  5020.2  749.79
  5040.4  751.15  5111.0  750.27  5481.4  751.14  6212.2  751.69  6419.2  752.29
#Mann=5,-1,0
  3158.9    0.05       0  3679.4     0.1       0  3767.0    0.05       0
  4996.0   0.035       0  5002.0    0.05       0
Bank Sta=4996,5002
Exp/Cntr=0.3,0.1

Type RM Length L Ch R = 1,6919,334,334,334
BEGIN DESCRIPTION:
Mapping XS c488cbb7
END DESCRIPTION:
XS GIS Cut Line= 4
      2025600.47     13641552.71      2024856.29     13640866.04
      2024053.86     13640945.85      2023877.46     13642251.42
#Sta/Elev= 30
  3554.0  751.17  3630.0  751.31  3747.4  751.23  3804.1  751.53  3931.1  750.98
  3966.9  751.45  4002.0  751.03  4129.6  751.02  4178.9  750.71  4221.5  750.97
  4242.5  750.71  4461.9  750.27  4469.3  750.52  4598.0  750.05  4688.5  750.47
  4799.0  750.11  4959.8  750.43  4990.0  750.26  4997.0  748.89  4997.5  748.09
  5002.5  748.09  5003.0  748.89  5020.1  749.64  5050.2  750.08  5108.6  749.75
  5755.6  751.24  6199.6  751.34  6320.6  751.72  6542.6  751.76  6690.4  752.27
#Mann=4,-1,0
  3554.0     0.1       0  3630.0    0.05       0  4997.0   0.035       0
  5003.0    0.05       0
Bank Sta=4997,5003
Exp/Cntr=0.3,0.1

Type RM Length L Ch R = 1,6585,172,172,172
BEGIN DESCRIPTION:
UNT 100 in HW 3.0
END DESCRIPTION:
XS GIS Cut Line= 5
      2025716.77     13641611.72      2024793.75     13640590.52
      2024425.00     13640575.00      2023928.99     13640590.07
      2023684.73     13641981.06
#Sta/Elev= 30
  3254.4  751.64  3396.0  751.24  3430.2  750.97  3501.3  751.12  3515.4  751.02
  3529.6  751.40  3621.5  750.95  3692.5  751.20  3812.8  750.65  3897.3  751.02
  3954.1  750.32  4357.6  750.16  4556.3  749.43  4612.4  749.79  4769.8  749.47
  4829.8  749.55  4859.9  749.99  4909.9  749.55  4970.0  749.82  4990.0  749.36
  4994.5  748.08  4995.0  747.28  5000.0  747.28  5000.5  748.08  5020.0  749.19
  5040.0  749.42  5110.1  749.18  5280.1  749.43  5988.6  751.05  6908.5  751.64
#Mann=5,-1,0
  3254.4    0.05       0  3396.0     0.1       0  3501.3    0.05       0
  4994.5   0.035       0  5000.5    0.05       0
Bank Sta=4994.5,5000.5
Exp/Cntr=0.3,0.1

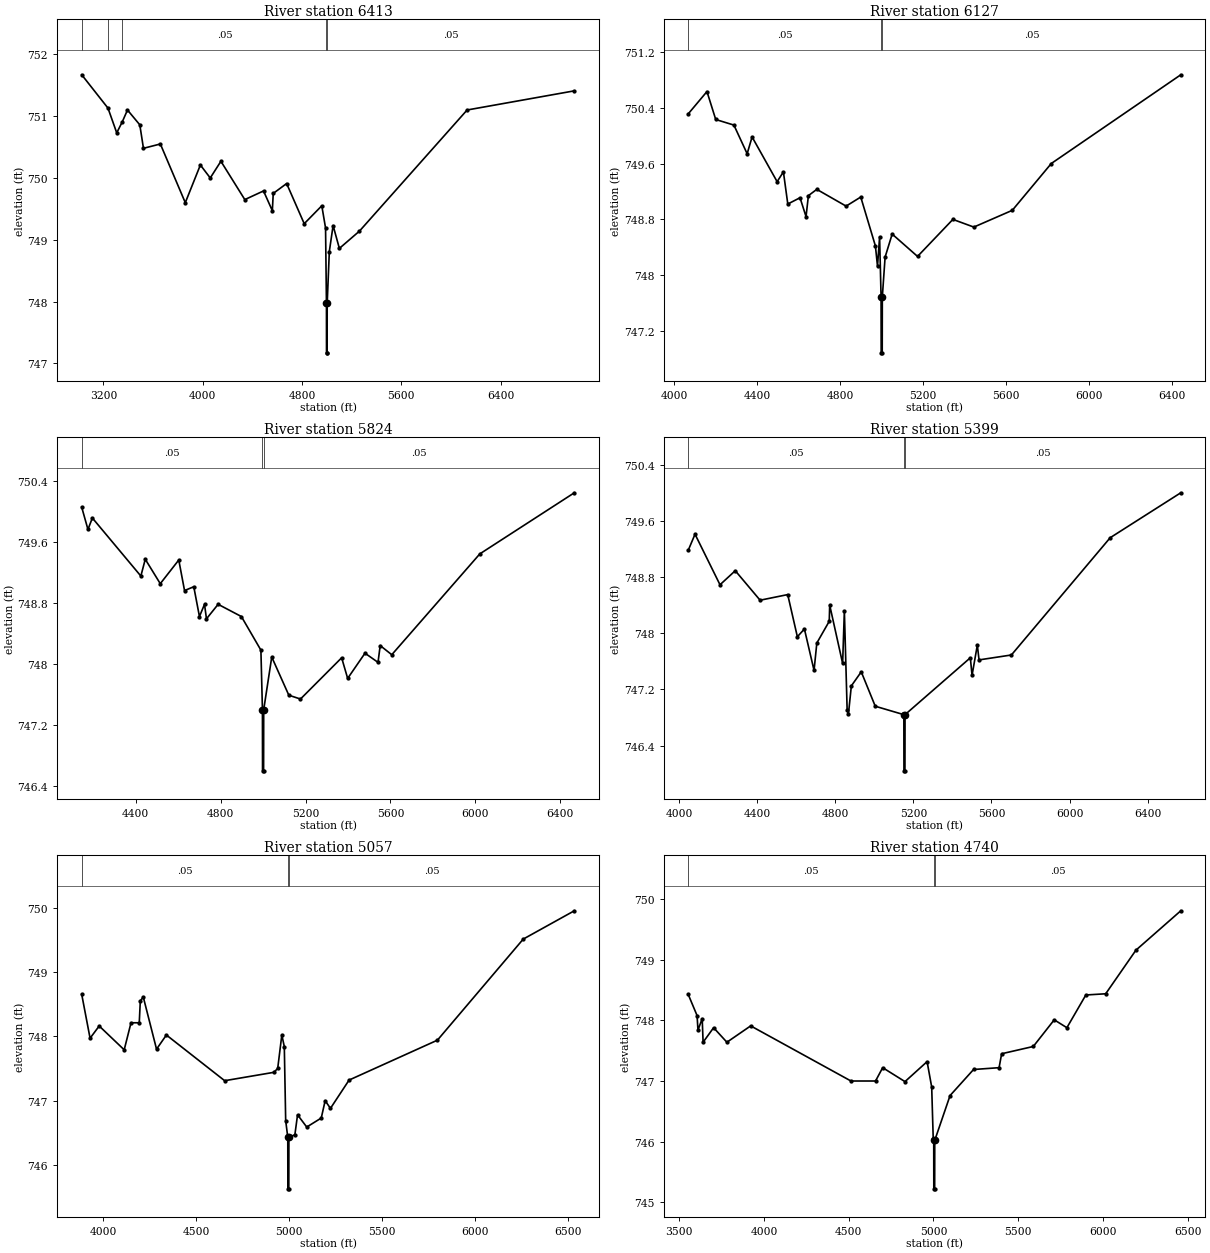
Type RM Length L Ch R = 1,6413,286,286,286
BEGIN DESCRIPTION:
Mapping XS d254e4c3
END DESCRIPTION:
XS GIS Cut Line= 4
      2025751.50     13641603.06      2024835.67     13640341.87
      2023933.81     13640477.04      2023596.02     13641935.14
#Sta/Elev= 30
  3026.1  751.67  3237.6  751.13  3308.0  750.73  3353.0  750.91  3394.5  751.10
  3493.8  750.86  3523.2  750.48  3659.3  750.55  3860.2  749.60  3981.6  750.21
  4061.2  750.00  4147.0  750.27  4339.5  749.65  4490.2  749.79  4561.3  749.47
  4568.5  749.75  4676.4  749.91  4818.0  749.26  4959.6  749.55  4989.9  749.19
  4997.0  747.97  4997.5  747.17  5002.5  747.17  5003.0  747.97  5020.2  748.81
  5050.6  749.23  5101.1  748.86  5262.9  749.14  6129.9  751.10  6993.4  751.41
#Mann=5,-1,0
  3026.1    0.05       0  3237.6     0.1       0  3353.0    0.05       0
  4997.0   0.035       0  5003.0    0.05       0
Bank Sta=4997,5003
Exp/Cntr=0.3,0.1

Type RM Length L Ch R = 1,6127,303,303,303
BEGIN DESCRIPTION:
Mapping XS d9c3b278
END DESCRIPTION:
XS GIS Cut Line= 4
      2025273.10     13640330.98      2024856.43     13640060.15
      2023840.81     13640195.57      2023726.22     13641039.36
#Sta/Elev= 30
  4067.8  750.31  4158.2  750.63  4200.4  750.23  4288.0  750.15  4351.8  749.74
  4375.6  749.98  4496.2  749.34  4526.5  749.48  4547.6  749.02  4606.5  749.11
  4635.5  748.84  4646.9  749.14  4687.3  749.23  4828.5  748.99  4899.1  749.12
  4969.7  748.42  4979.8  748.13  4989.9  748.55  4997.0  747.69  4997.5  746.89
  5002.5  746.89  5003.0  747.69  5016.4  748.26  5050.4  748.59  5172.7  748.27
  5343.0  748.80  5443.9  748.69  5629.2  748.93  5817.1  749.60  6440.9  750.87
#Mann=3,-1,0
  4067.8    0.05       0  4997.0   0.035       0  5003.0    0.05       0
Bank Sta=4997,5003
Exp/Cntr=0.3,0.1

Type RM Length L Ch R = 1,5824,425,425,425
BEGIN DESCRIPTION:
Mapping XS 05be5478
END DESCRIPTION:
XS GIS Cut Line= 4
      2025158.50     13640091.39      2024715.81     13639752.86
      2023851.23     13639935.15      2023715.80     13640804.98
#Sta/Elev= 30
  4145.5  750.05  4174.8  749.76  4195.6  749.91  4424.1  749.15  4444.9  749.37
  4515.6  749.05  4602.8  749.36  4629.9  748.96  4673.5  749.01  4700.2  748.62
  4724.1  748.78  4733.3  748.59  4788.2  748.78  4897.8  748.62  4989.8  748.18
  4997.0  747.40  4997.5  746.60  5002.5  746.60  5003.0  747.40  5040.9  748.09
  5121.4  747.59  5176.3  747.54  5370.3  748.08  5398.6  747.81  5480.3  748.14
  5541.7  748.02  5551.9  748.24  5606.5  748.12  6021.4  749.44  6466.7  750.24
#Mann=3,-1,0
  4145.5    0.05       0  4997.0   0.035       0  5003.0    0.05       0
Bank Sta=4997,5003
Exp/Cntr=0.3,0.1

Type RM Length L Ch R = 1,5399,342,342,342
BEGIN DESCRIPTION:
Mapping XS 359c1432
END DESCRIPTION:
XS GIS Cut Line= 4
      2024971.00     13639898.67      2024497.06     13639346.61
      2023736.64     13639867.44      2023674.23     13640741.24
#Sta/Elev= 30
  4045.2  749.18  4080.2  749.41  4208.2  748.69  4286.5  748.89  4413.8  748.47
  4555.4  748.55  4604.8  747.95  4641.0  748.06  4690.4  747.47  4704.6  747.86
  4768.3  748.17  4770.6  748.40  4836.9  747.57  4845.8  748.32  4860.1  746.90
  4866.7  746.85  4881.6  747.25  4932.4  747.45  5004.2  746.96  5150.8  746.84
  5151.3  746.04  5156.3  746.04  5156.8  746.84  5491.6  747.65  5500.4  747.40
  5527.4  747.83  5536.3  747.62  5702.1  747.69  6208.6  749.36  6570.5  750.00
#Mann=3,-1,0
  4045.2    0.05       0  5150.8   0.035       0  5156.8    0.05       0
Bank Sta=5150.8,5156.8
Exp/Cntr=0.3,0.1

Type RM Length L Ch R = 1,5057,317,317,317
BEGIN DESCRIPTION:
Mapping XS 400122d6
END DESCRIPTION:
XS GIS Cut Line= 4
      2024936.51     13639513.48      2024243.82     13639125.46
      2023523.10     13640002.86      2023642.88     13640716.35
#Sta/Elev= 30
  3883.1  748.65  3928.0  747.97  3977.2  748.16  4111.8  747.79  4148.5  748.21
  4192.9  748.21  4198.6  748.55  4214.6  748.61  4286.0  747.80  4339.0  748.02
  4652.9  747.31  4917.6  747.44  4938.5  747.50  4960.7  748.02  4974.1  747.84
  4981.5  746.69  4992.8  746.43  4993.3  745.63  4998.3  745.63  4998.8  746.43
  5031.0  746.47  5045.4  746.78  5094.9  746.59  5173.1  746.73  5194.1  747.00
  5222.6  746.88  5323.0  747.32  5798.8  747.94  6260.9  749.51  6536.0  749.95
#Mann=3,-1,0
  3883.1    0.05       0  4992.8   0.035       0  4998.8    0.05       0
Bank Sta=4992.8,4998.8
Exp/Cntr=0.3,0.1

Type RM Length L Ch R = 1,4740,283,283,283
BEGIN DESCRIPTION:
Mapping XS 60d01f12
END DESCRIPTION:
XS GIS Cut Line= 4
      2024905.31     13639359.85      2023965.17     13639005.67
      2023288.73     13640034.11      2023590.80     13640633.04
#Sta/Elev= 30
  3553.3  748.43  3605.7  748.08  3611.0  747.84  3635.9  748.03  3641.2  747.64
  3703.2  747.88  3781.6  747.64  3922.0  747.91  4513.7  747.00  4658.6  747.00
  4700.8  747.22  4832.4  746.99  4962.9  747.32  4990.0  746.90  4999.1  746.04
  5002.0  746.02  5002.5  745.22  5007.5  745.22  5008.0  746.02  5098.4  746.76
  5237.0  747.19  5387.6  747.22  5402.7  747.45  5589.4  747.57  5713.0  748.01
  5787.7  747.88  5899.5  748.42  6016.6  748.44  6195.1  749.16  6459.7  749.81
#Mann=3,-1,0
  3553.3    0.05       0  5002.0   0.035       0  5008.0    0.05       0
Bank Sta=5002,5008
Exp/Cntr=0.3,0.1

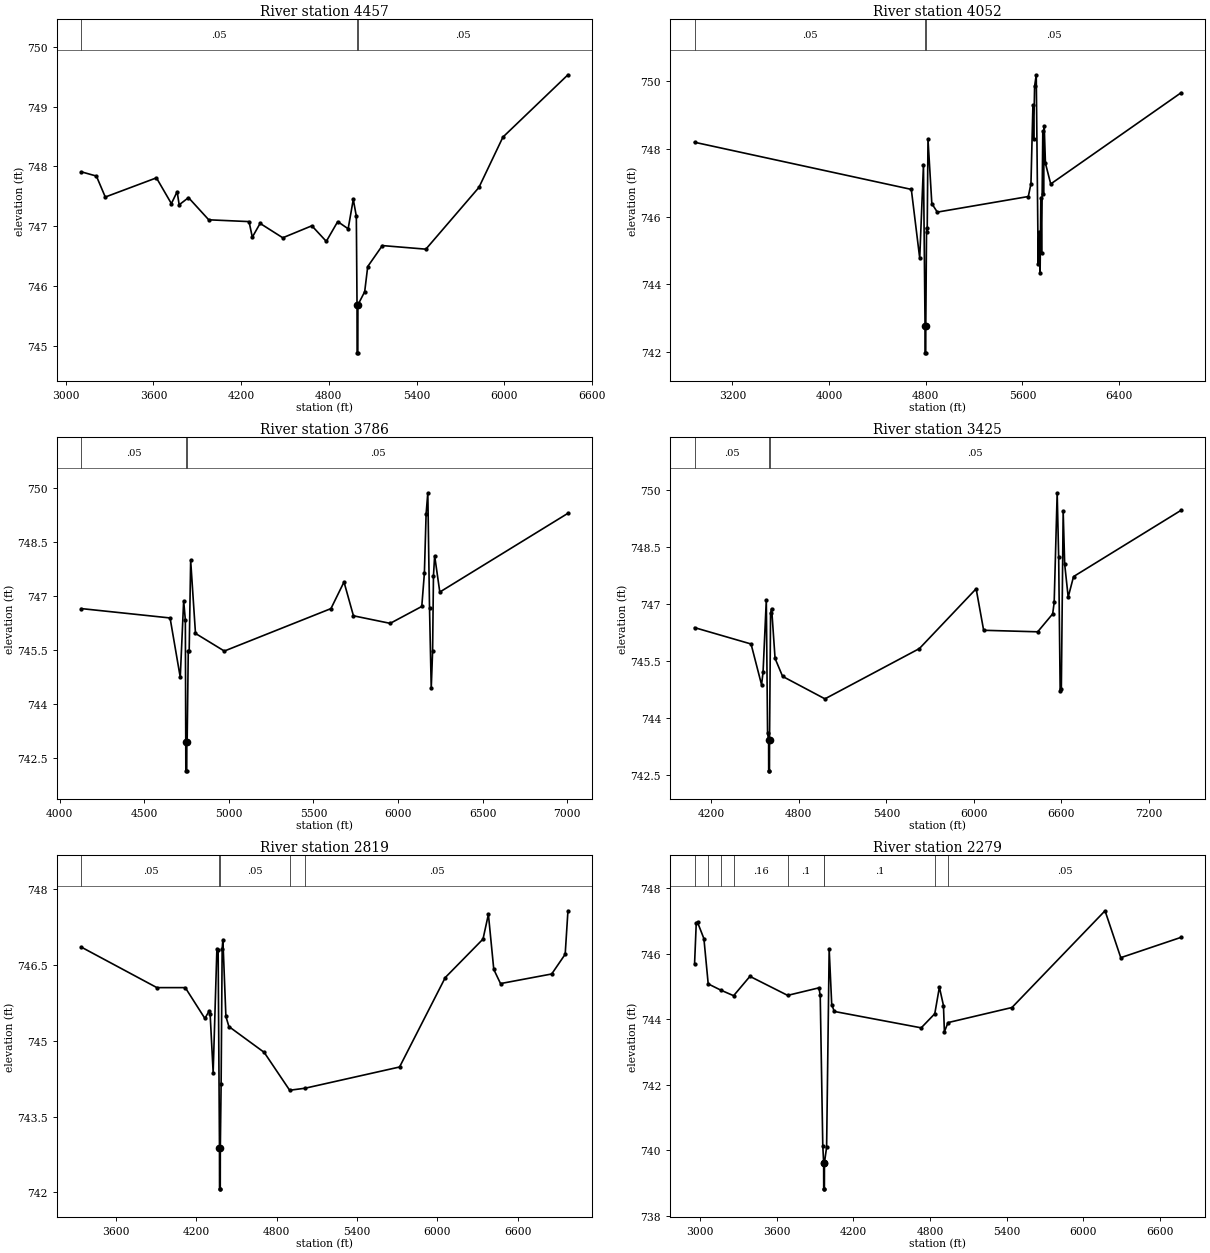
Type RM Length L Ch R = 1,4457,405,405,405
BEGIN DESCRIPTION:
Mapping XS 86d47b91
END DESCRIPTION:
XS GIS Cut Line= 4
      2025032.91     13639336.41      2023840.17     13638898.90
      2023111.64     13639763.27      2023512.25     13640600.91
#Sta/Elev= 30
  3106.9  747.91  3209.2  747.84  3270.2  747.49  3620.2  747.81  3722.5  747.38
  3762.0  747.58  3775.7  747.36  3839.6  747.48  3978.1  747.11  4253.9  747.08
  4276.3  746.82  4329.6  747.05  4484.8  746.81  4683.8  747.01  4782.6  746.75
  4860.7  747.08  4932.1  746.96  4967.3  747.45  4988.1  747.17  4992.9  745.69
  4993.4  744.89  4998.4  744.89  4998.9  745.69  5045.3  745.91  5066.1  746.33
  5166.2  746.68  5464.0  746.62  5827.0  747.65  5991.3  748.49  6436.3  749.53
#Mann=3,-1,0
  3106.9    0.05       0  4992.9   0.035       0  4998.9    0.05       0
Bank Sta=4992.9,4998.9
Exp/Cntr=0.3,0.1

Type RM Length L Ch R = 1,4052,266,266,266
BEGIN DESCRIPTION:
Mapping XS 0c6a51b9
END DESCRIPTION:
XS GIS Cut Line= 5
      2025116.24     13639344.22      2023902.67     13638828.59
      2023285.48     13639046.47      2022814.77     13639914.32
      2023533.18     13640700.41
#Sta/Elev= 30
  2887.5  748.19  4680.8  746.80  4750.4  744.77  4781.3  747.53  4794.4  742.78
  4794.9  741.98  4800.1  741.98  4800.6  742.78  4806.9  745.67  4812.2  745.55
  4818.7  748.28  4850.5  746.38  4895.9  746.13  5648.8  746.59  5670.7  746.97
  5686.9  749.29  5692.6  748.30  5700.8  749.84  5714.4  750.18  5730.6  744.59
  5736.3  745.53  5746.3  744.32  5752.5  746.56  5758.2  744.92  5768.7  748.53
  5774.3  746.66  5780.4  748.67  5790.5  747.57  5834.2  746.96  6912.8  749.65
#Mann=3,-1,0
  2887.5    0.05       0  4794.4   0.035       0  4800.6    0.05       0
Bank Sta=4794.4,4800.6
Exp/Cntr=0.3,0.1

Type RM Length L Ch R = 1,3786,361,361,361
BEGIN DESCRIPTION:
Mapping XS 26bf1d9d
END DESCRIPTION:
XS GIS Cut Line= 4
      2023967.73     13638784.32      2023335.60     13638830.98
      2022684.56     13639174.73      2022908.52     13640664.32
#Sta/Elev= 30
  4128.0  746.64  4652.1  746.38  4712.3  744.73  4732.4  746.86  4742.4  746.32
  4744.8  742.93  4745.3  742.13  4750.6  742.13  4751.1  742.93  4753.0  742.94
  4759.6  745.45  4765.0  745.45  4773.8  747.98  4802.3  745.95  4972.8  745.46
  5603.2  746.64  5680.4  747.38  5736.2  746.44  5953.4  746.23  6140.2  746.70
  6155.6  747.62  6165.8  749.27  6175.9  749.86  6186.0  746.66  6196.1  744.42
  6204.2  745.46  6209.3  747.55  6216.3  748.11  6246.7  747.10  7004.4  749.29
#Mann=3,-1,0
  4128.0    0.05       0  4744.8   0.035       0  4751.1    0.05       0
Bank Sta=4744.8,4751.1
Exp/Cntr=0.3,0.1

Type RM Length L Ch R = 1,3425,606,606,606
BEGIN DESCRIPTION:
Mapping XS 8ef4213a
END DESCRIPTION:
XS GIS Cut Line= 4
      2023851.20     13638705.98      2023148.10     13638534.11
      2022460.60     13638976.82      2022882.29     13640720.85
#Sta/Elev= 30
  4085.2  746.38  4472.5  745.95  4544.5  744.88  4554.8  745.21  4577.1  747.11
  4585.7  743.61  4592.9  743.42  4593.4  742.62  4598.7  742.62  4599.2  743.42
  4606.3  746.76  4613.6  746.88  4637.2  745.57  4688.7  745.10  4979.2  744.51
  5626.7  745.83  6015.8  747.40  6067.2  746.31  6437.7  746.27  6540.5  746.74
  6550.8  747.04  6571.4  749.92  6581.6  748.24  6591.9  744.72  6599.9  744.76
  6612.5  749.44  6622.8  748.05  6646.9  747.18  6683.6  747.72  7421.0  749.46
#Mann=3,-1,0
  4085.2    0.05       0  4592.9   0.035       0  4599.2    0.05       0
Bank Sta=4592.9,4599.2
Exp/Cntr=0.3,0.1

Type RM Length L Ch R = 1,2819,540,540,540
BEGIN DESCRIPTION:
Mapping XS 13ea92a8
END DESCRIPTION:
XS GIS Cut Line= 4
      2024400.09     13638878.07      2022939.77     13638153.90
      2022418.93     13638711.19      2022559.56     13639945.60
#Sta/Elev= 30
  3341.1  746.85  3905.0  746.05  4117.0  746.05  4263.6  745.44  4295.6  745.59
  4302.9  745.52  4325.3  744.37  4353.3  746.82  4362.5  746.79  4372.6  742.87
  4373.1  742.07  4378.4  742.07  4378.9  742.87  4384.8  744.14  4392.6  746.82
  4398.1  747.00  4420.5  745.48  4443.0  745.28  4706.4  744.77  4897.0  744.02
  5012.1  744.06  5718.1  744.48  6059.8  746.25  6341.6  747.01  6381.9  747.50
  6422.1  746.41  6472.5  746.13  6854.9  746.32  6955.6  746.71  6976.3  747.57
#Mann=5,-1,0
  3341.1    0.05       0  4372.6    0.07       0  4378.9    0.05       0
  4897.0    0.08       0  5012.1    0.05       0
Bank Sta=4372.6,4378.9
Exp/Cntr=0.3,0.1

Type RM Length L Ch R = 1,2279,424,424,424
BEGIN DESCRIPTION:
Mapping XS 48535b4f
END DESCRIPTION:
XS GIS Cut Line= 4
      2024288.08     13637965.74      2022481.43     13638002.86
      2022221.02     13638716.40      2022502.26     13639924.70
#Sta/Elev= 30
  2956.5  745.69  2969.6  746.93  2979.6  746.96  3029.6  746.46  3063.2  745.08
  3161.7  744.89  3262.1  744.72  3389.7  745.31  3684.8  744.73  3929.8  744.96
  3939.8  744.73  3959.8  740.15  3966.6  739.63  3967.1  738.83  3972.4  738.83
  3972.9  739.63  3989.8  740.10  4009.8  746.14  4029.8  744.45  4049.8  744.24
  4730.0  743.74  4836.2  744.17  4872.3  744.98  4904.2  744.42  4911.5  743.62
  4939.9  743.90  5440.2  744.36  6168.5  747.31  6291.7  745.88  6763.7  746.50
#Mann=9,-1,0
  2956.5    0.08       0  3063.2    0.05       0  3161.7    0.08       0
  3262.1    0.16       0  3684.8     0.1       0  3966.6   0.035       0
  3972.9     0.1       0  4836.2    0.08       0  4939.9    0.05       0
Bank Sta=3966.6,3972.9
Exp/Cntr=0.3,0.1

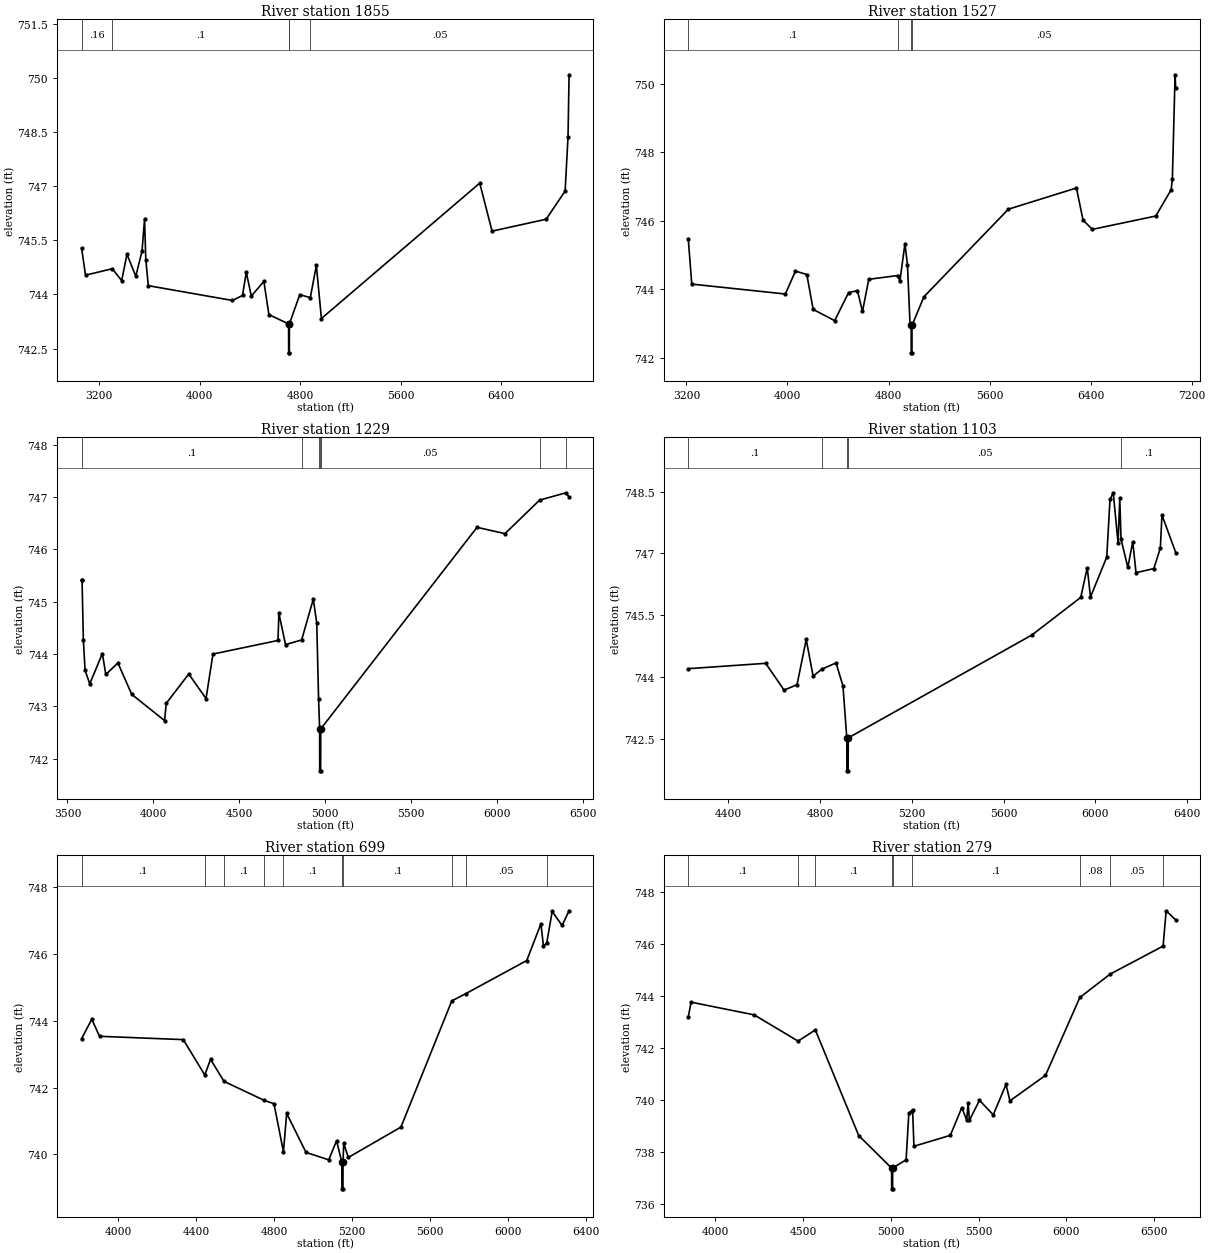
Type RM Length L Ch R = 1,1855,328,328,328
BEGIN DESCRIPTION:
Mapping XS e508413d
END DESCRIPTION:
XS GIS Cut Line= 4
      2023736.19     13637913.07      2022023.04     13637949.97
      2021934.56     13638737.23      2022501.73     13639991.26
#Sta/Elev= 30
  3060.0  745.28  3091.2  744.53  3304.2  744.71  3379.0  744.38  3421.3  745.11
  3491.3  744.50  3541.3  745.20  3561.3  746.08  3571.3  744.96  3591.3  744.24
  4261.5  743.83  4341.5  743.97  4371.5  744.61  4411.5  743.95  4511.5  744.36
  4551.5  743.44  4708.4  743.18  4708.9  742.38  4714.2  742.38  4714.7  743.18
  4797.2  743.99  4881.4  743.91  4929.6  744.80  4969.8  743.33  6230.7  747.08
  6328.7  745.75  6759.6  746.08  6910.7  746.86  6933.8  748.37  6942.1  750.08
#Mann=5,-1,0
  3060.0    0.16       0  3304.2     0.1       0  4708.4   0.035       0
  4714.7     0.1       0  4881.4    0.05       0
Bank Sta=4708.4,4714.7
Exp/Cntr=0.3,0.1

Type RM Length L Ch R = 1,1527,298,298,298
BEGIN DESCRIPTION:
Mapping XS c3756776
END DESCRIPTION:
XS GIS Cut Line= 4
      2023242.87     13637883.39      2021678.57     13637955.47
      2021648.10     13638664.32      2022470.51     13640017.66
#Sta/Elev= 30
  3214.3  745.48  3242.2  744.15  3983.0  743.86  4063.1  744.53  4153.2  744.43
  4203.2  743.41  4373.4  743.08  4483.5  743.90  4553.6  743.96  4593.6  743.35
  4643.7  744.29  4871.5  744.40  4889.9  744.24  4929.9  745.33  4950.0  744.70
  4970.0  742.99  4979.2  742.94  4979.7  742.14  4985.0  742.14  4985.5  742.94
  5080.1  743.78  5748.8  746.34  6287.5  746.96  6339.8  746.02  6413.4  745.75
  6915.3  746.14  7037.5  746.91  7046.9  747.22  7068.4  750.27  7073.4  749.88
#Mann=4,-1,0
  3214.3     0.1       0  4871.5    0.05       0  4979.2   0.035       0
  4985.5    0.05       0
Bank Sta=4979.2,4985.5
Exp/Cntr=0.3,0.1

Type RM Length L Ch R = 1,1229,126,126,126
BEGIN DESCRIPTION:
Mapping XS 20642076
END DESCRIPTION:
XS GIS Cut Line= 4
      2022565.10     13637835.00      2021373.01     13637955.47
      2021366.85     13638752.86      2021950.12     13639356.96
#Sta/Elev= 30
  3582.3  745.41  3584.9  745.41  3592.5  744.27  3602.5  743.69  3629.8  743.43
  3703.0  744.01  3723.1  743.61  3793.5  743.83  3873.9  743.23  4064.8  742.73
  4074.9  743.06  4205.6  743.62  4306.1  743.15  4346.3  744.00  4724.6  744.26
  4729.7  744.78  4768.4  744.18  4862.2  744.27  4930.0  745.05  4950.0  744.59
  4960.7  743.14  4966.8  742.57  4967.3  741.77  4972.6  741.77  4973.1  742.57
  5882.2  746.42  6044.8  746.30  6246.3  746.94  6399.7  747.08  6417.6  747.00
#Mann=7,-1,0
  3582.3     0.1       0  4862.2    0.08       0  4960.7    0.05       0
  4966.8   0.035       0  4973.1    0.05       0  6246.3     0.1       0
  6399.7    0.05       0
Bank Sta=4966.8,4973.1
Exp/Cntr=0.3,0.1

Type RM Length L Ch R = 1,1103,404,404,404
BEGIN DESCRIPTION:
Mapping XS e62587a5
END DESCRIPTION:
XS GIS Cut Line= 4
      2021722.08     13637892.76      2021263.20     13637910.33
      2021271.27     13638924.32      2021715.84     13639398.72
#Sta/Elev= 30
  4226.1  744.20  4563.4  744.33  4643.5  743.68  4700.0  743.81  4740.0  744.91
  4770.0  744.02  4808.8  744.19  4870.0  744.34  4900.0  743.78  4916.8  742.52
  4917.3  741.72  4922.6  741.72  4923.1  742.52  5723.8  745.02  5935.8  745.93
  5964.1  746.65  5978.3  745.94  6049.1  746.91  6063.3  748.31  6077.4  748.47
  6098.5  747.25  6105.8  748.34  6111.4  747.34  6140.9  746.66  6162.4  747.28
  6176.6  746.53  6254.3  746.63  6282.6  747.13  6289.6  747.93  6349.5  747.02
#Mann=5,-1,0
  4226.1     0.1       0  4808.8    0.05       0  4916.8   0.035       0
  4923.1    0.05       0  6111.4     0.1       0
Bank Sta=4916.8,4923.1
Exp/Cntr=0.3,0.1

Type RM Length L Ch R = 1,699,420,420,420
BEGIN DESCRIPTION:
Mapping XS 76469b84
END DESCRIPTION:
XS GIS Cut Line= 4
      2021767.13     13637873.00      2021010.16     13637845.22
      2020933.78     13638591.75      2021497.09     13639414.36
#Sta/Elev= 30
  3810.5  743.47  3862.7  744.05  3902.7  743.54  4333.0  743.44  4443.5  742.38
  4473.1  742.85  4541.9  742.19  4749.0  741.62  4799.0  741.52  4847.7  740.08
  4864.3  741.23  4963.7  740.06  5080.4  739.84  5120.6  740.41  5147.6  739.77
  5148.1  738.97  5153.4  738.97  5153.9  739.77  5157.4  740.33  5180.9  739.91
  5451.5  740.82  5712.7  744.60  5785.6  744.82  6098.0  745.81  6170.7  746.91
  6183.9  746.23  6200.7  746.34  6228.7  747.28  6279.5  746.86  6315.4  747.30
#Mann=10,-1,0
  3810.5     0.1       0  4443.5    0.05       0  4541.9     0.1       0
  4749.0    0.05       0  4847.7     0.1       0  5147.6    0.07       0
  5153.9     0.1       0  5712.7    0.08       0  5785.6    0.05       0
  6200.7     0.1       0
Bank Sta=5147.6,5153.9
Exp/Cntr=0.3,0.1

Type RM Length L Ch R = 1,279,0,0,0
BEGIN DESCRIPTION:
UNT 100 in HW 1.0
END DESCRIPTION:
XS GIS Cut Line= 4
      2021761.07     13637833.94      2020826.10     13637824.30
      2020616.98     13638171.51      2021398.10     13639377.86
#Sta/Elev= 30
  3845.1  743.19  3861.2  743.77  4221.2  743.28  4471.0  742.27  4569.3  742.70
  4816.6  738.63  5003.7  737.38  5004.2  736.58  5009.5  736.58  5010.0  737.38
  5086.5  737.70  5102.0  739.50  5117.3  739.57  5123.4  739.62  5131.1  738.22
  5338.4  738.64  5404.0  739.71  5432.0  739.22  5439.8  739.90  5447.2  739.22
  5504.5  739.99  5583.0  739.43  5655.6  740.60  5678.0  739.97  5880.6  740.95
  6076.3  743.95  6249.0  744.85  6550.7  745.93  6568.2  747.29  6622.6  746.94
#Mann=9,-1,0
  3845.1     0.1       0  4471.0    0.05       0  4569.3     0.1       0
  5003.7    0.07       0  5010.0     0.1       0  5117.3     0.1       0
  6076.3    0.08       0  6249.0    0.05       0  6550.7     0.1       0
Bank Sta=5003.7,5010
Exp/Cntr=0.3,0.1

Chan Stop Cuts=-1