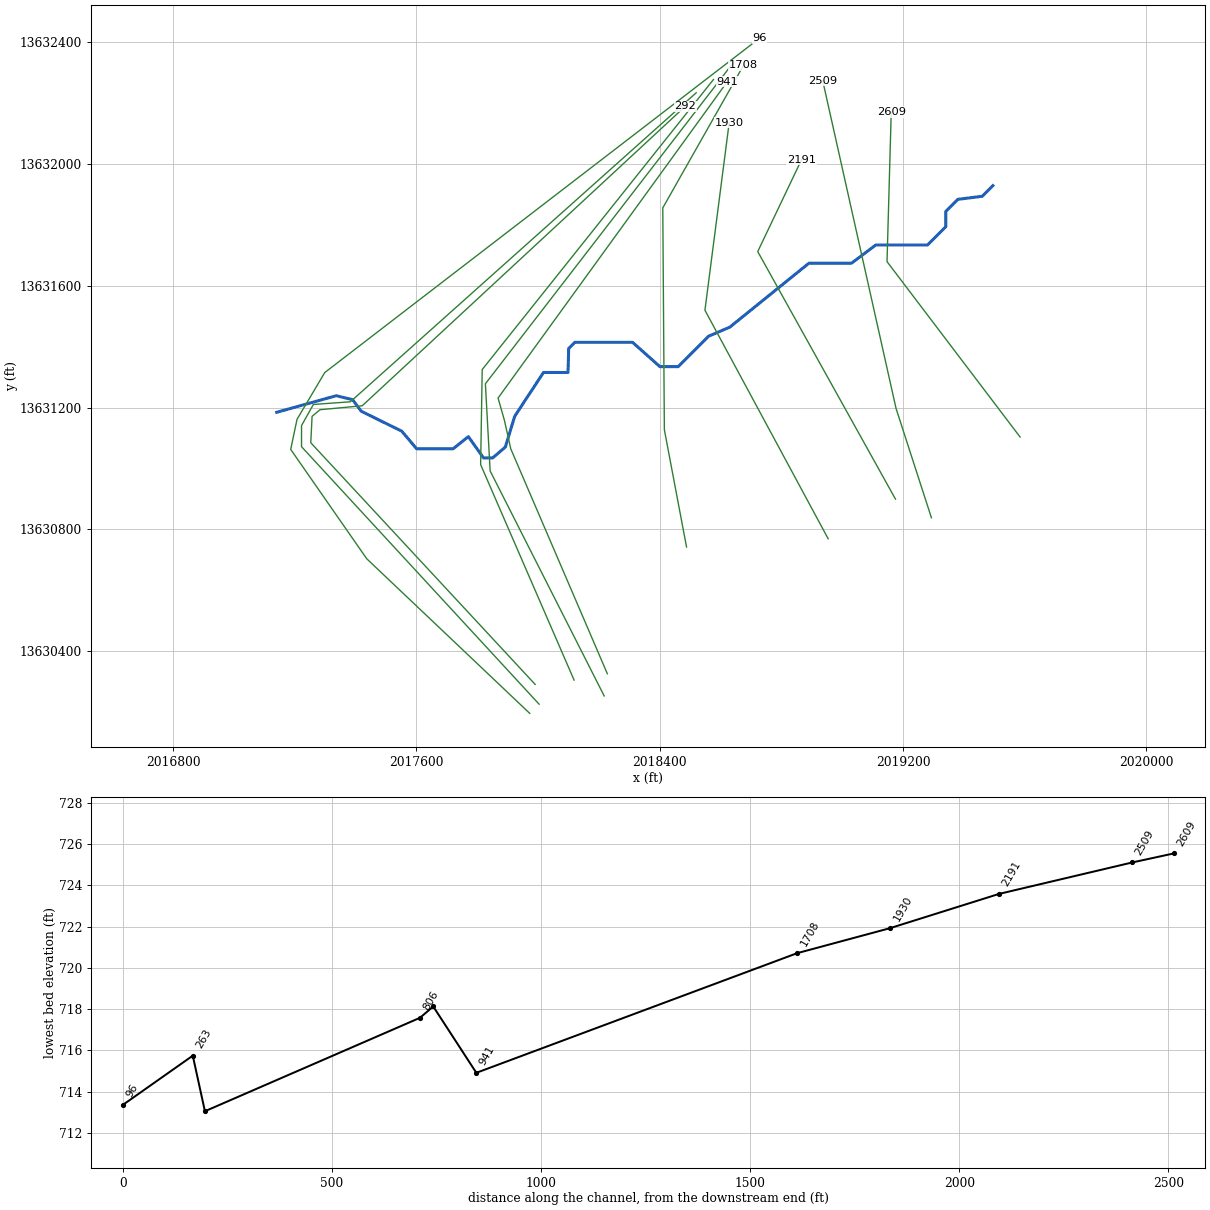
--- UNT 101 in HW.prj (project) ---

Proj Title=UNT 101 in HW Base Level Engineering
Current Plan=p01
Default Exp/Contr=0.3,0.1
English Units
Geom File=g01
Flow File=f01
Plan File=p01
BEGIN DESCRIPTION:
UNT 101 in HW
END DESCRIPTION:

--- UNT 101 in HW.p01 (plan) ---

Plan Title=Multiple Run
Short Identifier=Multiple
Geom File=g01
Flow File=f01
Subcritical Flow
K Sum by GR= 0
Std Step Tol= 0.01
Critical Tol= 0.01
Num of Std Step Trials= 20
Max Error Tol= 0.3
Flow Tol Ratio= 0.001
Split Flow NTrial= 30
Split Flow Tol= 0.02
Split Flow Ratio= 0.02
Log Output Level= 0
Friction Slope Method= 1
Unsteady Friction Slope Method= 2
Unsteady Bridges Friction Slope Method= 1
Parabolic Critical Depth
Global Vel Dist=  1 , 1 , 1
Global Log Level= 0
CheckData=True
Encroach Param= -1, 0, 0, 0
BEGIN DESCRIPTION:
Multiple Run
END DESCRIPTION:

--- UNT 101 in HW.f01 (steady flow) ---

Flow Title=Multiple
Number of Profiles=7
Profile Names=10-year,25-year,50-year,1pct_min,100-year,1pct_plu,500-year
River Rch & RM= UNT 101 in HW,Reach-1,2609
     466     640     781     472     942    1879    1372
Boundary for River Rch & Prof#=UNT 101 in HW,Reach-1,1
Up Type=0
Dn Type=3
Dn Slope=0.005
Boundary for River Rch & Prof#=UNT 101 in HW,Reach-1,2
Up Type=0
Dn Type=3
Dn Slope=0.005
Boundary for River Rch & Prof#=UNT 101 in HW,Reach-1,3
Up Type=0
Dn Type=3
Dn Slope=0.005
Boundary for River Rch & Prof#=UNT 101 in HW,Reach-1,4
Up Type=0
Dn Type=3
Dn Slope=0.005
Boundary for River Rch & Prof#=UNT 101 in HW,Reach-1,5
Up Type=0
Dn Type=3
Dn Slope=0.005
Boundary for River Rch & Prof#=UNT 101 in HW,Reach-1,6
Up Type=0
Dn Type=3
Dn Slope=0.005
Boundary for River Rch & Prof#=UNT 101 in HW,Reach-1,7
Up Type=0
Dn Type=3
Dn Slope=0.005

--- UNT 101 in HW.g01 (geometry) ---

Geom Title=Existing Conditions

River Reach=UNT 101 in HW,Reach-1
Reach XY= 30
      2019495.80     13631929.54      2019460.80     13631894.54
      2019380.80     13631884.54      2019340.80     13631844.54
      2019340.80     13631794.54      2019280.80     13631734.54
      2019110.80     13631734.54      2019030.80     13631674.54
      2018890.80     13631674.54      2018630.80     13631464.54
      2018560.80     13631434.54      2018460.80     13631334.54
      2018400.80     13631334.54      2018310.80     13631414.54
      2018120.80     13631414.54      2018100.80     13631394.54
      2018098.53     13631315.36      2018017.81     13631315.36
      2017923.19     13631171.27      2017892.40     13631070.22
      2017850.80     13631034.54      2017820.80     13631034.54
      2017770.80     13631104.54      2017720.80     13631064.54
      2017600.80     13631064.54      2017551.66     13631122.65
      2017418.85     13631187.76      2017390.20     13631225.95
      2017336.38     13631238.97      2017140.80     13631184.54

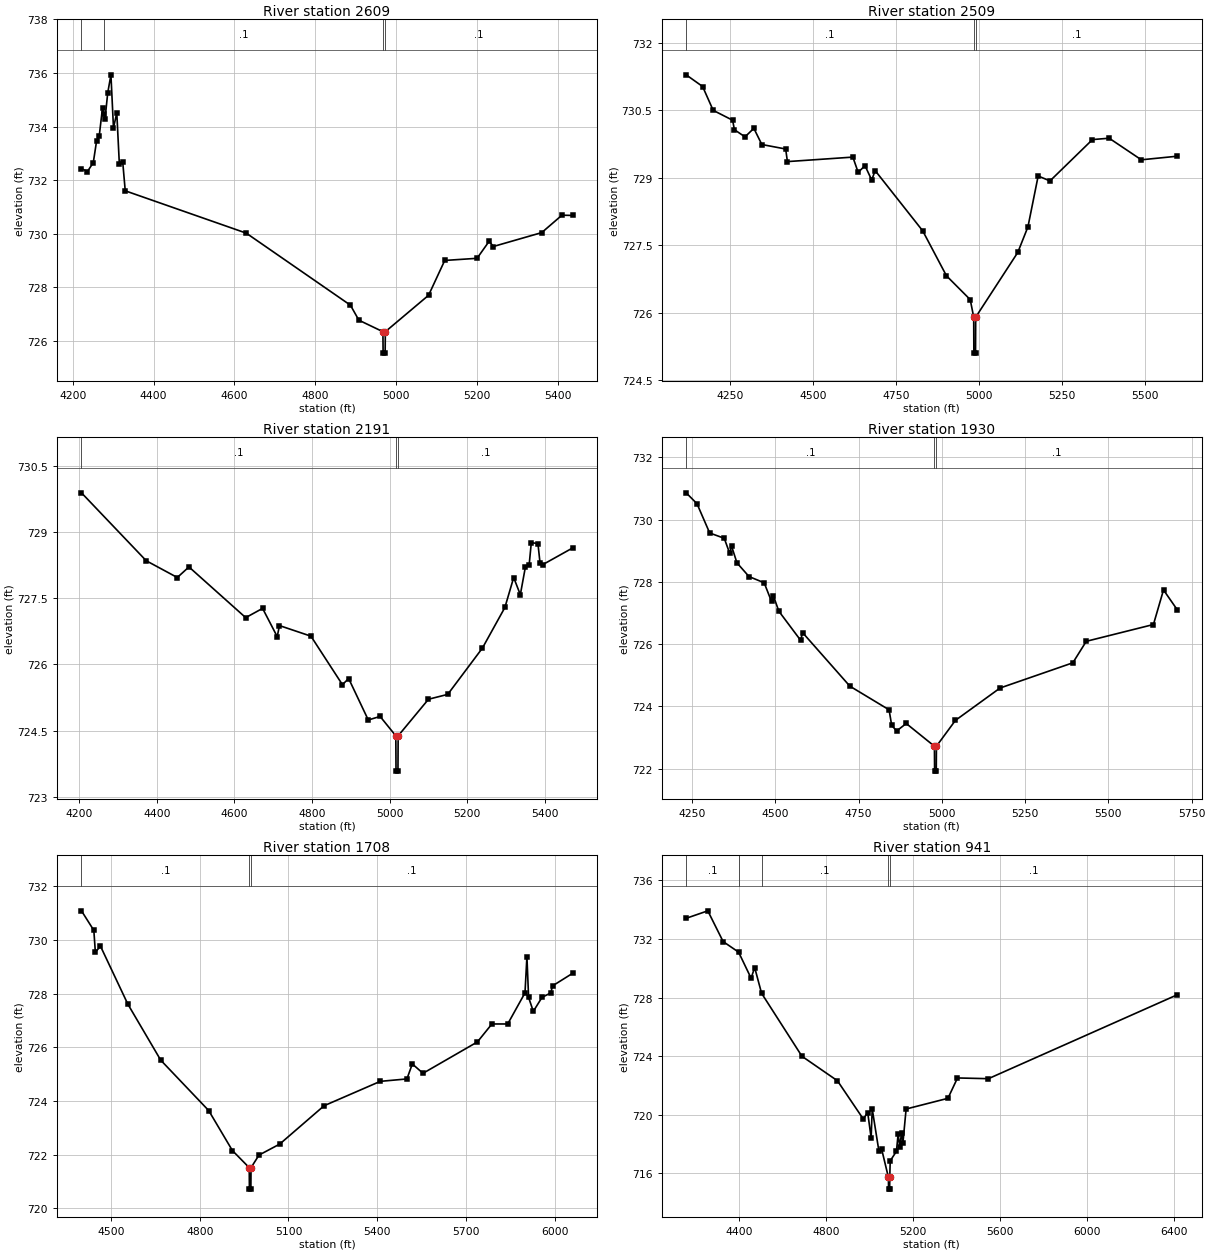
Type RM Length L Ch R = 1,2609,100,100,100
BEGIN DESCRIPTION:
UNT 101 in HW 2.0
END DESCRIPTION:
XS GIS Cut Line= 3
      2019585.09     13631103.30      2019147.58     13631679.70
      2019161.43     13632171.36
#Sta/Elev= 30
  4221.5  732.43  4236.2  732.32  4250.7  732.65  4259.0  733.47  4265.3  733.63
  4273.6  734.70  4276.9  734.48  4279.8  734.28  4286.4  735.25  4294.4  735.93
  4300.7  733.95  4308.9  734.51  4315.2  732.61  4323.5  732.69  4329.8  731.60
  4629.3  730.02  4887.1  727.33  4908.0  726.77  4967.5  726.34  4968.0  725.54
  4973.0  725.54  4973.5  726.34  5080.5  727.70  5120.5  729.00  5200.5  729.08
  5230.6  729.72  5240.6  729.52  5360.6  730.04  5410.6  730.69  5437.0  730.68
#Mann=4,-1,0
  4221.5    0.16       0  4276.9     0.1       0  4967.5    0.07       0
  4973.5     0.1       0
Bank Sta=4967.5,4973.5
Exp/Cntr=0.3,0.1

Type RM Length L Ch R = 1,2509,318,318,318
BEGIN DESCRIPTION:
Mapping XS d14f30e9
END DESCRIPTION:
XS GIS Cut Line= 3
      2019293.57     13630837.81      2019177.27     13631197.15
      2018936.00     13632274.78
#Sta/Elev= 30
  4116.7  731.29  4166.3  731.03  4198.2  730.50  4256.9  730.28  4262.2  730.07
  4294.2  729.91  4320.9  730.10  4345.0  729.74  4416.9  729.64  4422.2  729.36
  4619.7  729.46  4635.7  729.12  4656.2  729.27  4676.6  728.95  4686.9  729.16
  4830.4  727.82  4902.1  726.82  4973.8  726.29  4984.3  725.90  4984.8  725.10
  4989.8  725.10  4990.3  725.90  5117.3  727.34  5148.0  727.91  5178.8  729.04
  5214.4  728.93  5342.7  729.85  5393.1  729.88  5490.1  729.40  5598.7  729.48
#Mann=3,-1,0
  4116.7     0.1       0  4984.3    0.07       0  4990.3     0.1       0
Bank Sta=4984.3,4990.3
Exp/Cntr=0.3,0.1

Type RM Length L Ch R = 1,2191,261,261,261
BEGIN DESCRIPTION:
Mapping XS c391676f
END DESCRIPTION:
XS GIS Cut Line= 3
      2019175.36     13630899.15      2018722.40     13631712.77
      2018866.50     13632014.85
#Sta/Elev= 30
  4206.0  729.89  4372.9  728.35  4453.0  727.97  4483.0  728.21  4629.3  727.06
  4672.8  727.27  4710.5  726.63  4716.3  726.88  4797.4  726.64  4878.6  725.54
  4894.6  725.68  4945.2  724.74  4975.7  724.82  5016.2  724.38  5016.7  723.58
  5021.7  723.58  5022.2  724.38  5100.4  725.21  5150.0  725.32  5239.4  726.37
  5297.3  727.29  5320.0  727.97  5337.1  727.58  5350.2  728.21  5359.8  728.25
  5365.4  728.76  5382.5  728.74  5388.0  728.29  5394.5  728.26  5471.9  728.64
#Mann=3,-1,0
  4206.0     0.1       0  5016.2    0.07       0  5022.2     0.1       0
Bank Sta=5016.2,5022.2
Exp/Cntr=0.3,0.1

Type RM Length L Ch R = 1,1930,222,222,222
BEGIN DESCRIPTION:
Mapping XS a407a26e
END DESCRIPTION:
XS GIS Cut Line= 3
      2018954.03     13630768.89      2018548.79     13631520.06
      2018628.50     13632136.11
#Sta/Elev= 30
  4232.3  730.86  4264.8  730.51  4302.9  729.57  4346.6  729.40  4362.9  728.92
  4368.5  729.15  4384.8  728.61  4421.0  728.17  4466.5  727.97  4488.5  727.37
  4494.2  727.55  4510.4  727.06  4576.1  726.12  4581.8  726.37  4723.7  724.65
  4841.5  723.89  4849.4  723.39  4864.2  723.21  4893.1  723.45  4977.7  722.72
  4978.2  721.92  4983.2  721.92  4983.7  722.72  5040.7  723.55  5174.8  724.59
  5393.3  725.40  5433.6  726.09  5635.3  726.63  5665.5  727.74  5707.0  727.10
#Mann=3,-1,0
  4232.3     0.1       0  4977.7    0.07       0  4983.7     0.1       0
Bank Sta=4977.7,4983.7
Exp/Cntr=0.3,0.1

Type RM Length L Ch R = 1,1708,767,767,767
BEGIN DESCRIPTION:
Mapping XS fe416771
END DESCRIPTION:
XS GIS Cut Line= 4
      2018488.31     13630741.78      2018415.39     13631127.21
      2018410.18     13631856.37      2018675.79     13632325.10
#Sta/Elev= 30
  4400.4  731.09  4442.2  730.36  4447.3  729.55  4464.7  729.77  4557.1  727.61
  4668.3  725.52  4830.5  723.64  4910.5  722.15  4967.5  721.51  4968.0  720.71
  4973.0  720.71  4973.5  721.51  5000.5  721.98  5070.5  722.39  5220.5  723.82
  5410.5  724.73  5500.5  724.82  5518.7  725.38  5554.8  725.03  5738.7  726.20
  5787.8  726.87  5841.2  726.87  5899.6  728.03  5906.1  729.38  5911.8  727.86
  5927.7  727.34  5957.0  727.86  5986.9  728.03  5992.6  728.29  6060.6  728.76
#Mann=3,-1,0
  4400.4     0.1       0  4967.5    0.07       0  4973.5     0.1       0
Bank Sta=4967.5,4973.5
Exp/Cntr=0.3,0.1

Type RM Length L Ch R = 1,941,103,103,103
BEGIN DESCRIPTION:
Mapping XS e20255e0
END DESCRIPTION:
XS GIS Cut Line= 5
      2018227.87     13630325.17      2017910.18     13631064.71
      2017889.35     13631158.46      2017868.51     13631231.37
      2018622.62     13632271.51
#Sta/Elev= 30
  4154.7  733.41  4254.3  733.92  4324.9  731.82  4396.1  731.10  4453.6  729.32
  4470.1  730.05  4501.9  728.29  4687.8  723.99  4851.1  722.32  4970.1  719.71
  4990.6  720.15  5006.3  718.42  5011.4  720.39  5041.8  717.55  5054.1  717.69
  5086.0  715.72  5086.5  714.92  5091.6  714.92  5092.1  715.72  5094.2  716.85
  5122.8  717.50  5130.7  718.68  5138.1  717.81  5146.6  718.78  5152.7  718.07
  5167.4  720.39  5360.0  721.12  5404.0  722.51  5546.3  722.46  6416.2  728.19
#Mann=5,-1,0
  4154.7     0.1       0  4396.1    0.05       0  4501.9     0.1       0
  5086.0    0.07       0  5092.1     0.1       0
Bank Sta=5086,5092.1
Exp/Cntr=0.3,0.1

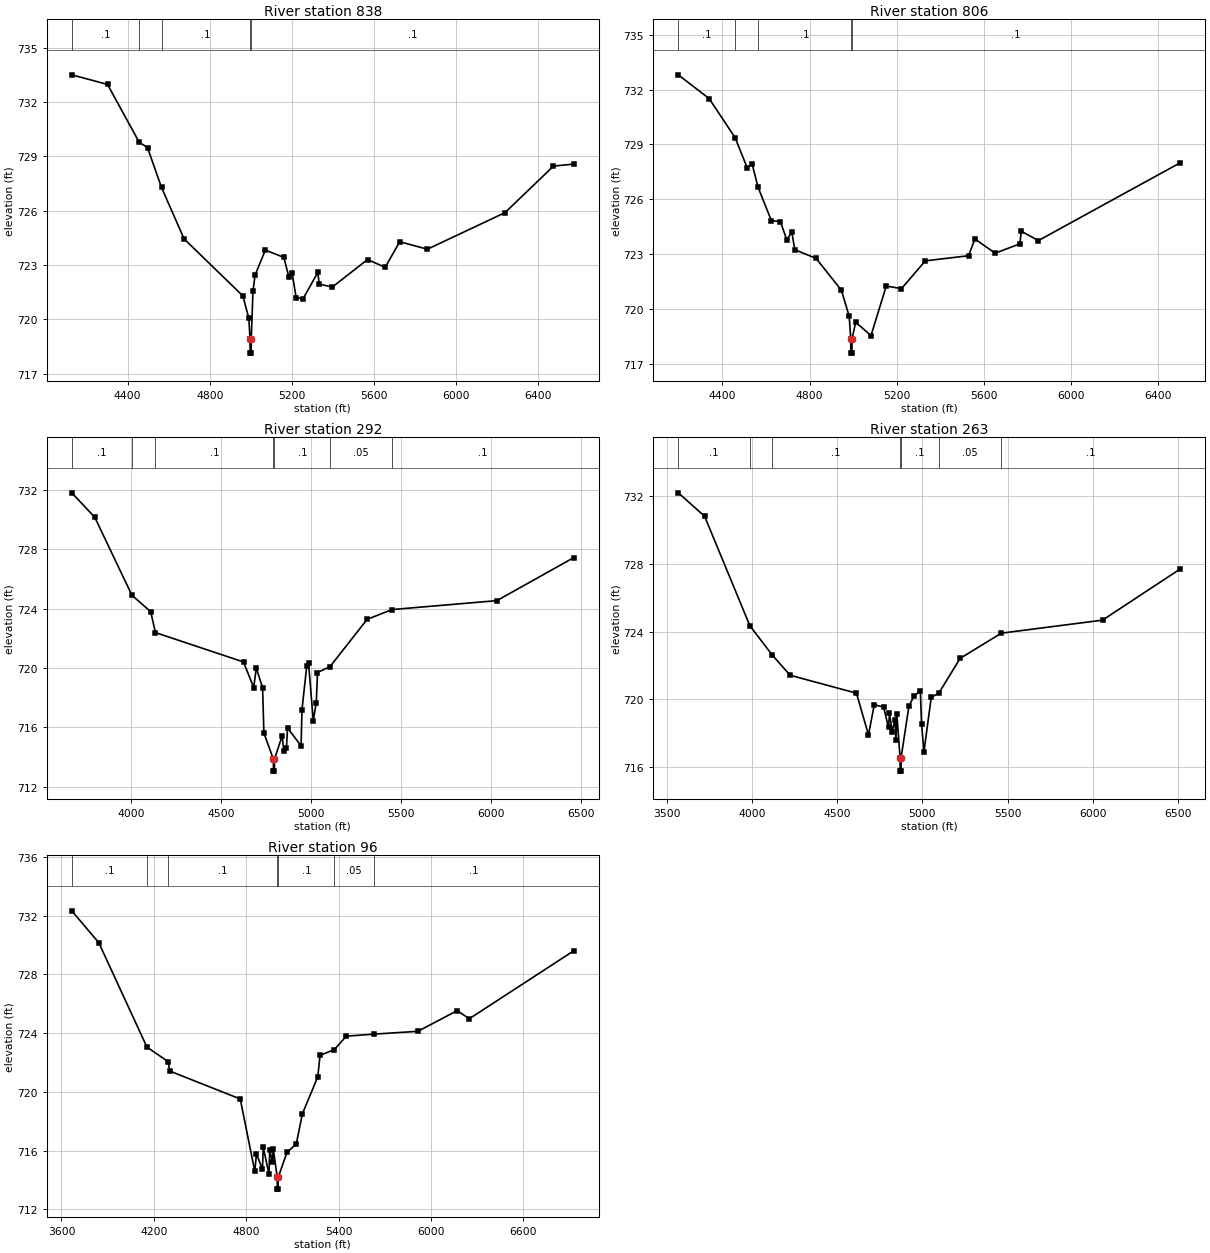
Type RM Length L Ch R = 1,838,32,32,32
BEGIN DESCRIPTION:
Mapping XS 310be930
END DESCRIPTION:
XS GIS Cut Line= 4
      2018217.46     13630252.24      2017842.47     13630991.79
      2017826.85     13631278.25      2018639.24     13632330.20
#Sta/Elev= 30
  4128.0  733.50  4302.1  732.97  4456.3  729.78  4496.9  729.48  4565.0  727.28
  4675.0  724.44  4961.3  721.29  4990.4  720.05  4996.0  718.93  4996.5  718.13
  5001.6  718.13  5002.1  718.93  5010.5  721.54  5020.5  722.43  5070.6  723.82
  5160.7  723.42  5186.0  722.31  5200.8  722.57  5220.8  721.20  5254.1  721.13
  5326.6  722.59  5332.9  721.94  5397.2  721.78  5568.5  723.30  5654.4  722.87
  5725.1  724.28  5860.0  723.87  6238.1  725.89  6474.1  728.46  6573.2  728.57
#Mann=5,-1,0
  4128.0     0.1       0  4456.3    0.05       0  4565.0     0.1       0
  4996.0    0.07       0  5002.1     0.1       0
Bank Sta=4996,5002.1
Exp/Cntr=0.3,0.1

Type RM Length L Ch R = 1,806,514,514,514
BEGIN DESCRIPTION:
Mapping XS 0e7955bb
END DESCRIPTION:
XS GIS Cut Line= 4
      2018118.52     13630304.29      2017811.22     13631012.62
      2017816.43     13631325.12      2018576.87     13632278.28
#Sta/Elev= 30
  4196.9  732.81  4338.9  731.51  4457.5  729.38  4513.8  727.71  4535.6  727.95
  4563.4  726.65  4624.3  724.83  4665.8  724.78  4694.7  723.79  4718.1  724.19
  4731.8  723.24  4829.9  722.76  4945.7  721.02  4981.4  719.60  4988.4  718.38
  4988.9  717.58  4994.0  717.58  4994.5  718.38  5011.4  719.27  5081.4  718.54
  5151.4  721.25  5221.4  721.11  5330.8  722.63  5529.3  722.91  5558.2  723.83
  5651.0  723.05  5764.7  723.56  5771.1  724.25  5849.6  723.74  6500.9  728.00
#Mann=5,-1,0
  4196.9     0.1       0  4457.5    0.05       0  4563.4     0.1       0
  4988.4    0.07       0  4994.5     0.1       0
Bank Sta=4988.4,4994.5
Exp/Cntr=0.3,0.1

Type RM Length L Ch R = 1,292,29,29,29
BEGIN DESCRIPTION:
Mapping XS 2a640c41
END DESCRIPTION:
XS GIS Cut Line= 6
      2017990.46     13630290.20      2017252.63     13631084.45
      2017256.97     13631171.26      2017283.01     13631192.96
      2017421.90     13631205.98      2018484.58     13632190.59
#Sta/Elev= 30
  3668.4  731.80  3796.1  730.16  4003.1  724.90  4107.4  723.80  4133.8  722.39
  4623.8  720.41  4680.5  718.69  4694.7  719.99  4729.9  718.69  4737.2  715.63
  4790.0  713.86  4790.5  713.06  4795.6  713.06  4796.1  713.86  4838.8  715.44
  4848.2  714.39  4862.5  714.62  4869.0  715.97  4944.1  714.76  4949.1  717.20
  4975.7  720.14  4985.8  720.31  5011.8  716.46  5028.6  717.66  5035.4  719.70
  5105.3  720.10  5311.5  723.28  5450.4  723.94  6033.3  724.54  6461.5  727.44
#Mann=7,-1,0
  3668.4     0.1       0  4003.1    0.05       0  4133.8     0.1       0
  4790.0    0.07       0  4796.1     0.1       0  5105.3    0.05       0
  5450.4     0.1       0
Bank Sta=4790,4796.1
Exp/Cntr=0.3,0.1

Type RM Length L Ch R = 1,263,167,167,167
BEGIN DESCRIPTION:
Mapping XS 86374ebf
END DESCRIPTION:
XS GIS Cut Line= 6
      2018003.51     13630225.07      2017222.25     13631071.43
      2017222.25     13631140.88      2017261.31     13631210.32
      2017382.84     13631219.00      2018520.02     13632234.66
#Sta/Elev= 30
  3567.0  732.21  3721.5  730.83  3987.5  724.35  4117.8  722.63  4223.9  721.42
  4613.5  720.36  4683.8  717.89  4717.9  719.68  4772.4  719.54  4801.4  718.34
  4807.2  719.16  4823.1  718.09  4838.9  718.77  4844.8  717.59  4850.5  719.11
  4869.3  716.55  4869.8  715.75  4874.9  715.75  4875.4  716.55  4921.8  719.62
  4951.9  720.19  4988.4  720.51  4995.3  718.54  5009.5  716.90  5052.2  720.11
  5096.7  720.36  5221.9  722.42  5464.0  723.91  6057.9  724.68  6514.5  727.71
#Mann=7,-1,0
  3567.0     0.1       0  3987.5    0.05       0  4117.8     0.1       0
  4869.3    0.07       0  4875.4     0.1       0  5096.7    0.05       0
  5464.0     0.1       0
Bank Sta=4869.3,4875.4
Exp/Cntr=0.3,0.1

Type RM Length L Ch R = 1,96,0,0,0
BEGIN DESCRIPTION:
UNT 101 in HW 1.0
END DESCRIPTION:
XS GIS Cut Line= 6
      2017972.69     13630194.90      2017436.64     13630703.14
      2017186.64     13631062.51      2017207.47     13631161.47
      2017298.62     13631315.11      2018727.88     13632413.66
#Sta/Elev= 30
  3667.1  732.33  3842.5  730.16  4155.5  723.04  4294.1  722.05  4302.1  721.42
  4761.3  719.51  4855.5  714.58  4866.5  715.78  4905.4  714.71  4910.5  716.23
  4947.8  714.39  4952.5  716.03  4970.3  715.22  4975.8  716.10  5001.5  714.17
  5002.0  713.37  5007.1  713.37  5007.6  714.17  5065.0  715.88  5124.8  716.44
  5165.0  718.51  5264.7  721.02  5279.2  722.48  5372.9  722.88  5449.6  723.79
  5629.8  723.93  5914.5  724.12  6170.0  725.53  6248.9  724.98  6927.5  729.61
#Mann=7,-1,0
  3667.1     0.1       0  4155.5    0.05       0  4294.1     0.1       0
  5001.5    0.07       0  5007.6     0.1       0  5372.9    0.05       0
  5629.8     0.1       0
Bank Sta=5001.5,5007.6
Exp/Cntr=0.3,0.1

Chan Stop Cuts=-1