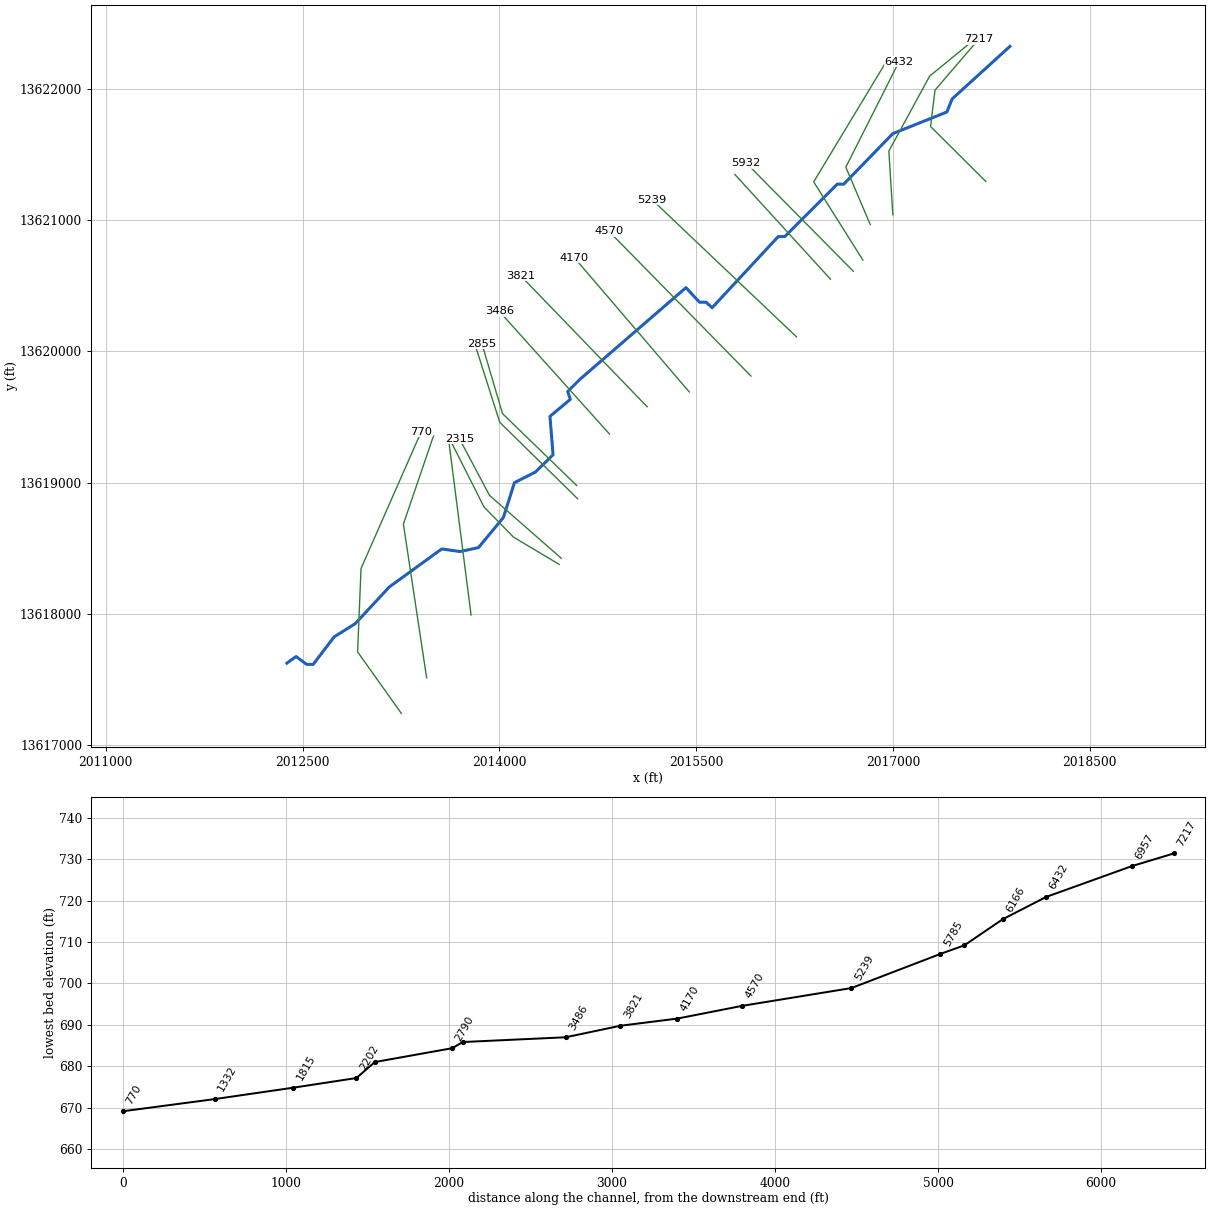
--- UNT 102 in HW.prj (project) ---

Proj Title=UNT 102 in HW Base Level Engineering
Current Plan=p01
Default Exp/Contr=0.3,0.1
English Units
Geom File=g01
Flow File=f01
Plan File=p01
BEGIN DESCRIPTION:
UNT 102 in HW
END DESCRIPTION:

--- UNT 102 in HW.p01 (plan) ---

Plan Title=Multiple Run
Short Identifier=Multiple
Geom File=g01
Flow File=f01
Subcritical Flow
K Sum by GR= 0
Std Step Tol= 0.01
Critical Tol= 0.01
Num of Std Step Trials= 20
Max Error Tol= 0.3
Flow Tol Ratio= 0.001
Split Flow NTrial= 30
Split Flow Tol= 0.02
Split Flow Ratio= 0.02
Log Output Level= 0
Friction Slope Method= 1
Unsteady Friction Slope Method= 2
Unsteady Bridges Friction Slope Method= 1
Parabolic Critical Depth
Global Vel Dist=  1 , 1 , 1
Global Log Level= 0
CheckData=True
Encroach Param= -1, 0, 0, 0
BEGIN DESCRIPTION:
Multiple Run
END DESCRIPTION:

--- UNT 102 in HW.f01 (steady flow) ---

Flow Title=Multiple
Number of Profiles=7
Profile Names=10-year,25-year,50-year,1pct_min,100-year,1pct_plu,500-year
River Rch & RM= UNT 102 in HW,Reach-1,7217
     535     753     934     575    1146    2287    1732
River Rch & RM= UNT 102 in HW,Reach-1,3486
     939    1361    1724    1080    2155    4300    3382
Boundary for River Rch & Prof#=UNT 102 in HW,Reach-1,1
Up Type=0
Dn Type=3
Dn Slope=0.005
Boundary for River Rch & Prof#=UNT 102 in HW,Reach-1,2
Up Type=0
Dn Type=3
Dn Slope=0.005
Boundary for River Rch & Prof#=UNT 102 in HW,Reach-1,3
Up Type=0
Dn Type=3
Dn Slope=0.005
Boundary for River Rch & Prof#=UNT 102 in HW,Reach-1,4
Up Type=0
Dn Type=3
Dn Slope=0.005
Boundary for River Rch & Prof#=UNT 102 in HW,Reach-1,5
Up Type=0
Dn Type=3
Dn Slope=0.005
Boundary for River Rch & Prof#=UNT 102 in HW,Reach-1,6
Up Type=0
Dn Type=3
Dn Slope=0.005
Boundary for River Rch & Prof#=UNT 102 in HW,Reach-1,7
Up Type=0
Dn Type=3
Dn Slope=0.005

--- UNT 102 in HW.g01 (geometry) ---

Geom Title=Existing Conditions

River Reach=UNT 102 in HW,Reach-1
Reach XY= 30
      2017890.80     13622324.54      2017450.80     13621924.54
      2017410.80     13621824.54      2016998.52     13621659.80
      2016625.00     13621275.00      2016575.00     13621275.00
      2016175.00     13620875.00      2016125.00     13620875.00
      2015621.20     13620332.55      2015575.00     13620375.00
      2015525.00     13620375.00      2015421.97     13620485.71
      2014610.80     13619784.54      2014520.80     13619694.54
      2014540.80     13619634.54      2014385.52     13619504.86
      2014409.13     13619211.81      2014273.72     13619079.86
      2014114.71     13618999.30      2014030.80     13618734.54
      2013840.80     13618504.54      2013700.80     13618474.54
      2013560.80     13618494.54      2013160.80     13618204.54
      2012900.80     13617924.54      2012740.80     13617824.54
      2012580.80     13617614.54      2012530.80     13617614.54
      2012450.80     13617674.54      2012380.80     13617624.54

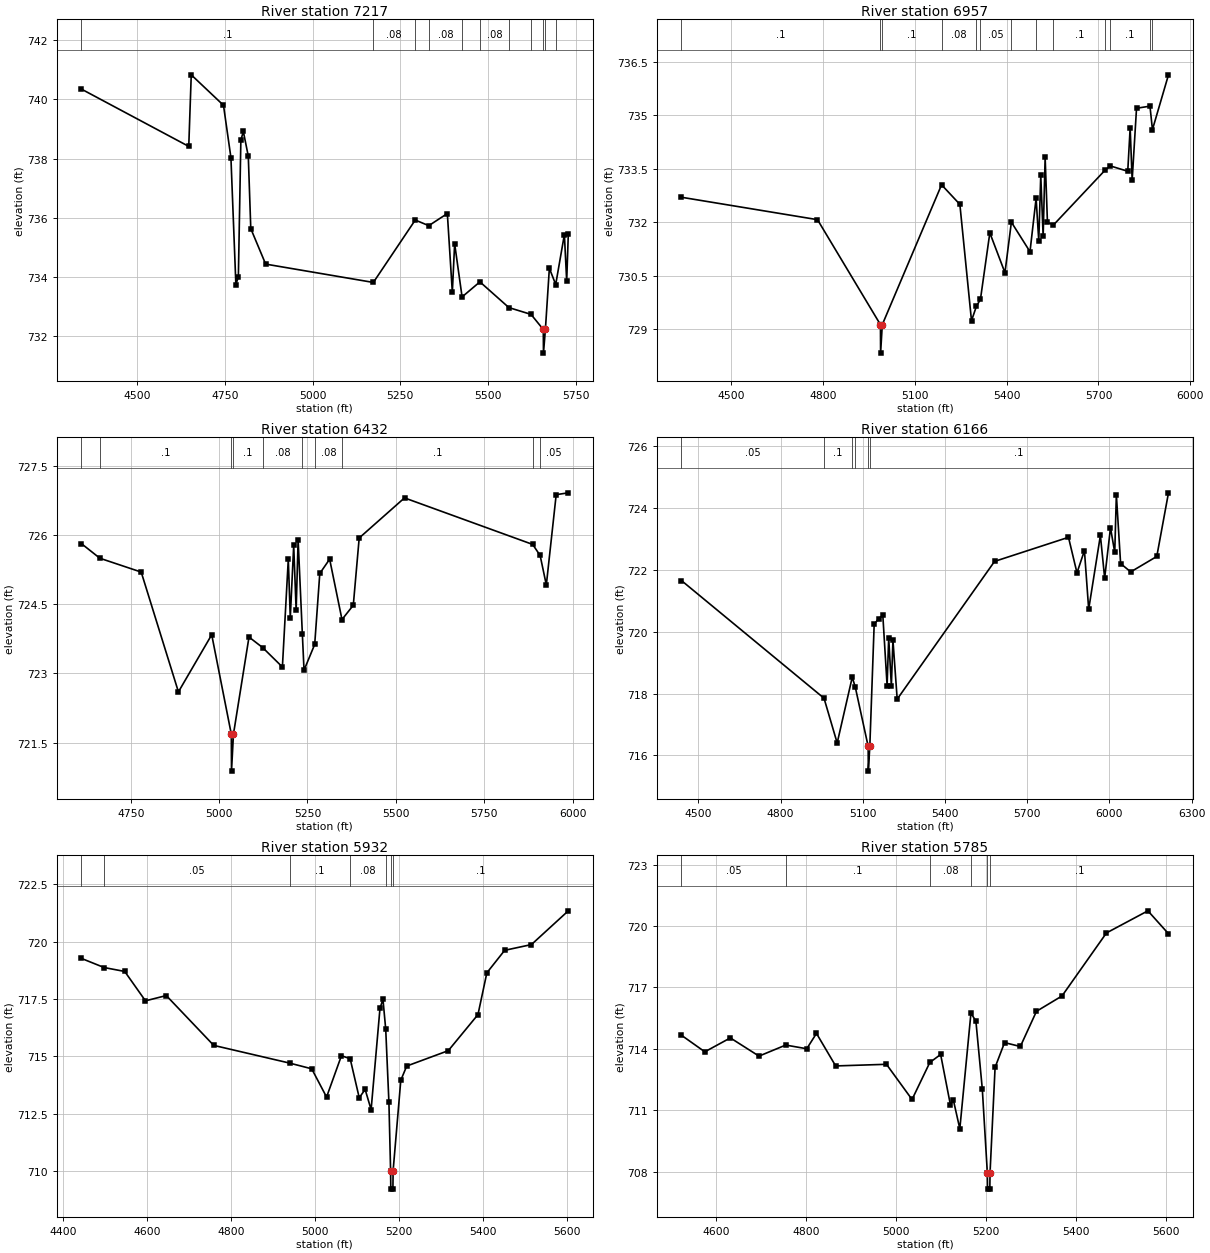
Type RM Length L Ch R = 1,7217,260,260,260
BEGIN DESCRIPTION:
Mapping XS 3130df7b
END DESCRIPTION:
XS GIS Cut Line= 4
      2017707.88     13621294.60      2017286.03     13621713.84
      2017320.04     13621991.26      2017655.00     13622381.21
#Sta/Elev= 30
  4340.8  740.35  4647.2  738.41  4654.3  740.83  4746.2  739.80  4767.4  738.03
  4781.5  733.74  4788.6  734.00  4795.7  738.61  4802.7  738.92  4816.9  738.08
  4824.0  735.63  4866.4  734.43  5173.4  733.81  5292.8  735.92  5331.4  735.73
  5384.3  736.14  5398.5  733.48  5405.1  735.12  5426.3  733.32  5477.1  733.83
  5559.7  732.96  5622.8  732.73  5657.8  732.22  5658.3  731.42  5663.8  732.22
  5675.1  734.29  5693.2  733.74  5717.9  735.43  5724.5  733.85  5729.1  735.45
#Mann=11,-1,0
  4340.8     0.1       0  5173.4    0.08       0  5292.8    0.05       0
  5331.4    0.08       0  5426.3     0.1       0  5477.1    0.08       0
  5559.7     0.1       0  5622.8    0.05       0  5657.8    0.07       0
  5663.8    0.05       0  5693.2     0.1       0
Bank Sta=5657.8,5663.8
Exp/Cntr=0.3,0.1

Type RM Length L Ch R = 1,6957,525,525,525
BEGIN DESCRIPTION:
Mapping XS a08bd99c
END DESCRIPTION:
XS GIS Cut Line= 4
      2016998.52     13621041.32      2016968.32     13621526.34
      2017279.02     13622097.72      2017631.08     13622385.88
#Sta/Elev= 30
  4337.5  732.70  4782.0  732.07  4987.7  729.12  4988.2  728.32  4993.7  729.12
  5187.4  733.05  5247.2  732.50  5285.2  729.23  5301.4  729.64  5314.4  729.83
  5345.1  731.70  5394.5  730.58  5415.5  732.00  5476.3  731.17  5496.3  732.67
  5505.0  731.47  5511.5  733.32  5519.3  731.60  5525.8  733.82  5533.3  732.00
  5552.9  731.92  5722.6  733.47  5739.0  733.58  5795.7  733.43  5803.6  734.65
  5810.1  733.18  5824.4  735.20  5868.3  735.26  5876.4  734.60  5928.8  736.14
#Mann=13,-1,0
  4337.5     0.1       0  4987.7    0.07       0  4993.7     0.1       0
  5187.4    0.08       0  5301.4     0.1       0  5314.4    0.05       0
  5415.5     0.1       0  5496.3    0.05       0  5552.9     0.1       0
  5722.6    0.08       0  5739.0     0.1       0  5868.3    0.05       0
  5876.4     0.1       0
Bank Sta=4987.7,4993.7
Exp/Cntr=0.3,0.1

Type RM Length L Ch R = 1,6432,266,266,266
BEGIN DESCRIPTION:
Mapping XS c6a7d7ef
END DESCRIPTION:
XS GIS Cut Line= 3
      2016827.06     13620965.40      2016640.20     13621403.95
      2017046.44     13622208.61
#Sta/Elev= 30
  4610.0  725.82  4662.7  725.50  4779.6  725.20  4884.9  722.60  4979.1  723.84
  5034.6  721.68  5035.1  720.88  5040.6  721.68  5084.6  723.79  5123.4  723.56
  5179.1  723.14  5195.8  725.48  5201.4  724.21  5211.1  725.78  5218.0  724.37
  5223.6  725.90  5235.6  723.85  5240.3  723.07  5270.5  723.63  5284.9  725.17
  5312.8  725.48  5347.7  724.17  5379.7  724.48  5396.4  725.94  5524.6  726.81
  5887.3  725.80  5908.4  725.56  5925.9  724.92  5953.8  726.88  5988.1  726.92
#Mann=10,-1,0
  4610.0    0.05       0  4662.7     0.1       0  5034.6    0.07       0
  5040.6     0.1       0  5123.4    0.08       0  5235.6     0.1       0
  5270.5    0.08       0  5347.7     0.1       0  5887.3    0.08       0
  5908.4    0.05       0
Bank Sta=5034.6,5040.6
Exp/Cntr=0.3,0.1

Type RM Length L Ch R = 1,6166,234,234,234
BEGIN DESCRIPTION:
Mapping XS 7d50b9eb
END DESCRIPTION:
XS GIS Cut Line= 3
      2016770.40     13620695.62      2016395.41     13621291.97
      2016949.68     13622210.55
#Sta/Elev= 30
  4438.1  721.66  4958.4  717.85  5006.4  716.40  5061.4  718.53  5072.5  718.21
  5119.5  716.29  5120.0  715.49  5125.5  716.29  5141.4  720.24  5157.8  720.43
  5173.0  720.53  5188.6  718.26  5194.4  719.81  5204.1  718.25  5209.9  719.73
  5225.4  717.82  5580.7  722.28  5850.5  723.06  5881.5  721.91  5908.7  722.63
  5924.2  720.73  5966.9  723.12  5982.5  721.74  6003.8  723.37  6019.3  722.57
  6025.2  724.44  6040.7  722.21  6077.6  721.94  6172.7  722.44  6215.4  724.50
#Mann=6,-1,0
  4438.1    0.05       0  4958.4     0.1       0  5061.4    0.08       0
  5072.5     0.1       0  5119.5    0.07       0  5125.5     0.1       0
Bank Sta=5119.5,5125.5
Exp/Cntr=0.3,0.1

Type RM Length L Ch R = 1,5932,147,147,147
BEGIN DESCRIPTION:
Mapping XS f1a6067f
END DESCRIPTION:
XS GIS Cut Line= 2
      2016697.24     13620610.94      2015881.27     13621435.59
#Sta/Elev= 30
  4444.0  719.27  4498.5  718.87  4547.5  718.70  4596.9  717.42  4646.5  717.65
  4759.5  715.48  4940.0  714.71  4992.9  714.46  5028.3  713.23  5063.7  715.03
  5084.5  714.90  5106.1  713.20  5120.2  713.56  5134.4  712.68  5155.5  717.09
  5162.6  717.49  5169.2  716.18  5176.8  713.00  5180.8  710.02  5181.3  709.22
  5186.3  709.22  5186.8  710.02  5205.1  713.96  5219.2  714.58  5318.2  715.25
  5388.9  716.82  5410.1  718.64  5452.5  719.62  5516.2  719.87  5604.1  721.34
#Mann=7,-1,0
  4444.0     0.1       0  4498.5    0.05       0  4940.0     0.1       0
  5084.5    0.08       0  5169.2     0.1       0  5180.8    0.07       0
  5186.8     0.1       0
Bank Sta=5180.8,5186.8
Exp/Cntr=0.3,0.1

Type RM Length L Ch R = 1,5785,546,546,546
BEGIN DESCRIPTION:
Mapping XS 6202d562
END DESCRIPTION:
XS GIS Cut Line= 2
      2016523.63     13620550.17      2015794.48     13621348.77
#Sta/Elev= 30
  4523.3  714.66  4575.2  713.85  4631.9  714.53  4695.5  713.64  4754.8  714.18
  4801.5  714.00  4823.1  714.75  4865.7  713.16  4978.5  713.24  5035.3  711.52
  5074.8  713.33  5098.8  713.72  5120.4  711.27  5127.2  711.48  5141.4  710.09
  5166.1  715.74  5177.1  715.35  5191.3  712.04  5202.5  707.94  5203.0  707.14
  5208.0  707.14  5208.5  707.94  5219.7  713.09  5240.7  714.30  5275.8  714.11
  5311.6  715.83  5368.3  716.58  5467.0  719.66  5559.0  720.74  5604.7  719.62
#Mann=6,-1,0
  4523.3    0.05       0  4754.8     0.1       0  5074.8    0.08       0
  5166.1     0.1       0  5202.5    0.07       0  5208.5     0.1       0
Bank Sta=5202.5,5208.5
Exp/Cntr=0.3,0.1

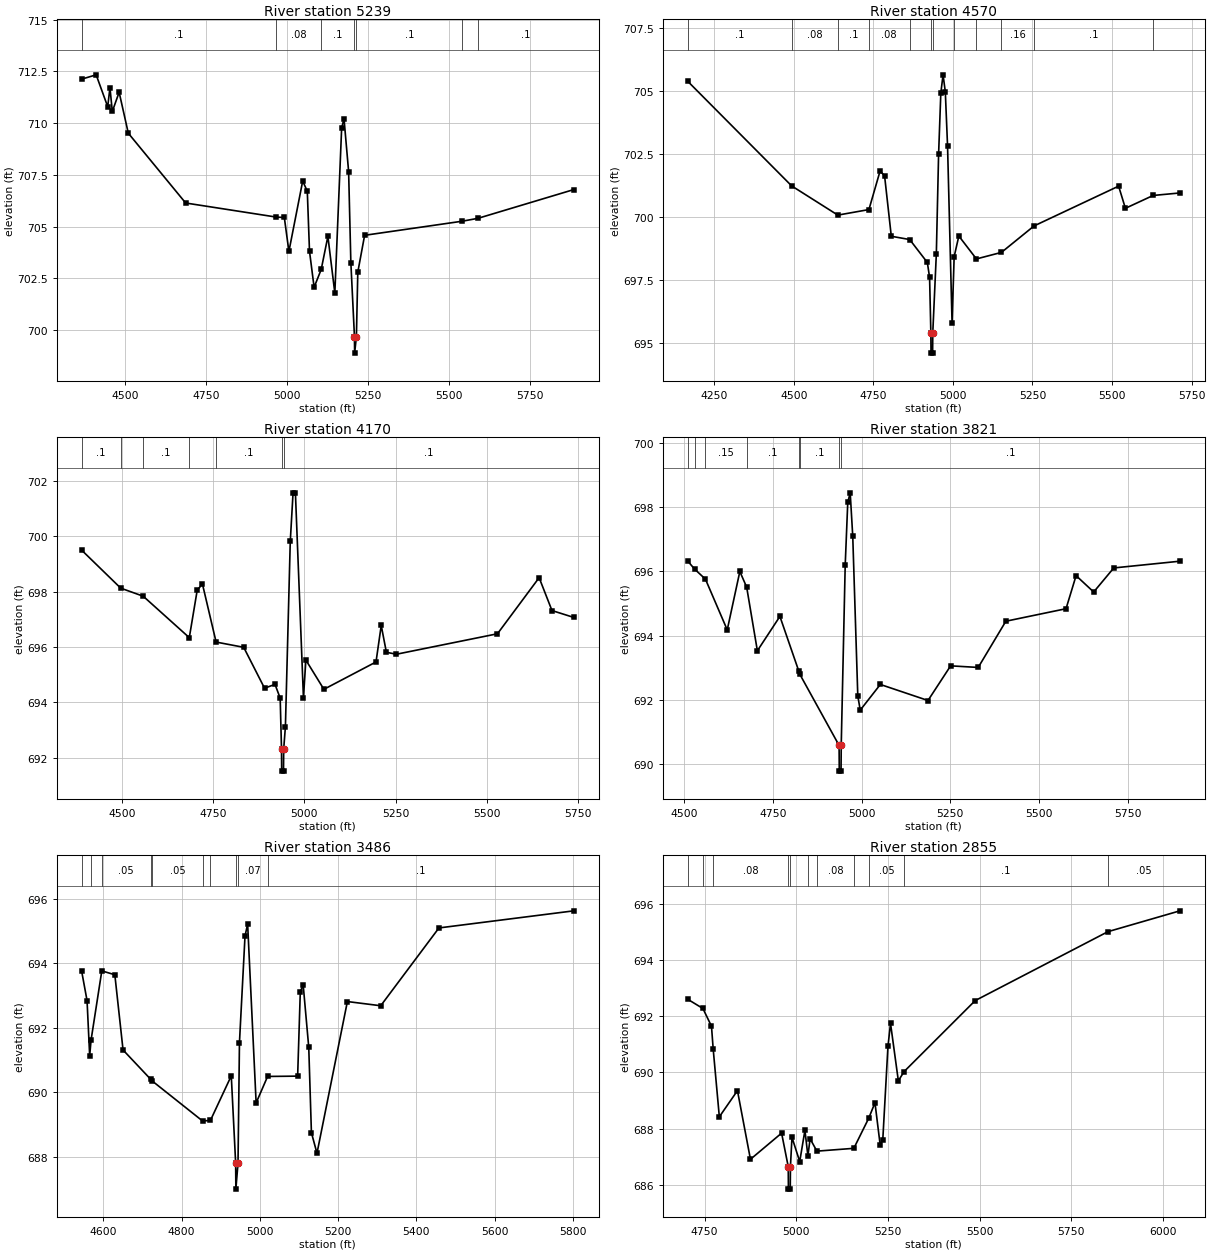
Type RM Length L Ch R = 1,5239,669,669,669
BEGIN DESCRIPTION:
Mapping XS 8e54e61c
END DESCRIPTION:
XS GIS Cut Line= 2
      2016264.53     13620110.64      2015163.79     13621155.82
#Sta/Elev= 30
  4366.6  712.12  4411.7  712.33  4447.3  710.79  4454.2  711.71  4461.5  710.56
  4482.5  711.49  4510.8  709.51  4687.6  706.14  4967.0  705.46  4991.8  705.44
  5005.9  703.80  5048.4  707.20  5062.6  706.71  5069.4  703.81  5083.6  702.07
  5105.5  702.93  5126.1  704.53  5147.5  701.79  5168.5  709.76  5175.8  710.21
  5190.0  707.66  5196.9  703.26  5208.0  699.69  5208.5  698.89  5214.0  699.69
  5218.3  702.80  5239.3  704.58  5540.0  705.26  5588.8  705.40  5884.5  706.79
#Mann=7,-1,0
  4366.6     0.1       0  4967.0    0.08       0  5105.5     0.1       0
  5208.0    0.07       0  5214.0     0.1       0  5540.0    0.16       0
  5588.8     0.1       0
Bank Sta=5208,5214
Exp/Cntr=0.3,0.1

Type RM Length L Ch R = 1,4570,400,400,400
BEGIN DESCRIPTION:
Mapping XS e67c7be0
END DESCRIPTION:
XS GIS Cut Line= 2
      2015917.28     13619812.05      2014833.93     13620916.24
#Sta/Elev= 30
  4166.3  705.40  4493.3  701.24  4638.4  700.08  4736.1  700.30  4771.1  701.83
  4785.3  701.64  4806.4  699.24  4864.2  699.11  4919.6  698.20  4926.7  697.61
  4930.7  695.40  4931.2  694.60  4936.2  694.60  4936.7  695.40  4947.9  698.54
  4955.0  702.49  4962.0  704.93  4969.0  705.65  4976.1  704.98  4983.1  702.84
  4997.3  695.81  5003.9  698.43  5018.6  699.25  5073.8  698.34  5152.5  698.60
  5254.9  699.65  5520.6  701.23  5541.9  700.35  5629.0  700.86  5713.2  700.96
#Mann=12,-1,0
  4166.3     0.1       0  4493.3    0.08       0  4638.4     0.1       0
  4736.1    0.08       0  4864.2     0.1       0  4930.7    0.07       0
  4936.7     0.1       0  5003.9    0.07       0  5073.8     0.1       0
  5152.5    0.16       0  5254.9     0.1       0  5629.0    0.16       0
Bank Sta=4930.7,4936.7
Exp/Cntr=0.3,0.1

Type RM Length L Ch R = 1,4170,349,349,349
BEGIN DESCRIPTION:
Mapping XS 63daba96
END DESCRIPTION:
XS GIS Cut Line= 2
      2015447.26     13619690.78      2014570.51     13620715.09
#Sta/Elev= 30
  4389.9  699.51  4497.3  698.13  4558.7  697.84  4685.0  696.34  4706.7  698.06
  4721.0  698.28  4758.4  696.18  4834.0  695.99  4891.1  694.51  4919.7  694.65
  4933.9  694.15  4937.5  692.31  4938.0  691.51  4943.0  691.51  4943.5  692.31
  4948.2  693.12  4961.5  699.82  4969.1  701.57  4975.6  701.58  4997.6  694.16
  5004.2  695.53  5053.6  694.47  5196.3  695.46  5210.6  696.78  5224.7  695.81
  5252.3  695.74  5528.9  696.48  5643.0  698.51  5678.2  697.32  5738.2  697.07
#Mann=7,-1,0
  4389.9     0.1       0  4497.3    0.08       0  4558.7     0.1       0
  4685.0    0.08       0  4758.4     0.1       0  4937.5    0.07       0
  4943.5     0.1       0
Bank Sta=4937.5,4943.5
Exp/Cntr=0.3,0.1

Type RM Length L Ch R = 1,3821,335,335,335
BEGIN DESCRIPTION:
Mapping XS 4e7bcc9a
END DESCRIPTION:
XS GIS Cut Line= 2
      2015126.07     13619577.94      2014162.54     13620576.19
#Sta/Elev= 30
  4509.7  696.33  4529.9  696.07  4560.1  695.76  4621.5  694.18  4657.0  696.00
  4676.3  695.51  4706.4  693.53  4769.9  694.60  4822.7  692.91  4825.9  692.80
  4936.7  690.58  4937.2  689.78  4942.2  689.78  4942.7  690.58  4953.9  696.19
  4961.1  698.15  4968.0  698.45  4975.2  697.09  4989.4  692.12  4996.3  691.68
  5052.9  692.48  5187.2  691.98  5251.0  693.06  5328.7  693.01  5406.6  694.45
  5576.2  694.84  5604.5  695.87  5654.1  695.36  5710.7  696.11  5897.1  696.32
#Mann=8,-1,0
  4509.7    0.08       0  4529.9     0.1       0  4560.1    0.15       0
  4676.3     0.1       0  4822.7    0.08       0  4825.9     0.1       0
  4936.7    0.07       0  4942.7     0.1       0
Bank Sta=4936.7,4942.7
Exp/Cntr=0.3,0.1

Type RM Length L Ch R = 1,3486,631,631,631
BEGIN DESCRIPTION:
Mapping XS 2fa7bb90
END DESCRIPTION:
XS GIS Cut Line= 2
      2014839.58     13619369.64      2013998.78     13620305.79
#Sta/Elev= 30
  4544.2  693.77  4558.3  692.84  4565.0  691.13  4568.6  691.62  4596.0  693.76
  4629.3  693.64  4650.3  691.31  4721.1  690.40  4724.8  690.35  4853.6  689.11
  4873.7  689.13  4926.9  690.51  4938.1  687.80  4938.6  687.00  4944.1  687.80
  4947.8  691.54  4962.0  694.84  4968.7  695.21  4990.4  689.67  5019.7  690.49
  5096.5  690.50  5103.3  693.12  5110.7  693.32  5124.9  691.39  5131.7  688.75
  5145.9  688.11  5223.6  692.81  5308.8  692.68  5457.6  695.09  5802.5  695.62
#Mann=10,-1,0
  4544.2     0.1       0  4568.6    0.08       0  4596.0    0.05       0
  4721.1     0.1       0  4724.8    0.05       0  4853.6     0.1       0
  4873.7    0.07       0  4938.1    0.07       0  4944.1    0.07       0
  5019.7     0.1       0
Bank Sta=4938.1,4944.1
Exp/Cntr=0.3,0.1

Type RM Length L Ch R = 1,2855,65,65,65
BEGIN DESCRIPTION:
Mapping XS 6551cf4b
END DESCRIPTION:
XS GIS Cut Line= 3
      2014589.59     13618977.27      2014023.62     13619525.88
      2013867.36     13620057.16
#Sta/Elev= 30
  4703.8  692.60  4745.6  692.27  4769.0  691.64  4773.7  690.82  4790.4  688.42
  4839.8  689.35  4875.2  686.91  4960.1  687.84  4978.2  686.65  4978.7  685.85
  4983.7  685.85  4984.2  686.65  4988.4  687.69  5009.5  686.83  5023.7  687.94
  5031.8  687.03  5037.8  687.64  5056.3  687.20  5157.0  687.30  5197.6  688.37
  5214.6  688.92  5228.7  687.43  5235.9  687.60  5250.0  690.92  5257.0  691.74
  5278.3  689.70  5294.2  690.03  5487.8  692.55  5849.7  695.00  6045.8  695.74
#Mann=11,-1,0
  4703.8    0.08       0  4745.6     0.1       0  4773.7    0.08       0
  4978.2    0.07       0  4984.2    0.08       0  5031.8     0.1       0
  5056.3    0.08       0  5157.0     0.1       0  5197.6    0.05       0
  5294.2     0.1       0  5849.7    0.05       0
Bank Sta=4978.2,4984.2
Exp/Cntr=0.3,0.1

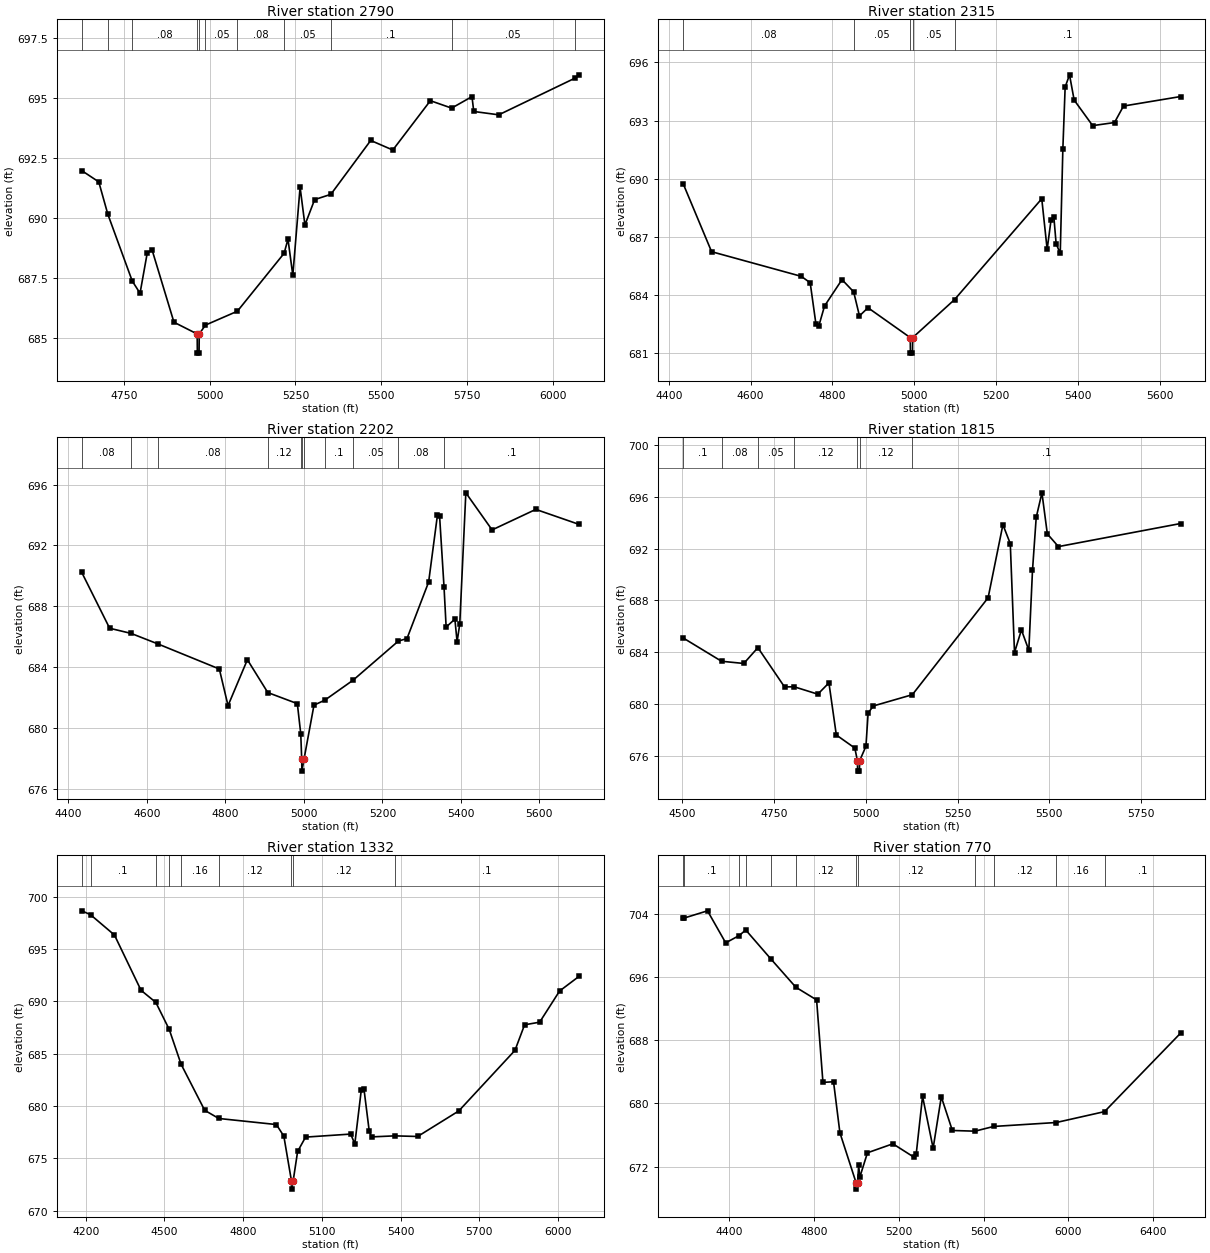
Type RM Length L Ch R = 1,2790,475,475,475
BEGIN DESCRIPTION:
Mapping XS bd8461a3
END DESCRIPTION:
XS GIS Cut Line= 3
      2014596.56     13618876.55      2014002.79     13619459.91
      2013815.28     13620048.47
#Sta/Elev= 30
  4627.0  691.98  4676.5  691.51  4702.9  690.16  4774.1  687.37  4796.8  686.86
  4817.9  688.55  4832.1  688.66  4895.7  685.65  4963.4  685.16  4963.9  684.36
  4968.9  684.36  4969.4  685.16  4987.5  685.53  5080.6  686.11  5216.9  688.53
  5228.1  689.12  5242.2  687.61  5263.4  691.29  5277.5  689.71  5305.8  690.77
  5353.1  690.99  5469.3  693.24  5533.7  692.84  5643.2  694.90  5705.2  694.59
  5764.5  695.07  5769.7  694.45  5842.6  694.31  6064.6  695.84  6077.1  695.98
#Mann=11,-1,0
  4627.0    0.08       0  4702.9     0.1       0  4774.1    0.08       0
  4963.4    0.04       0  4969.4    0.08       0  4987.5    0.05       0
  5080.6    0.08       0  5216.9    0.05       0  5353.1     0.1       0
  5705.2    0.05       0  6064.6     0.1       0
Bank Sta=4963.4,4969.4
Exp/Cntr=0.3,0.1

Type RM Length L Ch R = 1,2315,113,113,113
BEGIN DESCRIPTION:
Mapping XS bb8194f7
END DESCRIPTION:
XS GIS Cut Line= 3
      2014471.56     13618423.43      2013924.66     13618902.61
      2013695.50     13619334.90
#Sta/Elev= 30
  4435.0  689.75  4504.6  686.24  4723.8  684.97  4745.7  684.64  4759.9  682.49
  4766.5  682.39  4780.8  683.44  4823.5  684.80  4852.0  684.17  4866.2  682.93
  4887.1  683.35  4990.4  681.81  4990.9  681.01  4995.9  681.01  4996.4  681.81
  5098.7  683.77  5312.0  688.97  5325.2  686.36  5334.6  687.86  5341.6  688.02
  5347.2  686.65  5357.2  686.15  5363.6  691.54  5369.2  694.73  5379.9  695.36
  5391.2  694.06  5436.5  692.74  5489.9  692.90  5511.9  693.75  5651.4  694.24
#Mann=5,-1,0
  4435.0    0.08       0  4852.0    0.05       0  4990.4    0.04       0
  4996.4    0.05       0  5098.7     0.1       0
Bank Sta=4990.4,4996.4
Exp/Cntr=0.3,0.1

Type RM Length L Ch R = 1,2202,387,387,387
BEGIN DESCRIPTION:
Mapping XS b7786b0b
END DESCRIPTION:
XS GIS Cut Line= 4
      2014455.93     13618376.56      2014106.95     13618584.91
      2013882.99     13618814.07      2013639.10     13619296.68
#Sta/Elev= 30
  4433.9  690.22  4504.9  686.55  4559.7  686.21  4628.7  685.51  4784.4  683.87
  4806.6  681.46  4855.9  684.48  4907.9  682.32  4983.2  681.59  4991.9  679.61
  4994.3  677.95  4994.8  677.15  5000.3  677.95  5025.6  681.49  5053.3  681.82
  5125.6  683.14  5240.8  685.71  5262.6  685.87  5317.8  689.59  5340.1  693.97
  5345.7  693.93  5357.0  689.27  5362.4  686.63  5384.7  687.15  5390.3  685.66
  5397.1  686.82  5412.6  695.46  5479.5  693.02  5590.9  694.37  5701.5  693.38
#Mann=11,-1,0
  4433.9    0.08       0  4559.7    0.05       0  4628.7    0.08       0
  4907.9    0.12       0  4991.9    0.05       0  4994.3    0.04       0
  5000.3    0.05       0  5053.3     0.1       0  5125.6    0.05       0
  5240.8    0.08       0  5357.0     0.1       0
Bank Sta=4994.3,5000.3
Exp/Cntr=0.3,0.1

Type RM Length L Ch R = 1,1815,483,483,483
BEGIN DESCRIPTION:
Mapping XS d8f0fc71
END DESCRIPTION:
XS GIS Cut Line= 2
      2013784.04     13617991.16      2013612.16     13619334.91
#Sta/Elev= 30
  4502.6  685.10  4607.2  683.30  4667.8  683.13  4706.2  684.35  4778.7  681.32
  4805.1  681.33  4869.4  680.76  4899.7  681.63  4919.8  677.61  4970.2  676.60
  4977.3  675.62  4977.8  674.82  4982.8  674.82  4983.3  675.62  5000.5  676.74
  5006.4  679.30  5020.6  679.85  5126.9  680.72  5333.2  688.20  5373.5  693.84
  5393.6  692.38  5405.1  683.97  5423.9  685.72  5444.1  684.15  5454.1  690.32
  5464.2  694.40  5479.8  696.30  5494.5  693.13  5524.7  692.15  5857.3  693.93
#Mann=7,-1,0
  4502.6     0.1       0  4607.2    0.08       0  4706.2    0.05       0
  4805.1    0.12       0  4977.3    0.07       0  4983.3    0.12       0
  5126.9     0.1       0
Bank Sta=4977.3,4983.3
Exp/Cntr=0.3,0.1

Type RM Length L Ch R = 1,1332,562,562,562
BEGIN DESCRIPTION:
Mapping XS 606397fc
END DESCRIPTION:
XS GIS Cut Line= 3
      2013445.50     13617511.96      2013268.41     13618683.86
      2013497.58     13619355.74
#Sta/Elev= 30
  4185.3  698.65  4218.5  698.28  4309.7  696.34  4410.9  691.06  4467.4  689.90
  4518.4  687.32  4563.5  684.00  4653.6  679.59  4707.3  678.81  4926.7  678.23
  4955.1  677.12  4984.0  672.86  4984.5  672.06  4990.7  672.86  5007.6  675.66
  5037.9  677.03  5209.8  677.32  5225.5  676.38  5250.3  681.56  5260.4  681.62
  5280.6  677.57  5289.3  677.05  5377.9  677.15  5464.9  677.09  5621.6  679.53
  5835.7  685.32  5872.3  687.76  5929.7  688.01  6005.7  690.99  6080.4  692.40
#Mann=9,-1,0
  4185.3    0.08       0  4218.5     0.1       0  4467.4    0.08       0
  4518.4    0.05       0  4563.5    0.16       0  4707.3    0.12       0
  4984.0    0.07       0  4990.7    0.12       0  5377.9     0.1       0
Bank Sta=4984,4990.7
Exp/Cntr=0.3,0.1

Type RM Length L Ch R = 1,770,0,0,0
BEGIN DESCRIPTION:
UNT 102 in HW 1.0
END DESCRIPTION:
XS GIS Cut Line= 4
      2013252.76     13617241.19      2012919.45     13617709.91
      2012945.49     13618345.32      2013403.81     13619386.96
#Sta/Elev= 30
  4181.4  703.49  4183.3  703.49  4296.5  704.43  4382.4  700.37  4445.9  701.29
  4477.1  702.00  4595.3  698.34  4713.6  694.74  4811.7  693.13  4841.7  682.67
  4891.7  682.75  4921.8  676.28  4998.4  669.93  4998.9  669.13  5005.2  669.93
  5010.5  672.16  5015.5  670.63  5051.9  673.74  5172.0  674.88  5272.1  673.17
  5282.1  673.56  5312.1  680.90  5362.1  674.32  5400.6  680.84  5452.8  676.57
  5559.4  676.48  5648.0  677.08  5943.5  677.58  6171.6  678.96  6530.5  688.91
#Mann=12,-1,0
  4181.4    0.08       0  4183.3     0.1       0  4445.9    0.08       0
  4477.1     0.1       0  4595.3    0.05       0  4713.6    0.12       0
  4998.4    0.07       0  5005.2    0.12       0  5559.4    0.16       0
  5648.0    0.12       0  5943.5    0.16       0  6171.6     0.1       0
Bank Sta=4998.4,5005.2
Exp/Cntr=0.3,0.1

Chan Stop Cuts=-1