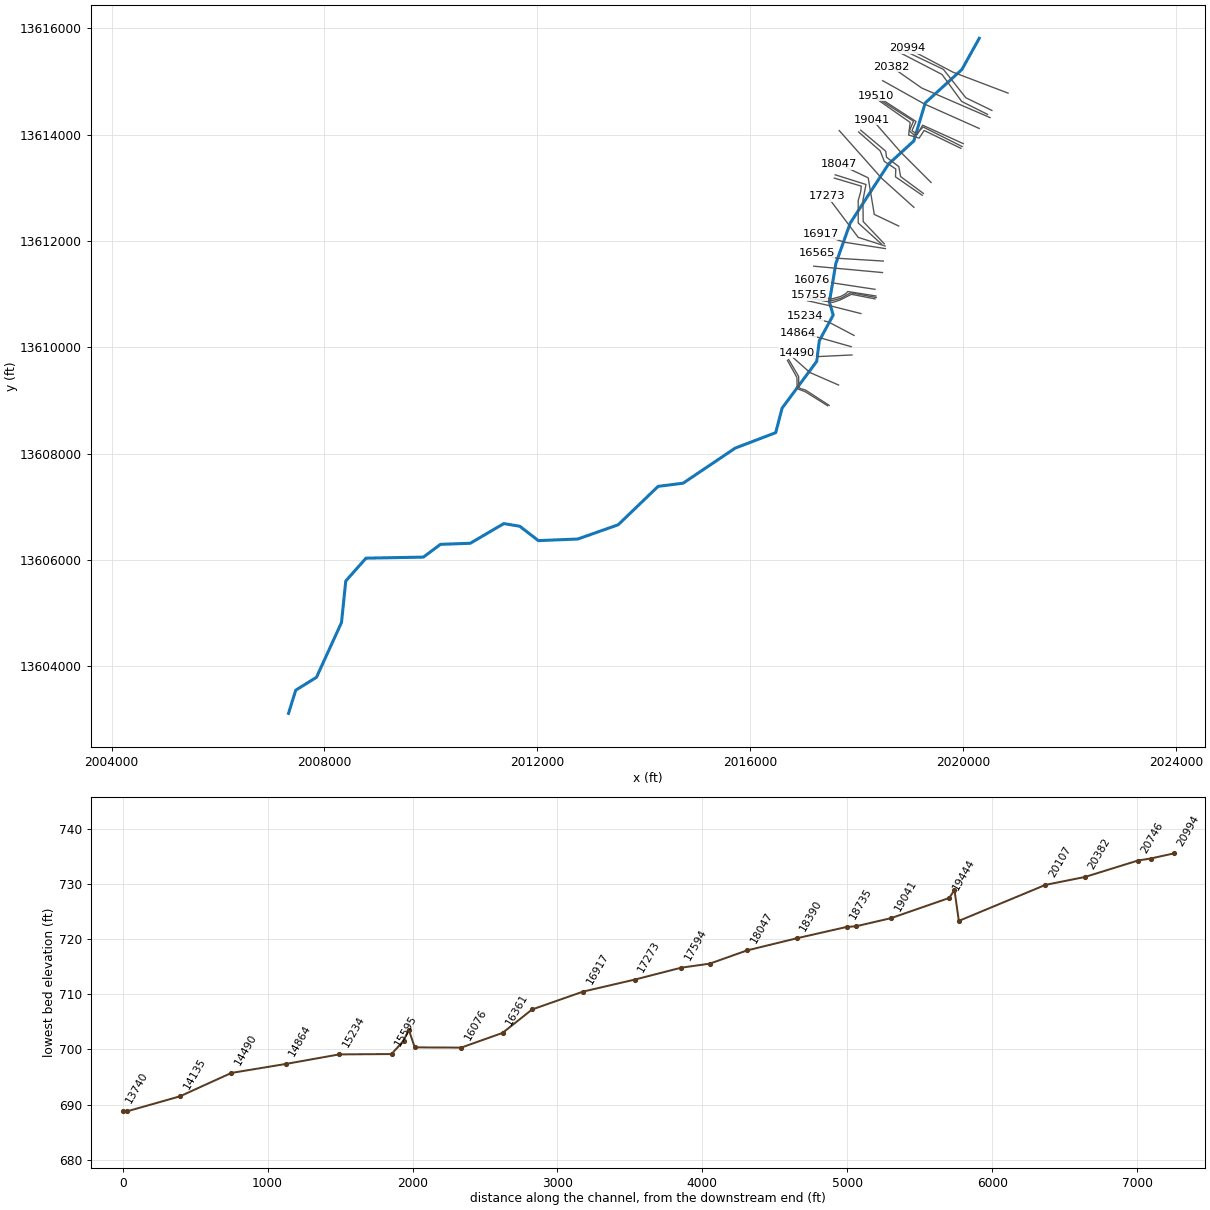
--- UNT 103 in HW.prj (project) ---

Proj Title=UNT 103 in HW Base Level Engineering
Current Plan=p01
Default Exp/Contr=0.3,0.1
English Units
Geom File=g01
Flow File=f01
Plan File=p01
Y Axis Title=Elevation
X Axis Title(PF)=Main Channel Distance
X Axis Title(XS)=Station
BEGIN DESCRIPTION:
UNT 103 in HW
END DESCRIPTION:
DSS Export Rating Curves= 0
DSS Export Rating Curve Sorted= 0
DSS Export Volume Flow Curves= 0
DXF OffsetX= 0
DXF OffsetY= 0
DXF ScaleX= 1
DXF ScaleY= 10

--- UNT 103 in HW.p01 (plan) ---

Plan Title=Multiple Run
Short Identifier=Multiple
Geom File=g01
Flow File=f01
Subcritical Flow
K Sum by GR= 0
Std Step Tol= 0.01
Critical Tol= 0.01
Num of Std Step Trials= 20
Max Error Tol= 0.3
Flow Tol Ratio= 0.001
Split Flow NTrial= 30
Split Flow Tol= 0.02
Split Flow Ratio= 0.02
Log Output Level= 0
Friction Slope Method= 1
Unsteady Friction Slope Method= 2
Unsteady Bridges Friction Slope Method= 1
Parabolic Critical Depth
Global Vel Dist=  1 , 1 , 1
Global Log Level= 0
CheckData=True
Encroach Param= -1, 0, 0, 0
BEGIN DESCRIPTION:
Multiple Run
END DESCRIPTION:

--- UNT 103 in HW.f01 (steady flow) ---

Flow Title=Multiple
Program Version=5.05
Number of Profiles= 7
Profile Names=10-year,25-year,50-year,1pct_min,100-year,1pct_plu,500-year
River Rch & RM=UNT 103 in HW,Reach-1         ,20994
     601     845    1049     645    1286    2566    1940
River Rch & RM=UNT 103 in HW,Reach-1         ,17273
    1080    1568    1987    1244    2482    4953    3892
River Rch & RM=UNT 103 in HW,Reach-1         ,12350
    1436    2114    2704    1707    3406    6796    5431
River Rch & RM=UNT 103 in HW,Reach-1         ,9753
    1646    2430    3114    1968    3928    7837    6279
River Rch & RM=UNT 103 in HW,Reach-1         ,3660
    1749    2585    3317    2098    4186    8351    6701
River Rch & RM=UNT 103 in HW,Reach-1         ,1842
    1749    2585    3317    2098    4186    8351    6701
Boundary for River Rch & Prof#=UNT 103 in HW,Reach-1         , 1
Up Type= 0
Dn Type= 3
Dn Slope=0.005
Boundary for River Rch & Prof#=UNT 103 in HW,Reach-1         , 2
Up Type= 0
Dn Type= 3
Dn Slope=0.005
Boundary for River Rch & Prof#=UNT 103 in HW,Reach-1         , 3
Up Type= 0
Dn Type= 3
Dn Slope=0.005
Boundary for River Rch & Prof#=UNT 103 in HW,Reach-1         , 4
Up Type= 0
Dn Type= 3
Dn Slope=0.005
Boundary for River Rch & Prof#=UNT 103 in HW,Reach-1         , 5
Up Type= 0
Dn Type= 3
Dn Slope=0.005
Boundary for River Rch & Prof#=UNT 103 in HW,Reach-1         , 6
Up Type= 0
Dn Type= 3
Dn Slope=0.005
Boundary for River Rch & Prof#=UNT 103 in HW,Reach-1         , 7
Up Type= 0
Dn Type= 3
Dn Slope=0.005
DSS Import GetInterval= 0
DSS Import GetPeak= 0
DSS Import FillOption= 0

--- UNT 103 in HW.g01 (geometry) ---

Geom Title=Existing Conditions
Program Version=5.05

River Reach=UNT 103 in HW   ,Reach-1
Reach XY= 30
       2020305.8     13615809.54       2019980.8     13615224.54
       2019290.8     13614594.54      2019076.76     13613880.49
       2018600.8     13613444.54       2017880.8     13612334.54
       2017610.8     13611574.54       2017490.8     13610854.54
       2017560.8     13610604.54       2017300.8     13610124.54
       2017250.8     13609734.54       2016600.8     13608854.54
       2016480.8     13608394.54       2015720.8     13608104.54
       2014740.8     13607444.54       2014270.8     13607384.54
       2013519.7     13606661.87       2012760.8     13606394.54
       2012020.8     13606364.54       2011670.8     13606634.54
       2011370.8     13606684.54       2010740.8     13606314.54
       2010180.8     13606294.54       2009860.8     13606054.54
       2008780.8     13606034.54       2008400.8     13605604.54
       2008320.8     13604824.54       2007850.8     13603794.54
      2007460.72     13603552.21       2007325.3     13603116.01

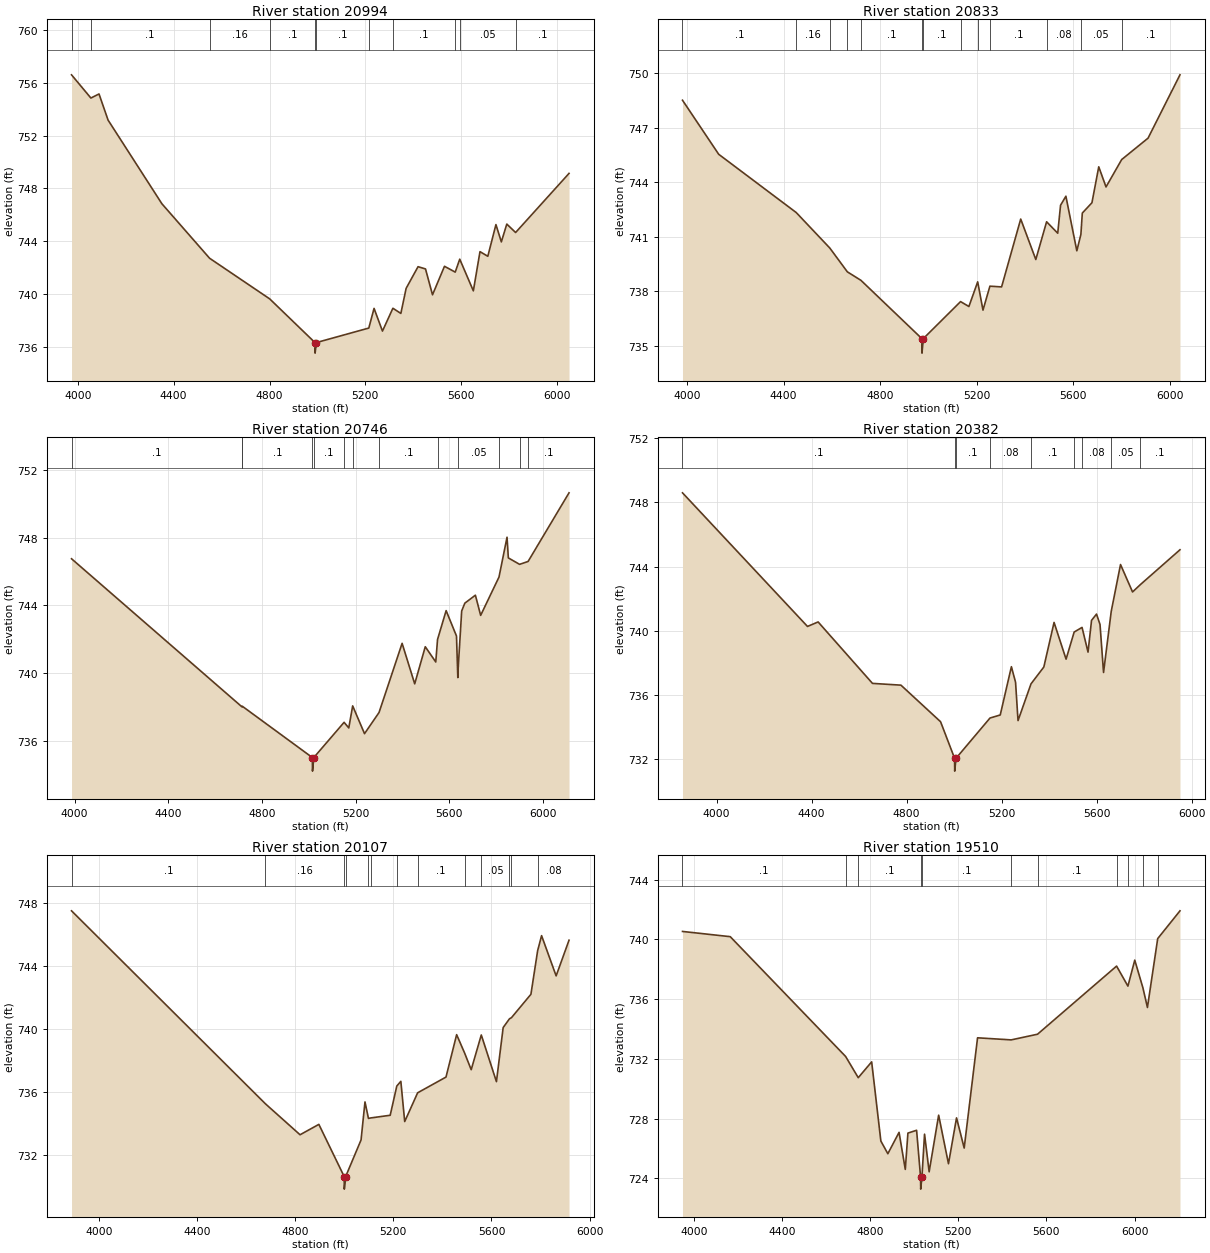
Type RM Length L Ch R = 1 ,20994   ,161,161,161
BEGIN DESCRIPTION:
UNT 103 in HW 43.0
END DESCRIPTION:
XS GIS Cut Line= 3
      2020847.54     13614779.31      2019810.21     13615174.28
      2018955.22     13615625.64
#Sta/Elev= 30
  3973.6   756.6  4054.4  754.84  4088.3  755.15  4126.1  753.17  4350.8  746.83
  4549.9   742.7  4800.9  739.62  4989.8  736.31  4990.3  735.51  4995.8  736.31
  5214.6  737.41  5236.5   738.9  5271.6  737.18  5315.1  738.91  5348.4  738.52
  5370.4  740.42  5420.1  742.06  5451.3  741.89  5480.5  739.93  5530.5  742.09
  5575.3  741.65  5594.2  742.63    5651  740.23  5678.7   743.2  5711.4  742.85
  5745.3  745.25  5767.9  743.94  5790.6  745.29  5827.4  744.65  6050.4  749.13
#Mann= 11 ,-1 , 0
  3973.6     .05       0  4054.4      .1       0  4549.9     .16       0
  4800.9      .1       0  4989.8     .07       0  4995.8      .1       0
  5214.6     .05       0  5315.1      .1       0  5575.3     .08       0
  5594.2     .05       0  5827.4      .1       0
Bank Sta=4989.8,4995.8
XS Rating Curve= 0 ,0
Exp/Cntr=0.3,0.1

Type RM Length L Ch R = 1 ,20833   ,87,87,87
BEGIN DESCRIPTION:
Mapping XS c4c98167
END DESCRIPTION:
XS GIS Cut Line= 4
      2020543.72     13614453.79      2020053.27     13614692.51
      2019632.26     13615226.36      2018878.56     13615585.88
#Sta/Elev= 30
  3981.4  748.52  4131.4  745.54  4452.4  742.33  4591.7  740.37  4664.2  739.06
  4720.7  738.59  4972.8  735.38  4973.3  734.58  4978.8  735.38  5133.1  737.42
  5167.6  737.15    5204  738.51  5225.9  736.95  5254.6  738.27    5303  738.23
  5382.2  741.97  5444.7  739.74  5489.4  741.82  5535.5  741.19  5547.2  742.73
  5569.3  743.23  5614.6  740.22  5631.4  741.12  5637.3   742.3  5677.2  742.87
  5705.4  744.85  5735.5  743.74  5800.4  745.25  5909.6  746.43  6041.8  749.92
#Mann= 13 ,-1 , 0
  3981.4      .1       0  4452.4     .16       0  4591.7      .1       0
  4664.2     .16       0  4720.7      .1       0  4972.8     .07       0
  4978.8      .1       0  5133.1     .08       0    5204     .05       0
  5254.6      .1       0  5489.4     .08       0  5631.4     .05       0
  5800.4      .1       0
Bank Sta=4972.8,4978.8
XS Rating Curve= 0 ,0
Exp/Cntr=0.3,0.1

Type RM Length L Ch R = 1 ,20746   ,364,364,364
BEGIN DESCRIPTION:
Mapping XS 2d26d092
END DESCRIPTION:
XS GIS Cut Line= 4
      2020461.25     13614380.01      2019975.14     13614623.06
      2019606.22     13615130.87      2018759.96     13615569.19
#Sta/Elev= 30
    3987  746.75  4714.8  738.01    4716  738.05  5015.4  735.02  5015.9  734.22
  5021.4  735.02  5150.8   737.1  5170.8  736.77  5187.4  738.07    5238  736.43
    5300  737.68  5398.5  741.76  5452.3  739.37  5497.4  741.56  5542.2  740.66
  5549.8  741.99  5586.5  743.69  5630.7  742.19  5636.4  739.74  5637.9  740.29
  5652.9  743.67  5666.3  744.13  5711.4   744.6  5733.9  743.41  5812.2  745.67
  5846.5  748.02  5852.1   746.8  5900.1  746.42  5936.4  746.59  6111.2  750.64
#Mann= 13 ,-1 , 0
    3987      .1       0  4714.8     .16       0    4716      .1       0
  5015.4     .07       0  5021.4      .1       0  5150.8     .08       0
  5187.4     .05       0    5300      .1       0  5549.8     .08       0
  5637.9     .05       0  5812.2      .1       0  5900.1     .08       0
  5936.4      .1       0
Bank Sta=5015.4,5021.4
XS Rating Curve= 0 ,0
Exp/Cntr=0.3,0.1

Type RM Length L Ch R = 1 ,20382   ,275,275,275
BEGIN DESCRIPTION:
UNT 103 in HW 42.0
END DESCRIPTION:
XS GIS Cut Line= 3
      2020509.01     13614319.24        2019225.       13614875.
      2018655.68     13615274.11
#Sta/Elev= 30
  3856.6   748.6  4382.9  740.27  4427.6  740.55  4656.4  736.72  4776.3  736.61
  4943.1  734.33  5002.1  732.05  5002.6  731.25  5008.1  732.05  5151.2  734.56
  5194.3  734.75  5241.3  737.76  5258.8  736.79  5269.2   734.4  5323.8  736.69
  5377.8  737.74  5420.9  740.52  5471.5  738.23  5505.5  739.92  5538.7  740.21
  5563.9  738.67  5578.7  740.65  5599.6  741.04  5614.4  740.39  5629.2   737.4
  5661.6  741.21  5700.7  744.13  5751.3  742.42  5784.4  742.88    5951  745.05
#Mann= 9 ,-1 , 0
  3856.6      .1       0  5002.1     .07       0  5008.1      .1       0
  5151.2     .08       0  5323.8      .1       0  5505.5     .05       0
  5538.7     .08       0  5661.6     .05       0  5784.4      .1       0
Bank Sta=5002.1,5008.1
XS Rating Curve= 0 ,0
Exp/Cntr=0.3,0.1

Type RM Length L Ch R = 1 ,20107   ,597,597,597
BEGIN DESCRIPTION:
UNT 103 in HW 41.0
END DESCRIPTION:
XS GIS Cut Line= 3
      2020305.05     13614115.23        2019275.       13614575.
      2018490.76     13615013.69
#Sta/Elev= 30
  3889.3  747.51  4679.1  735.23  4820.2  733.26  4896.8  733.92    5000   730.6
  5000.5   729.8    5006   730.6  5068.7  732.93  5084.7  735.35  5098.8   734.3
  5108.1  734.33  5187.4   734.5  5214.3  736.36  5230.8  736.66  5246.5   734.1
  5299.2  735.93  5414.7  736.93  5458.1  739.63  5490.3  738.47  5517.4   737.4
  5558.5  739.61  5620.2  736.64  5647.6  740.08  5673.3  740.64  5681.4  740.71
  5760.7   742.2    5788  744.97  5804.1  745.93  5863.4  743.37  5915.9  745.64
#Mann= 13 ,-1 , 0
  3889.3      .1       0  4679.1     .16       0    5000     .07       0
    5006     .16       0  5098.8      .1       0  5108.1     .08       0
  5214.3     .05       0  5299.2      .1       0  5490.3     .08       0
  5558.5     .05       0  5673.3      .1       0  5681.4     .05       0
    5788     .08       0
Bank Sta=5000,5006
XS Rating Curve= 0 ,0
Exp/Cntr=0.3,0.1

Type RM Length L Ch R = 1 ,19510   ,30,30,30
BEGIN DESCRIPTION:
Mapping XS 08b6ae37
END DESCRIPTION:
XS GIS Cut Line= 6
      2020005.56     13613829.64       2019242.5     13614176.01
      2019140.94     13614001.53      2019041.98     13614074.45
       2019117.5     13614246.32      2018372.68     13614728.12
#Sta/Elev= 30
  3948.4  740.53  4165.1  740.18  4688.8  732.16  4746.1  730.74    4807   731.8
  4848.7   726.5  4880.4  725.65  4931.3  727.08  4959.6   724.6  4971.5  727.03
  5010.9  727.22    5029  724.08  5029.5  723.28  5035.1  724.08    5047  726.96
  5067.9  724.44    5111  728.23  5155.6  724.98  5192.2  728.05  5226.9  726.03
  5287.6  733.41  5440.2  733.27  5559.8  733.65  5918.6  738.21    5970  736.87
  6001.1  738.61  6038.2  736.75  6058.6  735.44  6105.2  740.05  6206.3  741.91
#Mann= 11 ,-1 , 0
  3948.4      .1       0  4688.8     .16       0  4746.1      .1       0
    5029     .07       0  5035.1      .1       0  5440.2     .05       0
  5559.8      .1       0  5918.6     .08       0    5970     .05       0
  6038.2      .1       0  6105.2     .05       0
Bank Sta=5029,5035.1
XS Rating Curve= 0 ,0
Exp/Cntr=0.3,0.1

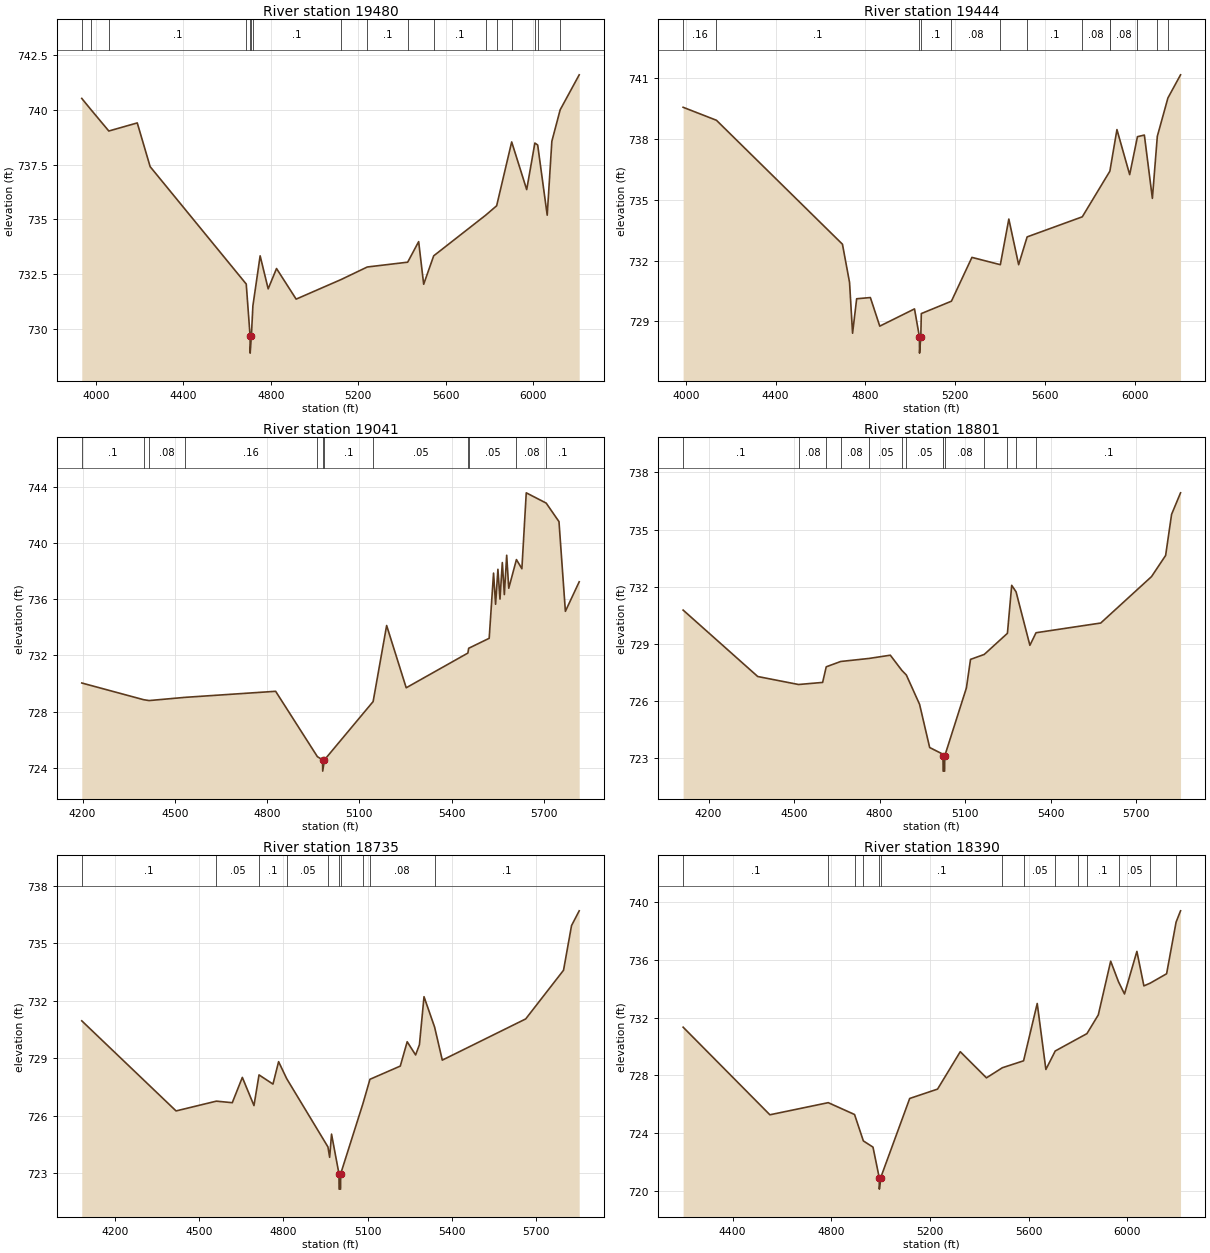
Type RM Length L Ch R = 1 ,19480   ,36,36,36
BEGIN DESCRIPTION:
Mapping XS 0ba0ede3
END DESCRIPTION:
XS GIS Cut Line= 6
      2019984.66     13613774.99      2019252.92     13614142.16
      2019091.46     13613985.91       2018992.5     13614069.24
      2019070.63     13614251.53      2018354.47     13614707.27
#Sta/Elev= 30
  3934.5  740.53  3974.6  740.04  4058.2  739.04  4188.4  739.41  4247.4  737.41
  4687.2  732.04  4704.7  729.68  4705.2  728.88  4710.8  729.68  4717.6  731.04
  4750.8  733.33  4787.6  731.82  4825.8  732.75  4915.6  731.35  5122.2  732.25
  5241.2  732.82  5426.1  733.04  5476.3  733.98  5499.3  732.03  5545.1  733.33
  5783.1  735.19  5833.3  735.62  5902.1  738.54  5970.8  736.36  6008.2  738.49
  6021.1   738.4  6064.7  735.19  6085.9  738.57    6124  740.01  6211.1  741.61
#Mann= 17 ,-1 , 0
  3934.5      .1       0  3974.6     .16       0  4058.2      .1       0
  4687.2     .16       0  4704.7     .07       0  4710.8     .16       0
  4717.6      .1       0  5122.2     .08       0  5241.2      .1       0
  5426.1     .05       0  5545.1      .1       0  5783.1     .08       0
  5833.3      .1       0  5902.1     .08       0  6008.2     .05       0
  6021.1      .1       0    6124     .05       0
Bank Sta=4704.7,4710.8
XS Rating Curve= 0 ,0
Exp/Cntr=0.3,0.1

Type RM Length L Ch R = 1 ,19444   ,403,403,403
BEGIN DESCRIPTION:
Mapping XS 481b65fc
END DESCRIPTION:
XS GIS Cut Line= 6
      2019961.23     13613741.13      2019271.15     13614077.05
       2019177.4     13613933.82      2018979.48     13613991.12
      2019008.13      13614228.1      2018358.58     13614682.78
#Sta/Elev= 30
  3988.1  739.56  4136.4  738.92  4697.5  732.81  4729.1  730.93  4742.6  728.42
  4760.8  730.12  4821.9  730.18  4863.7  728.77  5018.4  729.62  5040.3  728.24
  5040.8  727.44  5046.4  728.24  5048.7  729.39  5182.8     730  5274.1  732.16
  5400.6   731.8  5438.4  734.05  5482.1   731.8  5519.9  733.17  5765.5  734.16
  5888.3  736.41  5888.8  736.44  5919.8  738.46  5976.5  736.24  6011.1  738.11
  6041.9  738.19  6077.6  735.07  6099.6  738.13  6146.8  740.02    6203  741.16
#Mann= 13 ,-1 , 0
  3988.1     .16       0  4136.4      .1       0  5040.3     .07       0
  5046.4      .1       0  5182.8     .08       0  5400.6     .05       0
  5519.9      .1       0  5765.5     .08       0  5888.3      .1       0
  5888.8     .08       0  6011.1     .05       0  6099.6      .1       0
  6146.8     .05       0
Bank Sta=5040.3,5046.4
XS Rating Curve= 0 ,0
Exp/Cntr=0.3,0.1

Type RM Length L Ch R = 1 ,19041   ,240,240,240
BEGIN DESCRIPTION:
UNT 103 in HW 38.0
END DESCRIPTION:
XS GIS Cut Line= 3
      2019400.51     13613099.49        2018825.       13613675.
      2018297.26      13614280.1
#Sta/Elev= 30
  4197.6  730.04  4398.9  728.85  4416.5  728.79    4534  729.02  4827.7  729.45
  4963.4   724.8  4980.2  724.57  4980.7  723.77  4986.3  724.57  5144.6  728.72
  5188.5  734.13  5252.1   729.7  5452.6  732.17  5455.1  732.51  5521.8  733.22
    5536  737.86  5542.6  735.64  5550.2  738.13  5556.9  736.01  5564.5  738.61
  5571.1  736.33  5578.7  739.13  5585.4  736.78  5610.4  738.82  5628.1  738.17
  5642.3  743.57  5707.1  742.84  5748.7  741.52  5769.5  735.14  5814.4  737.24
#Mann= 12 ,-1 , 0
  4197.6      .1       0  4398.9     .05       0  4416.5     .08       0
    4534     .16       0  4963.4      .1       0  4980.2     .07       0
  4986.3      .1       0  5144.6     .05       0  5452.6     .08       0
  5455.1     .05       0  5610.4     .08       0  5707.1      .1       0
Bank Sta=4980.2,4986.3
XS Rating Curve= 0 ,0
Exp/Cntr=0.3,0.1

Type RM Length L Ch R = 1 ,18801   ,66,66,66
BEGIN DESCRIPTION:
UNT 103 in HW 37.0
END DESCRIPTION:
XS GIS Cut Line= 6
      2019257.66     13612892.34      2018828.44     13613209.87
      2018794.59     13613397.37      2018562.82     13613574.45
      2018549.79     13613686.43      2018078.41     13614082.29
#Sta/Elev= 30
  4110.8  730.77  4372.5  727.28  4515.6  726.86    4600  726.97  4612.7  727.79
  4663.4  728.07    4763  728.23  4837.4   728.4    4878   727.6  4893.6  727.36
    4940  725.82  4975.4  723.55  5020.5  723.21  5022.2  723.11  5022.7  722.31
  5027.8  722.31  5028.3  723.11  5104.2  726.68  5118.7  728.18  5166.8  728.44
  5248.1  729.55  5263.1  732.07  5278.4  731.73  5326.9  728.92  5348.4  729.58
  5575.3  730.09  5753.5  732.53  5802.9  733.64  5823.8   735.8  5855.2  736.93
#Mann= 14 ,-1 , 0
  4110.8      .1       0  4515.6     .08       0  4612.7     .05       0
  4663.4     .08       0    4763     .05       0    4878      .1       0
  4893.6     .05       0  5020.5     .08       0  5022.2     .04       0
  5028.3     .08       0  5166.8      .1       0  5248.1     .08       0
  5278.4     .05       0  5348.4      .1       0
Bank Sta=5022.2,5028.3
XS Rating Curve= 0 ,0
Exp/Cntr=0.3,0.1

Type RM Length L Ch R = 1 ,18735   ,345,345,345
BEGIN DESCRIPTION:
Mapping XS cf25d5f5
END DESCRIPTION:
XS GIS Cut Line= 6
       2019234.7      13612858.3      2018732.09     13613204.66
      2018737.29      13613353.1      2018521.15     13613496.32
      2018445.63     13613691.64      2018039.65     13614048.17
#Sta/Elev= 30
  4081.9  730.96  4417.6  726.26  4561.1  726.77  4617.8  726.69  4653.6  728.01
    4695  726.54    4713  728.14  4762.7  727.66  4782.7  728.83  4811.7  727.94
  4958.5  724.38  4964.5  723.84  4971.2  725.05  4997.7  722.98  4998.2  722.18
  5003.3  722.18  5003.8  722.98  5083.2  726.65    5108  727.91    5216   728.6
  5240.6  729.87  5270.6  729.18  5284.2  729.72  5300.5  732.22  5338.3  730.63
  5365.6  728.91  5662.6  731.06  5797.3   733.6  5825.8  735.93  5853.1   736.7
#Mann= 10 ,-1 , 0
  4081.9      .1       0  4561.1     .05       0    4713      .1       0
  4811.7     .05       0  4958.5     .08       0  4997.7     .07       0
  5003.8     .08       0  5083.2      .1       0    5108     .08       0
  5338.3      .1       0
Bank Sta=4997.7,5003.8
XS Rating Curve= 0 ,0
Exp/Cntr=0.3,0.1

Type RM Length L Ch R = 1 ,18390   ,343,343,343
BEGIN DESCRIPTION:
UNT 103 in HW 36.0
END DESCRIPTION:
XS GIS Cut Line= 3
      2019078.27     13612632.06        2018475.       13613175.
      2017674.98     13614075.02
#Sta/Elev= 30
  4199.9  731.34  4551.5  725.27    4788  726.11  4894.6  725.29  4930.3  723.46
  4969.3  723.03  4994.6  720.92  4995.1  720.12  5000.7  720.92  5118.1   726.4
    5231  727.05    5323  729.64  5429.2  727.83  5493.7  728.53  5579.6  729.01
  5634.9  732.98    5670  728.41  5707.9  729.69  5800.7  730.56  5836.2  730.89
  5882.4  732.19  5932.6  735.91  5964.4  734.48  5988.6  733.64  6038.8  736.59
  6067.2   734.2  6092.7  734.39  6159.2  735.04  6197.7  738.62  6215.7   739.4
#Mann= 14 ,-1 , 0
  4199.9      .1       0    4788     .08       0  4894.6     .05       0
  4930.3      .1       0  4994.6     .07       0  5000.7      .1       0
  5493.7     .08       0  5579.6     .05       0  5707.9      .1       0
  5800.7     .08       0  5836.2      .1       0  5964.4     .05       0
  6092.7      .1       0  6197.7     .05       0
Bank Sta=4994.6,5000.7
XS Rating Curve= 0 ,0
Exp/Cntr=0.3,0.1

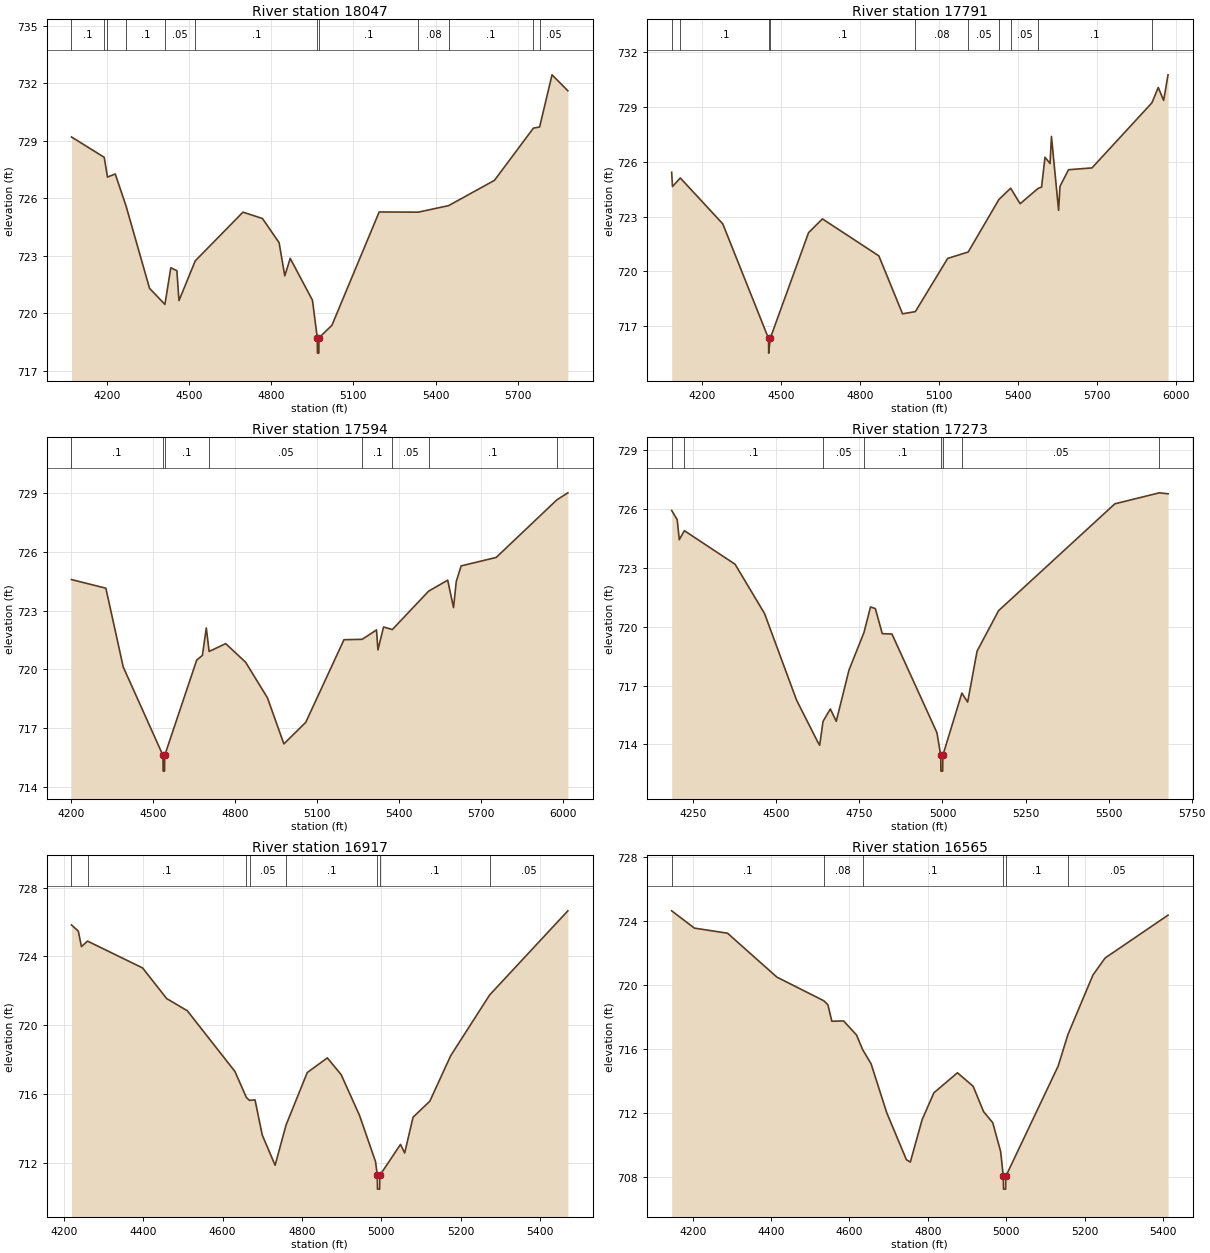
Type RM Length L Ch R = 1 ,18047   ,256,256,256
BEGIN DESCRIPTION:
Mapping XS b4344518
END DESCRIPTION:
XS GIS Cut Line= 4
      2018791.95     13612280.19      2018333.65     13612498.93
      2018219.07     13613186.43      2017672.21     13613446.84
#Sta/Elev= 30
  4071.6  729.19    4191  728.13  4202.9   727.1  4231.3  727.26  4271.3  725.56
  4356.3   721.3  4412.4  720.46  4433.9  722.37    4456  722.22  4463.7  720.66
    4523  722.73  4697.1  725.27  4768.1  724.94  4828.9  723.68  4849.6  721.95
  4869.4  722.86  4950.5  720.68  4968.2  718.72  4968.7  717.92  4973.8  717.92
  4974.3  718.72  5021.5  719.37  5193.9  725.28  5336.6  725.27  5447.2  725.61
  5614.5  726.93  5756.4  729.65  5779.1  729.71  5824.4  732.43  5882.1   731.6
#Mann= 12 ,-1 , 0
  4071.6      .1       0    4191     .08       0  4202.9     .05       0
  4271.3      .1       0  4412.4     .05       0    4523      .1       0
  4968.2     .07       0  4974.3      .1       0  5336.6     .08       0
  5447.2      .1       0  5756.4     .08       0  5779.1     .05       0
Bank Sta=4968.2,4974.3
XS Rating Curve= 0 ,0
Exp/Cntr=0.3,0.1

Type RM Length L Ch R = 1 ,17791   ,197,197,197
BEGIN DESCRIPTION:
Mapping XS 55787d66
END DESCRIPTION:
XS GIS Cut Line= 5
      2018521.18     13611946.81      2018125.32     13612363.51
      2018120.11     13612764.55       2018177.4     13613061.43
      2017599.63     13613243.61
#Sta/Elev= 30
  4084.1  725.42  4087.2  724.64  4116.8  725.11  4278.1   722.6  4451.8  716.33
  4452.3  715.53    4458  716.33  4603.7  722.12  4656.4  722.87  4870.4  720.85
  4960.4  717.68    5009   717.8  5131.7  720.71  5209.6  721.06  5326.1  723.93
  5370.7  724.55  5406.7   723.7  5474.9  724.54    5488  724.61  5501.1  726.24
  5520.3   725.9  5525.6  727.38  5552.7  723.34  5557.9  724.65  5590.3  725.56
  5679.4  725.66  5906.9  729.22    5931  730.06  5951.4  729.35  5968.1  730.75
#Mann= 10 ,-1 , 0
  4084.1     .05       0  4116.8      .1       0  4451.8     .07       0
    4458      .1       0    5009     .08       0  5209.6     .05       0
  5326.1      .1       0  5370.7     .05       0  5474.9      .1       0
  5906.9     .08       0
Bank Sta=4451.8,4458
XS Rating Curve= 0 ,0
Exp/Cntr=0.3,0.1

Type RM Length L Ch R = 1 ,17594   ,321,321,321
BEGIN DESCRIPTION:
Mapping XS 6c05dba8
END DESCRIPTION:
XS GIS Cut Line= 6
      2018469.05     13611941.65      2018031.57     13612337.47
      2018031.57     13612759.35      2018078.44     13612926.01
      2018088.86     13613030.18      2017583.61     13613181.23
#Sta/Elev= 30
  4202.2  724.58  4328.1  724.14  4391.6  720.12  4537.2   715.6  4537.7   714.8
  4542.9   714.8  4543.4   715.6  4660.6  720.47  4681.5  720.71  4695.7  722.11
    4706  720.91  4766.7  721.31  4839.7  720.36  4919.7  718.54  4979.7  716.19
  5059.7  717.29  5199.7  721.51  5266.4  721.53  5318.8  722.01    5324  720.99
  5344.6  722.16  5376.7  722.03  5509.6  723.99  5579.4  724.55  5600.7  723.15
  5610.7  724.48  5628.6  725.28  5756.8  725.71  5978.9  728.65  6019.2  729.01
#Mann= 8 ,-1 , 0
  4202.2      .1       0  4537.2     .04       0  4543.4      .1       0
    4706     .05       0  5266.4      .1       0  5376.7     .05       0
  5509.6      .1       0  5978.9     .08       0
Bank Sta=4537.2,4543.4
XS Rating Curve= 0 ,0
Exp/Cntr=0.3,0.1

Type RM Length L Ch R = 1 ,17273   ,356,356,356
BEGIN DESCRIPTION:
Mapping XS 20934895
END DESCRIPTION:
XS GIS Cut Line= 3
      2018536.78     13611905.18      2018031.57     13612066.64
      2017453.46     13612837.45
#Sta/Elev= 30
    4185  725.93  4201.7  725.46  4207.9  724.44  4223.2   724.9  4375.8  723.19
  4464.4  720.68  4560.9  716.26  4625.2  714.11  4630.5  713.96  4640.6  715.18
  4662.6  715.81  4680.3  715.18  4718.8   717.8  4763.8  719.71  4783.4  721.01
    4798  720.93  4818.8  719.65    4848  719.63  4983.4   714.6  4994.8  713.44
  4995.3  712.64  5000.6  712.64  5001.1  713.44  5058.4  716.62  5075.8  716.16
  5104.2  718.76  5168.8  720.82  5518.8  726.27  5652.8  726.83  5678.9  726.78
#Mann= 8 ,-1 , 0
    4185     .05       0  4223.2      .1       0  4640.6     .05       0
  4763.8      .1       0  4994.8     .07       0  5001.1      .1       0
  5058.4     .05       0  5652.8      .1       0
Bank Sta=4994.8,5001.1
XS Rating Curve= 0 ,0
Exp/Cntr=0.3,0.1

Type RM Length L Ch R = 1 ,16917   ,352,352,352
BEGIN DESCRIPTION:
UNT 103 in HW 32.0
END DESCRIPTION:
XS GIS Cut Line= 3
      2018541.95     13611855.71        2017775.       13611975.
      2017325.01       13612125.
#Sta/Elev= 30
  4219.4  725.83  4236.6  725.47  4244.5  724.57  4259.8  724.89  4398.5  723.33
  4459.2  721.55  4511.2  720.84  4631.2  717.31    4660   715.8  4667.9  715.63
  4681.8  715.66  4699.9  713.62  4732.4  711.86    4760   714.2  4813.4  717.25
    4864   718.1  4898.7  717.13    4945  714.76  4985.5  712.06  4989.8  711.27
  4990.3  710.47  4995.7  710.47  4996.2  711.27  5048.3  713.07  5058.8  712.57
  5079.9  714.65  5122.1  715.58  5174.8  718.23  5272.9  721.76  5469.9  726.65
#Mann= 8 ,-1 , 0
  4219.4     .05       0  4259.8      .1       0    4660     .08       0
  4667.9     .05       0    4760      .1       0  4989.8     .07       0
  4996.2      .1       0  5272.9     .05       0
Bank Sta=4989.8,4996.2
XS Rating Curve= 0 ,0
Exp/Cntr=0.3,0.1

Type RM Length L Ch R = 1 ,16565   ,204,204,204
BEGIN DESCRIPTION:
UNT 103 in HW 31.0
END DESCRIPTION:
XS GIS Cut Line= 3
      2018502.91     13611621.33        2017625.       13611675.
       2017248.9     13611766.87
#Sta/Elev= 30
  4146.3  724.62  4204.3  723.54    4289  723.22  4414.7  720.48  4534.6     719
    4545  718.75    4555  717.72    4585  717.74  4618.1  716.86  4633.4  715.96
  4655.2  715.06  4695.2     712  4745.3  709.07  4755.3  708.92  4785.4  711.57
  4815.5  713.25  4875.6   714.5  4915.6  713.66  4942.3  712.07  4965.7  711.38
  4985.8  709.58  4992.6  708.03  4993.1  707.23  4998.5  707.23    4999  708.03
  5132.6  714.92  5157.5  716.89  5221.4  720.61  5252.3  721.67    5413  724.35
#Mann= 6 ,-1 , 0
  4146.3      .1       0  4534.6     .08       0  4633.4      .1       0
  4992.6     .07       0    4999      .1       0  5157.5     .05       0
Bank Sta=4992.6,4999
XS Rating Curve= 0 ,0
Exp/Cntr=0.3,0.1

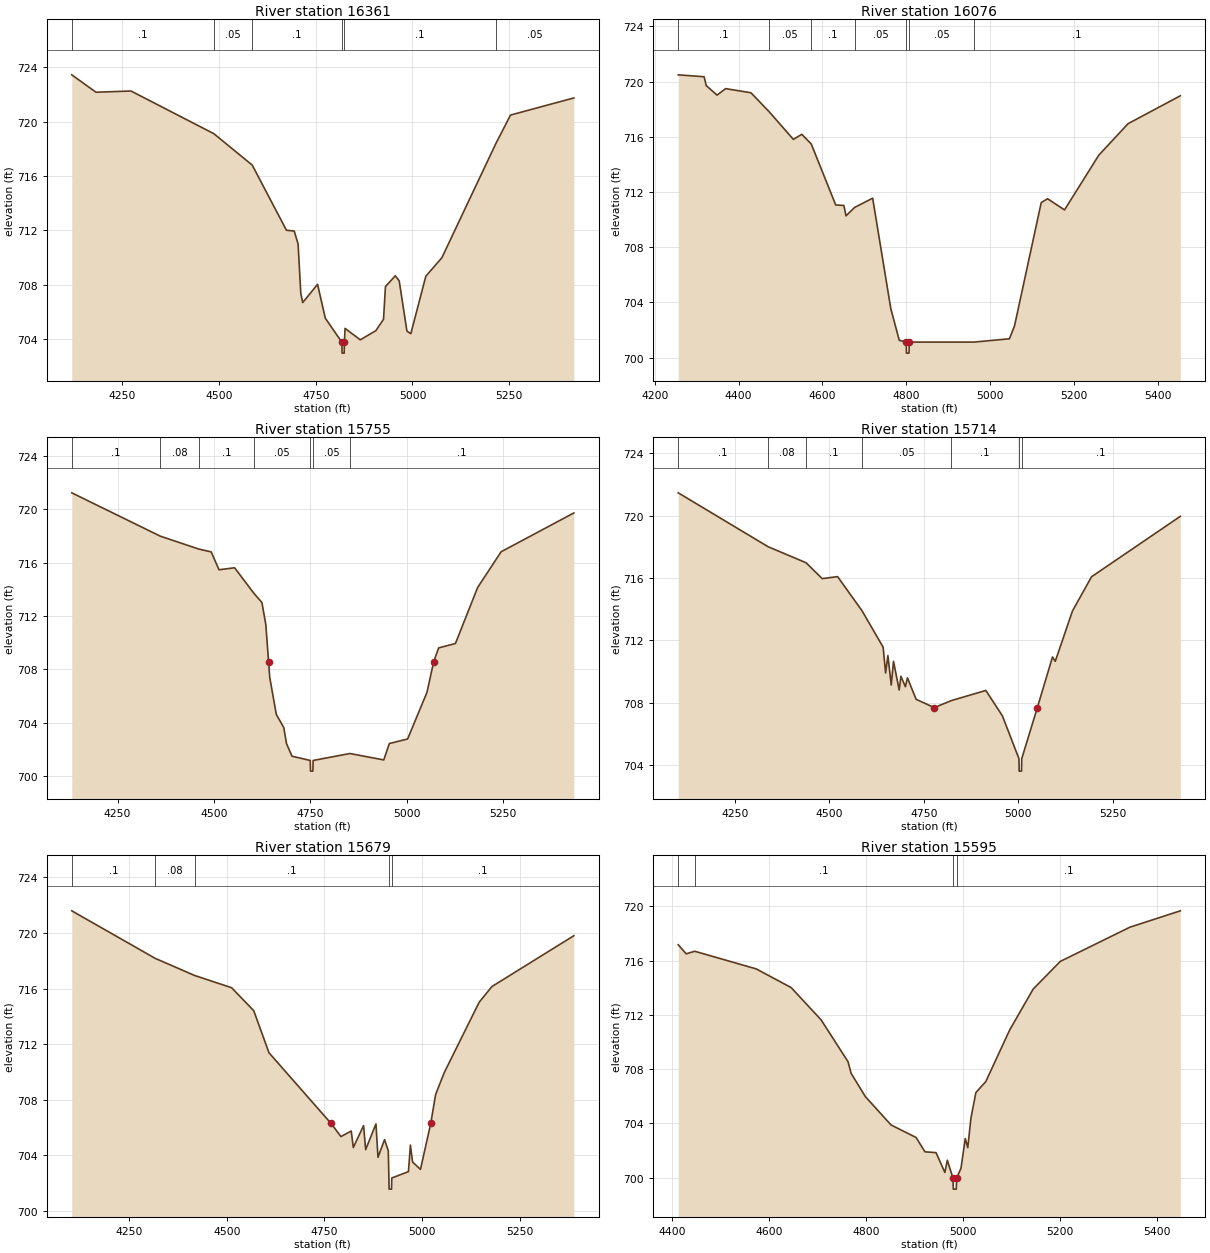
Type RM Length L Ch R = 1 ,16361   ,285,285,285
BEGIN DESCRIPTION:
Mapping XS d983c39d
END DESCRIPTION:
XS GIS Cut Line= 2
      2018487.34     13611405.18      2017195.58     13611524.98
#Sta/Elev= 30
  4119.7  723.45  4182.3  722.17  4272.7  722.26  4486.9  719.12    4586  716.81
  4674.4  712.02  4694.5  711.96  4704.5  711.01  4711.5  707.37  4716.5   706.7
  4754.8  708.04  4774.8  705.55  4817.7  703.78  4818.2  702.98  4823.6  702.98
  4824.1  703.78  4825.9   704.8  4865.2  703.96  4905.4  704.63  4925.2  705.47
  4930.2  707.87  4955.6  708.67  4965.7   708.3  4985.7   704.6  4995.8  704.41
  5034.6  708.64  5076.1     710  5215.6   718.4  5253.4  720.49    5417  721.75
#Mann= 6 ,-1 , 0
  4119.7      .1       0  4486.9     .05       0    4586      .1       0
  4817.7     .07       0  4824.1      .1       0  5215.6     .05       0
Bank Sta=4817.7,4824.1
XS Rating Curve= 0 ,0
Exp/Cntr=0.3,0.1

Type RM Length L Ch R = 1 ,16076   ,321,321,321
BEGIN DESCRIPTION:
Mapping XS 5185091d
END DESCRIPTION:
XS GIS Cut Line= 2
      2018346.69     13611090.07      2017161.73     13611269.77
#Sta/Elev= 30
  4255.7  720.49  4317.5  720.35  4322.5  719.71  4348.4  719.02  4368.7  719.49
  4429.3  719.19  4473.2   717.8  4530.5  715.81  4550.7  716.18  4573.2  715.48
  4631.6  711.06  4651.1  711.02  4656.2  710.27  4676.8  710.88  4719.8  711.55
  4763.1  703.55  4783.3  701.25    4800  701.12  4800.5  700.32  4806.6  700.32
  4807.2  701.12  4961.7  701.12  5046.3  701.36  5058.5   702.3  5122.2  711.23
  5137.4  711.51  5177.8   710.7  5259.7  714.67  5329.5  716.95  5454.2  718.97
#Mann= 7 ,-1 , 0
  4255.7      .1       0  4473.2     .05       0  4573.2      .1       0
  4676.8     .05       0    4800     .07       0  4807.2     .05       0
  4961.7      .1       0
Bank Sta=4800,4807.2
XS Rating Curve= 0 ,0
Exp/Cntr=0.3,0.1

Type RM Length L Ch R = 1 ,15755   ,41,41,41
BEGIN DESCRIPTION:
Mapping XS 2865c112
END DESCRIPTION:
XS GIS Cut Line= 6
       2018362.3     13610965.07      2017836.25     13611048.41
      2017791.98     13611004.14      2017700.84     13610954.66
      2017539.38     13610910.39      2017108.54     13610977.87
#Sta/Elev= 30
  4131.1  721.23  4360.8  717.98  4460.9  717.01  4492.9   716.8  4513.1  715.46
  4553.6  715.61  4603.5   713.7  4624.5     713  4634.6  711.34 4641.67708.5751
  4644.7  707.39  4661.8  704.61  4681.1  703.63  4688.2  702.43  4702.4  701.48
  4749.9  701.16  4750.5  700.36  4756.7  700.36  4757.3  701.16  4852.7  701.68
  4940.6   701.2    4955  702.43  5002.4  702.77  5052.7  706.27 5070.17 708.576
    5083   709.6  5126.5  709.93  5184.1  714.13    5245  716.81  5433.7  719.72
#Mann= 7 ,-1 , 0
  4131.1      .1       0  4360.8     .08       0  4460.9      .1       0
  4603.5     .05       0  4749.9     .07       0  4757.3     .05       0
  4852.7      .1       0
Bank Sta=4641.67,5070.17
XS Rating Curve= 0 ,0
Exp/Cntr=0.3,0.1

Type RM Length L Ch R = 1 ,15714   ,35,35,35
BEGIN DESCRIPTION:
Mapping XS 71a7bd47
END DESCRIPTION:
XS GIS Cut Line= 6
      2018370.09     13610936.43      2017890.94     13611024.97
      2017711.25     13610923.41        2017555.     13610881.74
      2017419.59     13610879.14      2017088.09     13610946.47
#Sta/Elev= 30
  4099.7  721.47  4337.7  718.01  4438.3  716.98  4481.1  715.96  4521.8  716.09
  4586.4   713.9  4642.4  711.56  4648.9   709.9    4655  711.02  4663.9  709.13
  4669.9  710.65  4684.9  708.81  4689.5  709.69  4701.3  709.02  4706.8  709.59
  4729.8  708.21 4777.98707.6785  4823.2  708.13  4914.4  708.78  4958.3  707.15
  5002.1   704.4  5002.7   703.6  5008.9   703.6  5009.5   704.4 5050.86 707.679
    5091  710.93  5098.3  710.65  5143.8  713.88  5194.4  716.08  5429.5  719.96
#Mann= 7 ,-1 , 0
  4099.7      .1       0  4337.7     .08       0  4438.3      .1       0
  4586.4     .05       0  4823.2      .1       0  5002.1     .07       0
  5009.5      .1       0
Bank Sta=4777.98,5050.86
XS Rating Curve= 0 ,0
Exp/Cntr=0.3,0.1

Type RM Length L Ch R = 1 ,15679   ,84,84,84
BEGIN DESCRIPTION:
Mapping XS b206c1d0
END DESCRIPTION:
XS GIS Cut Line= 6
      2018346.69     13610910.38      2017903.96     13610996.32
      2017690.42     13610889.55      2017557.61     13610845.28
      2017476.88      13610855.7      2017108.54     13610923.14
#Sta/Elev= 30
  4102.9   721.6  4316.6  718.18  4417.4  716.95  4512.1  716.07  4568.8  714.42
  4607.9  711.39 4766.89706.3043  4792.1  705.36  4818.5  705.76  4823.8  704.57
  4850.1  706.15  4855.4  704.42  4881.8  706.27    4887  703.87  4903.8  705.14
  4913.4  704.34  4914.9  702.38  4915.5  701.58  4921.7  701.58  4922.3  702.38
    4965  702.84    4970  704.75  4975.6  703.53  4995.8     703 5022.07706.3043
  5034.6  708.39  5056.6  709.96    5146  715.02  5178.6  716.15  5388.5  719.81
#Mann= 5 ,-1 , 0
  4102.9      .1       0  4316.6     .08       0  4417.4      .1       0
  4914.9     .07       0  4922.3      .1       0
Bank Sta=4766.89,5022.07
XS Rating Curve= 0 ,0
Exp/Cntr=0.3,0.1

Type RM Length L Ch R = 1 ,15595   ,361,361,361
BEGIN DESCRIPTION:
UNT 103 in HW 28.0
END DESCRIPTION:
XS GIS Cut Line= 3
      2018081.03     13610634.35        2017525.       13610775.
      2017073.21     13610876.54
#Sta/Elev= 30
  4411.9  717.17  4428.4   716.5  4445.8  716.69  4572.8  715.39  4645.1  714.01
  4706.9  711.63  4762.4  708.55  4768.8  707.69  4798.3  705.97  4851.3  703.88
  4902.9  702.96  4921.3   701.9  4944.2  701.84  4962.4  700.38  4967.5  701.28
  4979.2  699.95  4979.8  699.15    4986  699.15  4986.6  699.95  4995.7  700.69
  5004.5  702.88  5009.7  702.21  5016.2  704.38  5026.4  706.27  5046.9  707.08
  5096.3  710.89  5144.7   713.9  5200.7  715.94  5344.2  718.46  5448.5  719.67
#Mann= 4 ,-1 , 0
  4411.9     .05       0  4445.8      .1       0  4979.2     .07       0
  4986.6      .1       0
Bank Sta=4979.2,4986.6
XS Rating Curve= 0 ,0
Exp/Cntr=0.3,0.1

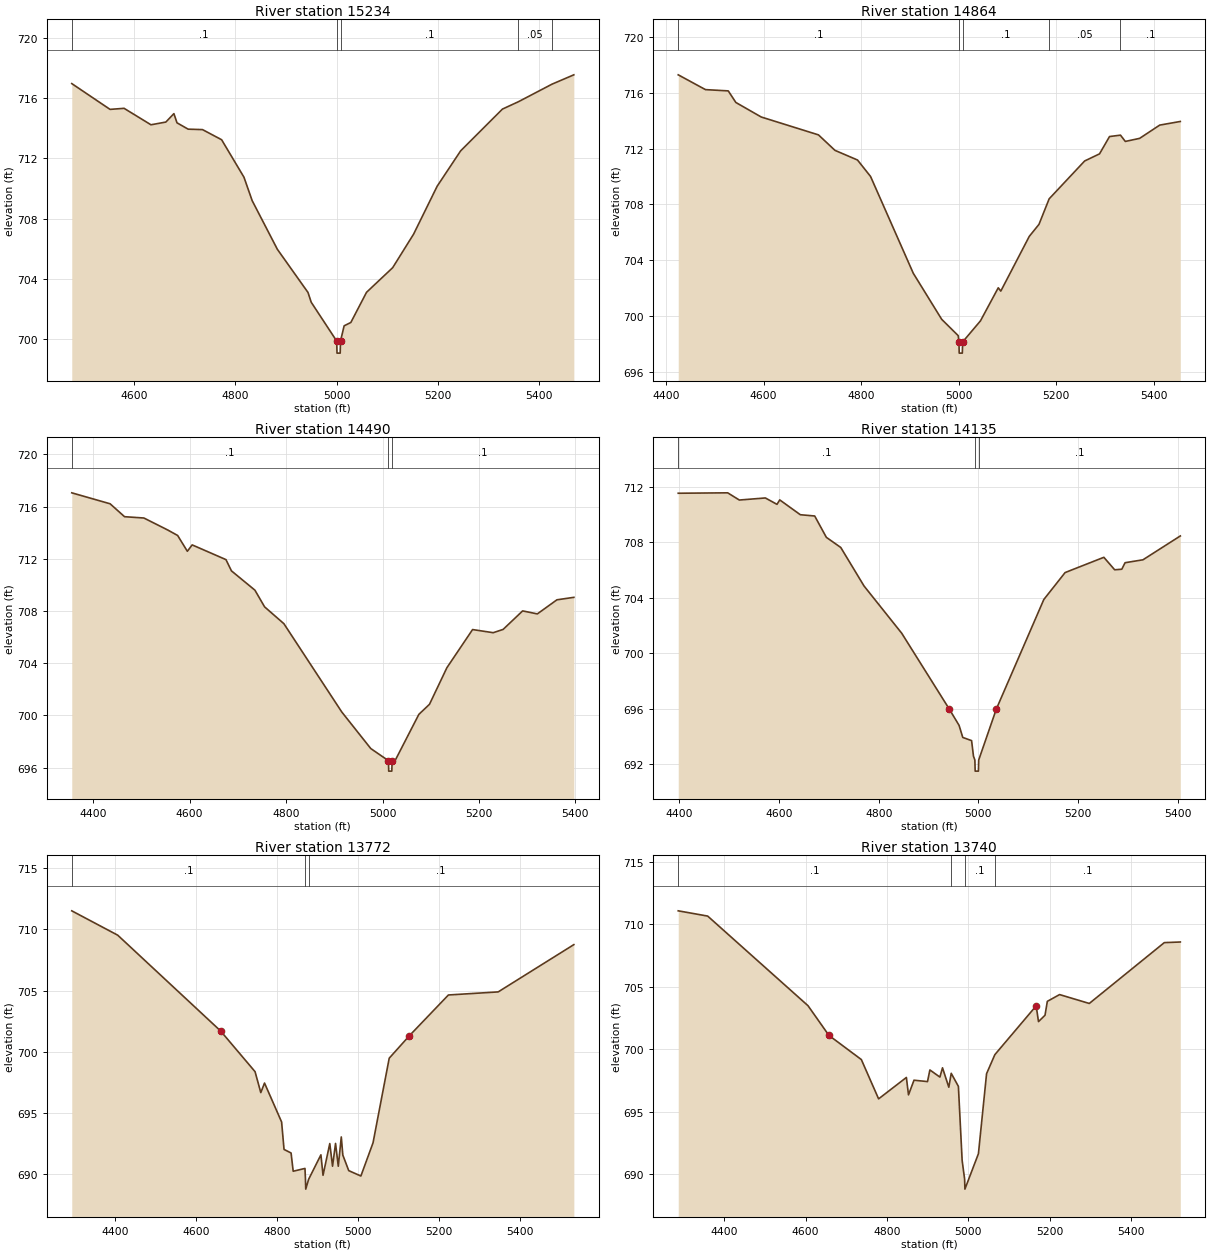
Type RM Length L Ch R = 1 ,15234   ,370,370,370
BEGIN DESCRIPTION:
UNT 103 in HW 27.0
END DESCRIPTION:
XS GIS Cut Line= 3
       2017953.4     13610222.91        2017475.       13610475.
      2017038.41     13610587.05
#Sta/Elev= 30
  4477.1  716.95  4552.7  715.24  4580.4  715.31  4633.5  714.22  4662.9   714.4
  4678.8  714.96  4684.9  714.35  4706.9  713.93  4735.3   713.9    4773  713.23
  4817.1  710.75  4833.4  709.19  4883.1  705.97  4943.6  703.11    4950  702.46
  5000.3  699.89  5000.9  699.09  5007.2  699.09  5007.8  699.89    5015   700.9
  5028.2  701.12  5059.2  703.12  5110.8  704.75  5152.1  706.97  5198.7  710.15
    5245  712.49  5327.6  715.26  5359.3  715.75  5425.4  716.91  5468.6  717.53
#Mann= 5 ,-1 , 0
  4477.1      .1       0  5000.3     .07       0  5007.8      .1       0
  5359.3     .05       0  5425.4      .1       0
Bank Sta=5000.3,5007.8
XS Rating Curve= 0 ,0
Exp/Cntr=0.3,0.1

Type RM Length L Ch R = 1 ,14864   ,374,374,374
BEGIN DESCRIPTION:
UNT 103 in HW 26.0
END DESCRIPTION:
XS GIS Cut Line= 3
      2017898.74     13610011.95        2017325.       13610175.
      2016903.97     13610277.57
#Sta/Elev= 30
  4424.8  717.28  4480.7  716.22  4527.4  716.13    4543   715.3    4595  714.26
  4712.4  712.98  4746.3  711.87  4792.5  711.18  4819.3     710  4906.9  703.07
  4965.2  699.77  4999.1   698.6  5000.6  698.15  5001.1  697.35  5007.5  697.35
  5008.1  698.15  5044.7  699.66  5081.2  702.03  5086.4  701.79  5144.8  705.71
  5164.7  706.57  5185.6   708.4  5258.4  711.11  5288.9  711.62  5309.4  712.86
  5331.9  712.96  5341.8  712.51  5371.2  712.73  5412.4  713.68  5454.6  713.94
#Mann= 5 ,-1 , 0
  4424.8      .1       0  5000.6     .07       0  5008.1      .1       0
  5185.6     .05       0  5331.9      .1       0
Bank Sta=5000.6,5008.1
XS Rating Curve= 0 ,0
Exp/Cntr=0.3,0.1

Type RM Length L Ch R = 1 ,14490   ,355,355,355
BEGIN DESCRIPTION:
UNT 103 in HW 25.0
END DESCRIPTION:
XS GIS Cut Line= 3
      2017914.39      13609855.7        2017275.       13609825.
      2016880.51     13609897.37
#Sta/Elev= 30
  4355.6  717.06  4435.1  716.22  4465.1  715.23  4505.2  715.13  4555.2   714.2
  4575.2  713.79  4595.3  712.58  4605.3  713.07  4675.4  711.94  4686.7  711.08
  4735.4   709.6  4755.5  708.32  4795.5  707.03  4915.6  700.26  4975.7  697.46
  5012.3  696.53  5012.9  695.73  5019.3  695.73  5019.9  696.53  5027.4  696.63
  5075.4  700.08  5097.4  700.85  5133.6  703.66  5186.8  706.58  5229.6  706.34
  5250.1  706.59  5290.6  708.01  5321.1  707.78  5361.7  708.86  5396.8  709.05
#Mann= 3 ,-1 , 0
  4355.6      .1       0  5012.3     .07       0  5019.9      .1       0
Bank Sta=5012.3,5019.9
XS Rating Curve= 0 ,0
Exp/Cntr=0.3,0.1

Type RM Length L Ch R = 1 ,14135   ,363,363,363
BEGIN DESCRIPTION:
UNT 103 in HW 24.0
END DESCRIPTION:
XS GIS Cut Line= 3
      2017661.74     13609290.61        2017125.       13609525.
      2016808.83     13609805.13
#Sta/Elev= 30
  4397.5  711.53  4496.8  711.56  4520.2  711.04  4572.4  711.19  4595.8  710.73
  4601.3  711.05  4642.7  709.98  4671.5  709.89  4694.9  708.35  4723.8  707.62
  4770.6  704.84  4846.3  701.43 4941.76695.9635  4961.4  694.79  4968.8  693.92
  4986.5  693.69  4990.3  692.57  4993.1  692.29  4993.7  691.49  5000.2  691.49
  5000.8  692.29 5036.16695.9634  5131.6  703.87  5174.3  705.81  5252.1  706.91
  5273.8  706.01  5288.1  706.05  5294.7  706.52  5330.6  706.73  5405.6  708.45
#Mann= 3 ,-1 , 0
  4397.5      .1       0  4993.1     .07       0  5000.8      .1       0
Bank Sta=4941.76,5036.16
XS Rating Curve= 0 ,0
Exp/Cntr=0.3,0.1

Type RM Length L Ch R = 1 ,13772   ,32,32,32
BEGIN DESCRIPTION:
Mapping XS 572a421f
END DESCRIPTION:
XS GIS Cut Line= 6
      2017484.72     13608907.76      2017039.38     13609196.85
      2016945.63     13609222.89      2016914.38     13609251.53
      2016911.77     13609452.05      2016724.26     13609769.78
#Sta/Elev= 30
  4292.7  711.51  4406.3  709.52  4660.1  701.71  4745.4  698.38  4759.6  696.67
  4768.8  697.45    4811  694.27    4817  692.03  4834.4  691.74  4839.6  690.25
  4868.7  690.48  4869.9  689.59  4870.6  688.79  4877.7  689.59  4908.1  691.59
  4913.3  689.92    4930  692.51  4936.8  690.66  4944.2  692.52    4951  690.66
  4958.4  693.05  4962.2  691.57  4976.8   690.3  5006.8  689.86  5036.8  692.57
  5076.8  699.48  5126.8  701.32    5223  704.64  5345.9  704.89  5532.8  708.75
#Mann= 3 ,-1 , 0
  4292.7      .1       0  4869.9     .07       0  4877.7      .1       0
Bank Sta=4660.1,5126.8
XS Rating Curve= 0 ,0
Exp/Cntr=0.3,0.1

Type RM Length L Ch R = 1 ,13740   ,26,26,26
BEGIN DESCRIPTION:
UNT 103 in HW 23.0
END DESCRIPTION:
XS GIS Cut Line= 6
      2017458.64     13608899.98      2017034.17      13609165.6
      2016906.57     13609212.47      2016883.13     13609251.53
      2016880.08      13609431.3      2016700.82     13609754.18
#Sta/Elev= 30
  4287.5  711.06  4359.8  710.64  4606.2  703.48  4657.5  701.11  4737.1  699.18
  4779.5  696.04  4847.7  697.75  4852.9  696.36  4866.4  697.53  4899.6  697.42
  4905.4  698.35    4930  697.78  4936.4  698.52  4951.9  696.97  4957.8  698.08
  4975.4  697.04  4984.6  691.12  4990.7  689.63  4991.4  688.83  5024.6  691.66
  5044.6  698.05  5064.9  699.57  5166.4  703.47  5172.1  702.21  5188.1  702.72
  5193.8  703.83  5223.9  704.37  5296.8  703.66    5481  708.52  5520.3  708.57
#Mann= 4 ,-1 , 0
  4287.5      .1       0  4957.8     .07       0  4990.7      .1       0
  5064.9      .1       0
Bank Sta=4657.5,5166.4
XS Rating Curve= 0 ,0
Exp/Cntr=0.3,0.1