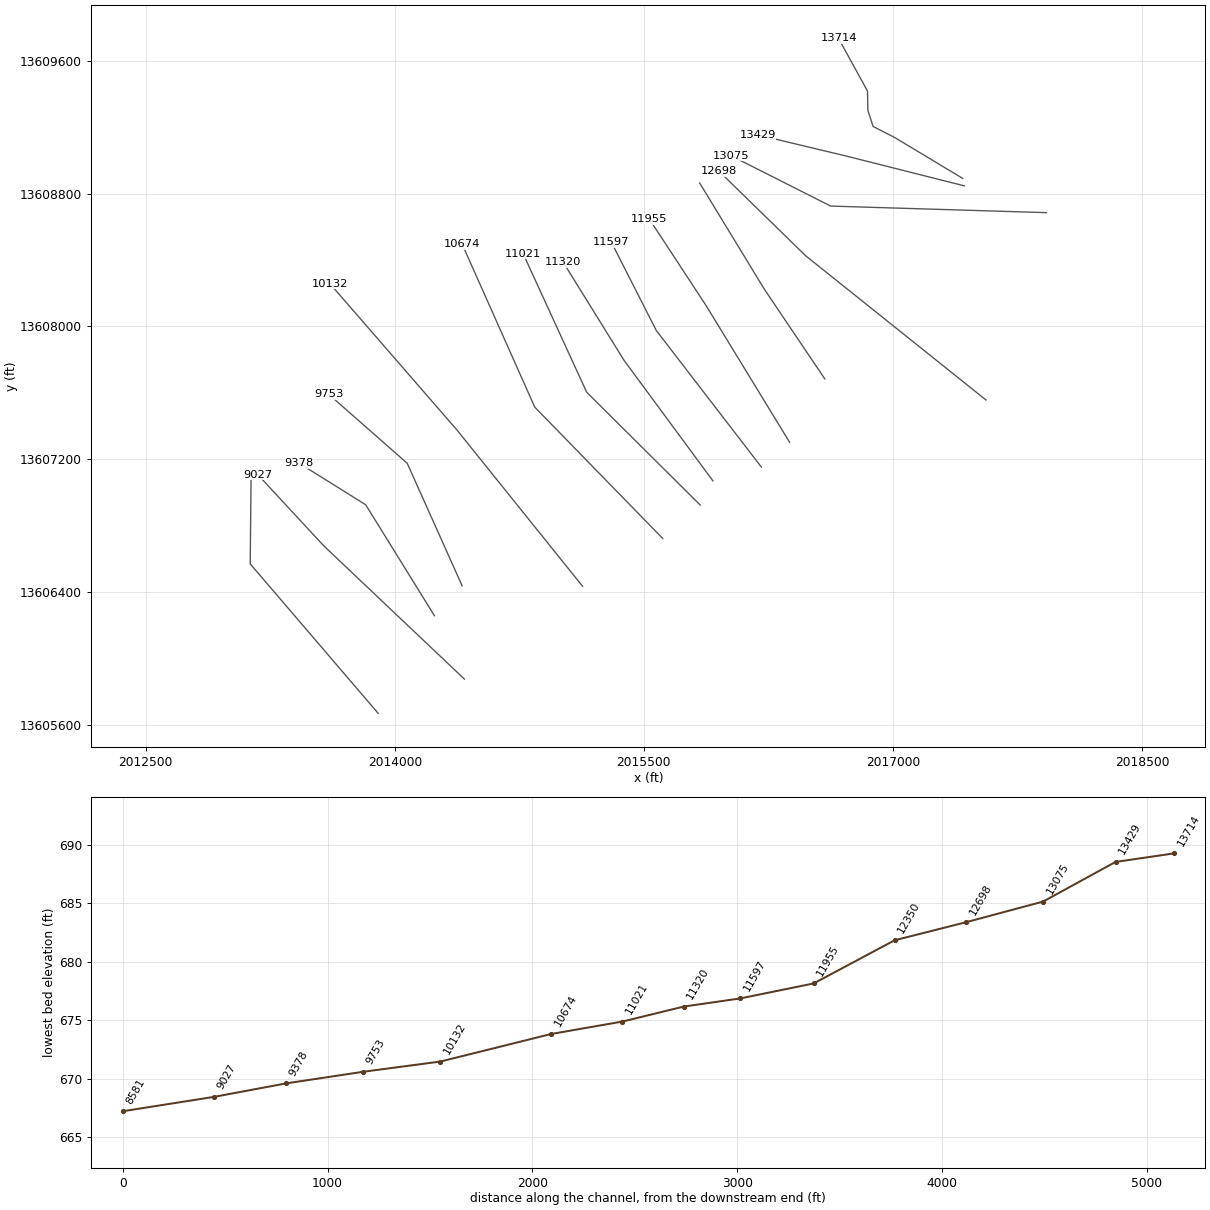
HEC-RAS study UNT 103 in HW.prj: UNT 103 in HW Base Level Engineering

--- UNT 103 in HW.g01 (geometry) --- (continued)

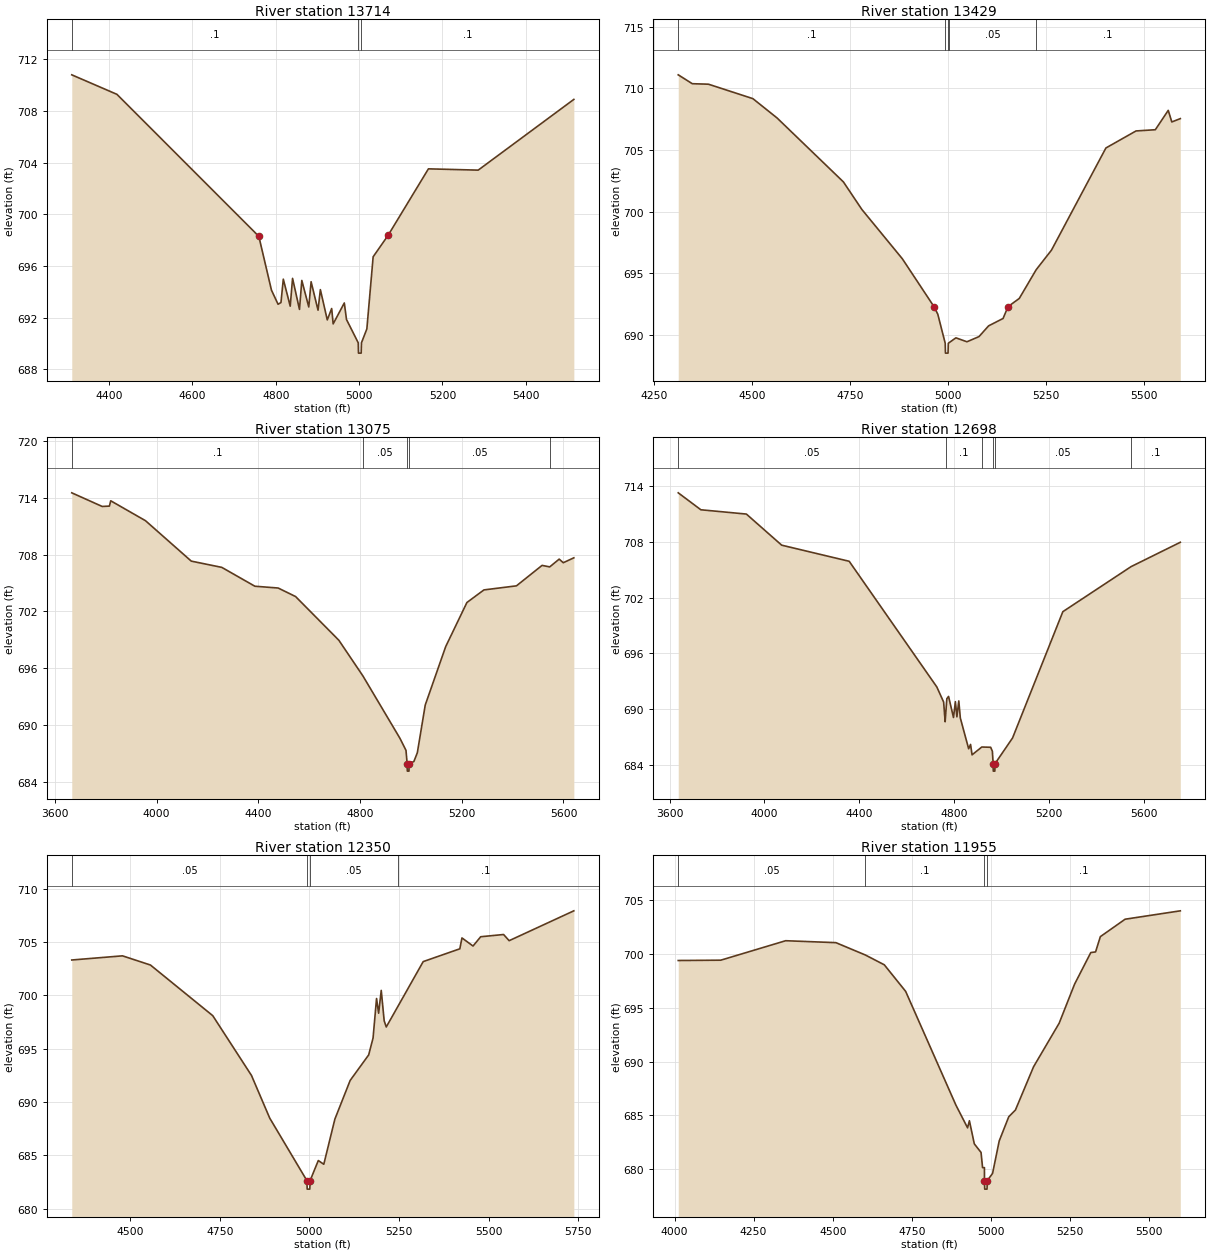
Type RM Length L Ch R = 1 ,13714   ,285,285,285
BEGIN DESCRIPTION:
Mapping XS 3855dcb5
END DESCRIPTION:
XS GIS Cut Line= 6
      2017419.59     13608892.16      2017008.13     13609139.55
      2016880.52     13609204.66      2016849.27     13609301.01
      2016846.67      13609418.2      2016672.21     13609735.88
#Sta/Elev= 30
  4310.8  710.78  4419.2  709.27  4759.5  698.29  4789.8  694.13  4805.6  693.04
  4812.6  693.17  4818.2  694.98  4834.8  692.89  4840.4  695.04    4857  692.64
  4862.6  694.88  4879.3  692.83  4884.9  694.78  4901.5  692.58  4907.1  694.17
  4923.7  691.83  4934.2  692.71  4937.8  691.52  4964.5  693.14  4969.8  691.86
  4997.9  690.06  4998.5  689.26    5005  689.26  5005.7  690.06  5018.6  691.13
  5033.7  696.71  5069.4  698.36  5166.3  703.51  5285.7  703.41  5515.1  708.88
#Mann= 3 ,-1 , 0
  4310.8      .1       0  4997.9     .07       0  5005.7      .1       0
Bank Sta=4759.5,5069.4
XS Rating Curve= 0 ,0
Exp/Cntr=0.3,0.1

Type RM Length L Ch R = 1 ,13429   ,354,354,354
BEGIN DESCRIPTION:
UNT 103 in HW 22.0
END DESCRIPTION:
XS GIS Cut Line= 3
      2017429.82     13608846.85        2016725.       13609025.
      2016185.02     13609154.14
#Sta/Elev= 30
  4311.1  711.09    4347  710.37  4388.3  710.33  4501.7  709.16  4563.6  707.59
  4732.9  702.41  4780.2  700.17  4883.4  696.18 4964.28692.2986    4974  691.68
  4992.9  689.33  4993.5  688.53  5000.1  688.53  5000.8  689.33  5002.6  689.37
  5020.2  689.77  5048.4  689.45  5079.2  689.87  5103.7  690.74  5140.7  691.34
 5153.32692.2988    5182  692.96  5225.2  695.29  5264.3  696.88  5403.3  705.16
  5480.2  706.54  5529.5  706.64  5562.5  708.21  5571.6  707.27  5593.3  707.54
#Mann= 5 ,-1 , 0
  4311.1      .1       0  4992.9     .07       0  5000.8      .1       0
  5002.6     .05       0  5225.2      .1       0
Bank Sta=4964.28,5153.32
XS Rating Curve= 0 ,0
Exp/Cntr=0.3,0.1

Type RM Length L Ch R = 1 ,13075   ,377,377,377
BEGIN DESCRIPTION:
UNT 103 in HW 21.0
END DESCRIPTION:
XS GIS Cut Line= 3
      2017924.65     13608685.39        2016625.       13608725.
      2016023.58     13609029.14
#Sta/Elev= 30
  3666.5  714.52  3786.2  713.08  3814.6  713.12  3819.6  713.68  3956.3  711.58
  4136.4  707.31  4256.4  706.65  4386.5  704.66    4478  704.47  4546.6  703.57
  4716.6  698.96  4811.3  695.19  4956.8  688.61  4980.7  687.33  4985.2  685.94
  4985.9  685.14  4992.5  685.14  4993.1  685.94  5011.6  686.15  5025.3  687.08
  5056.4  692.12  5136.7  698.28  5220.2  702.94  5287.1  704.27    5415   704.7
  5515.8  706.86  5545.8   706.7  5583.1  707.52  5599.1  707.14  5640.7  707.66
#Mann= 5 ,-1 , 0
  3666.5      .1       0  4811.3     .05       0  4985.2    .035       0
  4993.1     .05       0  5545.8      .1       0
Bank Sta=4985.2,4993.1
XS Rating Curve= 0 ,0
Exp/Cntr=0.3,0.1

Type RM Length L Ch R = 1 ,12698   ,348,348,348
BEGIN DESCRIPTION:
UNT 103 in HW 20.0
END DESCRIPTION:
XS GIS Cut Line= 3
      2017560.06     13607556.72        2016475.       13608425.
      2015953.29     13608934.32
#Sta/Elev= 30
  3636.1  713.25  3731.6  711.43  3923.7  710.97  4072.6  707.63  4357.5   705.9
  4727.3  692.41  4756.1  690.79  4762.5  688.67    4765  689.54  4769.6  691.15
  4776.9  691.39  4797.7  689.13  4805.7  690.83  4812.1   689.2  4820.1  690.91
  4826.5  689.08  4861.7  685.77  4869.7  686.24  4876.1  685.12  4917.2  685.96
  4954.6  685.93  4961.8   685.5    4965  684.17  4965.7  683.37  4972.3  683.37
  4972.9  684.17    5047  686.93  5259.2  700.49  5547.4  705.33  5754.9  707.94
#Mann= 6 ,-1 , 0
  3636.1     .05       0    4765      .1       0  4917.2     .05       0
    4965    .035       0  4972.9     .05       0  5547.4      .1       0
Bank Sta=4965,4972.9
XS Rating Curve= 0 ,0
Exp/Cntr=0.3,0.1

Type RM Length L Ch R = 1 ,12350   ,395,395,395
BEGIN DESCRIPTION:
UNT 103 in HW 19.0
END DESCRIPTION:
XS GIS Cut Line= 3
      2016589.55     13607683.47        2016225.       13608225.
      2015836.07     13608864.05
#Sta/Elev= 30
  4337.2  703.31  4478.7   703.7  4556.7  702.84  4730.6  698.09  4838.6  692.49
  4889.5  688.49  4993.2  682.63  4994.1  681.83  5001.4  681.83  5002.2  682.63
  5025.1  684.51  5040.4  684.16  5071.3  688.39    5114  692.02  5165.6  694.41
  5177.9     696  5187.6   699.7  5193.4  698.32  5200.7  700.46  5208.9  697.61
  5214.7  697.03  5248.7  699.05  5317.8  703.16    5420  704.36  5425.9  705.38
  5456.8  704.62  5478.2  705.49  5542.1   705.7  5557.6  705.12  5738.1  707.92
#Mann= 4 ,-1 , 0
  4337.2     .05       0  4993.2    .035       0  5002.2     .05       0
  5248.7      .1       0
Bank Sta=4993.2,5002.2
XS Rating Curve= 0 ,0
Exp/Cntr=0.3,0.1

Type RM Length L Ch R = 1 ,11955   ,358,358,358
BEGIN DESCRIPTION:
UNT 103 in HW 18.0
END DESCRIPTION:
XS GIS Cut Line= 3
      2016377.76      13607301.5        2015875.       13608125.
        2015534.     13608645.27
#Sta/Elev= 30
  4011.8   699.4  4146.2  699.43  4351.4  701.24  4510.2  701.06  4603.4  699.91
  4663.1     699  4730.6  696.53  4889.5  685.95  4926.3  683.84  4932.1   684.5
  4947.6  682.35  4968.9  681.55  4973.7  680.14  4979.6  680.14  4979.7  678.94
  4980.5  678.14  4987.8  678.14  4988.7  678.94  5005.3   679.6  5026.3  682.62
  5056.5  684.87  5077.6   685.5  5134.9  689.52  5215.8  693.57  5264.5   697.2
  5315.8  700.14  5330.9   700.2    5346  701.62  5424.3  703.24  5598.7  704.02
#Mann= 4 ,-1 , 0
  4011.8     .05       0  4603.4      .1       0  4979.7     .07       0
  4988.7      .1       0
Bank Sta=4979.7,4988.7
XS Rating Curve= 0 ,0
Exp/Cntr=0.3,0.1

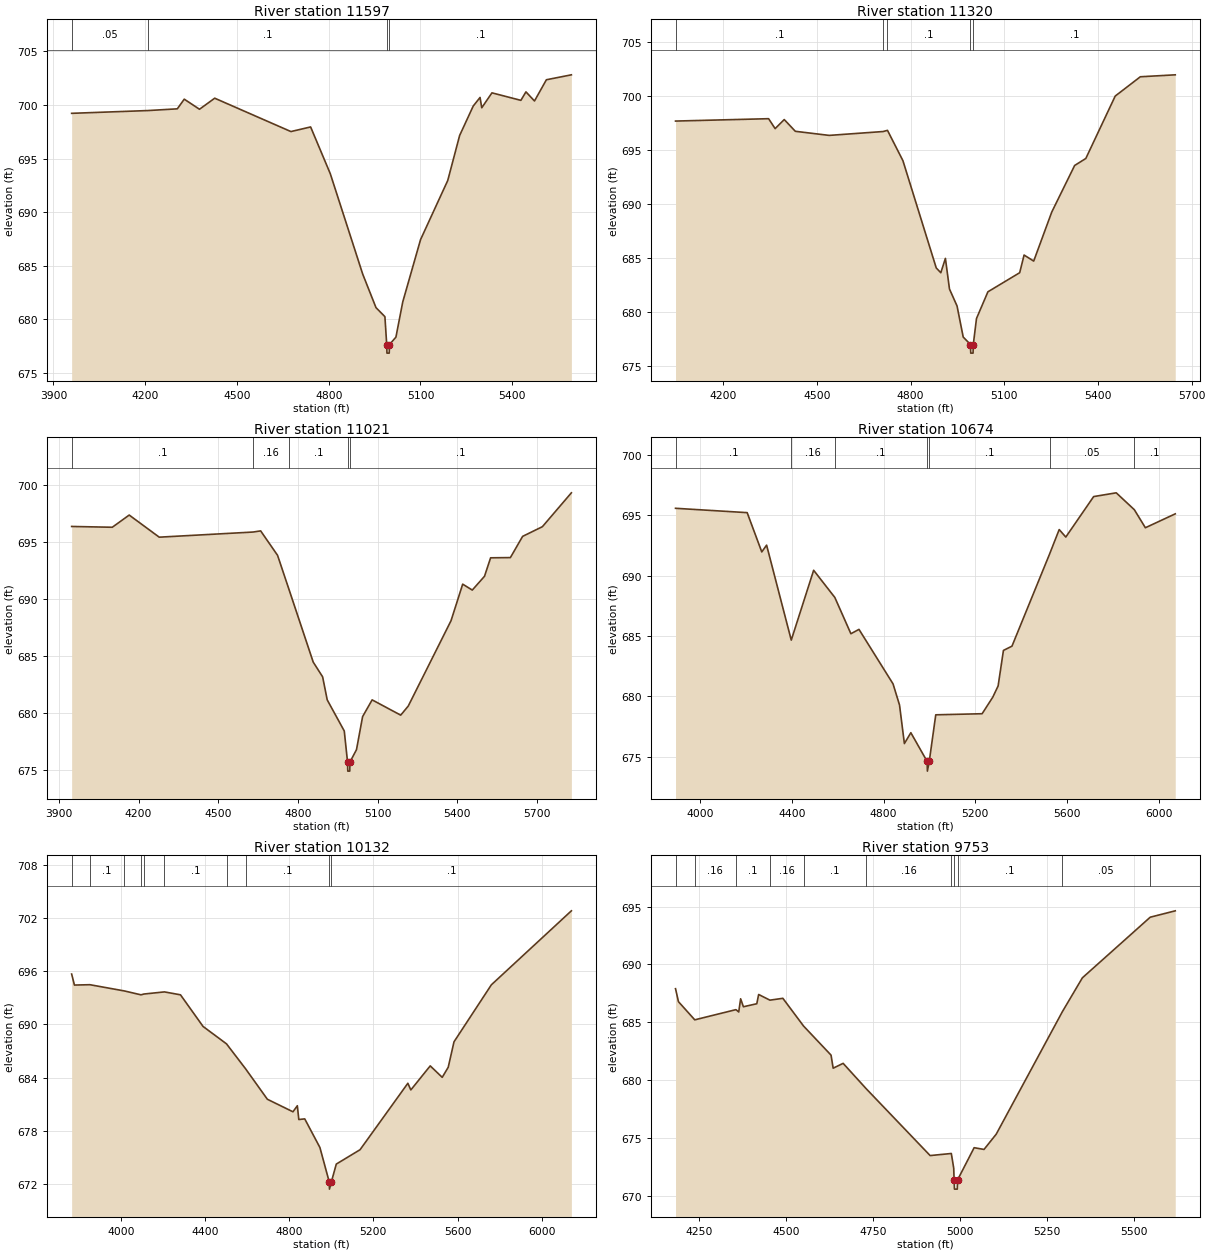
Type RM Length L Ch R = 1 ,11597   ,277,277,277
BEGIN DESCRIPTION:
UNT 103 in HW 17.0
END DESCRIPTION:
XS GIS Cut Line= 3
      2016207.58     13607152.26        2015575.       13607975.
      2015304.81     13608506.44
#Sta/Elev= 30
  3959.4  699.22  4210.5  699.48  4304.9  699.64  4327.6  700.54  4377.4   699.6
  4427.2  700.63  4676.4  697.52  4740.8  697.95  4805.1  693.59  4911.1  684.23
  4954.6   681.1  4983.7  680.26  4989.6  677.66  4990.4  676.86  4997.8  676.86
  4998.6  677.66  5019.7  678.35  5042.1  681.64  5100.2  687.44  5189.2  692.96
    5228  697.15  5272.5   699.9  5294.8   700.7  5300.4  699.74  5333.7  701.13
  5428.3  700.43  5444.9  701.22  5472.8  700.37  5511.7  702.35  5593.4  702.81
#Mann= 4 ,-1 , 0
  3959.4     .05       0  4210.5      .1       0  4989.6     .07       0
  4998.6      .1       0
Bank Sta=4989.6,4998.6
XS Rating Curve= 0 ,0
Exp/Cntr=0.3,0.1

Type RM Length L Ch R = 1 ,11320   ,299,299,299
BEGIN DESCRIPTION:
UNT 103 in HW 16.0
END DESCRIPTION:
XS GIS Cut Line= 3
      2015915.92     13607068.92      2015381.22     13607794.59
      2015013.14     13608388.37
#Sta/Elev= 30
  4047.5  697.69  4345.5  697.91  4366.4  696.99  4395.6  697.83  4431.1  696.74
  4539.5  696.36  4712.3  696.72  4726.1  696.83  4775.5  694.02  4882.3  684.06
  4896.9  683.62  4911.6  684.95  4924.6  682.11  4948.9  680.53  4968.6  677.65
  4991.9  676.96  4992.7  676.16  5000.1  676.16  5000.9  676.96  5011.1  679.37
  5047.7  681.85  5149.4  683.62  5163.5  685.26  5194.3   684.7  5252.1  689.25
  5325.4  693.57  5361.2  694.22  5455.3  700.01  5535.7   701.8  5647.5  701.98
#Mann= 5 ,-1 , 0
  4047.5      .1       0  4712.3     .16       0  4726.1      .1       0
  4991.9     .07       0  5000.9      .1       0
Bank Sta=4991.9,5000.9
XS Rating Curve= 0 ,0
Exp/Cntr=0.3,0.1

Type RM Length L Ch R = 1 ,11021   ,347,347,347
BEGIN DESCRIPTION:
UNT 103 in HW 15.0
END DESCRIPTION:
XS GIS Cut Line= 3
      2015839.52     13606923.09      2015155.52     13607603.62
      2014773.56     13608436.99
#Sta/Elev= 30
  3947.9  696.34  4100.9  696.27  4164.6  697.34  4277.7   695.4  4630.8  695.85
  4659.6  695.95  4723.2  693.81  4766.2  690.82  4857.5  684.44  4892.9  683.15
  4910.2  681.13  4974.4   678.4  4986.7  675.68  4987.6  674.88    4995  674.88
  4995.8  675.68  5020.4  676.76  5043.4  679.66  5079.3  681.13  5186.9  679.79
  5215.4  680.59  5376.3  688.07  5420.3  691.28  5456.4  690.76  5502.4  691.97
  5525.4  693.59  5599.9  693.61  5645.9  695.47  5720.4  696.32  5829.5  699.29
#Mann= 5 ,-1 , 0
  3947.9      .1       0  4630.8     .16       0  4766.2      .1       0
  4986.7     .07       0  4995.8      .1       0
Bank Sta=4986.7,4995.8
XS Rating Curve= 0 ,0
Exp/Cntr=0.3,0.1

Type RM Length L Ch R = 1 ,10674   ,542,542,542
BEGIN DESCRIPTION:
UNT 103 in HW 14.0
END DESCRIPTION:
XS GIS Cut Line= 3
      2015613.83     13606721.71      2014843.02     13607513.34
      2014405.54     13608495.94
#Sta/Elev= 30
  3892.5  695.57  4205.1  695.21  4268.8  691.96  4289.9  692.52  4397.5  684.66
  4495.2  690.44  4587.7  688.19  4657.7  685.19    4693  685.55  4841.6  681.04
  4869.9  679.29  4891.1   676.1  4919.3     677  4990.5  674.62  4991.4  673.82
  4999.6  674.62    5028  678.48  5230.3  678.57  5276.8  679.94  5300.1  680.87
  5323.3  683.81  5360.5  684.16  5525.2  691.81  5566.6  693.81  5595.4  693.19
    5717  696.54  5815.5  696.85  5894.6  695.45  5942.6  693.96    6073  695.11
#Mann= 7 ,-1 , 0
  3892.5      .1       0  4397.5     .16       0  4587.7      .1       0
  4990.5     .07       0  4999.6      .1       0  5525.2     .05       0
  5894.6      .1       0
Bank Sta=4990.5,4999.6
XS Rating Curve= 0 ,0
Exp/Cntr=0.3,0.1

Type RM Length L Ch R = 1 ,10132   ,379,379,379
BEGIN DESCRIPTION:
UNT 103 in HW 13.0
END DESCRIPTION:
XS GIS Cut Line= 3
      2015131.23     13606433.46        2014375.       13607375.
      2013610.36     13608256.42
#Sta/Elev= 30
  3766.5  695.68  3779.7  694.44  3853.2  694.48  4016.7  693.78    4096  693.34
  4109.9  693.43  4207.4  693.67  4283.7  693.34  4390.9  689.78  4502.3  687.82
  4593.3     685  4696.5  681.58  4818.1  680.17  4838.9  680.85  4845.9   679.3
  4874.1  679.37  4946.1  676.15  4990.6  672.26  4991.6  671.46  5000.4  672.26
    5024  674.28    5137   675.9    5364  683.38  5378.2  682.63  5470.3  685.34
  5527.3  684.05  5555.8  685.18  5583.3  688.05  5760.9  694.47    6141   702.8
#Mann= 10 ,-1 , 0
  3766.5     .05       0  3853.2      .1       0  4016.7     .16       0
    4096      .1       0  4109.9     .16       0  4207.4      .1       0
  4502.3     .16       0  4593.3      .1       0  4990.6     .07       0
  5000.4      .1       0
Bank Sta=4990.6,5000.4
XS Rating Curve= 0 ,0
Exp/Cntr=0.3,0.1

Type RM Length L Ch R = 1 ,9753    ,375,375,375
BEGIN DESCRIPTION:
UNT 103 in HW 12.0
END DESCRIPTION:
XS GIS Cut Line= 3
      2014405.52     13606436.96        2014075.       13607175.
       2013603.4     13607589.76
#Sta/Elev= 30
  4181.6   687.9    4190  686.78  4236.9  685.21  4355.3  686.09  4363.3  685.89
  4368.8  687.03  4376.7  686.34  4415.2   686.6  4420.6   687.4    4453  686.91
  4490.2  687.07  4549.8  684.67  4628.7  682.16  4634.8  681.03  4663.5  681.45
    4730  679.25  4913.6  673.48  4974.5  673.66  4981.4  672.39  4982.5  671.38
  4983.5  670.58  4991.6  670.58  4992.5  671.38  5040.1  674.16  5068.5  674.01
  5103.6  675.33  5293.7  685.91  5351.3  688.84  5546.4  694.08  5618.3  694.63
#Mann= 11 ,-1 , 0
  4181.6     .05       0  4236.9     .16       0  4355.3      .1       0
    4453     .16       0  4549.8      .1       0    4730     .16       0
  4974.5      .1       0  4982.5     .07       0  4992.5      .1       0
  5293.7     .05       0  5546.4      .1       0
Bank Sta=4982.5,4992.5
XS Rating Curve= 0 ,0
Exp/Cntr=0.3,0.1

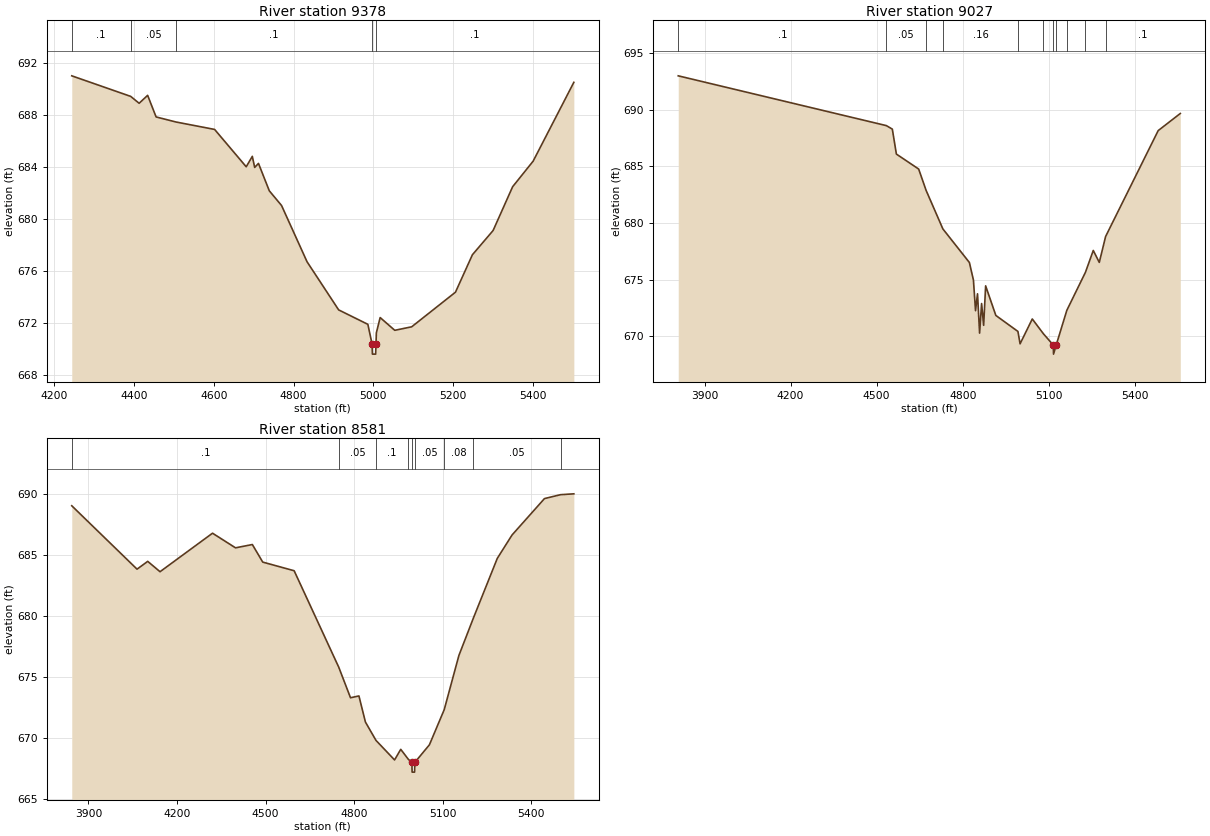
Type RM Length L Ch R = 1 ,9378    ,351,351,351
BEGIN DESCRIPTION:
UNT 103 in HW 11.0
END DESCRIPTION:
XS GIS Cut Line= 3
      2014238.83     13606256.44        2013825.       13606925.
      2013424.98     13607175.01
#Sta/Elev= 30
  4244.2  690.98  4391.8   689.4    4413  688.87  4434.3  689.48  4455.5  687.82
  4505.5  687.43  4602.1  686.86  4681.3  683.99  4696.6  684.79  4702.5  683.94
    4712  684.25  4739.2  682.14  4769.9  681.01  4833.7  676.69  4912.9  672.99
  4986.1  671.88  4996.5  670.39  4997.5  669.59  5005.6  669.59  5006.5  670.39
  5007.4  671.23  5016.9   672.4  5053.5  671.42  5095.9  671.69  5205.6  674.35
  5248.1  677.23  5299.9  679.09  5348.9  682.46  5400.2  684.42  5502.2  690.48
#Mann= 5 ,-1 , 0
  4244.2      .1       0  4391.8     .05       0  4505.5      .1       0
  4996.5     .07       0  5006.5      .1       0
Bank Sta=4996.5,5006.5
XS Rating Curve= 0 ,0
Exp/Cntr=0.3,0.1

Type RM Length L Ch R = 1 ,9027    ,446,446,446
BEGIN DESCRIPTION:
UNT 103 in HW 10.0
END DESCRIPTION:
XS GIS Cut Line= 3
      2014419.38     13605874.48        2013575.       13606675.
      2013176.39     13607105.32
#Sta/Elev= 30
  3808.4  692.98  4533.8  688.59  4554.7  688.28  4568.8  686.08  4646.5  684.76
  4672.4  682.88  4730.9  679.48  4823.3  676.52  4837.4  674.97  4844.7  672.27
  4851.6  673.76  4858.9  670.29  4865.8   672.9    4873  670.98  4879.9  674.46
  4915.5  671.85  4992.5  670.44    5000  669.35  5042.5  671.54  5081.5  670.23
  5115.7  669.24  5116.6  668.44  5125.9  669.24  5162.9   672.3  5227.9  675.66
  5255.1  677.58  5276.1  676.53  5298.1  678.81  5481.4  688.15  5558.5  689.66
#Mann= 11 ,-1 , 0
  3808.4      .1       0  4533.8     .05       0  4672.4      .1       0
  4730.9     .16       0  4992.5      .1       0  5081.5     .16       0
  5115.7     .07       0  5125.9     .16       0  5162.9      .1       0
  5227.9     .16       0  5298.1      .1       0
Bank Sta=5115.7,5125.9
XS Rating Curve= 0 ,0
Exp/Cntr=0.3,0.1

Type RM Length L Ch R = 1 ,8581    ,76,76,76
BEGIN DESCRIPTION:
UNT 103 in HW 9.0
END DESCRIPTION:
XS GIS Cut Line= 3
       2013900.3     13605667.87      2013129.48     13606568.89
      2013134.69     13607084.51
#Sta/Elev= 30
  3843.4  689.06  4064.6  683.86  4100.8   684.5  4142.5  683.65  4320.4  686.81
  4398.3  685.61  4455.4  685.88  4490.5  684.44    4597  683.73  4748.1  675.82
    4788  673.31  4816.5  673.46  4838.5  671.32  4874.4  669.81  4937.3  668.21
  4958.2  669.08    4984  668.26  4995.8  668.01  4996.8  667.21  5005.1  667.21
    5006  668.01  5055.3  669.45  5105.5  672.33  5155.3  676.78  5204.1  679.83
  5285.3  684.74  5335.3  686.66  5445.3  689.65  5499.8  689.97  5544.8  690.04
#Mann= 9 ,-1 , 0
  3843.4      .1       0  4748.1     .05       0  4874.4      .1       0
    4984     .05       0  4995.8     .04       0    5006     .05       0
  5105.5     .08       0  5204.1     .05       0  5499.8     .08       0
Bank Sta=4995.8,5006
XS Rating Curve= 0 ,0
Exp/Cntr=0.3,0.1