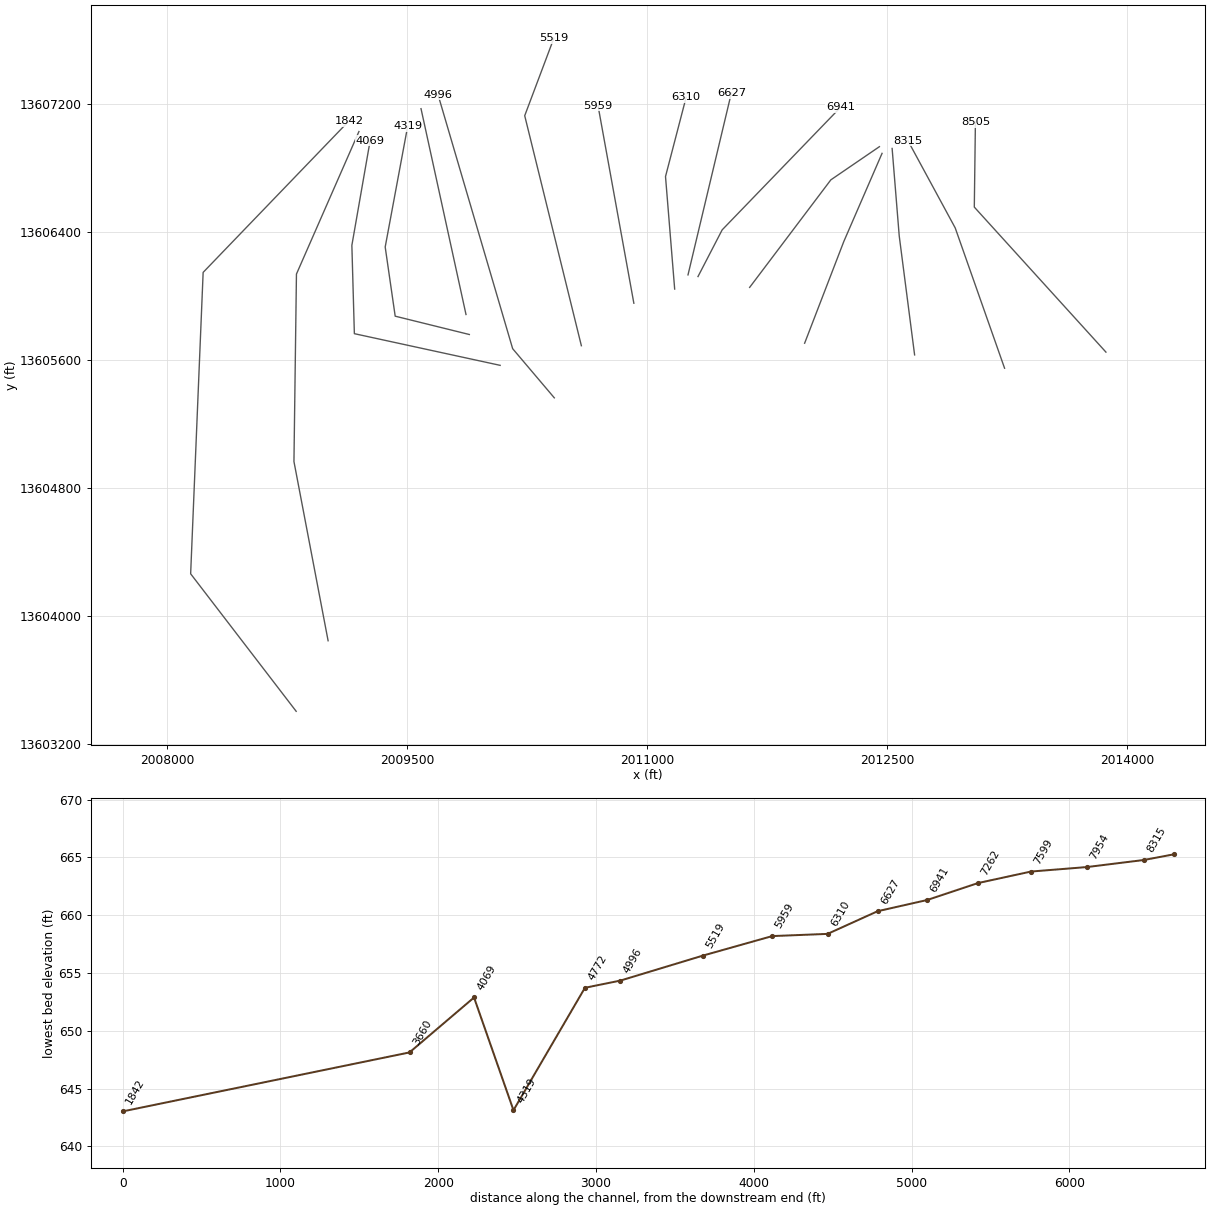
HEC-RAS study UNT 103 in HW.prj: UNT 103 in HW Base Level Engineering

--- UNT 103 in HW.g01 (geometry) --- (continued)

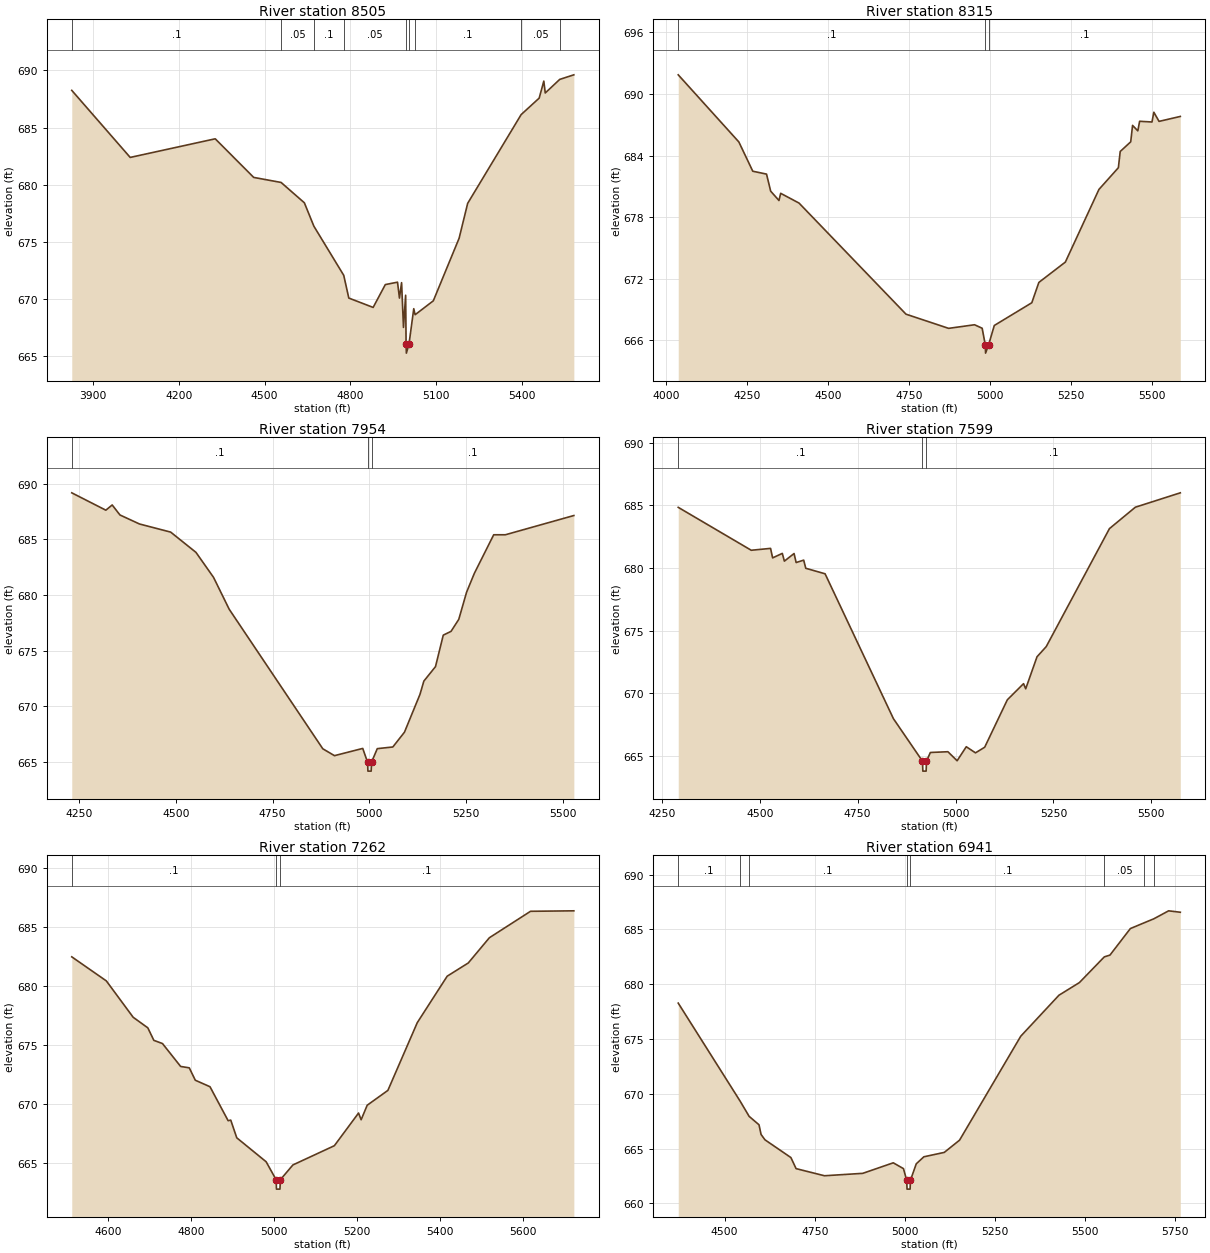
Type RM Length L Ch R = 1 ,8505    ,190,190,190
BEGIN DESCRIPTION:
Mapping XS 65789aed
END DESCRIPTION:
XS GIS Cut Line= 3
      2013867.34     13605648.74      2013044.41     13606555.01
      2013051.36     13607086.21
#Sta/Elev= 30
  3825.9  688.26  4030.2  682.39  4327.5  684.02    4462  680.64  4557.7   680.2
  4639.1  678.42  4672.4  676.37  4776.8  672.07  4794.5  670.08  4879.6  669.26
  4922.2  671.26  4964.8  671.47  4971.6  670.08    4979  671.43  4985.7  667.51
  4993.2  670.33  4994.8  666.06  4995.8  665.26    5005  666.06  5021.6  669.15
  5026.3  668.62    5090  669.84  5180.1  675.31  5210.1  678.37  5397.1  686.14
  5460.1  687.58  5476.3  689.07  5481.3  688.03    5532  689.22  5581.3  689.62
#Mann= 9 ,-1 , 0
  3825.9      .1       0  4557.7     .05       0  4672.4      .1       0
  4776.8     .05       0  4994.8     .04       0    5005     .05       0
  5026.3      .1       0  5397.1     .05       0    5532     .08       0
Bank Sta=4994.8,5005
XS Rating Curve= 0 ,0
Exp/Cntr=0.3,0.1

Type RM Length L Ch R = 1 ,8315    ,361,361,361
BEGIN DESCRIPTION:
UNT 103 in HW 8.0
END DESCRIPTION:
XS GIS Cut Line= 3
      2013233.64     13605548.09        2012925.       13606425.
      2012629.74     13606969.46
#Sta/Elev= 30
  4038.1  691.85  4225.1  685.32  4268.1  682.47  4310.5  682.19  4323.3  680.53
  4348.9  679.62  4354.2  680.32  4410.8  679.37  4740.8  668.56  4872.3  667.18
  4952.3  667.53  4975.8  667.19  4985.4  665.57  4986.3  664.77  4995.6  665.57
  5013.2  667.46  5128.9  669.67  5150.7  671.65  5232.5  673.63  5336.1   680.7
    5396  682.81  5401.7  684.39  5434.1  685.33  5439.8  686.93    5456   686.4
  5461.6  687.33  5499.7  687.26  5505.4  688.21  5521.5  687.32  5587.1   687.8
#Mann= 3 ,-1 , 0
  4038.1      .1       0  4985.4     .07       0  4995.6      .1       0
Bank Sta=4985.4,4995.6
XS Rating Curve= 0 ,0
Exp/Cntr=0.3,0.1

Type RM Length L Ch R = 1 ,7954    ,355,355,355
BEGIN DESCRIPTION:
UNT 103 in HW 7.0
END DESCRIPTION:
XS GIS Cut Line= 3
      2012671.15     13605631.39        2012575.       13606375.
      2012530.65     13606921.51
#Sta/Elev= 30
  4230.6  689.17  4318.7  687.61  4335.1  688.08  4355.2  687.18  4405.7  686.37
  4486.3  685.64  4551.7  683.82  4597.2  681.57  4637.6  678.71  4879.6  666.17
  4909.8  665.55  4982.9   666.2  4995.4  664.96  4996.3  664.16  5004.7  664.16
  5005.6  664.96  5020.5  666.18  5060.7  666.33  5090.8  667.66  5130.9  671.06
  5140.9  672.25    5171  673.55  5191.1  676.38  5211.2  676.72  5231.2   677.8
  5251.3  680.23  5271.4  681.93  5321.5   685.4  5351.6   685.4  5528.7  687.13
#Mann= 3 ,-1 , 0
  4230.6      .1       0  4995.4     .07       0  5005.6      .1       0
Bank Sta=4995.4,5005.6
XS Rating Curve= 0 ,0
Exp/Cntr=0.3,0.1

Type RM Length L Ch R = 1 ,7599    ,337,337,337
BEGIN DESCRIPTION:
Mapping XS a65d783b
END DESCRIPTION:
XS GIS Cut Line= 3
      2011983.64      13605704.3      2012228.44     13606339.73
      2012467.63     13606890.91
#Sta/Elev= 30
    4292  684.85  4478.4  681.42  4527.7  681.57    4533  680.81  4557.7  681.17
    4563  680.55  4587.7  681.16    4593  680.44  4612.3  680.63  4617.6  679.98
  4666.9  679.54  4841.4  667.96  4915.5  664.57  4916.5  663.77  4924.9  663.77
  4925.8  664.57  4935.7  665.26  4980.5  665.32    5004   664.6  5027.4  665.72
  5050.9  665.23  5074.4  665.68  5132.2  669.47  5173.6  670.76  5179.1  670.35
    5208  672.91  5231.5  673.72  5392.9  683.15    5459  684.86  5573.8  686.01
#Mann= 3 ,-1 , 0
    4292      .1       0  4915.5     .07       0  4925.8      .1       0
Bank Sta=4915.5,4925.8
XS Rating Curve= 0 ,0
Exp/Cntr=0.3,0.1

Type RM Length L Ch R = 1 ,7262    ,321,321,321
BEGIN DESCRIPTION:
UNT 103 in HW 6.0
END DESCRIPTION:
XS GIS Cut Line= 3
      2011639.92     13606053.29      2012147.51     13606725.29
       2012451.2     13606932.66
#Sta/Elev= 30
    4513  682.46  4596.3  680.42  4660.9  677.34  4696.3  676.44  4710.8  675.38
  4731.6  675.11  4775.3  673.17  4796.2  673.05  4810.7     672  4846.1  671.45
  4889.8  668.57  4896.1  668.62  4910.6  667.12  4981.4  665.09  5005.4  663.57
  5006.3  662.77  5014.7  662.77  5015.7  663.57  5045.9  664.82  5145.8  666.45
  5204.1  669.22  5210.3  668.65  5224.9  669.88  5274.8  671.14  5345.6  676.88
  5417.7  680.82  5468.5  681.94  5519.4  684.08  5618.5  686.32  5722.9  686.36
#Mann= 3 ,-1 , 0
    4513      .1       0  5005.4     .07       0  5015.7      .1       0
Bank Sta=5005.4,5015.7
XS Rating Curve= 0 ,0
Exp/Cntr=0.3,0.1

Type RM Length L Ch R = 1 ,6941    ,314,314,314
BEGIN DESCRIPTION:
Mapping XS 48845f9f
END DESCRIPTION:
XS GIS Cut Line= 3
      2011316.98     13606120.97      2011468.02     13606412.64
      2012207.63     13607178.29
#Sta/Elev= 30
  4371.2  678.28  4543.1  669.33  4567.9  667.95  4595.3  667.18    4601   666.3
  4611.8  665.81  4683.8  664.19  4698.2  663.18  4776.9  662.53  4883.2  662.75
  4967.8  663.71  4996.1  663.18  5005.1  662.11    5006  661.31  5014.5  661.31
  5015.4  662.11  5031.6  663.62  5052.7  664.26  5109.3  664.66  5151.8  665.78
  5321.5  675.26  5427.5     679  5484.1  680.15  5553.4   682.5    5569  682.66
  5625.6  685.08  5664.8  685.62  5690.6  685.97  5731.8   686.7  5764.2  686.57
#Mann= 8 ,-1 , 0
  4371.2      .1       0  4543.1     .05       0  4567.9      .1       0
  5005.1     .07       0  5015.4      .1       0  5553.4     .05       0
  5664.8      .1       0  5690.6     .08       0
Bank Sta=5005.1,5015.4
XS Rating Curve= 0 ,0
Exp/Cntr=0.3,0.1

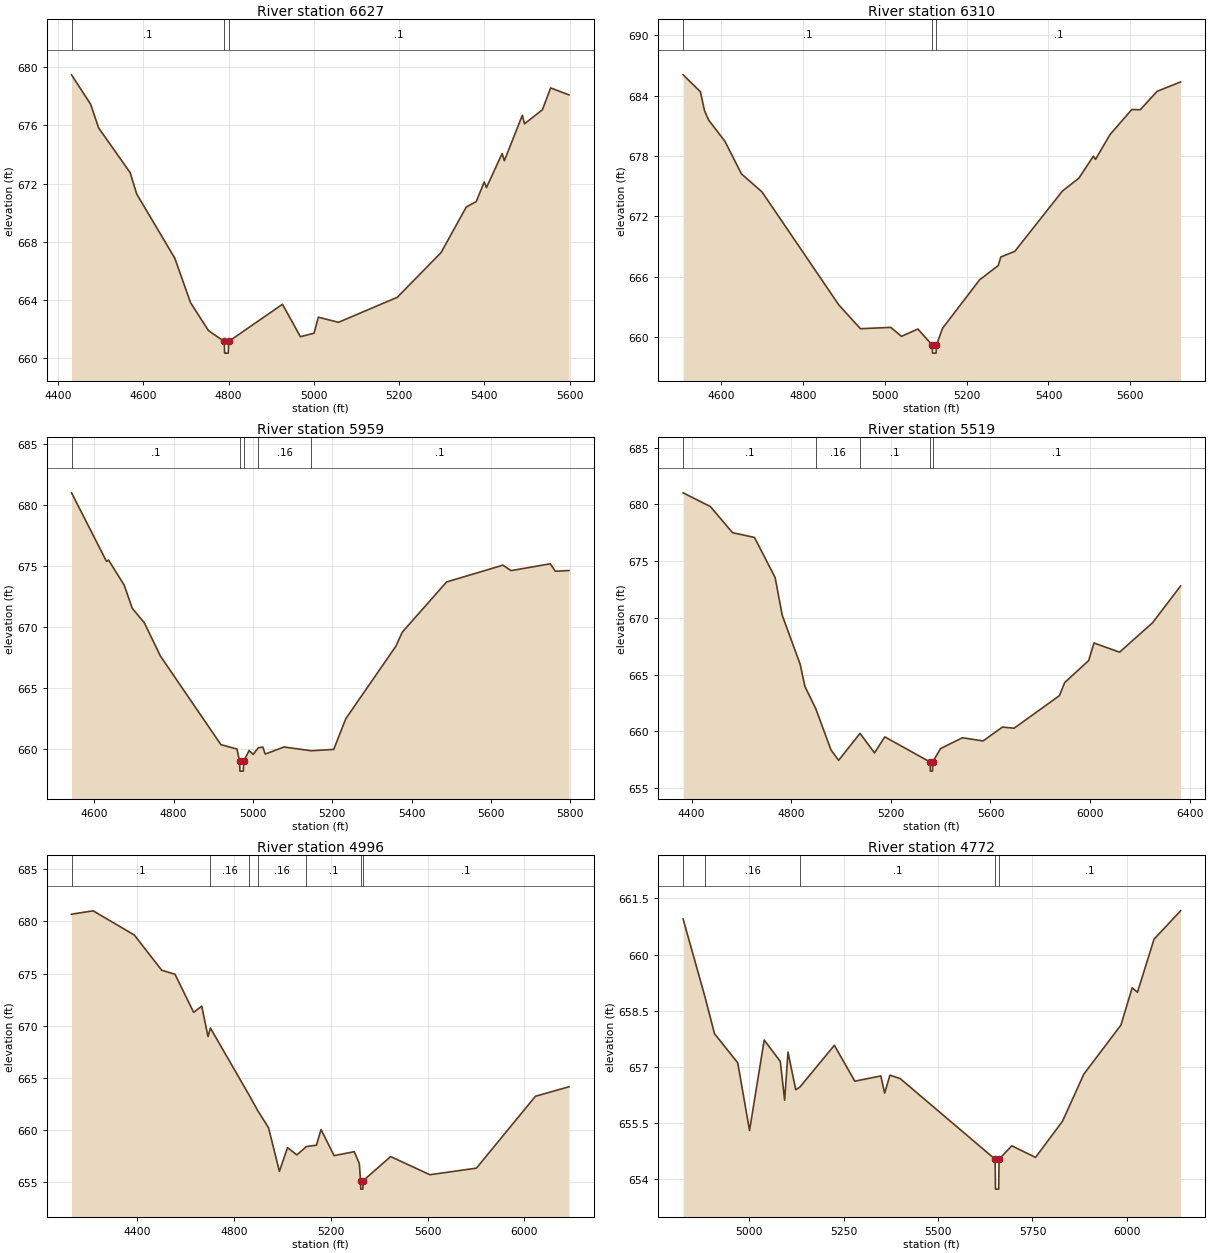
Type RM Length L Ch R = 1 ,6627    ,317,317,317
BEGIN DESCRIPTION:
Mapping XS 9f2e251c
END DESCRIPTION:
XS GIS Cut Line= 2
      2011254.47     13606131.36      2011525.31      13607266.8
#Sta/Elev= 30
  4431.3  679.48  4476.2  677.45  4494.9  675.83  4568.7  672.76  4584.3  671.28
  4673.6  666.87  4710.6  663.81  4752.7  661.89  4789.7  661.14  4790.6  660.34
  4799.1  660.34    4800  661.14  4926.3   663.7  4968.4  661.47  5000.5  661.71
  5010.5  662.81  5057.8  662.46  5195.8  664.18  5298.6  667.26  5357.7  670.39
  5380.9  670.76  5399.8  672.11  5404.9  671.72  5441.9  674.07    5447  673.57
  5489.2   676.7  5494.3  676.11  5536.4  677.08  5555.6  678.58  5598.6   678.1
#Mann= 3 ,-1 , 0
  4431.3      .1       0  4789.7     .07       0    4800      .1       0
Bank Sta=4789.7,4800
XS Rating Curve= 0 ,0
Exp/Cntr=0.3,0.1

Type RM Length L Ch R = 1 ,6310    ,351,351,351
BEGIN DESCRIPTION:
UNT 103 in HW 5.0
END DESCRIPTION:
XS GIS Cut Line= 3
      2011171.15     13606042.87      2011113.86     13606745.98
      2011242.63     13607240.34
#Sta/Elev= 30
  4506.7  686.06    4549  684.38    4559  682.49    4569  681.57  4609.2  679.43
  4649.3  676.21  4699.5  674.42  4887.7  663.16  4940.3  660.81  5014.4  660.94
  5040.6  660.05  5080.7  660.78  5115.7  659.18  5116.6  658.38  5125.2  658.38
  5126.1  659.18  5141.2  660.86  5231.6  665.67  5277.2  667.09  5283.5  667.94
  5317.7   668.5  5434.1   674.5  5474.6  675.79  5509.9  677.97  5515.1  677.65
  5550.4  680.11  5603.8  682.61  5624.5  682.59  5665.8  684.42    5723  685.35
#Mann= 3 ,-1 , 0
  4506.7      .1       0  5115.7     .07       0  5126.1      .1       0
Bank Sta=5115.7,5126.1
XS Rating Curve= 0 ,0
Exp/Cntr=0.3,0.1

Type RM Length L Ch R = 1 ,5959    ,440,440,440
BEGIN DESCRIPTION:
Mapping XS 048bca6d
END DESCRIPTION:
XS GIS Cut Line= 2
      2010915.94     13605954.29      2010691.97     13607188.73
#Sta/Elev= 30
  4542.4  681.01  4630.6  675.39  4635.7   675.5  4675.2  673.44  4695.6  671.54
  4726.1  670.35  4766.7  667.62  4919.2  660.36  4959.8     660  4966.2  658.99
  4967.1  658.19  4975.7  658.19  4976.6  658.99  4990.3  659.88  5000.5  659.56
  5013.6  660.11  5024.9  660.16    5031  659.59  5078.3  660.17    5147  659.86
  5203.7  659.97  5234.2  662.49  5360.6  668.44  5376.5  669.58  5488.3   673.7
  5630.6  675.08  5650.9  674.63  5749.8  675.19  5762.7  674.58    5797  674.64
#Mann= 5 ,-1 , 0
  4542.4      .1       0  4966.2     .07       0  4976.6      .1       0
  5013.6     .16       0    5147      .1       0
Bank Sta=4966.2,4976.6
XS Rating Curve= 0 ,0
Exp/Cntr=0.3,0.1

Type RM Length L Ch R = 1 ,5519    ,523,523,523
BEGIN DESCRIPTION:
Mapping XS aba8eeae
END DESCRIPTION:
XS GIS Cut Line= 3
      2010587.82     13605688.65      2010233.65     13607126.19
      2010415.85     13607610.32
#Sta/Elev= 30
  4365.7  681.02  4475.2  679.81  4564.2  677.51  4652.3  677.09  4735.3  673.55
  4763.6  670.24  4835.7  665.92  4854.7  663.97  4898.7  661.99  4959.3  658.38
  4990.2  657.45  5076.2  659.83  5134.4   658.1  5175.6  659.52  5357.8   657.3
  5358.7   656.5  5367.3   656.5  5368.2   657.3  5399.3  658.48  5487.5  659.44
  5570.5  659.16  5648.3  660.38    5695  660.28    5877  663.15  5898.4  664.31
  5994.5  666.24  6015.9  667.79  6118.6  666.98    6251  669.57  6363.5  672.81
#Mann= 5 ,-1 , 0
  4365.7      .1       0  4898.7     .16       0  5076.2      .1       0
  5357.8     .07       0  5368.2      .1       0
Bank Sta=5357.8,5368.2
XS Rating Curve= 0 ,0
Exp/Cntr=0.3,0.1

Type RM Length L Ch R = 1 ,4996    ,224,224,224
BEGIN DESCRIPTION:
UNT 103 in HW 4.0
END DESCRIPTION:
XS GIS Cut Line= 3
      2010418.65     13605362.94      2010158.24     13605670.22
      2009691.97     13607256.43
#Sta/Elev= 30
  4128.6  680.69  4217.9  681.01  4388.2  678.69  4501.3  675.32  4556.3  674.93
  4633.4  671.28  4666.8  671.88  4692.7  668.96  4702.6  669.78  4863.7  663.31
  4898.5  661.86  4942.9  660.22  4987.9  656.04  5021.3  658.32  5059.9  657.62
  5099.6  658.42  5140.9  658.55    5160  660.05  5213.9  657.55  5297.2  657.93
  5318.1   656.8  5323.3  655.14  5324.2  654.34  5332.8  654.34  5333.7  655.14
  5447.7  657.46  5609.9  655.72  5802.2  656.35  6046.2  663.24  6184.7  664.15
#Mann= 7 ,-1 , 0
  4128.6      .1       0  4702.6     .16       0  4863.7      .1       0
  4898.5     .16       0  5099.6      .1       0  5323.3     .07       0
  5333.7      .1       0
Bank Sta=5323.3,5333.7
XS Rating Curve= 0 ,0
Exp/Cntr=0.3,0.1

Type RM Length L Ch R = 1 ,4772    ,453,453,453
BEGIN DESCRIPTION:
Mapping XS 7f45885d
END DESCRIPTION:
XS GIS Cut Line= 2
      2009866.57     13605883.77      2009585.35     13607170.09
#Sta/Elev= 30
  4825.2  660.95  4883.2  658.86  4908.3  657.88  4969.8   657.1    5001  655.29
  5039.8  657.71  5082.4  657.14  5093.9   656.1  5102.8  657.39  5123.3  656.38
  5134.1  656.45  5225.5  657.57  5279.7  656.61  5348.5  656.75  5358.7  656.29
  5372.6  656.77  5399.7  656.68  5651.1  654.52    5652  653.72  5660.6  653.72
  5661.5  654.52  5695.1  654.88    5758  654.57  5829.6  655.54    5886   656.8
    5984  658.11  6013.9  659.11  6027.9  658.99  6071.7  660.41  6141.9  661.17
#Mann= 5 ,-1 , 0
  4825.2      .1       0  4883.2     .16       0  5134.1      .1       0
  5651.1     .07       0  5661.5      .1       0
Bank Sta=5651.1,5661.5
XS Rating Curve= 0 ,0
Exp/Cntr=0.3,0.1

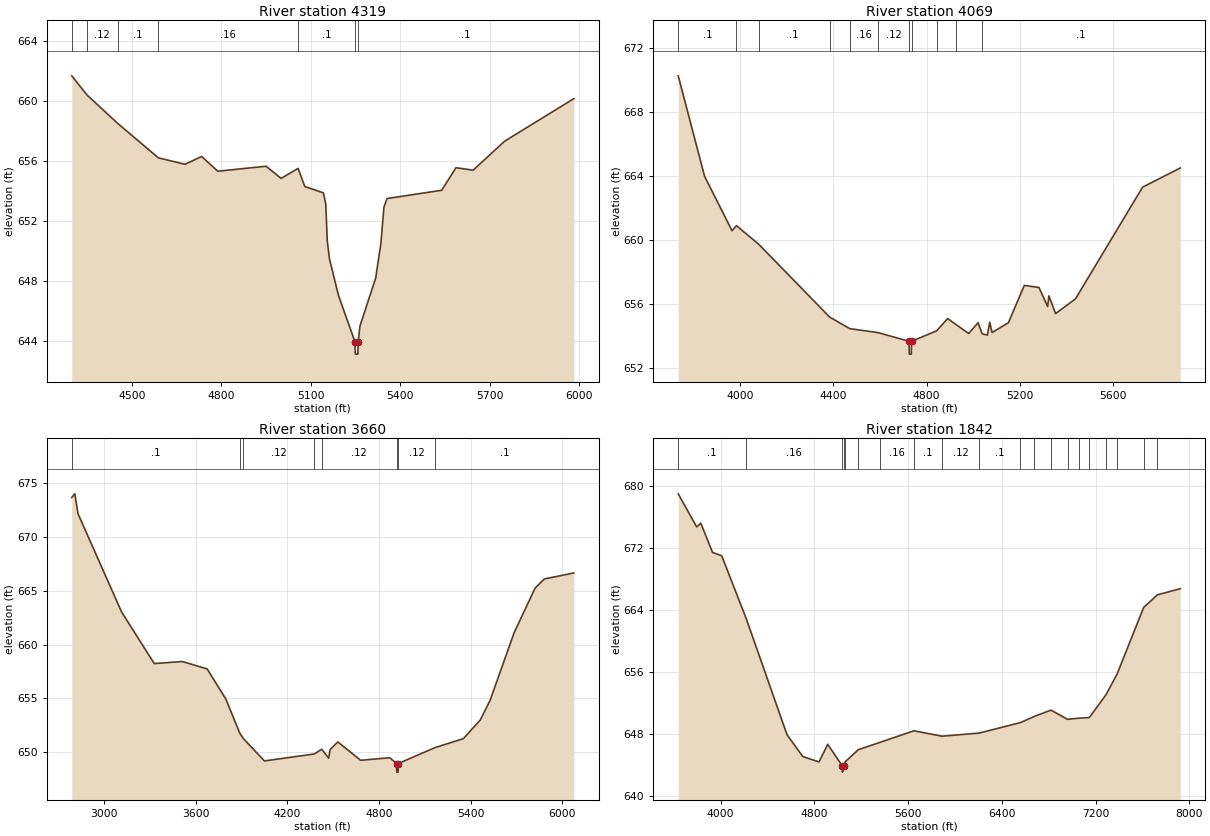
Type RM Length L Ch R = 1 ,4319    ,250,250,250
BEGIN DESCRIPTION:
Mapping XS cc1b3b56
END DESCRIPTION:
XS GIS Cut Line= 4
      2009887.42     13605758.76      2009423.87     13605873.34
      2009361.37     13606305.64      2009501.92     13607060.47
#Sta/Elev= 30
    4299  661.66  4350.3  660.38  4452.5   658.5  4589.1   656.2  4678.4  655.77
  4734.1  656.29  4788.3  655.31  4949.9  655.64  5000.5  654.83  5057.2   655.5
  5079.7  654.29  5141.9  653.87    5150  653.12    5155  650.68  5162.1   649.5
  5192.4  647.05  5248.1  643.93    5249  643.13  5257.6  643.13  5258.5  643.93
  5264.5     645  5317.3   648.2  5334.7  650.51  5344.9  652.92  5355.1  653.49
  5538.4  654.04  5586.1  655.54  5643.9  655.38  5749.4  657.31  5981.1  660.14
#Mann= 7 ,-1 , 0
    4299      .1       0  4350.3     .12       0  4452.5      .1       0
  4589.1     .16       0  5057.2      .1       0  5248.1     .07       0
  5258.5      .1       0
Bank Sta=5248.1,5258.5
XS Rating Curve= 0 ,0
Exp/Cntr=0.3,0.1

Type RM Length L Ch R = 1 ,4069    ,409,409,409
BEGIN DESCRIPTION:
UNT 103 in HW 3.0
END DESCRIPTION:
XS GIS Cut Line= 4
      2010080.12     13605566.05      2009168.66     13605763.97
      2009153.03     13606316.05      2009267.41     13606971.14
#Sta/Elev= 30
  3736.6  670.25  3849.4  663.98    3967  660.58  3985.8   660.9  4081.2  659.74
  4385.3  655.19  4471.4  654.47  4593.2  654.22  4725.1  653.68    4726  652.88
  4734.7  652.88  4735.6  653.68  4842.9  654.33  4890.4   655.1  4925.6  654.73
  4980.5  654.17  5020.5  654.84  5038.1  654.15  5060.5  654.07  5070.5  654.87
  5080.5  654.23  5150.5  654.84  5218.6  657.17  5281.4  657.04  5318.6  655.85
  5323.7  656.52  5352.5  655.41  5437.7  656.33  5725.1   663.3  5886.6   664.5
#Mann= 11 ,-1 , 0
  3736.6      .1       0  3985.8     .07       0  4081.2      .1       0
  4385.3     .12       0  4471.4     .16       0  4593.2     .12       0
  4725.1     .07       0  4735.6     .12       0  4842.9     .12       0
  4925.6     .16       0  5038.1      .1       0
Bank Sta=4725.1,4735.6
XS Rating Curve= 0 ,0
Exp/Cntr=0.3,0.1

Type RM Length L Ch R = 1 ,3660    ,1818,1818,1818
BEGIN DESCRIPTION:
UNT 103 in HW 2.0
END DESCRIPTION:
XS GIS Cut Line= 4
      2009004.49     13603844.91      2008790.94     13604964.73
      2008806.57      13606136.6      2009197.19     13607027.23
#Sta/Elev= 30
  2790.1  673.68  2809.8  674.02  2830.9  672.17    3116  663.03  3329.7  658.23
  3513.1  658.42  3675.9  657.73    3798  654.93  3889.1  651.76  3912.9  651.25
  4050.4  649.17  4376.8  649.82  4425.4  650.26  4470.4  649.43  4480.4  650.23
  4530.4  650.94  4680.4  649.23  4870.5  649.47  4915.2  648.93  4916.1  648.13
  4924.8  648.13  4925.7  648.93  5167.8  650.42  5351.5  651.24  5462.7  652.98
  5526.2  654.79  5683.9   661.1    5821  665.25  5881.7   666.1  6074.6  666.66
#Mann= 8 ,-1 , 0
  2790.1      .1       0  3889.1     .16       0  3912.9     .12       0
  4376.8      .1       0  4425.4     .12       0  4915.2     .07       0
  4925.7     .12       0  5167.8      .1       0
Bank Sta=4915.2,4925.7
XS Rating Curve= 0 ,0
Exp/Cntr=0.3,0.1

Type RM Length L Ch R = 1 ,1842    ,0,0,0
BEGIN DESCRIPTION:
UNT 103 in HW 1.0
END DESCRIPTION:
XS GIS Cut Line= 4
      2008804.81     13603403.99      2008145.11     13604263.34
      2008223.23     13606147.02      2009134.66     13607093.17
#Sta/Elev= 30
  3639.4  678.98  3796.7  674.71    3832  675.19  3931.7  671.42  4010.6  670.97
  4219.4  662.86  4567.1  647.87  4702.1  645.04  4840.2  644.35  4914.6  646.62
  5039.4  643.83  5040.2  643.03  5050.1  643.83    5065  644.39  5175.7  645.93
  5363.1  646.89  5649.5  648.37  5889.8  647.67  6207.8  648.08  6558.1  649.43
  6677.8  650.23  6818.9  651.04    6960  649.85  7059.8     650  7145.7  650.08
  7287.2  653.01  7383.2  655.72  7609.2   664.3  7726.1  665.93  7921.8  666.73
#Mann= 20 ,-1 , 0
  3639.4      .1       0  4219.4     .16       0  5039.4     .07       0
  5050.1     .12       0    5065     .16       0  5175.7     .12       0
  5363.1     .16       0  5649.5      .1       0  5889.8     .12       0
  6207.8      .1       0  6558.1     .05       0  6677.8     .05       0
  6818.9     .08       0    6960     .05       0  7059.8      .1       0
  7145.7     .05       0  7287.2      .1       0  7383.2     .08       0
  7609.2      .1       0  7726.1     .08       0
Bank Sta=5039.4,5050.1
XS Rating Curve= 0 ,0
Exp/Cntr=0.3,0.1
LCMann Table=0

Chan Stop Cuts=-1
Use User Specified Reach Order=0
Composite Channel Slope=5