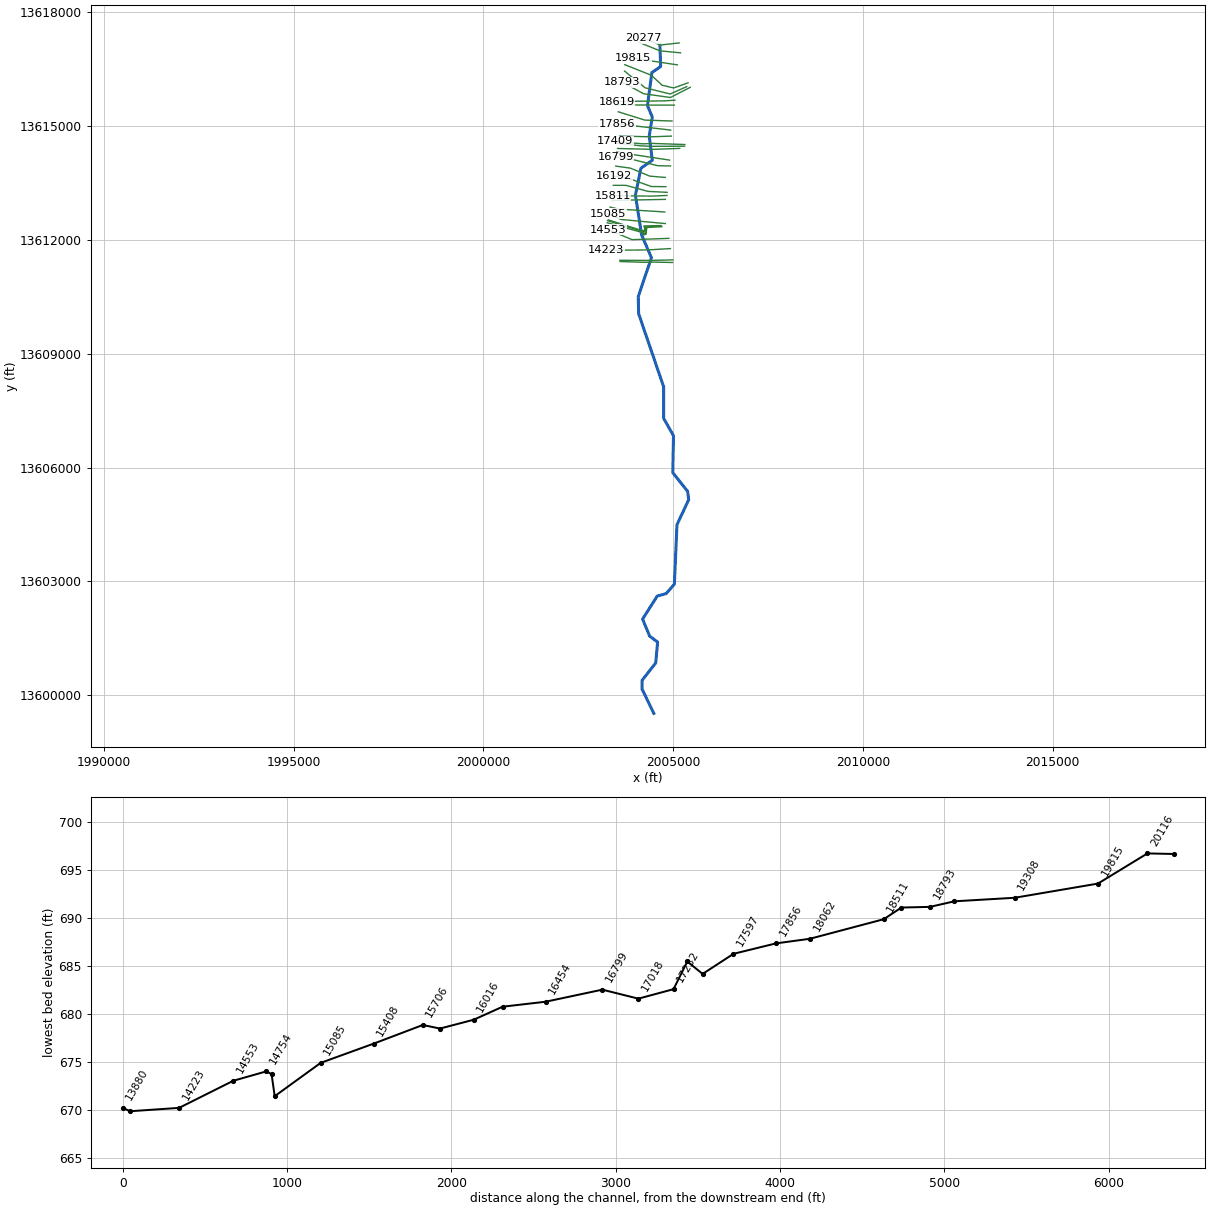
--- UNT 104 in HW.prj (project) ---

Proj Title=UNT 104 in HW Base Level Engineering
Current Plan=p01
Default Exp/Contr=0.3,0.1
English Units
Geom File=g01
Flow File=f01
Plan File=p01
BEGIN DESCRIPTION:
UNT 104 in HW
END DESCRIPTION:

--- UNT 104 in HW.p01 (plan) ---

Plan Title=Multiple Run
Short Identifier=Multiple
Geom File=g01
Flow File=f01
Subcritical Flow
K Sum by GR= 0
Std Step Tol= 0.01
Critical Tol= 0.01
Num of Std Step Trials= 20
Max Error Tol= 0.3
Flow Tol Ratio= 0.001
Split Flow NTrial= 30
Split Flow Tol= 0.02
Split Flow Ratio= 0.02
Log Output Level= 0
Friction Slope Method= 1
Unsteady Friction Slope Method= 2
Unsteady Bridges Friction Slope Method= 1
Parabolic Critical Depth
Global Vel Dist=  1 , 1 , 1
Global Log Level= 0
CheckData=True
Encroach Param= -1, 0, 0, 0
BEGIN DESCRIPTION:
Multiple Run
END DESCRIPTION:

--- UNT 104 in HW.f01 (steady flow) ---

Flow Title=Multiple
Number of Profiles=7
Profile Names=10-year,25-year,50-year,1pct_min,100-year,1pct_plu,500-year
River Rch & RM= UNT 104 in HW,Reach-1,20277
     555     780     968     595    1188    2370    1793
River Rch & RM= UNT 104 in HW,Reach-1,19815
     976    1413    1787    1117    2228    4446    3482
River Rch & RM= UNT 104 in HW,Reach-1,14223
    1345    1972    2516    1584    3161    6307    5014
River Rch & RM= UNT 104 in HW,Reach-1,8821
    1504    2213    2830    1785    3562    7106    5672
River Rch & RM= UNT 104 in HW,Reach-1,5505
    1627    2397    3066    1935    3860    7702    6148
Boundary for River Rch & Prof#=UNT 104 in HW,Reach-1,1
Up Type=0
Dn Type=3
Dn Slope=0.005
Boundary for River Rch & Prof#=UNT 104 in HW,Reach-1,2
Up Type=0
Dn Type=3
Dn Slope=0.005
Boundary for River Rch & Prof#=UNT 104 in HW,Reach-1,3
Up Type=0
Dn Type=3
Dn Slope=0.005
Boundary for River Rch & Prof#=UNT 104 in HW,Reach-1,4
Up Type=0
Dn Type=3
Dn Slope=0.005
Boundary for River Rch & Prof#=UNT 104 in HW,Reach-1,5
Up Type=0
Dn Type=3
Dn Slope=0.005
Boundary for River Rch & Prof#=UNT 104 in HW,Reach-1,6
Up Type=0
Dn Type=3
Dn Slope=0.005
Boundary for River Rch & Prof#=UNT 104 in HW,Reach-1,7
Up Type=0
Dn Type=3
Dn Slope=0.005

--- UNT 104 in HW.g01 (geometry) ---

Geom Title=Existing Conditions

River Reach=UNT 104 in HW,Reach-1
Reach XY= 30
      2004650.95     13617160.41      2004670.80     13616564.54
      2004440.80     13616404.54      2004323.68     13615535.89
      2004450.80     13615234.54      2004370.80     13614734.54
      2004450.80     13614094.54      2004150.80     13613884.54
      2004006.43     13613174.34      2004170.80     13612124.54
      2004428.29     13611527.32      2004080.80     13610504.54
      2004090.80     13610054.54      2004750.80     13608124.54
      2004750.80     13607294.54      2005009.13     13606838.28
      2004990.80     13605864.54      2005380.80     13605374.54
      2005410.80     13605154.54      2005100.80     13604494.54
      2005033.00     13602928.77      2004817.07     13602680.29
      2004580.80     13602614.54      2004194.69     13602008.56
      2004381.33     13601560.43      2004590.80     13601402.01
      2004540.80     13600852.96      2004180.80     13600394.54
      2004180.80     13600164.54      2004490.80     13599524.54

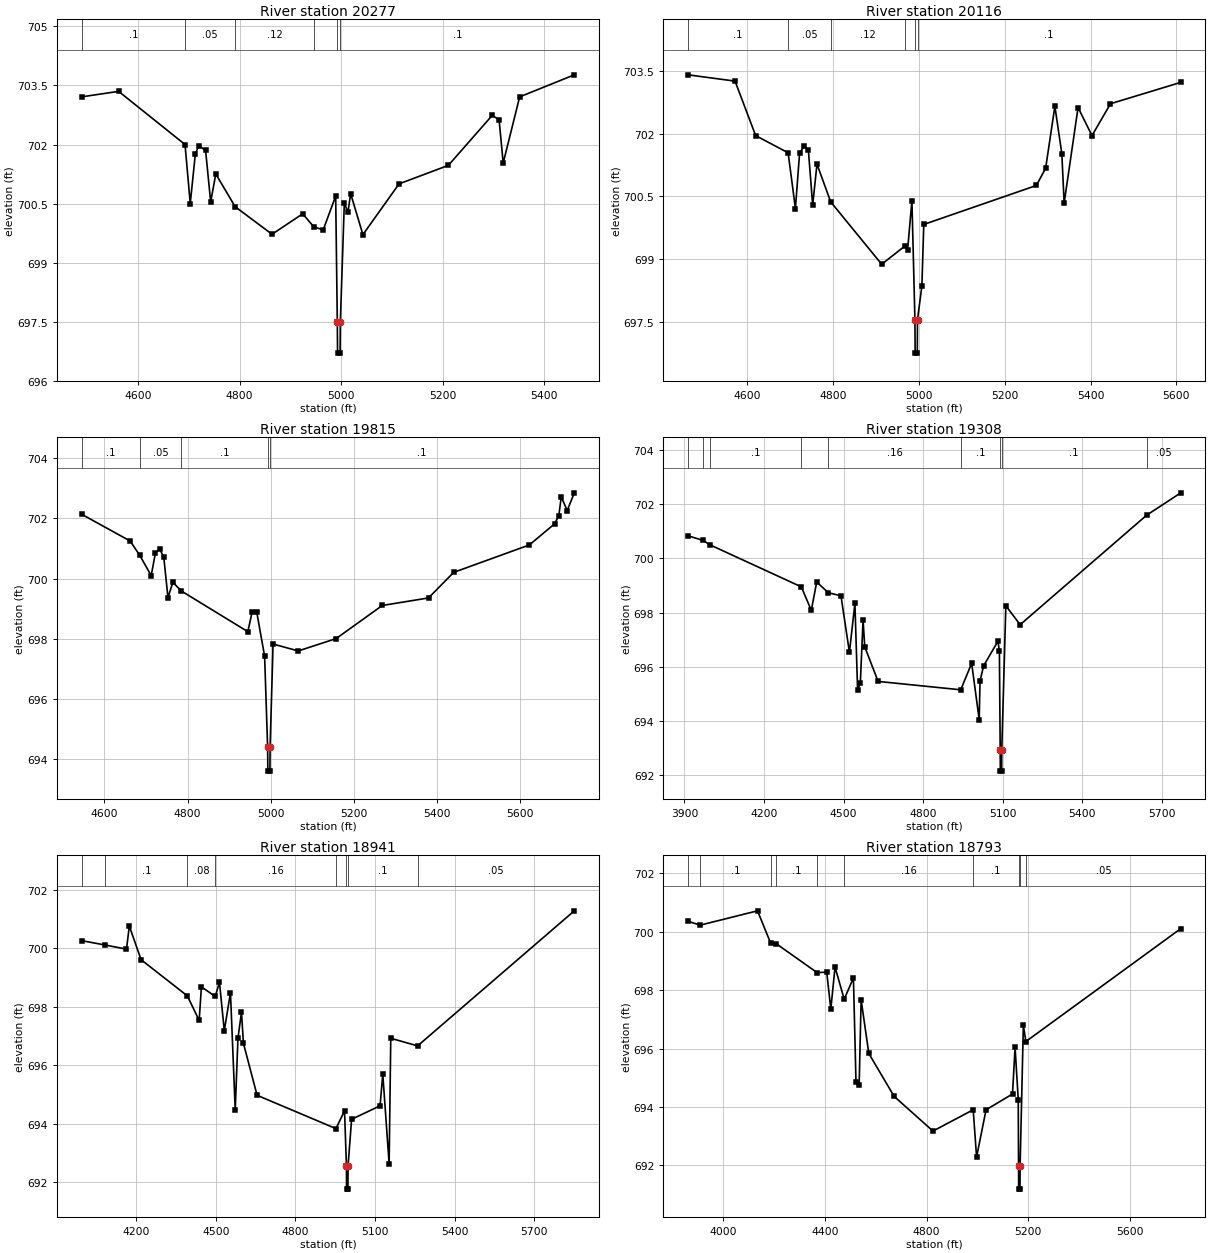
Type RM Length L Ch R = 1,20277,161,161,161
BEGIN DESCRIPTION:
UNT 104 in HW 24.0
END DESCRIPTION:
XS GIS Cut Line= 3
      2005157.55     13617186.76      2004662.75     13617129.46
      2004225.24     13617306.55
#Sta/Elev= 30
  4489.0  703.21  4562.0  703.35  4692.7  702.00  4703.0  700.50  4713.0  701.76
  4719.8  701.97  4733.2  701.85  4743.2  700.54  4753.3  701.25  4791.4  700.42
  4864.0  699.72  4924.4  700.24  4946.0  699.91  4964.7  699.83  4989.3  700.69
  4992.5  697.50  4993.0  696.70  4998.0  696.70  4998.5  697.50  5006.3  700.51
  5013.4  700.28  5018.8  700.75  5042.9  699.71  5114.1  701.00  5211.2  701.47
  5297.5  702.74  5311.0  702.63  5319.1  701.53  5351.5  703.21  5459.1  703.77
#Mann=6,-1,0
  4489.0     0.1       0  4692.7    0.05       0  4791.4    0.12       0
  4946.0     0.1       0  4992.5    0.07       0  4998.5     0.1       0
Bank Sta=4992.5,4998.5
Exp/Cntr=0.3,0.1

Type RM Length L Ch R = 1,20116,301,301,301
BEGIN DESCRIPTION:
Mapping XS b63c5ece
END DESCRIPTION:
XS GIS Cut Line= 3
      2005193.96     13616924.61      2004654.07     13616976.69
      2004093.33     13617204.11
#Sta/Elev= 30
  4462.7  703.40  4572.2  703.25  4620.2  701.95  4695.8  701.54  4712.8  700.21
  4722.5  701.53  4732.9  701.70  4743.0  701.60  4753.0  700.29  4763.0  701.27
  4794.9  700.37  4913.7  698.88  4968.3  699.32  4974.0  699.22  4984.1  700.40
  4991.1  697.56  4991.6  696.76  4996.6  696.76  4997.1  697.56  5007.3  698.36
  5011.7  699.83  5273.9  700.76  5295.5  701.17  5317.0  702.65  5333.2  701.52
  5338.6  700.34  5371.0  702.62  5403.4  701.95  5446.5  702.71  5610.2  703.22
#Mann=6,-1,0
  4462.7     0.1       0  4695.8    0.05       0  4794.9    0.12       0
  4968.3     0.1       0  4991.1    0.07       0  4997.1     0.1       0
Bank Sta=4991.1,4997.1
Exp/Cntr=0.3,0.1

Type RM Length L Ch R = 1,19815,507,507,507
BEGIN DESCRIPTION:
Mapping XS 9a4bd24f
END DESCRIPTION:
XS GIS Cut Line= 2
      2005110.71     13616607.75      2003938.07     13616784.56
#Sta/Elev= 30
  4545.0  702.14  4662.0  701.25  4685.3  700.77  4712.6  700.10  4722.7  700.85
  4732.8  700.99  4742.9  700.71  4753.0  699.37  4764.7  699.88  4785.3  699.59
  4945.2  698.24  4955.3  698.88  4966.5  698.90  4985.6  697.42  4992.8  694.41
  4993.3  693.61  4998.3  693.61  4998.8  694.41  5005.9  697.83  5066.5  697.60
  5157.6  698.01  5268.8  699.11  5380.0  699.36  5440.7  700.21  5622.8  701.12
  5683.4  701.82  5693.6  702.09  5699.5  702.72  5713.8  702.26  5730.9  702.85
#Mann=5,-1,0
  4545.0     0.1       0  4685.3    0.05       0  4785.3     0.1       0
  4992.8    0.07       0  4998.8     0.1       0
Bank Sta=4992.8,4998.8
Exp/Cntr=0.3,0.1

Type RM Length L Ch R = 1,19308,367,367,367
BEGIN DESCRIPTION:
Mapping XS 81a9bd74
END DESCRIPTION:
XS GIS Cut Line= 5
      2005394.38     13616135.51      2005014.20     13615999.36
      2004709.63     13616071.30      2004425.77     13616334.32
      2003725.22     13616612.98
#Sta/Elev= 30
  3913.8  700.84  3970.3  700.67  3995.5  700.51  4341.0  698.95  4378.5  698.08
  4399.0  699.13  4442.8  698.73  4490.4  698.62  4522.3  696.53  4543.0  698.34
  4553.1  695.13  4563.4  695.39  4573.7  697.72  4580.1  696.73  4630.4  695.45
  4941.9  695.14  4983.1  696.12  5011.5  694.04  5014.7  695.47  5028.3  696.03
  5082.3  696.94  5087.7  696.57  5090.7  692.93  5091.2  692.13  5096.2  692.13
  5096.7  692.93  5112.0  698.25  5165.9  697.55  5642.6  701.60  5771.5  702.43
#Mann=9,-1,0
  3913.8     0.1       0  3970.3    0.05       0  3995.5     0.1       0
  4341.0    0.08       0  4442.8    0.16       0  4941.9     0.1       0
  5090.7    0.07       0  5096.7     0.1       0  5642.6    0.05       0
Bank Sta=5090.7,5096.7
Exp/Cntr=0.3,0.1

Type RM Length L Ch R = 1,18941,148,148,148
BEGIN DESCRIPTION:
Mapping XS 0ad2ce7a
END DESCRIPTION:
XS GIS Cut Line= 4
      2005359.65     13616035.68      2004923.50     13615840.62
      2004261.71     13616003.59      2003720.02     13616443.72
#Sta/Elev= 30
  3994.2  700.26  4083.3  700.11  4163.6  699.97  4174.3  700.76  4218.4  699.61
  4393.0  698.37  4437.5  697.53  4446.0  698.68  4498.2  698.35  4514.0  698.84
  4532.2  697.18  4555.5  698.48  4573.4  694.47  4583.7  696.92  4597.0  697.81
  4604.3  696.75  4655.8  694.97  4953.2  693.83  4985.4  694.44  4992.6  692.56
  4993.1  691.76  4998.2  691.76  4998.7  692.56  5012.1  694.15  5119.3  694.61
  5129.6  695.69  5153.5  692.63  5159.7  696.92  5260.9  696.66  5851.5  701.28
#Mann=8,-1,0
  3994.2    0.05       0  4083.3     0.1       0  4393.0    0.08       0
  4498.2    0.16       0  4953.2     0.1       0  4992.6    0.07       0
  4998.7     0.1       0  5260.9    0.05       0
Bank Sta=4992.6,4998.7
Exp/Cntr=0.3,0.1

Type RM Length L Ch R = 1,18793,174,174,174
BEGIN DESCRIPTION:
Mapping XS 111a2197
END DESCRIPTION:
XS GIS Cut Line= 4
      2005450.75     13616016.12      2004928.56     13615748.31
      2004222.65     13615847.34      2003660.15     13616152.03
#Sta/Elev= 30
  3860.8  700.36  3909.0  700.23  4134.3  700.72  4186.2  699.61  4208.5  699.59
  4369.2  698.60  4406.7  698.62  4422.8  697.35  4439.4  698.79  4475.5  697.69
  4511.8  698.42  4521.9  694.85  4534.4  694.76  4542.1  697.67  4572.4  695.83
  4672.0  694.36  4824.9  693.17  4983.2  693.90  4996.5  692.28  5033.8  693.90
  5137.9  694.44  5148.0  696.04  5160.5  694.25  5161.7  691.98  5162.2  691.18
  5167.3  691.18  5167.8  691.98  5180.6  696.80  5190.5  696.24  5800.2  700.11
#Mann=10,-1,0
  3860.8    0.05       0  3909.0     0.1       0  4186.2    0.08       0
  4208.5     0.1       0  4369.2    0.08       0  4475.5    0.16       0
  4983.2     0.1       0  5161.7    0.07       0  5167.8     0.1       0
  5190.5    0.05       0
Bank Sta=5161.7,5167.8
Exp/Cntr=0.3,0.1

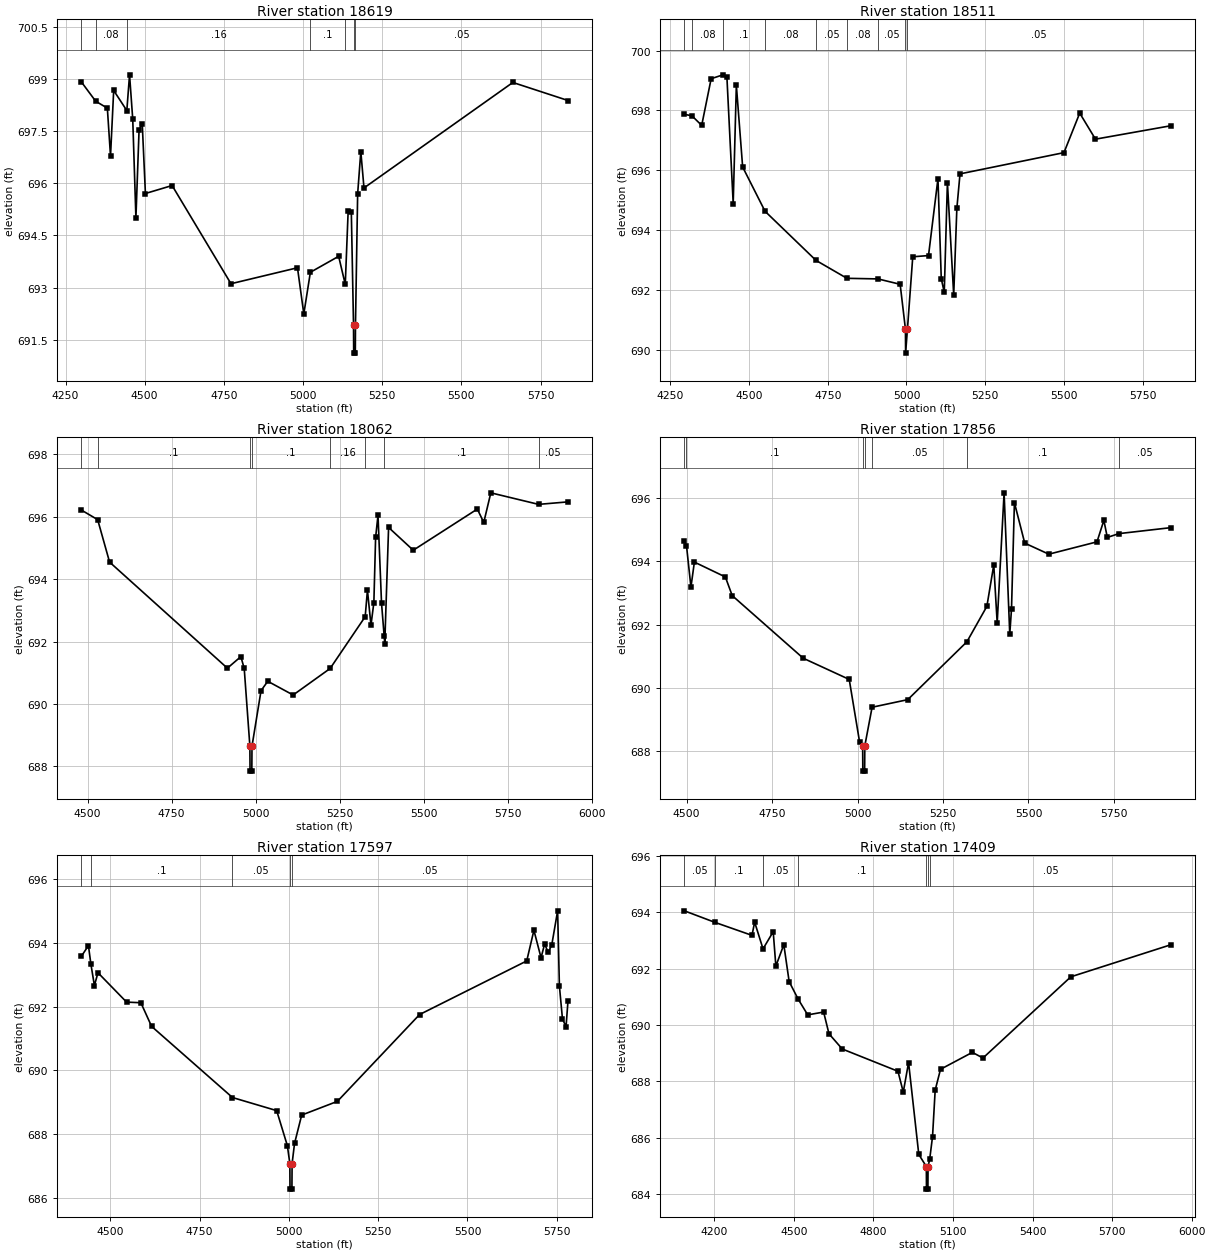
Type RM Length L Ch R = 1,18619,108,108,108
BEGIN DESCRIPTION:
UNT 104 in HW 23.0
END DESCRIPTION:
XS GIS Cut Line= 3
      2005047.26     13615676.77      2004760.84     13615659.41
      2003510.81     13615642.05
#Sta/Elev= 30
  4299.7  698.93  4345.2  698.37  4382.1  698.17  4392.1  696.79  4402.1  698.68
  4443.6  698.10  4452.2  699.13  4462.3  697.85  4472.3  695.01  4482.3  697.55
  4492.3  697.72  4502.3  695.71  4586.6  695.94  4772.5  693.11  4982.5  693.57
  5002.5  692.24  5023.2  693.44  5112.5  693.90  5133.4  693.09  5142.5  695.20
  5152.5  695.18  5159.5  691.91  5160.0  691.11  5165.1  691.11  5165.6  691.91
  5172.5  695.70  5182.5  696.92  5192.5  695.87  5662.6  698.91  5836.8  698.39
#Mann=7,-1,0
  4299.7     0.1       0  4345.2    0.08       0  4443.6    0.16       0
  5023.2     0.1       0  5133.4    0.05       0  5159.5    0.07       0
  5165.6    0.05       0
Bank Sta=5159.5,5165.6
Exp/Cntr=0.3,0.1

Type RM Length L Ch R = 1,18511,449,449,449
BEGIN DESCRIPTION:
UNT 104 in HW 22.0
END DESCRIPTION:
XS GIS Cut Line= 3
      2005029.96     13615546.56      2004700.08     13615546.56
      2003484.79     13615555.24
#Sta/Elev= 30
  4294.9  697.87  4319.0  697.82  4349.9  697.50  4379.9  699.06  4417.4  699.19
  4429.9  699.12  4449.9  694.89  4459.9  698.84  4479.9  696.11  4551.0  694.63
  4712.6  692.99  4811.0  692.39  4909.5  692.37  4979.9  692.19  4996.7  690.69
  4997.2  689.89  5003.0  690.69  5019.9  693.11  5069.9  693.15  5099.9  695.72
  5110.4  692.38  5119.9  691.92  5129.9  695.59  5149.9  691.83  5159.9  694.73
  5169.9  695.88  5499.9  696.59  5549.9  697.91  5599.9  697.04  5840.1  697.49
#Mann=9,-1,0
  4294.9     0.1       0  4319.0    0.08       0  4417.4     0.1       0
  4551.0    0.08       0  4712.6    0.05       0  4811.0    0.08       0
  4909.5    0.05       0  4996.7    0.04       0  5003.0    0.05       0
Bank Sta=4996.7,5003
Exp/Cntr=0.3,0.1

Type RM Length L Ch R = 1,18062,206,206,206
BEGIN DESCRIPTION:
Mapping XS d6859f51
END DESCRIPTION:
XS GIS Cut Line= 3
      2004969.20     13615128.59      2004253.90     13615152.90
      2003555.99     13615371.65
#Sta/Elev= 30
  4481.3  696.22  4530.1  695.91  4565.5  694.55  4915.7  691.15  4955.8  691.52
  4965.8  691.14  4982.6  688.65  4983.1  687.85  4988.4  687.85  4988.9  688.65
  5015.8  690.43  5035.8  690.73  5111.2  690.29  5221.2  691.14  5325.4  692.80
  5332.1  693.65  5342.6  692.53  5351.2  693.25  5356.4  695.34  5363.5  696.05
  5374.0  693.23  5381.9  692.17  5383.6  691.94  5395.0  695.66  5468.3  694.93
  5658.8  696.25  5677.9  695.82  5698.9  696.77  5840.9  696.40  5928.4  696.48
#Mann=8,-1,0
  4481.3    0.05       0  4530.1     0.1       0  4982.6    0.07       0
  4988.9     0.1       0  5221.2    0.16       0  5325.4    0.05       0
  5381.9     0.1       0  5840.9    0.05       0
Bank Sta=4982.6,4988.9
Exp/Cntr=0.3,0.1

Type RM Length L Ch R = 1,17856,259,259,259
BEGIN DESCRIPTION:
Mapping XS b2af9058
END DESCRIPTION:
XS GIS Cut Line= 2
      2004934.09     13614889.59      2003519.57     13615054.47
#Sta/Elev= 30
  4493.3  694.64  4499.5  694.50  4512.5  693.19  4522.6  693.98  4613.2  693.51
  4633.3  692.92  4841.0  690.94  4975.6  690.27  5005.8  688.30  5014.9  688.17
  5015.4  687.37  5020.7  687.37  5021.2  688.17  5042.5  689.39  5146.8  689.63
  5319.9  691.46  5378.3  692.58  5398.5  693.89  5408.5  692.06  5428.7  696.17
  5445.3  691.70  5450.4  692.50  5458.9  695.86  5489.1  694.58  5559.6  694.23
  5700.5  694.62  5720.6  695.30  5730.7  694.76  5764.5  694.88  5917.4  695.07
#Mann=7,-1,0
  4493.3    0.08       0  4499.5     0.1       0  5014.9    0.07       0
  5021.2     0.1       0  5042.5    0.05       0  5319.9     0.1       0
  5764.5    0.05       0
Bank Sta=5014.9,5021.2
Exp/Cntr=0.3,0.1

Type RM Length L Ch R = 1,17597,188,188,188
BEGIN DESCRIPTION:
UNT 104 in HW 21.0
END DESCRIPTION:
XS GIS Cut Line= 3
      2004951.81     13614730.59      2004413.62     13614713.23
      2003589.47     13614730.58
#Sta/Elev= 30
  4418.7  693.57  4438.8  693.91  4445.7  693.33  4455.5  692.66  4465.5  693.06
  4545.6  692.14  4585.6  692.12  4615.6  691.38  4842.1  689.15  4965.8  688.74
  4995.8  687.64  5002.7  687.08  5003.2  686.28  5008.5  686.28  5009.0  687.08
  5015.8  687.71  5035.8  688.60  5135.8  689.03  5365.9  691.75  5665.9  693.43
  5686.0  694.39  5706.0  693.53  5716.0  693.96  5726.0  693.70  5736.0  693.93
  5752.4  695.00  5757.4  692.64  5766.0  691.61  5776.0  691.37  5781.5  692.19
#Mann=5,-1,0
  4418.7    0.05       0  4445.7     0.1       0  4842.1    0.05       0
  5002.7   0.035       0  5009.0    0.05       0
Bank Sta=5002.7,5009
Exp/Cntr=0.3,0.1

Type RM Length L Ch R = 1,17409,93,93,93
BEGIN DESCRIPTION:
Mapping XS 0c169351
END DESCRIPTION:
XS GIS Cut Line= 6
      2005309.73     13614508.98      2004423.02     13614539.66
      2004351.41     13614533.15      2004247.24     13614528.80
      2004151.76     13614530.97      2003478.39     13614591.60
#Sta/Elev= 30
  4087.6  694.05  4203.0  693.64  4342.5  693.18  4352.5  693.65  4384.1  692.70
  4422.5  693.31  4432.5  692.09  4462.5  692.85  4482.6  691.54  4516.4  690.92
  4552.6  690.36  4612.6  690.46  4632.7  689.69  4682.7  689.15  4892.8  688.36
  4912.8  687.62  4932.8  688.67  4971.3  685.41  4999.8  684.98  5000.3  684.18
  5005.7  684.18  5006.2  684.98  5012.4  685.24  5023.1  686.04  5033.1  687.69
  5053.2  688.43  5173.2  689.03  5213.3  688.83  5544.5  691.71  5922.6  692.85
#Mann=7,-1,0
  4087.6    0.05       0  4203.0     0.1       0  4384.1    0.05       0
  4516.4     0.1       0  4999.8    0.07       0  5006.2     0.1       0
  5012.4    0.05       0
Bank Sta=4999.8,5006.2
Exp/Cntr=0.3,0.1

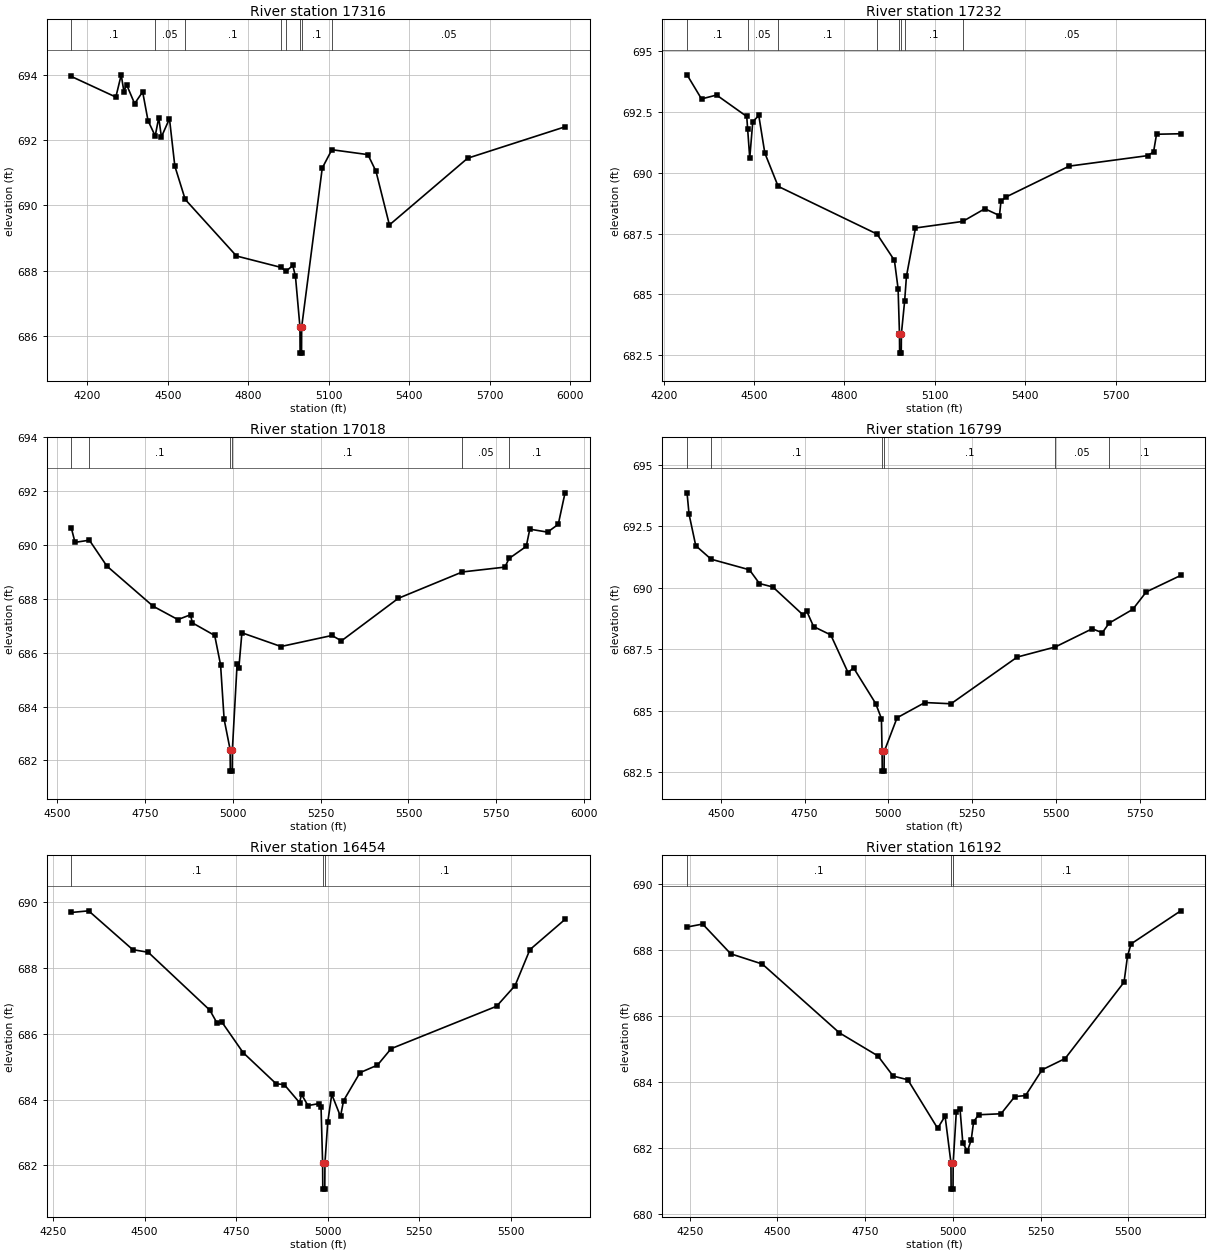
Type RM Length L Ch R = 1,17316,84,84,84
BEGIN DESCRIPTION:
Mapping XS 93ea902e
END DESCRIPTION:
XS GIS Cut Line= 5
      2005300.99     13614465.57      2004394.81     13614461.53
      2004273.28     13614468.04      2004132.22     13614476.72
      2003463.80     13614550.51
#Sta/Elev= 30
  4139.8  693.94  4305.8  693.31  4325.8  693.99  4335.8  693.48  4345.8  693.69
  4375.8  693.11  4405.8  693.47  4425.8  692.59  4452.6  692.12  4465.8  692.68
  4475.8  692.09  4505.8  692.65  4525.8  691.20  4564.5  690.18  4755.8  688.45
  4922.7  688.10  4940.4  687.98  4965.8  688.16  4975.8  687.83  4992.6  686.28
  4993.1  685.48  4998.5  685.48  4999.0  686.28  5075.8  691.14  5111.6  691.70
  5246.1  691.55  5276.2  691.04  5326.3  689.40  5618.1  691.44  5981.5  692.40
#Mann=8,-1,0
  4139.8     0.1       0  4452.6    0.05       0  4564.5     0.1       0
  4922.7    0.05       0  4940.4     0.1       0  4992.6    0.07       0
  4999.0     0.1       0  5111.6    0.05       0
Bank Sta=4992.6,4999
Exp/Cntr=0.3,0.1

Type RM Length L Ch R = 1,17232,214,214,214
BEGIN DESCRIPTION:
UNT 104 in HW 20.0
END DESCRIPTION:
XS GIS Cut Line= 3
      2005173.03     13614406.98      2004472.83     13614381.42
      2003534.69     13614405.07
#Sta/Elev= 30
  4277.3  694.02  4325.4  693.03  4375.4  693.19  4475.5  692.31  4478.6  691.78
  4485.5  690.60  4495.5  692.09  4515.5  692.35  4535.5  690.81  4579.8  689.44
  4908.1  687.48  4965.8  686.40  4978.0  685.24  4982.6  683.39  4983.1  682.59
  4988.5  682.59  4989.0  683.39  4999.7  684.72  5005.8  685.75  5035.8  687.73
  5192.8  688.00  5265.9  688.52  5314.6  688.24  5319.6  688.83  5335.9  689.00
  5546.0  690.27  5806.1  690.70  5826.1  690.85  5836.1  691.58  5916.4  691.60
#Mann=8,-1,0
  4277.3     0.1       0  4478.6    0.05       0  4579.8     0.1       0
  4908.1    0.05       0  4982.6    0.07       0  4989.0    0.05       0
  4999.7     0.1       0  5192.8    0.05       0
Bank Sta=4982.6,4989
Exp/Cntr=0.3,0.1

Type RM Length L Ch R = 1,17018,219,219,219
BEGIN DESCRIPTION:
Mapping XS 4675a62d
END DESCRIPTION:
XS GIS Cut Line= 2
      2004904.81     13614099.11      2003515.88     13614309.63
#Sta/Elev= 30
  4540.8  690.63  4551.2  690.10  4592.1  690.18  4641.8  689.22  4773.2  687.73
  4844.0  687.23  4879.9  687.41  4885.0  687.11  4948.7  686.64  4965.4  685.55
  4975.5  683.53  4992.6  682.40  4993.1  681.60  4998.5  681.60  4999.0  682.40
  5012.4  685.57  5017.4  685.43  5026.1  686.74  5137.3  686.23  5282.4  686.64
  5309.3  686.44  5471.1  688.02  5653.3  689.00  5774.5  689.18  5786.3  689.50
  5835.2  689.95  5845.3  690.59  5895.9  690.48  5926.3  690.77  5945.6  691.94
#Mann=6,-1,0
  4540.8    0.08       0  4592.1     0.1       0  4992.6    0.07       0
  4999.0     0.1       0  5653.3    0.05       0  5786.3     0.1       0
Bank Sta=4992.6,4999
Exp/Cntr=0.3,0.1

Type RM Length L Ch R = 1,16799,345,345,345
BEGIN DESCRIPTION:
Mapping XS 4def04aa
END DESCRIPTION:
XS GIS Cut Line= 4
      2004930.97     13613944.57      2004594.17     13613951.51
      2003889.31     13614125.12      2003483.03     13614177.21
#Sta/Elev= 30
  4399.6  693.86  4405.6  692.99  4425.6  691.71  4471.4  691.16  4585.6  690.73
  4615.6  690.17  4655.6  690.03  4745.9  688.89  4756.2  689.06  4777.0  688.42
  4828.3  688.08  4879.8  686.55  4896.3  686.74  4962.2  685.29  4979.3  684.68
  4981.3  683.34  4981.8  682.54  4987.2  682.54  4987.7  683.34  5026.0  684.71
  5109.0  685.33  5186.9  685.28  5384.4  687.18  5497.8  687.59  5607.9  688.33
  5638.1  688.17  5658.5  688.56  5728.9  689.12  5769.2  689.83  5872.0  690.50
#Mann=6,-1,0
  4399.6    0.05       0  4471.4     0.1       0  4981.3    0.07       0
  4987.7     0.1       0  5497.8    0.05       0  5658.5     0.1       0
Bank Sta=4981.3,4987.7
Exp/Cntr=0.3,0.1

Type RM Length L Ch R = 1,16454,262,262,262
BEGIN DESCRIPTION:
Mapping XS 6bdf38f2
END DESCRIPTION:
XS GIS Cut Line= 4
      2004792.08     13613642.49      2004382.37     13613677.21
      2003878.90     13613885.54      2003489.99     13613941.10
#Sta/Elev= 30
  4299.8  689.69  4347.0  689.74  4467.5  688.56  4509.9  688.48  4678.2  686.72
  4698.3  686.32  4711.0  686.36  4769.1  685.43  4859.6  684.48  4881.3  684.46
  4923.3  683.91  4928.8  684.16  4946.2  683.82  4976.5  683.88  4982.0  683.78
  4986.3  682.08  4986.8  681.28  4992.2  681.28  4992.7  682.08  5000.3  683.31
  5011.3  684.16  5035.2  683.49  5043.6  683.97  5088.4  684.82  5136.2  685.05
  5173.5  685.55  5461.8  686.84  5512.3  687.47  5552.7  688.56  5648.7  689.48
#Mann=3,-1,0
  4299.8     0.1       0  4986.3    0.07       0  4992.7     0.1       0
Bank Sta=4986.3,4992.7
Exp/Cntr=0.3,0.1

Type RM Length L Ch R = 1,16192,176,176,176
BEGIN DESCRIPTION:
Mapping XS add09878
END DESCRIPTION:
XS GIS Cut Line= 4
      2004809.46     13613399.43      2004424.04     13613402.90
      2003809.45     13613625.12      2003444.84     13613673.74
#Sta/Elev= 30
  4242.6  688.69  4287.1  688.78  4367.1  687.88  4457.1  687.57  4676.6  685.49
  4786.5  684.79  4829.9  684.18  4871.6  684.07  4956.7  682.60  4977.9  682.97
  4994.6  681.56  4995.1  680.76  5000.5  680.76  5001.0  681.56  5009.8  683.08
  5020.5  683.18  5028.5  682.15  5041.7  681.91  5052.4  682.25  5059.2  682.80
  5073.6  683.01  5137.4  683.04  5176.5  683.56  5207.1  683.59  5254.4  684.37
  5319.9  684.71  5487.8  687.02  5497.9  687.82  5508.0  688.18  5649.4  689.18
#Mann=3,-1,0
  4242.6     0.1       0  4994.6    0.07       0  5001.0     0.1       0
Bank Sta=4994.6,5001
Exp/Cntr=0.3,0.1

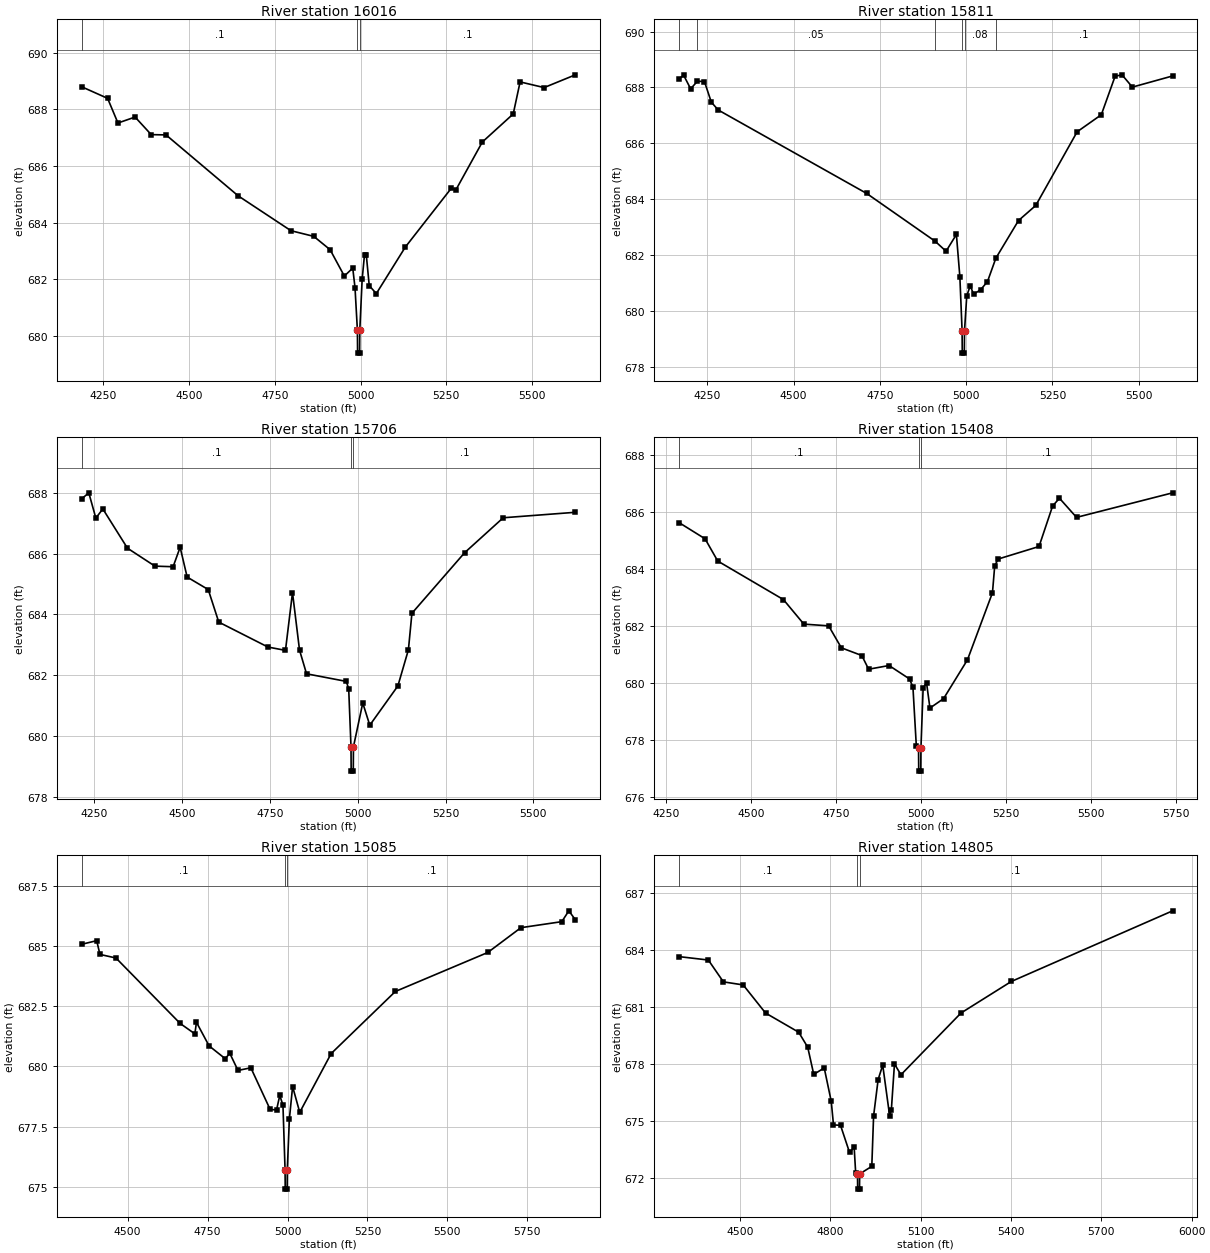
Type RM Length L Ch R = 1,16016,205,205,205
BEGIN DESCRIPTION:
Mapping XS 61b44817
END DESCRIPTION:
XS GIS Cut Line= 4
      2004840.73     13613250.12      2004337.23     13613274.43
      2003757.37     13613434.15      2003424.01     13613434.15
#Sta/Elev= 30
  4187.2  688.80  4263.0  688.39  4293.1  687.52  4343.1  687.73  4390.1  687.11
  4433.2  687.10  4643.5  684.95  4797.3  683.72  4863.8  683.52  4911.4  683.05
  4952.9  682.12  4977.4  682.40  4984.0  681.71  4991.0  680.20  4991.5  679.40
  4997.4  679.40  4997.9  680.20  5004.8  682.00  5011.7  682.88  5016.9  682.86
  5025.5  681.78  5046.1  681.50  5130.5  683.14  5264.1  685.21  5278.4  685.17
  5355.1  686.85  5445.1  687.84  5465.1  688.97  5535.1  688.77  5626.1  689.22
#Mann=3,-1,0
  4187.2     0.1       0  4991.0    0.07       0  4997.9     0.1       0
Bank Sta=4991,4997.9
Exp/Cntr=0.3,0.1

Type RM Length L Ch R = 1,15811,105,105,105
BEGIN DESCRIPTION:
UNT 104 in HW 19.0
END DESCRIPTION:
XS GIS Cut Line= 3
      2004838.94     13613168.09      2004430.98     13613150.73
      2003408.35     13613159.40
#Sta/Elev= 30
  4167.4  688.31  4181.4  688.43  4201.4  687.95  4221.2  688.22  4241.4  688.21
  4261.4  687.47  4281.4  687.19  4711.7  684.20  4909.9  682.49  4941.7  682.13
  4971.7  682.73  4981.7  681.22  4988.2  679.28  4988.7  678.48  4994.7  678.48
  4995.2  679.28  5001.7  680.53  5011.7  680.89  5021.7  680.59  5041.7  680.75
  5061.7  681.04  5086.0  681.88  5151.7  683.23  5201.7  683.77  5321.7  686.41
  5391.7  687.02  5431.7  688.40  5451.7  688.45  5481.7  688.01  5598.4  688.41
#Mann=6,-1,0
  4167.4    0.08       0  4221.2    0.05       0  4909.9    0.08       0
  4988.2    0.07       0  4995.2    0.08       0  5086.0     0.1       0
Bank Sta=4988.2,4995.2
Exp/Cntr=0.3,0.1

Type RM Length L Ch R = 1,15706,298,298,298
BEGIN DESCRIPTION:
Mapping XS 6692a6db
END DESCRIPTION:
XS GIS Cut Line= 2
      2004795.54     13613063.92      2003389.68     13613037.89
#Sta/Elev= 30
  4213.6  687.80  4234.1  688.00  4254.1  687.17  4274.1  687.47  4344.2  686.18
  4422.4  685.59  4474.2  685.57  4494.2  686.21  4514.2  685.23  4574.2  684.82
  4604.2  683.75  4744.2  682.93  4794.2  682.82  4814.2  684.72  4834.2  682.83
  4854.2  682.05  4967.5  681.80  4974.3  681.55  4980.8  679.65  4981.3  678.85
  4987.3  678.85  4987.8  679.65  5014.3  681.09  5034.3  680.36  5114.3  681.65
  5144.3  682.84  5154.3  684.04  5304.3  686.03  5414.3  687.18  5619.7  687.36
#Mann=3,-1,0
  4213.6     0.1       0  4980.8    0.07       0  4987.8     0.1       0
Bank Sta=4980.8,4987.8
Exp/Cntr=0.3,0.1

Type RM Length L Ch R = 1,15408,323,323,323
BEGIN DESCRIPTION:
Mapping XS 8e4d1ebe
END DESCRIPTION:
XS GIS Cut Line= 3
      2004781.72     13612732.76      2003555.98     13612809.15
      2003338.57     13612860.91
#Sta/Elev= 30
  4287.7  685.62  4364.6  685.05  4401.9  684.27  4595.0  682.92  4655.1  682.06
  4728.0  682.00  4765.3  681.23  4825.5  680.96  4845.5  680.48  4905.6  680.61
  4965.7  680.14  4975.8  679.85  4985.8  677.78  4992.3  677.71  4992.8  676.91
  4998.8  676.91  4999.3  677.71  5005.8  679.83  5015.8  680.00  5025.8  679.12
  5065.9  679.45  5136.1  680.81  5209.6  683.16  5216.2  684.10  5226.2  684.34
  5346.5  684.78  5386.5  686.20  5406.6  686.47  5456.7  685.80  5739.3  686.66
#Mann=3,-1,0
  4287.7     0.1       0  4992.3    0.07       0  4999.3     0.1       0
Bank Sta=4992.3,4999.3
Exp/Cntr=0.3,0.1

Type RM Length L Ch R = 1,15085,280,280,280
BEGIN DESCRIPTION:
Mapping XS 82bfe508
END DESCRIPTION:
XS GIS Cut Line= 3
      2004792.04     13612427.21      2003632.37     13612534.84
      2003286.35     13612690.55
#Sta/Elev= 30
  4356.0  685.07  4403.2  685.22  4413.3  684.65  4463.5  684.50  4664.4  681.78
  4710.2  681.35  4715.2  681.83  4754.7  680.85  4805.0  680.32  4819.5  680.54
  4845.1  679.83  4885.3  679.94  4945.6  678.21  4965.7  678.19  4975.7  678.79
  4985.7  678.39  4992.3  675.70  4992.8  674.90  4998.8  674.90  4999.3  675.70
  5005.8  677.82  5015.9  679.16  5038.2  678.09  5136.4  680.53  5337.2  683.11
  5626.3  684.73  5729.9  685.76  5857.7  686.01  5879.8  686.46  5900.1  686.09
#Mann=3,-1,0
  4356.0     0.1       0  4992.3    0.07       0  4999.3     0.1       0
Bank Sta=4992.3,4999.3
Exp/Cntr=0.3,0.1

Type RM Length L Ch R = 1,14805,19,19,19
BEGIN DESCRIPTION:
Mapping XS ff88d22b
END DESCRIPTION:
XS GIS Cut Line= 6
      2004682.75     13612375.12      2004229.16     13612364.27
      2004250.86     13612303.51      2004233.50     13612197.17
      2004209.63     13612234.06      2003293.87     13612522.68
#Sta/Elev= 30
  4296.9  683.66  4394.7  683.48  4444.7  682.33  4510.4  682.17  4584.7  680.69
  4694.8  679.68  4724.8  678.89  4744.8  677.46  4779.6  677.80  4802.9  676.04
  4810.4  674.80  4833.7  674.78  4863.7  673.35  4879.0  673.63  4884.0  672.29
  4890.1  672.22  4890.7  671.42  4896.8  671.42  4897.3  672.22  4937.6  672.62
  4943.6  675.28  4958.7  677.19  4973.9  677.95  4996.8  675.29  5002.5  675.58
  5012.9  678.01  5034.4  677.44  5233.8  680.69  5400.9  682.35  5936.8  686.07
#Mann=3,-1,0
  4296.9     0.1       0  4890.1    0.07       0  4897.3     0.1       0
Bank Sta=4890.1,4897.3
Exp/Cntr=0.3,0.1

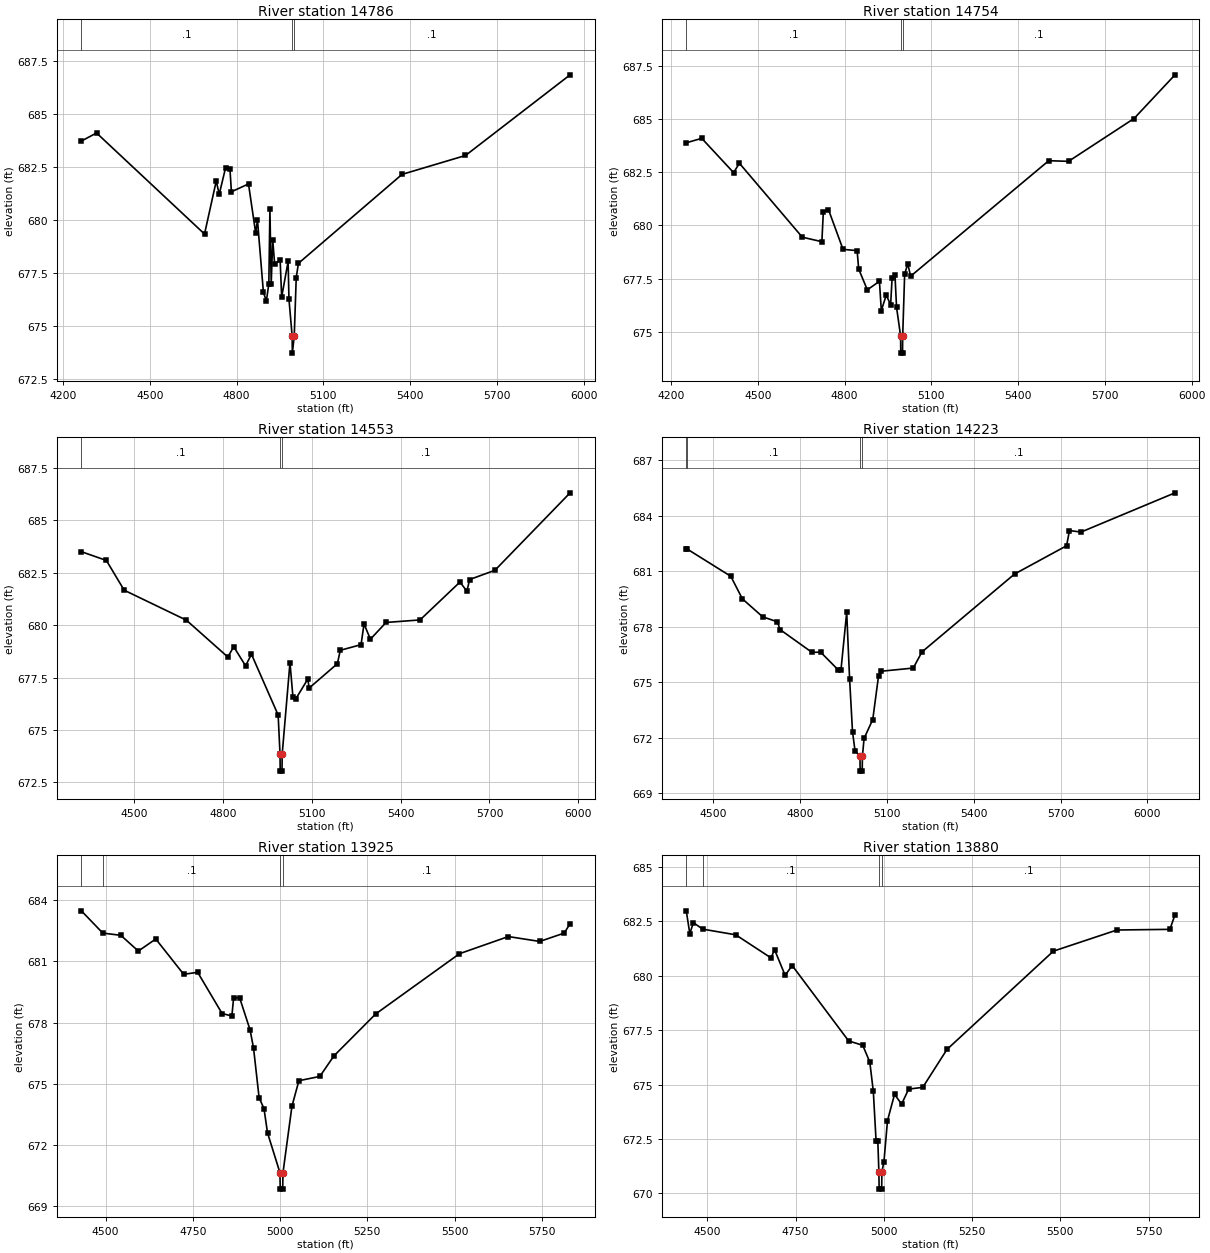
Type RM Length L Ch R = 1,14786,32,32,32
BEGIN DESCRIPTION:
Mapping XS 93b175b0
END DESCRIPTION:
XS GIS Cut Line= 6
      2004694.87     13612350.82      2004267.79     13612343.87
      2004271.26     13612170.26      2004222.65     13612159.84
      2004201.81     13612218.87      2003268.92     13612503.25
#Sta/Elev= 30
  4262.9  683.71  4315.5  684.09  4688.9  679.33  4729.5  681.83  4739.7  681.20
  4761.7  682.45  4776.8  682.40  4781.9  681.32  4841.0  681.69  4865.7  679.39
  4872.1  679.97  4892.6  676.58  4902.8  676.18  4911.3  676.98  4915.1  680.50
  4919.5  676.98  4924.8  679.05  4931.5  677.91  4950.4  678.11  4955.7  676.36
  4978.0  678.04  4980.9  676.27  4992.0  674.52  4992.6  673.72  4999.2  674.52
  5006.1  677.28  5013.7  677.95  5372.0  682.14  5591.5  683.03  5953.3  686.83
#Mann=3,-1,0
  4262.9     0.1       0  4992.0    0.07       0  4999.2     0.1       0
Bank Sta=4992,4999.2
Exp/Cntr=0.3,0.1

Type RM Length L Ch R = 1,14754,201,201,201
BEGIN DESCRIPTION:
Mapping XS c5368727
END DESCRIPTION:
XS GIS Cut Line= 6
      2004698.37     13612347.35      2004305.98     13612323.04
      2004288.62     13612149.43      2004226.12     13612125.12
      2004191.40     13612191.09      2003264.31     13612448.04
#Sta/Elev= 30
  4252.9  683.88  4306.4  684.09  4416.6  682.48  4436.6  682.92  4654.1  679.45
  4721.7  679.24  4726.7  680.62  4744.4  680.75  4794.8  678.88  4843.6  678.82
  4848.9  677.96  4878.8  676.98  4920.7  677.38  4927.2  676.01  4944.3  676.73
  4959.4  676.28  4964.4  677.52  4974.4  677.68  4979.9  676.16  4993.9  674.81
  4994.4  674.01  5000.5  674.01  5001.1  674.81  5007.9  677.72  5018.6  678.20
  5028.6  677.62  5506.0  683.04  5574.4  683.01  5800.9  685.02  5942.5  687.07
#Mann=3,-1,0
  4252.9     0.1       0  4993.9    0.07       0  5001.1     0.1       0
Bank Sta=4993.9,5001.1
Exp/Cntr=0.3,0.1

Type RM Length L Ch R = 1,14553,330,330,330
BEGIN DESCRIPTION:
Mapping XS 8de4ff37
END DESCRIPTION:
XS GIS Cut Line= 3
      2004889.57     13612037.48      2003917.38     13612002.76
      2003292.35     13612267.53
#Sta/Elev= 30
  4320.8  683.51  4405.4  683.09  4465.5  681.67  4675.6  680.24  4815.7  678.48
  4835.7  678.97  4875.7  678.06  4895.7  678.61  4985.8  675.71  4992.2  673.83
  4992.7  673.03  4998.9  673.03  4999.4  673.83  5025.8  678.21  5035.8  676.57
  5045.8  676.49  5085.8  677.42  5090.8  677.00  5185.9  678.16  5195.9  678.80
  5266.0  679.07  5276.0  680.06  5297.6  679.33  5350.5  680.13  5465.3  680.25
  5600.3  682.06  5623.6  681.62  5632.9  682.18  5718.3  682.62  5972.4  686.32
#Mann=3,-1,0
  4320.8     0.1       0  4992.2    0.07       0  4999.4     0.1       0
Bank Sta=4992.2,4999.4
Exp/Cntr=0.3,0.1

Type RM Length L Ch R = 1,14223,298,298,298
BEGIN DESCRIPTION:
Mapping XS dd8e7a48
END DESCRIPTION:
XS GIS Cut Line= 3
      2004928.65     13611768.39      2004342.73     13611733.67
      2003240.26     13611720.64
#Sta/Elev= 30
  4406.2  682.22  4407.5  682.22  4560.1  680.73  4600.2  679.51  4670.3  678.54
  4721.2  678.27  4730.4  677.85  4840.6  676.62  4870.7  676.63  4930.8  675.68
  4940.8  675.64  4960.8  678.78  4970.8  675.19  4980.9  672.33  4989.5  671.31
  5006.6  671.00  5007.4  670.20  5014.4  670.20  5015.1  671.00  5020.9  671.97
  5050.9  672.99  5070.9  675.35  5080.9  675.60  5190.9  675.77  5220.9  676.64
  5540.9  680.85  5720.9  682.38  5730.9  683.20  5770.9  683.12  6095.7  685.24
#Mann=4,-1,0
  4406.2    0.08       0  4407.5     0.1       0  5006.6    0.07       0
  5015.1     0.1       0
Bank Sta=5006.6,5015.1
Exp/Cntr=0.3,0.1

Type RM Length L Ch R = 1,13925,45,45,45
BEGIN DESCRIPTION:
Mapping XS 72c5d877
END DESCRIPTION:
XS GIS Cut Line= 4
      2004998.10     13611471.08      2004488.13     13611458.06
      2004327.54     13611455.89      2003598.10     13611460.22
#Sta/Elev= 30
  4430.6  683.48  4492.0  682.39  4543.7  682.28  4593.8  681.51  4643.8  682.10
  4723.8  680.37  4763.8  680.47  4833.8  678.45  4861.8  678.33  4866.8  679.21
  4883.9  679.23  4913.9  677.65  4923.9  676.76  4939.8  674.33  4953.9  673.79
  4963.9  672.61  4999.6  670.65  5000.3  669.85  5007.4  669.85  5008.2  670.65
  5033.9  673.91  5053.9  675.16  5113.9  675.37  5153.9  676.37  5273.9  678.43
  5513.9  681.38  5653.9  682.22  5743.9  681.98  5813.9  682.39  5830.8  682.85
#Mann=4,-1,0
  4430.6    0.08       0  4492.0     0.1       0  4999.6    0.07       0
  5008.2     0.1       0
Bank Sta=4999.6,5008.2
Exp/Cntr=0.3,0.1

Type RM Length L Ch R = 1,13880,322,322,322
BEGIN DESCRIPTION:
Mapping XS 18573a93
END DESCRIPTION:
XS GIS Cut Line= 4
      2004985.13     13611401.63      2004444.72     13611412.49
      2004242.90     13611405.97      2003600.51     13611427.68
#Sta/Elev= 30
  4439.9  682.97  4450.0  681.92  4460.0  682.43  4486.3  682.13  4580.1  681.87
  4680.1  680.81  4690.1  681.19  4720.1  680.01  4740.1  680.46  4900.1  677.00
  4940.1  676.80  4960.1  676.03  4970.1  674.68  4977.8  672.43  4982.8  672.43
  4985.8  671.00  4986.6  670.20  4993.7  670.20  4994.4  671.00  5000.2  671.46
  5010.2  673.34  5030.2  674.55  5050.2  674.10  5070.2  674.79  5110.2  674.87
  5178.8  676.61  5480.4  681.12  5660.5  682.09  5810.6  682.12  5825.1  682.79
#Mann=4,-1,0
  4439.9    0.08       0  4486.3     0.1       0  4985.8    0.07       0
  4994.4     0.1       0
Bank Sta=4985.8,4994.4
Exp/Cntr=0.3,0.1