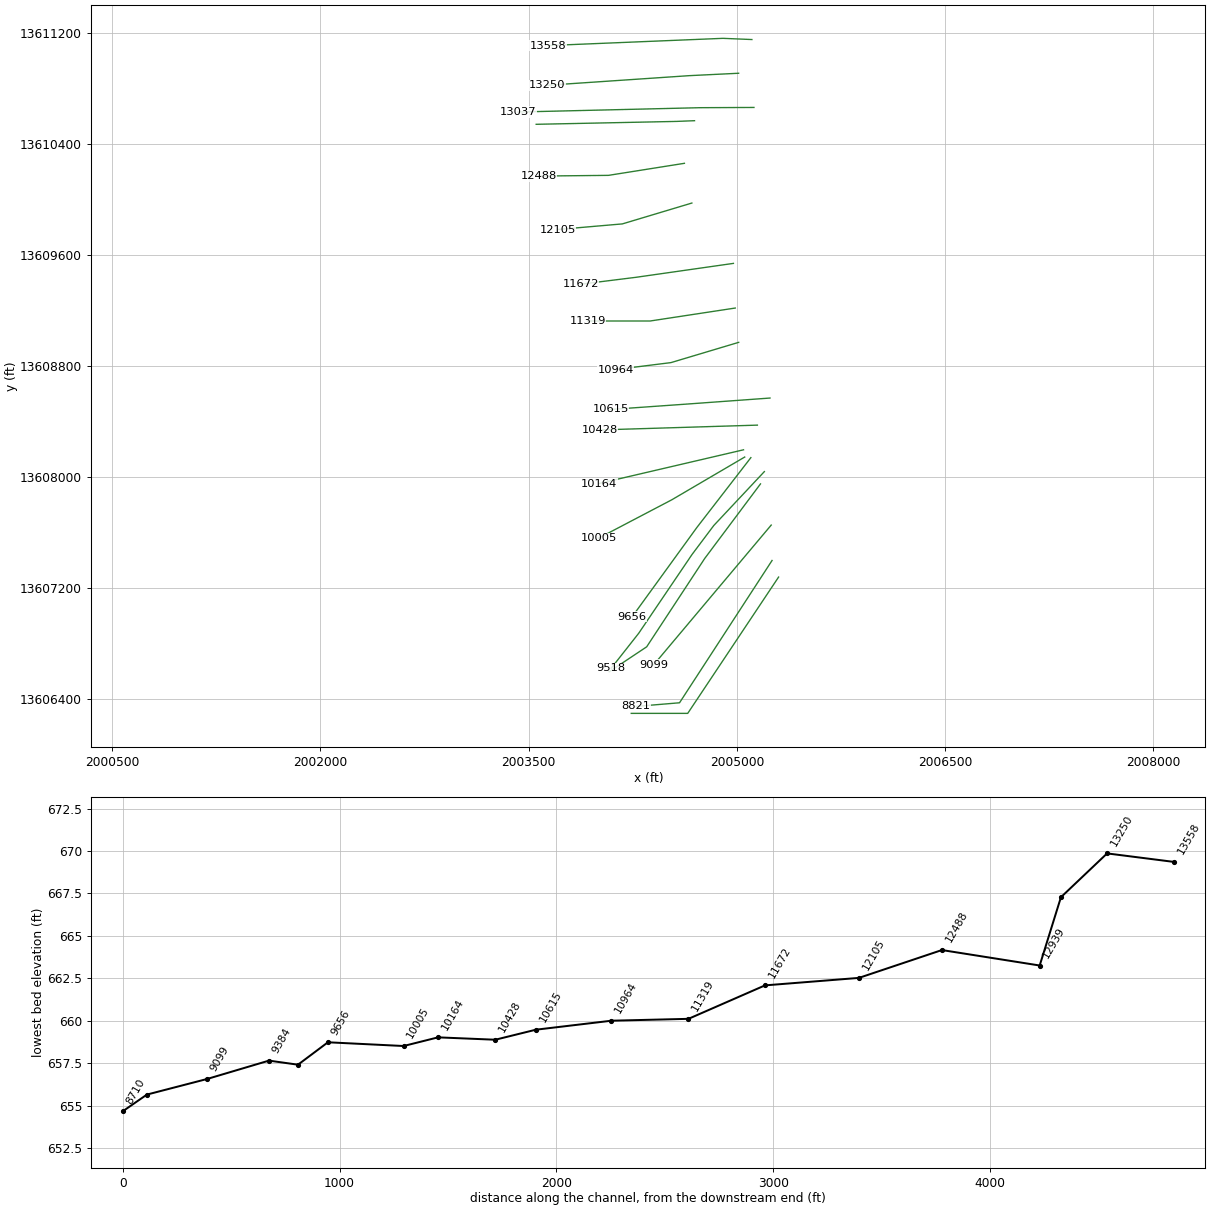
HEC-RAS study UNT 104 in HW.prj: UNT 104 in HW Base Level Engineering

--- UNT 104 in HW.g01 (geometry) --- (continued)

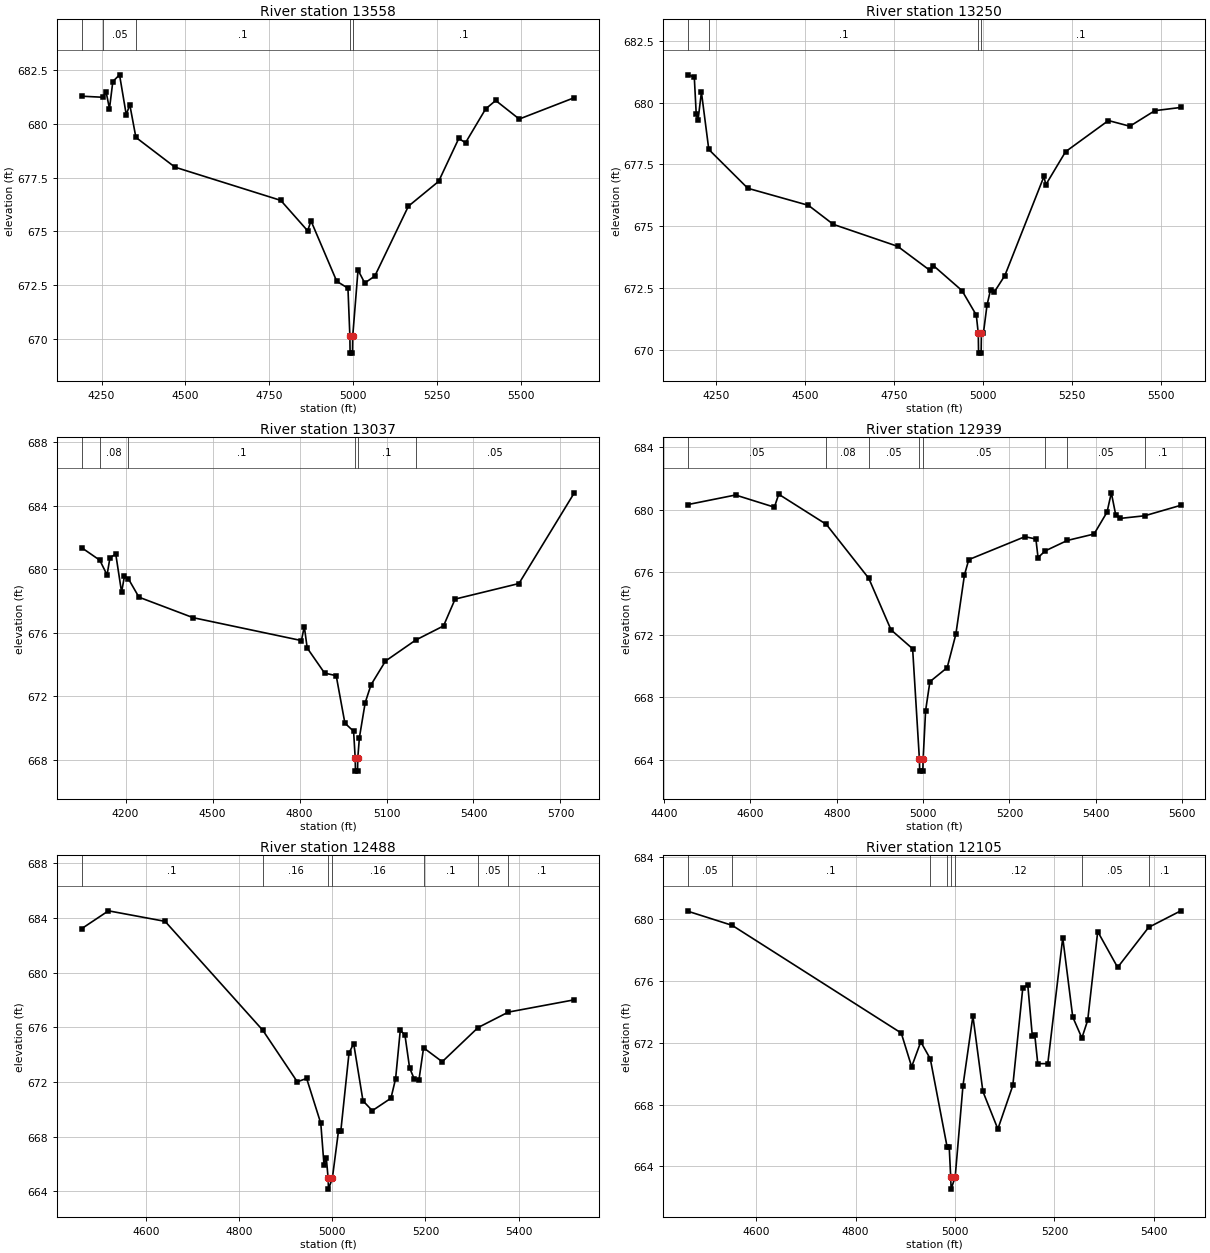
Type RM Length L Ch R = 1,13558,308,308,308
BEGIN DESCRIPTION:
UNT 104 in HW 18.0
END DESCRIPTION:
XS GIS Cut Line= 3
      2005108.08     13611154.20      2004899.73     13611162.88
      2003641.04     13611110.80
#Sta/Elev= 30
  4190.5  681.27  4253.8  681.22  4263.6  681.47  4273.7  680.69  4283.7  681.95
  4303.7  682.26  4323.7  680.41  4334.2  680.88  4352.4  679.36  4468.8  677.98
  4784.1  676.44  4864.2  675.03  4874.2  675.49  4950.9  672.69  4984.3  672.37
  4990.0  670.16  4990.7  669.36  4997.8  669.36  4998.6  670.16  5014.3  673.21
  5034.3  672.61  5064.3  672.93  5164.4  676.17  5254.5  677.32  5314.5  679.31
  5334.6  679.11  5394.6  680.68  5424.6  681.07  5494.7  680.21  5658.8  681.20
#Mann=5,-1,0
  4190.5     0.1       0  4253.8    0.05       0  4352.4     0.1       0
  4990.0    0.07       0  4998.6     0.1       0
Bank Sta=4990,4998.6
Exp/Cntr=0.3,0.1

Type RM Length L Ch R = 1,13250,213,213,213
BEGIN DESCRIPTION:
UNT 104 in HW 17.0
END DESCRIPTION:
XS GIS Cut Line= 3
      2005012.53     13610911.14      2004656.67     13610893.79
      2003632.41     13610824.34
#Sta/Elev= 30
  4171.4  681.12  4189.0  681.03  4194.4  679.54  4199.4  679.28  4209.0  680.42
  4229.7  678.10  4339.1  676.53  4509.3  675.84  4579.1  675.07  4759.9  674.18
  4850.1  673.21  4860.1  673.40  4940.3  672.39  4980.4  671.40  4986.0  670.66
  4986.8  669.86  4994.0  669.86  4994.8  670.66  5000.4  670.67  5010.5  671.80
  5020.5  672.43  5031.3  672.34  5060.6  673.00  5170.4  677.01  5175.4  676.67
  5231.0  678.01  5351.2  679.27  5411.4  679.04  5481.5  679.67  5554.3  679.80
#Mann=4,-1,0
  4171.4    0.08       0  4229.7     0.1       0  4986.0    0.07       0
  4994.8     0.1       0
Bank Sta=4986,4994.8
Exp/Cntr=0.3,0.1

Type RM Length L Ch R = 1,13037,98,98,98
BEGIN DESCRIPTION:
UNT 104 in HW 16.0
END DESCRIPTION:
XS GIS Cut Line= 3
      2005123.04     13610664.58      2004736.54     13610662.88
      2003424.02     13610631.63
#Sta/Elev= 30
  4048.3  681.35  4111.1  680.56  4136.3  679.63  4146.3  680.72  4166.3  680.94
  4186.3  678.55  4196.3  679.55  4209.4  679.40  4246.3  678.23  4433.1  676.94
  4806.5  675.50  4816.5  676.38  4826.5  675.03  4886.5  673.45  4926.5  673.29
  4956.5  670.30  4986.5  669.79  4992.1  668.08  4992.9  667.28  5000.1  667.28
  5000.9  668.08  5006.5  669.39  5026.5  671.59  5046.5  672.71  5096.5  674.21
  5200.7  675.53  5296.6  676.42  5336.6  678.11  5556.7  679.09  5747.7  684.80
#Mann=6,-1,0
  4048.3     0.1       0  4111.1    0.08       0  4209.4     0.1       0
  4992.1    0.07       0  5000.9     0.1       0  5200.7    0.05       0
Bank Sta=4992.1,5000.9
Exp/Cntr=0.3,0.1

Type RM Length L Ch R = 1,12939,451,451,451
BEGIN DESCRIPTION:
UNT 104 in HW 15.0
END DESCRIPTION:
XS GIS Cut Line= 3
      2004694.91     13610569.13      2004564.66     13610563.92
      2003554.23     13610543.09
#Sta/Elev= 30
  4455.7  680.34  4565.7  680.95  4655.7  680.17  4665.7  681.00  4775.9  679.07
  4874.3  675.61  4925.8  672.31  4975.8  671.10  4991.4  664.06  4992.2  663.26
  4999.4  663.26  5000.2  664.06  5005.8  667.13  5015.8  668.99  5055.8  669.89
  5075.8  672.02  5095.8  675.83  5105.8  676.81  5235.8  678.28  5261.2  678.13
  5266.2  676.94  5282.8  677.37  5334.1  678.04  5395.9  678.45  5425.9  679.85
  5435.9  681.09  5445.9  679.70  5455.9  679.45  5513.2  679.62  5596.7  680.29
#Mann=8,-1,0
  4455.7    0.05       0  4775.9    0.08       0  4874.3    0.05       0
  4991.4    0.04       0  5000.2    0.05       0  5282.8     0.1       0
  5334.1    0.05       0  5513.2     0.1       0
Bank Sta=4991.4,5000.2
Exp/Cntr=0.3,0.1

Type RM Length L Ch R = 1,12488,383,383,383
BEGIN DESCRIPTION:
UNT 104 in HW 14.0
END DESCRIPTION:
XS GIS Cut Line= 3
      2004621.95     13610261.84      2004075.00     13610175.00
      2003571.62     13610169.83
#Sta/Elev= 30
  4462.2  683.22  4519.9  684.53  4641.4  683.76  4851.1  675.79  4925.1  672.02
  4945.1  672.27  4975.5  668.98  4982.3  665.97  4987.4  666.42  4991.2  664.97
  4992.0  664.17  5000.3  664.97  5013.5  668.44  5018.5  668.44  5036.0  674.12
  5046.0  674.82  5066.0  670.63  5086.0  669.91  5126.0  670.82  5136.0  672.25
  5146.0  675.79  5156.0  675.45  5166.0  673.04  5176.0  672.23  5186.0  672.14
  5196.0  674.51  5236.0  673.49  5312.9  675.99  5377.8  677.12  5519.4  678.02
#Mann=7,-1,0
  4462.2     0.1       0  4851.1    0.16       0  4991.2    0.07       0
  5000.3    0.16       0  5196.0     0.1       0  5312.9    0.05       0
  5377.8     0.1       0
Bank Sta=4991.2,5000.3
Exp/Cntr=0.3,0.1

Type RM Length L Ch R = 1,12105,433,433,433
BEGIN DESCRIPTION:
UNT 104 in HW 13.0
END DESCRIPTION:
XS GIS Cut Line= 3
      2004675.75     13609975.38      2004175.00     13609825.00
      2003708.50     13609784.54
#Sta/Elev= 30
  4462.9  680.51  4551.7  679.60  4891.8  672.63  4912.7  670.45  4931.0  672.06
  4950.2  670.96  4984.2  665.23  4988.3  665.23  4991.2  663.33  4992.1  662.53
  5000.3  663.33  5015.9  669.22  5035.9  673.73  5056.0  668.85  5086.1  666.42
  5116.2  669.24  5136.3  675.57  5146.3  675.73  5155.4  672.44  5160.4  672.48
  5166.4  670.65  5186.5  670.65  5216.6  678.80  5236.7  673.67  5255.1  672.31
  5266.8  673.46  5286.9  679.20  5327.0  676.88  5389.3  679.47  5454.0  680.54
#Mann=8,-1,0
  4462.9    0.05       0  4551.7     0.1       0  4950.2    0.16       0
  4984.2    0.12       0  4991.2    0.07       0  5000.3    0.12       0
  5255.1    0.05       0  5389.3     0.1       0
Bank Sta=4991.2,5000.3
Exp/Cntr=0.3,0.1

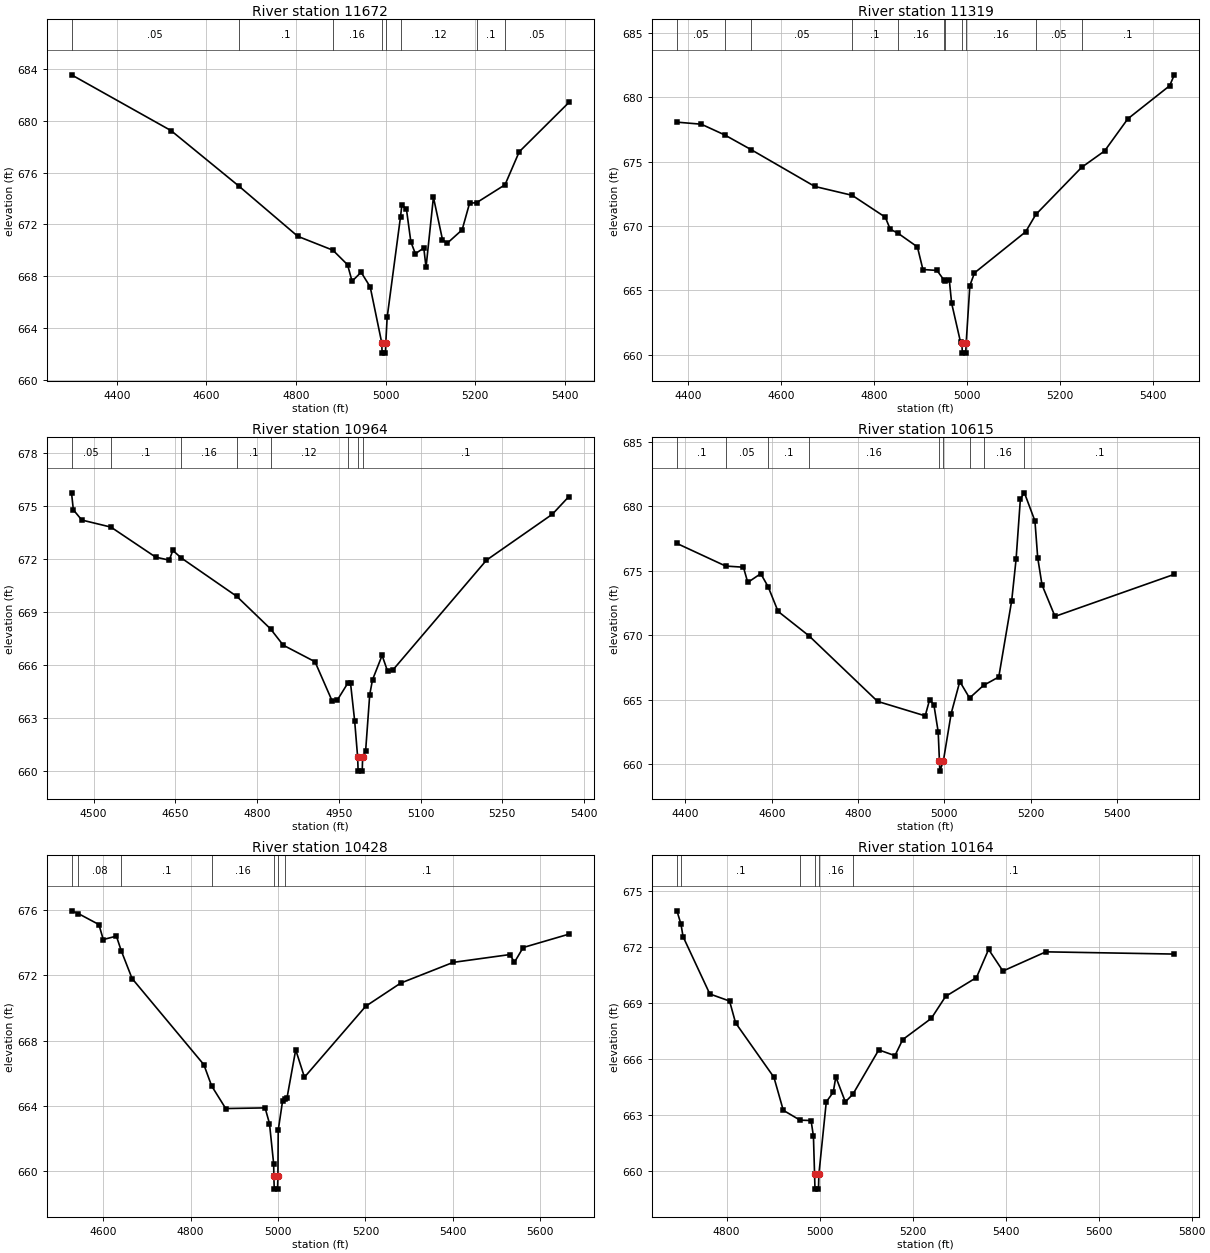
Type RM Length L Ch R = 1,11672,353,353,353
BEGIN DESCRIPTION:
UNT 104 in HW 12.0
END DESCRIPTION:
XS GIS Cut Line= 3
      2004974.95     13609540.27      2004275.00     13609440.28
      2003874.97     13609390.27
#Sta/Elev= 30
  4298.8  683.53  4521.0  679.23  4672.3  674.96  4803.8  671.09  4882.2  670.02
  4914.9  668.90  4925.0  667.63  4945.2  668.32  4965.5  667.19  4991.2  662.89
  4992.1  662.09  4999.5  662.09  5000.3  662.89  5003.3  664.84  5033.2  672.61
  5036.1  673.47  5046.2  673.22  5056.2  670.67  5066.3  669.75  5085.1  670.19
  5090.1  668.70  5106.6  674.10  5126.8  670.84  5136.9  670.54  5170.7  671.59
  5187.3  673.64  5203.0  673.68  5266.4  675.06  5298.1  677.60  5409.0  681.40
#Mann=8,-1,0
  4298.8    0.05       0  4672.3     0.1       0  4882.2    0.16       0
  4991.2    0.07       0  5000.3    0.16       0  5033.2    0.12       0
  5203.0     0.1       0  5266.4    0.05       0
Bank Sta=4991.2,5000.3
Exp/Cntr=0.3,0.1

Type RM Length L Ch R = 1,11319,355,355,355
BEGIN DESCRIPTION:
UNT 104 in HW 11.0
END DESCRIPTION:
XS GIS Cut Line= 3
      2004988.32     13609218.45      2004375.00     13609125.00
      2003925.00     13609125.00
#Sta/Elev= 30
  4375.4  678.08  4427.9  677.92  4478.0  677.09  4534.7  675.95  4672.1  673.08
  4752.6  672.39  4823.8  670.69  4834.4  669.76  4851.7  669.43  4892.9  668.38
  4904.8  666.62  4935.1  666.55  4950.7  665.77  4952.2  665.69  4961.5  665.83
  4966.6  664.00  4985.7  660.98  4988.7  660.92  4989.6  660.12  4997.0  660.12
  4997.9  660.92  5005.8  665.37  5015.8  666.36  5125.8  669.55  5147.8  670.90
  5246.2  674.56  5295.8  675.84  5345.8  678.34  5435.8  680.91  5445.8  681.76
#Mann=11,-1,0
  4375.4    0.05       0  4478.0     0.1       0  4534.7    0.05       0
  4752.6     0.1       0  4851.7    0.16       0  4950.7    0.12       0
  4952.2    0.16       0  4988.7    0.07       0  4997.9    0.16       0
  5147.8    0.05       0  5246.2     0.1       0
Bank Sta=4988.7,4997.9
Exp/Cntr=0.3,0.1

Type RM Length L Ch R = 1,10964,349,349,349
BEGIN DESCRIPTION:
UNT 104 in HW 10.0
END DESCRIPTION:
XS GIS Cut Line= 3
      2005012.97     13608971.03      2004525.00     13608825.00
      2004124.96     13608775.00
#Sta/Elev= 30
  4459.6  675.76  4462.9  674.80  4478.4  674.22  4531.9  673.82  4614.0  672.12
  4638.9  671.95  4645.4  672.50  4661.1  672.07  4762.8  669.90  4824.7  668.06
  4847.9  667.14  4906.3  666.20  4937.6  663.99  4947.2  664.03  4966.3  664.98
  4971.5  664.98  4979.0  662.87  4984.5  660.81  4985.4  660.01  4992.9  660.01
  4993.7  660.81  4999.2  661.17  5006.7  664.34  5011.8  665.18  5029.4  666.56
  5039.5  665.66  5049.6  665.75  5220.9  671.95  5341.8  674.55  5372.1  675.55
#Mann=8,-1,0
  4459.6    0.05       0  4531.9     0.1       0  4661.1    0.16       0
  4762.8     0.1       0  4824.7    0.12       0  4966.3     0.1       0
  4984.5    0.07       0  4993.7     0.1       0
Bank Sta=4984.5,4993.7
Exp/Cntr=0.3,0.1

Type RM Length L Ch R = 1,10615,187,187,187
BEGIN DESCRIPTION:
UNT 104 in HW 9.0
END DESCRIPTION:
XS GIS Cut Line= 3
      2005238.72     13608569.57      2004625.00     13608525.00
      2004089.27     13608487.15
#Sta/Elev= 30
  4380.3  677.11  4493.2  675.36  4534.4  675.27  4544.4  674.09  4574.5  674.77
  4591.6  673.76  4614.6  671.85  4686.5  669.95  4845.2  664.88  4955.5  663.76
  4965.6  664.99  4975.6  664.63  4985.6  662.53  4988.5  660.28  4989.4  659.48
  4997.7  660.28  5015.7  663.94  5035.7  666.42  5058.3  665.14  5090.7  666.12
  5126.0  666.77  5156.0  672.69  5166.1  675.88  5176.1  680.57  5185.4  681.03
  5209.8  678.85  5216.2  676.01  5226.2  673.90  5256.3  671.46  5532.7  674.72
#Mann=9,-1,0
  4380.3     0.1       0  4493.2    0.05       0  4591.6     0.1       0
  4686.5    0.16       0  4988.5    0.07       0  4997.7    0.16       0
  5058.3     0.1       0  5090.7    0.16       0  5185.4     0.1       0
Bank Sta=4988.5,4997.7
Exp/Cntr=0.3,0.1

Type RM Length L Ch R = 1,10428,264,264,264
BEGIN DESCRIPTION:
Mapping XS 6eb3dfc9
END DESCRIPTION:
XS GIS Cut Line= 2
      2005147.58     13608374.26      2004010.41     13608339.53
#Sta/Elev= 30
  4527.7  675.95  4543.3  675.78  4590.3  675.11  4600.3  674.19  4630.3  674.40
  4641.6  673.49  4666.2  671.80  4830.4  666.52  4848.1  665.22  4880.4  663.83
  4970.5  663.87  4980.5  662.91  4990.1  660.43  4990.5  659.69  4991.4  658.89
  4998.9  658.89  4999.8  659.69  5000.5  662.50  5010.5  664.30  5016.1  664.40
  5020.5  664.47  5040.5  667.43  5060.5  665.75  5200.6  670.10  5280.6  671.52
  5400.7  672.79  5530.7  673.27  5540.7  672.79  5560.8  673.70  5665.4  674.52
#Mann=7,-1,0
  4527.7     0.1       0  4543.3    0.08       0  4641.6     0.1       0
  4848.1    0.16       0  4990.5    0.07       0  4999.8    0.16       0
  5016.1     0.1       0
Bank Sta=4990.5,4999.8
Exp/Cntr=0.3,0.1

Type RM Length L Ch R = 1,10164,159,159,159
BEGIN DESCRIPTION:
Mapping XS a8aa8f71
END DESCRIPTION:
XS GIS Cut Line= 2
      2005047.76     13608196.31      2004006.04     13607953.24
#Sta/Elev= 30
  4693.0  673.96  4701.8  673.23  4706.1  672.58  4763.7  669.50  4806.2  669.12
  4819.1  667.95  4901.6  665.03  4921.7  663.26  4957.8  662.73  4981.5  662.71
  4986.6  661.86  4989.0  659.83  4989.9  659.03  4997.4  659.03  4998.3  659.83
  5014.2  663.71  5029.2  664.23  5034.7  665.05  5055.2  663.71  5071.4  664.12
  5127.1  666.50  5161.9  666.19  5178.5  667.05  5240.1  668.19  5270.9  669.37
  5337.2  670.38  5363.3  671.89  5394.1  670.73  5486.5  671.76  5762.7  671.64
#Mann=6,-1,0
  4693.0    0.08       0  4701.8     0.1       0  4957.8    0.16       0
  4989.0    0.07       0  4998.3    0.16       0  5071.4     0.1       0
Bank Sta=4989,4998.3
Exp/Cntr=0.3,0.1

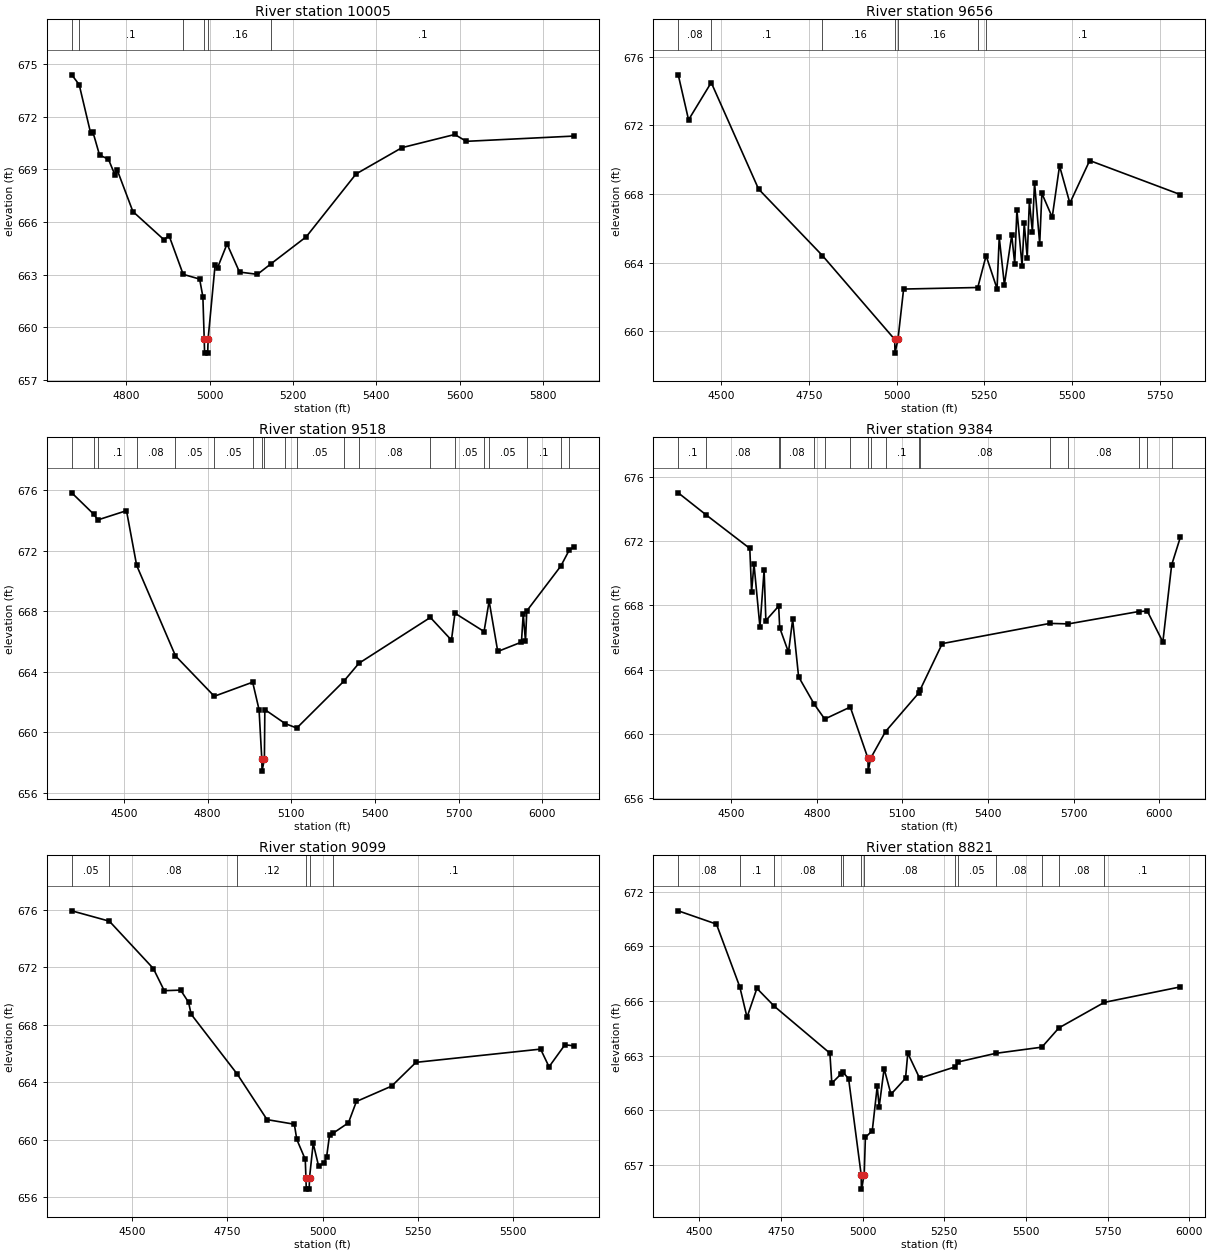
Type RM Length L Ch R = 1,10005,349,349,349
BEGIN DESCRIPTION:
UNT 104 in HW 8.0
END DESCRIPTION:
XS GIS Cut Line= 3
      2005056.45     13608144.24      2004531.24     13607836.06
      2004003.32     13607559.12
#Sta/Elev= 30
  4668.8  674.38  4686.6  673.82  4713.9  671.08  4719.7  671.11  4735.4  669.81
  4756.8  669.57  4772.5  668.67  4778.3  668.93  4815.5  666.59  4889.8  664.99
  4902.4  665.21  4936.2  663.01  4975.7  662.74  4983.5  661.73  4986.7  659.32
  4987.6  658.52  4995.1  658.52  4996.0  659.32  5012.8  663.54  5018.6  663.38
  5041.5  664.74  5071.4  663.14  5114.4  663.01  5146.9  663.61  5231.6  665.15
  5351.1  668.73  5461.4  670.23  5588.1  670.98  5615.8  670.59  5873.9  670.89
#Mann=6,-1,0
  4668.8    0.08       0  4686.6     0.1       0  4936.2    0.16       0
  4986.7    0.07       0  4996.0    0.16       0  5146.9     0.1       0
Bank Sta=4986.7,4996
Exp/Cntr=0.3,0.1

Type RM Length L Ch R = 1,9656,138,138,138
BEGIN DESCRIPTION:
UNT 104 in HW 7.0
END DESCRIPTION:
XS GIS Cut Line= 3
      2005100.66     13608139.84      2004711.80     13607636.41
      2004246.51     13606994.04
#Sta/Elev= 30
  4378.6  674.94  4408.0  672.32  4472.5  674.49  4607.3  668.29  4789.0  664.42
  4994.8  659.54  4995.7  658.74  5004.1  659.54  5020.2  662.47  5231.3  662.56
  5255.0  664.41  5286.2  662.49  5292.4  665.48  5307.1  662.72  5328.0  665.61
  5336.5  663.93  5342.7  667.07  5357.4  663.83  5363.6  666.30  5372.1  664.30
  5378.2  667.58  5386.8  665.81  5392.9  668.67  5407.6  665.10  5413.8  668.04
  5443.2  666.65  5464.1  669.64  5493.5  667.47  5549.9  669.95  5807.9  667.97
#Mann=7,-1,0
  4378.6    0.08       0  4472.5     0.1       0  4789.0    0.16       0
  4994.8    0.07       0  5004.1    0.16       0  5231.3    0.05       0
  5255.0     0.1       0
Bank Sta=4994.8,5004.1
Exp/Cntr=0.3,0.1

Type RM Length L Ch R = 1,9518,134,134,134
BEGIN DESCRIPTION:
Mapping XS 1e7c597f
END DESCRIPTION:
XS GIS Cut Line= 5
      2005197.93     13608039.21      2004833.32     13607650.30
      2004677.07     13607441.96      2004292.33     13606873.07
      2004094.43     13606621.59
#Sta/Elev= 30
  4312.7  675.82  4391.2  674.41  4406.3  674.03  4508.9  674.64  4545.4  671.02
  4684.6  665.04  4823.8  662.37  4961.3  663.30  4984.2  661.49  4994.1  658.22
  4994.9  657.42  5003.4  658.22  5005.0  661.49  5078.1  660.56  5119.6  660.27
  5287.4  663.35  5342.3  664.55  5598.5  667.58  5674.1  666.08  5686.8  667.86
  5791.0  666.65  5809.2  668.66  5840.2  665.33  5925.1  665.95  5931.5  667.80
  5939.6  666.02  5944.2  668.01  6066.4  670.98  6097.2  672.06  6113.0  672.22
#Mann=20,-1,0
  4312.7     0.1       0  4391.2    0.08       0  4406.3     0.1       0
  4545.4    0.08       0  4684.6    0.05       0  4823.8    0.05       0
  4961.3    0.05       0  4994.1    0.04       0  5003.4    0.05       0
  5078.1    0.08       0  5119.6    0.05       0  5287.4     0.1       0
  5342.3    0.08       0  5598.5     0.1       0  5686.8    0.05       0
  5791.0     0.1       0  5809.2    0.05       0  5944.2     0.1       0
  6066.4    0.05       0  6097.2     0.1       0
Bank Sta=4994.1,5003.4
Exp/Cntr=0.3,0.1

Type RM Length L Ch R = 1,9384,285,285,285
BEGIN DESCRIPTION:
UNT 104 in HW 6.0
END DESCRIPTION:
XS GIS Cut Line= 4
      2005170.13     13607950.65      2004769.09     13607414.19
      2004350.10     13606775.96      2004079.66     13606595.84
#Sta/Elev= 30
  4315.1  675.03  4413.7  673.64  4565.7  671.56  4572.0  668.85  4580.3  670.60
  4601.2  666.66  4615.8  670.20  4622.0  667.06  4666.8  667.96  4670.4  666.61
  4701.2  665.08  4715.8  667.13  4736.6  663.55  4791.6  661.83  4828.1  660.91
  4917.6  661.66  4979.4  658.46  4980.3  657.66  4988.8  658.46  5041.0  660.13
  5157.0  662.53  5161.3  662.70  5239.7  665.62  5616.6  666.88  5681.5  666.85
  5927.2  667.62  5957.7  667.65  6012.2  665.72  6043.0  670.53  6073.3  672.25
#Mann=17,-1,0
  4315.1     0.1       0  4413.7    0.08       0  4666.8    0.12       0
  4670.4    0.08       0  4791.6    0.12       0  4828.1     0.1       0
  4917.6    0.12       0  4979.4    0.07       0  4988.8    0.12       0
  5041.0     0.1       0  5157.0    0.05       0  5161.3    0.08       0
  5616.6     0.1       0  5681.5    0.08       0  5927.2     0.1       0
  5957.7    0.05       0  6043.0     0.1       0
Bank Sta=4979.4,4988.8
Exp/Cntr=0.3,0.1

Type RM Length L Ch R = 1,9099,278,278,278
BEGIN DESCRIPTION:
Mapping XS d4e854d0
END DESCRIPTION:
XS GIS Cut Line= 2
      2005247.38     13607653.76      2004401.02     13606646.81
#Sta/Elev= 30
  4342.9  675.92  4441.4  675.20  4556.6  671.91  4585.2  670.37  4628.1  670.41
  4649.0  669.56  4655.5  668.74  4776.8  664.56  4854.5  661.41  4926.0  661.09
  4932.5  660.03  4954.6  658.65  4956.4  657.38  4957.3  656.58  4964.9  656.58
  4965.8  657.38  4975.4  659.76  4989.8  658.16  5004.1  658.42  5010.6  658.83
  5018.4  660.36  5026.6  660.45  5067.8  661.19  5088.6  662.67  5181.0  663.74
  5244.7  665.39  5571.2  666.31  5593.3  665.08  5634.9  666.61  5658.3  666.54
#Mann=6,-1,0
  4342.9    0.05       0  4441.4    0.08       0  4776.8    0.12       0
  4956.4    0.07       0  4965.8    0.12       0  5026.6     0.1       0
Bank Sta=4956.4,4965.8
Exp/Cntr=0.3,0.1

Type RM Length L Ch R = 1,8821,111,111,111
BEGIN DESCRIPTION:
UNT 104 in HW 5.0
END DESCRIPTION:
XS GIS Cut Line= 3
      2005253.44     13607398.53      2004586.80     13606372.52
      2004274.25     13606346.47
#Sta/Elev= 30
  4435.4  670.95  4552.4  670.22  4623.9  666.77  4646.0  665.10  4676.2  666.69
  4730.0  665.70  4899.7  663.13  4905.6  661.48  4933.5  661.98  4939.1  662.09
  4957.0  661.73  4995.4  656.46  4996.3  655.66  5004.8  656.46  5008.4  658.50
  5029.5  658.87  5044.6  661.30  5050.6  660.18  5065.7  662.28  5086.8  660.87
  5131.3  661.75  5138.2  663.13  5174.5  661.75  5283.7  662.38  5293.4  662.65
  5407.2  663.12  5548.8  663.46  5601.0  664.52  5739.9  665.92  5972.6  666.77
#Mann=13,-1,0
  4435.4    0.08       0  4623.9     0.1       0  4730.0    0.08       0
  4933.5     0.1       0  4939.1    0.08       0  4995.4    0.07       0
  5004.8    0.08       0  5283.7     0.1       0  5293.4    0.05       0
  5407.2    0.08       0  5548.8    0.05       0  5601.0    0.08       0
  5739.9     0.1       0
Bank Sta=4995.4,5004.8
Exp/Cntr=0.3,0.1

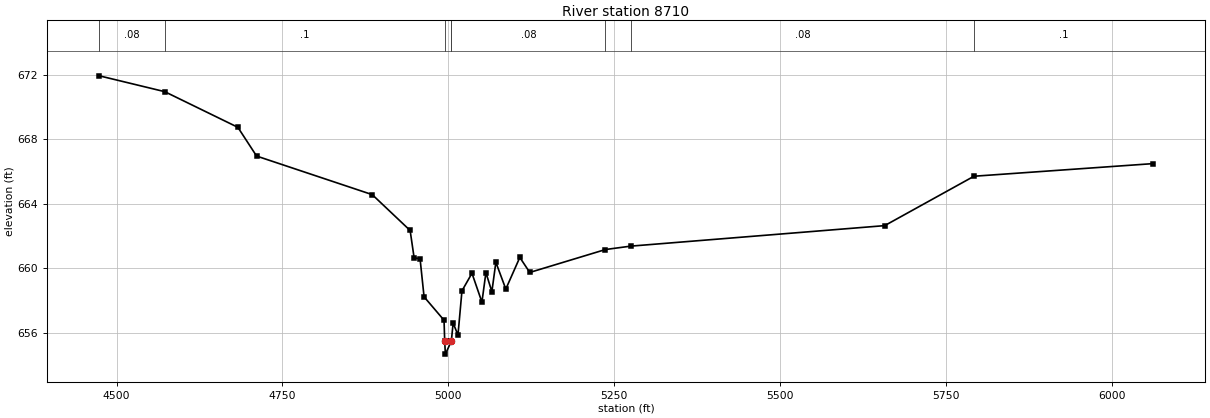
Type RM Length L Ch R = 1,8710,528,528,528
BEGIN DESCRIPTION:
UNT 104 in HW 4.0
END DESCRIPTION:
XS GIS Cut Line= 3
      2005300.36     13607278.80      2004645.82     13606296.13
      2004238.92     13606296.13
#Sta/Elev= 30
  4474.1  671.92  4572.6  670.94  4682.9  668.73  4711.1  666.95  4885.4  664.56
  4942.5  662.34  4948.5  660.65  4957.5  660.58  4963.5  658.23  4993.6  656.78
  4994.6  655.48  4995.6  654.68  5004.6  655.48  5004.7  655.52  5007.3  656.61
  5014.6  655.86  5020.6  658.60  5035.7  659.69  5050.7  657.90  5056.7  659.73
  5065.7  658.55  5071.7  660.37  5086.7  658.71  5107.8  660.67  5122.8  659.74
  5236.9  661.16  5275.0  661.37  5657.7  662.64  5792.3  665.70  6061.7  666.48
#Mann=8,-1,0
  4474.1    0.08       0  4572.6     0.1       0  4994.6    0.07       0
  5004.6     0.1       0  5004.7    0.08       0  5236.9    0.05       0
  5275.0    0.08       0  5792.3     0.1       0
Bank Sta=4994.6,5004.6
Exp/Cntr=0.3,0.1