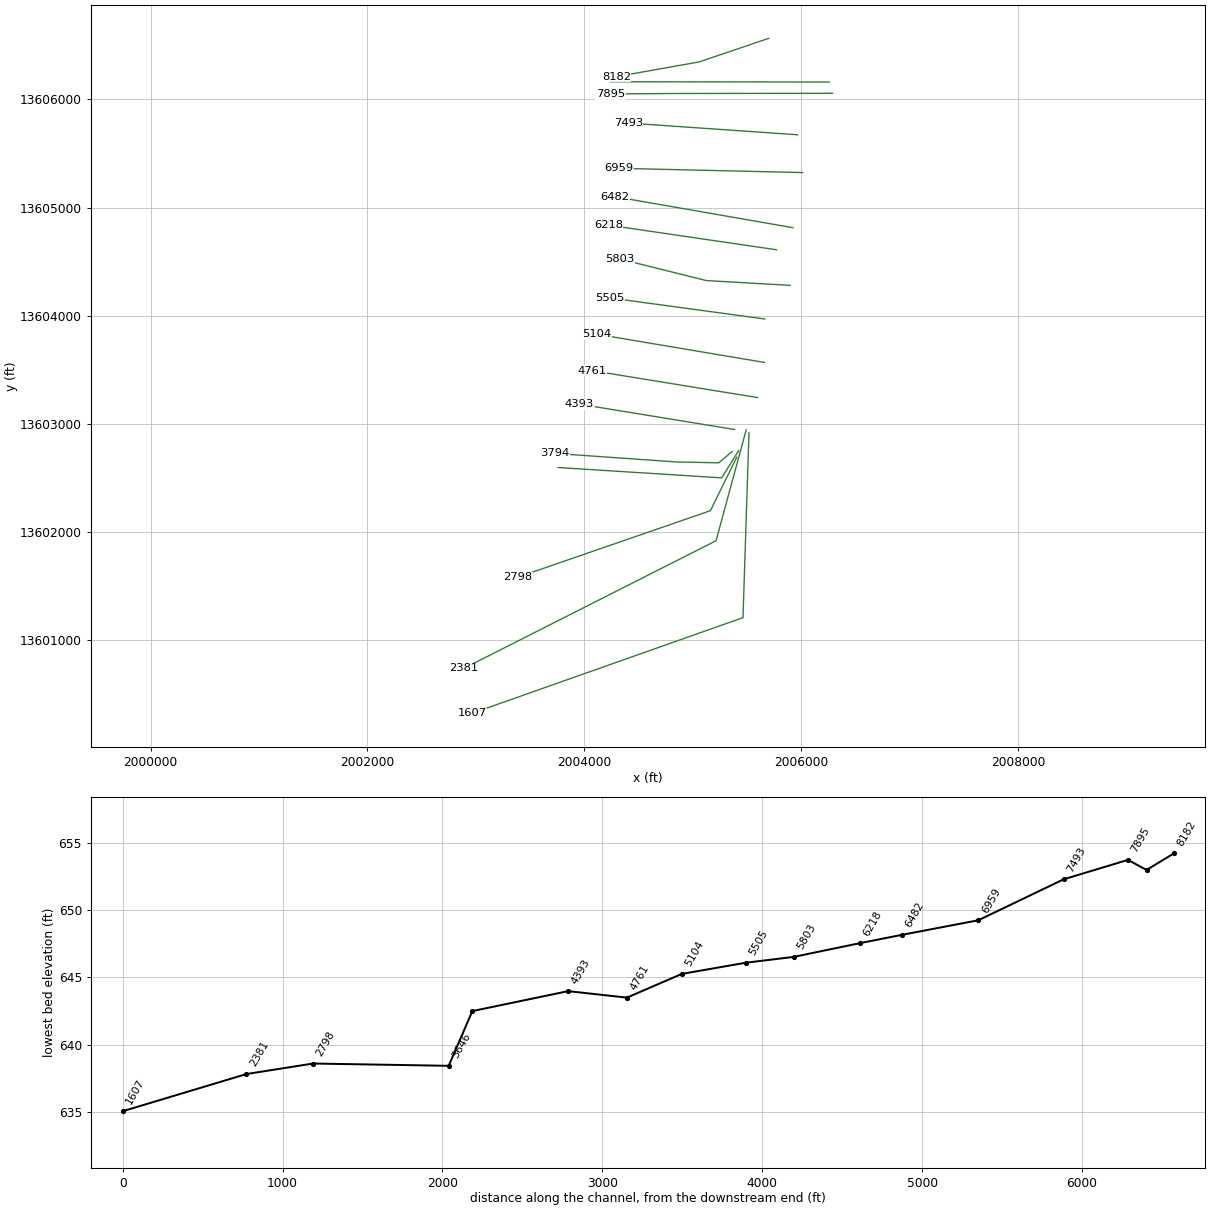
HEC-RAS study UNT 104 in HW.prj: UNT 104 in HW Base Level Engineering

--- UNT 104 in HW.g01 (geometry) --- (continued)

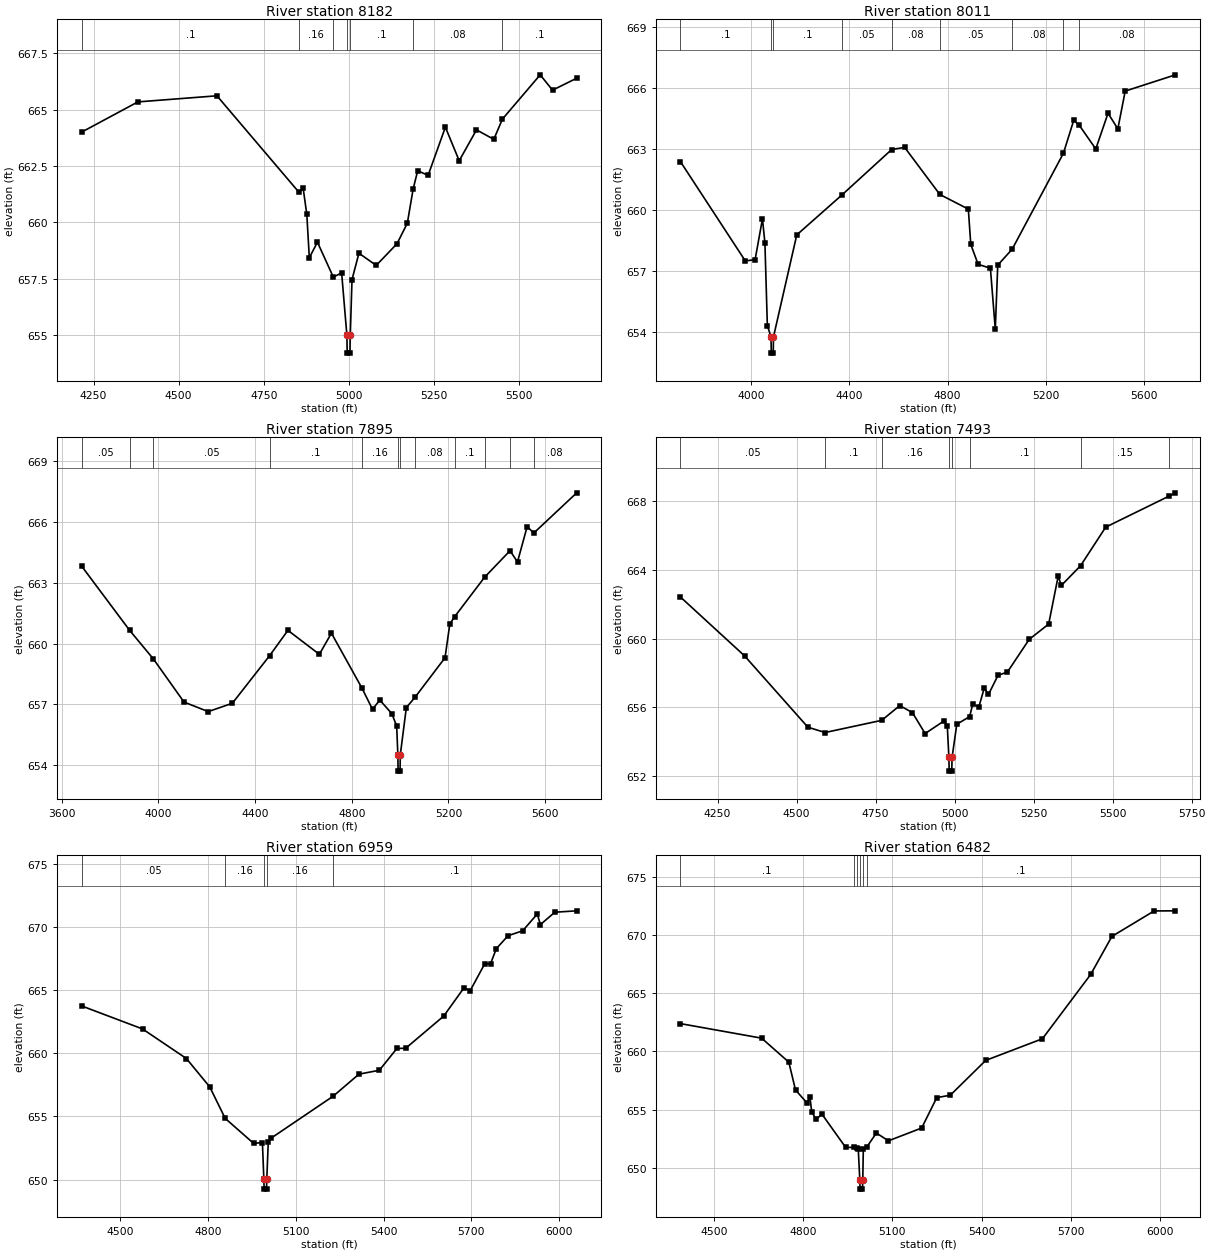
Type RM Length L Ch R = 1,8182,171,171,171
BEGIN DESCRIPTION:
Mapping XS 318d553e
END DESCRIPTION:
XS GIS Cut Line= 3
      2005701.43     13606565.24      2005055.55     13606346.48
      2004295.13     13606211.06
#Sta/Elev= 30
  4215.1  664.00  4380.3  665.34  4612.5  665.61  4853.6  661.33  4865.9  661.50
  4876.5  660.35  4883.9  658.43  4907.7  659.12  4954.4  657.57  4978.8  657.76
  4994.2  655.00  4995.2  654.20  5003.2  654.20  5004.2  655.00  5009.3  657.46
  5029.6  658.63  5080.4  658.09  5141.4  659.05  5171.8  659.96  5188.9  661.48
  5202.3  662.29  5232.8  662.08  5283.6  664.22  5324.2  662.73  5375.0  664.10
  5425.8  663.68  5451.3  664.58  5562.1  666.54  5598.4  665.86  5669.4  666.39
#Mann=7,-1,0
  4215.1     0.1       0  4853.6    0.16       0  4954.4     0.1       0
  4994.2    0.07       0  5004.2     0.1       0  5188.9    0.08       0
  5451.3     0.1       0
Bank Sta=4994.2,5004.2
Exp/Cntr=0.3,0.1

Type RM Length L Ch R = 1,8011,116,116,116
BEGIN DESCRIPTION:
Mapping XS 4a92b4ac
END DESCRIPTION:
XS GIS Cut Line= 2
      2006259.81     13606161.10      2004240.01     13606163.75
#Sta/Elev= 30
  3710.1  662.40  3974.9  657.51  4014.9  657.57  4044.9  659.58  4054.9  658.40
  4064.9  654.32  4079.9  653.77  4080.9  652.97  4088.9  652.97  4089.9  653.77
  4184.9  658.79  4368.6  660.75  4571.9  662.99  4624.9  663.10  4768.7  660.78
  4884.9  660.06  4894.9  658.32  4924.9  657.34  4974.9  657.15  4994.9  654.15
  5004.9  657.30  5063.9  658.09  5272.9  662.81  5314.9  664.43  5336.7  664.20
  5404.9  663.02  5454.9  664.78  5494.9  664.01  5524.9  665.87  5729.9  666.67
#Mann=9,-1,0
  3710.1     0.1       0  4079.9    0.04       0  4089.9     0.1       0
  4368.6    0.05       0  4571.9    0.08       0  4768.7    0.05       0
  5063.9    0.08       0  5272.9     0.1       0  5336.7    0.08       0
Bank Sta=4079.9,4089.9
Exp/Cntr=0.3,0.1

Type RM Length L Ch R = 1,7895,402,402,402
BEGIN DESCRIPTION:
UNT 104 in HW 3.0
END DESCRIPTION:
XS GIS Cut Line= 3
      2006288.50     13606056.94      2004821.60     13606055.24
      2004240.01     13606050.90
#Sta/Elev= 30
  3682.3  663.81  3880.8  660.65  3979.2  659.24  4105.8  657.12  4205.8  656.65
  4305.8  657.06  4459.8  659.40  4535.8  660.65  4665.8  659.47  4715.8  660.51
  4842.9  657.79  4885.8  656.76  4915.8  657.22  4965.8  656.55  4985.8  655.94
  4990.7  654.52  4991.7  653.72  4999.8  653.72  5000.8  654.52  5025.8  656.85
  5061.4  657.35  5185.8  659.30  5205.8  660.97  5226.2  661.33  5349.3  663.26
  5454.8  664.57  5485.8  664.02  5525.8  665.76  5553.2  665.44  5730.8  667.42
#Mann=12,-1,0
  3682.3    0.05       0  3880.8    0.08       0  3979.2    0.05       0
  4459.8     0.1       0  4842.9    0.16       0  4990.7    0.07       0
  5000.8    0.16       0  5061.4    0.08       0  5226.2     0.1       0
  5349.3    0.15       0  5454.8     0.1       0  5553.2    0.08       0
Bank Sta=4990.7,5000.8
Exp/Cntr=0.3,0.1

Type RM Length L Ch R = 1,7493,534,534,534
BEGIN DESCRIPTION:
Mapping XS 8a415cba
END DESCRIPTION:
XS GIS Cut Line= 2
      2005967.45     13605673.30      2004404.91     13605781.81
#Sta/Elev= 30
  4132.4  662.43  4335.3  659.00  4535.8  654.84  4590.2  654.53  4769.3  655.24
  4826.5  656.10  4866.6  655.69  4906.7  654.47  4966.9  655.21  4976.9  654.90
  4981.9  653.08  4982.8  652.28  4991.0  652.28  4992.0  653.08  5006.9  655.01
  5047.6  655.46  5057.1  656.17  5077.1  656.04  5093.7  657.12  5107.2  656.75
  5137.3  657.86  5167.3  658.06  5236.0  659.96  5297.6  660.85  5327.7  663.64
  5337.7  663.10  5398.5  664.25  5478.1  666.50  5677.5  668.30  5698.7  668.50
#Mann=8,-1,0
  4132.4    0.05       0  4590.2     0.1       0  4769.3    0.16       0
  4981.9    0.07       0  4992.0    0.16       0  5047.6     0.1       0
  5398.5    0.15       0  5677.5     0.1       0
Bank Sta=4981.9,4992
Exp/Cntr=0.3,0.1

Type RM Length L Ch R = 1,6959,477,477,477
BEGIN DESCRIPTION:
Mapping XS 8eee346e
END DESCRIPTION:
XS GIS Cut Line= 2
      2006013.03     13605323.91      2004320.28     13605362.97
#Sta/Elev= 30
  4367.6  663.74  4575.7  661.92  4725.7  659.58  4805.7  657.33  4858.5  654.84
  4955.8  652.86  4985.8  652.93  4990.7  650.04  4991.7  649.24  4999.9  649.24
  5000.8  650.04  5005.8  652.96  5015.8  653.28  5228.0  656.60  5315.9  658.34
  5385.9  658.65  5445.9  660.38  5475.9  660.39  5606.0  662.94  5676.0  665.20
  5696.0  664.93  5746.0  667.07  5766.0  667.08  5786.0  668.28  5826.0  669.30
  5876.0  669.69  5926.0  671.02  5936.5  670.18  5986.1  671.16  6060.8  671.27
#Mann=5,-1,0
  4367.6    0.05       0  4858.5    0.16       0  4990.7    0.07       0
  5000.8    0.16       0  5228.0     0.1       0
Bank Sta=4990.7,5000.8
Exp/Cntr=0.3,0.1

Type RM Length L Ch R = 1,6482,264,264,264
BEGIN DESCRIPTION:
Mapping XS 1d1add63
END DESCRIPTION:
XS GIS Cut Line= 2
      2005924.07     13604813.92      2004284.48     13605100.20
#Sta/Elev= 30
  4387.6  662.38  4660.7  661.13  4752.1  659.07  4774.6  656.68  4813.0  655.57
  4823.2  656.05  4829.1  654.80  4843.5  654.17  4863.8  654.59  4943.1  651.75
  4970.5  651.74  4981.9  651.66  4985.6  651.64  4990.7  648.96  4991.6  648.16
  4999.8  648.16  5000.8  648.96  5002.6  651.64  5014.6  651.79  5046.5  652.98
  5087.1  652.31  5198.8  653.41  5249.5  656.02  5295.1  656.23  5414.2  659.22
  5604.8  661.08  5767.2  666.61  5838.3  669.87  5980.4  672.06  6052.0  672.07
#Mann=6,-1,0
  4387.6     0.1       0  4970.5    0.16       0  4981.9    0.12       0
  4990.7    0.07       0  5000.8    0.12       0  5014.6     0.1       0
Bank Sta=4990.7,5000.8
Exp/Cntr=0.3,0.1

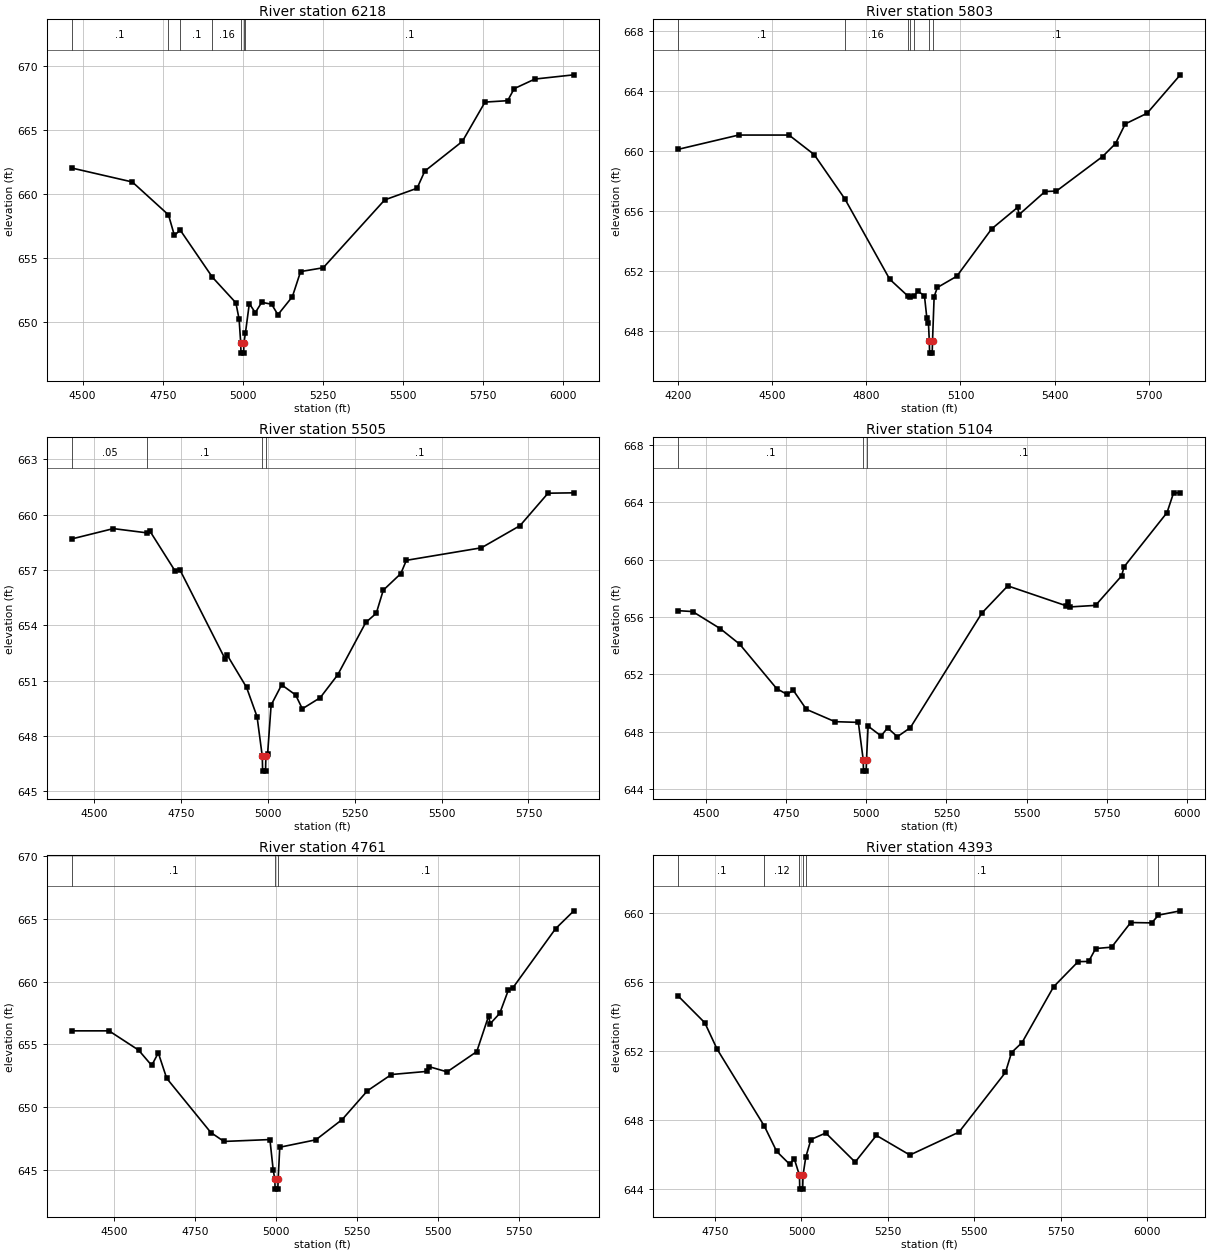
Type RM Length L Ch R = 1,6218,415,415,415
BEGIN DESCRIPTION:
Mapping XS 901ee46b
END DESCRIPTION:
XS GIS Cut Line= 2
      2005772.12     13604609.93      2004220.46     13604837.80
#Sta/Elev= 30
  4466.0  662.00  4655.1  660.91  4768.1  658.34  4786.5  656.74  4804.8  657.15
  4905.3  653.47  4978.6  651.47  4988.7  650.19  4993.7  648.34  4994.7  647.54
  5002.9  647.54  5003.8  648.34  5008.6  649.14  5020.6  651.41  5039.2  650.70
  5059.4  651.51  5090.3  651.36  5109.9  650.54  5155.1  651.95  5180.7  653.91
  5251.5  654.21  5443.5  659.51  5544.6  660.42  5568.7  661.76  5686.1  664.08
  5756.8  667.15  5827.6  667.26  5847.9  668.20  5912.6  668.95  6034.3  669.28
#Mann=7,-1,0
  4466.0     0.1       0  4768.1    0.16       0  4804.8     0.1       0
  4905.3    0.16       0  4993.7    0.07       0  5003.8    0.16       0
  5008.6     0.1       0
Bank Sta=4993.7,5003.8
Exp/Cntr=0.3,0.1

Type RM Length L Ch R = 1,5803,298,298,298
BEGIN DESCRIPTION:
UNT 104 in HW 2.0
END DESCRIPTION:
XS GIS Cut Line= 3
      2005896.88     13604280.70      2005125.00     13604325.00
      2004324.98     13604525.01
#Sta/Elev= 30
  4201.9  660.09  4394.1  661.04  4554.4  661.04  4634.5  659.74  4732.4  656.78
  4874.9  651.44  4932.3  650.33  4940.8  650.28  4950.9  650.32  4965.0  650.63
  4985.4  650.35  4993.1  648.85  4998.2  648.51  5000.9  647.32  5001.9  646.52
  5010.1  646.52  5011.1  647.32  5016.3  650.29  5026.6  650.89  5088.4  651.64
  5199.2  654.79  5281.7  656.22  5286.9  655.75  5369.3  657.28  5405.4  657.31
  5552.3  659.61  5593.5  660.47  5624.4  661.78  5694.0  662.49  5799.7  665.05
#Mann=7,-1,0
  4201.9     0.1       0  4732.4    0.16       0  4932.3     0.1       0
  4940.8    0.16       0  4950.9     0.1       0  5000.9    0.07       0
  5011.1     0.1       0
Bank Sta=5000.9,5011.1
Exp/Cntr=0.3,0.1

Type RM Length L Ch R = 1,5505,401,401,401
BEGIN DESCRIPTION:
Mapping XS cf577cfd
END DESCRIPTION:
XS GIS Cut Line= 2
      2005663.62     13603969.74      2004231.37     13604165.05
#Sta/Elev= 30
  4435.1  658.68  4554.8  659.24  4651.3  659.01  4659.9  659.11  4732.3  656.95
  4746.6  657.00  4876.9  652.16  4882.0  652.40  4938.3  650.63  4968.6  649.04
  4983.6  646.89  4984.6  646.09  4993.0  646.09  4993.9  646.89  4998.9  647.02
  5009.0  649.67  5039.3  650.77  5079.6  650.22  5098.9  649.47  5150.3  650.07
  5200.7  651.31  5281.5  654.15  5311.8  654.65  5331.9  655.90  5382.4  656.80
  5398.4  657.52  5614.5  658.20  5725.6  659.40  5806.3  661.16  5880.6  661.18
#Mann=4,-1,0
  4435.1    0.05       0  4651.3     0.1       0  4983.6    0.07       0
  4993.9     0.1       0
Bank Sta=4983.6,4993.9
Exp/Cntr=0.3,0.1

Type RM Length L Ch R = 1,5104,343,343,343
BEGIN DESCRIPTION:
Mapping XS 365fdaf2
END DESCRIPTION:
XS GIS Cut Line= 2
      2005659.31     13603568.26      2004114.11     13603828.69
#Sta/Elev= 30
  4412.9  656.45  4457.8  656.39  4543.9  655.20  4604.4  654.12  4720.3  651.01
  4751.9  650.62  4772.2  650.89  4812.8  649.57  4901.9  648.71  4975.0  648.66
  4990.2  646.06  4991.1  645.26  4999.5  645.26  5000.5  646.06  5005.5  648.40
  5046.0  647.71  5066.3  648.28  5096.7  647.66  5137.3  648.29  5360.4  656.28
  5441.4  658.18  5622.9  656.80  5628.0  657.09  5634.2  656.71  5715.3  656.82
  5796.5  658.87  5804.4  659.51  5938.4  663.29  5958.7  664.66  5979.9  664.67
#Mann=3,-1,0
  4412.9     0.1       0  4990.2    0.07       0  5000.5     0.1       0
Bank Sta=4990.2,5000.5
Exp/Cntr=0.3,0.1

Type RM Length L Ch R = 1,4761,368,368,368
BEGIN DESCRIPTION:
Mapping XS 79d5569f
END DESCRIPTION:
XS GIS Cut Line= 2
      2005598.49     13603242.75      2004069.30     13603492.19
#Sta/Elev= 30
  4370.0  656.08  4485.0  656.08  4576.2  654.55  4616.7  653.33  4637.0  654.33
  4662.9  652.31  4799.1  648.00  4839.6  647.29  4981.5  647.44  4991.6  645.02
  4996.6  644.30  4997.5  643.50  5005.9  643.50  5006.9  644.30  5011.9  646.83
  5123.3  647.42  5204.4  649.03  5282.5  651.32  5356.4  652.61  5466.9  652.86
  5471.9  653.24  5528.3  652.82  5619.8  654.43  5656.3  657.26  5661.4  656.65
  5690.7  657.47  5717.7  659.35  5731.2  659.50  5863.0  664.20  5919.4  665.62
#Mann=3,-1,0
  4370.0     0.1       0  4996.6    0.07       0  5006.9     0.1       0
Bank Sta=4996.6,5006.9
Exp/Cntr=0.3,0.1

Type RM Length L Ch R = 1,4393,599,599,599
BEGIN DESCRIPTION:
Mapping XS bfe81d94
END DESCRIPTION:
XS GIS Cut Line= 2
      2005385.86     13602947.60      2003953.51     13603181.99
#Sta/Elev= 30
  4643.8  655.19  4720.6  653.64  4756.1  652.11  4893.0  647.63  4928.4  646.17
  4966.1  645.42  4979.1  645.75  4994.2  644.78  4995.1  643.98  5003.5  643.98
  5004.5  644.78  5012.4  645.83  5027.4  646.86  5070.3  647.24  5155.2  645.55
  5216.6  647.10  5313.4  645.96  5455.3  647.29  5589.8  650.76  5607.3  651.91
  5637.7  652.49  5728.9  655.73  5799.8  657.19  5830.2  657.20  5850.5  657.95
  5896.6  658.03  5951.8  659.46  6012.6  659.44  6032.0  659.89  6095.2  660.14
#Mann=6,-1,0
  4643.8     0.1       0  4893.0    0.12       0  4994.2    0.07       0
  5004.5    0.12       0  5012.4     0.1       0  6032.0    0.16       0
Bank Sta=4994.2,5004.5
Exp/Cntr=0.3,0.1

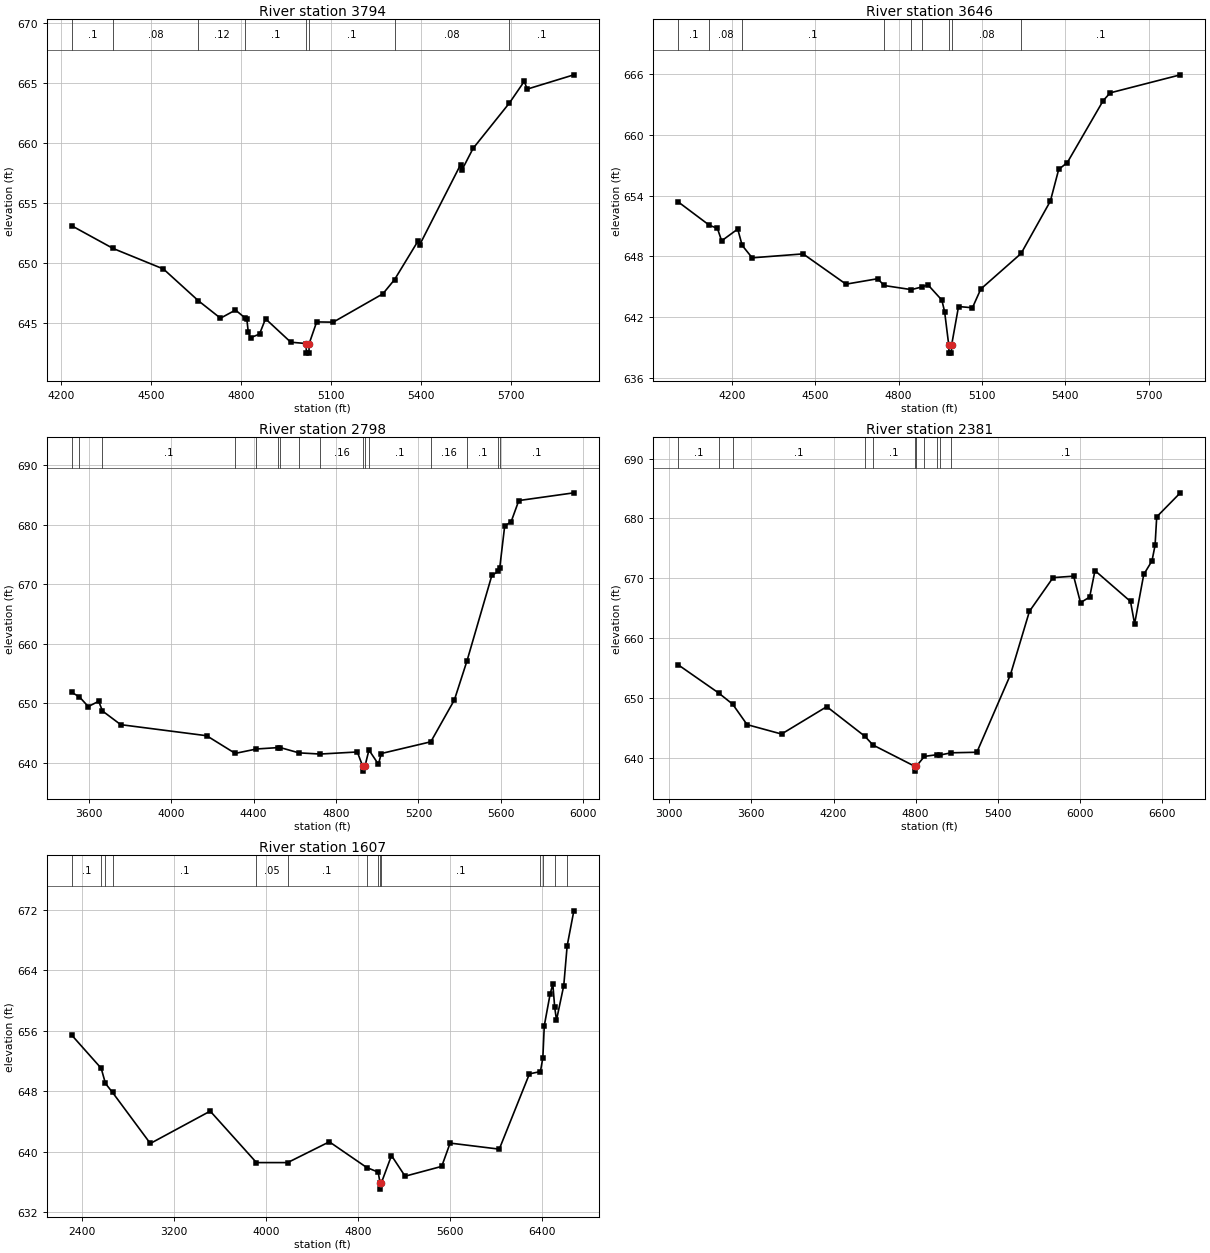
Type RM Length L Ch R = 1,3794,148,148,148
BEGIN DESCRIPTION:
Mapping XS b080af01
END DESCRIPTION:
XS GIS Cut Line= 4
      2005361.95     13602743.59      2005240.44     13602639.45
      2004841.14     13602648.13      2003730.01     13602726.25
#Sta/Elev= 30
  4235.4  653.11  4373.3  651.22  4540.9  649.51  4657.1  646.87  4731.0  645.41
  4781.0  646.09  4812.1  645.45  4818.8  645.34  4823.8  644.22  4831.1  643.78
  4861.1  644.09  4881.2  645.36  4965.3  643.41  5016.4  643.30  5017.3  642.50
  5025.8  642.50  5026.7  643.30  5051.6  645.10  5106.7  645.08  5272.1  647.44
  5311.0  648.62  5389.6  651.85  5394.6  651.51  5531.1  658.20  5536.1  657.78
  5572.9  659.56  5693.9  663.34  5743.3  665.14  5753.3  664.50  5908.7  665.69
#Mann=8,-1,0
  4235.4     0.1       0  4373.3    0.08       0  4657.1    0.12       0
  4812.1     0.1       0  5016.4    0.07       0  5026.7     0.1       0
  5311.0    0.08       0  5693.9     0.1       0
Bank Sta=5016.4,5026.7
Exp/Cntr=0.3,0.1

Type RM Length L Ch R = 1,3646,848,848,848
BEGIN DESCRIPTION:
Mapping XS c77fa0ba
END DESCRIPTION:
XS GIS Cut Line= 3
      2005422.75     13602752.33      2005266.48     13602500.56
      2003758.02     13602595.92
#Sta/Elev= 30
  4006.6  653.37  4118.5  651.07  4147.6  650.76  4162.9  649.53  4220.8  650.69
  4236.8  649.08  4272.8  647.85  4456.2  648.24  4610.6  645.25  4725.3  645.79
  4747.2  645.12  4846.0  644.71  4886.1  644.99  4905.6  645.19  4955.7  643.68
  4965.7  642.54  4980.6  639.24  4981.5  638.44  4990.1  638.44  4991.0  639.24
  5015.8  643.04  5065.9  642.92  5096.0  644.77  5241.1  648.28  5346.5  653.45
  5376.5  656.58  5407.6  657.26  5536.9  663.38  5562.0  664.14  5814.4  665.92
#Mann=9,-1,0
  4006.6     0.1       0  4118.5    0.08       0  4236.8     0.1       0
  4747.2    0.07       0  4846.0    0.12       0  4886.1    0.08       0
  4980.6    0.07       0  4991.0    0.08       0  5241.1     0.1       0
Bank Sta=4980.6,4991
Exp/Cntr=0.3,0.1

Type RM Length L Ch R = 1,2798,417,417,417
BEGIN DESCRIPTION:
Mapping XS ef8b718b
END DESCRIPTION:
XS GIS Cut Line= 3
      2005405.37     13602691.52      2005162.32     13602196.74
      2003382.78     13601580.41
#Sta/Elev= 30
  3518.8  651.84  3556.1  651.08  3598.7  649.46  3649.3  650.35  3667.6  648.72
  3756.1  646.42  4173.0  644.56  4311.3  641.59  4414.3  642.33  4517.3  642.56
  4530.6  642.56  4620.3  641.68  4723.3  641.48  4903.3  641.83  4929.8  639.41
  4930.7  638.61  4940.2  639.41  4959.8  642.16  5005.6  639.77  5019.7  641.57
  5259.7  643.54  5374.1  650.58  5435.1  657.13  5555.7  671.50  5587.1  672.18
  5593.6  672.68  5618.0  679.81  5649.2  680.52  5686.4  684.08  5953.3  685.38
#Mann=16,-1,0
  3518.8     0.1       0  3556.1    0.08       0  3667.6     0.1       0
  4311.3    0.07       0  4414.3    0.12       0  4517.3     0.1       0
  4530.6    0.16       0  4620.3     0.1       0  4723.3    0.16       0
  4929.8    0.07       0  4940.2    0.16       0  4959.8     0.1       0
  5259.7    0.16       0  5435.1     0.1       0  5587.1    0.16       0
  5593.6     0.1       0
Bank Sta=4929.8,4940.2
Exp/Cntr=0.3,0.1

Type RM Length L Ch R = 1,2381,774,774,774
BEGIN DESCRIPTION:
Mapping XS 6743c5d1
END DESCRIPTION:
XS GIS Cut Line= 3
      2005492.19     13602943.30      2005214.40     13601918.96
      2002890.62     13600739.73
#Sta/Elev= 30
  3065.8  655.57  3360.5  650.88  3463.5  649.00  3568.7  645.59  3820.4  644.02
  4150.7  648.59  4429.4  643.64  4488.2  642.19  4794.1  638.63  4794.9  637.83
  4804.5  638.63  4863.8  640.29  4952.4  640.56  4976.9  640.52  5061.2  640.89
  5247.0  640.98  5491.9  653.90  5631.1  664.51  5803.6  670.13  5953.8  670.37
  6004.0  665.95  6070.8  666.88  6109.7  671.30  6369.2  666.15  6399.1  662.41
  6465.9  670.65  6526.2  672.93  6548.7  675.54  6560.6  680.27  6733.0  684.28
#Mann=11,-1,0
  3065.8     0.1       0  3360.5    0.08       0  3463.5     0.1       0
  4429.4    0.12       0  4488.2     0.1       0  4794.1    0.07       0
  4804.5     0.1       0  4863.8    0.07       0  4952.4     0.1       0
  4976.9    0.07       0  5061.2     0.1       0
Bank Sta=4794.1,4804.5
Exp/Cntr=0.3,0.1

Type RM Length L Ch R = 1,1607,0,0,0
BEGIN DESCRIPTION:
UNT 104 in HW 1.0
END DESCRIPTION:
XS GIS Cut Line= 3
      2005518.22     13602917.25      2005462.82     13601207.78
      2002962.84     13600322.38
#Sta/Elev= 30
  2311.5  655.44  2567.1  651.06  2604.1  649.05  2665.8  647.86  2994.1  641.11
  3514.4  645.39  3916.3  638.58  4187.1  638.58  4549.5  641.33  4874.3  637.93
  4973.8  637.32  4990.3  635.87  4991.2  635.07  5000.8  635.87  5089.6  639.51
  5207.7  636.78  5526.0  638.08  5598.9  641.16  6026.0  640.36  6288.1  650.32
  6383.4  650.62  6404.6  652.43  6417.1  656.69  6468.1  660.89  6491.4  662.20
  6507.8  659.10  6523.2  657.44  6586.4  662.00  6615.8  667.25  6674.0  671.89
#Mann=14,-1,0
  2311.5     0.1       0  2567.1    0.05       0  2604.1    0.08       0
  2665.8     0.1       0  3916.3    0.05       0  4187.1     0.1       0
  4874.3    0.16       0  4973.8     0.1       0  4990.3    0.07       0
  5000.8     0.1       0  6383.4    0.16       0  6404.6     0.1       0
  6507.8    0.16       0  6615.8     0.1       0
Bank Sta=4990.3,5000.8
Exp/Cntr=0.3,0.1

Chan Stop Cuts=-1