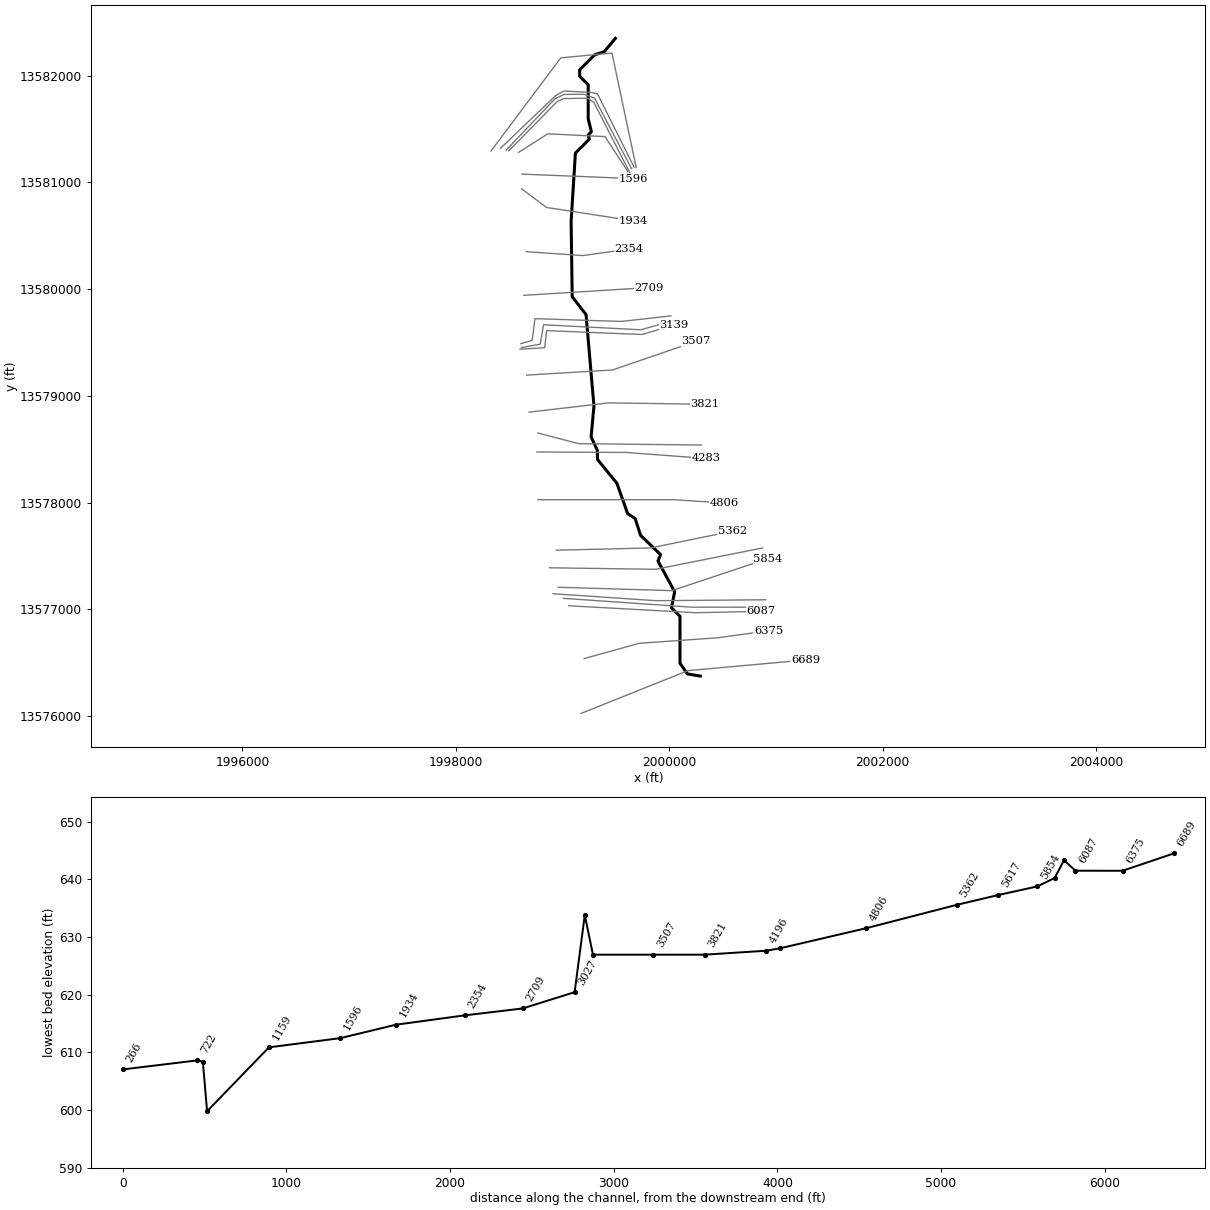
--- UNT 106 in HW.prj (project) ---

Proj Title=UNT 106 in HW Base Level Engineering
Current Plan=p01
Default Exp/Contr=0.3,0.1
English Units
Geom File=g01
Flow File=f01
Plan File=p01
Y Axis Title=Elevation
X Axis Title(PF)=Main Channel Distance
X Axis Title(XS)=Station
BEGIN DESCRIPTION:
UNT 106 in HW
END DESCRIPTION:
DSS Export Rating Curves= 0
DSS Export Rating Curve Sorted= 0
DSS Export Volume Flow Curves= 0
DXF OffsetX= 0
DXF OffsetY= 0
DXF ScaleX= 1
DXF ScaleY= 10

--- UNT 106 in HW.p01 (plan) ---

Plan Title=Multiple Run
Short Identifier=Multiple
Geom File=g01
Flow File=f01
Subcritical Flow
K Sum by GR= 0
Std Step Tol= 0.01
Critical Tol= 0.01
Num of Std Step Trials= 20
Max Error Tol= 0.3
Flow Tol Ratio= 0.001
Split Flow NTrial= 30
Split Flow Tol= 0.02
Split Flow Ratio= 0.02
Log Output Level= 0
Friction Slope Method= 1
Unsteady Friction Slope Method= 2
Unsteady Bridges Friction Slope Method= 1
Parabolic Critical Depth
Global Vel Dist=  1 , 1 , 1
Global Log Level= 0
CheckData=True
Encroach Param= -1, 0, 0, 0
BEGIN DESCRIPTION:
Multiple Run
END DESCRIPTION:

--- UNT 106 in HW.f01 (steady flow) ---

Flow Title=Multiple
Number of Profiles=7
Profile Names=10-year,25-year,50-year,1pct_min,100-year,1pct_plu,500-year
River Rch & RM= UNT 106 in HW,Reach-1,6689
     541     763     948     583    1164    2323    1763
Boundary for River Rch & Prof#=UNT 106 in HW,Reach-1,1
Up Type=0
Dn Type=3
Dn Slope=0.005
Boundary for River Rch & Prof#=UNT 106 in HW,Reach-1,2
Up Type=0
Dn Type=3
Dn Slope=0.005
Boundary for River Rch & Prof#=UNT 106 in HW,Reach-1,3
Up Type=0
Dn Type=3
Dn Slope=0.005
Boundary for River Rch & Prof#=UNT 106 in HW,Reach-1,4
Up Type=0
Dn Type=3
Dn Slope=0.005
Boundary for River Rch & Prof#=UNT 106 in HW,Reach-1,5
Up Type=0
Dn Type=3
Dn Slope=0.005
Boundary for River Rch & Prof#=UNT 106 in HW,Reach-1,6
Up Type=0
Dn Type=3
Dn Slope=0.005
Boundary for River Rch & Prof#=UNT 106 in HW,Reach-1,7
Up Type=0
Dn Type=3
Dn Slope=0.005

--- UNT 106 in HW.g01 (geometry) ---

Geom Title=Existing Conditions
Program Version=5.05

River Reach=UNT 106 in HW   ,Reach-1
Reach XY= 30
      2000291.09     13576374.54       2000170.8     13576394.54
       2000100.8     13576494.54       2000100.8     13576934.54
       2000020.8     13577014.54       2000050.8     13577164.54
      1999894.53     13577451.79      1999918.84     13577512.56
      1999731.34     13577693.11      1999680.99     13577850.23
      1999609.81      13577897.1      1999509.12     13578181.83
      1999328.56     13578403.18      1999325.96     13578490.85
       1999267.8     13578615.85      1999294.71     13578904.48
      1999220.49     13579761.51       1999090.8     13579928.18
       1999080.8     13580634.54       1999120.8     13581274.54
       1999250.8     13581404.54       1999240.8     13581444.54
       1999270.8     13581474.54       1999240.8     13581594.54
       1999240.8     13581914.54       1999160.8     13581994.54
       1999160.8     13582054.54       1999300.8     13582194.54
       1999390.8     13582224.54      1999495.58     13582349.64

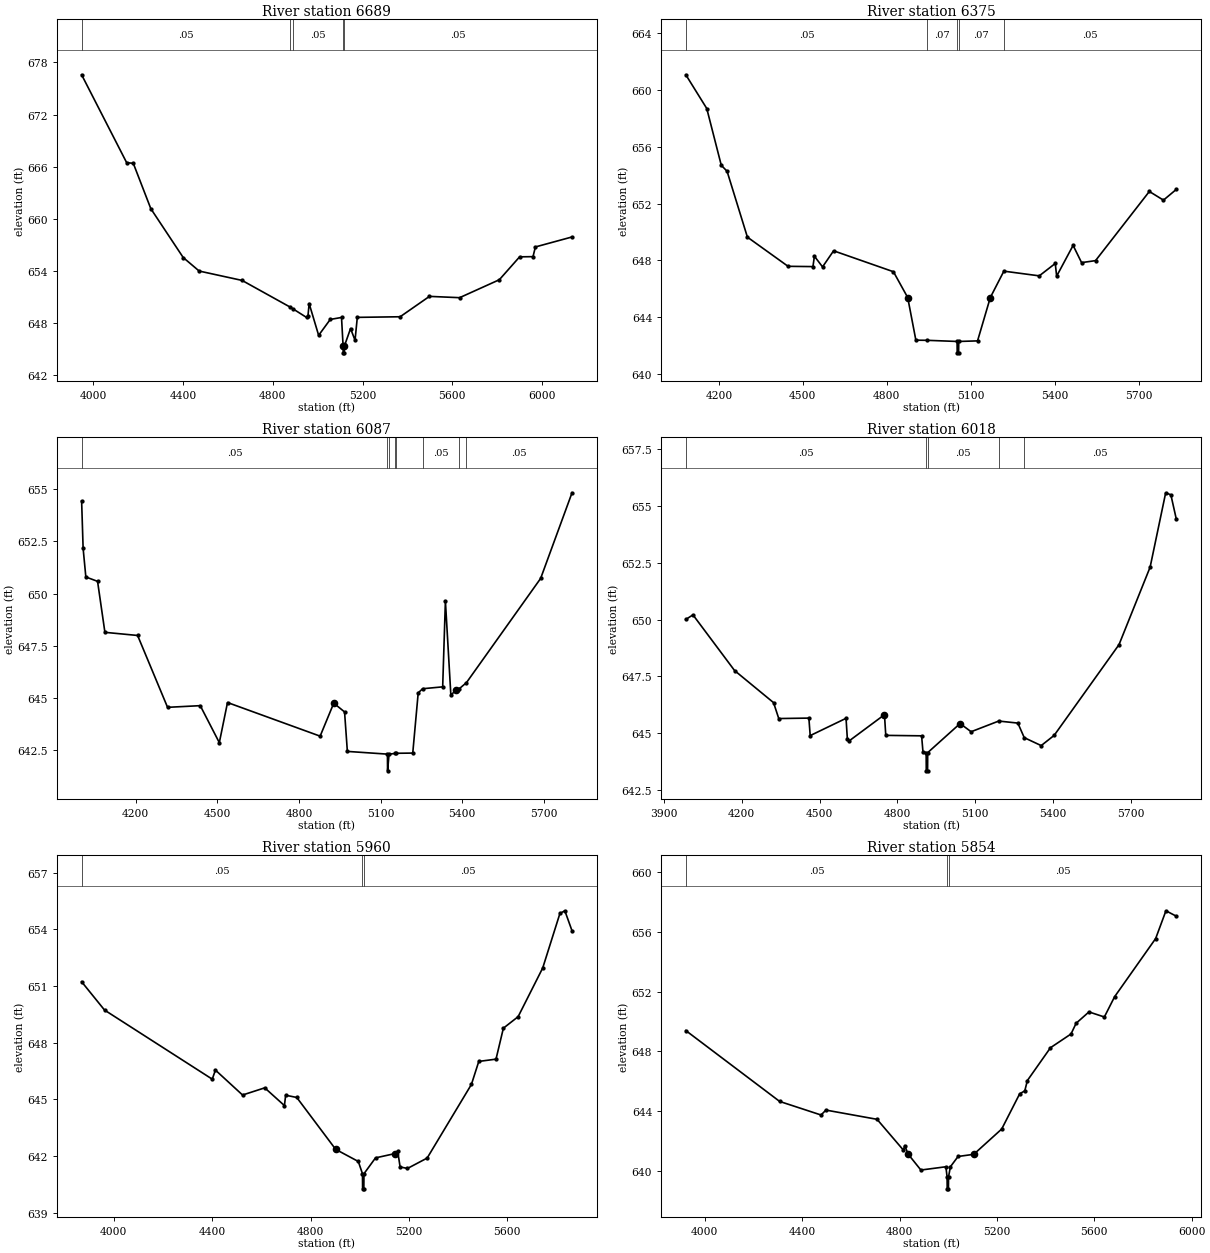
Type RM Length L Ch R = 1 ,6689    ,314,314,314
BEGIN DESCRIPTION:
UNT 106 in HW 16.0
END DESCRIPTION:
XS GIS Cut Line= 3
      1999175.02     13576025.01      2000175.03     13576425.45
      2001277.42     13576525.27
#Sta/Elev= 30
  3948.9  676.58  4149.4  666.45    4179  666.37  4257.1  661.14  4401.3  655.51
  4472.4  653.95  4663.5  652.87  4875.1  649.83  4892.1  649.56  4950.7   648.6
  4956.8  648.72  4962.2   650.2  5004.5  646.54  5056.2  648.37  5106.4   648.6
  5113.4  645.32  5113.9  644.52  5118.9  644.52  5119.4  645.32  5146.6  647.32
  5166.6  645.97  5176.7  648.61  5367.5  648.68    5498  651.03  5632.3  650.88
  5809.3  652.95  5899.6  655.59  5959.2  655.61  5969.9  656.73    6133  657.88
#Mann= 5 ,-1 , 0
  3948.9     .05       0  4875.1     .08       0  4892.1     .05       0
  5113.4     .03       0  5119.4     .05       0
Bank Sta=5113.4,5119.4
XS Rating Curve= 0 ,0
Exp/Cntr=0.3,0.1

Type RM Length L Ch R = 1 ,6375    ,288,288,288
BEGIN DESCRIPTION:
Mapping XS 5cedc1f4
END DESCRIPTION:
XS GIS Cut Line= 4
      1999202.84     13576538.31       1999719.3     13576681.53
      2000457.15     13576733.61      2000930.15      13576798.7
#Sta/Elev= 30
  4081.6  661.05  4156.5  658.68  4208.4  654.69  4229.1  654.27  4301.8  649.64
  4447.1  647.59  4536.1  647.57  4541.3   648.3  4570.4  647.55  4609.9  648.68
  4823.8  647.21 4874.85645.3967    4904   642.4  4944.5  642.39  5051.3  642.31
  5051.8  641.51  5056.8  641.51  5057.3  642.31  5124.5  642.35 5170.13 645.397
  5218.6  647.25  5345.1  646.92  5402.3  647.79  5407.3   646.9  5466.1  649.06
  5496.4  647.85  5546.3  647.99  5738.6  652.85  5789.1  652.24  5834.7  652.99
#Mann= 5 ,-1 , 0
  4081.6     .05       0  4944.5     .07       0  5051.3     .07       0
  5057.3     .07       0  5218.6     .05       0
Bank Sta=4874.85,5170.13
XS Rating Curve= 0 ,0
Exp/Cntr=0.3,0.1

Type RM Length L Ch R = 1 ,6087    ,69,69,69
BEGIN DESCRIPTION:
Mapping XS 48737978
END DESCRIPTION:
XS GIS Cut Line= 3
      1999059.53     13577033.09      2000248.81     13576967.99
      2000860.41       13576981.
#Sta/Elev= 30
  4001.2  654.44  4006.7  652.17  4016.7   650.8  4059.8  650.59  4086.8  648.15
    4207     648  4317.1  644.56  4437.3  644.64  4507.4  642.87  4537.5  644.79
    4878  643.18  4928.1  644.76  4967.8  644.34  4978.1  642.45  5125.4  642.32
  5125.9  641.52  5131.4  642.32  5152.6  642.35  5156.2  642.36  5218.5  642.37
  5238.5  645.25  5254.6  645.45  5328.5  645.54  5338.5  649.65  5358.5  645.16
 5378.17645.3708  5388.5  645.44  5415.8  645.74  5688.6  650.73    5804  654.83
#Mann= 8 ,-1 , 0
  4001.2     .05       0  5125.4    .035       0  5131.4     .05       0
  5152.6     .07       0  5156.2      .1       0  5254.6     .05       0
  5388.5      .1       0  5415.8     .05       0
Bank Sta=4928.1,5378.17
XS Rating Curve= 0 ,0
Exp/Cntr=0.3,0.1

Type RM Length L Ch R = 1 ,6018    ,58,58,58
BEGIN DESCRIPTION:
Mapping XS ac0e71dc
END DESCRIPTION:
XS GIS Cut Line= 3
      1999007.48     13577102.54      2000209.75     13577020.07
      2000895.55     13577020.07
#Sta/Elev= 30
  3984.3  650.01  4011.9  650.21  4172.4  647.76  4322.6  646.35  4342.7  645.65
  4458.8  645.67  4463.9   644.9  4602.1  645.66  4607.1  644.77  4613.3  644.66
  4750.3  645.82  4755.3  644.91  4893.5  644.89  4898.6   644.2    4911  644.15
  4911.5  643.35  4916.5  643.35    4917  644.15  5041.8  645.43  5084.4  645.07
  5190.9  645.54  5264.6  645.45  5289.2  644.81  5354.6  644.46  5404.6  644.91
  5654.6   648.9  5774.6  652.31  5834.6  655.58  5854.6  655.49  5875.2  654.44
#Mann= 5 ,-1 , 0
  3984.3     .05       0    4911    .035       0    4917     .05       0
  5190.9      .1       0  5289.2     .05       0
Bank Sta=4750.3,5041.8
XS Rating Curve= 0 ,0
Exp/Cntr=0.3,0.1

Type RM Length L Ch R = 1 ,5960    ,106,106,106
BEGIN DESCRIPTION:
UNT 106 in HW 15.0
END DESCRIPTION:
XS GIS Cut Line= 3
        1998912.     13577145.94      1999875.55     13577080.83
      2000904.17     13577089.51
#Sta/Elev= 30
    3869  651.23  3962.2  649.73  4400.2  646.07  4413.2  646.55  4523.5  645.23
  4613.7  645.61  4693.8  644.67  4698.8  645.22    4744   645.1 4902.21642.3517
  4994.2  641.71  5011.2  641.06  5011.7  640.26  5016.7  640.26  5017.2  641.06
  5064.2   641.9  5144.2  642.13  5154.2  642.27  5164.2  641.42  5194.2  641.34
  5274.2  641.89  5454.2  645.79  5484.2  647.01  5554.2  647.13  5584.2  648.77
  5644.2  649.38  5744.2  651.96  5814.2  654.85  5834.2  654.99  5863.4  653.93
#Mann= 3 ,-1 , 0
    3869     .05       0  5011.2    .035       0  5017.2     .05       0
Bank Sta=4902.21,5144.2
XS Rating Curve= 0 ,0
Exp/Cntr=0.3,0.1

Type RM Length L Ch R = 1 ,5854    ,237,237,237
BEGIN DESCRIPTION:
UNT 106 in HW 14.0
END DESCRIPTION:
XS GIS Cut Line= 3
       1998959.8      13577206.7        2000025.       13577175.
      2000925.04     13577475.01
#Sta/Elev= 30
  3922.2   649.4  4307.6  644.65  4477.7  643.74  4497.7  644.07  4707.8  643.45
  4816.3  641.38  4821.3  641.69 4836.03641.1031  4887.8  640.05  4990.5  640.27
  4995.4  639.59  4995.9  638.79  5000.9  638.79  5001.4  639.59    5009  640.27
  5040.6  640.96 5104.87641.1032  5219.8   642.8  5293.6  645.16  5314.6  645.36
  5325.2  646.05  5420.1  648.25  5504.4  649.17  5525.5  649.89  5578.2  650.65
  5641.4  650.31  5683.6  651.67  5852.2  655.57  5894.4  657.43  5936.6  657.07
#Mann= 3 ,-1 , 0
  3922.2     .05       0  4995.4    .035       0  5001.4     .05       0
Bank Sta=4836.03,5104.87
XS Rating Curve= 0 ,0
Exp/Cntr=0.3,0.1

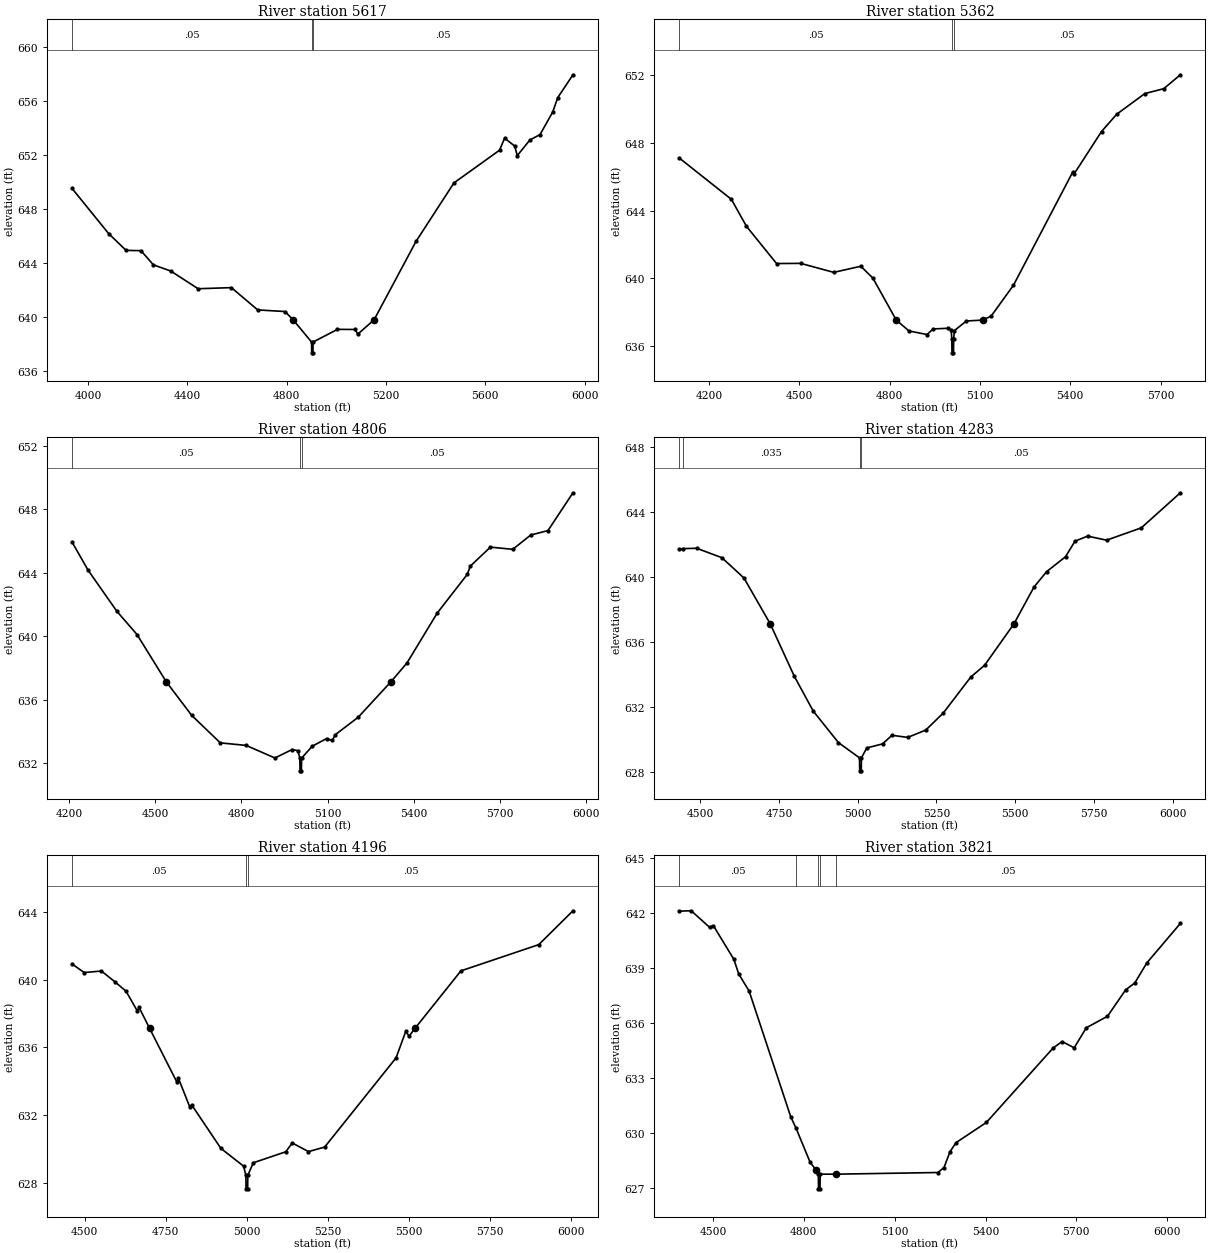
Type RM Length L Ch R = 1 ,5617    ,255,255,255
BEGIN DESCRIPTION:
UNT 106 in HW 13.0
END DESCRIPTION:
XS GIS Cut Line= 3
      1998877.31     13577388.99        1999875.       13577375.
      2000875.01       13577575.
#Sta/Elev= 30
  3935.2  649.49  4082.9  646.14  4152.9   644.9  4212.9  644.88  4262.9  643.83
  4332.9  643.37  4442.9  642.06  4577.2  642.14    4683  640.49    4793  640.37
 4825.48639.7617    4900  638.11  4900.5  637.31  4905.5  637.31    4906  638.11
  5004.4  639.05  5075.8  639.04    5086  638.69 5152.02639.7617  5320.5  645.56
  5473.5   649.9    5657  652.32  5677.4  653.21  5718.2  652.63  5728.4  651.92
  5779.4  653.08  5820.2  653.48  5871.2  655.15  5891.6  656.22  5952.8  657.91
#Mann= 3 ,-1 , 0
  3935.2     .05       0    4900    .035       0    4906     .05       0
Bank Sta=4825.48,5152.02
XS Rating Curve= 0 ,0
Exp/Cntr=0.3,0.1

Type RM Length L Ch R = 1 ,5362    ,556,556,556
BEGIN DESCRIPTION:
UNT 106 in HW 12.0
END DESCRIPTION:
XS GIS Cut Line= 3
      1998942.42     13577553.92        1999825.       13577575.
       2000590.8     13577731.69
#Sta/Elev= 30
  4101.3  647.09  4273.9  644.66  4323.9  643.07    4424  640.87    4504  640.88
    4614  640.35  4704.1  640.71  4744.1  640.01 4821.74637.5328  4864.1  636.89
  4924.1  636.68  4944.1  637.01  4994.3  637.05  5004.3  636.95  5006.4   636.4
  5006.9   635.6  5011.9   635.6  5012.4   636.4  5014.8  636.91  5054.7  637.48
 5109.05637.5327  5137.2  637.77  5211.2  639.59  5407.9  646.26  5413.1  646.17
  5503.8  648.66  5554.2  649.68  5647.6   650.9  5710.7  651.19  5765.8  652.01
#Mann= 3 ,-1 , 0
  4101.3     .05       0  5006.4    .035       0  5012.4     .05       0
Bank Sta=4821.74,5109.05
XS Rating Curve= 0 ,0
Exp/Cntr=0.3,0.1

Type RM Length L Ch R = 1 ,4806    ,523,523,523
BEGIN DESCRIPTION:
UNT 106 in HW 11.0
END DESCRIPTION:
XS GIS Cut Line= 3
       1998768.8     13578027.01      2000040.48     13578027.01
      2000511.83     13577996.74
#Sta/Elev= 30
  4210.2  645.93  4266.4  644.15  4366.4  641.57  4436.4  640.11 4538.36637.1328
  4626.4  635.03  4726.4  633.29  4816.4  633.13  4916.4  632.34  4976.4  632.87
  4996.4   632.8  5003.4  632.33  5003.9  631.53  5008.9  631.53  5009.4  632.33
  5046.4  633.08  5096.4  633.56  5116.4  633.44  5126.4   633.8  5206.4   634.9
 5320.35637.1328  5376.4  638.32  5481.6  641.46  5586.5   643.9  5596.6  644.41
  5666.8  645.61  5744.6  645.47  5807.1  646.37  5867.2  646.65  5954.2  649.03
#Mann= 3 ,-1 , 0
  4210.2     .05       0  5003.4    .035       0  5009.4     .05       0
Bank Sta=4538.36,5320.35
XS Rating Curve= 0 ,0
Exp/Cntr=0.3,0.1

Type RM Length L Ch R = 1 ,4283    ,87,87,87
BEGIN DESCRIPTION:
UNT 106 in HW 10.0
END DESCRIPTION:
XS GIS Cut Line= 3
      1998760.07     13578474.06      1999597.77     13578469.72
      2000348.64      13578413.3
#Sta/Elev= 30
  4434.1  641.71  4443.9  641.76    4489  641.78    4569   641.2    4639  639.95
  4722.3 637.131    4799  633.89    4859  631.75    4939  629.81    5006  628.87
  5006.5  628.07  5011.5  628.07    5012  628.87    5029  629.48    5079  629.73
    5109  630.26    5159  630.13  5216.2  630.58  5271.8  631.63  5359.3  633.85
    5403  634.57 5496.51637.1311  5559.9  639.39    5600  640.34  5660.1  641.26
  5690.2  642.22  5730.3  642.53  5790.5  642.28  5900.8  643.04  6024.8   645.2
#Mann= 4 ,-1 , 0
  4434.1     .05       0  4443.9    .035       0    5006     .05       0
    5012     .05       0
Bank Sta=4722.3,5496.51
XS Rating Curve= 0 ,0
Exp/Cntr=0.3,0.1

Type RM Length L Ch R = 1 ,4196    ,375,375,375
BEGIN DESCRIPTION:
Mapping XS 5dabfeae
END DESCRIPTION:
XS GIS Cut Line= 3
      1998768.81     13578652.01      1999150.72     13578552.19
      2000300.41     13578539.17
#Sta/Elev= 30
  4461.2  640.93  4498.6  640.42  4551.8  640.51  4592.3  639.89  4627.6  639.32
  4662.8  638.14    4668  638.36 4700.14637.1313  4784.2  633.96  4789.3  634.17
  4824.6  632.46  4829.8  632.61  4920.2  630.03  4990.2  628.98  4997.2  628.44
  4997.7  627.64  5002.7  627.64  5003.2  628.44  5020.2  629.18  5120.2  629.83
  5140.2  630.35  5190.2  629.84  5240.2  630.11  5460.3  635.38  5490.3  636.95
  5500.3  636.66    5519 637.131  5660.3  640.52  5900.3  642.07  6005.7  644.07
#Mann= 3 ,-1 , 0
  4461.2     .05       0  4997.2    .035       0  5003.2     .05       0
Bank Sta=4700.14,5519
XS Rating Curve= 0 ,0
Exp/Cntr=0.3,0.1

Type RM Length L Ch R = 1 ,3821    ,314,314,314
BEGIN DESCRIPTION:
UNT 106 in HW 9.0
END DESCRIPTION:
XS GIS Cut Line= 3
      1998686.29     13578847.32      1999432.84     13578934.13
      2000335.67     13578921.11
#Sta/Elev= 30
    4389   642.1    4428  642.12  4488.4  641.22  4501.1  641.31  4568.9  639.47
  4584.7  638.68  4619.2  637.74  4756.8  630.88  4774.3  630.26  4820.6  628.41
  4840.4  627.98  4847.8  627.76  4848.3  626.96  4853.3  626.96  4853.8  627.76
  4906.3  627.76  5242.7  627.85  5262.8  628.12  5282.8  628.99  5302.8  629.48
  5402.8  630.58  5622.8  634.63  5652.8  634.99  5692.8  634.65  5732.8  635.74
  5802.8  636.37  5862.8  637.81  5892.8  638.18  5932.8  639.28  6043.5  641.43
#Mann= 5 ,-1 , 0
    4389     .05       0  4774.3    .035       0  4847.8     .05       0
  4853.8    .035       0  4906.3     .05       0
Bank Sta=4840.4,4906.3
XS Rating Curve= 0 ,0
Exp/Cntr=0.3,0.1

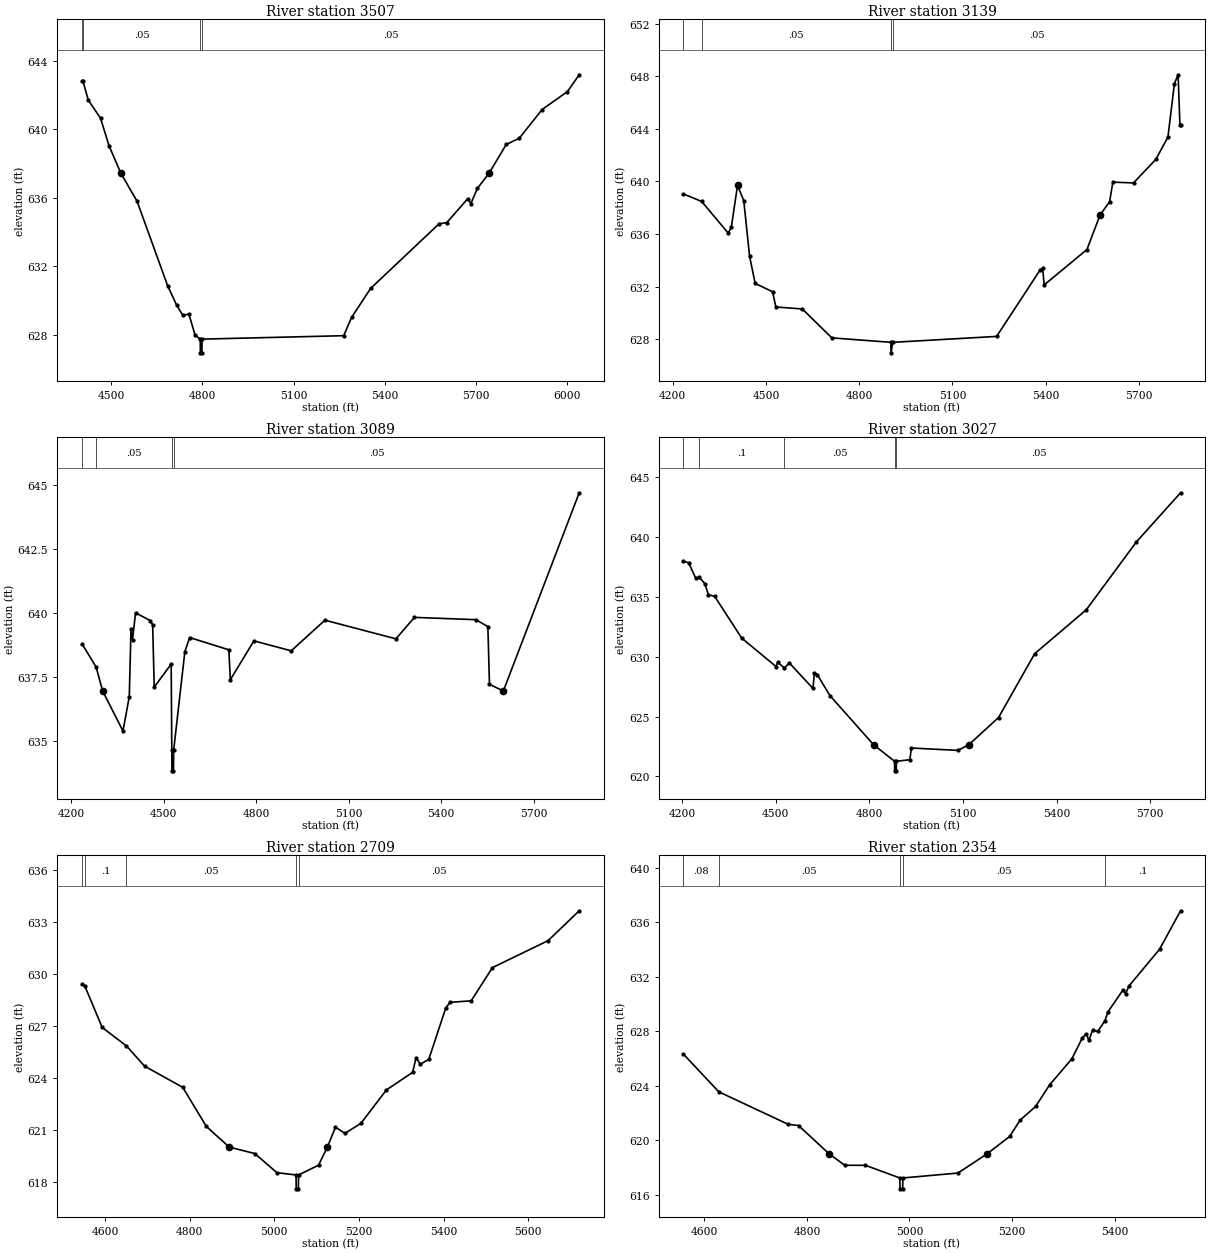
Type RM Length L Ch R = 1 ,3507    ,368,368,368
BEGIN DESCRIPTION:
UNT 106 in HW 8.0
END DESCRIPTION:
XS GIS Cut Line= 3
      1998664.62     13579194.55      1999467.56     13579242.29
      2000251.58     13579510.85
#Sta/Elev= 30
  4405.4  642.81  4408.3   642.8  4425.8   641.7  4465.9  640.65  4494.1  639.03
 4532.75637.4377  4586.1   635.8  4686.3  630.88  4716.3  629.73  4736.4  629.15
  4756.4  629.22  4776.4     628  4793.5  627.76    4794  626.96    4799  626.96
  4799.5  627.76  5264.8  627.96  5290.8  629.03  5353.4  630.72  5577.6  634.48
  5603.6  634.56  5672.2  635.95  5682.7  635.67  5703.9  636.55 5742.35637.4379
    5799  639.12  5841.3  639.47  5916.5  641.15  5999.8   642.2  6038.5  643.18
#Mann= 4 ,-1 , 0
  4405.4     .08       0  4408.3     .05       0  4793.5     .05       0
  4799.5     .05       0
Bank Sta=4532.75,5742.35
XS Rating Curve= 0 ,0
Exp/Cntr=0.3,0.1

Type RM Length L Ch R = 1 ,3139    ,50,50,50
BEGIN DESCRIPTION:
UNT 106 in HW 6.0
END DESCRIPTION:
XS GIS Cut Line= 5
      1998601.21     13579436.73      1998833.26     13579450.97
      1998851.25     13579611.22      1999744.47     13579574.76
      2000043.95      13579663.3
#Sta/Elev= 30
  4234.4  639.05  4293.2  638.48  4378.5  636.07  4388.5  636.51  4408.5   639.7
  4428.6  638.54  4447.3  634.31  4465.3  632.24  4521.3  631.61  4531.8  630.45
  4616.9   630.3    4712   628.1  4902.1  627.76  4902.6  626.96  4908.1  627.76
  5242.4  628.21  5382.5  633.27  5390.5  633.41  5395.5  632.13  5533.1  634.82
 5575.06637.4389    5606  638.46  5616.5  639.95    5683  639.89  5754.8  641.68
  5793.8  643.38  5814.6  647.45  5826.5  648.12  5832.3  644.32  5834.4  644.32
#Mann= 4 ,-1 , 0
  4234.4     .08       0  4293.2     .05       0  4902.1    .033       0
  4908.1     .05       0
Bank Sta=4408.5,5575.06
XS Rating Curve= 0 ,0
Exp/Cntr=0.3,0.1

Type RM Length L Ch R = 1 ,3089    ,62,62,62
BEGIN DESCRIPTION:
UNT 106 in HW 5.0
END DESCRIPTION:
XS GIS Cut Line= 5
      1998614.28     13579452.36      1998791.35     13579483.61
       1998822.6      13579665.9      1999734.06     13579619.03
      2000056.63     13579710.08
#Sta/Elev= 30
  4235.2  638.79  4280.9  637.88 4301.94636.9457  4367.9  635.38  4388.3  636.73
  4393.8  639.36  4398.9  638.96  4408.6  640.01    4457   639.7  4464.1  639.53
  4469.2   637.1  4524.2     638  4526.2  634.62  4526.7  633.82  4531.7  633.82
  4532.2  634.62  4568.6  638.49  4584.2  639.04  4711.2  638.56  4716.2  637.39
  4792.6  638.91  4913.7  638.52  5022.9  639.72  5253.2  638.99  5313.3  639.83
  5512.6  639.74  5551.5  639.47  5556.7  637.21 5601.62636.9456  5847.8  644.71
#Mann= 4 ,-1 , 0
  4235.2     .08       0  4280.9     .05       0  4526.2    .035       0
  4532.2     .05       0
Bank Sta=4301.94,5601.62
XS Rating Curve= 0 ,0
Exp/Cntr=0.3,0.1

Type RM Length L Ch R = 1 ,3027    ,318,318,318
BEGIN DESCRIPTION:
UNT 106 in HW 7.0
END DESCRIPTION:
XS GIS Cut Line= 5
      1998609.01     13579488.81      1998715.83     13579520.07
      1998741.87     13579723.19      1999551.77     13579697.15
      2000015.35     13579749.24
#Sta/Elev= 30
  4204.3  637.99    4221  637.87  4244.1  636.55  4255.2  636.65  4273.1  636.11
  4284.2  635.19  4304.3  635.06  4391.1  631.56  4501.3  629.18  4506.4  629.54
  4527.9  629.06  4543.5  629.49  4619.2  627.36  4624.2  628.66  4633.6  628.49
  4673.6  626.76 4813.38622.6493  4880.7  621.26  4881.2  620.46  4886.2  620.46
  4886.7  621.26  4929.8  621.39  4934.8  622.37  5083.8  622.17 5118.97622.6493
  5213.9  624.92  5329.8  630.26    5495  633.93    5656  639.62  5797.2  643.72
#Mann= 5 ,-1 , 0
  4204.3     .08       0  4255.2      .1       0  4527.9     .05       0
  4880.7    .035       0  4886.7     .05       0
Bank Sta=4813.38,5118.97
XS Rating Curve= 0 ,0
Exp/Cntr=0.3,0.1

Type RM Length L Ch R = 1 ,2709    ,355,355,355
BEGIN DESCRIPTION:
UNT 106 in HW 4.0
END DESCRIPTION:
XS GIS Cut Line= 3
      1998637.66     13579941.94        1999175.       13579975.
      1999809.59     13580014.86
#Sta/Elev= 30
    4546  629.42  4552.5   629.3  4593.4  626.92  4650.9  625.85  4693.6  624.69
  4783.8  623.47  4839.5  621.22 4893.58620.0309  4954.1  619.66  5006.1  618.56
  5051.3  618.43  5051.8  617.63  5056.8  617.63  5057.3  618.43  5104.4  618.99
 5125.36620.0308  5144.5  621.18  5166.8  620.82  5204.6   621.4  5264.7  623.32
  5326.7  624.33  5334.9  625.18  5344.9   624.8  5364.9  625.08    5405  628.04
    5415  628.36  5465.1  628.45  5515.2  630.36  5646.6  631.91  5720.2  633.63
#Mann= 5 ,-1 , 0
    4546     .05       0  4552.5      .1       0  4650.9     .05       0
  5051.3    .035       0  5057.3     .05       0
Bank Sta=4893.58,5125.36
XS Rating Curve= 0 ,0
Exp/Cntr=0.3,0.1

Type RM Length L Ch R = 1 ,2354    ,420,420,420
BEGIN DESCRIPTION:
UNT 106 in HW 3.0
END DESCRIPTION:
XS GIS Cut Line= 3
      1998661.14      13580350.8      1999189.79     13580314.34
      1999624.98       13580375.
#Sta/Elev= 30
  4559.3  626.33  4628.2  623.56  4763.6  621.17  4783.7  621.08 4843.83618.9893
  4873.9  618.16    4914  618.16  4981.2  617.23  4981.7  616.43  4986.7  616.43
  4987.2  617.23  5094.5  617.59 5150.94618.9894  5195.4  620.28  5215.6  621.47
  5245.9  622.48  5273.1  624.06  5316.6  625.98  5336.8   627.5  5344.7  627.83
  5349.7  627.33    5357  628.08  5367.1     628    5381  628.77  5387.3  629.45
  5416.2  631.03  5421.3  630.75  5427.7  631.32  5487.8  634.04  5528.6  636.86
#Mann= 5 ,-1 , 0
  4559.3     .08       0  4628.2     .05       0  4981.2    .035       0
  4987.2     .05       0    5381      .1       0
Bank Sta=4843.83,5150.94
XS Rating Curve= 0 ,0
Exp/Cntr=0.3,0.1

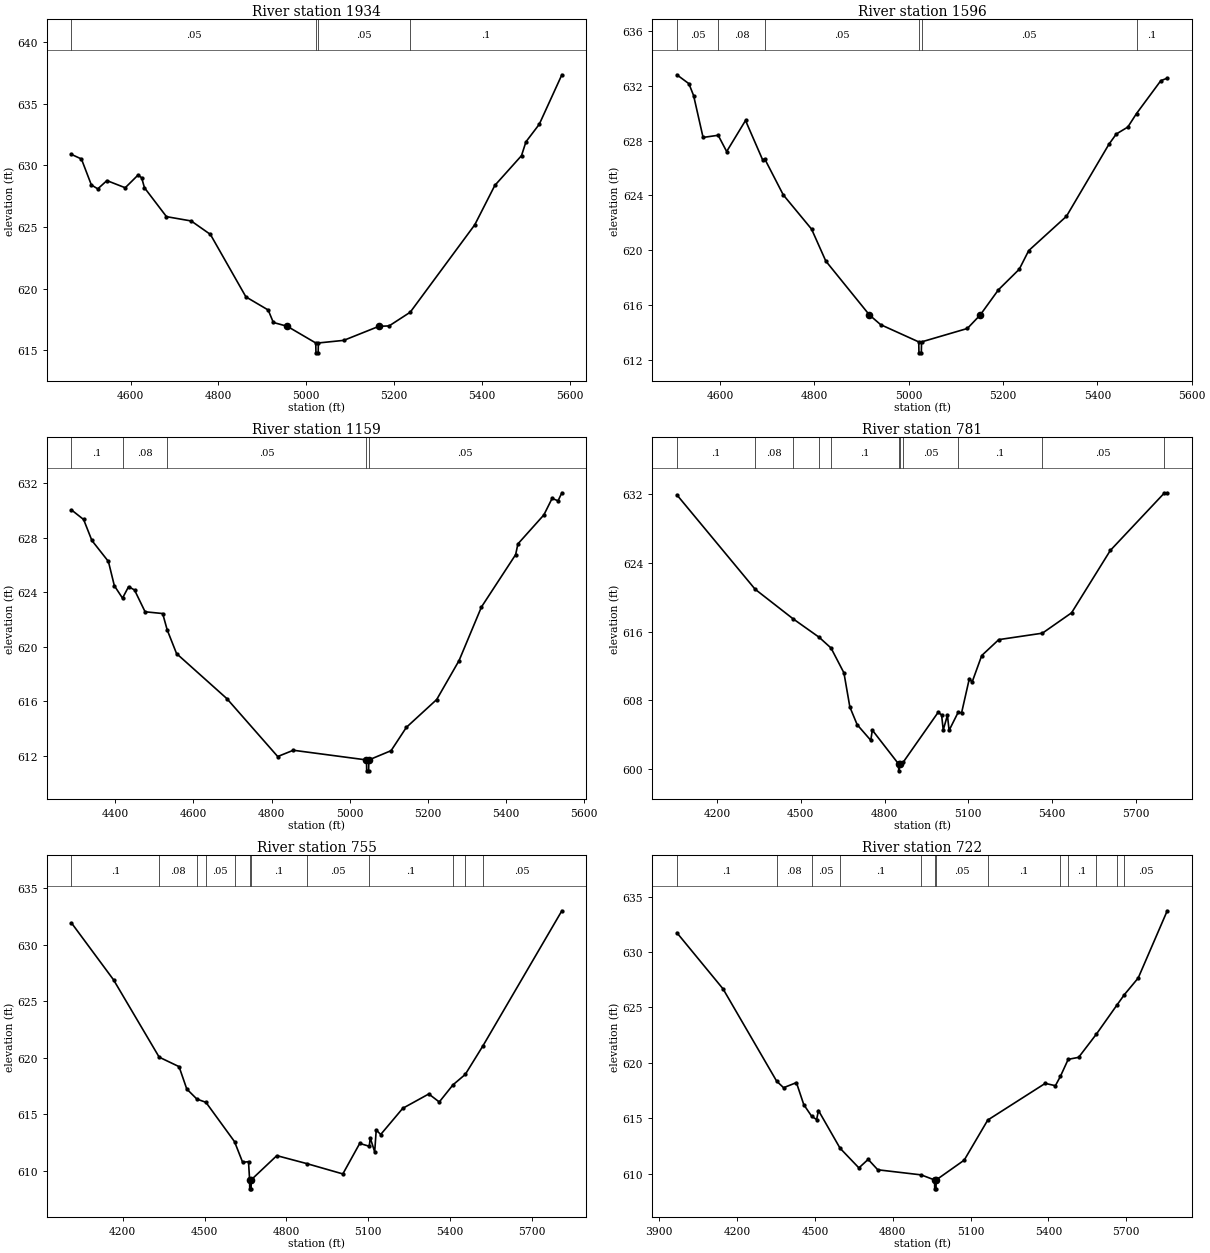
Type RM Length L Ch R = 1 ,1934    ,338,338,338
BEGIN DESCRIPTION:
UNT 106 in HW 2.0
END DESCRIPTION:
XS GIS Cut Line= 3
       1998616.9     13580939.31      1998851.25     13580764.86
      1999665.88     13580639.93
#Sta/Elev= 30
  4465.5  630.88  4488.1  630.51  4510.7  628.41  4525.3  628.09  4546.1  628.76
  4587.8  628.18    4617  629.21  4625.2  628.99  4631.6  628.18  4681.7  625.84
    4738  625.49  4781.7   624.4  4862.6  619.34  4913.2  618.28    4925  617.27
 4956.67  616.96  5021.5  615.61    5022  614.81    5027  614.81  5027.5  615.61
  5085.2  615.82 5165.43  616.96  5188.5  616.99  5236.6   618.1  5383.5  625.18
  5429.2  628.37  5489.9  630.78    5500   631.9  5530.3  633.32  5581.8  637.33
#Mann= 4 ,-1 , 0
  4465.5     .05       0  5021.5     .03       0  5027.5     .05       0
  5236.6      .1       0
Bank Sta=4956.67,5165.43
XS Rating Curve= 0 ,0
Exp/Cntr=0.3,0.1

Type RM Length L Ch R = 1 ,1596    ,437,437,437
BEGIN DESCRIPTION:
Mapping XS a412cb8e
END DESCRIPTION:
XS GIS Cut Line= 2
      1998619.49     13581077.36      1999658.56     13581035.69
#Sta/Elev= 30
  4508.3  632.81  4533.8  632.16  4543.8  631.29  4563.9  628.23  4595.9  628.39
  4613.9   627.2  4653.9  629.47  4690.5  626.57  4694.5  626.67    4734  624.03
    4794  621.53  4824.1   619.2 4916.71 615.256  4940.4  614.55  5021.2  613.29
  5021.7  612.49  5026.7  612.49  5027.2  613.29  5124.3  614.27 5151.58615.2557
  5190.3   617.1  5234.4   618.6  5254.4  619.96  5334.5  622.47  5424.5  627.73
  5440.1  628.48  5464.6  628.99  5483.1  629.98  5534.6  632.38  5548.2  632.56
#Mann= 6 ,-1 , 0
  4508.3     .05       0  4595.9     .08       0  4694.5     .05       0
  5021.2    .035       0  5027.2     .05       0  5483.1      .1       0
Bank Sta=4916.71,5151.58
XS Rating Curve= 0 ,0
Exp/Cntr=0.3,0.1

Type RM Length L Ch R = 1 ,1159    ,378,378,378
BEGIN DESCRIPTION:
Mapping XS 04bf6f5c
END DESCRIPTION:
XS GIS Cut Line= 4
      1998588.26     13581280.51      1998861.66     13581454.97
      1999398.12     13581428.92      1999613.66     13581099.12
#Sta/Elev= 30
  4287.7  630.03  4318.7  629.33  4339.9  627.79  4382.2  626.25  4397.4  624.47
  4418.3  623.56  4433.8   624.4    4449  624.16  4476.1  622.56  4521.1  622.43
  4532.7  621.23  4556.7  619.49  4685.4  616.19  4815.6  611.94  4855.6   612.4
  5042.9  611.69  5043.4  610.89  5048.4  610.89  5048.9  611.69  5105.9  612.37
    5145  614.08  5222.6  616.12  5279.9  618.98  5337.2  622.91  5424.7  626.75
  5430.6  627.54  5497.1  629.67  5518.1  630.88  5533.3   630.7  5543.1  631.29
#Mann= 5 ,-1 , 0
  4287.7      .1       0  4418.3     .08       0  4532.7     .05       0
  5042.9    .035       0  5048.9     .05       0
Bank Sta=5042.9,5048.9
XS Rating Curve= 0 ,0
Exp/Cntr=0.3,0.1

Type RM Length L Ch R = 1 ,781     ,26,26,26
BEGIN DESCRIPTION:
Mapping XS 8d1c5b56
END DESCRIPTION:
XS GIS Cut Line= 6
      1998497.11     13581296.14       1998950.2     13581757.05
       1999010.1     13581785.69      1999236.66      13581788.3
      1999293.95     13581749.24      1999635.09     13581082.58
#Sta/Elev= 30
  4055.7  631.93  4336.3  620.94  4472.3   617.5  4565.8  615.35  4608.3   614.1
  4654.5  611.21  4675.7  607.24  4701.9  605.18  4750.7  603.36  4756.2  604.55
  4850.3  600.61  4850.8  599.81  4856.3  600.61    4867  600.82  4991.7   606.6
  5004.4  606.33  5010.4  604.57  5025.4  606.27  5031.4  604.52  5063.7  606.61
  5076.2  606.57    5104  610.55    5114  610.15  5148.4  613.23  5209.4  615.08
  5365.8  615.83  5470.3   618.2  5609.2  625.46  5801.6   632.1  5813.2  632.17
#Mann= 11 ,-1 , 0
  4055.7      .1       0  4336.3     .08       0  4472.3      .1       0
  4565.8     .05       0  4608.3      .1       0  4850.3     .03       0
  4856.3      .1       0    4867     .05       0  5063.7      .1       0
  5365.8     .05       0  5801.6      .1       0
Bank Sta=4850.3,4856.3
XS Rating Curve= 0 ,0
Exp/Cntr=0.3,0.1

Type RM Length L Ch R = 1 ,755     ,33,33,33
BEGIN DESCRIPTION:
Mapping XS c821497c
END DESCRIPTION:
XS GIS Cut Line= 6
      1998471.02     13581301.31      1998929.37     13581783.09
      1999017.91     13581824.76      1999202.81     13581824.76
      1999299.16      13581790.9      1999647.27     13581128.46
#Sta/Elev= 30
    4012  631.94  4166.1  626.91  4333.5  620.06  4406.4  619.22  4434.7  617.24
  4471.7  616.35    4505  616.06  4609.8  612.58  4639.7  610.74  4661.1  610.81
  4665.1   609.2  4665.6   608.4  4670.6   608.4  4671.1   609.2  4764.9  611.34
    4874  610.64    5007  609.72  5068.9  612.42    5104  612.17  5107.4  612.92
  5123.8  611.67  5129.4  613.61  5145.8  613.21  5226.7  615.53  5322.2   616.8
  5360.6  616.09    5411  617.61  5455.9  618.53  5520.5  621.05  5810.2  633.02
#Mann= 12 ,-1 , 0
    4012      .1       0  4333.5     .08       0  4471.7      .1       0
    4505     .05       0  4609.8      .1       0  4665.1     .03       0
  4671.1      .1       0    4874     .05       0    5104      .1       0
    5411     .05       0  5455.9      .1       0  5520.5     .05       0
Bank Sta=4665.1,4671.1
XS Rating Curve= 0 ,0
Exp/Cntr=0.3,0.1

Type RM Length L Ch R = 1 ,722     ,456,456,456
BEGIN DESCRIPTION:
Mapping XS c121c73b
END DESCRIPTION:
XS GIS Cut Line= 6
      1998418.93     13581319.52      1998934.58     13581811.74
       1999012.7     13581856.01      1999267.91     13581842.99
      1999327.81     13581829.97      1999670.75     13581141.49
#Sta/Elev= 30
  3968.2  631.75  4146.1  626.68  4352.7  618.35  4379.4  617.76  4428.9  618.22
  4457.2  616.23  4487.6  615.18  4506.7  614.88  4513.8   615.7  4596.9   612.3
  4669.6  610.52  4705.3  611.29  4742.3  610.35  4909.6  609.89  4961.2  609.43
  4961.7  608.63  4966.7  608.63  4967.2  609.43  5075.3  611.22  5166.1  614.84
  5387.5  618.15  5426.7  617.94  5446.1  618.79    5476  620.32  5516.2   620.5
  5584.4  622.59    5665  625.26  5692.8  626.17  5745.7  627.66  5857.6  633.73
#Mann= 13 ,-1 , 0
  3968.2      .1       0  4352.7     .08       0  4487.6     .05       0
  4596.9      .1       0  4909.6     .05       0  4961.2     .03       0
  4967.2     .05       0  5166.1      .1       0  5446.1     .05       0
    5476      .1       0  5584.4     .05       0    5665      .1       0
  5692.8     .05       0
Bank Sta=4961.2,4967.2
XS Rating Curve= 0 ,0
Exp/Cntr=0.3,0.1

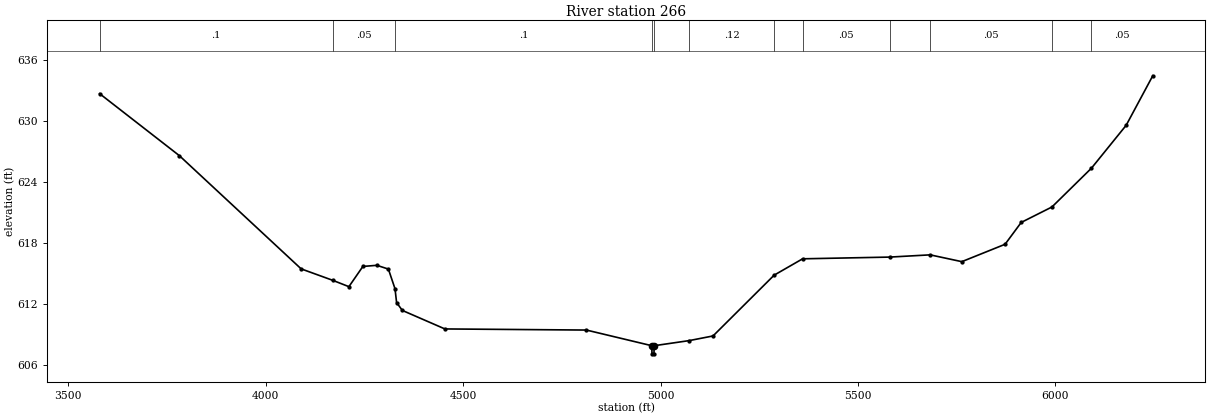
Type RM Length L Ch R = 1 ,266     ,0,0,0
BEGIN DESCRIPTION:
UNT 106 in HW 1.0
END DESCRIPTION:
XS GIS Cut Line= 4
      1998331.29     13581295.26      1998984.06     13582166.77
      1999463.22     13582211.91      1999690.77     13581139.14
#Sta/Elev= 30
  3579.6  632.66  3781.5  626.56  4089.9  615.42  4170.1  614.29  4210.8  613.67
  4246.2  615.66  4281.6  615.77  4310.8   615.4  4327.6  613.46  4331.6   612.1
  4346.2  611.33  4453.9  609.51  4812.3   609.4  4977.8  607.86  4978.3  607.06
  4983.3  607.06  4983.8  607.86  5072.2  608.36  5132.9  608.82  5287.6   614.8
  5359.7  616.41  5580.4  616.58  5682.7   616.8  5762.9  616.13  5872.4  617.84
  5913.3  619.99  5991.1  621.51  6091.2  625.33  6179.1  629.55  6246.4  634.42
#Mann= 12 ,-1 , 0
  3579.6      .1       0  4170.1     .05       0  4327.6      .1       0
  4977.8     .07       0  4983.8      .1       0  5072.2     .12       0
  5287.6      .1       0  5359.7     .05       0  5580.4      .1       0
  5682.7     .05       0  5991.1      .1       0  6091.2     .05       0
Bank Sta=4977.8,4983.8
XS Rating Curve= 0 ,0
Exp/Cntr=0.3,0.1
LCMann Table=0

Chan Stop Cuts=-1
Use User Specified Reach Order=0
Composite Channel Slope=5