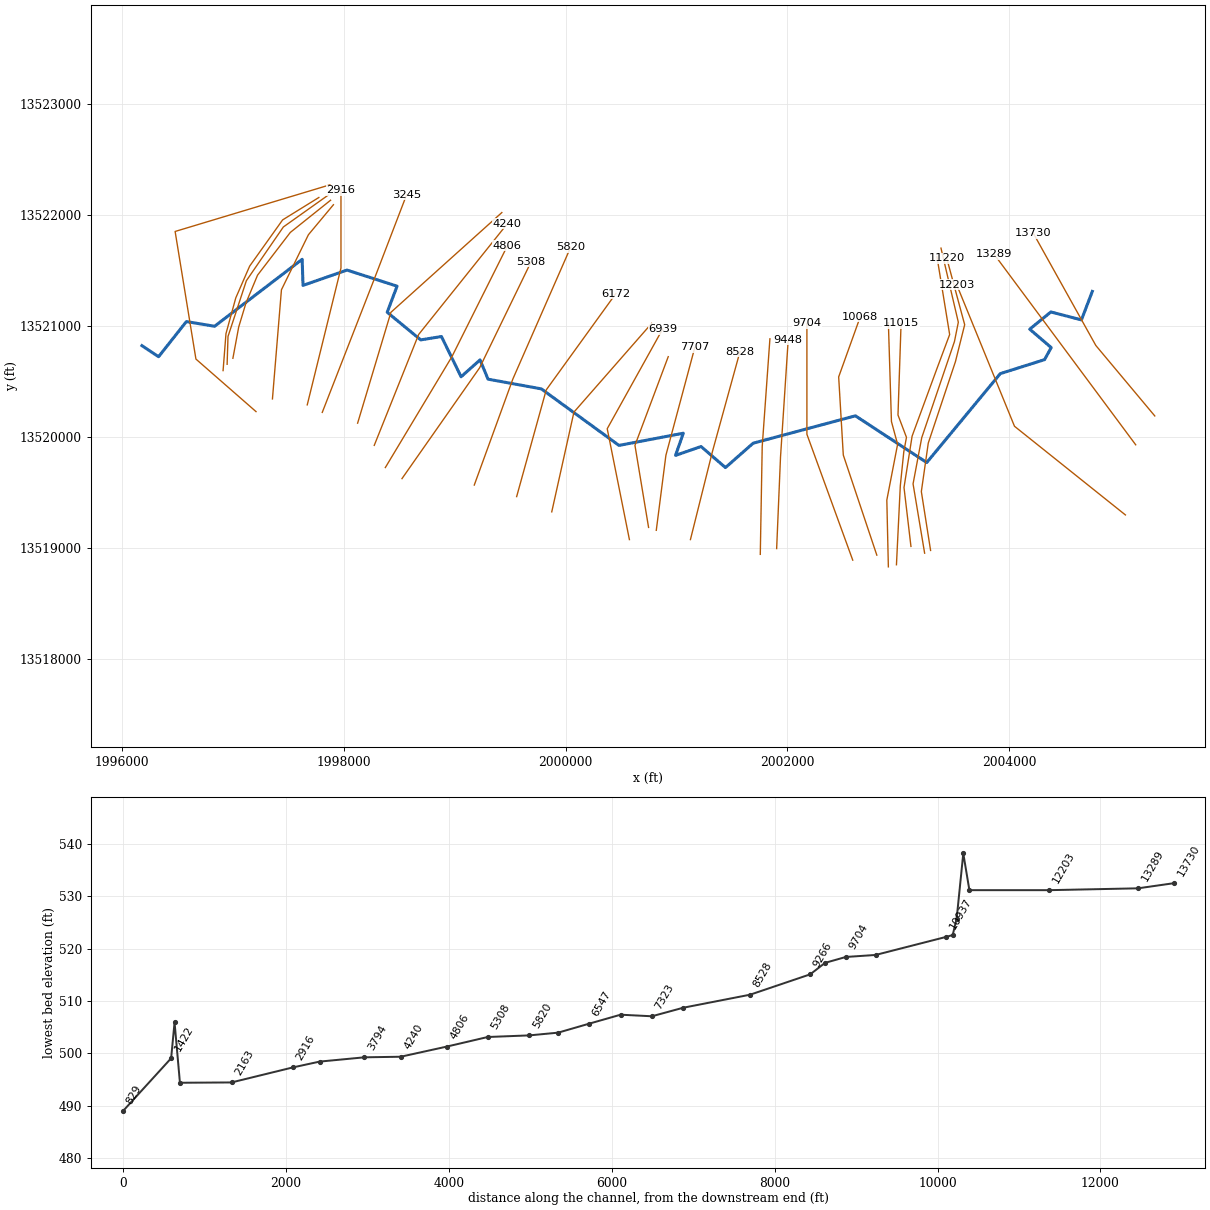
--- UNT 107 in HW.prj (project) ---

Proj Title=UNT 107 in HW Base Level Engineering
Current Plan=p01
Default Exp/Contr=0.3,0.1
English Units
Geom File=g01
Flow File=f01
Plan File=p01
BEGIN DESCRIPTION:
UNT 107 in HW
END DESCRIPTION:

--- UNT 107 in HW.p01 (plan) ---

Plan Title=Multiple Run
Short Identifier=Multiple
Geom File=g01
Flow File=f01
Subcritical Flow
K Sum by GR= 0
Std Step Tol= 0.01
Critical Tol= 0.01
Num of Std Step Trials= 20
Max Error Tol= 0.3
Flow Tol Ratio= 0.001
Split Flow NTrial= 30
Split Flow Tol= 0.02
Split Flow Ratio= 0.02
Log Output Level= 0
Friction Slope Method= 1
Unsteady Friction Slope Method= 2
Unsteady Bridges Friction Slope Method= 1
Parabolic Critical Depth
Global Vel Dist=  1 , 1 , 1
Global Log Level= 0
CheckData=True
Encroach Param= -1, 0, 0, 0
BEGIN DESCRIPTION:
Multiple Run
END DESCRIPTION:

--- UNT 107 in HW.f01 (steady flow) ---

Flow Title=Multiple
Number of Profiles=7
Profile Names=10-year,25-year,50-year,1pct_min,100-year,1pct_plu,500-year
River Rch & RM= UNT 107 in HW,Reach-1,13730
     170     231     281     170     340     678     504
River Rch & RM= UNT 107 in HW,Reach-1,11220
     261     362     445     273     545    1088     831
River Rch & RM= UNT 107 in HW,Reach-1,5308
     331     464     575     355     708    1413    1093
Boundary for River Rch & Prof#=UNT 107 in HW,Reach-1,1
Up Type=0
Dn Type=3
Dn Slope=0.005
Boundary for River Rch & Prof#=UNT 107 in HW,Reach-1,2
Up Type=0
Dn Type=3
Dn Slope=0.005
Boundary for River Rch & Prof#=UNT 107 in HW,Reach-1,3
Up Type=0
Dn Type=3
Dn Slope=0.005
Boundary for River Rch & Prof#=UNT 107 in HW,Reach-1,4
Up Type=0
Dn Type=3
Dn Slope=0.005
Boundary for River Rch & Prof#=UNT 107 in HW,Reach-1,5
Up Type=0
Dn Type=3
Dn Slope=0.005
Boundary for River Rch & Prof#=UNT 107 in HW,Reach-1,6
Up Type=0
Dn Type=3
Dn Slope=0.005
Boundary for River Rch & Prof#=UNT 107 in HW,Reach-1,7
Up Type=0
Dn Type=3
Dn Slope=0.005

--- UNT 107 in HW.g01 (geometry) ---

Geom Title=Existing Conditions

River Reach=UNT 107 in HW,Reach-1
Reach XY= 30
      2004747.81     13521313.72      2004649.72     13521056.78
      2004374.11     13521128.39      2004183.57     13520973.01
      2004377.15     13520807.21      2004317.25     13520698.27
      2003917.95     13520571.97      2003255.19     13519769.89
      2002612.23     13520191.46      2001690.80     13519944.54
      2001440.80     13519724.54      2001220.80     13519914.54
      2000990.80     13519834.54      2001060.80     13520034.54
      2000480.80     13519924.54      1999780.80     13520434.54
      1999300.60     13520522.09      1999228.55     13520695.76
      1999057.72     13520543.68      1998880.64     13520906.87
      1998693.83     13520876.31      1998391.75     13521125.62
      1998480.64     13521361.04      1998029.25     13521506.18
      1997632.72     13521367.98      1997625.08     13521603.40
      1996835.50     13520999.23      1996581.33     13521041.59
      1996330.80     13520724.54      1996180.80     13520824.54

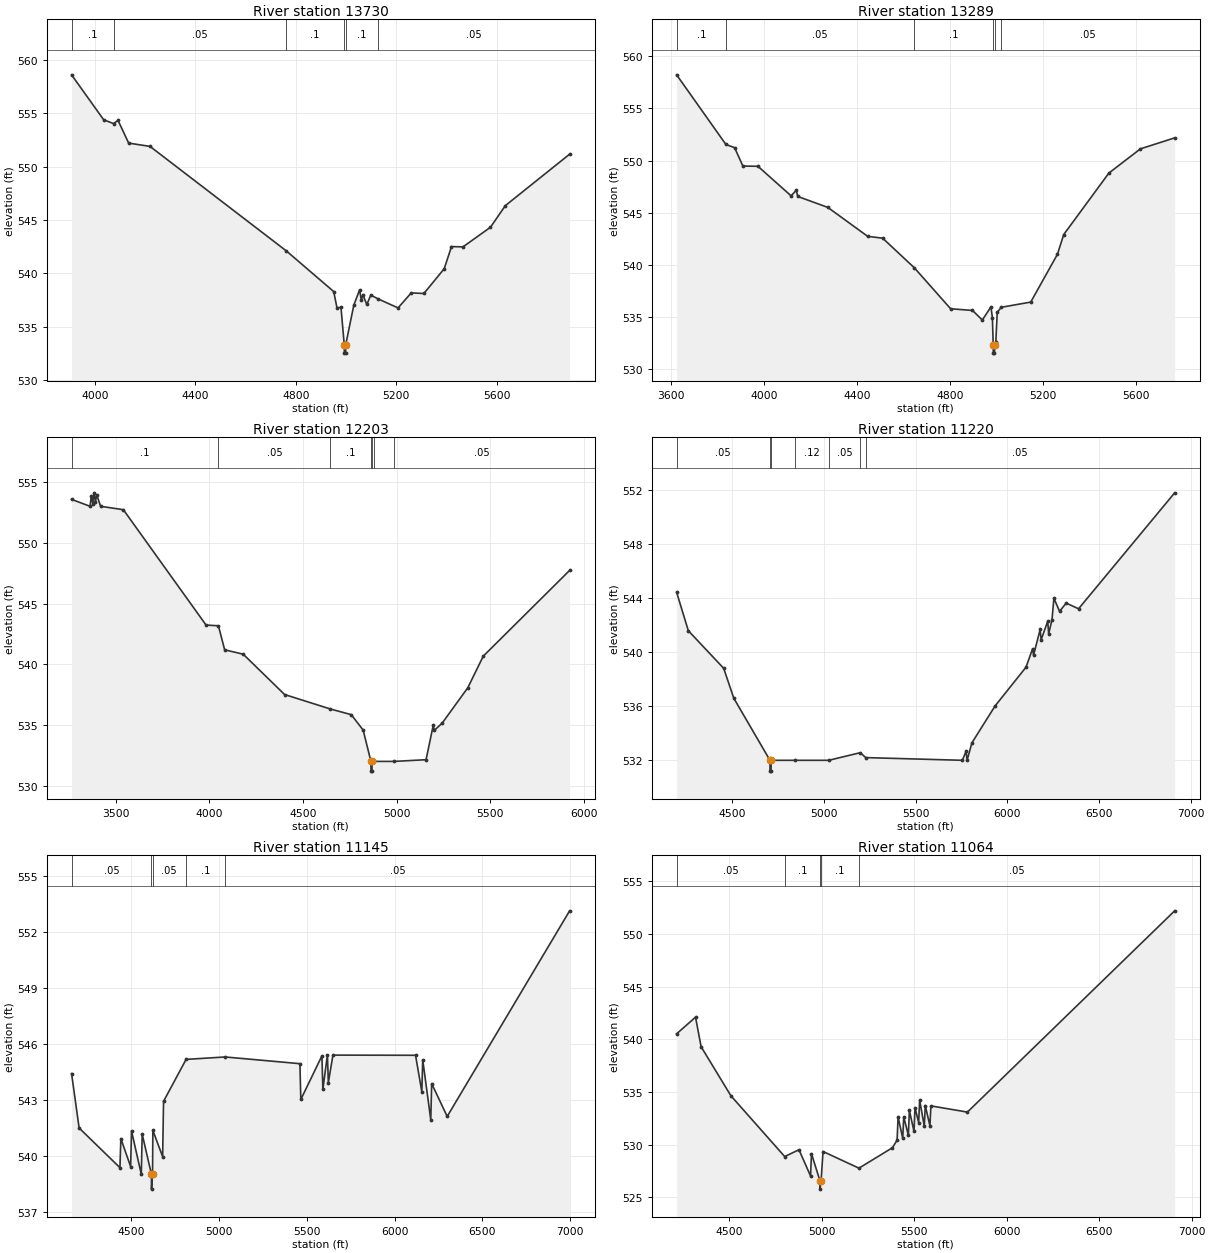
Type RM Length L Ch R = 1,13730,441,441,441
BEGIN DESCRIPTION:
Mapping XS 093eb450
END DESCRIPTION:
XS GIS Cut Line= 3
      2005310.71     13520190.43      2004779.46     13520825.85
      2004216.95     13521836.29
#Sta/Elev= 30
  3906.4  558.62  4034.2  554.41  4073.6  554.05  4091.5  554.35  4133.9  552.22
  4219.0  551.91  4761.9  542.12  4951.1  538.30  4964.0  536.78  4980.0  536.82
  4993.0  533.33  4993.5  532.53  4998.5  532.53  4999.0  533.33  5031.2  537.03
  5054.1  538.46  5061.2  537.49  5066.9  538.01  5082.9  537.09  5098.9  537.97
  5128.2  537.61  5207.5  536.77  5260.1  538.18  5310.4  538.12  5391.6  540.45
  5420.4  542.52  5466.2  542.49  5575.7  544.33  5635.1  546.36  5891.1  551.18
#Mann=6,-1,0
  3906.4     0.1       0  4073.6    0.05       0  4761.9     0.1       0
  4993.0    0.07       0  4999.0     0.1       0  5128.2    0.05       0
Bank Sta=4993,4999
Exp/Cntr=0.3,0.1

Type RM Length L Ch R = 1,13289,1086,1086,1086
BEGIN DESCRIPTION:
Mapping XS 2d2fe733
END DESCRIPTION:
XS GIS Cut Line= 2
      2005138.82     13519930.04      2003862.80     13521648.75
#Sta/Elev= 30
  3623.9  558.21  3835.7  551.54  3873.2  551.23  3908.7  549.47  3973.4  549.45
  4115.8  546.62  4138.2  547.15  4144.5  546.56  4273.8  545.51  4444.9  542.74
  4509.6  542.56  4645.8  539.72  4801.6  535.80  4895.5  535.64  4937.8  534.72
  4974.8  535.98  4981.1  534.96  4984.6  532.35  4985.1  531.55  4990.1  531.55
  4990.6  532.35  4995.7  532.57  5001.9  535.45  5019.2  535.94  5145.9  536.44
  5260.7  541.02  5287.7  542.91  5481.8  548.80  5617.4  551.12  5764.5  552.17
#Mann=6,-1,0
  3623.9     0.1       0  3835.7    0.05       0  4645.8     0.1       0
  4984.6    0.07       0  4990.6     0.1       0  5019.2    0.05       0
Bank Sta=4984.6,4990.6
Exp/Cntr=0.3,0.1

Type RM Length L Ch R = 1,12203,983,983,983
BEGIN DESCRIPTION:
UNT 107 in HW 22.0
END DESCRIPTION:
XS GIS Cut Line= 3
      2005046.17     13519297.23      2004046.18     13520097.22
      2003525.00     13521375.00
#Sta/Elev= 30
  3263.9  553.58  3362.9  553.01  3369.3  553.88  3377.3  553.23  3383.7  554.12
  3391.7  553.39  3398.1  553.96  3419.1  553.01  3540.6  552.73  3982.4  543.23
  4048.4  543.17  4081.7  541.19  4180.9  540.83  4401.8  537.51  4645.8  536.32
  4758.1  535.85  4821.6  534.58  4863.1  532.00  4863.6  531.20  4868.6  531.20
  4869.1  532.00  4881.8  532.00  4986.9  532.00  5157.7  532.14  5195.9  534.97
  5201.3  534.55  5244.0  535.16  5380.4  538.06  5463.3  540.67  5924.5  547.73
#Mann=7,-1,0
  3263.9     0.1       0  4048.4    0.05       0  4645.8     0.1       0
  4863.1    0.03       0  4869.1     0.1       0  4881.8    0.12       0
  4986.9    0.05       0
Bank Sta=4863.1,4869.1
Exp/Cntr=0.3,0.1

Type RM Length L Ch R = 1,11220,75,75,75
BEGIN DESCRIPTION:
Mapping XS 2851d418
END DESCRIPTION:
XS GIS Cut Line= 6
      2003289.87     13518976.94      2003206.54     13519508.14
      2003269.04     13519945.64      2003513.84     13520680.02
      2003597.17     13521013.35      2003436.02     13521611.18
#Sta/Elev= 30
  4196.4  544.42  4260.2  541.58  4453.1  538.80  4508.2  536.59  4705.6  532.00
  4706.1  531.20  4711.4  531.20  4711.9  532.00  4842.7  532.00  5025.8  532.00
  5197.5  532.56  5228.3  532.20  5755.1  532.00  5775.4  532.68  5780.7  532.00
  5807.0  533.29  5933.5  536.02  6102.0  538.88  6138.1  540.25  6143.2  539.77
  6179.3  541.67  6184.5  540.90  6220.5  542.28  6225.7  541.35  6243.9  542.40
  6254.2  543.98  6285.1  543.01  6321.3  543.62  6388.7  543.20  6912.9  551.77
#Mann=7,-1,0
  4196.4    0.05       0  4705.6    0.07       0  4711.9    0.05       0
  4842.7    0.12       0  5025.8    0.05       0  5197.5    0.12       0
  5228.3    0.05       0
Bank Sta=4705.6,4711.9
Exp/Cntr=0.3,0.1

Type RM Length L Ch R = 1,11145,81,81,81
BEGIN DESCRIPTION:
Mapping XS 6f3292f0
END DESCRIPTION:
XS GIS Cut Line= 6
      2003236.06     13518952.48      2003131.89     13519577.50
      2003210.02     13519994.17      2003505.15     13520862.22
      2003539.88     13521035.83      2003383.63     13521704.24
#Sta/Elev= 30
  4159.0  544.42  4202.1  541.50  4434.7  539.37  4439.8  540.93  4495.5  539.43
  4500.6  541.34  4556.3  539.02  4561.4  541.17  4614.0  539.02  4614.5  538.22
  4620.3  539.02  4622.2  541.37  4678.0  539.96  4683.1  542.93  4811.6  545.18
  5034.3  545.31  5460.1  544.95  5465.3  543.03  5585.6  545.37  5590.9  543.57
  5616.9  545.43  5622.2  543.94  5648.3  545.41  6119.0  545.40  6154.8  543.45
  6159.9  545.16  6205.8  541.94  6210.9  543.88  6299.4  542.12  6996.9  553.15
#Mann=5,-1,0
  4159.0    0.05       0  4614.0    0.07       0  4620.3    0.05       0
  4811.6     0.1       0  5034.3    0.05       0
Bank Sta=4614,4620.3
Exp/Cntr=0.3,0.1

Type RM Length L Ch R = 1,11064,49,49,49
BEGIN DESCRIPTION:
Mapping XS 11c338bc
END DESCRIPTION:
XS GIS Cut Line= 6
      2003112.79     13519013.37      2003050.29     13519544.60
      2003123.21     13520008.14      2003347.17     13520617.52
      2003461.75     13520924.81      2003347.17     13521627.92
#Sta/Elev= 30
  4214.5  540.52  4316.8  542.10  4347.0  539.29  4508.1  534.64  4799.1  528.87
  4876.3  529.52  4938.8  527.03  4943.9  529.14  4989.6  526.58  4990.1  525.78
  4995.9  526.58  5006.4  529.35  5200.7  527.77  5381.8  529.71  5407.0  530.43
  5412.3  532.62  5437.5  530.61  5442.8  532.64  5467.9  530.89  5473.3  533.25
  5498.4  531.26  5503.7  533.52  5523.6  532.10  5528.9  534.23  5554.0  531.76
  5559.4  533.71  5584.5  531.79  5589.8  533.68  5787.2  533.09  6908.2  552.19
#Mann=5,-1,0
  4214.5    0.05       0  4799.1     0.1       0  4989.6    0.07       0
  4995.9     0.1       0  5200.7    0.05       0
Bank Sta=4989.6,4995.9
Exp/Cntr=0.3,0.1

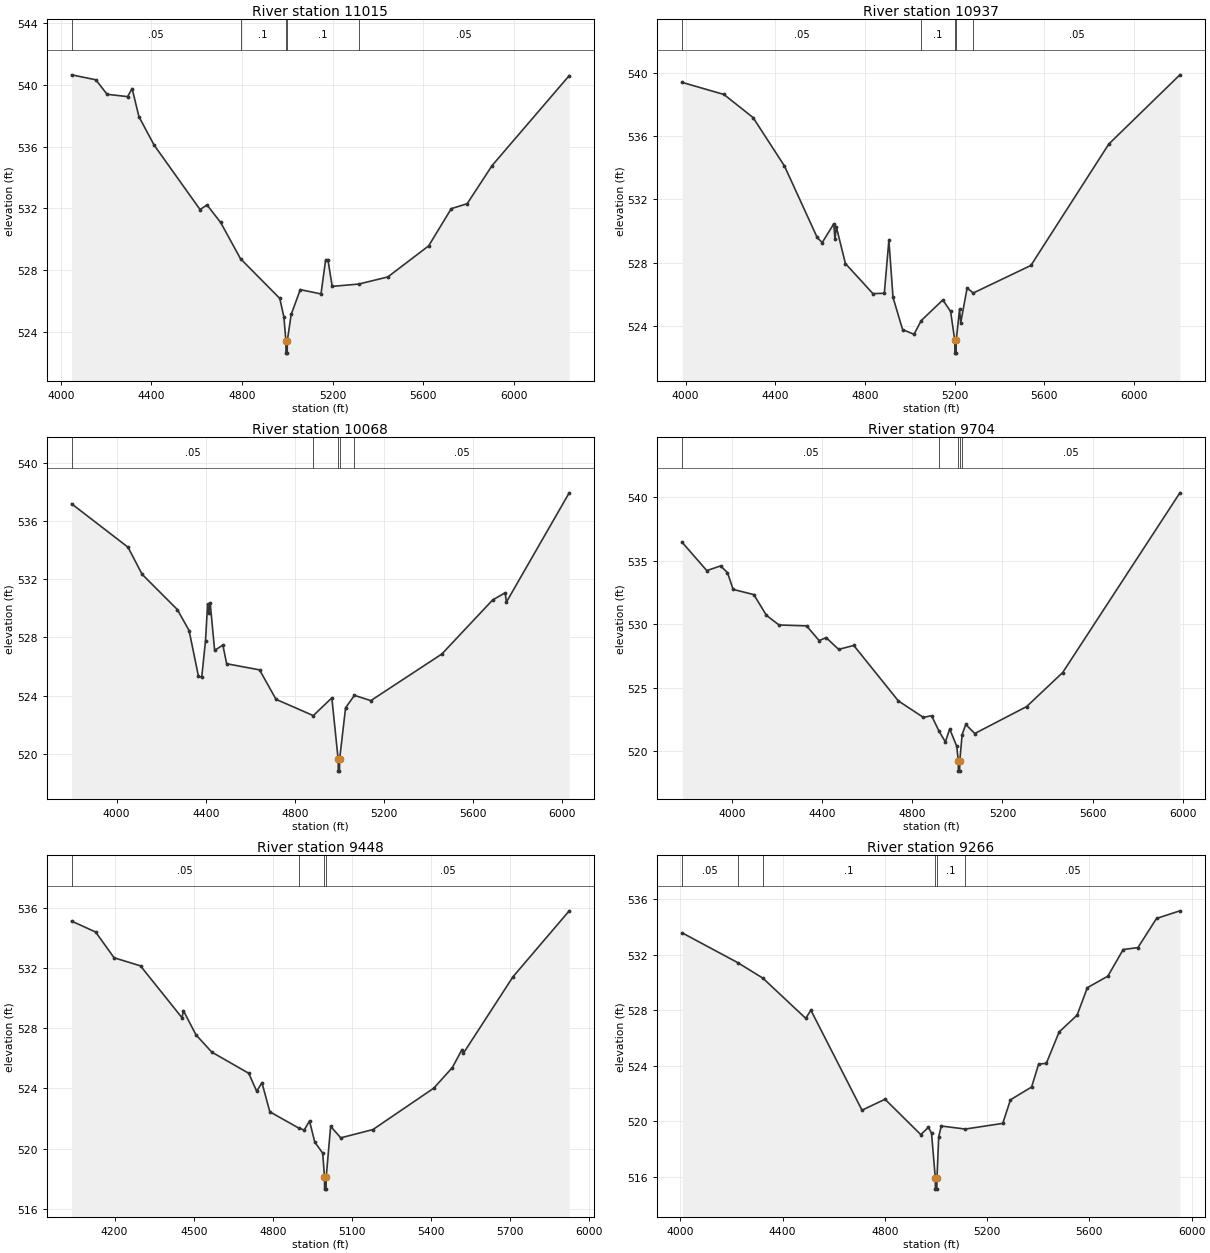
Type RM Length L Ch R = 1,11015,78,78,78
BEGIN DESCRIPTION:
Mapping XS 2a431982
END DESCRIPTION:
XS GIS Cut Line= 6
      2002982.14     13518847.99      2003016.87     13519559.82
      2003048.12     13519865.38      2003072.42     13519997.32
      2002996.03     13520198.71      2003023.81     13521025.07
#Sta/Elev= 30
  4047.3  540.64  4154.4  540.32  4204.0  539.38  4294.6  539.23  4314.6  539.75
  4344.7  537.93  4411.8  536.09  4614.5  531.92  4645.0  532.22  4705.1  531.09
  4792.9  528.74  4966.2  526.17  4984.3  524.98  4993.2  523.43  4993.7  522.63
  4999.0  522.63  4999.5  523.43  5016.5  525.13  5056.7  526.74  5148.1  526.46
  5168.4  528.64  5178.6  528.68  5197.6  526.95  5314.8  527.10  5443.0  527.56
  5623.1  529.57  5723.1  531.98  5793.2  532.30  5903.2  534.77  6243.5  540.59
#Mann=5,-1,0
  4047.3    0.05       0  4792.9     0.1       0  4993.2    0.07       0
  4999.5     0.1       0  5314.8    0.05       0
Bank Sta=4993.2,4999.5
Exp/Cntr=0.3,0.1

Type RM Length L Ch R = 1,10937,869,869,869
BEGIN DESCRIPTION:
UNT 107 in HW 21.0
END DESCRIPTION:
XS GIS Cut Line= 5
      2002909.23     13518828.95      2002895.34     13519431.35
      2002992.56     13519934.82      2002937.00     13520139.68
      2002909.29     13521031.86
#Sta/Elev= 30
  3984.7  539.38  4170.8  538.62  4300.8  537.16  4440.9  534.10  4586.6  529.59
  4609.0  529.26  4660.9  530.45  4666.0  529.47  4672.5  530.24  4712.7  527.94
  4835.4  526.04  4886.3  526.06  4906.7  529.42  4925.1  525.80  4967.8  523.77
  5018.7  523.47  5051.2  524.34  5147.4  525.64  5182.1  524.91  5200.7  523.08
  5201.2  522.28  5206.5  522.28  5207.0  523.08  5221.9  525.05  5227.1  524.19
  5255.6  526.39  5283.3  526.08  5540.3  527.82  5887.9  535.49  6204.9  539.86
#Mann=5,-1,0
  3984.7    0.05       0  5051.2     0.1       0  5200.7   0.035       0
  5207.0     0.1       0  5283.3    0.05       0
Bank Sta=5200.7,5207
Exp/Cntr=0.3,0.1

Type RM Length L Ch R = 1,10068,364,364,364
BEGIN DESCRIPTION:
Mapping XS 8458eabc
END DESCRIPTION:
XS GIS Cut Line= 4
      2002805.07     13518934.80      2002502.98     13519837.60
      2002461.31     13520542.46      2002655.75     13521084.12
#Sta/Elev= 30
  3797.5  537.17  4050.8  534.19  4114.1  532.33  4272.2  529.91  4325.0  528.47
  4367.1  525.33  4381.8  525.27  4398.8  527.78  4408.1  530.29  4413.4  529.68
  4419.9  530.34  4439.7  527.11  4476.6  527.47  4493.7  526.19  4641.3  525.77
  4715.1  523.75  4882.5  522.63  4965.8  523.85  4994.1  519.62  4994.6  518.82
  5000.0  518.82  5000.5  519.62  5027.4  523.17  5067.2  524.02  5140.7  523.66
  5459.6  526.86  5687.6  530.57  5743.8  531.06  5749.1  530.42  6031.1  537.92
#Mann=5,-1,0
  3797.5    0.05       0  4882.5     0.1       0  4994.1    0.07       0
  5000.5     0.1       0  5067.2    0.05       0
Bank Sta=4994.1,5000.5
Exp/Cntr=0.3,0.1

Type RM Length L Ch R = 1,9704,256,256,256
BEGIN DESCRIPTION:
UNT 107 in HW 20.0
END DESCRIPTION:
XS GIS Cut Line= 3
      2002588.05     13518889.69      2002175.00     13520025.00
      2002175.00     13521024.99
#Sta/Elev= 30
  3779.3  536.44  3888.3  534.22  3949.5  534.59  3980.1  534.06  4005.3  532.74
  4097.1  532.33  4152.9  530.70  4208.8  529.94  4331.1  529.87  4387.0  528.71
  4417.6  528.95  4473.4  528.02  4540.5  528.33  4738.1  523.97  4849.1  522.67
  4885.7  522.80  4919.4  521.56  4946.9  520.74  4966.1  521.76  4997.4  520.39
  5004.2  519.24  5004.7  518.44  5010.2  518.44  5010.7  519.24  5021.3  521.32
  5037.4  522.11  5077.4  521.40  5307.4  523.52  5467.4  526.20  5987.4  540.34
#Mann=5,-1,0
  3779.3    0.05       0  4919.4    0.12       0  5004.2    0.07       0
  5010.7    0.12       0  5021.3    0.05       0
Bank Sta=5004.2,5010.7
Exp/Cntr=0.3,0.1

Type RM Length L Ch R = 1,9448,182,182,182
BEGIN DESCRIPTION:
UNT 107 in HW 19.0
END DESCRIPTION:
XS GIS Cut Line= 3
      2001902.28     13518993.82      2001937.00     13519818.50
      2002006.45     13520877.52
#Sta/Elev= 30
  4036.8  535.13  4128.1  534.40  4198.1  532.69  4298.2  532.15  4455.7  528.70
  4460.7  529.18  4508.4  527.57  4568.4  526.42  4708.6  525.01  4738.6  523.82
  4758.6  524.38  4788.6  522.45  4898.1  521.37  4918.8  521.24  4938.9  521.84
  4958.9  520.44  4989.0  519.70  4995.7  518.11  4996.2  517.31  5001.7  517.31
  5002.2  518.11  5019.0  521.48  5057.5  520.72  5179.4  521.27  5409.9  524.02
  5480.0  525.38  5517.2  526.59  5522.2  526.34  5710.5  531.43  5923.5  535.81
#Mann=4,-1,0
  4036.8    0.05       0  4898.1    0.12       0  4995.7   0.035       0
  5002.2    0.05       0
Bank Sta=4995.7,5002.2
Exp/Cntr=0.3,0.1

Type RM Length L Ch R = 1,9266,738,738,738
BEGIN DESCRIPTION:
UNT 107 in HW 18.0
END DESCRIPTION:
XS GIS Cut Line= 3
      2001754.71     13518941.75      2001772.07     13519913.99
      2001841.52     13520886.21
#Sta/Elev= 30
  4007.0  533.59  4223.8  531.45  4322.4  530.33  4490.3  527.43  4510.3  528.02
  4710.4  520.81  4800.4  521.60  4940.4  519.05  4970.4  519.58  4982.4  519.15
  4997.2  515.92  4997.7  515.12  5003.2  515.12  5003.7  515.92  5010.5  518.89
  5020.5  519.67  5114.4  519.45  5261.1  519.86  5291.2  521.56  5373.9  522.48
  5401.5  524.13  5431.6  524.19  5481.7  526.45  5551.9  527.66  5592.0  529.64
  5672.2  530.47  5732.3  532.39  5789.9  532.53  5862.7  534.63  5954.1  535.18
#Mann=6,-1,0
  4007.0    0.05       0  4223.8    0.08       0  4322.4     0.1       0
  4997.2    0.07       0  5003.7     0.1       0  5114.4    0.05       0
Bank Sta=4997.2,5003.7
Exp/Cntr=0.3,0.1

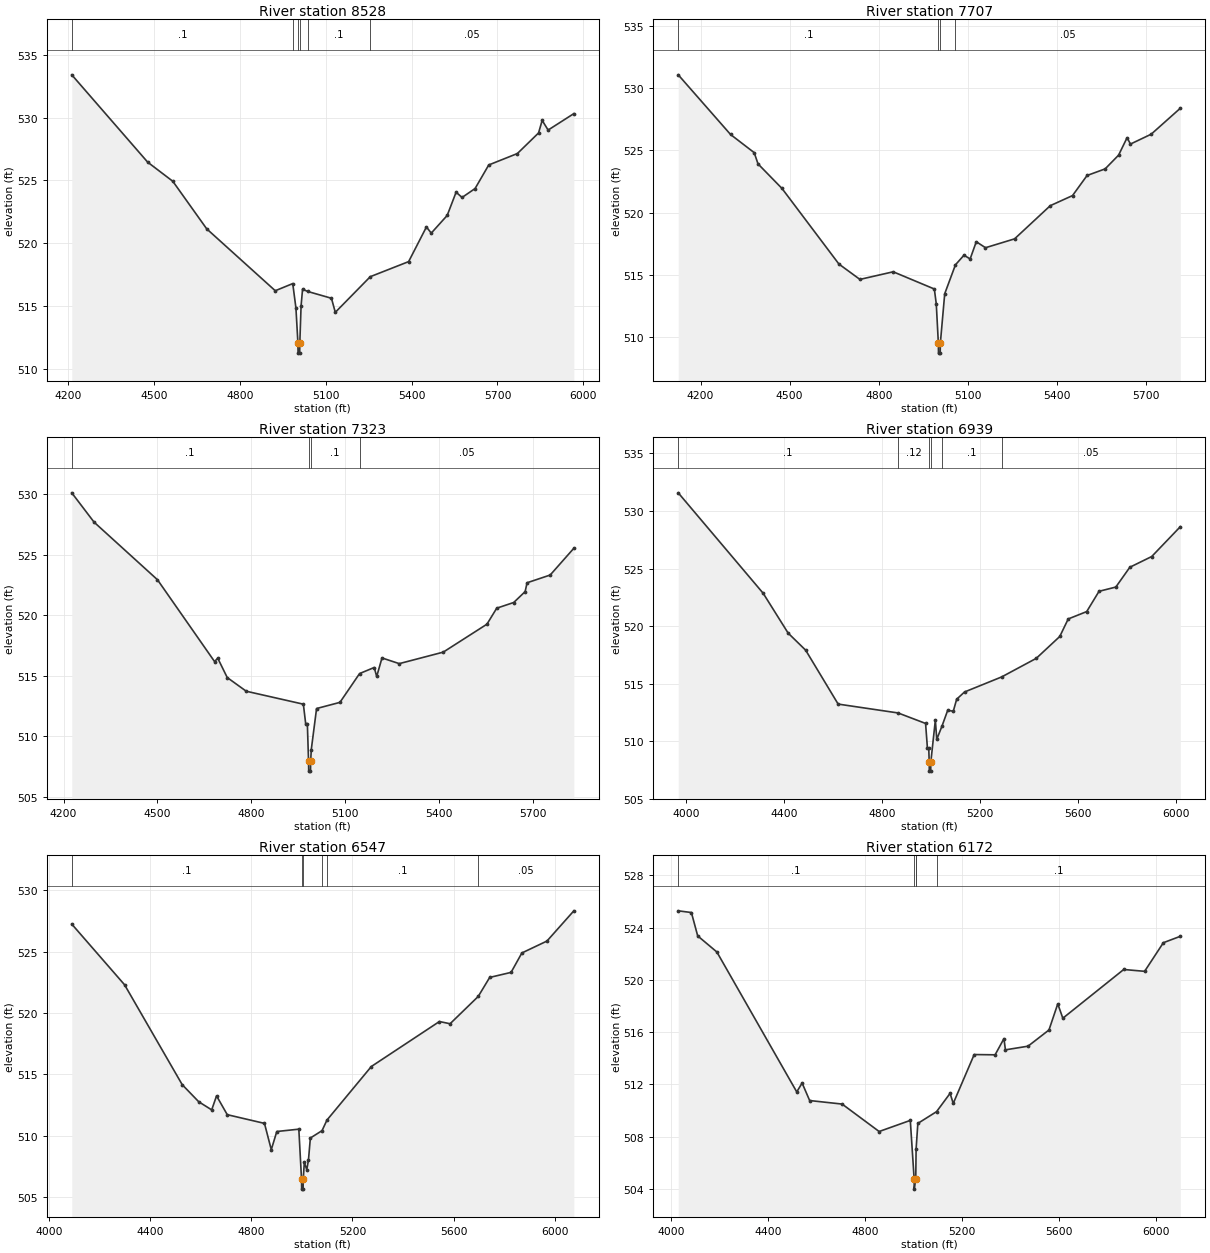
Type RM Length L Ch R = 1,8528,821,821,821
BEGIN DESCRIPTION:
UNT 107 in HW 17.0
END DESCRIPTION:
XS GIS Cut Line= 3
      2001125.00     13519074.99      2001325.00     13519875.00
      2001571.96     13520771.68
#Sta/Elev= 30
  4212.2  533.40  4477.6  526.44  4565.3  524.92  4683.8  521.13  4923.4  516.20
  4984.5  516.77  4995.6  514.83  5002.6  512.03  5003.1  511.23  5008.7  511.23
  5009.2  512.03  5013.6  514.99  5018.8  516.32  5037.2  516.14  5119.8  515.60
  5133.2  514.48  5255.5  517.32  5389.5  518.52  5451.7  521.28  5468.6  520.79
  5524.3  522.20  5555.4  524.05  5576.2  523.63  5621.7  524.34  5669.5  526.22
  5769.6  527.13  5843.6  528.77  5856.2  529.77  5877.0  529.00  5966.9  530.31
#Mann=6,-1,0
  4212.2     0.1       0  4984.5    0.12       0  5002.6    0.07       0
  5009.2    0.12       0  5037.2     0.1       0  5255.5    0.05       0
Bank Sta=5002.6,5009.2
Exp/Cntr=0.3,0.1

Type RM Length L Ch R = 1,7707,384,384,384
BEGIN DESCRIPTION:
UNT 107 in HW 16.0
END DESCRIPTION:
XS GIS Cut Line= 3
      2000817.21     13519158.76      2000904.02     13519835.86
      2001164.43     13520808.05
#Sta/Elev= 30
  4125.1  531.05  4301.0  526.27  4380.7  524.81  4393.5  523.91  4474.2  521.94
  4665.7  515.88  4736.3  514.65  4848.3  515.26  4986.7  513.88  4993.2  512.69
  5000.2  509.54  5000.7  508.74  5006.4  508.74  5006.9  509.54  5021.6  513.50
  5057.7  515.82  5086.4  516.59  5107.1  516.29  5127.8  517.67  5158.8  517.19
  5256.6  517.90  5376.7  520.56  5451.6  521.37  5500.5  522.98  5561.3  523.51
  5606.5  524.61  5635.1  526.01  5646.5  525.50  5716.2  526.29  5814.2  528.37
#Mann=4,-1,0
  4125.1     0.1       0  5000.2    0.07       0  5006.9     0.1       0
  5057.7    0.05       0
Bank Sta=5000.2,5006.9
Exp/Cntr=0.3,0.1

Type RM Length L Ch R = 1,7323,384,384,384
BEGIN DESCRIPTION:
UNT 107 in HW 15.0
END DESCRIPTION:
XS GIS Cut Line= 3
      2000747.77     13519184.79      2000625.00     13519925.00
      2000924.99     13520724.98
#Sta/Elev= 30
  4226.2  530.10  4297.4  527.68  4500.1  522.92  4682.6  516.16  4692.7  516.44
  4723.1  514.84  4783.9  513.71  4966.4  512.64  4974.0  510.99  4979.2  510.99
  4983.0  507.91  4983.5  507.11  4989.2  507.11  4989.7  507.91  4991.7  508.89
  5008.6  512.28  5083.3  512.79  5146.1  515.17  5192.8  515.67  5200.8  514.93
  5217.7  516.46  5272.9  515.99  5413.5  516.94  5553.2  519.25  5584.4  520.57
  5638.7  521.04  5675.2  521.94  5681.4  522.67  5755.3  523.31  5830.9  525.52
#Mann=4,-1,0
  4226.2     0.1       0  4983.0    0.07       0  4989.7     0.1       0
  5146.1    0.05       0
Bank Sta=4983,4989.7
Exp/Cntr=0.3,0.1

Type RM Length L Ch R = 1,6939,392,392,392
BEGIN DESCRIPTION:
UNT 107 in HW 14.0
END DESCRIPTION:
XS GIS Cut Line= 3
      2000575.00     13519075.01      2000375.00     13520075.00
      2000875.02     13520975.04
#Sta/Elev= 30
  3969.3  531.57  4316.0  522.85  4418.0  519.39  4489.4  517.91  4622.0  513.23
  4866.7  512.46  4978.9  511.55  4986.5  509.40  4991.9  509.40  4993.7  508.21
  4994.2  507.41  4999.9  507.41  5000.4  508.21  5018.8  511.84  5024.6  510.17
  5046.3  511.34  5069.2  512.69  5092.0  512.61  5105.8  513.65  5137.8  514.28
  5289.7  515.59  5430.7  517.20  5526.7  519.10  5561.1  520.62  5636.6  521.26
  5686.9  523.02  5755.5  523.39  5812.7  525.11  5902.0  526.04  6018.7  528.63
#Mann=6,-1,0
  3969.3     0.1       0  4866.7    0.12       0  4993.7    0.07       0
  5000.4    0.12       0  5046.3     0.1       0  5289.7    0.05       0
Bank Sta=4993.7,5000.4
Exp/Cntr=0.3,0.1

Type RM Length L Ch R = 1,6547,375,375,375
BEGIN DESCRIPTION:
UNT 107 in HW 13.0
END DESCRIPTION:
XS GIS Cut Line= 3
      1999874.99     13519324.96      2000075.00     13520225.00
      2000775.00     13521025.00
#Sta/Elev= 30
  4090.3  527.24  4299.1  522.30  4527.0  514.17  4592.3  512.78  4643.5  512.12
  4662.7  513.26  4705.0  511.73  4852.2  511.02  4879.1  508.88  4900.9  510.36
  4988.0  510.55  4998.7  506.47  4999.2  505.67  5004.9  505.67  5005.4  506.47
  5009.7  507.85  5019.4  507.25  5026.1  508.04  5033.6  509.83  5079.8  510.43
  5099.2  511.29  5274.7  515.65  5543.8  519.31  5586.0  519.13  5697.2  521.35
  5742.6  522.90  5827.1  523.31  5869.8  524.89  5969.0  525.86  6075.3  528.32
#Mann=6,-1,0
  4090.3     0.1       0  4998.7    0.07       0  5005.4     0.1       0
  5079.8    0.12       0  5099.2     0.1       0  5697.2    0.05       0
Bank Sta=4998.7,5005.4
Exp/Cntr=0.3,0.1

Type RM Length L Ch R = 1,6172,352,352,352
BEGIN DESCRIPTION:
UNT 107 in HW 12.0
END DESCRIPTION:
XS GIS Cut Line= 3
      1999558.54     13519462.64      1999825.00     13520425.00
      2000452.64     13521294.21
#Sta/Elev= 30
  4029.6  525.28  4083.9  525.15  4109.9  523.36  4188.9  522.13  4518.4  511.42
  4540.5  512.10  4571.6  510.76  4705.5  510.49  4858.2  508.39  4986.7  509.24
  5002.5  504.78  5003.0  503.98  5009.2  504.78  5010.6  507.04  5017.8  509.01
  5095.0  509.91  5150.8  511.31  5163.8  510.54  5250.2  514.28  5336.5  514.26
  5372.9  515.50  5379.0  514.64  5472.2  514.92  5558.6  516.16  5594.9  518.16
  5615.8  517.06  5866.9  520.79  5953.1  520.65  6030.4  522.84  6100.3  523.33
#Mann=5,-1,0
  4029.6     0.1       0  5002.5    0.07       0  5009.2     0.1       0
  5010.6    0.12       0  5095.0     0.1       0
Bank Sta=5002.5,5009.2
Exp/Cntr=0.3,0.1

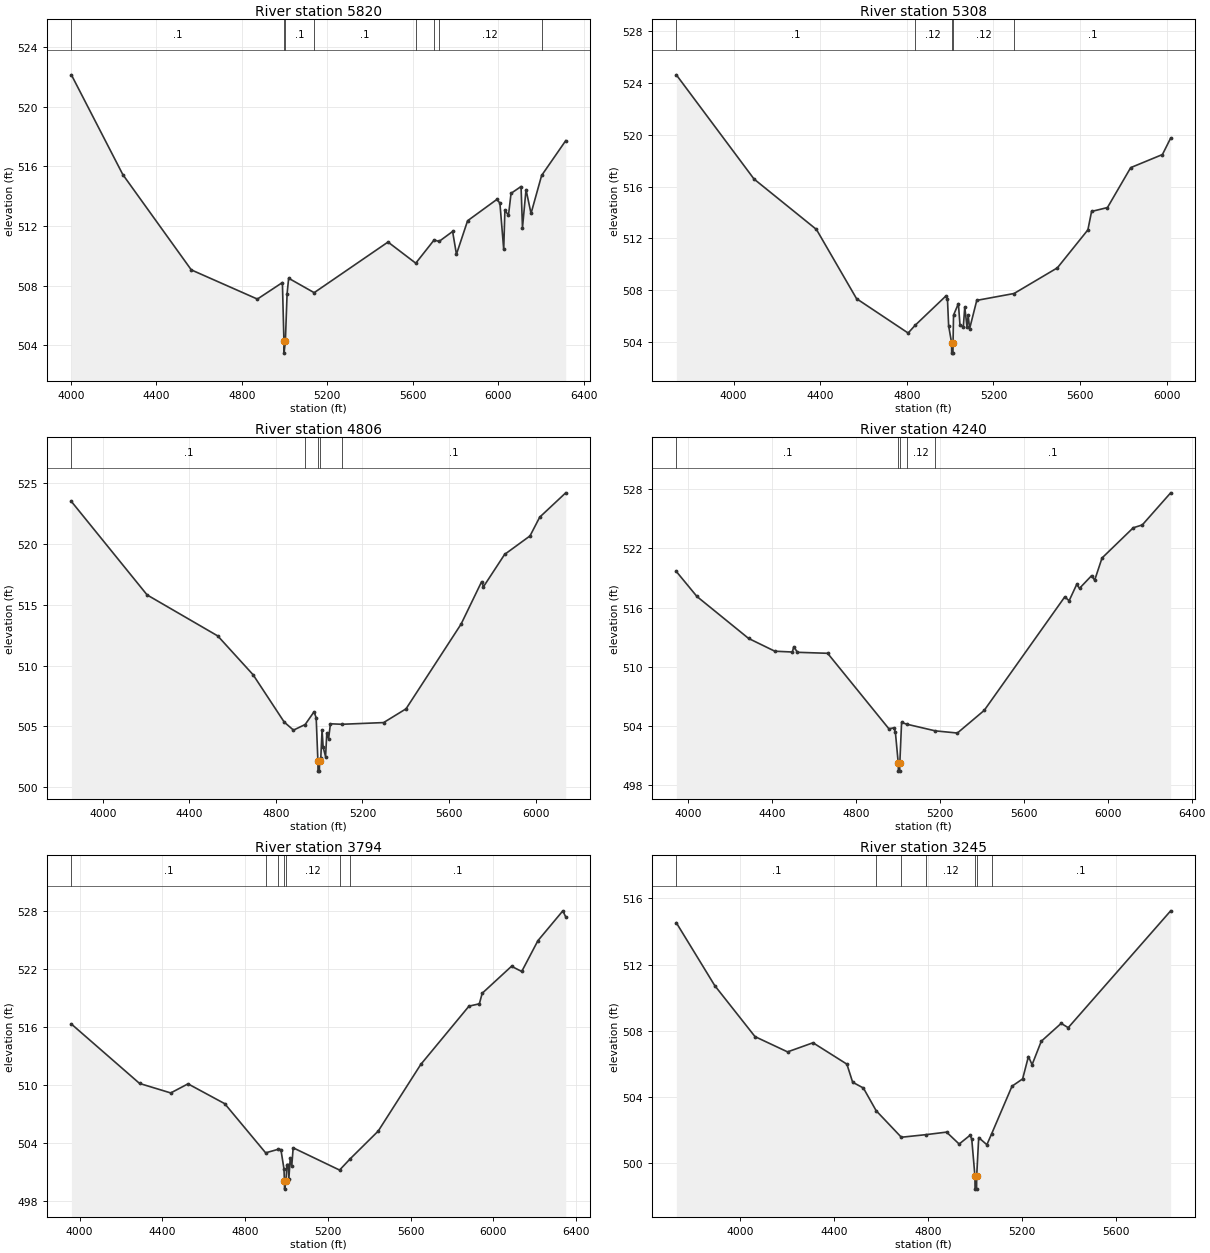
Type RM Length L Ch R = 1,5820,512,512,512
BEGIN DESCRIPTION:
UNT 107 in HW 11.0
END DESCRIPTION:
XS GIS Cut Line= 3
      1999176.60     13519566.80      1999525.00     13520525.00
      2000044.45     13521710.41
#Sta/Elev= 30
  4002.2  522.15  4243.0  515.45  4563.5  509.05  4872.8  507.09  4989.9  508.20
  4997.1  504.26  4997.6  503.46  5003.8  504.26  5011.8  507.44  5019.1  508.49
  5138.6  507.52  5484.2  510.92  5614.1  509.50  5700.0  511.06  5723.2  510.96
  5786.6  511.63  5804.5  510.10  5856.7  512.35  5993.5  513.78  6007.9  513.54
  6025.8  510.42  6031.3  513.05  6048.1  512.72  6060.1  514.19  6106.9  514.65
  6113.6  511.88  6130.2  514.44  6153.6  512.84  6203.2  515.39  6316.0  517.73
#Mann=8,-1,0
  4002.2     0.1       0  4997.1    0.07       0  5003.8     0.1       0
  5138.6     0.1       0  5614.1    0.12       0  5700.0     0.1       0
  5723.2    0.12       0  6203.2     0.1       0
Bank Sta=4997.1,5003.8
Exp/Cntr=0.3,0.1

Type RM Length L Ch R = 1,5308,502,502,502
BEGIN DESCRIPTION:
UNT 107 in HW 10.0
END DESCRIPTION:
XS GIS Cut Line= 3
      1998524.99     13519624.98      1999225.00     13520625.00
      1999688.56     13521580.29
#Sta/Elev= 30
  3736.0  524.62  4094.8  516.58  4383.0  512.69  4568.2  507.35  4806.3  504.70
  4838.2  505.29  4978.9  507.53  4987.8  507.36  4993.3  505.26  5006.9  503.95
  5007.4  503.15  5013.2  503.15  5013.7  503.95  5015.9  506.08  5038.4  506.97
  5045.6  505.34  5061.0  505.16  5067.8  506.71  5078.0  505.20  5083.6  506.06
  5090.1  505.03  5123.2  507.22  5295.4  507.75  5495.4  509.73  5636.3  512.66
  5653.3  514.08  5726.6  514.38  5833.9  517.46  5980.4  518.47  6018.5  519.74
#Mann=5,-1,0
  3736.0     0.1       0  4838.2    0.12       0  5006.9    0.07       0
  5013.7    0.12       0  5295.4     0.1       0
Bank Sta=5006.9,5013.7
Exp/Cntr=0.3,0.1

Type RM Length L Ch R = 1,4806,566,566,566
BEGIN DESCRIPTION:
UNT 107 in HW 9.0
END DESCRIPTION:
XS GIS Cut Line= 3
      1998374.98     13519724.97      1998975.00     13520725.00
      1999475.02     13521725.04
#Sta/Elev= 30
  3855.3  523.48  4205.2  515.80  4531.7  512.43  4695.0  509.24  4838.8  505.35
  4881.6  504.69  4935.6  505.15  4976.8  506.20  4986.5  505.70  4994.5  502.12
  4995.0  501.32  5001.3  501.32  5001.9  502.12  5007.9  502.43  5013.7  504.71
  5018.6  503.30  5029.9  502.51  5035.5  504.43  5043.9  503.99  5052.3  505.21
  5105.9  505.17  5298.2  505.31  5401.7  506.44  5656.0  513.40  5751.0  516.89
  5759.4  516.47  5857.3  519.13  5974.6  520.65  6019.4  522.19  6139.6  524.19
#Mann=5,-1,0
  3855.3     0.1       0  4935.6    0.12       0  4994.5    0.07       0
  5001.9    0.12       0  5105.9     0.1       0
Bank Sta=4994.5,5001.9
Exp/Cntr=0.3,0.1

Type RM Length L Ch R = 1,4240,446,446,446
BEGIN DESCRIPTION:
UNT 107 in HW 8.0
END DESCRIPTION:
XS GIS Cut Line= 3
      1998275.00     13519925.00      1998675.00     13520925.00
      1999475.03     13521925.04
#Sta/Elev= 30
  3942.2  519.66  4040.5  517.12  4286.8  512.86  4412.1  511.56  4495.5  511.48
  4502.3  512.02  4519.8  511.45  4663.8  511.35  4956.0  503.68  4980.2  503.78
  4986.9  503.34  5000.7  500.18  5001.3  499.38  5007.6  499.38  5008.1  500.18
  5016.5  504.33  5040.9  504.15  5177.3  503.47  5282.6  503.25  5410.6  505.55
  5794.8  517.08  5815.6  516.69  5851.6  518.34  5865.2  517.95  5922.9  519.24
  5937.3  518.77  5972.5  521.03  6121.4  524.10  6164.6  524.39  6299.9  527.65
#Mann=5,-1,0
  3942.2     0.1       0  5000.7    0.07       0  5008.1     0.1       0
  5040.9    0.12       0  5177.3     0.1       0
Bank Sta=5000.7,5008.1
Exp/Cntr=0.3,0.1

Type RM Length L Ch R = 1,3794,549,549,549
BEGIN DESCRIPTION:
UNT 107 in HW 7.0
END DESCRIPTION:
XS GIS Cut Line= 3
      1998125.01     13520125.04      1998425.00     13521125.00
      1999425.03     13522025.03
#Sta/Elev= 30
  3960.6  516.33  4290.3  510.19  4440.8  509.21  4524.3  510.15  4701.8  508.10
  4899.6  503.02  4957.7  503.37  4973.3  503.36  4988.1  501.37  4990.5  500.07
  4991.0  499.27  4997.9  500.07  5002.0  501.81  5008.0  501.81  5011.7  500.32
  5018.4  502.46  5025.9  501.69  5032.6  503.54  5256.9  501.24  5308.5  502.41
  5443.7  505.27  5649.2  512.15  5882.4  518.18  5932.5  518.42  5946.3  519.51
  6088.0  522.30  6137.3  521.76  6215.4  524.94  6336.1  528.03  6350.0  527.40
#Mann=7,-1,0
  3960.6     0.1       0  4899.6    0.05       0  4957.7    0.12       0
  4990.5    0.07       0  4997.9    0.12       0  5256.9    0.07       0
  5308.5     0.1       0
Bank Sta=4990.5,4997.9
Exp/Cntr=0.3,0.1

Type RM Length L Ch R = 1,3245,329,329,329
BEGIN DESCRIPTION:
UNT 107 in HW 6.0
END DESCRIPTION:
XS GIS Cut Line= 3
      1997806.37     13520222.55      1998275.00     13521425.00
      1998566.77     13522186.05
#Sta/Elev= 30
  3728.8  514.52  3892.4  510.73  4064.0  507.65  4202.6  506.73  4311.0  507.28
  4455.3  505.99  4479.8  504.90  4525.6  504.55  4580.0  503.18  4687.2  501.58
  4794.3  501.74  4879.8  501.89  4933.5  501.17  4979.9  501.70  4987.1  501.47
  5000.6  499.25  5001.2  498.45  5007.6  498.45  5008.2  499.25  5016.7  501.56
  5051.5  501.13  5071.6  501.78  5158.6  504.66  5203.8  505.10  5228.5  506.45
  5244.2  505.96  5283.2  507.37  5368.0  508.45  5398.0  508.19  5834.4  515.24
#Mann=7,-1,0
  3728.8     0.1       0  4580.0    0.05       0  4687.2    0.07       0
  4794.3    0.12       0  5000.6    0.07       0  5008.2    0.12       0
  5071.6     0.1       0
Bank Sta=5000.6,5008.2
Exp/Cntr=0.3,0.1

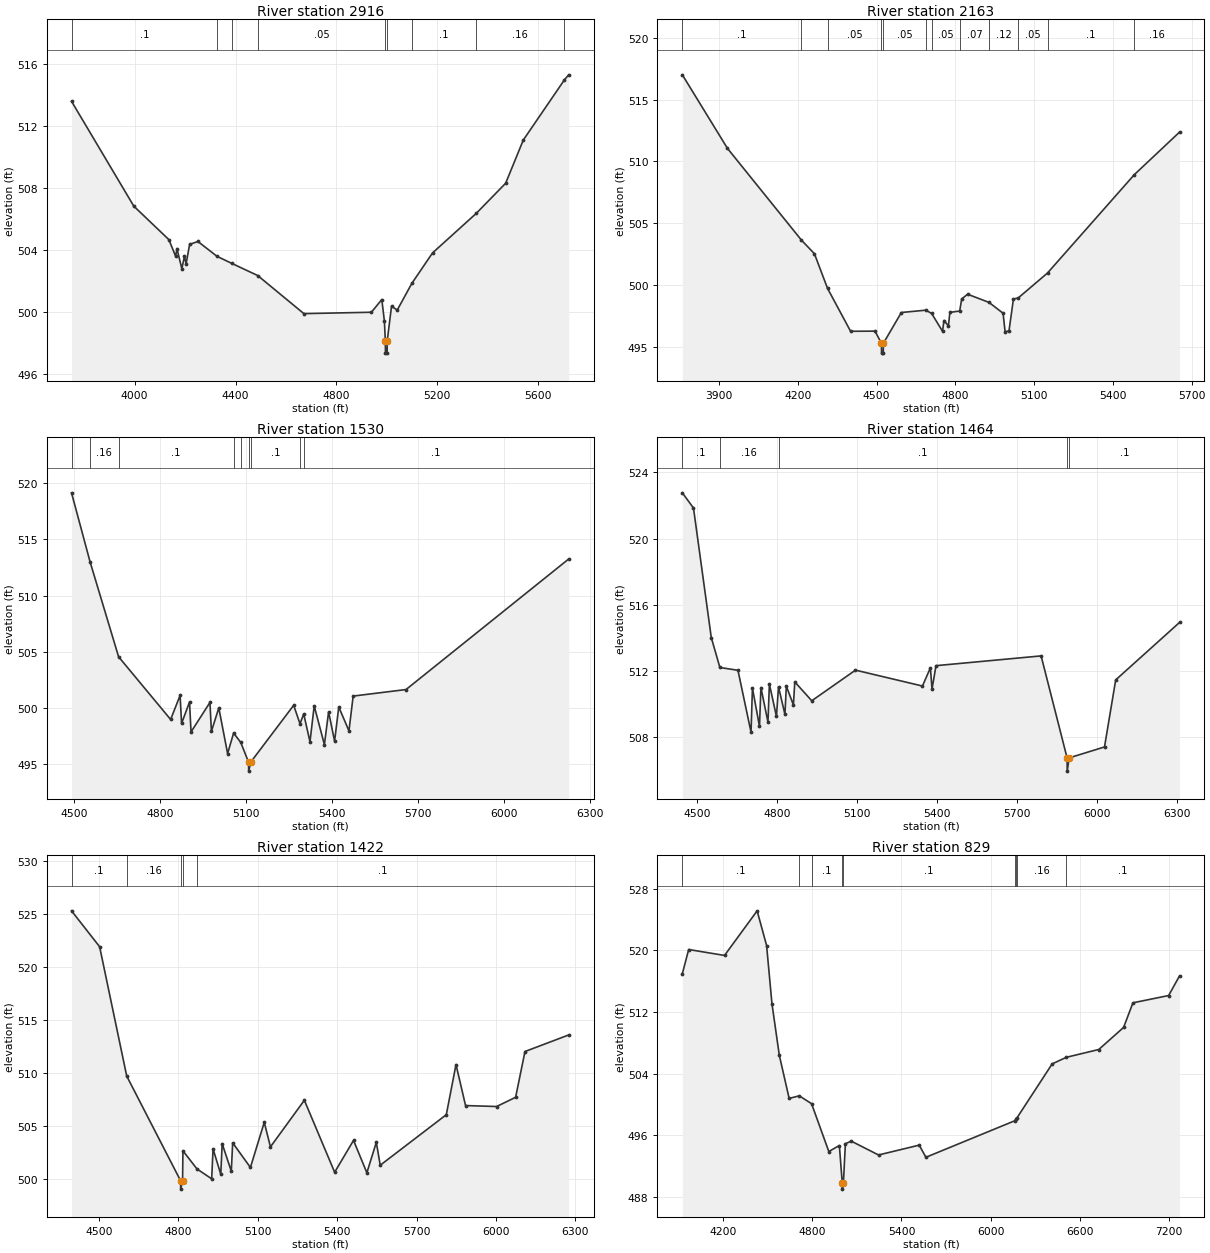
Type RM Length L Ch R = 1,2916,753,753,753
BEGIN DESCRIPTION:
UNT 107 in HW 5.0
END DESCRIPTION:
XS GIS Cut Line= 3
      1997670.94     13520290.23      1997975.00     13521525.00
      1997975.00     13522225.04
#Sta/Elev= 30
  3749.6  513.60  3996.6  506.83  4135.6  504.67  4162.6  503.59  4167.7  504.09
  4187.1  502.79  4197.4  503.58  4204.1  503.12  4218.0  504.36  4250.8  504.55
  4326.6  503.59  4385.7  503.13  4488.0  502.35  4671.1  499.89  4938.9  499.98
  4980.1  500.80  4990.4  499.41  4994.1  498.14  4994.7  497.34  5001.1  497.34
  5001.7  498.14  5018.7  500.37  5041.3  500.12  5099.1  501.84  5181.3  503.81
  5354.5  506.36  5471.3  508.31  5541.3  511.10  5704.5  514.99  5721.3  515.31
#Mann=9,-1,0
  3749.6     0.1       0  4326.6    0.05       0  4385.7    0.07       0
  4488.0    0.05       0  4994.1    0.07       0  5001.7    0.05       0
  5099.1     0.1       0  5354.5    0.16       0  5704.5     0.1       0
Bank Sta=4994.1,5001.7
Exp/Cntr=0.3,0.1

Type RM Length L Ch R = 1,2163,633,633,633
BEGIN DESCRIPTION:
Mapping XS 105da707
END DESCRIPTION:
XS GIS Cut Line= 4
      1997357.22     13520343.73      1997438.31     13521328.46
      1997681.37     13521824.98      1997907.04     13522095.79
#Sta/Elev= 30
  3760.5  517.01  3932.4  511.05  4214.1  503.62  4263.5  502.52  4313.3  499.72
  4401.2  496.24  4494.2  496.25  4518.6  495.27  4519.2  494.47  4525.6  494.47
  4526.2  495.27  4594.6  497.76  4688.1  497.95  4710.0  497.68  4751.3  496.24
  4756.9  497.11  4773.8  496.68  4779.4  497.77  4816.7  497.88  4824.4  498.86
  4846.9  499.24  4928.2  498.58  4982.0  497.70  4989.7  496.19  5004.5  496.28
  5021.4  498.85  5039.7  498.94  5151.2  500.96  5482.0  508.93  5653.9  512.37
#Mann=12,-1,0
  3760.5     0.1       0  4214.1    0.12       0  4313.3    0.05       0
  4518.6    0.07       0  4526.2    0.05       0  4688.1    0.12       0
  4710.0    0.05       0  4816.7    0.07       0  4928.2    0.12       0
  5039.7    0.05       0  5151.2     0.1       0  5482.0    0.16       0
Bank Sta=4518.6,4526.2
Exp/Cntr=0.3,0.1

Type RM Length L Ch R = 1,1530,66,66,66
BEGIN DESCRIPTION:
Mapping XS e3f495ba
END DESCRIPTION:
XS GIS Cut Line= 6
      1997000.82     13520710.42      1997052.90     13520991.65
      1997118.87     13521210.40      1997223.04     13521460.40
      1997518.18     13521845.82      1997881.38     13522136.38
#Sta/Elev= 30
  4491.1  519.14  4555.7  513.02  4655.5  504.57  4837.2  499.00  4870.2  501.14
  4875.4  498.65  4903.2  500.55  4908.4  497.89  4974.4  500.51  4979.6  497.94
  5005.4  500.03  5036.1  495.97  5057.1  497.79  5082.1  496.96  5109.2  495.21
  5109.8  494.41  5116.9  495.21  5266.8  500.26  5288.9  498.62  5301.9  499.49
  5323.8  497.02  5338.5  500.21  5374.1  496.77  5388.8  499.68  5409.7  497.07
  5424.3  500.11  5459.9  497.99  5474.6  501.08  5659.2  501.66  6227.2  513.26
#Mann=9,-1,0
  4491.1     0.1       0  4555.7    0.16       0  4655.5     0.1       0
  5057.1    0.05       0  5082.1     0.1       0  5109.2    0.07       0
  5116.9     0.1       0  5288.9    0.07       0  5301.9     0.1       0
Bank Sta=5109.2,5116.9
Exp/Cntr=0.3,0.1

Type RM Length L Ch R = 1,1464,42,42,42
BEGIN DESCRIPTION:
Mapping XS cb0f1626
END DESCRIPTION:
XS GIS Cut Line= 5
      1996948.73     13520656.54      1996956.68     13520907.42
      1997122.30     13521410.40      1997455.58     13521894.98
      1997860.09     13522182.55
#Sta/Elev= 30
  4444.1  522.76  4485.9  521.84  4552.6  514.02  4584.9  512.21  4652.7  512.04
  4701.8  508.30  4707.0  510.97  4733.5  508.65  4738.8  511.00  4765.3  508.91
  4770.6  511.21  4797.1  509.25  4804.8  511.04  4828.9  509.38  4834.2  511.08
  4860.7  509.95  4865.9  511.34  4929.5  510.20  5093.6  512.05  5344.8  511.09
  5374.6  512.19  5380.7  510.91  5395.6  512.32  5789.9  512.91  5887.3  506.75
  5887.9  505.95  5895.0  506.75  6027.7  507.41  6069.7  511.46  6309.1  514.93
#Mann=5,-1,0
  4444.1     0.1       0  4584.9    0.16       0  4804.8     0.1       0
  5887.3    0.07       0  5895.0     0.1       0
Bank Sta=5887.3,5895
Exp/Cntr=0.3,0.1

Type RM Length L Ch R = 1,1422,593,593,593
BEGIN DESCRIPTION:
Mapping XS 2574072a
END DESCRIPTION:
XS GIS Cut Line= 6
      1996912.27     13520599.24      1996938.31     13520932.62
      1997026.86     13521255.54      1997151.86     13521542.00
      1997448.73     13521958.66      1997775.42     13522160.90
#Sta/Elev= 30
  4396.9  525.30  4503.0  521.92  4605.3  509.74  4808.6  499.89  4809.2  499.09
  4816.3  499.89  4817.6  502.70  4870.8  500.99  4926.2  500.06  4931.4  502.88
  4960.6  500.49  4965.8  503.37  5000.3  500.78  5005.5  503.45  5072.5  501.13
  5124.8  505.38  5148.2  503.07  5276.2  507.46  5390.6  500.68  5461.9  503.68
  5512.3  500.63  5548.0  503.50  5562.7  501.34  5812.3  506.10  5848.9  510.82
  5885.0  506.96  6002.2  506.87  6074.1  507.74  6109.4  512.05  6274.5  513.61
#Mann=5,-1,0
  4396.9     0.1       0  4605.3    0.16       0  4808.6    0.07       0
  4816.3    0.16       0  4870.8     0.1       0
Bank Sta=4808.6,4816.3
Exp/Cntr=0.3,0.1

Type RM Length L Ch R = 1,829,0,0,0
BEGIN DESCRIPTION:
UNT 107 in HW 4.0
END DESCRIPTION:
XS GIS Cut Line= 4
      1997209.17     13520229.48      1996667.48     13520703.46
      1996479.98     13521854.50      1997874.99     13522275.00
#Sta/Elev= 30
  3926.5  516.98  3969.1  520.12  4210.1  519.35  4429.4  525.15  4493.0  520.64
  4529.0  513.08  4578.4  506.38  4644.6  500.76  4712.5  501.10  4795.3  500.08
  4911.3  493.86  4982.2  494.64  5001.8  489.77  5002.4  488.97  5009.5  489.77
  5022.7  494.87  5062.1  495.21  5245.6  493.41  5519.2  494.69  5564.2  493.11
  6163.3  497.87  6170.0  498.15  6174.4  498.17  6413.1  505.25  6508.9  506.11
  6726.4  507.12  6893.5  509.99  6956.2  513.19  7196.4  514.14  7269.5  516.69
#Mann=9,-1,0
  3926.5     0.1       0  4712.5    0.16       0  4795.3     0.1       0
  5001.8    0.07       0  5009.5     0.1       0  6163.3    0.16       0
  6170.0     0.1       0  6174.4    0.16       0  6508.9     0.1       0
Bank Sta=5001.8,5009.5
Exp/Cntr=0.3,0.1

Chan Stop Cuts=-1