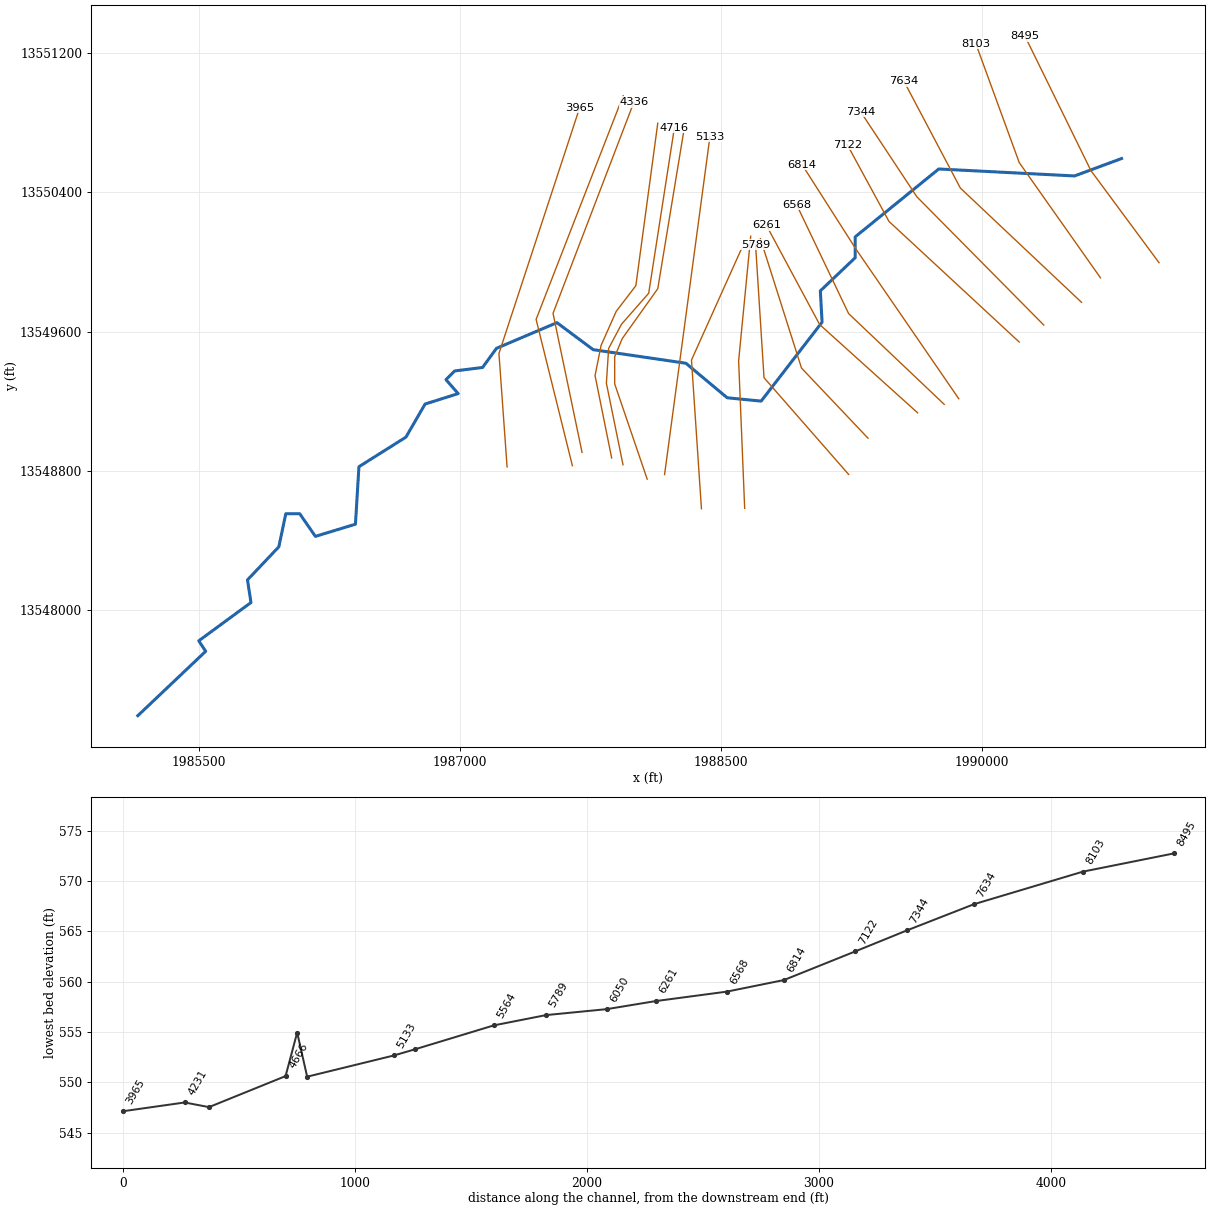
--- UNT 108 in HW.prj (project) ---

Proj Title=UNT 108 in HW Base Level Engineering
Current Plan=p01
Default Exp/Contr=0.3,0.1
English Units
Geom File=g01
Flow File=f01
Plan File=p01
BEGIN DESCRIPTION:
UNT 108 in HW
END DESCRIPTION:

--- UNT 108 in HW.p01 (plan) ---

Plan Title=Multiple Run
Short Identifier=Multiple
Geom File=g01
Flow File=f01
Subcritical Flow
K Sum by GR= 0
Std Step Tol= 0.01
Critical Tol= 0.01
Num of Std Step Trials= 20
Max Error Tol= 0.3
Flow Tol Ratio= 0.001
Split Flow NTrial= 30
Split Flow Tol= 0.02
Split Flow Ratio= 0.02
Log Output Level= 0
Friction Slope Method= 1
Unsteady Friction Slope Method= 2
Unsteady Bridges Friction Slope Method= 1
Parabolic Critical Depth
Global Vel Dist=  1 , 1 , 1
Global Log Level= 0
CheckData=True
Encroach Param= -1, 0, 0, 0
BEGIN DESCRIPTION:
Multiple Run
END DESCRIPTION:

--- UNT 108 in HW.f01 (steady flow) ---

Flow Title=Multiple
Number of Profiles=7
Profile Names=10-year,25-year,50-year,1pct_min,100-year,1pct_plu,500-year
River Rch & RM= UNT 108 in HW,Reach-1,8495
     455     632     778     474     945    1886    1402
River Rch & RM= UNT 108 in HW,Reach-1,7634
     617     875    1091     674    1345    2683    2053
River Rch & RM= UNT 108 in HW,Reach-1,4336
     889    1285    1624    1014    2023    4036    3161
Boundary for River Rch & Prof#=UNT 108 in HW,Reach-1,1
Up Type=0
Dn Type=3
Dn Slope=0.005
Boundary for River Rch & Prof#=UNT 108 in HW,Reach-1,2
Up Type=0
Dn Type=3
Dn Slope=0.005
Boundary for River Rch & Prof#=UNT 108 in HW,Reach-1,3
Up Type=0
Dn Type=3
Dn Slope=0.005
Boundary for River Rch & Prof#=UNT 108 in HW,Reach-1,4
Up Type=0
Dn Type=3
Dn Slope=0.005
Boundary for River Rch & Prof#=UNT 108 in HW,Reach-1,5
Up Type=0
Dn Type=3
Dn Slope=0.005
Boundary for River Rch & Prof#=UNT 108 in HW,Reach-1,6
Up Type=0
Dn Type=3
Dn Slope=0.005
Boundary for River Rch & Prof#=UNT 108 in HW,Reach-1,7
Up Type=0
Dn Type=3
Dn Slope=0.005

--- UNT 108 in HW.g01 (geometry) ---

Geom Title=Existing Conditions

River Reach=UNT 108 in HW,Reach-1
Reach XY= 30
      1990800.80     13550594.54      1990530.80     13550494.54
      1989750.80     13550534.54      1989270.80     13550144.54
      1989270.80     13550024.54      1989070.80     13549834.54
      1989080.80     13549654.54      1988730.93     13549201.35
      1988535.81     13549220.47      1988298.72     13549418.85
      1987766.29     13549496.76      1987558.09     13549651.95
      1987210.80     13549504.54      1987130.80     13549394.54
      1986970.80     13549374.54      1986920.80     13549324.54
      1986990.80     13549244.54      1986800.80     13549184.54
      1986690.80     13548994.54      1986420.80     13548824.54
      1986400.80     13548494.54      1986170.80     13548424.54
      1986080.80     13548554.54      1986000.80     13548554.54
      1985960.80     13548364.54      1985780.80     13548174.54
      1985800.80     13548044.54      1985500.80     13547824.54
      1985540.80     13547764.54      1985150.80     13547394.54

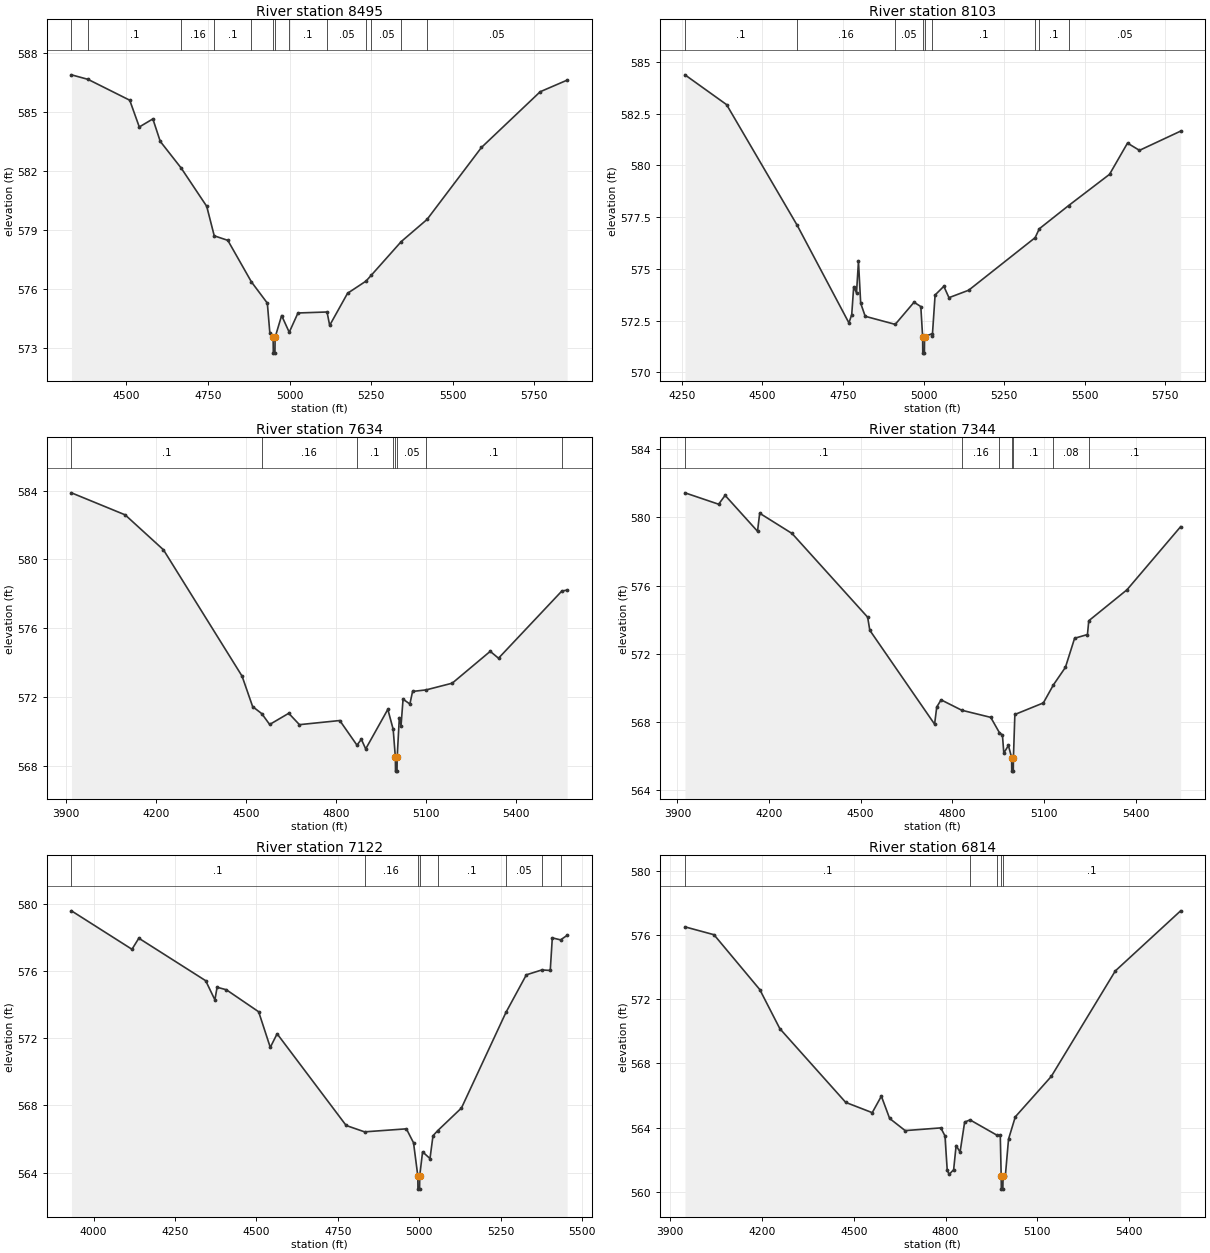
Type RM Length L Ch R = 1,8495,392,392,392
BEGIN DESCRIPTION:
UNT 108 in HW 19.0
END DESCRIPTION:
XS GIS Cut Line= 3
      1991016.06     13549996.22      1990625.00     13550525.00
      1990245.66     13551298.29
#Sta/Elev= 30
  4331.7  586.88  4382.4  586.65  4510.3  585.59  4539.6  584.23  4581.2  584.64
  4603.8  583.50  4668.1  582.14  4746.2  580.20  4769.3  578.70  4810.9  578.47
  4883.2  576.36  4932.0  575.28  4939.6  573.78  4949.8  573.54  4950.3  572.74
  4955.3  572.74  4955.8  573.54  4975.8  574.65  4999.1  573.80  5025.9  574.78
  5115.0  574.83  5123.0  574.15  5177.8  575.78  5234.4  576.40  5250.7  576.70
  5342.5  578.41  5421.3  579.53  5588.2  583.19  5768.1  586.02  5850.7  586.61
#Mann=13,-1,0
  4331.7    0.05       0  4382.4     0.1       0  4668.1    0.16       0
  4769.3     0.1       0  4883.2    0.05       0  4949.8    0.07       0
  4955.8    0.05       0  4999.1     0.1       0  5115.0    0.05       0
  5234.4     0.1       0  5250.7    0.05       0  5342.5     0.1       0
  5421.3    0.05       0
Bank Sta=4949.8,4955.8
Exp/Cntr=0.3,0.1

Type RM Length L Ch R = 1,8103,469,469,469
BEGIN DESCRIPTION:
UNT 108 in HW 18.0
END DESCRIPTION:
XS GIS Cut Line= 3
      1990679.66     13549909.46      1990213.09     13550571.33
      1989963.53     13551254.91
#Sta/Elev= 30
  4259.7  584.38  4388.8  582.94  4608.1  577.10  4768.3  572.39  4777.0  572.79
  4783.1  574.14  4791.8  573.84  4797.9  575.36  4804.8  573.34  4818.8  572.71
  4911.9  572.32  4970.3  573.39  4991.3  573.18  4996.9  571.73  4997.4  570.93
  5002.4  570.93  5002.9  571.73  5025.1  571.86  5027.0  571.76  5035.6  573.74
  5062.7  574.16  5078.6  573.61  5139.7  573.97  5345.9  576.51  5358.8  576.94
  5449.6  578.06  5576.6  579.57  5632.4  581.08  5669.5  580.73  5797.2  581.66
#Mann=9,-1,0
  4259.7     0.1       0  4608.1    0.16       0  4911.9    0.05       0
  4996.9    0.04       0  5002.9    0.05       0  5025.1     0.1       0
  5345.9    0.05       0  5358.8     0.1       0  5449.6    0.05       0
Bank Sta=4996.9,5002.9
Exp/Cntr=0.3,0.1

Type RM Length L Ch R = 1,7634,290,290,290
BEGIN DESCRIPTION:
UNT 108 in HW 17.0
END DESCRIPTION:
XS GIS Cut Line= 3
      1990571.20     13549768.35      1989875.00     13550425.00
      1989551.20     13551037.91
#Sta/Elev= 30
  3919.1  583.87  4097.9  582.59  4225.4  580.56  4487.1  573.22  4522.3  571.45
  4552.7  571.04  4579.0  570.41  4642.5  571.06  4678.1  570.40  4812.4  570.64
  4869.6  569.21  4884.3  569.55  4898.7  568.99  4972.4  571.29  4990.2  570.13
  4997.5  568.50  4998.0  567.70  5003.0  567.70  5003.5  568.50  5010.7  570.81
  5016.4  570.35  5023.1  571.88  5045.8  571.60  5054.8  572.33  5099.9  572.42
  5186.8  572.81  5313.3  574.66  5340.9  574.26  5551.5  578.16  5569.3  578.22
#Mann=8,-1,0
  3919.1     0.1       0  4552.7    0.16       0  4869.6     0.1       0
  4990.2    0.05       0  4997.5    0.04       0  5003.5    0.05       0
  5099.9     0.1       0  5551.5    0.05       0
Bank Sta=4997.5,5003.5
Exp/Cntr=0.3,0.1

Type RM Length L Ch R = 1,7344,222,222,222
BEGIN DESCRIPTION:
UNT 108 in HW 16.0
END DESCRIPTION:
XS GIS Cut Line= 3
      1990354.15     13549638.17      1989625.00     13550375.00
      1989301.64     13550864.29
#Sta/Elev= 30
  3924.6  581.45  4034.9  580.78  4056.1  581.30  4162.2  579.19  4169.3  580.25
  4275.3  579.06  4522.8  574.14  4529.9  573.37  4742.0  567.85  4749.1  568.86
  4763.3  569.28  4830.9  568.67  4925.9  568.25  4954.0  567.36  4964.2  567.21
  4968.7  566.15  4983.8  566.60  4994.2  565.89  4994.7  565.09  4999.7  565.09
  5000.2  565.89  5004.9  568.42  5098.2  569.10  5131.1  570.16  5170.4  571.19
  5200.5  572.90  5242.6  573.12  5246.9  573.93  5372.0  575.75  5547.7  579.46
#Mann=7,-1,0
  3924.6     0.1       0  4830.9    0.16       0  4954.0     0.1       0
  4994.2    0.07       0  5000.2     0.1       0  5131.1    0.08       0
  5246.9     0.1       0
Bank Sta=4994.2,5000.2
Exp/Cntr=0.3,0.1

Type RM Length L Ch R = 1,7122,308,308,308
BEGIN DESCRIPTION:
UNT 108 in HW 15.0
END DESCRIPTION:
XS GIS Cut Line= 3
      1990213.06     13549540.55      1989465.00     13550233.49
      1989225.01     13550674.99
#Sta/Elev= 30
  3932.2  579.58  4118.1  577.29  4139.1  577.95  4344.4  575.42  4372.7  574.28
  4379.5  575.03  4407.9  574.88  4507.1  573.57  4542.8  571.45  4563.8  572.26
  4775.8  566.80  4832.4  566.42  4960.8  566.60  4982.7  565.77  4995.8  563.81
  4996.3  563.01  5001.3  563.01  5001.8  563.81  5010.5  565.23  5033.3  564.83
  5042.5  566.19  5057.4  566.50  5129.9  567.84  5266.5  573.53  5329.2  575.77
  5376.8  576.06  5402.6  576.03  5408.9  577.97  5434.4  577.85  5454.4  578.12
#Mann=8,-1,0
  3932.2     0.1       0  4832.4    0.16       0  4995.8    0.07       0
  5001.8    0.16       0  5057.4     0.1       0  5266.5    0.05       0
  5376.8     0.1       0  5434.4    0.05       0
Bank Sta=4995.8,5001.8
Exp/Cntr=0.3,0.1

Type RM Length L Ch R = 1,6814,246,246,246
BEGIN DESCRIPTION:
UNT 108 in HW 14.0
END DESCRIPTION:
XS GIS Cut Line= 3
      1989865.85     13549215.03      1989275.00     13550075.00
      1988965.40     13550560.26
#Sta/Elev= 30
  3948.8  576.52  4043.6  576.03  4193.1  572.61  4258.7  570.17  4473.9  565.57
  4560.5  564.93  4590.3  565.96  4617.3  564.57  4668.1  563.81  4784.5  563.98
  4798.1  563.48  4805.4  561.35  4811.5  561.08  4826.4  561.37  4834.5  562.88
  4847.4  562.47  4862.3  564.34  4879.9  564.48  4968.2  563.52  4978.7  563.52
  4981.7  560.96  4982.2  560.16  4987.2  560.16  4987.7  560.96  4995.2  560.97
  5005.7  563.28  5027.8  564.67  5145.3  567.19  5354.4  573.77  5567.8  577.52
#Mann=5,-1,0
  3948.8     0.1       0  4879.9    0.16       0  4968.2     0.1       0
  4981.7    0.07       0  4987.7     0.1       0
Bank Sta=4981.7,4987.7
Exp/Cntr=0.3,0.1

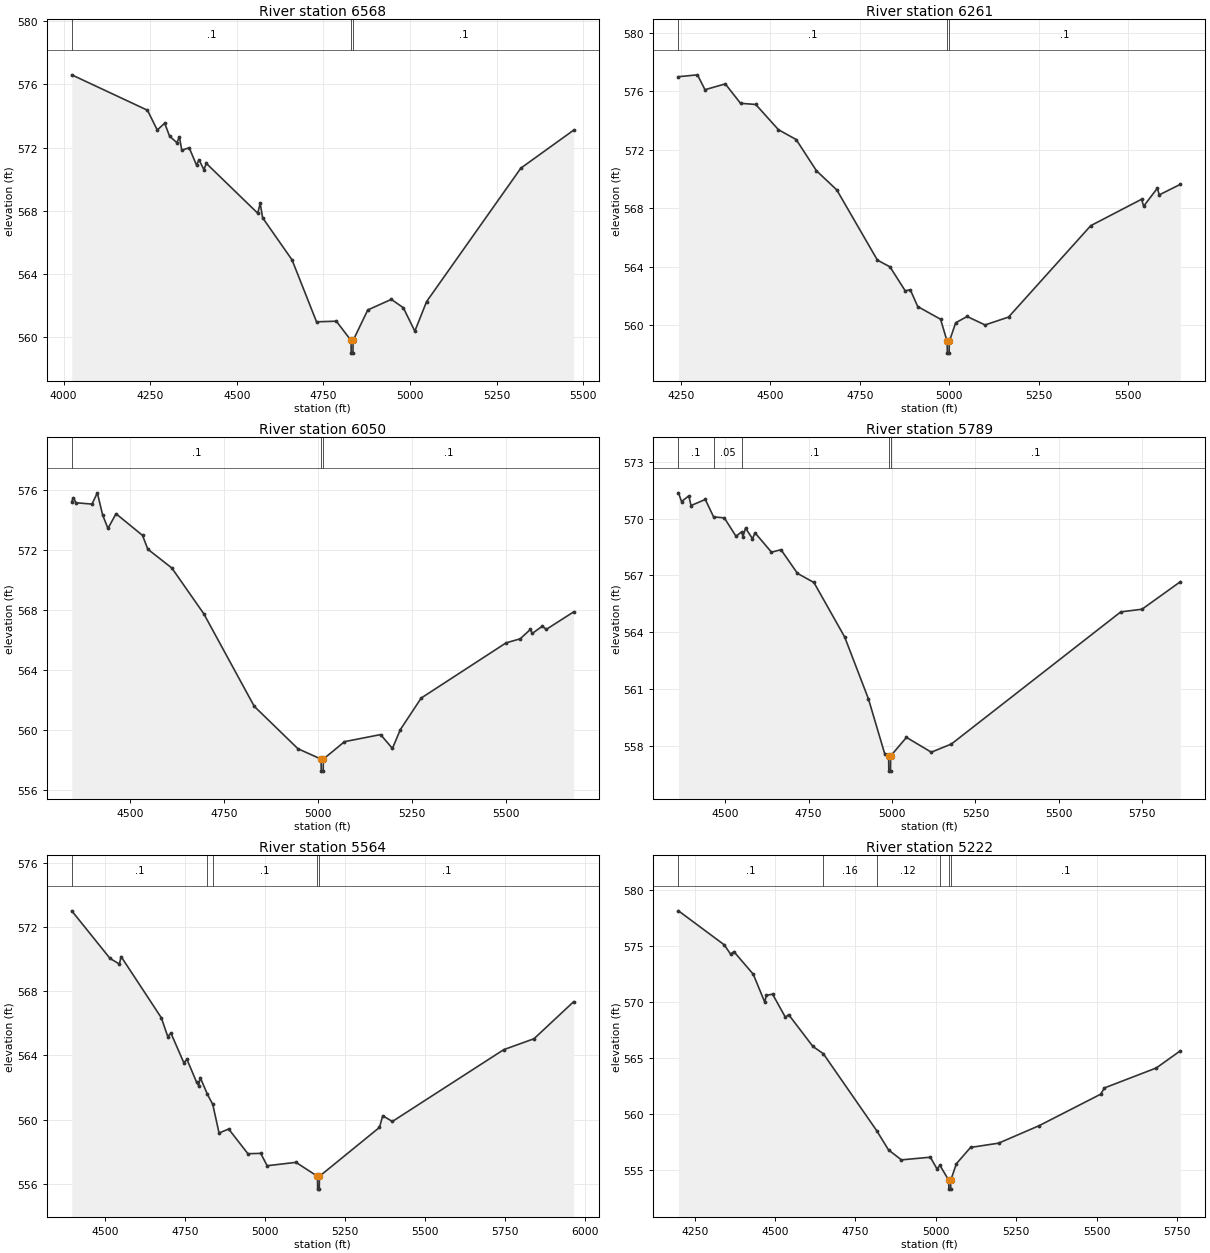
Type RM Length L Ch R = 1,6568,307,307,307
BEGIN DESCRIPTION:
UNT 108 in HW 13.0
END DESCRIPTION:
XS GIS Cut Line= 3
      1989782.11     13549182.88      1989233.49     13549703.71
      1988934.90     13550328.67
#Sta/Elev= 30
  4023.4  576.61  4242.0  574.37  4270.3  573.12  4291.7  573.55  4305.9  572.73
  4326.9  572.32  4334.2  572.68  4341.1  571.84  4362.5  572.00  4383.6  570.90
  4390.8  571.24  4405.0  570.61  4411.9  571.01  4560.3  567.86  4567.6  568.48
  4574.5  567.57  4659.4  564.91  4730.2  560.99  4787.4  561.03  4829.8  559.81
  4830.3  559.01  4835.3  559.01  4835.8  559.81  4878.1  561.74  4946.2  562.41
  4980.8  561.88  5014.0  560.40  5048.0  562.27  5320.2  570.71  5472.5  573.11
#Mann=3,-1,0
  4023.4     0.1       0  4829.8    0.07       0  4835.8     0.1       0
Bank Sta=4829.8,4835.8
Exp/Cntr=0.3,0.1

Type RM Length L Ch R = 1,6261,211,211,211
BEGIN DESCRIPTION:
UNT 108 in HW 12.0
END DESCRIPTION:
XS GIS Cut Line= 3
      1989629.35     13549134.25      1989066.83     13549641.21
      1988761.46     13550210.30
#Sta/Elev= 30
  4243.2  577.00  4296.4  577.13  4317.3  576.11  4374.1  576.51  4416.7  575.18
  4459.3  575.10  4522.8  573.37  4572.2  572.70  4629.0  570.56  4685.8  569.25
  4799.4  564.44  4834.5  563.98  4877.1  562.34  4891.3  562.41  4912.2  561.26
  4976.0  560.39  4994.4  558.87  4994.9  558.07  4999.9  558.07  5000.4  558.87
  5018.3  560.15  5050.2  560.58  5100.4  560.00  5166.1  560.54  5395.9  566.80
  5538.1  568.61  5543.7  568.13  5581.9  569.36  5587.6  568.91  5646.3  569.63
#Mann=3,-1,0
  4243.2     0.1       0  4994.4    0.07       0  5000.4     0.1       0
Bank Sta=4994.4,5000.4
Exp/Cntr=0.3,0.1

Type RM Length L Ch R = 1,6050,261,261,261
BEGIN DESCRIPTION:
Mapping XS e70efdd8
END DESCRIPTION:
XS GIS Cut Line= 3
      1989344.63     13548988.40      1988962.66     13549391.21
      1988726.54     13550134.28
#Sta/Elev= 30
  4345.2  575.20  4349.7  575.45  4356.6  575.12  4399.0  575.03  4413.2  575.78
  4427.3  574.31  4441.5  573.41  4462.9  574.39  4533.4  572.95  4547.5  572.03
  4611.4  570.78  4696.3  567.74  4830.6  561.58  4946.8  558.76  5008.3  558.07
  5008.8  557.27  5013.9  557.27  5014.4  558.07  5070.6  559.23  5166.6  559.70
  5198.1  558.78  5219.1  560.03  5274.6  562.13  5500.3  565.80  5537.8  566.07
  5564.8  566.69  5570.1  566.43  5596.8  566.91  5607.5  566.70  5680.0  567.86
#Mann=3,-1,0
  4345.2     0.1       0  5008.3    0.07       0  5014.4     0.1       0
Bank Sta=5008.3,5014.4
Exp/Cntr=0.3,0.1

Type RM Length L Ch R = 1,5789,225,225,225
BEGIN DESCRIPTION:
Mapping XS 8b2d07dc
END DESCRIPTION:
XS GIS Cut Line= 3
      1989233.47     13548780.13      1988747.38     13549335.66
      1988698.77     13550099.55
#Sta/Elev= 30
  4360.2  571.36  4369.4  570.90  4391.2  571.20  4397.9  570.69  4440.6  571.01
  4465.5  570.09  4497.5  570.04  4532.6  569.07  4549.3  569.30  4553.5  569.05
  4561.1  569.50  4582.0  568.94  4589.6  569.25  4638.9  568.23  4667.4  568.36
  4716.8  567.11  4766.1  566.63  4858.3  563.75  4929.4  560.49  4978.7  557.56
  4989.9  557.48  4990.4  556.68  4995.5  556.68  4996.0  557.48  5043.3  558.46
  5117.7  557.68  5177.9  558.11  5685.4  565.08  5749.0  565.22  5863.8  566.67
#Mann=5,-1,0
  4360.2     0.1       0  4465.5    0.05       0  4549.3     0.1       0
  4989.9    0.07       0  4996.0     0.1       0
Bank Sta=4989.9,4996
Exp/Cntr=0.3,0.1

Type RM Length L Ch R = 1,5564,342,342,342
BEGIN DESCRIPTION:
Mapping XS 034742c0
END DESCRIPTION:
XS GIS Cut Line= 3
      1988636.27     13548585.61      1988601.55     13549432.88
      1988670.99     13550148.14
#Sta/Elev= 30
  4396.6  573.02  4516.1  570.05  4545.4  569.70  4550.5  570.17  4676.2  566.35
  4696.2  565.18  4706.2  565.39  4746.3  563.55  4756.3  563.75  4786.3  562.33
  4792.7  562.12  4797.7  562.62  4819.9  561.58  4836.7  560.95  4856.4  559.16
  4886.4  559.41  4946.5  557.87  4986.5  557.89  5006.5  557.12  5096.6  557.33
  5163.6  556.46  5164.1  555.66  5169.2  555.66  5169.7  556.46  5357.2  559.51
  5367.3  560.24  5397.4  559.88  5745.0  564.36  5839.5  565.04  5963.2  567.35
#Mann=5,-1,0
  4396.6     0.1       0  4819.9    0.16       0  4836.7     0.1       0
  5163.6    0.07       0  5169.7     0.1       0
Bank Sta=5163.6,5169.7
Exp/Cntr=0.3,0.1

Type RM Length L Ch R = 1,5222,89,89,89
BEGIN DESCRIPTION:
UNT 108 in HW 11.0
END DESCRIPTION:
XS GIS Cut Line= 3
      1988388.01     13548583.03      1988330.72     13549437.22
      1988619.70     13550080.27
#Sta/Elev= 30
  4199.4  578.10  4341.7  575.07  4361.7  574.23  4371.8  574.46  4431.9  572.45
  4467.7  569.96  4472.7  570.55  4492.0  570.67  4532.1  568.60  4542.1  568.84
  4617.6  566.00  4649.8  565.36  4815.7  558.50  4852.8  556.77  4892.9  555.88
  4983.1  556.12  5003.2  555.09  5012.9  555.38  5040.0  554.07  5040.5  553.27
  5046.0  553.27  5046.5  554.07  5064.0  555.54  5108.0  556.99  5195.1  557.37
  5321.9  558.94  5512.7  561.74  5524.5  562.30  5685.8  564.08  5760.5  565.61
#Mann=6,-1,0
  4199.4     0.1       0  4649.8    0.16       0  4815.7    0.12       0
  5012.9     0.1       0  5040.0    0.07       0  5046.5     0.1       0
Bank Sta=5040,5046.5
Exp/Cntr=0.3,0.1

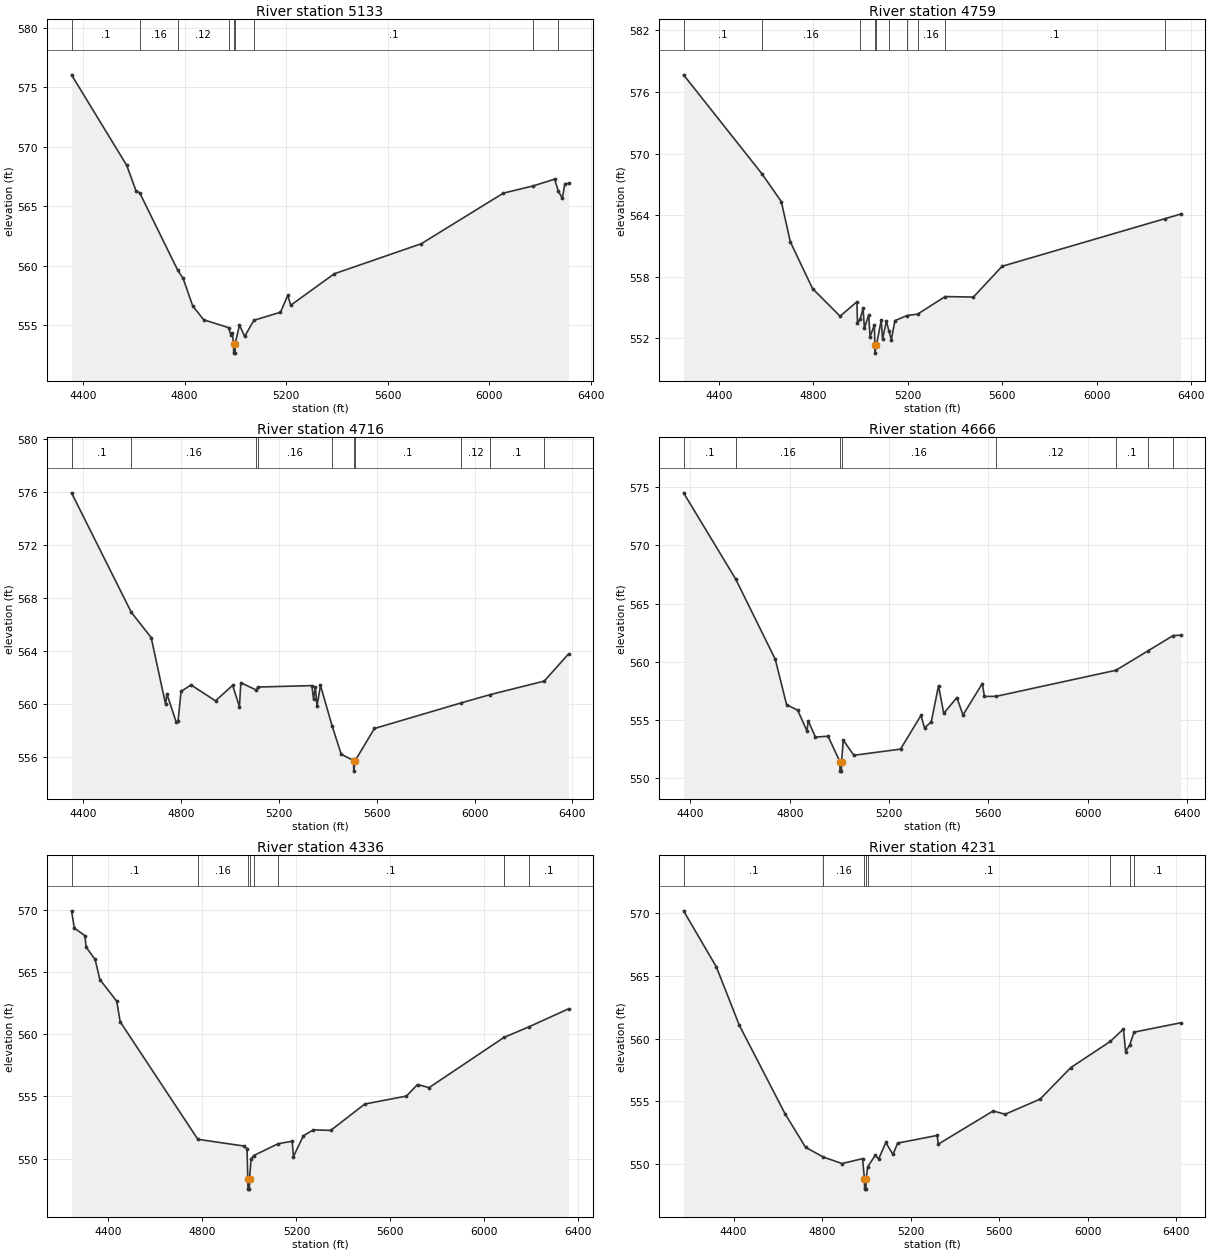
Type RM Length L Ch R = 1,5133,374,374,374
BEGIN DESCRIPTION:
Mapping XS 040a58b3
END DESCRIPTION:
XS GIS Cut Line= 2
      1988176.21     13548779.27      1988436.62     13550719.37
#Sta/Elev= 30
  4354.9  576.03  4572.6  568.42  4608.4  566.32  4623.8  566.11  4773.7  559.61
  4794.5  558.94  4832.1  556.64  4875.3  555.47  4973.5  554.81  4983.0  554.15
  4988.0  554.37  4993.1  553.47  4993.6  552.67  4999.1  552.67  4999.6  553.47
  5016.5  555.03  5036.7  554.07  5073.4  555.43  5177.9  556.10  5206.7  557.52
  5218.3  556.69  5389.8  559.33  5732.1  561.85  6055.8  566.10  6172.0  566.70
  6257.5  567.27  6271.9  566.30  6287.8  565.65  6297.9  566.89  6312.4  566.91
#Mann=9,-1,0
  4354.9     0.1       0  4623.8    0.16       0  4773.7    0.12       0
  4973.5    0.07       0  4993.1    0.07       0  4999.6    0.07       0
  5073.4     0.1       0  6172.0    0.05       0  6271.9    0.08       0
Bank Sta=4993.1,4999.6
Exp/Cntr=0.3,0.1

Type RM Length L Ch R = 1,4759,43,43,43
BEGIN DESCRIPTION:
Mapping XS 5e9f47a2
END DESCRIPTION:
XS GIS Cut Line= 6
      1988076.39     13548753.14      1987889.74     13549300.07
      1987889.74     13549456.32      1987933.15     13549560.48
      1988137.14     13549846.94      1988284.62     13550740.53
#Sta/Elev= 30
  4251.0  577.67  4583.6  568.01  4665.0  565.32  4703.1  561.40  4797.1  556.85
  4913.8  554.16  4985.1  555.56  4987.5  553.46  4998.6  553.86  5011.3  554.94
  5016.7  552.96  5035.1  554.31  5040.6  552.16  5059.0  553.30  5061.1  551.36
  5061.6  550.56  5067.7  551.36  5088.2  553.78  5093.6  551.92  5109.9  553.69
  5121.0  552.67  5130.9  551.87  5145.9  553.72  5196.6  554.22  5242.0  554.36
  5358.6  556.07  5478.3  556.02  5599.9  559.02  6288.3  563.65  6355.5  564.10
#Mann=10,-1,0
  4251.0     0.1       0  4583.6    0.16       0  4998.6    0.12       0
  5061.1    0.07       0  5067.7    0.12       0  5121.0    0.16       0
  5196.6    0.12       0  5242.0    0.16       0  5358.6     0.1       0
  6288.3    0.08       0
Bank Sta=5061.1,5067.7
Exp/Cntr=0.3,0.1

Type RM Length L Ch R = 1,4716,50,50,50
BEGIN DESCRIPTION:
Mapping XS 0779ac51
END DESCRIPTION:
XS GIS Cut Line= 6
      1987937.48     13548835.68      1987842.00     13549304.41
      1987855.02     13549504.06      1987928.81     13549642.95
      1988085.06     13549820.90      1988232.51     13550770.71
#Sta/Elev= 30
  4351.0  575.97  4595.5  566.95  4676.9  565.04  4736.1  559.99  4741.2  560.79
  4778.9  558.68  4786.7  558.70  4799.3  560.97  4840.0  561.46  4940.2  560.26
  5010.3  561.43  5038.1  559.81  5043.8  561.63  5107.5  561.07  5113.2  561.30
  5334.6  561.41  5341.3  560.39  5348.9  561.31  5355.5  559.85  5369.7  561.42
  5417.0  558.39  5454.4  556.23  5505.3  555.75  5505.8  554.95  5511.9  555.75
  5590.4  558.17  5944.6  560.10  6064.2  560.73  6285.3  561.75  6384.7  563.80
#Mann=10,-1,0
  4351.0     0.1       0  4595.5    0.16       0  5107.5    0.12       0
  5113.2    0.16       0  5417.0     0.1       0  5505.3    0.07       0
  5511.9     0.1       0  5944.6    0.12       0  6064.2     0.1       0
  6285.3    0.05       0
Bank Sta=5505.3,5511.9
Exp/Cntr=0.3,0.1

Type RM Length L Ch R = 1,4666,330,330,330
BEGIN DESCRIPTION:
Mapping XS fa6e5cbb
END DESCRIPTION:
XS GIS Cut Line= 6
      1987872.38     13548874.72      1987776.90     13549347.81
      1987811.62     13549521.42      1987898.42     13549716.73
      1988011.27     13549864.30      1988137.14     13550797.47
#Sta/Elev= 30
  4372.7  574.51  4582.7  567.10  4741.9  560.22  4787.6  556.32  4832.1  555.85
  4869.5  554.07  4874.6  554.94  4903.5  553.54  4954.4  553.62  5002.1  551.42
  5002.6  550.62  5008.2  550.62  5008.7  551.42  5015.6  553.28  5058.3  551.98
  5246.1  552.51  5328.4  555.40  5342.9  554.33  5370.0  554.86  5399.1  557.95
  5420.2  555.58  5472.9  556.93  5497.7  555.44  5575.4  558.14  5583.9  557.03
  5631.0  557.04  6113.6  559.28  6244.3  560.97  6344.2  562.26  6373.5  562.29
#Mann=8,-1,0
  4372.7     0.1       0  4582.7    0.16       0  5002.1    0.07       0
  5008.7    0.16       0  5631.0    0.12       0  6113.6     0.1       0
  6244.3    0.05       0  6344.2     0.1       0
Bank Sta=5002.1,5008.7
Exp/Cntr=0.3,0.1

Type RM Length L Ch R = 1,4336,105,105,105
BEGIN DESCRIPTION:
Mapping XS c218724a
END DESCRIPTION:
XS GIS Cut Line= 3
      1987702.24     13548906.83      1987535.58     13549705.45
      1988000.27     13550919.21
#Sta/Elev= 30
  4242.9  569.94  4255.1  568.55  4300.0  567.94  4305.1  567.02  4343.2  566.03
  4363.6  564.41  4435.1  562.67  4450.1  561.01  4780.6  551.55  4976.5  551.01
  4990.0  550.79  4993.3  548.34  4993.9  547.54  5000.1  547.54  5000.6  548.34
  5007.2  549.98  5017.9  550.24  5122.0  551.19  5182.2  551.40  5187.5  550.16
  5229.6  551.83  5272.4  552.31  5346.4  552.27  5491.3  554.39  5668.6  555.03
  5715.6  555.96  5765.0  555.71  6083.6  559.75  6190.4  560.61  6358.4  562.05
#Mann=8,-1,0
  4242.9     0.1       0  4780.6    0.16       0  4993.3    0.07       0
  5000.6    0.16       0  5017.9    0.12       0  5122.0     0.1       0
  6083.6    0.08       0  6190.4     0.1       0
Bank Sta=4993.3,5000.6
Exp/Cntr=0.3,0.1

Type RM Length L Ch R = 1,4231,266,266,266
BEGIN DESCRIPTION:
Mapping XS 186623ac
END DESCRIPTION:
XS GIS Cut Line= 3
      1987646.70     13548830.42      1987438.35     13549670.73
      1987938.34     13550955.41
#Sta/Elev= 30
  4174.4  570.19  4322.5  565.72  4426.4  561.06  4632.4  554.02  4725.2  551.34
  4805.1  550.56  4890.0  550.04  4982.7  550.43  4991.3  548.80  4991.9  548.00
  4998.1  548.00  4998.6  548.80  5006.0  549.78  5039.8  550.69  5055.5  550.41
  5087.7  551.72  5119.9  550.77  5141.3  551.67  5319.4  552.28  5324.8  551.59
  5572.2  554.23  5626.6  553.97  5784.5  555.18  5923.1  557.69  6101.8  559.78
  6160.7  560.77  6170.6  558.97  6188.9  559.49  6208.9  560.52  6418.7  561.26
#Mann=8,-1,0
  4174.4     0.1       0  4805.1    0.16       0  4991.3    0.07       0
  4998.6    0.16       0  5006.0     0.1       0  6101.8    0.05       0
  6188.9    0.08       0  6208.9     0.1       0
Bank Sta=4991.3,4998.6
Exp/Cntr=0.3,0.1

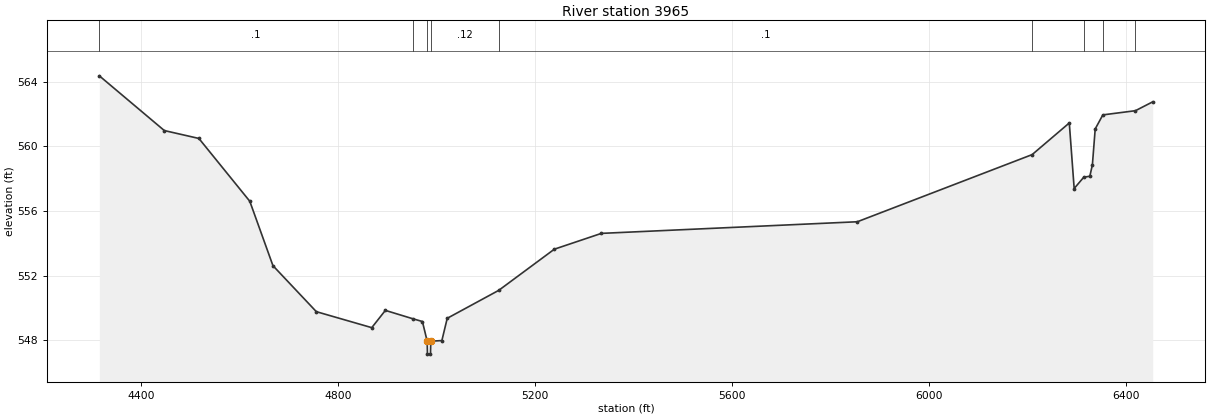
Type RM Length L Ch R = 1,3965,0,0,0
BEGIN DESCRIPTION:
UNT 108 in HW 9.0
END DESCRIPTION:
XS GIS Cut Line= 3
      1987271.69     13548823.46      1987225.00     13549475.00
      1987688.34     13550885.96
#Sta/Elev= 30
  4315.7  564.37  4447.6  560.98  4517.8  560.49  4621.1  556.60  4668.1  552.61
  4756.2  549.76  4868.7  548.77  4896.3  549.84  4952.2  549.32  4971.5  549.15
  4981.2  547.93  4981.7  547.13  4987.9  547.13  4988.5  547.93  5011.0  547.97
  5021.9  549.35  5126.4  551.08  5239.3  553.63  5334.8  554.61  5854.3  555.33
  6209.2  559.49  6284.6  561.45  6294.5  557.39  6314.0  558.09  6326.3  558.15
  6331.5  558.86  6337.2  561.08  6352.7  561.95  6418.9  562.21  6454.0  562.76
#Mann=9,-1,0
  4315.7     0.1       0  4952.2    0.12       0  4981.2    0.07       0
  4988.5    0.12       0  5126.4     0.1       0  6209.2    0.05       0
  6314.0     0.1       0  6352.7    0.05       0  6418.9    0.08       0
Bank Sta=4981.2,4988.5
Exp/Cntr=0.3,0.1

Chan Stop Cuts=-1