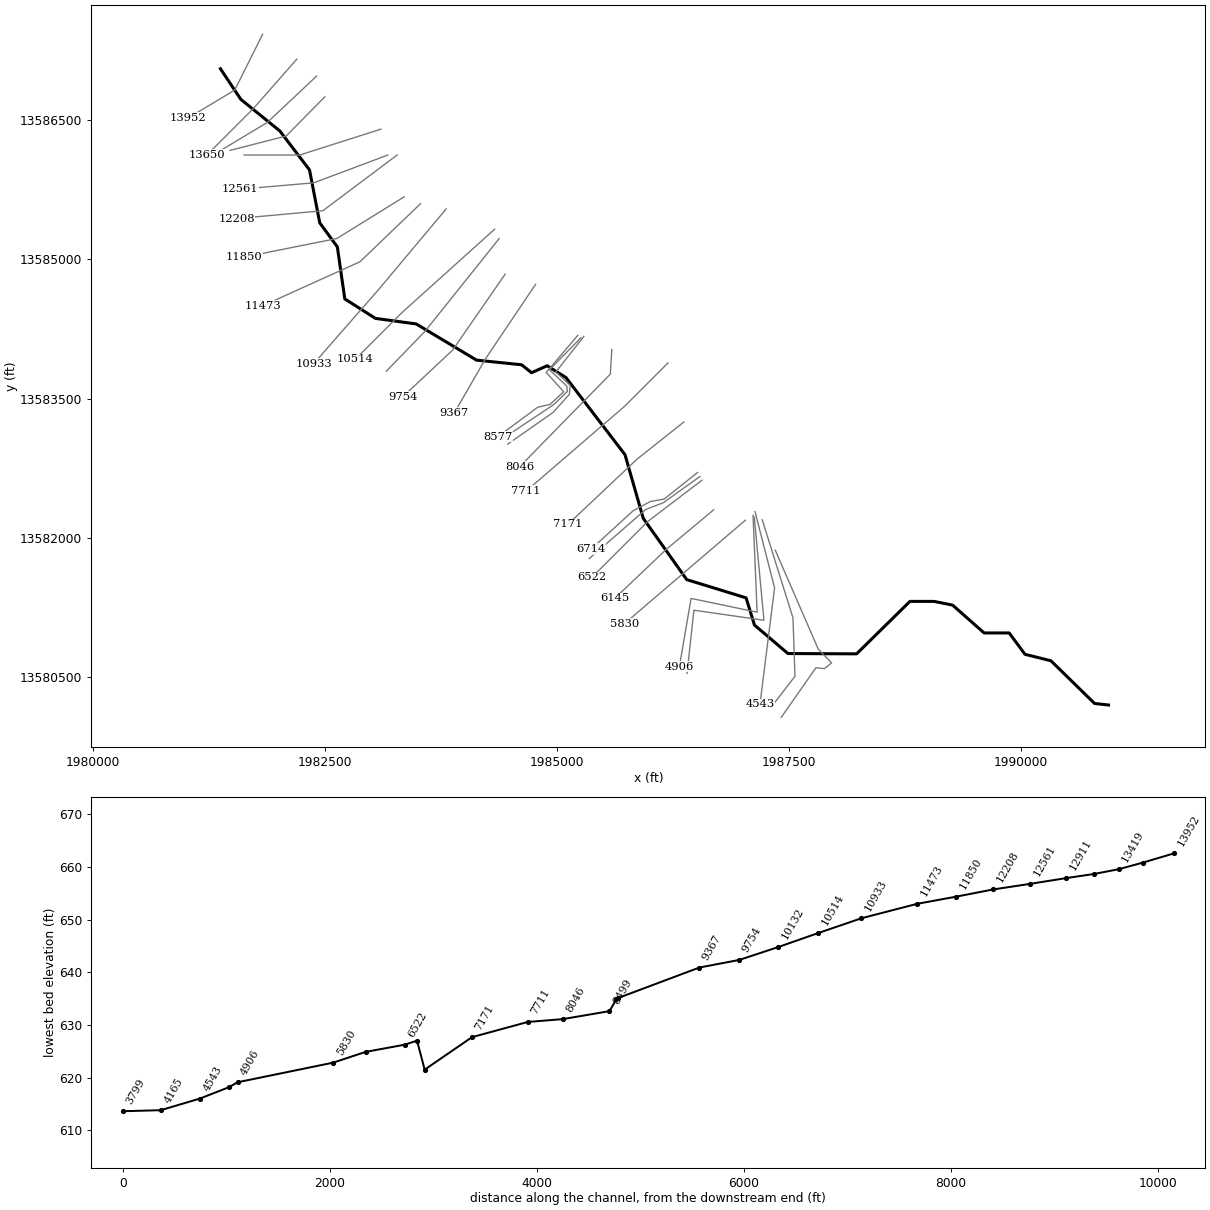
--- UNT 109 in HW.prj (project) ---

Proj Title=UNT 109 in HW Base Level Engineering
Current Plan=p01
Default Exp/Contr=0.3,0.1
English Units
Geom File=g01
Flow File=f01
Plan File=p01
Y Axis Title=Elevation
X Axis Title(PF)=Main Channel Distance
X Axis Title(XS)=Station
BEGIN DESCRIPTION:
UNT 109 in HW
END DESCRIPTION:
DSS Export Rating Curves= 0
DSS Export Rating Curve Sorted= 0
DSS Export Volume Flow Curves= 0
DXF OffsetX= 0
DXF OffsetY= 0
DXF ScaleX= 1
DXF ScaleY= 10

--- UNT 109 in HW.p01 (plan) ---

Plan Title=Multiple Run
Short Identifier=Multiple
Geom File=g01
Flow File=f01
Subcritical Flow
K Sum by GR= 0
Std Step Tol= 0.01
Critical Tol= 0.01
Num of Std Step Trials= 20
Max Error Tol= 0.3
Flow Tol Ratio= 0.001
Split Flow NTrial= 30
Split Flow Tol= 0.02
Split Flow Ratio= 0.02
Log Output Level= 0
Friction Slope Method= 1
Unsteady Friction Slope Method= 2
Unsteady Bridges Friction Slope Method= 1
Parabolic Critical Depth
Global Vel Dist=  1 , 1 , 1
Global Log Level= 0
CheckData=True
Encroach Param= -1, 0, 0, 0
BEGIN DESCRIPTION:
Multiple Run
END DESCRIPTION:

--- UNT 109 in HW.f01 (steady flow) ---

Flow Title=Multiple
Number of Profiles=7
Profile Names=10-year,25-year,50-year,1pct_min,100-year,1pct_plu,500-year
River Rch & RM= UNT 109 in HW,Reach-1,13952
     540     760     943     579    1156    2306    1745
River Rch & RM= UNT 109 in HW,Reach-1,12561
    1018    1478    1872    1172    2338    4665    3664
River Rch & RM= UNT 109 in HW,Reach-1,2330
    1329    1953    2494    1572    3137    6260    4990
Boundary for River Rch & Prof#=UNT 109 in HW,Reach-1,1
Up Type=0
Dn Type=3
Dn Slope=0.005
Boundary for River Rch & Prof#=UNT 109 in HW,Reach-1,2
Up Type=0
Dn Type=3
Dn Slope=0.005
Boundary for River Rch & Prof#=UNT 109 in HW,Reach-1,3
Up Type=0
Dn Type=3
Dn Slope=0.005
Boundary for River Rch & Prof#=UNT 109 in HW,Reach-1,4
Up Type=0
Dn Type=3
Dn Slope=0.005
Boundary for River Rch & Prof#=UNT 109 in HW,Reach-1,5
Up Type=0
Dn Type=3
Dn Slope=0.005
Boundary for River Rch & Prof#=UNT 109 in HW,Reach-1,6
Up Type=0
Dn Type=3
Dn Slope=0.005
Boundary for River Rch & Prof#=UNT 109 in HW,Reach-1,7
Up Type=0
Dn Type=3
Dn Slope=0.005

--- UNT 109 in HW.g01 (geometry) ---

Geom Title=Existing Conditions
Program Version=5.05

River Reach=UNT 109 in HW   ,Reach-1
Reach XY= 30
       1981370.8     13587054.54       1981590.8     13586724.54
       1982010.8     13586384.54       1982330.8     13585964.54
       1982440.8     13585394.54       1982630.8     13585134.54
       1982710.8     13584574.54       1983040.8     13584364.54
       1983480.8     13584304.54       1984130.8     13583914.54
      1984616.21     13583864.54      1984723.85     13583778.89
       1984891.9     13583854.23      1985094.68     13583726.45
      1985730.55     13582895.64      1985927.16     13582209.87
      1986395.82     13581549.28      1987035.41     13581352.76
       1987125.8     13581059.54       1987486.5     13580752.63
      1988226.52     13580749.37       1988800.8     13581314.54
      1989062.38     13581314.54       1989260.8     13581274.54
       1989600.8     13580974.54       1989870.8     13580974.54
       1990040.8     13580744.54       1990320.8     13580674.54
       1990790.8     13580214.54      1990940.85     13580197.96

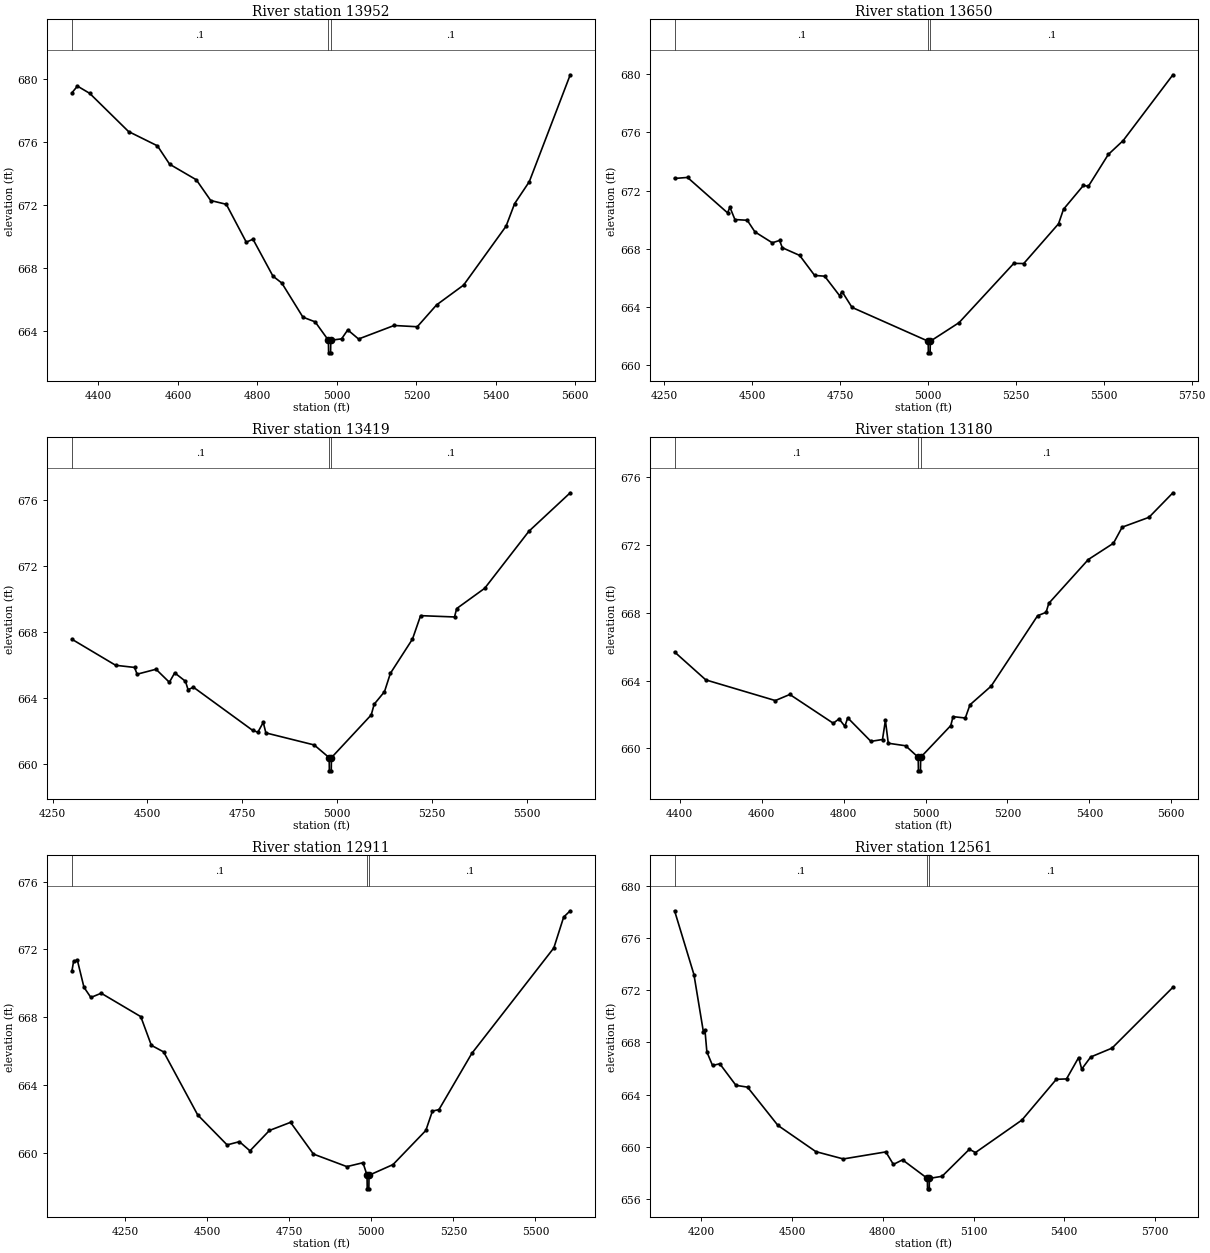
Type RM Length L Ch R = 1 ,13952   ,302,302,302
BEGIN DESCRIPTION:
UNT 109 in HW 31.0
END DESCRIPTION:
XS GIS Cut Line= 3
      1981824.98     13587424.96        1981525.       13586825.
      1981024.98     13586524.99
#Sta/Elev= 30
  4333.2  679.12  4347.1  679.55  4377.9  679.09  4475.7  676.66  4548.4  675.75
  4579.1  674.58  4646.2  673.59  4682.5  672.27  4721.7  672.03    4772  669.62
  4788.8  669.81  4839.1  667.46  4861.4  667.02  4914.5  664.85  4945.3  664.55
  4978.6  663.38  4979.1  662.58  4984.1  662.58  4984.6  663.38  5011.8  663.47
  5027.3  664.04  5054.5  663.46  5143.9  664.32  5202.2  664.24  5250.8  665.63
  5318.8  666.89  5425.7  670.64  5447.1  672.07  5484.1  673.47  5587.1  680.27
#Mann= 3 ,-1 , 0
  4333.2      .1       0  4978.6     .07       0  4984.6      .1       0
Bank Sta=4978.6,4984.6
XS Rating Curve= 0 ,0
Exp/Cntr=0.3,0.1

Type RM Length L Ch R = 1 ,13650   ,231,231,231
BEGIN DESCRIPTION:
UNT 109 in HW 30.0
END DESCRIPTION:
XS GIS Cut Line= 3
      1982193.85     13587158.22        1981725.       13586625.
      1981225.03     13586125.03
#Sta/Elev= 30
  4279.6  672.83  4316.4   672.9  4430.3  670.46  4436.9  670.85  4451.2     670
  4486.3  669.95  4508.1  669.15  4557.4   668.4  4578.3  668.56  4585.9  668.06
  4635.3  667.53  4677.9  666.15  4706.4   666.1  4749.1  664.75  4755.8  665.04
  4784.2  663.95  5000.8  661.62  5001.3  660.82  5006.3  660.82  5006.8  661.62
  5088.6   662.9  5244.2  666.98  5272.5  666.97  5371.5  669.71  5385.6  670.71
  5442.2  672.35  5456.3  672.29  5512.9  674.48  5555.3  675.44  5696.7  679.97
#Mann= 3 ,-1 , 0
  4279.6      .1       0  5000.8     .07       0  5006.8      .1       0
Bank Sta=5000.8,5006.8
XS Rating Curve= 0 ,0
Exp/Cntr=0.3,0.1

Type RM Length L Ch R = 1 ,13419   ,239,239,239
BEGIN DESCRIPTION:
UNT 109 in HW 29.0
END DESCRIPTION:
XS GIS Cut Line= 3
      1982407.37      13586975.9        1981875.       13586475.
      1981374.97     13586174.98
#Sta/Elev= 30
  4301.1  667.56  4416.5  665.98  4466.2  665.85  4473.1  665.44  4522.9  665.74
  4558.1  664.95  4572.2  665.52  4600.6  665.01  4607.4   664.5  4621.6  664.65
  4777.4  662.04  4791.5  661.92  4805.7  662.52  4812.6  661.88    4940  661.15
  4979.5  660.38    4980  659.58    4985  659.58  4985.5  660.38  5090.4  662.97
  5098.2  663.62  5125.4  664.38  5140.9  665.49  5199.2  667.57  5220.6  668.99
    5310  668.91  5315.8  669.42  5389.7  670.65  5506.3  674.11  5615.2  676.44
#Mann= 3 ,-1 , 0
  4301.1      .1       0  4979.5     .07       0  4985.5      .1       0
Bank Sta=4979.5,4985.5
XS Rating Curve= 0 ,0
Exp/Cntr=0.3,0.1

Type RM Length L Ch R = 1 ,13180   ,269,269,269
BEGIN DESCRIPTION:
UNT 109 in HW 28.0
END DESCRIPTION:
XS GIS Cut Line= 3
      1982495.94     13586751.98      1982079.26     13586330.09
      1981475.02       13586175.
#Sta/Elev= 30
  4387.3  665.69  4463.6  664.04  4633.3  662.82  4668.7  663.18  4774.8  661.48
  4788.9  661.74  4803.1   661.3  4810.1   661.8  4866.7  660.41    4895  660.52
  4902.1  661.65  4909.1   660.3  4951.5  660.15  4982.2  659.47  4982.7  658.67
  4987.7  658.67  4988.2  659.47  5061.6  661.34  5067.3  661.87  5097.2  661.79
  5108.6  662.57  5160.2  663.67  5273.7  667.83  5294.4  668.03    5301  668.56
  5397.6  671.15  5458.9  672.11  5480.2  673.06  5545.6  673.64  5604.1  675.09
#Mann= 3 ,-1 , 0
  4387.3      .1       0  4982.2     .07       0  4988.2      .1       0
Bank Sta=4982.2,4988.2
XS Rating Curve= 0 ,0
Exp/Cntr=0.3,0.1

Type RM Length L Ch R = 1 ,12911   ,350,350,350
BEGIN DESCRIPTION:
UNT 109 in HW 27.0
END DESCRIPTION:
XS GIS Cut Line= 3
      1983100.09     13586403.65        1982225.       13586125.
      1981624.99       13586125.
#Sta/Elev= 30
  4087.7  670.72    4093  671.31  4104.3  671.37  4124.5  669.77  4145.5  669.17
    4177  669.42  4297.6  668.04  4329.8  666.35  4367.3  665.96  4470.9  662.25
  4560.6  660.48  4598.1  660.67  4630.3  660.13  4689.5  661.33  4753.9  661.81
  4823.6  659.94  4925.5   659.2  4974.6  659.43    4987  658.69  4987.5  657.89
  4992.5  657.89    4993  658.69  5066.1  659.32  5166.1  661.33  5186.1  662.47
  5206.1  662.56  5306.1  665.87  5556.1  672.09  5586.1  673.91  5606.1  674.28
#Mann= 3 ,-1 , 0
  4087.7      .1       0    4987     .07       0    4993      .1       0
Bank Sta=4987,4993
XS Rating Curve= 0 ,0
Exp/Cntr=0.3,0.1

Type RM Length L Ch R = 1 ,12561   ,353,353,353
BEGIN DESCRIPTION:
UNT 109 in HW 26.0
END DESCRIPTION:
XS GIS Cut Line= 3
      1983174.97     13586124.99        1982375.       13585825.
      1981584.48     13585757.17
#Sta/Elev= 30
  4111.3  678.09  4175.4   673.2  4206.5  668.83  4211.8  668.94  4218.1  667.28
  4236.8  666.24  4260.8  666.37  4314.2  664.72  4352.5  664.58    4453  661.65
  4578.5  659.64  4669.3  659.08  4809.9  659.62  4834.8  658.66  4865.1  659.01
  4947.2  657.59  4947.7  656.79  4953.4  656.79  4953.9  657.59  4995.8  657.75
  5086.1  659.82  5106.2  659.57  5259.9  662.06  5373.6  665.18  5407.3  665.21
  5447.4  666.85  5457.5  665.96  5487.3  666.89  5557.8  667.57  5759.1  672.23
#Mann= 3 ,-1 , 0
  4111.3      .1       0  4947.2     .07       0  4953.9      .1       0
Bank Sta=4947.2,4953.9
XS Rating Curve= 0 ,0
Exp/Cntr=0.3,0.1

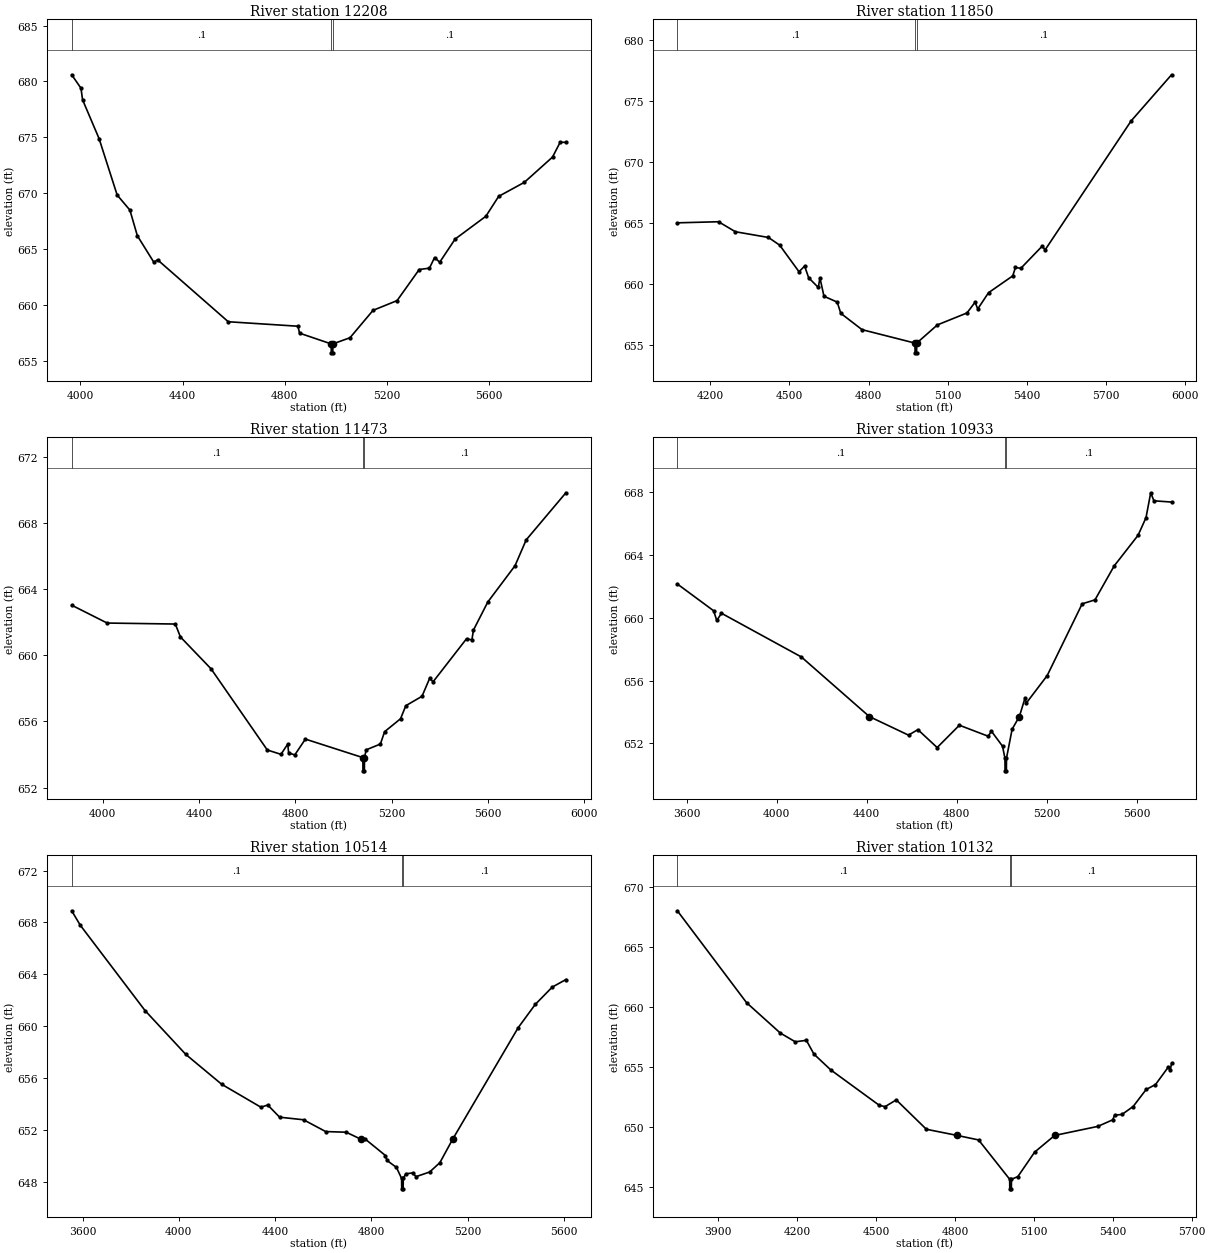
Type RM Length L Ch R = 1 ,12208   ,358,358,358
BEGIN DESCRIPTION:
UNT 109 in HW 25.0
END DESCRIPTION:
XS GIS Cut Line= 3
      1983274.96     13586124.97        1982475.       13585525.
      1981542.77     13585439.46
#Sta/Elev= 30
  3965.7   680.6  4002.1   679.4  4008.4  678.36  4072.9   674.9  4143.8  669.85
  4193.8   668.5  4222.9  666.21  4287.5  663.84  4302.1  664.06  4579.2  658.52
  4852.1  658.12  4858.4   657.5  4982.3  656.54  4982.8  655.74  4988.6  655.74
  4989.1  656.54    5056  657.09  5146.4  659.54  5240.5  660.41  5327.2  663.19
  5367.3  663.31  5387.4  664.26  5407.5  663.84  5467.8  665.91  5588.3  667.95
  5638.5  669.73  5738.9  670.98  5849.4  673.24  5879.5  674.57  5901.8  674.56
#Mann= 3 ,-1 , 0
  3965.7      .1       0  4982.3     .07       0  4989.1      .1       0
Bank Sta=4982.3,4989.1
XS Rating Curve= 0 ,0
Exp/Cntr=0.3,0.1

Type RM Length L Ch R = 1 ,11850   ,377,377,377
BEGIN DESCRIPTION:
UNT 109 in HW 24.0
END DESCRIPTION:
XS GIS Cut Line= 3
      1983350.08     13585673.83        1982625.       13585225.
      1981624.95     13585024.99
#Sta/Elev= 30
  4075.3  665.03  4231.4  665.12  4295.2   664.3  4420.5  663.83    4463   663.2
  4536.3  661.02  4557.6  661.48    4573  660.52  4609.6  659.73  4615.5  660.53
  4630.9  659.01  4681.1  658.53  4694.6  657.61  4775.2  656.27  4975.6  655.17
  4976.1  654.37  4981.9  654.37  4982.4  655.17  5060.6  656.66  5172.8  657.64
  5203.4  658.52  5213.6  657.97  5254.4   659.3  5346.2  660.68  5356.4  661.37
  5376.8   661.3  5458.3  663.13  5468.5   662.8  5794.9  673.39  5947.9  677.17
#Mann= 3 ,-1 , 0
  4075.3      .1       0  4975.6     .07       0  4982.4      .1       0
Bank Sta=4975.6,4982.4
XS Rating Curve= 0 ,0
Exp/Cntr=0.3,0.1

Type RM Length L Ch R = 1 ,11473   ,540,540,540
BEGIN DESCRIPTION:
UNT 109 in HW 23.0
END DESCRIPTION:
XS GIS Cut Line= 3
       1983527.2     13585600.94        1982875.       13584975.
      1981829.65     13584502.14
#Sta/Elev= 30
  3871.9  663.03  4019.1  661.95  4302.1  661.89  4323.2  661.11  4450.5  659.18
  4683.9  654.27  4740.5  654.01  4768.8  654.63  4772.4   654.1  4797.8  653.97
  4841.9  654.93  5080.5  653.81    5081  653.01  5086.8  653.01  5087.3  653.81
  5094.2  654.28  5153.2  654.63  5170.9  655.38  5236.9  656.16  5258.8  656.95
    5326  657.52  5357.6   658.6  5372.2   658.4  5510.8     661  5533.2  660.93
  5539.4  661.52    5599  663.22  5712.2  665.42  5758.4  666.98  5923.2  669.83
#Mann= 3 ,-1 , 0
  3871.9      .1       0  5080.5     .07       0  5087.3      .1       0
Bank Sta=5080.5,5087.3
XS Rating Curve= 0 ,0
Exp/Cntr=0.3,0.1

Type RM Length L Ch R = 1 ,10933   ,419,419,419
BEGIN DESCRIPTION:
UNT 109 in HW 22.0
END DESCRIPTION:
XS GIS Cut Line= 3
       1983803.2      13585543.6        1983075.       13584675.
      1982374.99     13583874.98
#Sta/Elev= 30
  3558.5  662.14  3719.5  660.44  3733.8  659.82  3754.6  660.28  4109.8   657.5
 4411.75653.7121  4585.9  652.53  4627.6  652.88  4713.3  651.74    4812  653.16
  4940.2  652.46  4954.4  652.78  5003.7  651.83  5014.6  651.06  5015.1  650.26
  5020.9  650.26  5021.4  651.06  5046.5  652.91  5078.7653.7121  5103.4  654.87
  5110.1  654.58  5202.1  656.31  5357.8  660.88  5414.7  661.13  5500.1  663.29
  5606.4  665.24  5641.6  666.36  5662.4  667.94  5676.7  667.43    5755  667.35
#Mann= 3 ,-1 , 0
  3558.5      .1       0  5014.6     .07       0  5021.4      .1       0
Bank Sta=4411.75,5078.7
XS Rating Curve= 0 ,0
Exp/Cntr=0.3,0.1

Type RM Length L Ch R = 1 ,10514   ,382,382,382
BEGIN DESCRIPTION:
UNT 109 in HW 21.0
END DESCRIPTION:
XS GIS Cut Line= 3
      1984324.99     13585324.99        1983325.       13584425.
      1982824.97     13583924.97
#Sta/Elev= 30
    3555   668.9  3590.5  667.79  3859.6   661.2  4029.2  657.81    4178  655.51
  4340.9  653.74  4369.3  653.91  4418.6  652.97    4518  652.77    4610  651.86
  4695.2  651.81 4756.65651.2643  4772.9   651.3  4858.1  650.01  4864.8  649.63
  4903.9  649.09  4925.2  648.24  4925.7  647.44  4931.6  647.44  4932.1  648.24
  4942.8   648.6  4971.1  648.67  4985.2  648.38  5041.8  648.74  5084.2  649.46
 5137.15651.2643  5409.5  659.88  5480.2  661.67  5550.9  663.01  5607.5  663.59
#Mann= 3 ,-1 , 0
    3555      .1       0  4925.2     .07       0  4932.1      .1       0
Bank Sta=4756.65,5137.15
XS Rating Curve= 0 ,0
Exp/Cntr=0.3,0.1

Type RM Length L Ch R = 1 ,10132   ,378,378,378
BEGIN DESCRIPTION:
UNT 109 in HW 20.0
END DESCRIPTION:
XS GIS Cut Line= 3
        1984375.       13585225.        1983575.       13584225.
      1983158.72     13583795.01
#Sta/Elev= 30
  3744.4  668.01  4007.7  660.34  4135.8  657.81  4192.6  657.08    4235   657.2
  4263.8  656.05  4327.9  654.73  4512.8  651.77  4534.4  651.67  4576.8  652.23
  4691.3  649.78 4808.66649.2654  4889.8  648.89    5008  645.61  5008.5  644.81
  5014.4  644.81  5014.9  645.61  5039.1  645.83  5102.8  647.87 5179.08649.2653
  5343.3  650.02  5399.9  650.57  5406.9  650.95  5435.2  651.02  5477.6  651.68
    5527   653.1  5562.5  653.51  5611.9  654.99  5619.1  654.75  5623.5  655.28
#Mann= 3 ,-1 , 0
  3744.4      .1       0    5008     .07       0  5014.9      .1       0
Bank Sta=4808.66,5179.08
XS Rating Curve= 0 ,0
Exp/Cntr=0.3,0.1

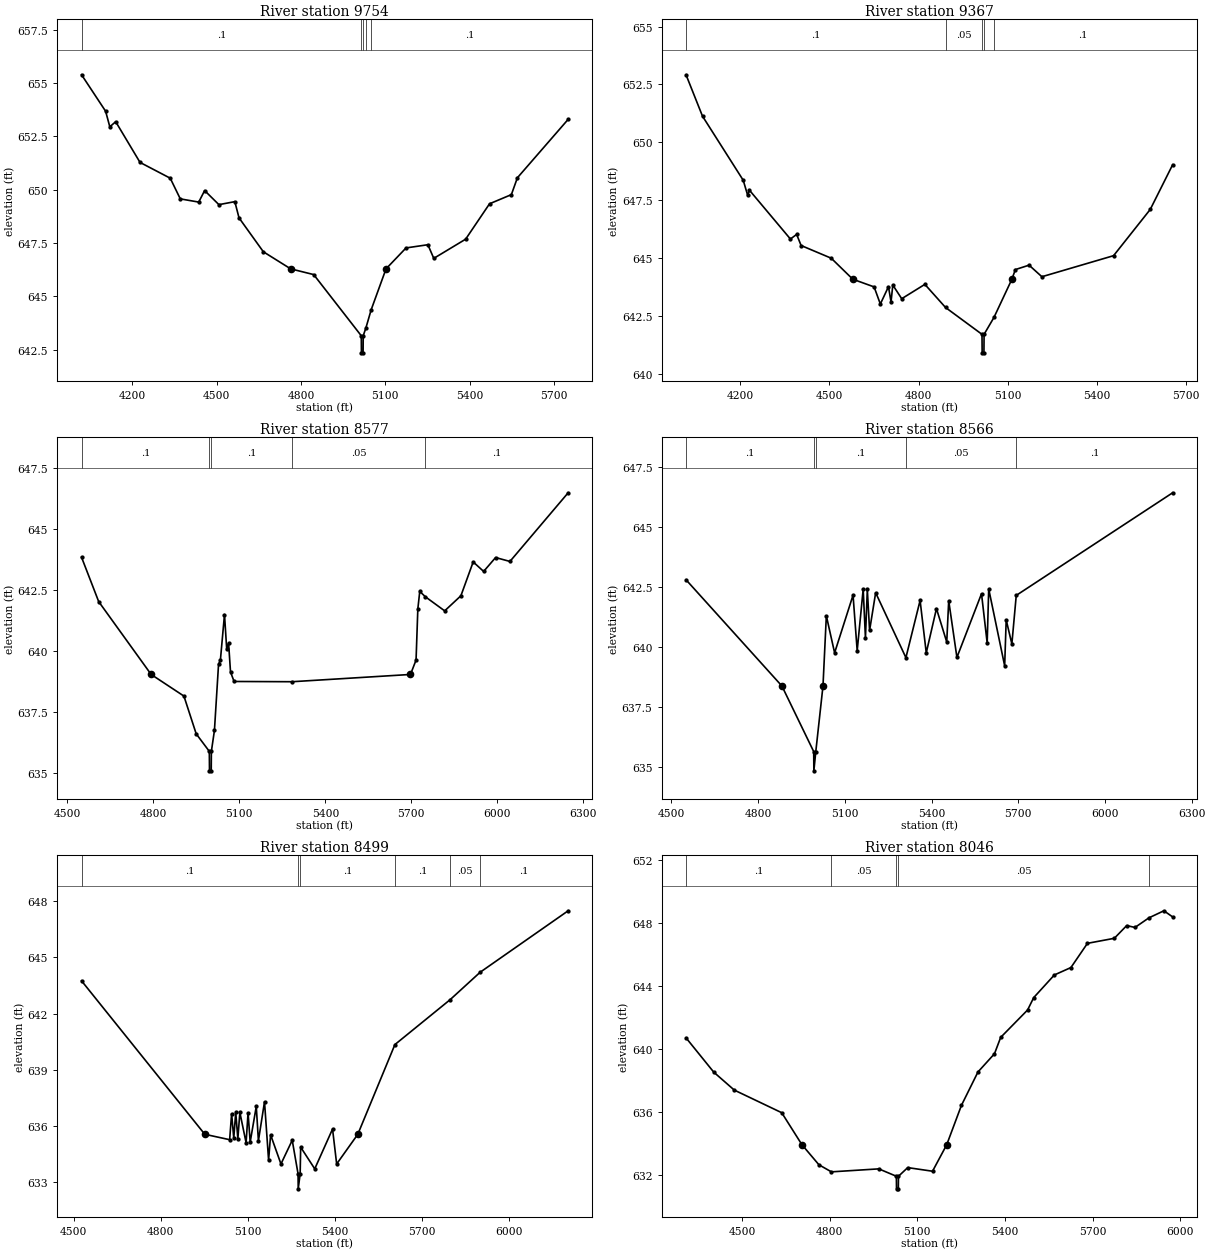
Type RM Length L Ch R = 1 ,9754    ,387,387,387
BEGIN DESCRIPTION:
UNT 109 in HW 19.0
END DESCRIPTION:
XS GIS Cut Line= 3
      1984438.63      13584840.5        1983875.       13584025.
      1983335.78     13583518.82
#Sta/Elev= 30
  4019.7  655.39  4105.3  653.68  4120.2  652.95  4141.1  653.19  4227.7  651.28
  4335.1  650.54  4370.9  649.57  4436.5  649.42  4457.5  649.96  4508.2   649.3
  4564.9  649.44  4579.8  648.68  4666.3  647.09 4763.58646.2881  4845.4  646.02
  5014.7  643.15  5015.2  642.35  5021.1  642.35  5021.6  643.15  5031.4  643.53
  5049.9  644.37 5102.71646.2882  5173.9  647.27  5251.6  647.42  5272.6  646.78
  5385.9  647.68  5470.9  649.34  5548.6  649.77    5570  650.56  5750.6   653.3
#Mann= 5 ,-1 , 0
  4019.7      .1       0  5014.7     .07       0  5021.6      .1       0
  5031.4     .05       0  5049.9      .1       0
Bank Sta=4763.58,5102.71
XS Rating Curve= 0 ,0
Exp/Cntr=0.3,0.1

Type RM Length L Ch R = 1 ,9367    ,790,790,790
BEGIN DESCRIPTION:
UNT 109 in HW 18.0
END DESCRIPTION:
XS GIS Cut Line= 3
      1984766.75      13584731.1        1984225.       13583925.
      1983891.78     13583345.74
#Sta/Elev= 30
  4016.7  652.92  4072.2  651.13  4209.4  648.36  4224.4  647.71  4230.4  647.93
  4368.4  645.82  4389.4  646.02  4404.4  645.54    4506  644.99 4578.52644.0828
  4650.4  643.75  4671.4  643.01  4698.8  643.76  4707.4   643.1  4713.4  643.83
  4743.4  643.24  4821.4  643.86  4891.1  642.86  5013.9   641.7  5014.4   640.9
  5020.4   640.9  5020.9   641.7  5054.2  642.43 5114.63644.0829  5126.4   644.5
  5172.5  644.69  5215.7  644.19  5457.2   645.1  5580.8   647.1  5656.2  649.03
#Mann= 5 ,-1 , 0
  4016.7      .1       0  4891.1     .05       0  5013.9    .035       0
  5020.9     .05       0  5054.2      .1       0
Bank Sta=4578.52,5114.63
XS Rating Curve= 0 ,0
Exp/Cntr=0.3,0.1

Type RM Length L Ch R = 1 ,8577    ,11,11,11
BEGIN DESCRIPTION:
Mapping XS d0768bae
END DESCRIPTION:
XS GIS Cut Line= 6
      1985222.05     13584181.64      1984881.35     13583782.34
      1985070.15     13583574.01      1984922.58     13583437.29
       1984790.2     13583406.91      1984358.36     13583087.91
#Sta/Elev= 30
  4549.2  643.84    4609  642.02 4792.13 639.028  4906.5  638.14  4949.3  636.59
  4995.1  635.87  4995.7  635.07  5001.8  635.07  5002.3  635.87    5013  636.73
  5027.3  639.44  5033.8  639.62  5048.1  641.49  5055.8  640.07  5062.4  640.32
  5069.1  639.13  5081.6  638.74  5284.1  638.73 5697.24639.0284  5716.7  639.62
  5722.9  641.72  5729.6  642.44  5749.1  642.22  5816.6  641.64  5873.2  642.26
  5916.1  643.65  5952.6  643.26  5994.3  643.83  6044.4  643.67  6247.6  646.49
#Mann= 5 ,-1 , 0
  4549.2      .1       0  4995.1     .07       0  5002.3      .1       0
  5284.1     .05       0  5749.1      .1       0
Bank Sta=4792.13,5697.24
XS Rating Curve= 0 ,0
Exp/Cntr=0.3,0.1

Type RM Length L Ch R = 1 ,8566    ,67,67,67
BEGIN DESCRIPTION:
Mapping XS 168f3976
END DESCRIPTION:
XS GIS Cut Line= 6
      1985255.06     13584154.75       1984916.5     13583810.99
        1985104.     13583633.91      1985109.21     13583576.61
      1984963.38     13583435.99      1984400.86     13583060.98
#Sta/Elev= 30
  4550.5  642.81 4882.26  638.39  4992.3  635.66  4992.8  634.86  4999.5  635.66
 5024.38638.3907    5036  641.31  5064.6  639.77  5128.4  642.17  5142.7  639.86
  5163.5  642.42  5171.3  640.39  5177.8  642.41  5185.6   640.7  5206.6  642.27
  5311.3  639.57  5360.4  641.95  5381.7  639.77    5417  641.61  5452.6  640.22
  5459.4  641.94  5487.8  639.58  5572.9  642.23  5592.5  640.18  5597.8  642.43
    5653  639.23  5658.3  641.14  5677.9  640.14  5693.1  642.16  6234.2  646.43
#Mann= 5 ,-1 , 0
  4550.5      .1       0  4992.3     .07       0  4999.5      .1       0
  5311.3     .05       0  5693.1      .1       0
Bank Sta=4882.26,5024.38
XS Rating Curve= 0 ,0
Exp/Cntr=0.3,0.1

Type RM Length L Ch R = 1 ,8499    ,453,453,453
BEGIN DESCRIPTION:
Mapping XS 82fecfe0
END DESCRIPTION:
XS GIS Cut Line= 6
      1985287.19     13584170.83      1984985.51     13583786.68
      1985139.59     13583643.45      1985130.91      13583545.8
      1984955.13     13583350.49      1984467.01     13583009.91
#Sta/Elev= 30
  4526.6  643.75 4951.46635.5396  5037.2  635.25    5044  636.64  5051.4  635.33
  5058.2  636.71  5065.5   635.3  5072.4  636.71  5093.9  635.09  5100.7  636.69
    5108  635.12    5129  637.03  5136.4  635.19  5157.4  637.28  5171.5  634.15
  5178.4  635.51  5214.1  633.95    5253  635.22  5273.1  633.42  5273.6  632.62
  5280.3  633.42  5282.1  634.85  5330.6  633.69    5392  635.82  5406.2  633.95
 5479.11635.5395    5607  640.34  5797.2  642.74  5900.9  644.21  6204.4   647.5
#Mann= 6 ,-1 , 0
  4526.6      .1       0  5273.1     .07       0  5280.3      .1       0
    5607      .1       0  5797.2     .05       0  5900.9      .1       0
Bank Sta=4951.46,5479.11
XS Rating Curve= 0 ,0
Exp/Cntr=0.3,0.1

Type RM Length L Ch R = 1 ,8046    ,335,335,335
BEGIN DESCRIPTION:
Mapping XS dd1f0d2c
END DESCRIPTION:
XS GIS Cut Line= 3
      1985588.38     13584029.79      1985572.75     13583764.11
      1984593.58     13582764.11
#Sta/Elev= 30
  4308.5   640.7  4403.4  638.52  4473.6  637.38  4636.1  635.94 4705.22633.9073
  4763.4  632.63  4806.2  632.18  4968.4  632.37  5028.5   631.9    5029   631.1
  5035.2   631.1  5035.7   631.9  5067.4  632.45  5152.3  632.22 5200.91633.9074
  5251.3  636.41  5307.8  638.53  5364.4  639.69  5385.6  640.73  5477.6  642.47
  5498.7  643.26  5569.4   644.7    5626  645.17  5682.6  646.71  5774.6  647.03
    5817  647.84  5845.3  647.72    5893  648.33  5944.3  648.78  5974.2  648.39
#Mann= 5 ,-1 , 0
  4308.5      .1       0  4806.2     .05       0  5028.5     .03       0
  5035.7     .05       0    5893      .1       0
Bank Sta=4705.22,5200.91
XS Rating Curve= 0 ,0
Exp/Cntr=0.3,0.1

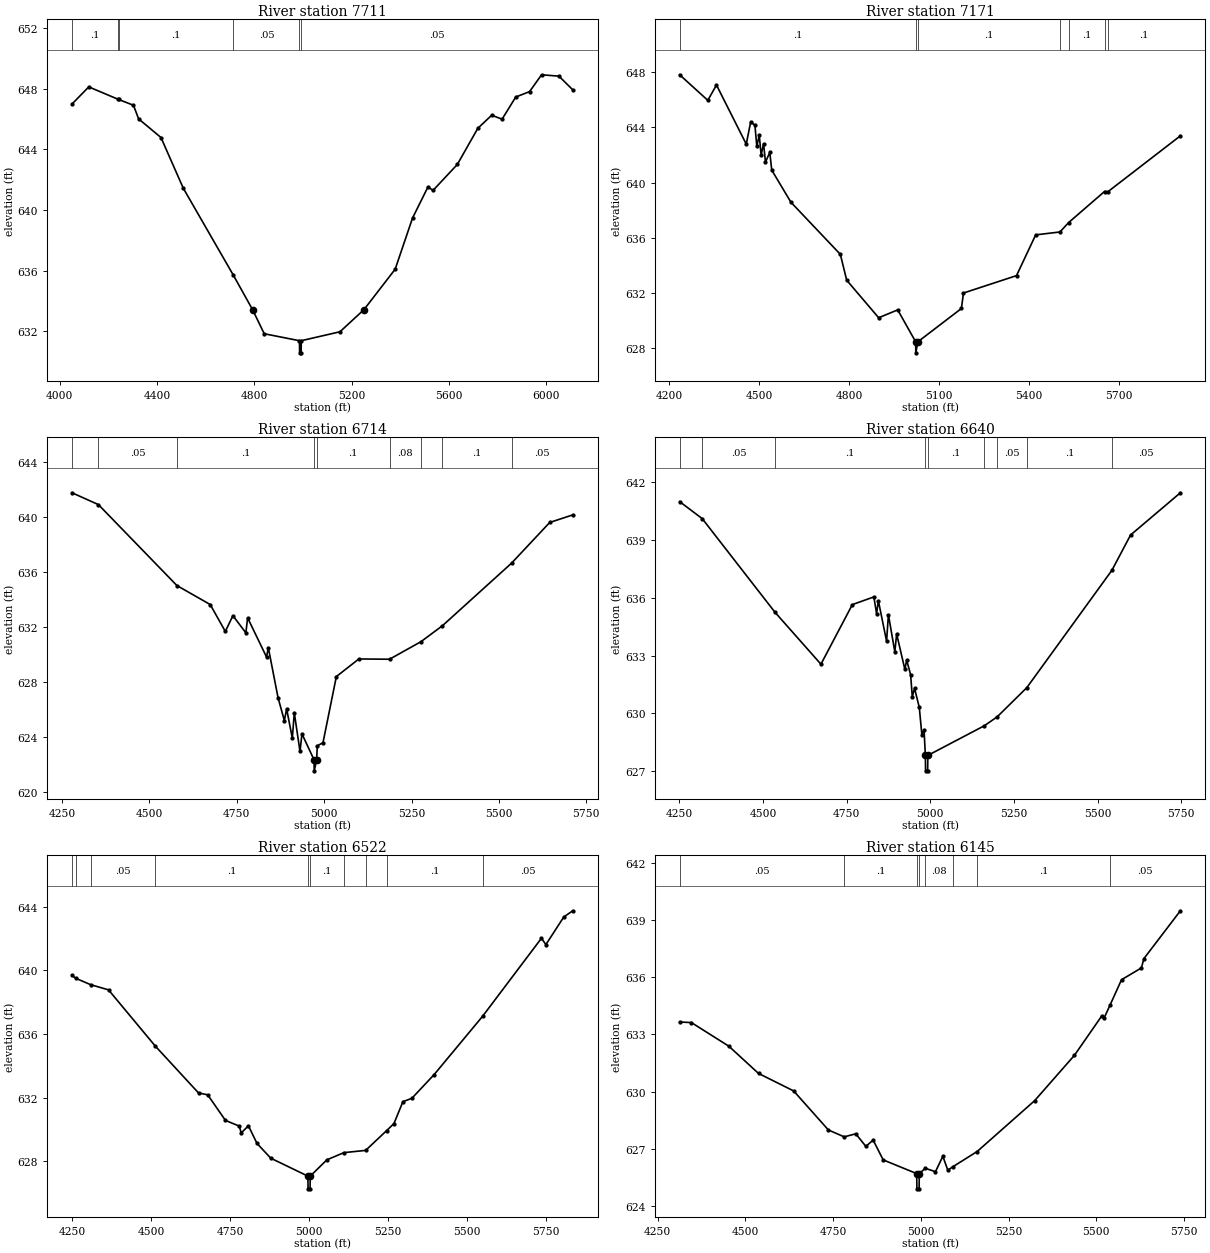
Type RM Length L Ch R = 1 ,7711    ,540,540,540
BEGIN DESCRIPTION:
UNT 109 in HW 14.0
END DESCRIPTION:
XS GIS Cut Line= 3
      1986193.39     13583884.17      1985724.66     13583415.45
      1984665.66     13582504.01
#Sta/Elev= 30
  4050.1  646.99  4119.1  648.12  4238.7  647.31  4241.8  647.29  4302.9  646.91
  4324.1  646.01  4416.1  644.78    4508  641.43  4714.4  635.68 4792.94633.4198
  4840.9  631.83    4986  631.37  4986.5  630.57  4992.7  630.57  4993.3  631.37
  5152.5  631.96 5251.24633.4199  5379.7  636.09    5451  639.46  5514.6  641.52
  5535.5  641.29  5635.3     643  5719.8  645.39  5776.9  646.25  5819.6  645.99
  5875.6  647.45  5932.7  647.81    5982  648.92  6053.4  648.83  6110.2  647.93
#Mann= 6 ,-1 , 0
  4050.1      .1       0  4238.7     .05       0  4241.8      .1       0
  4714.4     .05       0    4986    .035       0  4993.3     .05       0
Bank Sta=4792.94,5251.24
XS Rating Curve= 0 ,0
Exp/Cntr=0.3,0.1

Type RM Length L Ch R = 1 ,7171    ,457,457,457
BEGIN DESCRIPTION:
UNT 109 in HW 13.0
END DESCRIPTION:
XS GIS Cut Line= 3
      1986364.39     13583247.62      1985857.45     13582844.84
      1985114.37     13582143.44
#Sta/Elev= 30
  4234.4  647.81  4328.2  645.96  4357.1  647.07  4456.4  642.79  4470.8  644.36
  4485.2  644.18  4491.6  642.63  4499.7  643.44    4506     642  4514.1  642.81
  4520.5  641.49  4534.9  642.19  4541.3  640.91  4605.4  638.58  4770.1  634.81
  4791.2  632.94  4897.8  630.22  4961.3  630.79  5021.1  628.48  5021.7  627.68
  5028.5  628.48  5173.7  630.89  5180.6  632.01  5357.4  633.27  5421.3  636.22
  5502.2  636.43  5531.1  637.11  5650.8  639.36  5662.4  639.35  5903.7  643.39
#Mann= 7 ,-1 , 0
  4234.4      .1       0  5021.1     .07       0  5028.5      .1       0
  5502.2     .05       0  5531.1      .1       0  5650.8     .05       0
  5662.4      .1       0
Bank Sta=5021.1,5028.5
XS Rating Curve= 0 ,0
Exp/Cntr=0.3,0.1

Type RM Length L Ch R = 1 ,6714    ,74,74,74
BEGIN DESCRIPTION:
Mapping XS f7d48354
END DESCRIPTION:
XS GIS Cut Line= 5
      1986512.45     13582703.66      1986152.18     13582417.18
      1986004.61     13582391.14      1985817.98     13582291.31
      1985367.15      13581879.5
#Sta/Elev= 30
  4278.6  641.74  4354.1  640.88  4578.7  634.99  4673.9  633.61  4717.2  631.65
  4738.9   632.8  4775.9  631.55    4781  632.64  4835.1  629.79  4840.2  630.47
    4868  626.83    4886  625.17  4892.6  626.01  4908.8  623.89  4914.5  625.73
  4930.8  622.92  4936.4   624.2    4971  622.31  4971.5  621.51  4978.4  622.31
  4980.3  623.33  4996.6  623.56  5034.8  628.37  5099.2  629.65    5187  629.63
    5277  630.91  5338.4  632.07    5536  636.62  5645.2  639.58    5711  640.13
#Mann= 9 ,-1 , 0
  4278.6      .1       0  4354.1     .05       0  4578.7      .1       0
    4971     .07       0  4978.4      .1       0    5187     .08       0
    5277     .05       0  5338.4      .1       0    5536     .05       0
Bank Sta=4971,4978.4
XS Rating Curve= 0 ,0
Exp/Cntr=0.3,0.1

Type RM Length L Ch R = 1 ,6640    ,118,118,118
BEGIN DESCRIPTION:
Mapping XS bb3ae586
END DESCRIPTION:
XS GIS Cut Line= 4
      1986538.46     13582660.24       1986143.5     13582378.12
      1985952.53     13582304.33      1985344.88     13581774.81
#Sta/Elev= 30
  4251.3  640.98  4318.7   640.1  4535.8  635.25  4673.4  632.55  4767.2  635.64
  4831.5  636.04  4839.7  635.17    4845  635.84  4869.6  633.74    4875  635.12
  4894.2  633.19  4899.6  634.12  4924.2  632.28  4929.5  632.77  4941.4     632
  4946.4  630.86    4953   631.3  4967.3  630.31  4974.9   628.9  4981.5  629.15
  4985.4  627.82    4986  627.02  4992.3  627.02  4992.8  627.82  5161.8  629.36
    5200  629.82  5288.8  631.34  5542.8  637.42  5598.6  639.25  5747.4  641.44
#Mann= 9 ,-1 , 0
  4251.3      .1       0  4318.7     .05       0  4535.8      .1       0
  4985.4     .07       0  4992.8      .1       0  5161.8     .08       0
    5200     .05       0  5288.8      .1       0  5542.8     .05       0
Bank Sta=4985.4,4992.8
XS Rating Curve= 0 ,0
Exp/Cntr=0.3,0.1

Type RM Length L Ch R = 1 ,6522    ,377,377,377
BEGIN DESCRIPTION:
UNT 109 in HW 12.0
END DESCRIPTION:
XS GIS Cut Line= 3
       1986560.6     13582620.91        1985975.       13582175.
      1985374.98     13581574.98
#Sta/Elev= 30
  4250.2  639.69  4261.8  639.51  4308.7  639.11  4365.7  638.78  4513.3  635.25
  4650.5  632.29  4679.6  632.17  4735.8  630.56  4779.4   630.2  4785.7  629.77
  4808.5  630.22  4835.6  629.11  4879.2  628.18  4996.7  627.05  4997.2  626.25
  5003.5  626.25  5004.1  627.05    5057  628.08  5110.7  628.53  5179.4  628.67
  5245.5  629.91  5269.1  630.36  5297.4  631.74  5325.7  631.95  5396.4  633.45
  5549.7  637.12  5735.8  642.03  5749.9  641.63  5806.5  643.37  5834.8  643.76
#Mann= 10 ,-1 , 0
  4250.2     .05       0  4261.8      .1       0  4308.7     .05       0
  4513.3      .1       0  4996.7     .07       0  5004.1      .1       0
  5110.7     .08       0  5179.4     .05       0  5245.5      .1       0
  5549.7     .05       0
Bank Sta=4996.7,5004.1
XS Rating Curve= 0 ,0
Exp/Cntr=0.3,0.1

Type RM Length L Ch R = 1 ,6145    ,315,315,315
BEGIN DESCRIPTION:
UNT 109 in HW 11.0
END DESCRIPTION:
XS GIS Cut Line= 3
       1986685.6     13582301.46        1986175.       13581875.
      1985623.05     13581350.03
#Sta/Elev= 30
  4312.6  633.65    4346  633.62  4452.7  632.38  4537.3  630.95  4637.5  630.03
  4736.5  627.98  4781.6  627.62  4814.5  627.78  4843.2  627.12    4864  627.45
  4892.6  626.41  4988.1  625.69  4988.7  624.89    4995  624.89  4995.5  625.69
  5012.5  625.97  5041.6  625.79  5062.6   626.6  5076.8  625.87  5091.2  626.05
  5160.4  626.85  5324.3  629.52  5437.6   631.9  5515.6  633.97  5522.5  633.87
  5539.7  634.56  5571.9  635.87  5628.5  636.49  5635.7  636.98  5739.6  639.49
#Mann= 8 ,-1 , 0
  4312.6     .05       0  4781.6      .1       0  4988.1     .07       0
  4995.5      .1       0  5012.5     .08       0  5091.2     .05       0
  5160.4      .1       0  5539.7     .05       0
Bank Sta=4988.1,4995.5
XS Rating Curve= 0 ,0
Exp/Cntr=0.3,0.1

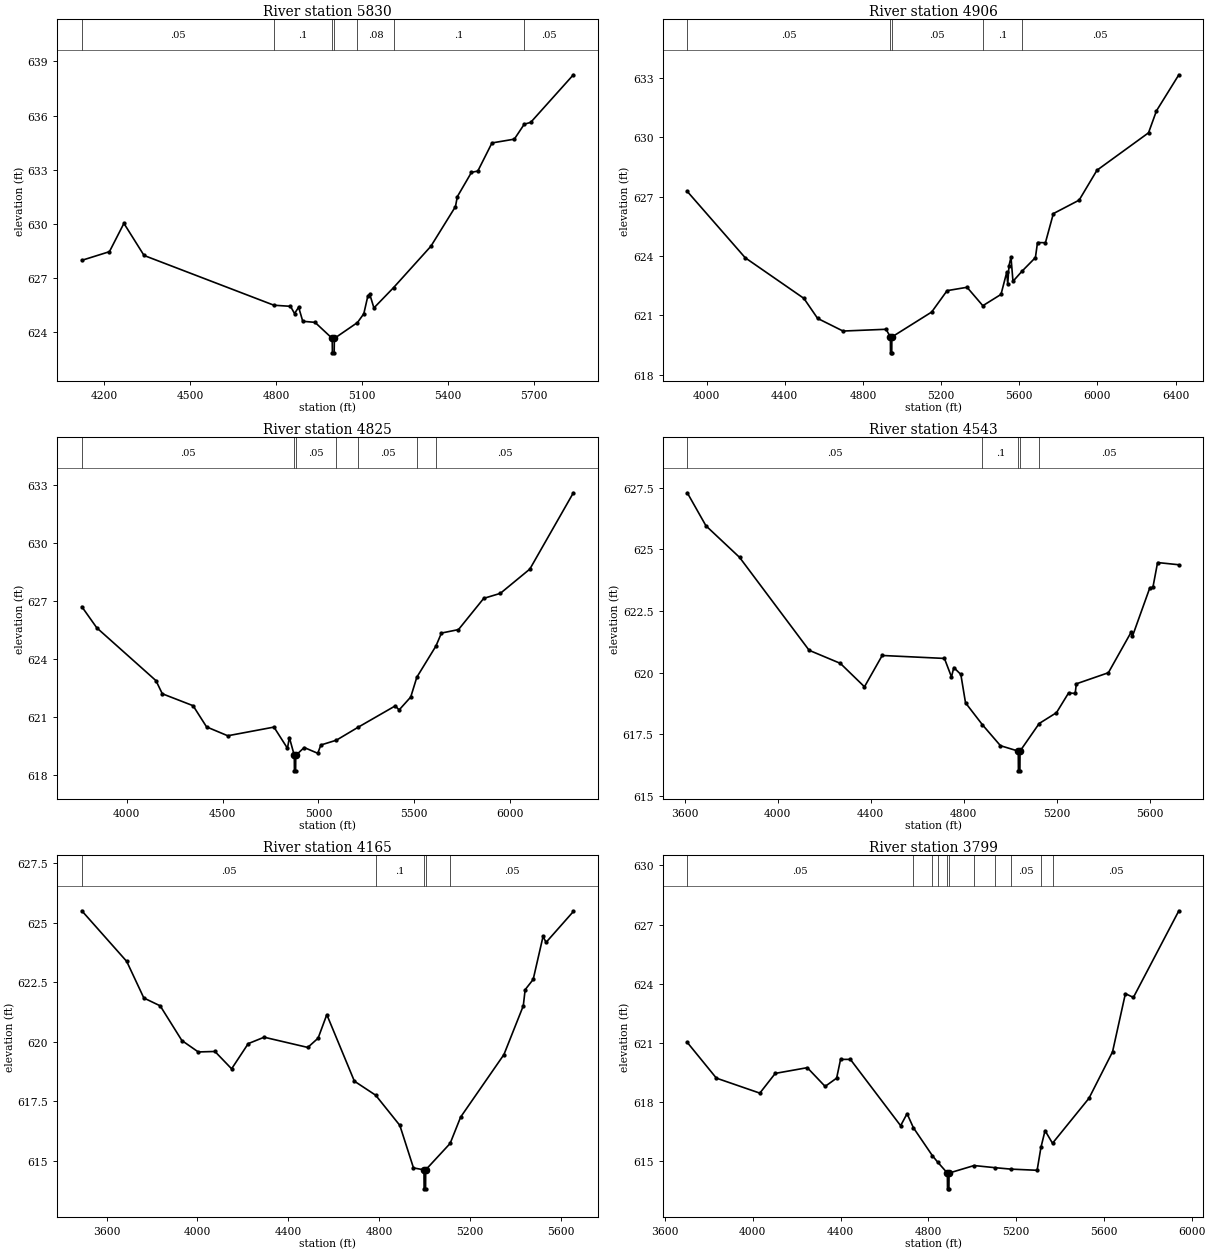
Type RM Length L Ch R = 1 ,5830    ,924,924,924
BEGIN DESCRIPTION:
UNT 109 in HW 10.0
END DESCRIPTION:
XS GIS Cut Line= 2
      1987027.21     13582189.11      1985724.97     13581074.98
#Sta/Elev= 30
  4122.6  627.97  4218.9  628.45  4269.4  630.02  4339.6  628.24  4792.5  625.48
  4850.1  625.42  4864.3  625.02  4878.6  625.37  4892.9  624.59  4935.7  624.53
  4995.6  623.64  4996.2  622.84  5002.5  622.84  5003.1  623.64  5083.7  624.52
  5105.8  625.01  5120.1  626.01  5126.7  626.08    5141  625.33  5209.7  626.46
  5339.6  628.75  5425.3  630.95  5431.8   631.5  5481.2  632.85  5503.2  632.92
  5552.6  634.48  5630.5  634.69  5665.2  635.52  5687.6  635.62  5836.4  638.26
#Mann= 7 ,-1 , 0
  4122.6     .05       0  4792.5      .1       0  4995.6     .07       0
  5003.1      .1       0  5083.7     .08       0  5209.7      .1       0
  5665.2     .05       0
Bank Sta=4995.6,5003.1
XS Rating Curve= 0 ,0
Exp/Cntr=0.3,0.1

Type RM Length L Ch R = 1 ,4906    ,81,81,81
BEGIN DESCRIPTION:
Mapping XS b3f8d186
END DESCRIPTION:
XS GIS Cut Line= 5
      1987110.54      13582241.2      1987154.32     13581198.14
      1986511.96     13581332.69      1986442.51     13581345.71
      1986316.64     13580612.17
#Sta/Elev= 30
  3901.3  627.26  4197.8  623.91    4498  621.86  4568.1  620.85  4698.2  620.21
  4918.4   620.3  4940.6  619.91  4941.2  619.11  4947.5  619.11  4948.1  619.91
  5151.7  621.17  5230.7  622.25  5332.8  622.42  5413.6  621.49  5506.5  622.06
  5535.9  623.18    5541  622.58  5547.4  623.51  5557.6  623.94  5567.8  622.72
  5612.9  623.22  5682.6  623.92  5693.3  624.68  5733.8  624.67  5774.4  626.14
  5906.3  626.82  5997.6  628.33  6261.4  630.22    6302  631.33  6416.5  633.15
#Mann= 5 ,-1 , 0
  3901.3     .05       0  4940.6     .04       0  4948.1     .05       0
  5413.6      .1       0  5612.9     .05       0
Bank Sta=4940.6,4948.1
XS Rating Curve= 0 ,0
Exp/Cntr=0.3,0.1

Type RM Length L Ch R = 1 ,4825    ,282,282,282
BEGIN DESCRIPTION:
Mapping XS 4de5d7a4
END DESCRIPTION:
XS GIS Cut Line= 4
      1987123.57     13582222.94      1987228.11     13581111.34
       1986472.9     13581219.84       1986399.2     13580539.19
#Sta/Elev= 30
  3765.6  626.71  3843.9  625.61  4152.5  622.87  4185.4  622.19  4346.1  621.57
  4416.4  620.47  4526.9  620.01  4767.9  620.46  4838.3  619.36  4848.3  619.92
    4874  618.99  4874.6  618.19  4880.9  618.19  4881.5  618.99  4925.7   619.4
  4996.4   619.1  5012.4  619.53  5093.4  619.78  5206.5  620.45  5400.5  621.56
  5420.7  621.35  5481.3  622.02  5513.2  623.05    5613  624.67  5641.5  625.34
  5730.4  625.52    5862  627.14  5948.7   627.4  6102.6  628.66  6329.7  632.62
#Mann= 7 ,-1 , 0
  3765.6     .05       0    4874     .04       0  4881.5     .05       0
  5093.4      .1       0  5206.5     .05       0  5513.2     .08       0
    5613     .05       0
Bank Sta=4874,4881.5
XS Rating Curve= 0 ,0
Exp/Cntr=0.3,0.1

Type RM Length L Ch R = 1 ,4543    ,378,378,378
BEGIN DESCRIPTION:
Mapping XS 0b08c6a8
END DESCRIPTION:
XS GIS Cut Line= 3
      1987131.37     13582282.89      1987342.74     13581460.22
       1987184.7     13580204.22
#Sta/Elev= 30
  3610.7   627.3  3691.1  625.96  3835.7  624.68  4135.1  620.91  4269.3  620.38
  4373.2  619.43  4449.5   620.7  4717.3  620.58  4747.6  619.83  4757.6  620.21
  4787.9  619.93    4808  618.78  4880.7  617.89  4958.4  617.04    5035  616.82
  5035.6  616.02    5042  616.02  5042.6  616.82    5125  617.94  5199.5  618.38
  5251.5  619.18  5279.9  619.16  5284.9  619.55  5422.8     620    5521  621.65
    5526  621.47  5601.3  623.45  5614.3  623.46  5634.5  624.47    5726  624.38
#Mann= 5 ,-1 , 0
  3610.7     .05       0  4880.7      .1       0    5035     .07       0
  5042.6      .1       0    5125     .05       0
Bank Sta=5035,5042.6
XS Rating Curve= 0 ,0
Exp/Cntr=0.3,0.1

Type RM Length L Ch R = 1 ,4165    ,366,366,366
BEGIN DESCRIPTION:
Mapping XS 3ae569e0
END DESCRIPTION:
XS GIS Cut Line= 4
      1987209.51      13582194.3      1987540.61     13581137.38
      1987562.31     13580508.04      1987302.07     13580169.74
#Sta/Elev= 30
  3490.7  625.51  3688.4  623.38  3763.8  621.84  3835.8  621.51  3931.3  620.05
  4003.5  619.57  4076.8  619.59  4150.2  618.86  4223.3  619.92  4293.4  620.19
  4485.5  619.76    4531  620.15  4569.3  621.14  4690.7  618.34  4784.4  617.75
  4890.8  616.48  4950.9  614.69  4997.1  614.61  4997.7  613.81  5004.1  613.81
  5004.7  614.61  5112.2  615.72  5158.5  616.83  5349.1  619.46  5434.3  621.51
  5442.5  622.19  5477.8  622.62  5521.3  624.43  5534.6  624.18  5654.8  625.48
#Mann= 5 ,-1 , 0
  3490.7     .05       0  4784.4      .1       0  4997.1     .07       0
  5004.7      .1       0  5112.2     .05       0
Bank Sta=4997.1,5004.7
XS Rating Curve= 0 ,0
Exp/Cntr=0.3,0.1

Type RM Length L Ch R = 1 ,3799    ,43,43,43
BEGIN DESCRIPTION:
Mapping XS b6a54a68
END DESCRIPTION:
XS GIS Cut Line= 6
      1987349.63     13581866.55      1987814.04     13580798.84
      1987957.27     13580651.27      1987879.15      13580590.5
        1987788.     13580599.18      1987414.73     13580065.32
#Sta/Elev= 30
  3701.7  621.03  3834.3  619.22  4032.3  618.46  4102.6  619.46  4248.6  619.75
  4329.9   618.8  4382.3  619.22  4400.2  620.17  4444.9  620.17  4673.9  616.81
  4703.3  617.42  4731.9  616.71  4818.7  615.29  4843.8  614.95  4886.9  614.41
  4887.5  613.61  4893.9  613.61  4894.6  614.41  5008.6  614.79    5106  614.68
  5175.5  614.61  5295.9  614.55  5313.3  615.71    5332  616.56    5366  615.92
  5532.2   618.2  5639.5  620.55  5698.1   623.5  5734.6  623.31  5941.7   627.7
#Mann= 11 ,-1 , 0
  3701.7     .05       0  4731.9      .1       0  4818.7     .08       0
  4843.8      .1       0  4886.9     .07       0  4894.6      .1       0
  5008.6     .05       0    5106      .1       0  5175.5     .05       0
  5313.3      .1       0    5366     .05       0
Bank Sta=4886.9,4894.6
XS Rating Curve= 0 ,0
Exp/Cntr=0.3,0.1