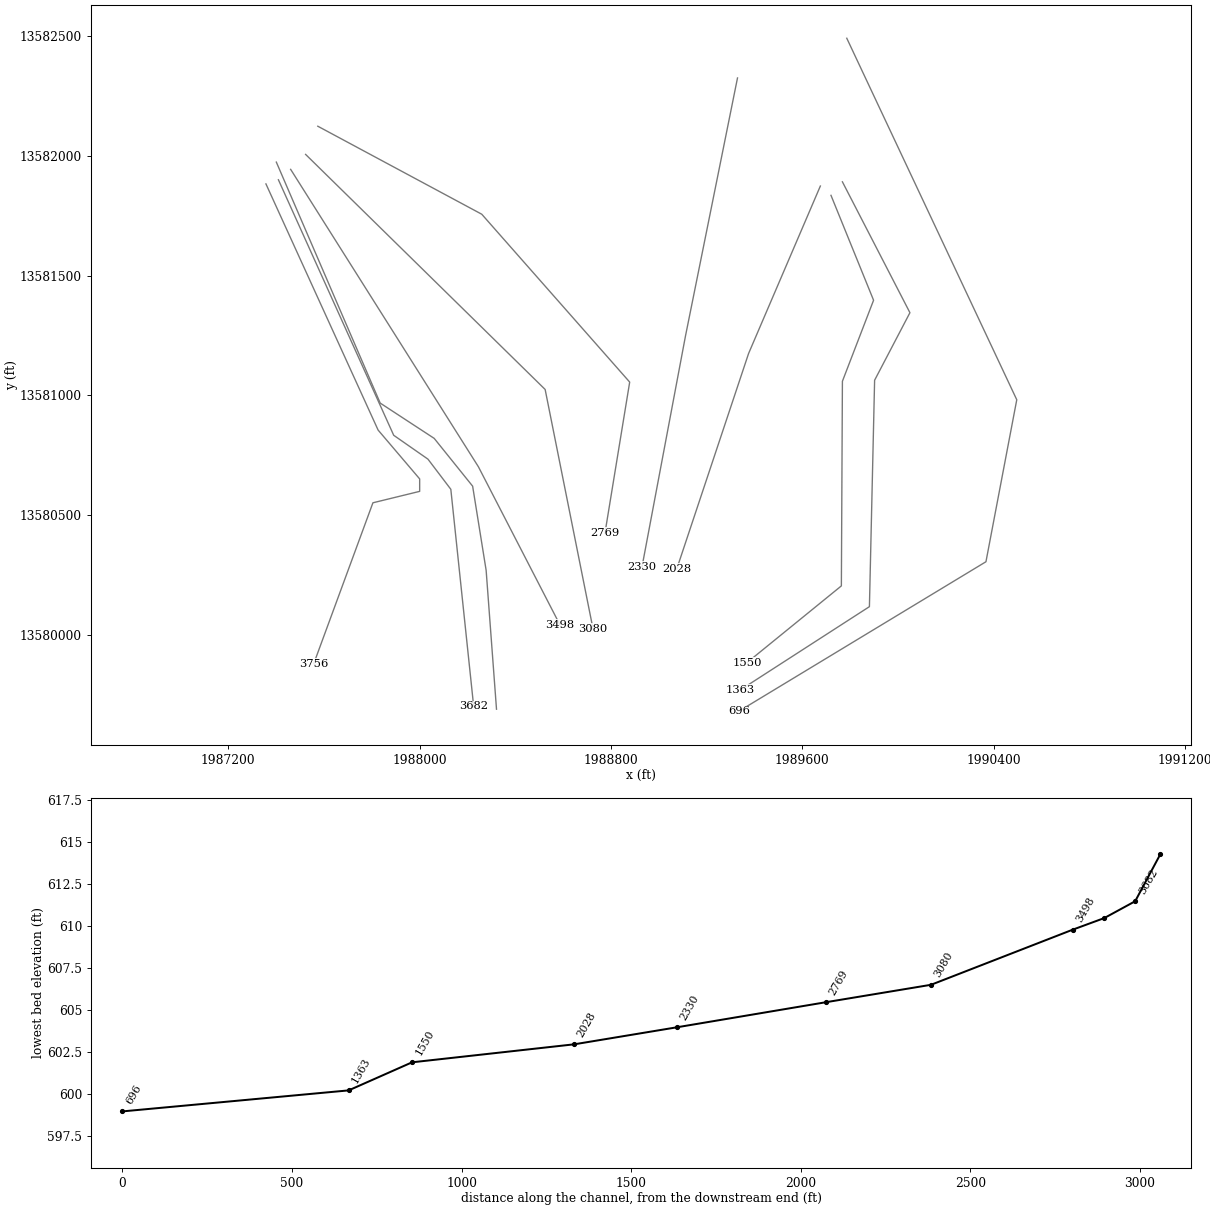
HEC-RAS study UNT 109 in HW.prj: UNT 109 in HW Base Level Engineering

--- UNT 109 in HW.g01 (geometry) --- (continued)

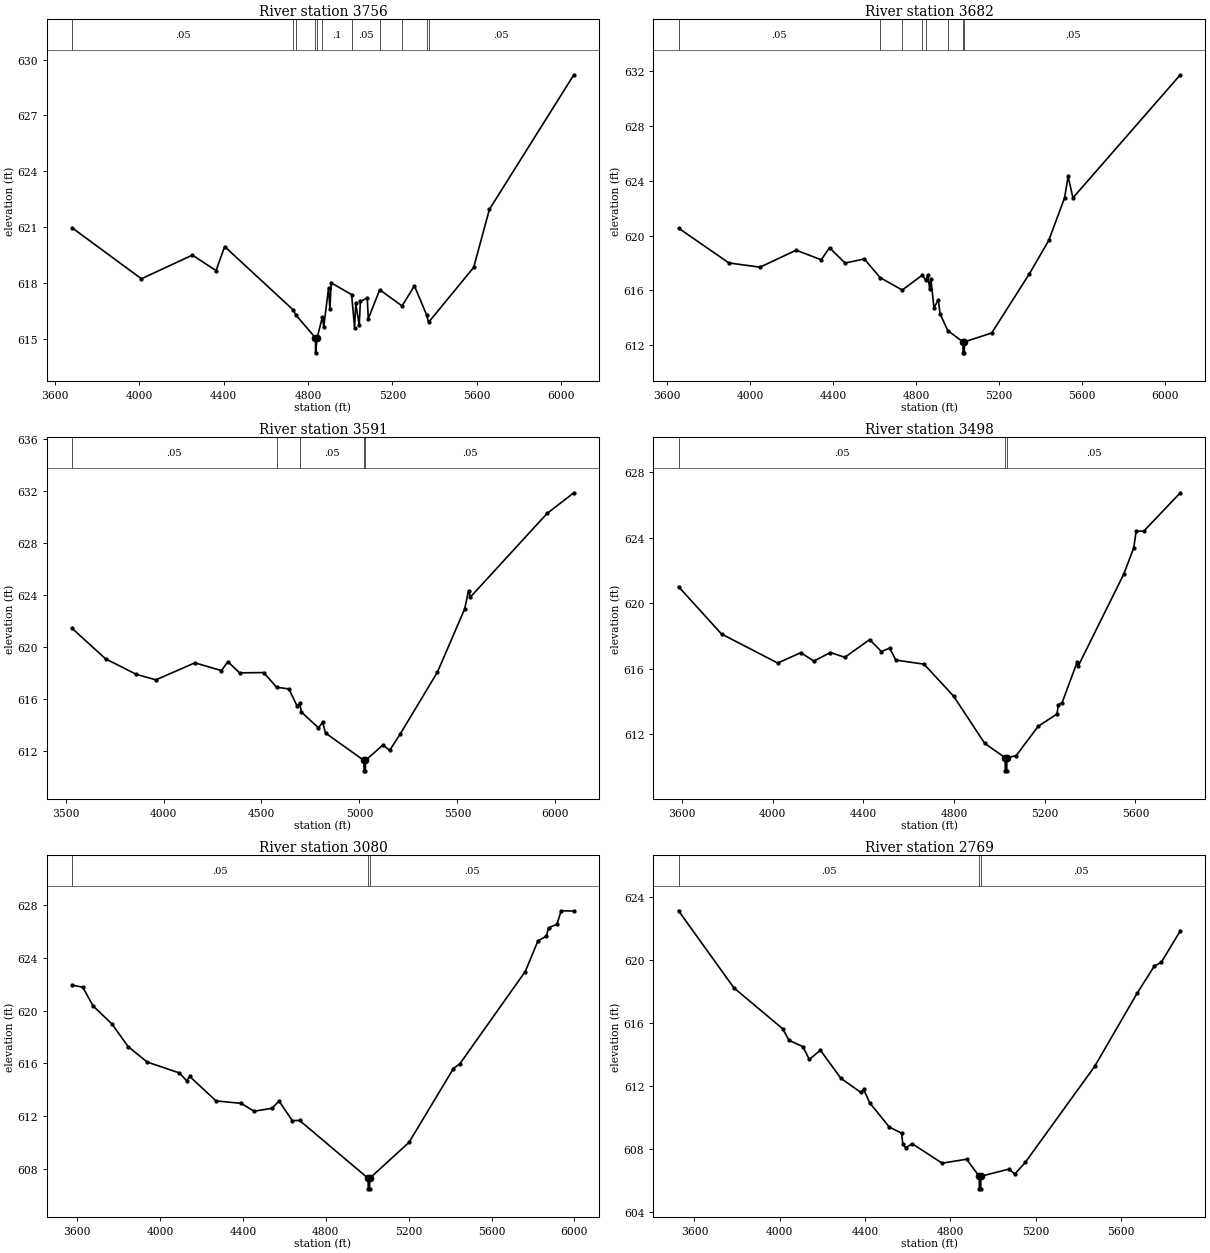
Type RM Length L Ch R = 1 ,3756    ,74,74,74
BEGIN DESCRIPTION:
Mapping XS 5c5698f4
END DESCRIPTION:
XS GIS Cut Line= 6
      1987358.31     13581883.92      1987827.06     13580855.26
      1988000.67     13580651.27      1988000.67     13580599.18
      1987805.36     13580551.44      1987558.21     13579879.36
#Sta/Elev= 30
  3681.5  620.96    4010  618.22  4251.8  619.49    4364  618.66  4404.6  619.95
  4728.3  616.56  4743.4  616.26  4835.1  615.04  4835.7  614.24  4842.8  615.04
  4867.9  616.17  4874.3  615.64  4897.1  617.73  4903.4   616.6  4909.8     618
  5006.3  617.37  5020.3   615.6    5026   616.9  5042.2  615.71  5047.9     617
  5080.4  617.19  5085.4  616.07  5139.4  617.63  5245.4  616.76  5303.9  617.84
  5361.3  616.29    5371  615.88  5584.8  618.83  5659.4  621.95  6059.6  629.18
#Mann= 11 ,-1 , 0
  3681.5     .05       0  4728.3      .1       0  4743.4     .08       0
  4835.1     .07       0  4842.8     .08       0  4867.9      .1       0
  5006.3     .05       0  5139.4      .1       0  5245.4     .05       0
  5361.3      .1       0    5371     .05       0
Bank Sta=4835.1,4842.8
XS Rating Curve= 0 ,0
Exp/Cntr=0.3,0.1

Type RM Length L Ch R = 1 ,3682    ,91,91,91
BEGIN DESCRIPTION:
Mapping XS ce09e6a6
END DESCRIPTION:
XS GIS Cut Line= 5
      1987410.41     13581901.25      1987892.17     13580833.56
       1988035.4     13580733.73      1988130.88     13580607.86
      1988226.36     13579700.79
#Sta/Elev= 30
  3656.3  620.55  3898.7  618.01  4048.5   617.7  4222.7  618.94  4343.3  618.24
  4383.2  619.12  4458.1     618  4550.6   618.3  4626.9  616.94  4733.5  616.03
  4829.7  617.12    4847  616.74  4856.5  617.13  4865.2  616.14  4871.3  616.85
  4886.1  614.73  4907.1  615.32  4915.8  614.29  4952.3  613.08  5025.4  612.25
    5026  611.45  5032.5  611.45  5033.1  612.25  5164.2   612.9    5346  617.23
    5439  619.66    5515  622.76    5532  624.32  5555.3  622.76  6072.3  631.74
#Mann= 8 ,-1 , 0
  3656.3     .05       0  4626.9      .1       0  4733.5     .08       0
  4829.7     .05       0    4847      .1       0  4952.3     .05       0
  5025.4     .04       0  5033.1     .05       0
Bank Sta=5025.4,5033.1
XS Rating Curve= 0 ,0
Exp/Cntr=0.3,0.1

Type RM Length L Ch R = 1 ,3591    ,93,93,93
BEGIN DESCRIPTION:
UNT 109 in HW 9.0
END DESCRIPTION:
XS GIS Cut Line= 6
      1987401.72     13581975.05      1987835.74     13580968.11
      1988061.44     13580820.54      1988222.03     13580620.89
      1988278.45     13580269.32      1988321.77     13579688.88
#Sta/Elev= 30
  3533.4  621.43  3704.1  619.08  3861.5  617.88  3961.1  617.46  4160.1  618.77
  4295.7  618.17  4328.4  618.86  4388.1     618  4511.2  618.02    4577  616.89
  4639.8  616.76    4682  615.43  4695.6  615.66  4703.1  614.99  4790.6  613.76
  4811.7  614.19  4826.8  613.36  5022.9  611.25  5023.5  610.45    5030  610.45
  5030.6  611.25  5119.5  612.44  5154.2  612.03  5206.7  613.26  5397.6  618.05
  5536.9  622.93  5556.3  624.33  5566.3  623.84  5957.4  630.28  6093.9  631.87
#Mann= 5 ,-1 , 0
  3533.4     .05       0    4577      .1       0  4695.6     .05       0
  5022.9    .035       0  5030.6     .05       0
Bank Sta=5022.9,5030.6
XS Rating Curve= 0 ,0
Exp/Cntr=0.3,0.1

Type RM Length L Ch R = 1 ,3498    ,418,418,418
BEGIN DESCRIPTION:
UNT 109 in HW 8.0
END DESCRIPTION:
XS GIS Cut Line= 3
       1987461.6     13581944.69      1988246.33     13580701.61
      1988586.63     13580041.86
#Sta/Elev= 30
  3585.3     621  3774.9  618.11  4022.5  616.34  4124.3  616.97    4182  616.46
  4254.9  616.98  4318.5  616.69  4427.9  617.77  4479.6  617.04  4516.1  617.25
  4543.2  616.52  4667.9  616.27  4798.5  614.31    4935  611.44  5025.3  610.56
  5025.9  609.76  5032.4  609.76    5033  610.56    5074  610.69  5171.1  612.48
  5254.1  613.23  5259.7  613.79  5276.2  613.91  5342.7  616.39  5348.3  616.18
  5547.8  621.75  5592.1  623.36  5602.9  624.38  5636.6  624.39  5797.7  626.73
#Mann= 3 ,-1 , 0
  3585.3     .05       0  5025.3    .035       0    5033     .05       0
Bank Sta=5025.3,5033
XS Rating Curve= 0 ,0
Exp/Cntr=0.3,0.1

Type RM Length L Ch R = 1 ,3080    ,311,311,311
BEGIN DESCRIPTION:
UNT 109 in HW 7.0
END DESCRIPTION:
XS GIS Cut Line= 3
      1987524.12     13582007.16        1988525.       13581025.
        1988725.     13580024.99
#Sta/Elev= 30
  3575.4  621.94  3627.1  621.78  3676.5  620.37  3768.5  618.98  3846.2  617.27
  3938.2   616.1  4093.8  615.27  4129.1  614.67  4143.3  615.01  4270.5  613.15
  4390.7  612.97  4454.4  612.37  4539.3  612.59  4574.6  613.14  4638.3  611.66
  4673.6  611.67  5004.4  607.28    5005  606.48  5011.5  606.48  5012.1  607.28
    5202  610.01  5416.2  615.61  5446.8  615.96  5762.9  622.97  5824.1  625.29
  5864.9  625.66  5875.1  626.28  5915.9  626.56  5936.3  627.58  5997.5  627.56
#Mann= 3 ,-1 , 0
  3575.4     .05       0  5004.4    .035       0  5012.1     .05       0
Bank Sta=5004.4,5012.1
XS Rating Curve= 0 ,0
Exp/Cntr=0.3,0.1

Type RM Length L Ch R = 1 ,2769    ,439,439,439
BEGIN DESCRIPTION:
UNT 109 in HW 6.0
END DESCRIPTION:
XS GIS Cut Line= 4
      1987575.02     13582124.99      1988260.22     13581757.17
      1988878.28     13581055.78        1988775.     13580425.01
#Sta/Elev= 30
  3525.7   623.1  3785.5   618.2  4013.7  615.61  4042.9  614.88  4108.6  614.47
  4138.6  613.66  4190.7  614.24  4286.1  612.47  4379.1  611.57  4393.4  611.75
  4421.8   610.9  4513.8  609.36  4570.7  608.98  4577.4  608.26  4591.6  608.04
  4620.1  608.31  4761.5  607.07  4875.3  607.32  4934.9  606.24  4935.6  605.44
  4942.1  605.44  4942.7  606.24  5073.6  606.69    5102  606.38  5151.4  607.13
  5476.1  613.22  5674.7  617.86  5755.8  619.59  5787.9  619.82  5877.4  621.83
#Mann= 3 ,-1 , 0
  3525.7     .05       0  4934.9    .035       0  4942.7     .05       0
Bank Sta=4934.9,4942.7
XS Rating Curve= 0 ,0
Exp/Cntr=0.3,0.1

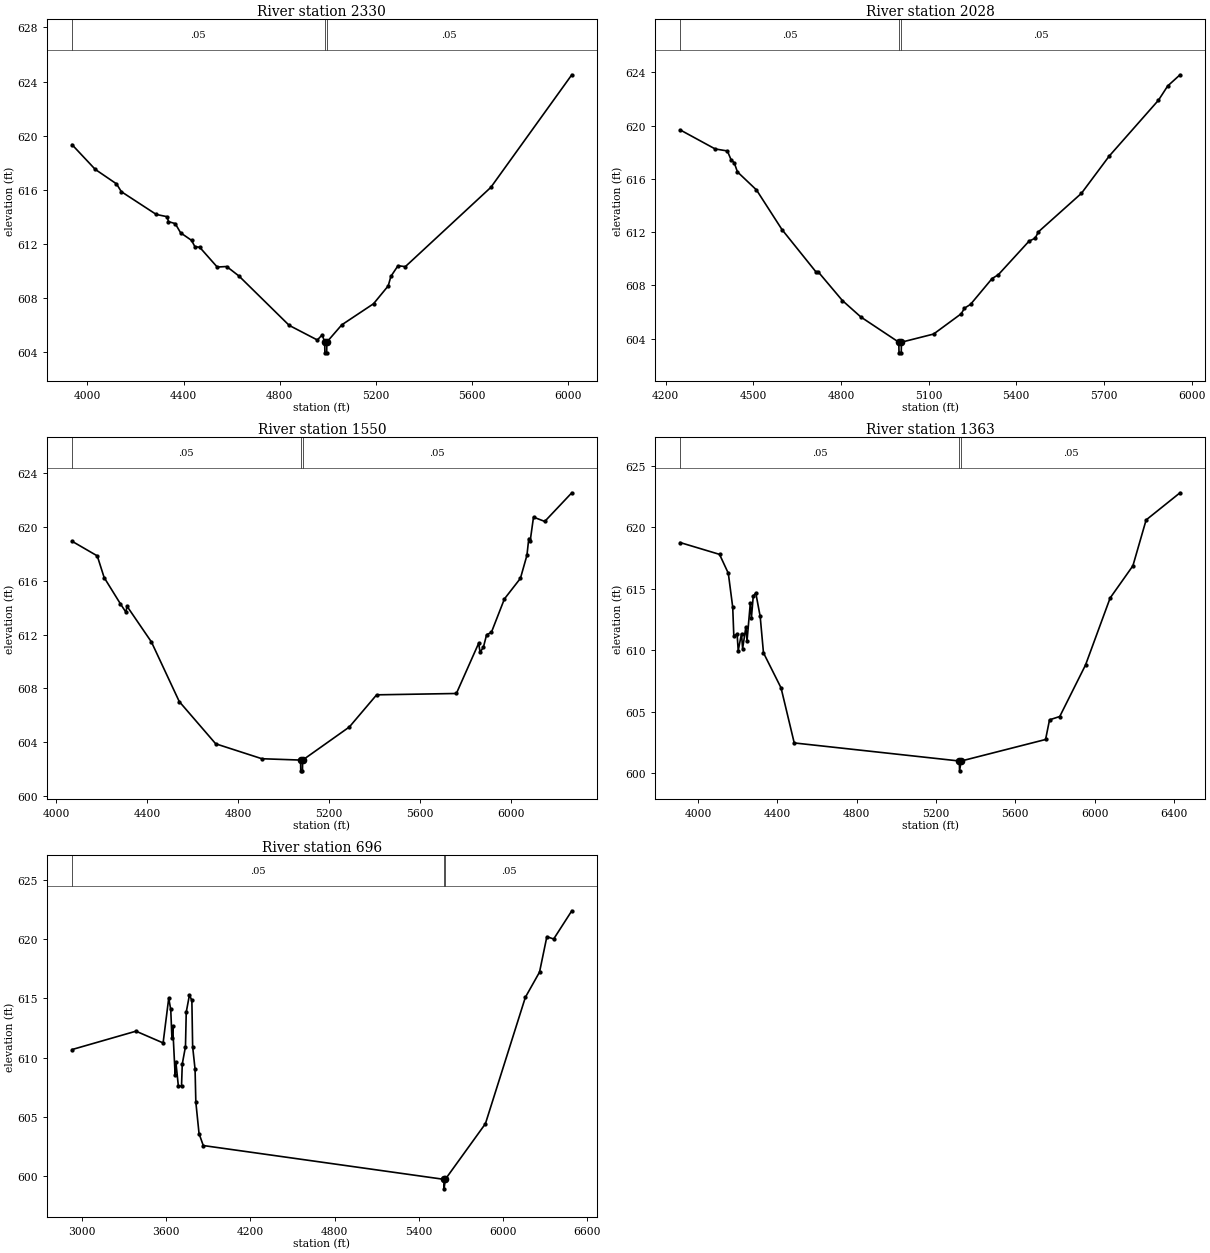
Type RM Length L Ch R = 1 ,2330    ,302,302,302
BEGIN DESCRIPTION:
UNT 109 in HW 5.0
END DESCRIPTION:
XS GIS Cut Line= 3
       1989328.8     13582326.62      1989111.79     13581250.23
      1988929.74     13580283.67
#Sta/Elev= 30
  3935.4  619.34  4032.2  617.51  4120.7  616.44  4141.1  615.86  4286.3  614.18
    4332  614.01  4337.1  613.65  4365.5   613.5  4387.9  612.82  4433.6  612.26
  4447.1   611.8  4467.5  611.75  4540.3  610.29  4579.7  610.33  4630.7  609.63
    4840  605.98  4957.2   604.9  4977.6  605.28  4987.8  604.75  4988.7  603.95
  4996.1  603.95    4997  604.75  5059.1  606.02  5191.4  607.58  5252.5   608.9
  5263.5   609.6  5293.2  610.39  5323.7  610.32  5679.8  616.18    6017   624.5
#Mann= 3 ,-1 , 0
  3935.4     .05       0  4987.8    .035       0    4997     .05       0
Bank Sta=4987.8,4997
XS Rating Curve= 0 ,0
Exp/Cntr=0.3,0.1

Type RM Length L Ch R = 1 ,2028    ,478,478,478
BEGIN DESCRIPTION:
UNT 109 in HW 4.0
END DESCRIPTION:
XS GIS Cut Line= 3
        1989675.       13581875.        1989375.       13581175.
      1989074.99     13580274.96
#Sta/Elev= 30
  4250.1  619.68  4369.8  618.25  4411.5   618.1  4424.2  617.44  4435.1  617.21
  4445.9  616.53  4511.2  615.17  4598.3   612.2  4716.1  608.98  4721.6  609.04
    4805  606.87  4868.4  605.63    4998  603.74  4998.9  602.94  5006.4  602.94
  5007.2  603.74  5117.1  604.35    5212  605.88  5222.5  606.29  5243.6  606.58
  5317.4  608.52  5338.4   608.8  5443.9  611.33  5464.9  611.55  5475.5  612.02
  5623.1  614.92  5717.9  617.71  5886.6  621.91  5918.2  622.98  5960.4  623.82
#Mann= 3 ,-1 , 0
  4250.1     .05       0    4998    .035       0  5007.2     .05       0
Bank Sta=4998,5007.2
XS Rating Curve= 0 ,0
Exp/Cntr=0.3,0.1

Type RM Length L Ch R = 1 ,1550    ,187,187,187
BEGIN DESCRIPTION:
Mapping XS 22bcf3b6
END DESCRIPTION:
XS GIS Cut Line= 5
      1989719.44     13581836.12      1989897.38     13581397.79
      1989767.17     13581059.25      1989762.83     13580204.22
      1989368.95     13579883.92
#Sta/Elev= 30
  4069.5  618.94  4180.7  617.85    4211  616.24  4282.4  614.29  4306.5  613.67
  4311.9   614.1    4419  611.45  4541.4  607.02  4701.7  603.88  4904.9  602.77
  5074.9  602.67  5075.8  601.87  5083.3  601.87  5084.1  602.67  5289.5  605.13
  5409.5  607.52  5760.3  607.62  5858.2  611.35  5864.6  610.69    5879  611.05
  5893.3  611.99  5914.2  612.16  5971.6  614.65    6042  616.18  6070.7   617.9
  6078.7  619.14  6085.1  618.98  6099.5  620.73    6149  620.41    6268  622.54
#Mann= 3 ,-1 , 0
  4069.5     .05       0  5074.9    .035       0  5084.1     .05       0
Bank Sta=5074.9,5084.1
XS Rating Curve= 0 ,0
Exp/Cntr=0.3,0.1

Type RM Length L Ch R = 1 ,1363    ,667,667,667
BEGIN DESCRIPTION:
Mapping XS 128b3f6b
END DESCRIPTION:
XS GIS Cut Line= 5
      1989767.15     13581892.62      1990049.29     13581345.71
      1989901.72     13581063.59      1989880.01     13580117.41
      1989341.81     13579770.18
#Sta/Elev= 30
  3909.8  618.77  4108.2  617.81  4152.5  616.27  4174.7  613.51  4180.3  611.14
  4196.8  611.35  4202.4  609.98    4219  611.36  4224.6  610.15  4241.1  611.91
  4246.8  610.76  4263.3  613.82  4268.9  612.64  4278.4  614.43  4291.1  614.66
  4313.2  612.76  4329.8   609.8  4418.4  606.95  4484.9  602.47  5317.7     601
  5318.5   600.2  5326.9     601  5752.4  602.75  5772.4  604.35  5823.9  604.62
  5953.9  608.81    6078  614.26  6192.8  616.88  6259.5  620.61  6430.5  622.82
#Mann= 3 ,-1 , 0
  3909.8     .05       0  5317.7    .035       0  5326.9     .05       0
Bank Sta=5317.7,5326.9
XS Rating Curve= 0 ,0
Exp/Cntr=0.3,0.1

Type RM Length L Ch R = 1 ,696     ,0,0,0
BEGIN DESCRIPTION:
UNT 109 in HW 3.0
END DESCRIPTION:
XS GIS Cut Line= 4
      1989785.41     13582492.61      1990495.73     13580981.96
      1990366.99     13580305.13      1989334.03     13579680.14
#Sta/Elev= 30
  2926.7  610.69  3383.3  612.24  3576.8  611.25  3616.9  615.02  3631.3  614.07
  3639.7  611.67  3645.2  612.65  3662.5  608.57    3668  609.62  3685.3  607.65
  3708.1  607.59  3713.6  609.48  3736.4  610.94  3741.9  613.85  3764.7  615.29
    3782  614.83  3787.5  610.94  3804.8  609.03  3810.3  606.26  3833.1  603.61
  3863.3   602.6  5580.3  599.75  5581.2  598.95  5589.7  599.75    5876  604.44
  6161.1   615.1    6262  617.22  6314.4  620.21  6362.9  620.01  6492.3  622.39
#Mann= 3 ,-1 , 0
  2926.7     .05       0  5580.3    .035       0  5589.7     .05       0
Bank Sta=5580.3,5589.7
XS Rating Curve= 0 ,0
Exp/Cntr=0.3,0.1
LCMann Table=0

Chan Stop Cuts=-1
Use User Specified Reach Order=0
Composite Channel Slope=5