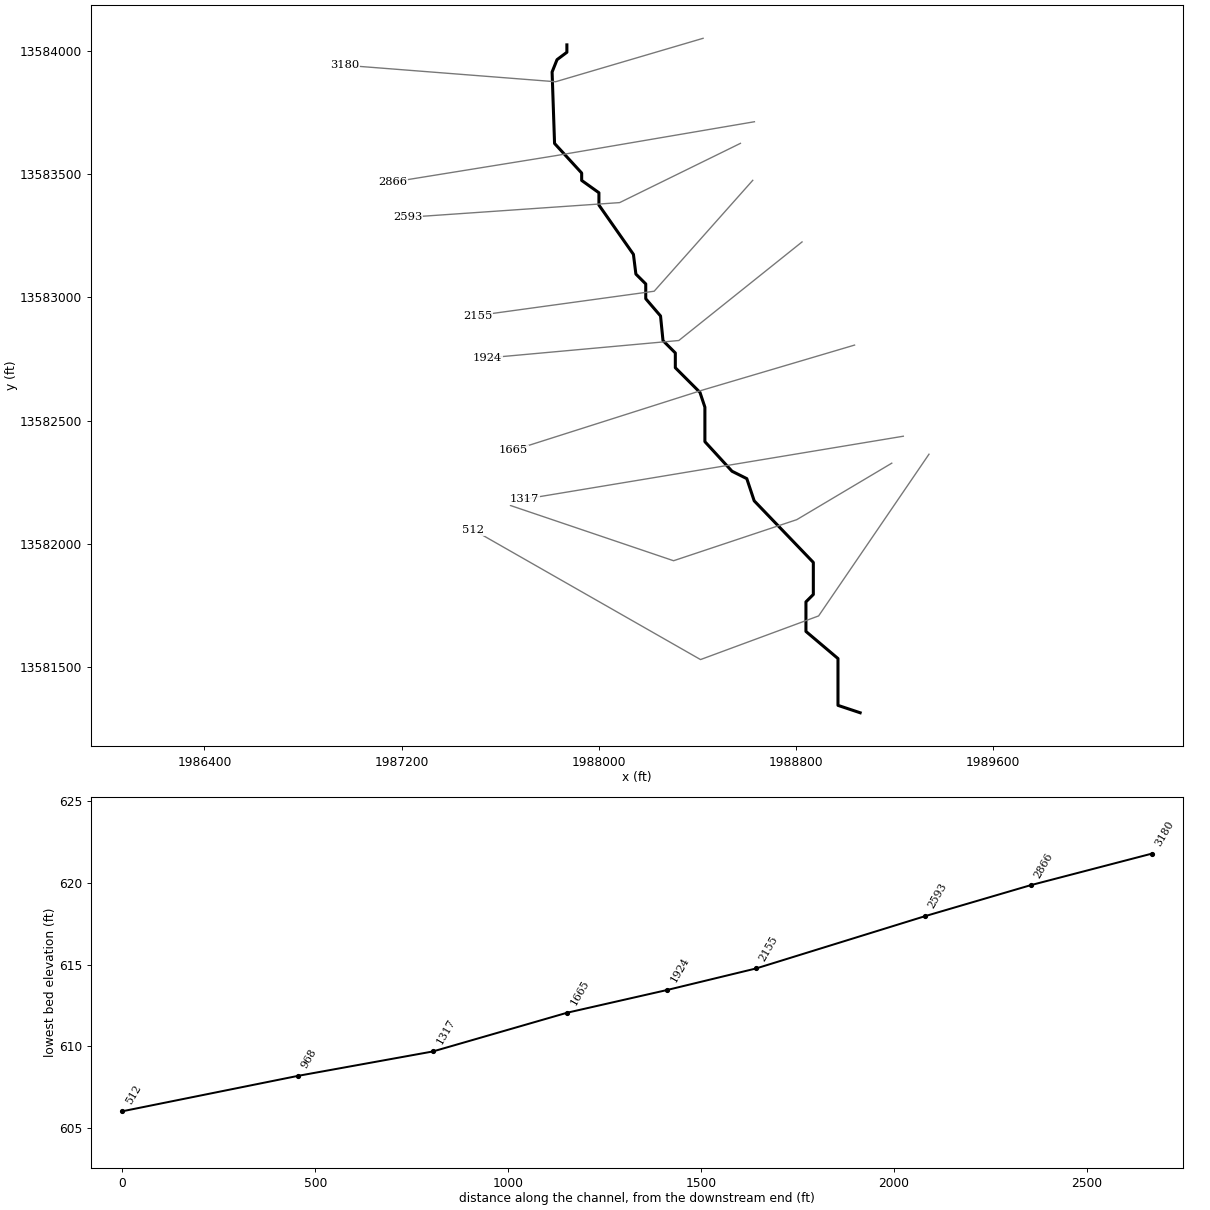
--- UNT 111 in HW.prj (project) ---

Proj Title=UNT 111 in HW Base Level Engineering
Current Plan=p01
Default Exp/Contr=0.3,0.1
English Units
Geom File=g01
Flow File=f01
Plan File=p01
BEGIN DESCRIPTION:
UNT 111 in HW
END DESCRIPTION:

--- UNT 111 in HW.p01 (plan) ---

Plan Title=Multiple Run
Short Identifier=Multiple
Geom File=g01
Flow File=f01
Subcritical Flow
K Sum by GR= 0
Std Step Tol= 0.01
Critical Tol= 0.01
Num of Std Step Trials= 20
Max Error Tol= 0.3
Flow Tol Ratio= 0.001
Split Flow NTrial= 30
Split Flow Tol= 0.02
Split Flow Ratio= 0.02
Log Output Level= 0
Friction Slope Method= 1
Unsteady Friction Slope Method= 2
Unsteady Bridges Friction Slope Method= 1
Parabolic Critical Depth
Global Vel Dist=  1 , 1 , 1
Global Log Level= 0
CheckData=True
Encroach Param= -1, 0, 0, 0
BEGIN DESCRIPTION:
Multiple Run
END DESCRIPTION:

--- UNT 111 in HW.f01 (steady flow) ---

Flow Title=Multiple
Number of Profiles=7
Profile Names=10-year,25-year,50-year,1pct_min,100-year,1pct_plu,500-year
River Rch & RM= UNT 111 in HW,Reach-1,3180
     500     701     868     533    1064    2123    1603
Boundary for River Rch & Prof#=UNT 111 in HW,Reach-1,1
Up Type=0
Dn Type=3
Dn Slope=0.005
Boundary for River Rch & Prof#=UNT 111 in HW,Reach-1,2
Up Type=0
Dn Type=3
Dn Slope=0.005
Boundary for River Rch & Prof#=UNT 111 in HW,Reach-1,3
Up Type=0
Dn Type=3
Dn Slope=0.005
Boundary for River Rch & Prof#=UNT 111 in HW,Reach-1,4
Up Type=0
Dn Type=3
Dn Slope=0.005
Boundary for River Rch & Prof#=UNT 111 in HW,Reach-1,5
Up Type=0
Dn Type=3
Dn Slope=0.005
Boundary for River Rch & Prof#=UNT 111 in HW,Reach-1,6
Up Type=0
Dn Type=3
Dn Slope=0.005
Boundary for River Rch & Prof#=UNT 111 in HW,Reach-1,7
Up Type=0
Dn Type=3
Dn Slope=0.005

--- UNT 111 in HW.g01 (geometry) ---

Geom Title=Existing Conditions

River Reach=UNT 111 in HW,Reach-1
Reach XY= 30
      1987870.80     13584024.54      1987870.80     13583994.54
      1987830.80     13583964.54      1987810.80     13583914.54
      1987820.80     13583624.54      1987930.80     13583504.54
      1987930.80     13583474.54      1988000.80     13583424.54
      1988000.80     13583374.54      1988140.80     13583174.54
      1988150.80     13583094.54      1988190.80     13583054.54
      1988190.80     13582994.54      1988250.80     13582924.54
      1988260.80     13582824.54      1988310.80     13582774.54
      1988310.80     13582714.54      1988410.80     13582614.54
      1988430.80     13582554.54      1988430.80     13582414.54
      1988540.80     13582294.54      1988600.80     13582264.54
      1988630.80     13582174.54      1988870.80     13581924.54
      1988870.80     13581794.54      1988840.80     13581764.54
      1988840.80     13581644.54      1988970.80     13581534.54
      1988970.80     13581344.54      1989060.80     13581314.54

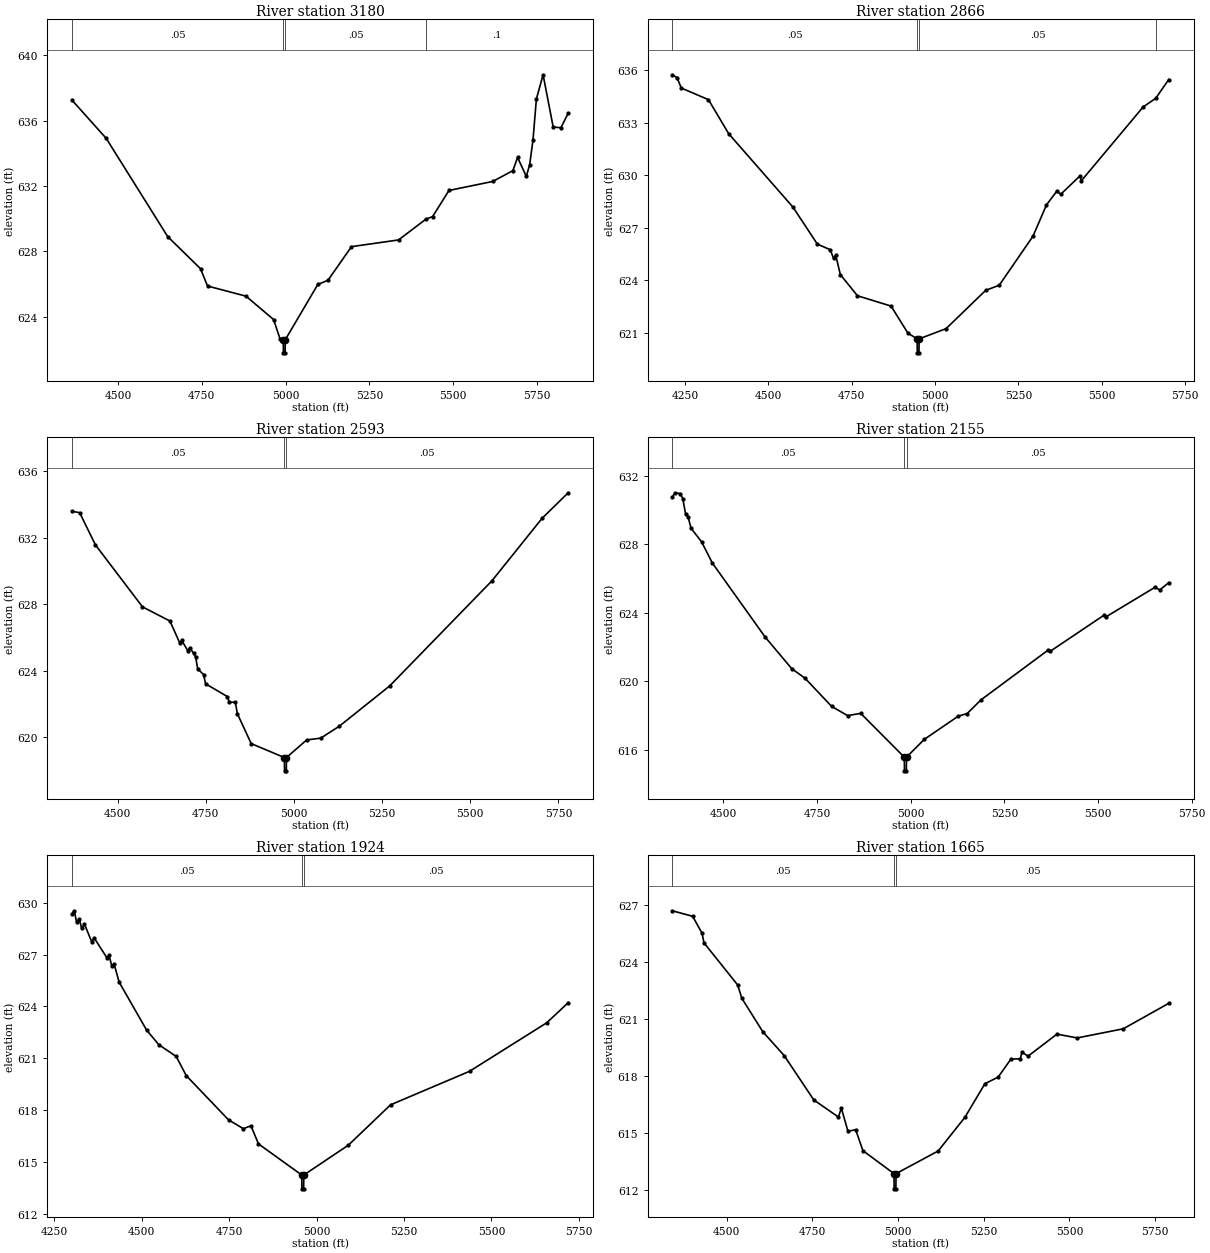
Type RM Length L Ch R = 1,3180,314,314,314
BEGIN DESCRIPTION:
UNT 111 in HW 7.0
END DESCRIPTION:
XS GIS Cut Line= 3
      1988423.45     13584051.22      1987825.00     13583875.00
      1986970.37     13583941.85
#Sta/Elev= 30
  4361.9  637.26  4464.5  634.91  4648.2  628.89  4746.0  626.93  4766.8  625.87
  4881.5  625.25  4963.9  623.82  4983.1  622.64  4992.8  622.58  4993.3  621.78
  4998.3  621.78  4998.8  622.58  5096.1  625.97  5126.2  626.22  5196.4  628.28
  5336.8  628.69  5418.3  629.96  5438.4  630.12  5487.3  631.72  5617.7  632.27
  5677.9  632.93  5692.0  633.74  5718.0  632.58  5728.0  633.29  5738.0  634.82
  5748.1  637.32  5768.1  638.80  5798.2  635.60  5821.3  635.56  5843.0  636.45
#Mann=4,-1,0
  4361.9    0.05       0  4992.8   0.035       0  4998.8    0.05       0
  5418.3     0.1       0
Bank Sta=4992.8,4998.8
Exp/Cntr=0.3,0.1

Type RM Length L Ch R = 1,2866,273,273,273
BEGIN DESCRIPTION:
UNT 111 in HW 6.0
END DESCRIPTION:
XS GIS Cut Line= 3
      1988631.76     13583712.68      1987825.00     13583575.00
      1987163.03     13583467.89
#Sta/Elev= 30
  4212.2  635.73  4226.1  635.57  4239.3  634.97  4320.5  634.31  4381.4  632.36
  4574.1  628.17  4647.2  626.06  4685.7  625.74  4695.9  625.24  4702.3  625.43
  4716.1  624.32  4767.5  623.11  4868.3  622.52  4919.0  620.97  4946.5  620.65
  4947.0  619.85  4952.0  619.85  4952.5  620.65  5033.2  621.23  5152.2  623.42
  5192.7  623.71  5294.0  626.51  5334.5  628.30  5364.9  629.07  5377.5  628.91
  5434.2  629.94  5439.2  629.68  5624.3  633.89  5662.4  634.39  5701.2  635.46
#Mann=4,-1,0
  4212.2    0.05       0  4946.5   0.035       0  4952.5    0.05       0
  5662.4     0.1       0
Bank Sta=4946.5,4952.5
Exp/Cntr=0.3,0.1

Type RM Length L Ch R = 1,2593,438,438,438
BEGIN DESCRIPTION:
UNT 111 in HW 5.0
END DESCRIPTION:
XS GIS Cut Line= 3
      1988574.99     13583625.00      1988084.91     13583384.56
      1987224.96     13583325.00
#Sta/Elev= 30
  4369.8  633.59  4392.1  633.50  4436.6  631.57  4570.3  627.83  4648.1  626.98
  4676.2  625.65  4681.8  625.81  4698.7  625.19  4704.3  625.38  4715.1  625.04
  4721.2  624.80  4726.8  624.10  4743.7  623.75  4749.2  623.20  4811.1  622.43
  4816.7  622.08  4833.6  622.10  4839.2  621.41  4878.6  619.60  4972.7  618.76
  4973.2  617.96  4978.2  617.96  4978.7  618.76  5035.9  619.82  5076.0  619.93
  5128.7  620.65  5271.3  623.07  5561.4  629.40  5703.9  633.17  5777.7  634.70
#Mann=3,-1,0
  4369.8    0.05       0  4972.7   0.035       0  4978.7    0.05       0
Bank Sta=4972.7,4978.7
Exp/Cntr=0.3,0.1

Type RM Length L Ch R = 1,2155,231,231,231
BEGIN DESCRIPTION:
UNT 111 in HW 4.0
END DESCRIPTION:
XS GIS Cut Line= 3
      1988625.00     13583475.00      1988225.00     13583025.00
      1987508.42     13582926.45
#Sta/Elev= 30
  4363.4  630.78  4370.5  631.02  4384.7  630.97  4391.4  630.67  4398.9  629.76
  4405.6  629.61  4413.2  628.95  4441.6  628.15  4470.0  626.92  4611.3  622.58
  4682.4  620.73  4717.5  620.18  4788.6  618.53  4831.3  617.99  4866.4  618.12
  4982.7  615.56  4983.2  614.76  4988.2  614.76  4988.7  615.56  5036.1  616.60
  5127.0  617.96  5150.6  618.11  5187.5  618.91  5366.7  621.82  5371.7  621.74
  5515.8  623.86  5520.8  623.76  5651.9  625.49  5664.9  625.34  5688.8  625.76
#Mann=3,-1,0
  4363.4    0.05       0  4982.7   0.035       0  4988.7    0.05       0
Bank Sta=4982.7,4988.7
Exp/Cntr=0.3,0.1

Type RM Length L Ch R = 1,1924,259,259,259
BEGIN DESCRIPTION:
UNT 111 in HW 3.0
END DESCRIPTION:
XS GIS Cut Line= 3
      1988824.98     13583224.98      1988325.00     13582825.00
      1987549.19     13582754.42
#Sta/Elev= 30
  4300.2  629.35  4307.4  629.53  4313.8  628.87  4321.8  629.06  4328.2  628.52
  4336.2  628.77  4357.0  627.74  4364.2  627.96  4400.2  626.82  4406.6  626.96
  4414.6  626.33  4421.0  626.46  4435.4  625.41  4513.9  622.63  4549.1  621.78
  4598.7  621.10  4627.5  619.99  4748.4  617.43  4790.8  616.92  4812.4  617.09
  4834.0  616.04  4957.6  614.24  4958.1  613.44  4963.1  613.44  4963.6  614.24
  5091.1  615.97  5211.5  618.30  5437.3  620.24  5658.2  623.05  5719.5  624.21
#Mann=3,-1,0
  4300.2    0.05       0  4957.6   0.035       0  4963.6    0.05       0
Bank Sta=4957.6,4963.6
Exp/Cntr=0.3,0.1

Type RM Length L Ch R = 1,1665,348,348,348
BEGIN DESCRIPTION:
UNT 111 in HW 2.0
END DESCRIPTION:
XS GIS Cut Line= 3
      1989038.08     13582806.45      1988425.00     13582625.00
      1987653.64     13582379.67
#Sta/Elev= 30
  4341.0  626.68  4400.3  626.39  4427.6  625.50  4433.5  624.99  4531.9  622.77
  4543.7  622.08  4604.9  620.32  4667.5  619.06  4753.7  616.73  4825.5  615.83
  4834.4  616.29  4853.5  615.08  4876.1  615.16  4897.2  614.06  4987.9  612.85
  4988.4  612.05  4993.4  612.05  4993.9  612.85  5116.8  614.04  5195.2  615.82
  5253.2  617.58  5291.9  617.93  5329.4  618.88  5356.3  618.89  5361.6  619.24
  5379.1  619.03  5463.5  620.19  5522.8  619.99  5657.0  620.47  5789.8  621.81
#Mann=3,-1,0
  4341.0    0.05       0  4987.9   0.035       0  4993.9    0.05       0
Bank Sta=4987.9,4993.9
Exp/Cntr=0.3,0.1

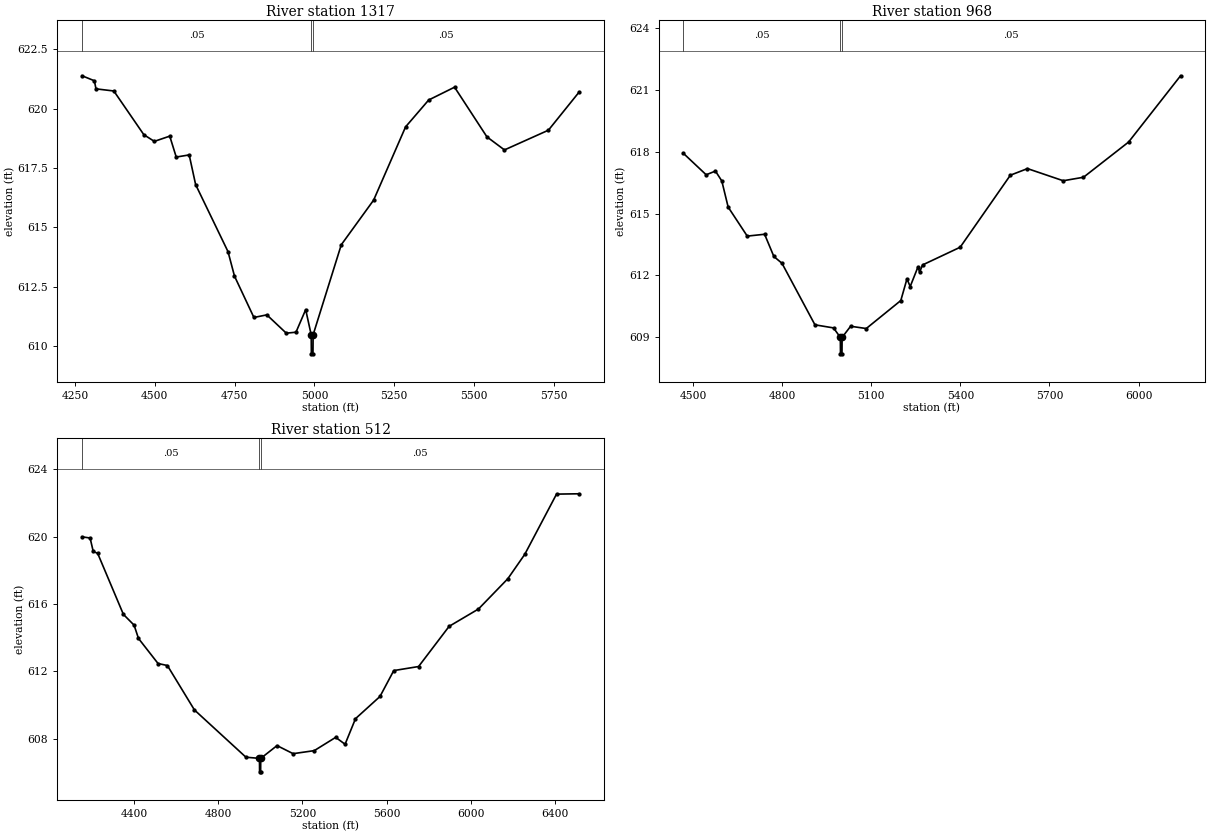
Type RM Length L Ch R = 1,1317,349,349,349
BEGIN DESCRIPTION:
Mapping XS 361380f8
END DESCRIPTION:
XS GIS Cut Line= 2
      1989235.92     13582436.64      1987699.77     13582181.48
#Sta/Elev= 30
  4272.2  621.38  4310.7  621.17  4315.7  620.83  4371.6  620.74  4465.7  618.90
  4498.5  618.62  4546.8  618.84  4567.1  617.96  4607.7  618.05  4627.9  616.80
  4729.3  613.98  4749.6  612.95  4810.4  611.21  4850.9  611.32  4911.8  610.55
  4942.2  610.59  4972.6  611.54  4989.9  610.48  4990.4  609.68  4995.4  609.68
  4995.9  610.48  5084.1  614.27  5185.5  616.15  5285.5  619.23  5357.8  620.36
  5438.9  620.90  5540.3  618.81  5595.2  618.26  5732.9  619.09  5829.4  620.70
#Mann=3,-1,0
  4272.2    0.05       0  4989.9   0.035       0  4995.9    0.05       0
Bank Sta=4989.9,4995.9
Exp/Cntr=0.3,0.1

Type RM Length L Ch R = 1,968,456,456,456
BEGIN DESCRIPTION:
Mapping XS 85ff6f33
END DESCRIPTION:
XS GIS Cut Line= 4
      1989189.04     13582327.25      1988803.66     13582098.10
      1988303.66     13581931.43      1987642.16     13582155.40
#Sta/Elev= 30
  4467.5  617.93  4544.1  616.89  4575.3  617.07  4596.7  616.59  4618.1  615.32
  4682.4  613.91  4740.8  614.00  4772.0  612.92  4799.3  612.59  4910.3  609.60
  4972.8  609.45  4995.8  608.99  4996.3  608.19  5001.3  608.19  5001.8  608.99
  5030.4  609.53  5083.1  609.42  5199.4  610.78  5220.1  611.83  5231.0  611.46
  5257.4  612.42  5262.6  612.16  5272.8  612.51  5399.3  613.37  5568.3  616.87
  5625.9  617.19  5746.3  616.60  5814.5  616.77  5966.3  618.48  6141.3  621.70
#Mann=3,-1,0
  4467.5    0.05       0  4995.8   0.035       0  5001.8    0.05       0
Bank Sta=4995.8,5001.8
Exp/Cntr=0.3,0.1

Type RM Length L Ch R = 1,512,0,0,0
BEGIN DESCRIPTION:
UNT 111 in HW 1.0
END DESCRIPTION:
XS GIS Cut Line= 4
      1989340.09     13582363.69      1988892.20     13581707.47
      1988413.03     13581530.39      1987491.20     13582056.41
#Sta/Elev= 30
  4150.7  619.99  4188.9  619.92  4203.8  619.12  4224.8  619.01  4347.4  615.38
  4398.3  614.74  4419.2  613.95  4512.3  612.46  4556.8  612.34  4685.5  609.70
  4930.7  606.89  4995.2  606.82  4995.7  606.02  5000.7  606.02  5001.2  606.82
  5078.8  607.58  5155.4  607.10  5256.0  607.28  5358.0  608.07  5402.7  607.66
  5452.3  609.18  5568.9  610.50  5634.5  612.04  5752.6  612.28  5898.1  614.67
  6037.8  615.70  6177.5  617.50  6258.2  618.95  6409.4  622.53  6517.4  622.55
#Mann=3,-1,0
  4150.7    0.05       0  4995.2   0.035       0  5001.2    0.05       0
Bank Sta=4995.2,5001.2
Exp/Cntr=0.3,0.1

Chan Stop Cuts=-1