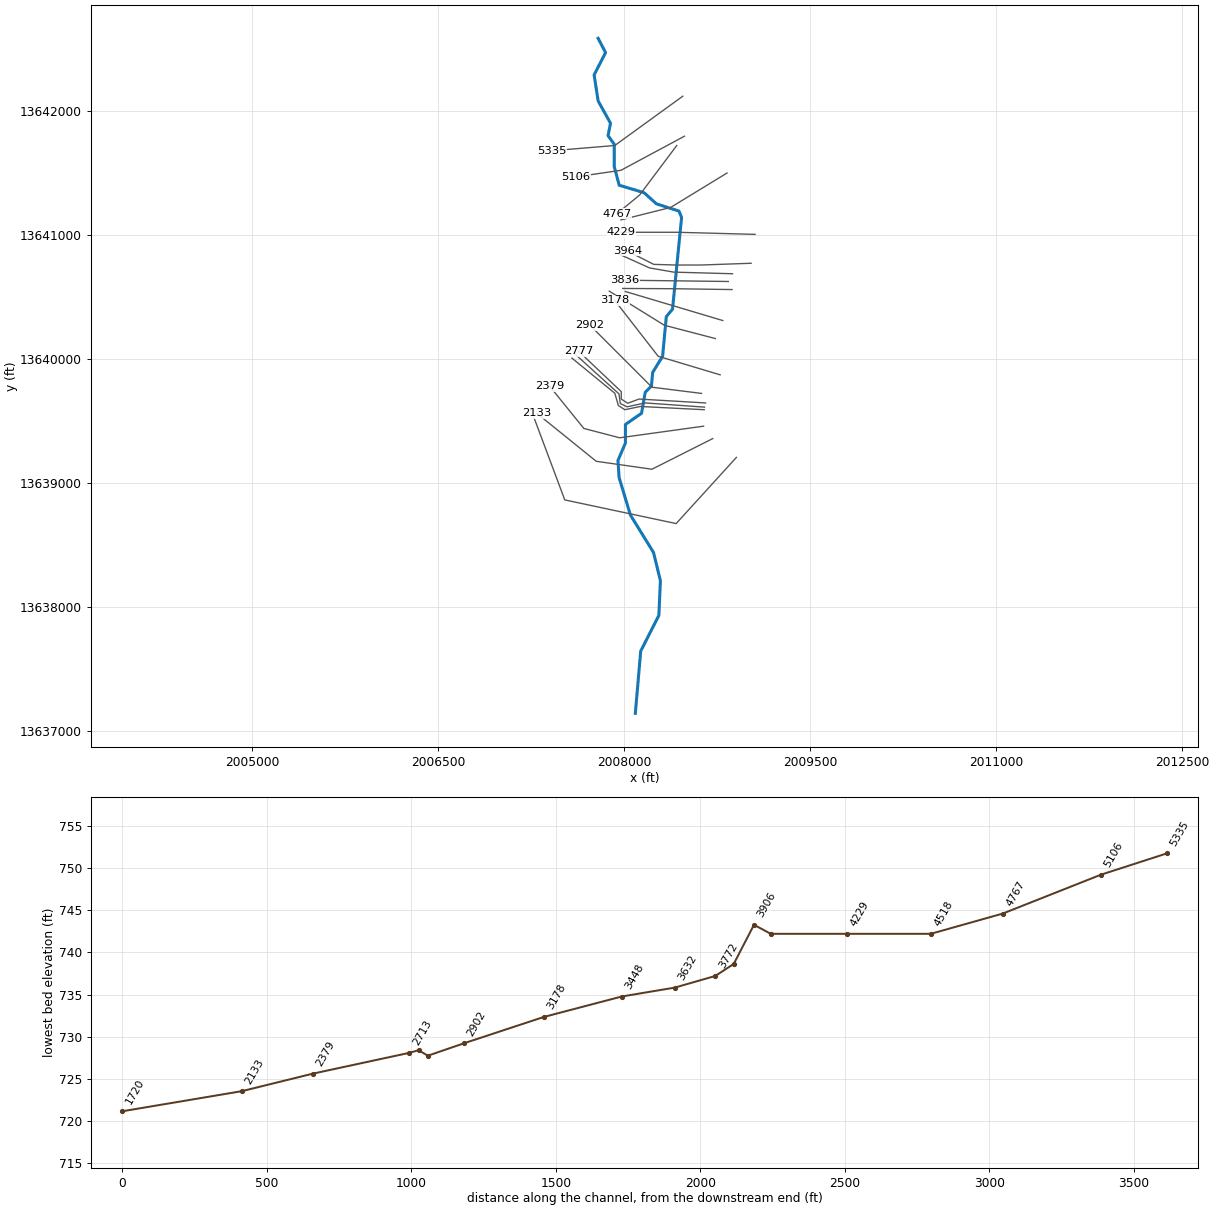
--- UNT 112 in HW.prj (project) ---

Proj Title=UNT 112 in HW Base Level Engineering
Current Plan=p01
Default Exp/Contr=0.3,0.1
English Units
Geom File=g01
Flow File=f01
Plan File=p01
BEGIN DESCRIPTION:
UNT 112 in HW
END DESCRIPTION:

--- UNT 112 in HW.p01 (plan) ---

Plan Title=Multiple Run
Short Identifier=Multiple
Geom File=g01
Flow File=f01
Subcritical Flow
K Sum by GR= 0
Std Step Tol= 0.01
Critical Tol= 0.01
Num of Std Step Trials= 20
Max Error Tol= 0.3
Flow Tol Ratio= 0.001
Split Flow NTrial= 30
Split Flow Tol= 0.02
Split Flow Ratio= 0.02
Log Output Level= 0
Friction Slope Method= 1
Unsteady Friction Slope Method= 2
Unsteady Bridges Friction Slope Method= 1
Parabolic Critical Depth
Global Vel Dist=  1 , 1 , 1
Global Log Level= 0
CheckData=True
Encroach Param= -1, 0, 0, 0
BEGIN DESCRIPTION:
Multiple Run
END DESCRIPTION:

--- UNT 112 in HW.f01 (steady flow) ---

Flow Title=Multiple
Number of Profiles=7
Profile Names=10-year,25-year,50-year,1pct_min,100-year,1pct_plu,500-year
River Rch & RM= UNT 112 in HW,Reach-1,5335
     414     570     698     424     847    1689    1248
Boundary for River Rch & Prof#=UNT 112 in HW,Reach-1,1
Up Type=0
Dn Type=3
Dn Slope=0.005
Boundary for River Rch & Prof#=UNT 112 in HW,Reach-1,2
Up Type=0
Dn Type=3
Dn Slope=0.005
Boundary for River Rch & Prof#=UNT 112 in HW,Reach-1,3
Up Type=0
Dn Type=3
Dn Slope=0.005
Boundary for River Rch & Prof#=UNT 112 in HW,Reach-1,4
Up Type=0
Dn Type=3
Dn Slope=0.005
Boundary for River Rch & Prof#=UNT 112 in HW,Reach-1,5
Up Type=0
Dn Type=3
Dn Slope=0.005
Boundary for River Rch & Prof#=UNT 112 in HW,Reach-1,6
Up Type=0
Dn Type=3
Dn Slope=0.005
Boundary for River Rch & Prof#=UNT 112 in HW,Reach-1,7
Up Type=0
Dn Type=3
Dn Slope=0.005

--- UNT 112 in HW.g01 (geometry) ---

Geom Title=Existing Conditions

River Reach=UNT 112 in HW,Reach-1
Reach XY= 30
      2007790.80     13642589.54      2007850.80     13642474.54
      2007758.35     13642294.75      2007790.80     13642084.54
      2007890.80     13641904.54      2007870.80     13641804.54
      2007920.80     13641734.54      2007920.80     13641554.54
      2007960.80     13641404.54      2008160.80     13641344.54
      2008260.80     13641254.54      2008443.25     13641195.79
      2008464.08     13641143.71      2008390.80     13640404.54
      2008340.80     13640344.54      2008310.80     13640024.54
      2008230.80     13639894.54      2008220.80     13639784.54
      2008170.80     13639734.54      2008140.80     13639564.54
      2008010.80     13639474.54      2008010.80     13639324.54
      2007950.80     13639184.54      2007959.74     13639046.92
      2008050.80     13638744.54      2008237.52     13638441.89
      2008293.08     13638214.46      2008280.80     13637934.54
      2008134.22     13637645.88      2008090.80     13637143.76

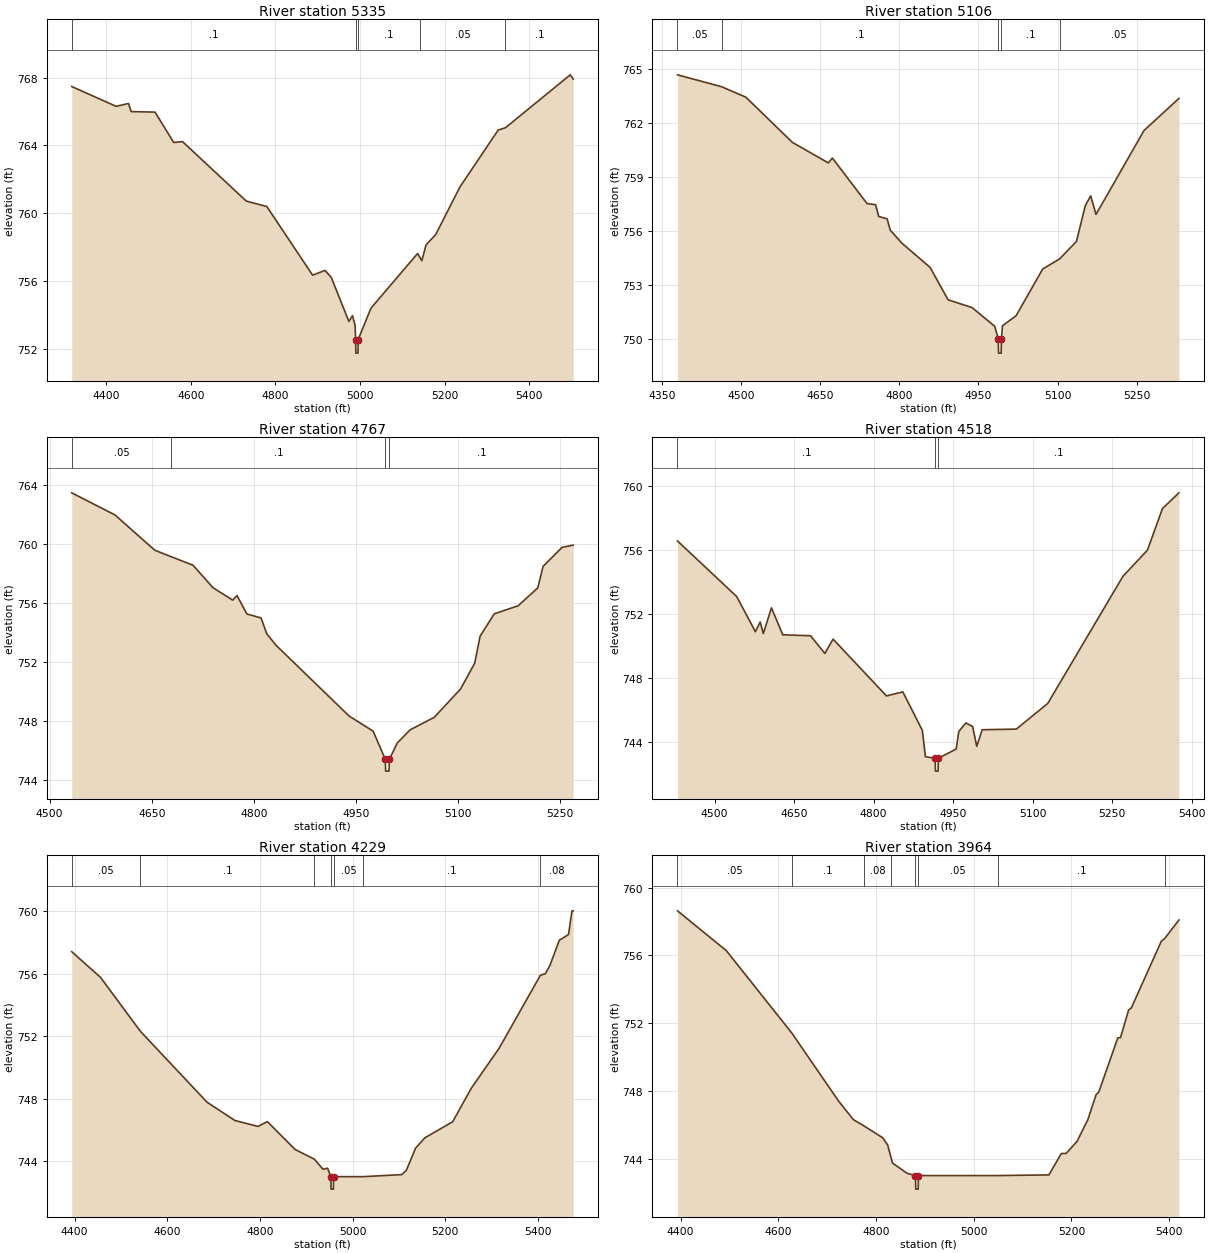
Type RM Length L Ch R = 1,5335,229,229,229
BEGIN DESCRIPTION:
UNT 112 in HW 13.0
END DESCRIPTION:
XS GIS Cut Line= 3
      2008473.69     13642122.74      2007925.00     13641725.00
      2007418.24     13641682.80
#Sta/Elev= 30
  4318.1  767.47  4423.2  766.30  4452.3  766.47  4458.8  765.99  4515.2  765.96
  4559.3  764.17  4580.2  764.22  4731.0  760.71  4779.6  760.39  4887.9  756.34
  4917.3  756.62  4932.0  756.21  4973.7  753.61  4982.3  753.95  4988.4  753.39
  4989.7  752.54  4990.2  751.74  4995.2  751.74  4995.7  752.54  5025.9  754.39
  5136.3  757.62  5141.5  757.40  5146.3  757.19  5156.3  758.13  5179.0  758.73
  5236.6  761.55  5326.9  764.90  5344.2  765.04  5497.5  768.16  5504.3  767.91
#Mann=5,-1,0
  4318.1     0.1       0  4989.7    0.07       0  4995.7     0.1       0
  5141.5    0.05       0  5344.2     0.1       0
Bank Sta=4989.7,4995.7
Exp/Cntr=0.3,0.1

Type RM Length L Ch R = 1,5106,339,339,339
BEGIN DESCRIPTION:
UNT 112 in HW 12.0
END DESCRIPTION:
XS GIS Cut Line= 3
      2008486.77     13641799.85      2007975.00     13641525.00
      2007609.56     13641471.77
#Sta/Elev= 30
  4379.7  764.65  4463.3  763.99  4509.2  763.41  4597.4  760.90  4665.5  759.76
  4673.2  760.03  4739.0  757.50  4755.2  757.44  4760.9  756.79  4777.1  756.65
  4782.8  756.03  4804.7  755.31  4858.4  753.96  4892.5  752.16  4937.9  751.73
  4980.8  750.69  4987.6  750.00  4988.1  749.20  4993.1  749.20  4993.6  750.00
  4995.6  750.72  5021.2  751.27  5071.8  753.87  5103.8  754.43  5135.7  755.40
  5152.6  757.40  5162.7  757.93  5172.8  756.90  5263.8  761.56  5329.9  763.34
#Mann=5,-1,0
  4379.7    0.05       0  4463.3     0.1       0  4987.6    0.07       0
  4993.6     0.1       0  5103.8    0.05       0
Bank Sta=4987.6,4993.6
Exp/Cntr=0.3,0.1

Type RM Length L Ch R = 1,4767,249,249,249
BEGIN DESCRIPTION:
UNT 112 in HW 11.0
END DESCRIPTION:
XS GIS Cut Line= 3
      2008424.99     13641724.99      2008125.00     13641325.00
      2007942.42     13641174.81
#Sta/Elev= 30
  4532.4  763.48  4595.9  761.98  4654.3  759.59  4678.8  759.14  4710.5  758.57
  4739.7  757.05  4768.8  756.20  4775.1  756.51  4789.7  755.26  4810.5  754.99
  4818.8  753.92  4832.4  753.14  4939.7  748.34  4975.1  747.31  4992.9  745.40
  4993.4  744.60  4998.4  744.60  4998.9  745.40  5010.5  746.51  5029.3  747.40
  5064.8  748.25  5103.4  750.17  5124.2  751.92  5132.1  753.75  5152.9  755.27
  5188.1  755.82  5216.8  757.03  5224.6  758.49  5252.5  759.78  5268.8  759.93
#Mann=4,-1,0
  4532.4    0.05       0  4678.8     0.1       0  4992.9    0.07       0
  4998.9     0.1       0
Bank Sta=4992.9,4998.9
Exp/Cntr=0.3,0.1

Type RM Length L Ch R = 1,4518,289,289,289
BEGIN DESCRIPTION:
UNT 112 in HW 10.0
END DESCRIPTION:
XS GIS Cut Line= 3
      2008830.45     13641502.94      2008375.00     13641225.00
      2007974.97     13641124.99
#Sta/Elev= 30
  4430.1  756.55  4541.9  753.08  4577.1  750.89  4586.1  751.50  4592.0  750.78
  4607.4  752.38  4628.7  750.70  4681.0  750.64  4708.1  749.54  4723.6  750.43
  4824.3  746.89  4855.2  747.14  4892.0  744.74  4897.8  743.10  4916.2  743.00
  4916.7  742.20  4921.7  742.20  4922.2  743.00  4955.9  743.58  4960.7  744.67
  4974.0  745.20  4986.8  744.99  4994.6  743.75  5004.9  744.78  5069.3  744.82
  5128.6  746.42  5270.3  754.34  5316.7  755.98  5345.0  758.57  5376.0  759.55
#Mann=3,-1,0
  4430.1     0.1       0  4916.2    0.07       0  4922.2     0.1       0
Bank Sta=4916.2,4922.2
Exp/Cntr=0.3,0.1

Type RM Length L Ch R = 1,4229,265,265,265
BEGIN DESCRIPTION:
UNT 112 in HW 9.0
END DESCRIPTION:
XS GIS Cut Line= 3
      2009057.01     13641008.16      2008425.00     13641025.00
      2007975.03     13641025.00
#Sta/Elev= 30
  4393.8  757.42  4455.8  755.78  4541.9  752.32  4685.9  747.77  4745.9  746.60
  4795.9  746.22  4816.0  746.53  4876.0  744.74  4917.4  744.12  4936.0  743.48
  4946.0  743.54  4953.0  743.00  4953.5  742.20  4958.5  742.20  4959.0  743.00
  5023.1  743.00  5106.0  743.13  5116.0  743.41  5136.0  744.83  5156.0  745.49
  5216.0  746.52  5256.0  748.66  5316.0  751.22  5405.3  755.91  5416.0  756.01
  5426.0  756.55  5446.0  758.15  5466.0  758.52  5473.5  760.04  5476.0  760.04
#Mann=7,-1,0
  4393.8    0.05       0  4541.9     0.1       0  4917.4    0.05       0
  4953.0   0.033       0  4959.0    0.05       0  5023.1     0.1       0
  5405.3    0.08       0
Bank Sta=4953,4959
Exp/Cntr=0.3,0.1

Type RM Length L Ch R = 1,3964,58,58,58
BEGIN DESCRIPTION:
UNT 112 in HW 8.0
END DESCRIPTION:
XS GIS Cut Line= 5
      2009024.98     13640775.00      2008619.53     13640760.77
      2008421.62     13640760.77      2008239.33     13640765.98
      2008025.04     13640874.98
#Sta/Elev= 30
  4393.5  758.63  4493.5  756.28  4627.9  751.40  4723.7  747.38  4753.7  746.30
  4774.3  745.95  4813.7  745.23  4823.7  744.81  4831.3  744.00  4833.7  743.74
  4863.7  743.13  4880.7  743.00  4881.2  742.20  4886.2  742.20  4886.7  743.00
  5049.4  743.00  5153.8  743.04  5179.1  744.30  5189.2  744.31  5211.4  745.02
  5233.6  746.31  5250.3  747.77  5255.9  747.93  5294.8  751.13  5300.4  751.15
  5317.0  752.78  5322.6  752.90  5383.8  756.83  5390.9  757.00  5419.9  758.09
#Mann=8,-1,0
  4393.5    0.05       0  4627.9     0.1       0  4774.3    0.08       0
  4831.3    0.05       0  4880.7   0.033       0  4886.7    0.05       0
  5049.4     0.1       0  5390.9    0.05       0
Bank Sta=4880.7,4886.7
Exp/Cntr=0.3,0.1

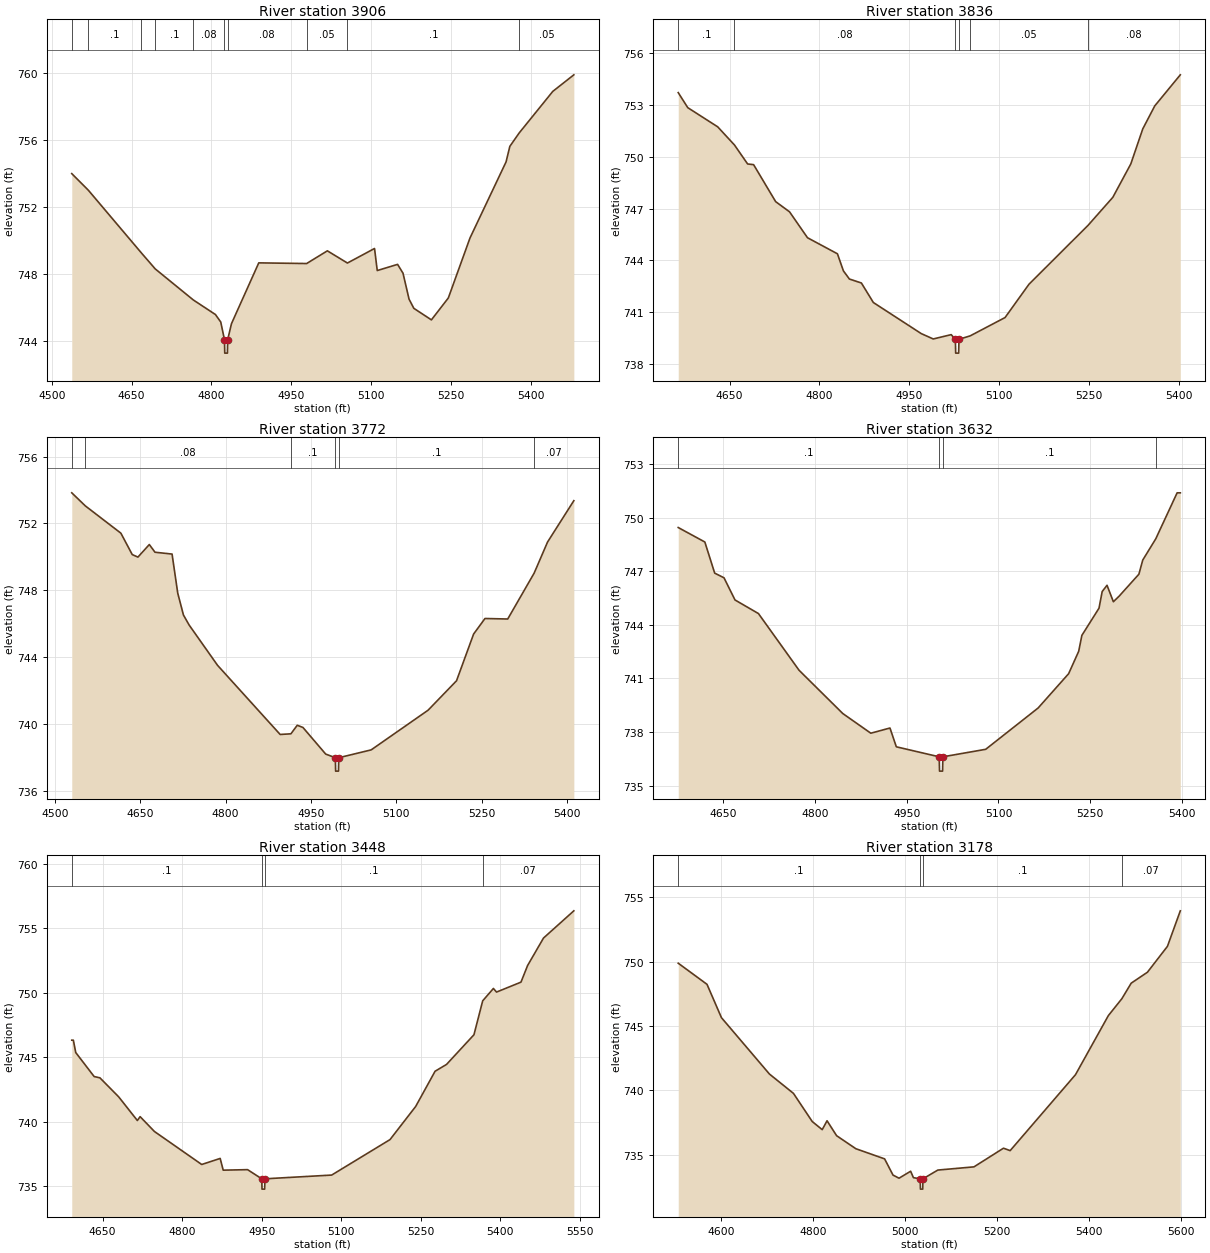
Type RM Length L Ch R = 1,3906,70,70,70
BEGIN DESCRIPTION:
Mapping XS d7cd883b
END DESCRIPTION:
XS GIS Cut Line= 4
      2008874.74     13640690.46      2008400.78     13640703.48
      2008205.47     13640737.33      2007959.00     13640848.89
#Sta/Elev= 30
  4537.6  754.01  4568.9  753.01  4667.4  749.30  4694.3  748.31  4765.9  746.45
  4807.4  745.58  4817.4  745.13  4824.4  744.07  4824.9  743.27  4829.9  743.27
  4830.4  744.07  4837.5  745.03  4888.8  748.67  4978.7  748.63  5017.6  749.39
  5055.3  748.66  5106.2  749.53  5111.3  748.21  5149.5  748.58  5159.7  748.05
  5171.0  746.50  5180.0  745.95  5213.0  745.26  5244.8  746.57  5285.5  750.16
  5353.2  754.71  5360.3  755.64  5377.8  756.44  5441.0  758.93  5480.5  759.92
#Mann=10,-1,0
  4537.6    0.05       0  4568.9     0.1       0  4667.4    0.08       0
  4694.3     0.1       0  4765.9    0.08       0  4824.4   0.033       0
  4830.4    0.08       0  4978.7    0.05       0  5055.3     0.1       0
  5377.8    0.05       0
Bank Sta=4824.4,4830.4
Exp/Cntr=0.3,0.1

Type RM Length L Ch R = 1,3836,64,64,64
BEGIN DESCRIPTION:
Mapping XS c4e38280
END DESCRIPTION:
XS GIS Cut Line= 2
      2008840.85     13640627.96      2008002.32     13640638.37
#Sta/Elev= 30
  4564.1  753.71  4580.0  752.84  4630.0  751.73  4658.0  750.68  4680.0  749.58
  4690.0  749.54  4726.8  747.40  4750.0  746.81  4780.0  745.31  4830.0  744.38
  4840.0  743.39  4850.0  742.92  4870.0  742.69  4890.0  741.56  4970.0  739.76
  4990.0  739.45  5020.0  739.70  5027.0  739.43  5027.5  738.63  5032.5  738.63
  5033.0  739.43  5051.8  739.63  5110.0  740.69  5150.0  742.62  5248.7  746.03
  5290.0  747.65  5320.0  749.58  5340.0  751.61  5360.0  752.94  5402.7  754.74
#Mann=6,-1,0
  4564.1     0.1       0  4658.0    0.08       0  5027.0    0.07       0
  5033.0    0.08       0  5051.8    0.05       0  5248.7    0.08       0
Bank Sta=5027,5033
Exp/Cntr=0.3,0.1

Type RM Length L Ch R = 1,3772,140,140,140
BEGIN DESCRIPTION:
UNT 112 in HW 7.0
END DESCRIPTION:
XS GIS Cut Line= 3
      2008871.25     13640562.85      2008383.42     13640569.80
      2007988.80     13640571.53
#Sta/Elev= 30
  4529.5  753.83  4553.3  753.05  4615.8  751.42  4635.8  750.14  4645.8  749.99
  4665.8  750.74  4675.8  750.28  4705.8  750.17  4715.8  747.83  4725.8  746.53
  4735.8  745.93  4785.8  743.52  4895.8  739.39  4914.7  739.43  4925.8  739.94
  4935.8  739.81  4975.8  738.22  4992.8  738.00  4993.3  737.20  4998.3  737.20
  4998.8  738.00  5055.8  738.47  5155.8  740.84  5205.8  742.60  5235.8  745.39
  5255.8  746.32  5295.8  746.29  5342.2  749.03  5365.8  750.89  5412.0  753.36
#Mann=6,-1,0
  4529.5    0.05       0  4553.3    0.08       0  4914.7     0.1       0
  4992.8    0.07       0  4998.8     0.1       0  5342.2    0.07       0
Bank Sta=4992.8,4998.8
Exp/Cntr=0.3,0.1

Type RM Length L Ch R = 1,3632,184,184,184
BEGIN DESCRIPTION:
Mapping XS 7160a73a
END DESCRIPTION:
XS GIS Cut Line= 2
      2008796.66     13640312.84      2008010.14     13640547.23
#Sta/Elev= 30
  4576.5  749.44  4620.0  748.63  4636.1  746.89  4651.3  746.63  4669.3  745.39
  4707.6  744.63  4774.0  741.46  4845.5  739.04  4891.3  737.94  4922.6  738.23
  4933.0  737.18  5003.1  736.62  5003.6  735.82  5008.6  735.82  5009.1  736.62
  5079.1  737.04  5164.8  739.35  5214.7  741.27  5231.1  742.52  5236.3  743.41
  5264.3  744.93  5269.5  745.86  5277.4  746.21  5287.8  745.29  5297.4  745.61
  5329.5  746.83  5335.8  747.62  5357.1  748.81  5392.0  751.38  5397.2  751.38
#Mann=4,-1,0
  4576.5     0.1       0  5003.1    0.07       0  5009.1     0.1       0
  5357.1    0.07       0
Bank Sta=5003.1,5009.1
Exp/Cntr=0.3,0.1

Type RM Length L Ch R = 1,3448,270,270,270
BEGIN DESCRIPTION:
UNT 112 in HW 6.0
END DESCRIPTION:
XS GIS Cut Line= 3
      2008735.86     13640167.74      2008325.00     13640275.00
      2007880.80     13640549.70
#Sta/Elev= 30
  4591.7  746.31  4594.7  746.31  4599.2  745.35  4633.9  743.49  4644.8  743.39
  4680.1  741.92  4715.4  740.08  4720.6  740.38  4747.6  739.23  4836.8  736.67
  4871.6  737.14  4877.3  736.23  4923.3  736.27  4950.0  735.56  4950.5  734.76
  4955.5  734.76  4956.0  735.56  5081.9  735.85  5191.9  738.60  5240.3  741.17
  5276.9  743.90  5298.5  744.43  5350.2  746.73  5366.7  749.36  5386.9  750.32
  5392.8  750.04  5438.9  750.81  5451.4  752.10  5481.4  754.23  5538.6  756.34
#Mann=4,-1,0
  4591.7     0.1       0  4950.0    0.07       0  4956.0     0.1       0
  5366.7    0.07       0
Bank Sta=4950,4956
Exp/Cntr=0.3,0.1

Type RM Length L Ch R = 1,3178,276,276,276
BEGIN DESCRIPTION:
UNT 112 in HW 5.0
END DESCRIPTION:
XS GIS Cut Line= 3
      2008775.01     13639875.00      2008275.00     13640025.00
      2007925.01     13640474.99
#Sta/Elev= 30
  4507.1  749.88  4569.7  748.24  4601.1  745.65  4705.5  741.27  4757.7  739.77
  4798.6  737.58  4820.3  736.95  4830.8  737.64  4851.6  736.48  4893.4  735.47
  4956.0  734.68  4974.3  733.42  4987.4  733.18  5012.6  733.72  5018.7  733.22
  5033.4  733.13  5033.9  732.33  5038.9  732.33  5039.4  733.13  5071.7  733.81
  5150.4  734.06  5214.6  735.51  5229.1  735.32  5371.2  741.22  5442.7  745.81
  5472.0  747.12  5492.4  748.33  5527.7  749.18  5571.2  751.19  5599.2  753.95
#Mann=4,-1,0
  4507.1     0.1       0  5033.4    0.07       0  5039.4     0.1       0
  5472.0    0.07       0
Bank Sta=5033.4,5039.4
Exp/Cntr=0.3,0.1

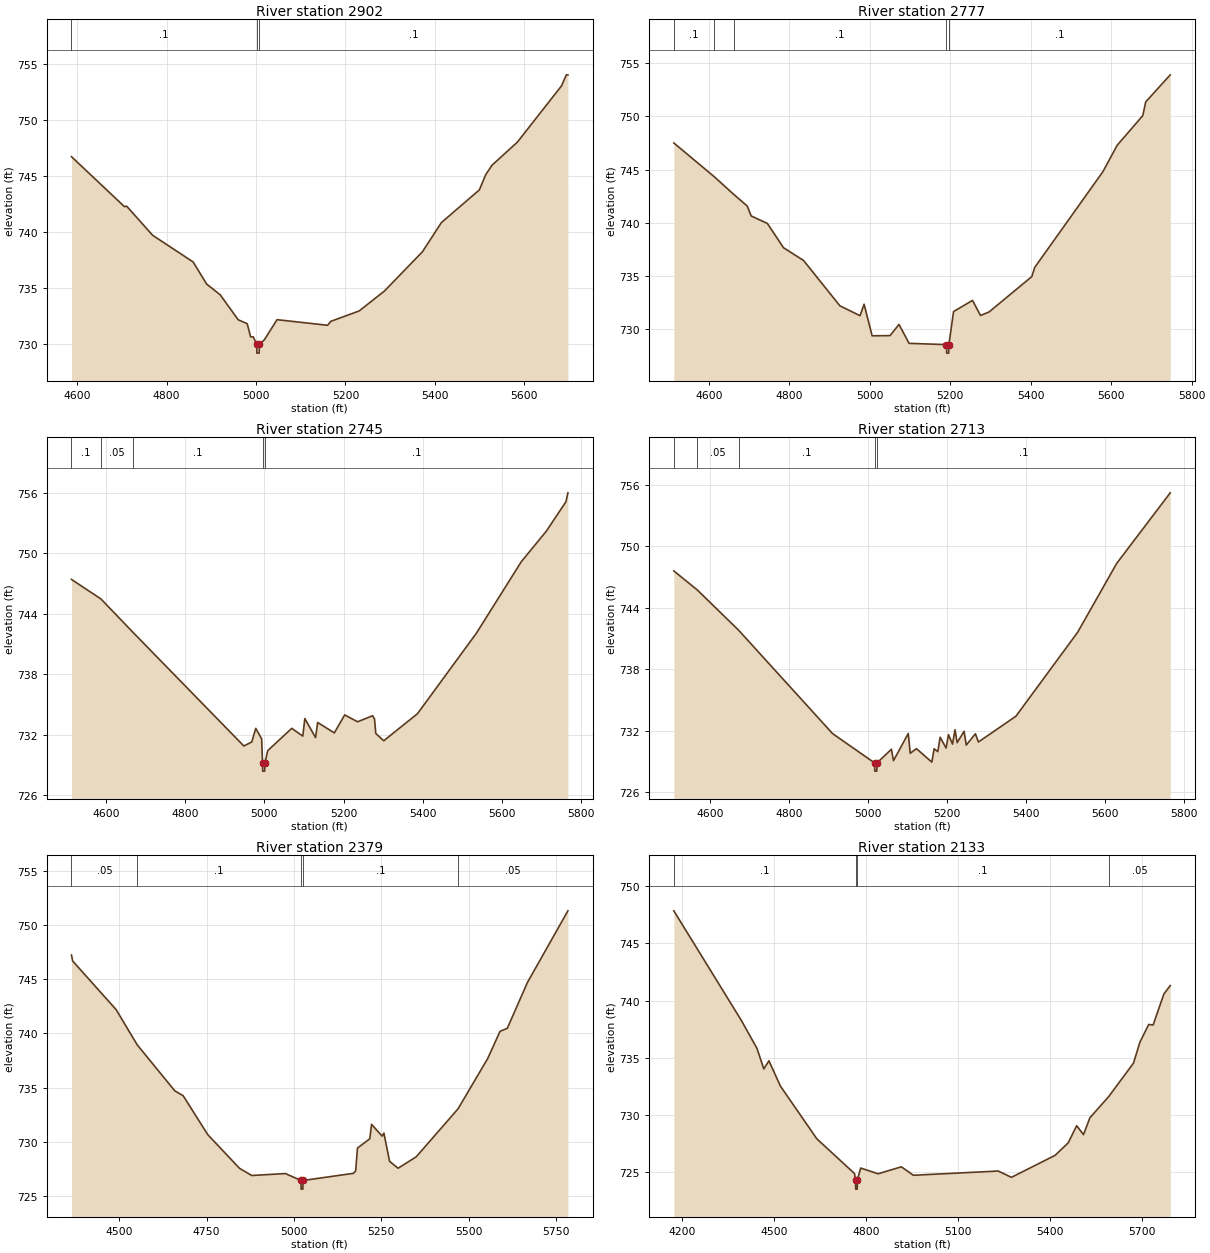
Type RM Length L Ch R = 1,2902,125,125,125
BEGIN DESCRIPTION:
UNT 112 in HW 4.0
END DESCRIPTION:
XS GIS Cut Line= 3
      2008624.97     13639725.00      2008225.00     13639775.00
      2007724.99     13640275.01
#Sta/Elev= 30
  4587.2  746.71  4705.6  742.26  4710.6  742.30  4768.6  739.71  4859.3  737.33
  4889.5  735.36  4919.7  734.41  4960.1  732.18  4980.2  731.83  4987.8  730.66
  4993.8  730.66  5001.4  730.01  5001.9  729.21  5006.9  729.21  5007.4  730.01
  5018.6  730.40  5046.9  732.19  5160.0  731.69  5167.1  732.04  5230.7  732.97
  5287.3  734.75  5372.1  738.24  5414.5  740.84  5499.4  743.75  5513.5  745.10
  5527.7  745.95  5584.3  748.00  5683.2  753.02  5693.9  754.00  5697.4  754.00
#Mann=3,-1,0
  4587.2     0.1       0  5001.4    0.07       0  5007.4     0.1       0
Bank Sta=5001.4,5007.4
Exp/Cntr=0.3,0.1

Type RM Length L Ch R = 1,2777,32,32,32
BEGIN DESCRIPTION:
Mapping XS 177cf7a6
END DESCRIPTION:
XS GIS Cut Line= 6
      2008657.07     13639648.21      2008120.62     13639679.46
      2008029.47     13639645.61      2007977.39     13639679.46
      2007977.39     13639739.36      2007631.02     13640067.49
#Sta/Elev= 30
  4512.9  747.51  4613.8  744.32  4661.6  742.68  4695.3  741.58  4705.3  740.64
  4745.4  739.94  4785.4  737.66  4835.5  736.45  4925.7  732.19  4975.8  731.26
  4985.8  732.34  5005.8  729.37  5050.3  729.39  5072.6  730.44  5097.6  728.66
  5190.6  728.54  5191.1  727.74  5196.1  727.74  5196.6  728.54  5208.2  731.65
  5255.3  732.70  5275.2  731.28  5296.7  731.62  5402.7  734.94  5409.9  735.80
  5579.4  744.81  5615.0  747.30  5678.5  750.08  5685.8  751.37  5746.8  753.92
#Mann=5,-1,0
  4512.9     0.1       0  4613.8    0.05       0  4661.6     0.1       0
  5190.6    0.07       0  5196.6     0.1       0
Bank Sta=5190.6,5196.6
Exp/Cntr=0.3,0.1

Type RM Length L Ch R = 1,2745,32,32,32
BEGIN DESCRIPTION:
Mapping XS 88d57331
END DESCRIPTION:
XS GIS Cut Line= 6
      2008649.30     13639614.35      2008170.10     13639648.21
      2008024.27     13639616.96      2007969.58     13639643.00
      2007959.16     13639721.13      2007599.91     13640046.53
#Sta/Elev= 30
  4512.8  747.39  4587.3  745.45  4668.5  742.13  4948.2  730.88  4968.2  731.28
  4978.3  732.63  4993.2  731.59  4995.4  729.19  4995.9  728.39  5000.9  728.39
  5001.4  729.19  5008.5  730.42  5069.3  732.63  5097.1  731.86  5102.3  733.60
  5129.4  731.71  5134.6  733.21  5176.8  732.18  5203.0  733.96  5235.5  733.28
  5273.3  733.88  5278.3  733.56  5281.5  732.12  5301.6  731.40  5386.8  734.08
  5535.5  742.05  5649.0  749.14  5712.5  752.18  5761.9  755.09  5766.8  755.97
#Mann=5,-1,0
  4512.8     0.1       0  4587.3    0.05       0  4668.5     0.1       0
  4995.4    0.07       0  5001.4     0.1       0
Bank Sta=4995.4,5001.4
Exp/Cntr=0.3,0.1

Type RM Length L Ch R = 1,2713,334,334,334
BEGIN DESCRIPTION:
Mapping XS 9e69e040
END DESCRIPTION:
XS GIS Cut Line= 6
      2008646.71     13639593.52      2008131.04     13639619.56
      2008006.04     13639593.52      2007953.95     13639627.38
      2007925.31     13639726.34      2007579.59     13640009.67
#Sta/Elev= 30
  4507.3  747.59  4566.6  745.74  4671.3  741.82  4909.5  731.74  5016.1  728.88
  5016.6  728.08  5021.6  728.08  5022.1  728.88  5058.7  730.21  5063.9  729.10
  5101.4  731.75  5106.4  729.82  5122.2  730.27  5161.0  728.96  5167.0  730.26
  5176.2  729.98  5182.2  731.38  5197.3  730.33  5203.3  731.64  5213.6  730.71
  5219.8  732.11  5225.3  730.86  5242.9  731.96  5248.4  730.62  5271.5  731.72
  5279.2  730.92  5374.2  733.43  5530.6  741.61  5629.7  748.33  5765.3  755.20
#Mann=5,-1,0
  4507.3     0.1       0  4566.6    0.05       0  4671.3     0.1       0
  5016.1    0.07       0  5022.1     0.1       0
Bank Sta=5016.1,5022.1
Exp/Cntr=0.3,0.1

Type RM Length L Ch R = 1,2379,246,246,246
BEGIN DESCRIPTION:
Mapping XS a79e27aa
END DESCRIPTION:
XS GIS Cut Line= 4
      2008641.48     13639460.71      2007964.37     13639366.96
      2007675.31     13639442.48      2007399.63     13639783.18
#Sta/Elev= 30
  4363.3  747.25  4366.7  746.70  4491.0  742.21  4551.2  738.96  4658.9  734.70
  4682.8  734.25  4753.5  730.64  4844.3  727.53  4879.3  726.87  4975.6  727.05
  5019.9  726.41  5020.4  725.61  5025.4  725.61  5025.9  726.41  5170.2  727.07
  5176.5  727.29  5181.7  729.41  5216.9  730.26  5222.1  731.60  5252.2  730.51
  5257.4  730.79  5273.6  728.18  5297.9  727.54  5349.9  728.60  5469.4  733.03
  5554.5  737.69  5589.7  740.20  5610.5  740.48  5668.0  744.71  5783.9  751.34
#Mann=5,-1,0
  4363.3    0.05       0  4551.2     0.1       0  5019.9    0.07       0
  5025.9     0.1       0  5469.4    0.05       0
Bank Sta=5019.9,5025.9
Exp/Cntr=0.3,0.1

Type RM Length L Ch R = 1,2133,413,413,413
BEGIN DESCRIPTION:
UNT 112 in HW 2.0
END DESCRIPTION:
XS GIS Cut Line= 4
      2008715.25     13639360.68      2008224.79     13639113.27
      2007775.35     13639177.43      2007295.94     13639564.68
#Sta/Elev= 30
  4173.9  747.84  4395.0  738.23  4445.2  735.82  4467.5  734.03  4484.2  734.74
  4521.4  732.54  4640.3  727.93  4763.4  724.89  4766.7  724.33  4767.2  723.53
  4772.2  723.53  4772.7  724.33  4783.6  725.37  4840.4  724.87  4916.2  725.48
  4955.4  724.74  5232.3  725.11  5275.4  724.56  5417.8  726.48  5460.5  727.57
  5488.2  729.07  5510.5  728.29  5531.3  729.76  5593.2  731.63  5673.6  734.54
  5694.4  736.36  5723.2  737.91  5737.6  737.87  5772.8  740.58  5793.5  741.31
#Mann=4,-1,0
  4173.9     0.1       0  4766.7    0.07       0  4772.7     0.1       0
  5593.2    0.05       0
Bank Sta=4766.7,4772.7
Exp/Cntr=0.3,0.1

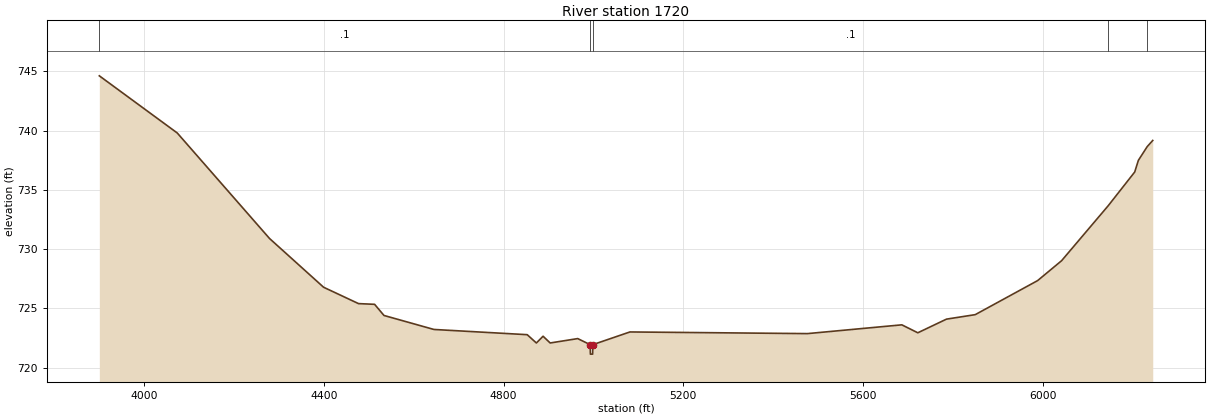
Type RM Length L Ch R = 1,1720,0,0,0
BEGIN DESCRIPTION:
UNT 112 in HW 1.0
END DESCRIPTION:
XS GIS Cut Line= 4
      2008906.23     13639208.78      2008420.10     13638674.90
      2007521.66     13638865.88      2007275.01     13639524.98
#Sta/Elev= 30
  3900.4  744.62  4073.8  739.80  4279.2  730.90  4399.5  726.79  4477.2  725.41
  4513.0  725.35  4533.9  724.41  4645.0  723.23  4852.6  722.79  4873.0  722.09
  4887.9  722.66  4903.7  722.09  4965.0  722.46  4992.7  721.95  4993.2  721.15
  4998.2  721.15  4998.7  721.95  5081.2  723.02  5476.2  722.88  5686.3  723.62
  5721.9  722.95  5785.6  724.10  5849.7  724.48  5988.5  727.35  6041.9  729.03
  6145.5  733.66  6204.6  736.51  6212.7  737.49  6232.4  738.65  6244.7  739.17
#Mann=5,-1,0
  3900.4     0.1       0  4992.7    0.07       0  4998.7     0.1       0
  6145.5    0.05       0  6232.4     0.1       0
Bank Sta=4992.7,4998.7
Exp/Cntr=0.3,0.1

Chan Stop Cuts=-1