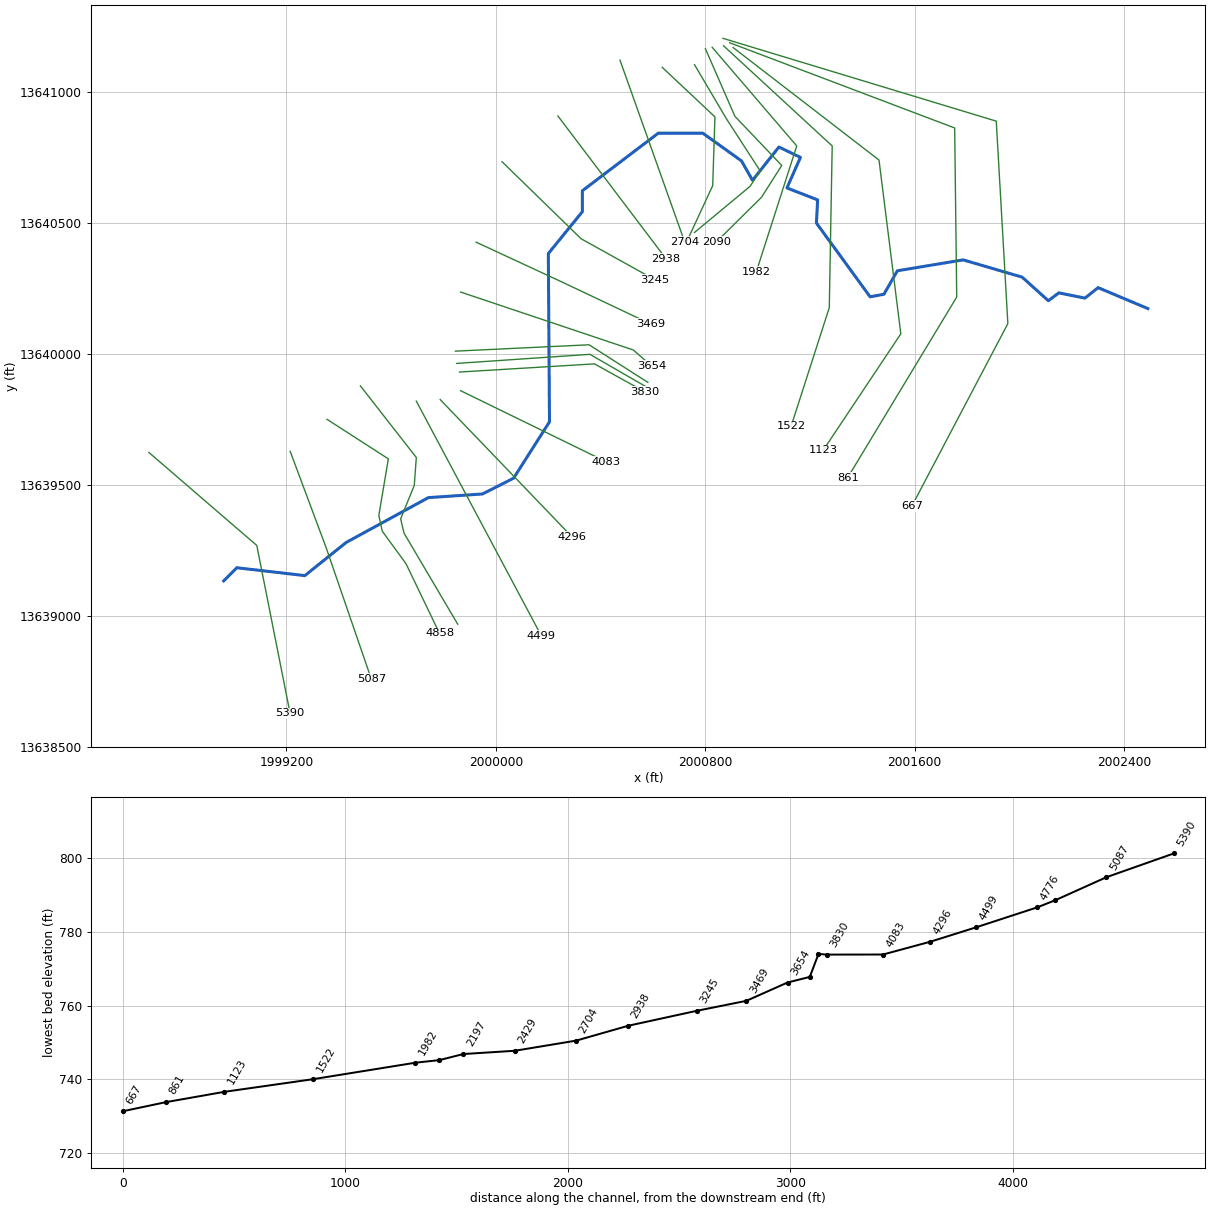
--- UNT 113 in HW.prj (project) ---

Proj Title=UNT 113 in HW Base Level Engineering
Current Plan=p01
Default Exp/Contr=0.3,0.1
English Units
Geom File=g01
Flow File=f01
Plan File=p01
BEGIN DESCRIPTION:
UNT 113 in HW
END DESCRIPTION:

--- UNT 113 in HW.p01 (plan) ---

Plan Title=Multiple Run
Short Identifier=Multiple
Geom File=g01
Flow File=f01
Subcritical Flow
K Sum by GR= 0
Std Step Tol= 0.01
Critical Tol= 0.01
Num of Std Step Trials= 20
Max Error Tol= 0.3
Flow Tol Ratio= 0.001
Split Flow NTrial= 30
Split Flow Tol= 0.02
Split Flow Ratio= 0.02
Log Output Level= 0
Friction Slope Method= 1
Unsteady Friction Slope Method= 2
Unsteady Bridges Friction Slope Method= 1
Parabolic Critical Depth
Global Vel Dist=  1 , 1 , 1
Global Log Level= 0
CheckData=True
Encroach Param= -1, 0, 0, 0
BEGIN DESCRIPTION:
Multiple Run
END DESCRIPTION:

--- UNT 113 in HW.f01 (steady flow) ---

Flow Title=Multiple
Number of Profiles=7
Profile Names=10-year,25-year,50-year,1pct_min,100-year,1pct_plu,500-year
River Rch & RM= UNT 113 in HW,Reach-1,5390
     401     556     686     420     838    1671    1252
Boundary for River Rch & Prof#=UNT 113 in HW,Reach-1,1
Up Type=0
Dn Type=3
Dn Slope=0.005
Boundary for River Rch & Prof#=UNT 113 in HW,Reach-1,2
Up Type=0
Dn Type=3
Dn Slope=0.005
Boundary for River Rch & Prof#=UNT 113 in HW,Reach-1,3
Up Type=0
Dn Type=3
Dn Slope=0.005
Boundary for River Rch & Prof#=UNT 113 in HW,Reach-1,4
Up Type=0
Dn Type=3
Dn Slope=0.005
Boundary for River Rch & Prof#=UNT 113 in HW,Reach-1,5
Up Type=0
Dn Type=3
Dn Slope=0.005
Boundary for River Rch & Prof#=UNT 113 in HW,Reach-1,6
Up Type=0
Dn Type=3
Dn Slope=0.005
Boundary for River Rch & Prof#=UNT 113 in HW,Reach-1,7
Up Type=0
Dn Type=3
Dn Slope=0.005

--- UNT 113 in HW.g01 (geometry) ---

Geom Title=Existing Conditions

River Reach=UNT 113 in HW,Reach-1
Reach XY= 30
      1998960.80     13639134.54      1999010.80     13639184.54
      1999270.80     13639154.54      1999428.17     13639280.87
      1999742.76     13639452.40      1999949.01     13639466.28
      2000068.17     13639526.60      2000205.26     13639741.98
      2000200.80     13640384.54      2000330.80     13640544.54
      2000330.80     13640624.54      2000620.80     13640844.54
      2000790.80     13640844.54      2000938.66     13640738.63
      2000980.80     13640664.54      2001081.54     13640791.58
      2001163.84     13640752.00      2001112.27     13640635.33
      2001229.55     13640589.72      2001224.86     13640501.18
      2001430.07     13640219.41      2001482.68     13640229.31
      2001534.24     13640318.89      2001785.28     13640360.56
      2002010.80     13640294.54      2002110.80     13640204.54
      2002150.80     13640234.54      2002250.80     13640214.54
      2002300.80     13640254.54      2002490.80     13640174.54

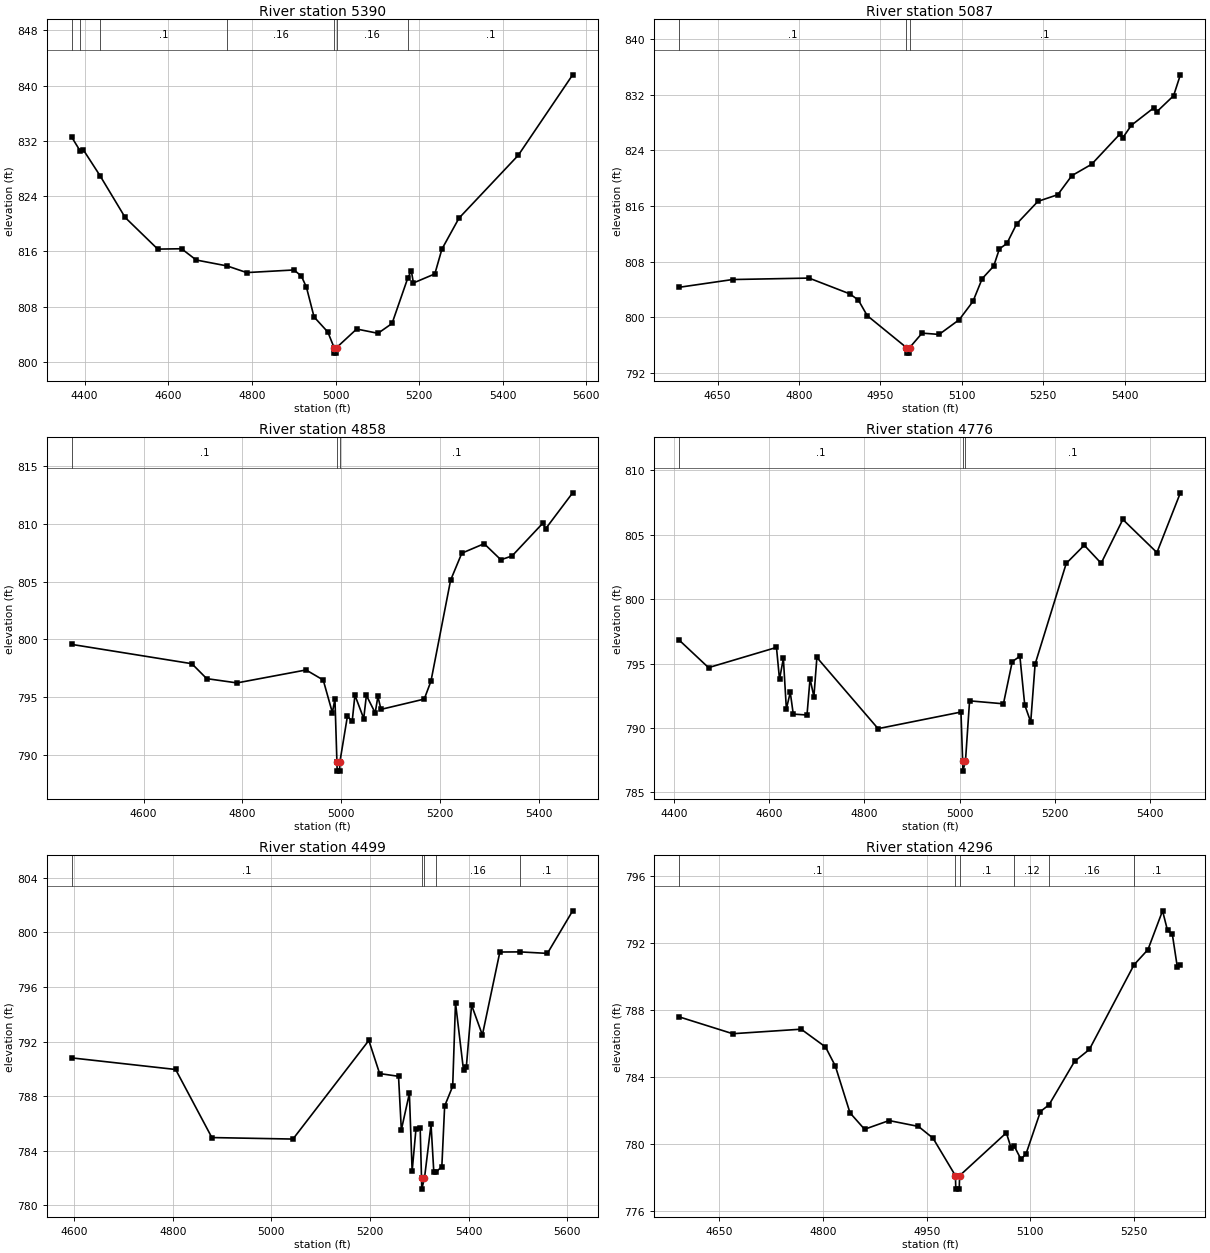
Type RM Length L Ch R = 1,5390,303,303,303
BEGIN DESCRIPTION:
UNT 113 in HW 8.0
END DESCRIPTION:
XS GIS Cut Line= 3
      1998675.02     13639624.98      1999087.20     13639269.74
      1999214.45     13638628.28
#Sta/Elev= 30
  4369.0  832.54  4389.8  830.48  4397.0  830.68  4436.7  826.96  4496.8  820.91
  4574.7  816.33  4631.7  816.38  4666.8  814.75  4740.9  813.89  4787.5  812.93
  4900.5  813.31  4918.1  812.44  4930.4  810.81  4948.6  806.51  4981.6  804.32
  4996.5  802.07  4997.0  801.27  5002.0  801.27  5002.5  802.07  5050.5  804.76
  5101.5  804.14  5135.1  805.56  5173.0  812.18  5181.2  813.18  5186.3  811.43
  5237.5  812.74  5254.4  816.33  5295.2  820.81  5437.1  829.92  5567.1  841.56
#Mann=7,-1,0
  4369.0     0.1       0  4389.8    0.16       0  4436.7     0.1       0
  4740.9    0.16       0  4996.5    0.07       0  5002.5    0.16       0
  5173.0     0.1       0
Bank Sta=4996.5,5002.5
Exp/Cntr=0.3,0.1

Type RM Length L Ch R = 1,5087,229,229,229
BEGIN DESCRIPTION:
UNT 113 in HW 7.0
END DESCRIPTION:
XS GIS Cut Line= 3
      1999214.80     13639629.12      1999352.82     13639259.32
      1999524.59     13638759.64
#Sta/Elev= 30
  4579.5  804.30  4677.4  805.41  4818.3  805.62  4893.4  803.35  4909.2  802.46
  4925.5  800.22  4997.8  795.62  4998.3  794.82  5003.3  794.82  5003.8  795.62
  5026.7  797.70  5058.0  797.51  5095.1  799.63  5120.4  802.26  5137.4  805.54
  5158.6  807.34  5169.1  809.82  5182.9  810.60  5200.9  813.42  5240.1  816.66
  5276.7  817.62  5302.6  820.36  5339.1  822.00  5391.1  826.34  5396.3  825.79
  5412.3  827.61  5453.5  830.11  5458.8  829.53  5490.1  831.86  5502.6  834.87
#Mann=3,-1,0
  4579.5     0.1       0  4997.8    0.07       0  5003.8     0.1       0
Bank Sta=4997.8,5003.8
Exp/Cntr=0.3,0.1

Type RM Length L Ch R = 1,4858,82,82,82
BEGIN DESCRIPTION:
UNT 113 in HW 6.0
END DESCRIPTION:
XS GIS Cut Line= 6
      1999355.45     13639751.49      1999589.80     13639600.47
      1999553.35     13639384.32      1999566.37     13639324.43
      1999657.51     13639199.43      1999785.13     13638933.77
#Sta/Elev= 30
  4454.8  799.56  4697.8  797.89  4727.8  796.60  4789.1  796.23  4928.8  797.35
  4963.5  796.48  4982.0  793.66  4987.2  794.84  4991.2  789.40  4991.7  788.60
  4996.7  788.60  4997.2  789.40  5012.4  793.34  5022.1  792.91  5027.6  795.17
  5045.4  793.15  5050.8  795.15  5068.6  793.64  5074.1  795.06  5080.3  793.94
  5167.8  794.83  5181.4  796.38  5221.1  805.11  5243.8  807.45  5289.0  808.27
  5322.8  806.88  5345.4  807.21  5407.8  810.05  5413.3  809.56  5468.0  812.67
#Mann=3,-1,0
  4454.8     0.1       0  4991.2    0.07       0  4997.2     0.1       0
Bank Sta=4991.2,4997.2
Exp/Cntr=0.3,0.1

Type RM Length L Ch R = 1,4776,277,277,277
BEGIN DESCRIPTION:
Mapping XS 22c35613
END DESCRIPTION:
XS GIS Cut Line= 6
      1999483.01     13639879.14      1999696.57     13639605.68
      1999688.76     13639498.90      1999636.68     13639371.30
      1999649.70     13639316.61      1999854.79     13638968.83
#Sta/Elev= 30
  4410.9  796.80  4472.1  794.68  4615.0  796.25  4621.4  793.77  4629.5  795.40
  4635.8  791.47  4644.0  792.76  4650.3  791.07  4679.2  791.00  4685.6  793.82
  4693.7  792.42  4700.0  795.47  4828.7  789.94  5003.0  791.23  5006.5  787.44
  5007.0  786.64  5012.5  787.44  5021.1  792.10  5092.3  791.87  5110.9  795.15
  5126.9  795.56  5137.1  791.78  5149.7  790.46  5158.9  794.95  5224.4  802.78
  5262.3  804.19  5297.8  802.79  5343.4  806.19  5415.1  803.62  5464.4  808.26
#Mann=3,-1,0
  4410.9     0.1       0  5006.5    0.07       0  5012.5     0.1       0
Bank Sta=5006.5,5012.5
Exp/Cntr=0.3,0.1

Type RM Length L Ch R = 1,4499,203,203,203
BEGIN DESCRIPTION:
Mapping XS ba08213a
END DESCRIPTION:
XS GIS Cut Line= 2
      1999696.56     13639820.99      2000173.99     13638924.72
#Sta/Elev= 30
  4595.2  790.80  4805.9  789.95  4879.3  784.96  5043.7  784.85  5197.5  792.08
  5219.4  789.65  5257.7  789.45  5263.4  785.52  5279.7  788.20  5285.3  782.49
  5293.1  785.61  5301.6  785.65  5304.3  781.98  5304.8  781.18  5310.3  781.98
  5323.6  785.92  5329.2  782.45  5333.1  782.41  5345.5  782.83  5351.2  787.27
  5367.5  788.72  5373.2  794.84  5389.5  789.88  5395.1  790.12  5405.8  794.67
  5427.7  792.48  5463.1  798.56  5504.1  798.57  5559.5  798.46  5610.7  801.58
#Mann=5,-1,0
  4595.2     0.1       0  5304.3    0.07       0  5310.3     0.1       0
  5333.1    0.16       0  5504.1     0.1       0
Bank Sta=5304.3,5310.3
Exp/Cntr=0.3,0.1

Type RM Length L Ch R = 1,4296,213,213,213
BEGIN DESCRIPTION:
Mapping XS ed732960
END DESCRIPTION:
XS GIS Cut Line= 2
      1999787.75     13639826.99      2000290.17     13639303.75
#Sta/Elev= 30
  4592.0  787.60  4669.2  786.60  4768.3  786.87  4803.5  785.81  4817.7  784.68
  4839.0  781.88  4860.1  780.90  4895.6  781.42  4938.1  781.07  4959.2  780.37
  4991.7  778.13  4992.2  777.33  4997.2  777.33  4997.7  778.13  5065.4  780.69
  5072.4  779.77  5076.5  779.92  5086.5  779.12  5093.8  779.42  5114.8  781.96
  5127.2  782.36  5164.2  784.95  5185.6  785.66  5250.3  790.71  5270.5  791.62
  5291.6  793.93  5298.8  792.76  5305.7  792.55  5312.9  790.60  5317.4  790.69
#Mann=6,-1,0
  4592.0     0.1       0  4991.7    0.07       0  4997.7     0.1       0
  5076.5    0.12       0  5127.2    0.16       0  5250.3     0.1       0
Bank Sta=4991.7,4997.7
Exp/Cntr=0.3,0.1

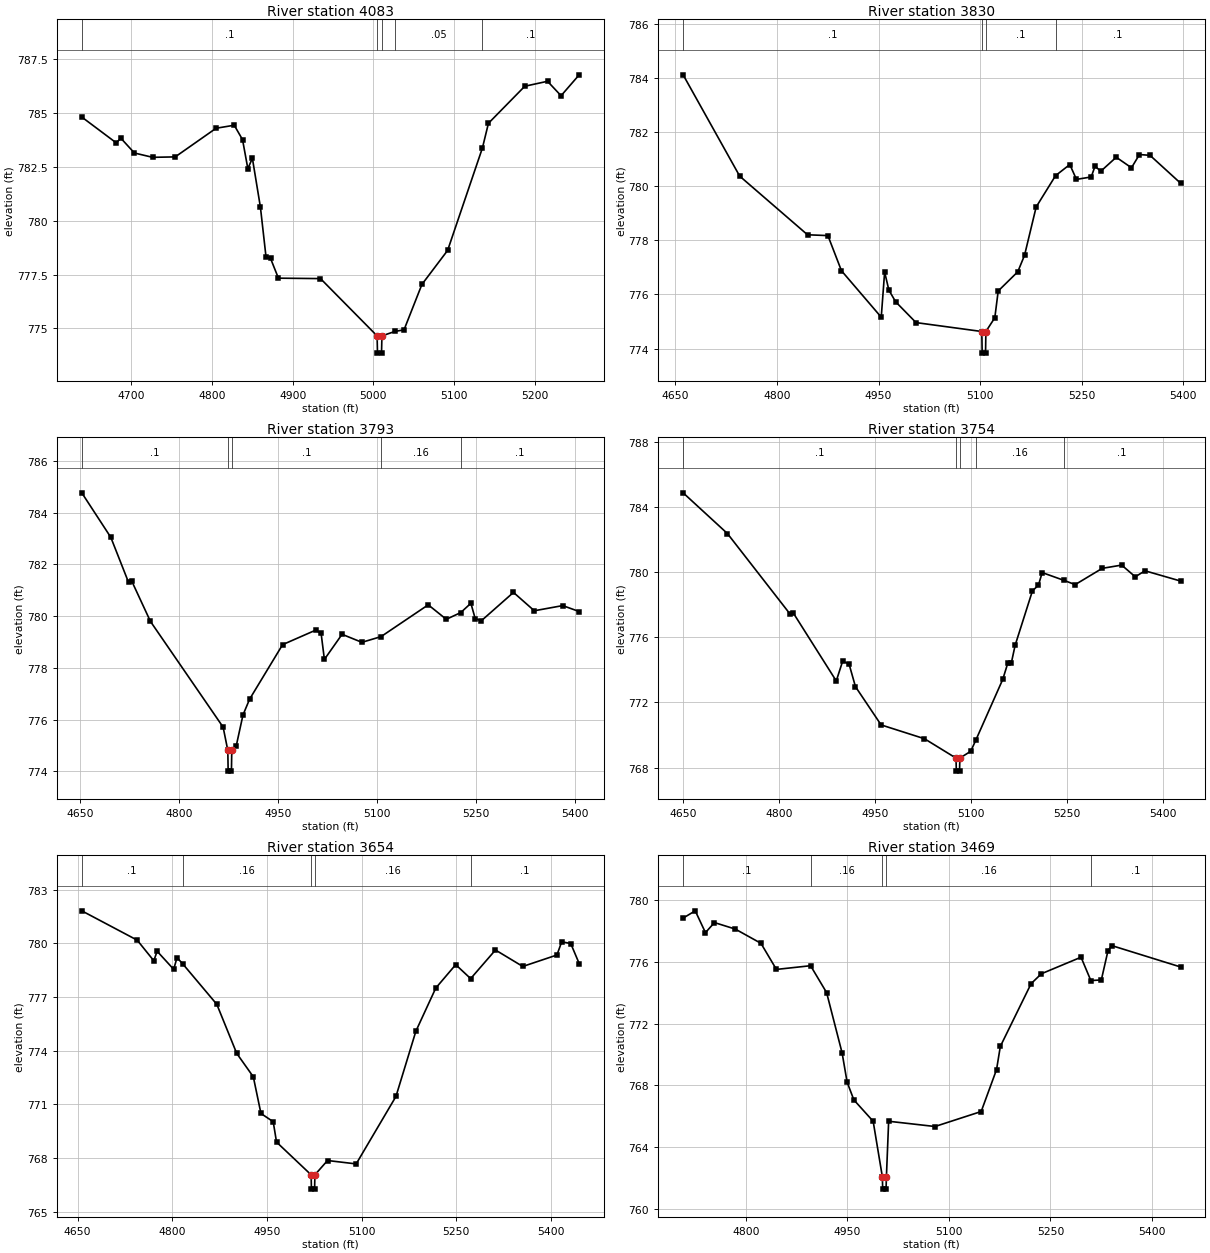
Type RM Length L Ch R = 1,4083,253,253,253
BEGIN DESCRIPTION:
Mapping XS a06f4177
END DESCRIPTION:
XS GIS Cut Line= 2
      1999865.84     13639860.89      2000420.28     13639590.17
#Sta/Elev= 30
  4638.4  784.81  4681.2  783.61  4686.8  783.83  4703.7  783.14  4726.3  782.94
  4754.3  782.96  4805.0  784.29  4827.5  784.43  4837.8  783.76  4844.4  782.41
  4850.0  782.90  4860.0  780.62  4867.0  778.29  4872.5  778.25  4882.3  777.33
  4934.5  777.31  5004.7  774.65  5005.2  773.85  5010.2  773.85  5010.7  774.65
  5027.0  774.86  5038.1  774.93  5060.3  777.04  5092.2  778.62  5135.4  783.38
  5142.8  784.52  5187.9  786.24  5216.1  786.47  5232.9  785.80  5255.4  786.77
#Mann=5,-1,0
  4638.4     0.1       0  5004.7    0.07       0  5010.7     0.1       0
  5027.0    0.05       0  5135.4     0.1       0
Bank Sta=5004.7,5010.7
Exp/Cntr=0.3,0.1

Type RM Length L Ch R = 1,3830,37,37,37
BEGIN DESCRIPTION:
Mapping XS 3cce0298
END DESCRIPTION:
XS GIS Cut Line= 3
      1999861.54     13639932.07      2000377.13     13639963.31
      2000568.09     13639857.42
#Sta/Elev= 30
  4661.3  784.13  4744.9  780.38  4845.1  778.21  4875.2  778.18  4895.2  776.88
  4954.0  775.16  4959.0  776.83  4965.3  776.16  4975.3  775.73  5005.4  774.96
  5102.6  774.63  5103.1  773.83  5108.1  773.83  5108.6  774.63  5121.8  775.14
  5126.8  776.13  5155.7  776.84  5165.7  777.45  5182.9  779.24  5211.6  780.40
  5232.6  780.81  5242.4  780.26  5264.2  780.35  5269.9  780.75  5278.3  780.56
  5301.2  781.08  5323.7  780.69  5335.5  781.18  5351.1  781.15  5396.2  780.12
#Mann=4,-1,0
  4661.3     0.1       0  5102.6    0.07       0  5108.6     0.1       0
  5211.6     0.1       0
Bank Sta=5102.6,5108.6
Exp/Cntr=0.3,0.1

Type RM Length L Ch R = 1,3793,39,39,39
BEGIN DESCRIPTION:
Mapping XS 5afcae67
END DESCRIPTION:
XS GIS Cut Line= 3
      1999851.10     13639965.05      2000359.77     13639999.77
      2000571.65     13639877.47
#Sta/Elev= 30
  4652.5  784.77  4696.5  783.05  4723.4  781.31  4728.4  781.35  4756.6  779.80
  4866.9  775.71  4874.0  774.81  4874.5  774.01  4879.5  774.01  4880.0  774.81
  4886.9  775.00  4897.0  776.18  4907.0  776.79  4957.1  778.90  5007.2  779.46
  5015.5  779.34  5020.5  778.33  5047.3  779.30  5077.4  778.99  5106.4  779.21
  5178.0  780.44  5205.4  779.88  5227.3  780.14  5242.7  780.50  5249.2  779.91
  5258.4  779.82  5307.3  780.92  5338.9  780.21  5382.0  780.41  5407.0  780.18
#Mann=5,-1,0
  4652.5     0.1       0  4874.0    0.07       0  4880.0     0.1       0
  5106.4    0.16       0  5227.3     0.1       0
Bank Sta=4874,4880
Exp/Cntr=0.3,0.1

Type RM Length L Ch R = 1,3754,100,100,100
BEGIN DESCRIPTION:
Mapping XS edef7066
END DESCRIPTION:
XS GIS Cut Line= 3
      1999845.89     13640011.93      2000356.30     13640036.23
      2000581.01     13639892.76
#Sta/Elev= 30
  4649.7  784.88  4718.9  782.38  4816.7  777.44  4821.7  777.51  4889.1  773.32
  4899.1  774.54  4909.1  774.36  4919.1  772.97  4959.2  770.62  5027.0  769.77
  5076.3  768.58  5076.8  767.78  5081.8  767.78  5082.3  768.58  5099.3  769.00
  5107.1  769.67  5149.4  773.42  5157.5  774.45  5162.9  774.45  5168.7  775.51
  5195.8  778.86  5205.1  779.20  5211.0  779.98  5244.4  779.51  5262.6  779.24
  5304.9  780.24  5335.3  780.44  5356.5  779.72  5371.7  780.09  5427.3  779.46
#Mann=5,-1,0
  4649.7     0.1       0  5076.3    0.07       0  5082.3     0.1       0
  5107.1    0.16       0  5244.4     0.1       0
Bank Sta=5076.3,5082.3
Exp/Cntr=0.3,0.1

Type RM Length L Ch R = 1,3654,185,185,185
BEGIN DESCRIPTION:
UNT 113 in HW 5.0
END DESCRIPTION:
XS GIS Cut Line= 3
      1999865.83     13640237.62      2000525.57     13640016.27
      2000595.04     13639955.47
#Sta/Elev= 30
  4656.5  781.82  4744.3  780.18  4770.6  779.03  4775.9  779.56  4802.1  778.55
  4807.4  779.20  4816.1  778.87  4870.5  776.59  4902.0  773.85  4928.3  772.54
  4940.4  770.49  4959.8  770.03  4965.1  768.89  5019.9  767.06  5020.4  766.26
  5025.4  766.26  5025.9  767.06  5045.9  767.86  5091.3  767.67  5154.3  771.44
  5185.9  775.09  5217.4  777.50  5249.0  778.81  5272.7  778.03  5312.0  779.63
  5355.3  778.71  5409.4  779.35  5417.0  780.09  5431.3  779.99  5444.7  778.87
#Mann=5,-1,0
  4656.5     0.1       0  4816.1    0.16       0  5019.9    0.07       0
  5025.9    0.16       0  5272.7     0.1       0
Bank Sta=5019.9,5025.9
Exp/Cntr=0.3,0.1

Type RM Length L Ch R = 1,3469,224,224,224
BEGIN DESCRIPTION:
UNT 113 in HW 4.0
END DESCRIPTION:
XS GIS Cut Line= 3
      1999925.11     13640428.15      2000250.61     13640277.12
      2000590.89     13640116.07
#Sta/Elev= 30
  4707.1  778.82  4725.0  779.29  4740.1  777.88  4753.4  778.53  4784.2  778.11
  4822.1  777.19  4845.0  775.50  4895.5  775.74  4919.2  774.00  4942.1  770.10
  4949.5  768.21  4959.5  767.06  4988.0  765.68  5001.6  762.09  5002.1  761.29
  5007.1  761.29  5007.6  762.09  5010.9  765.68  5079.4  765.34  5147.7  766.31
  5170.4  769.02  5176.0  770.52  5221.5  774.58  5236.7  775.22  5295.3  776.29
  5309.8  774.78  5325.3  774.82  5335.2  776.72  5340.8  777.04  5442.4  775.66
#Mann=5,-1,0
  4707.1     0.1       0  4895.5    0.16       0  5001.6    0.07       0
  5007.6    0.16       0  5309.8     0.1       0
Bank Sta=5001.6,5007.6
Exp/Cntr=0.3,0.1

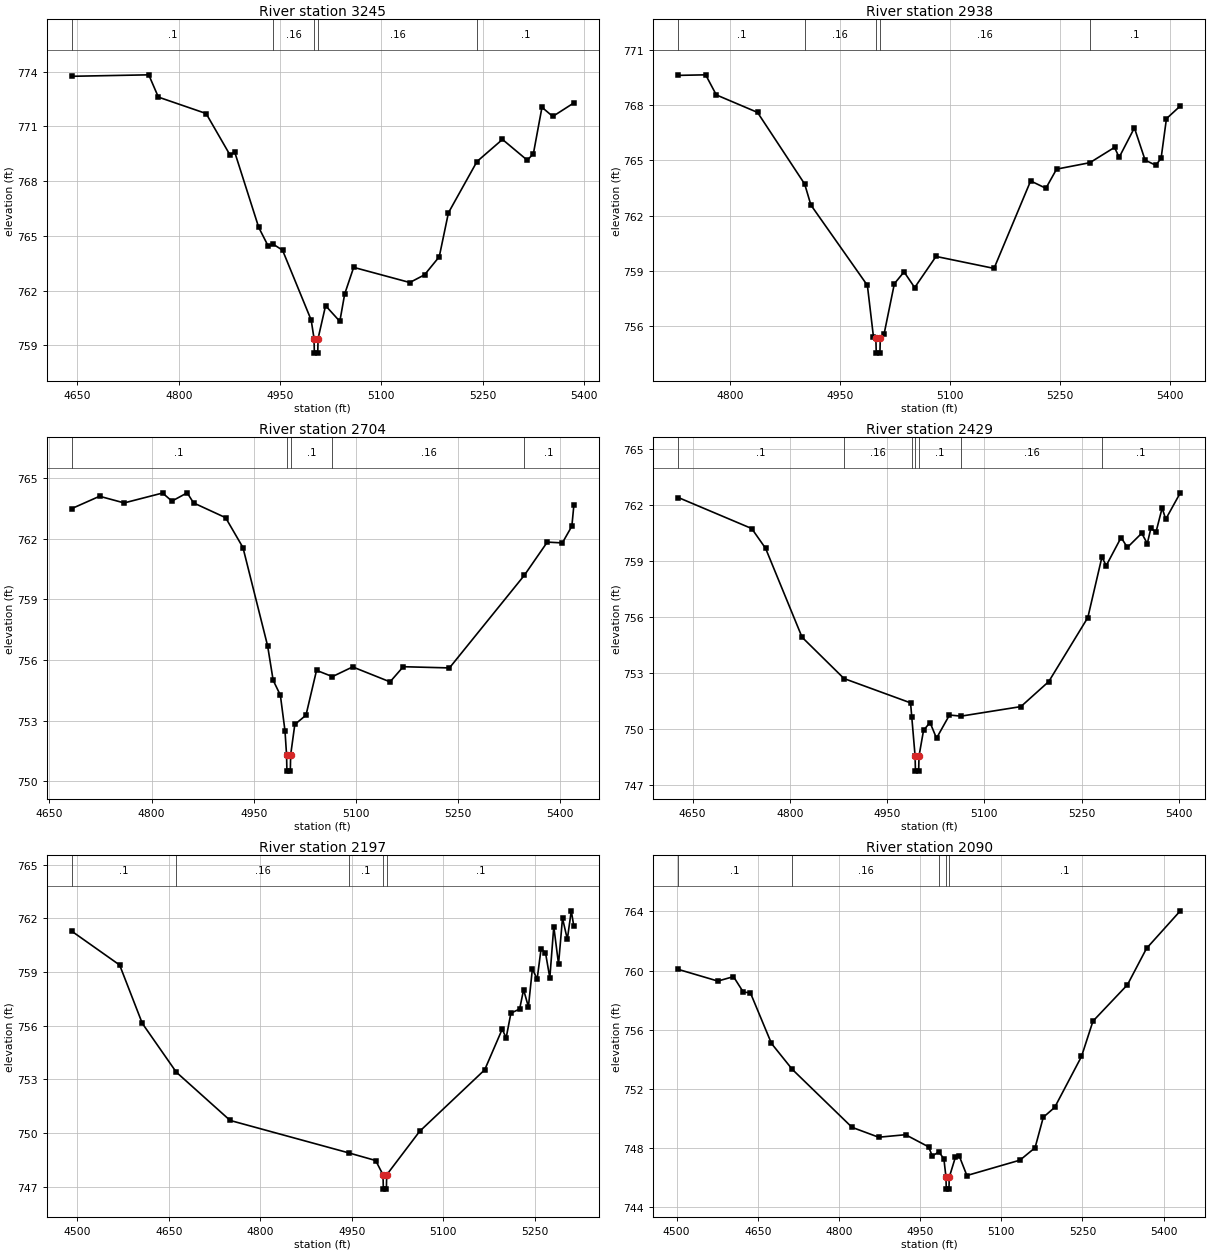
Type RM Length L Ch R = 1,3245,307,307,307
BEGIN DESCRIPTION:
UNT 113 in HW 3.0
END DESCRIPTION:
XS GIS Cut Line= 3
      2000024.07     13640735.43      2000326.13     13640441.18
      2000607.36     13640284.94
#Sta/Elev= 30
  4641.6  773.74  4755.6  773.82  4769.8  772.60  4840.5  771.70  4876.0  769.42
  4882.9  769.58  4918.4  765.46  4932.5  764.43  4940.2  764.53  4953.7  764.21
  4996.1  760.38  5000.3  759.37  5000.8  758.57  5005.8  758.57  5006.3  759.37
  5017.4  761.17  5038.5  760.31  5045.7  761.81  5059.0  763.27  5142.1  762.44
  5163.9  762.86  5185.7  763.85  5199.3  766.26  5241.6  769.07  5279.3  770.28
  5316.1  769.14  5325.1  769.50  5337.8  772.04  5353.8  771.54  5385.0  772.28
#Mann=5,-1,0
  4641.6     0.1       0  4940.2    0.16       0  5000.3    0.07       0
  5006.3    0.16       0  5241.6     0.1       0
Bank Sta=5000.3,5006.3
Exp/Cntr=0.3,0.1

Type RM Length L Ch R = 1,2938,234,234,234
BEGIN DESCRIPTION:
Mapping XS 54566c3b
END DESCRIPTION:
XS GIS Cut Line= 2
      2000237.57     13640909.95      2000650.83     13640364.15
#Sta/Elev= 30
  4729.6  769.61  4767.0  769.64  4781.5  768.55  4837.7  767.60  4902.0  763.71
  4910.5  762.57  4987.5  758.21  4995.8  755.41  4999.1  755.33  4999.6  754.53
  5004.6  754.53  5005.1  755.33  5010.4  755.59  5024.3  758.30  5037.5  758.94
  5052.0  758.09  5081.1  759.78  5160.2  759.13  5210.1  763.88  5230.9  763.48
  5245.5  764.52  5290.9  764.87  5324.5  765.70  5330.8  765.16  5351.6  766.76
  5366.2  765.01  5380.7  764.73  5388.0  765.11  5395.3  767.26  5414.2  767.95
#Mann=5,-1,0
  4729.6     0.1       0  4902.0    0.16       0  4999.1    0.07       0
  5005.1    0.16       0  5290.9     0.1       0
Bank Sta=4999.1,5005.1
Exp/Cntr=0.3,0.1

Type RM Length L Ch R = 1,2704,275,275,275
BEGIN DESCRIPTION:
Mapping XS 91d559d7
END DESCRIPTION:
XS GIS Cut Line= 2
      2000474.57     13641123.48      2000721.62     13640429.12
#Sta/Elev= 30
  4682.7  763.50  4723.5  764.11  4759.6  763.78  4816.0  764.27  4829.7  763.87
  4852.1  764.28  4861.5  763.78  4908.5  763.05  4934.0  761.57  4970.2  756.70
  4978.3  755.00  4988.9  754.26  4995.7  752.49  4998.0  751.30  4998.5  750.50
  5003.5  750.50  5004.0  751.30  5010.1  752.81  5026.5  753.27  5042.0  755.49
  5065.3  755.18  5095.0  755.66  5149.9  754.92  5169.3  755.67  5237.1  755.61
  5347.1  760.20  5380.7  761.84  5402.8  761.80  5416.8  762.63  5419.7  763.66
#Mann=5,-1,0
  4682.7     0.1       0  4998.0    0.07       0  5004.0     0.1       0
  5065.3    0.16       0  5347.1     0.1       0
Bank Sta=4998,5004
Exp/Cntr=0.3,0.1

Type RM Length L Ch R = 1,2429,232,232,232
BEGIN DESCRIPTION:
Mapping XS 422a7ee0
END DESCRIPTION:
XS GIS Cut Line= 4
      2000635.86     13641096.05      2000837.23     13640906.83
      2000828.74     13640644.30      2000729.88     13640430.98
#Sta/Elev= 30
  4628.0  762.38  4741.3  760.72  4762.7  759.66  4818.9  754.91  4883.6  752.70
  4986.2  751.40  4988.0  750.67  4993.2  748.55  4993.7  747.75  4998.7  747.75
  4999.2  748.55  5006.2  749.93  5016.2  750.35  5026.2  749.51  5046.2  750.75
  5064.0  750.69  5156.3  751.20  5199.3  752.54  5259.5  755.96  5281.2  759.19
  5287.9  758.74  5310.8  760.24  5320.5  759.71  5342.6  760.47  5351.2  759.92
  5356.7  760.73  5364.6  760.53  5374.1  761.82  5379.6  761.22  5402.1  762.63
#Mann=7,-1,0
  4628.0     0.1       0  4883.6    0.16       0  4988.0     0.1       0
  4993.2    0.07       0  4999.2     0.1       0  5064.0    0.16       0
  5281.2     0.1       0
Bank Sta=4993.2,4999.2
Exp/Cntr=0.3,0.1

Type RM Length L Ch R = 1,2197,107,107,107
BEGIN DESCRIPTION:
Mapping XS 3f635e14
END DESCRIPTION:
XS GIS Cut Line= 5
      2000759.28     13641106.13      2000880.38     13640900.66
      2001009.97     13640700.41      2000971.31     13640641.33
      2000759.20     13640465.26
#Sta/Elev= 30
  4491.0  761.28  4569.5  759.39  4606.6  756.13  4662.4  753.40  4750.7  750.70
  4944.8  748.89  4989.3  748.46  5001.4  747.66  5001.9  746.86  5006.9  746.86
  5007.4  747.66  5061.4  750.09  5168.1  753.53  5196.8  755.80  5203.3  755.32
  5211.1  756.70  5225.4  756.93  5231.9  758.01  5239.8  757.05  5246.3  759.17
  5254.1  758.60  5260.6  760.30  5267.8  760.08  5274.9  758.67  5281.4  761.54
  5289.2  759.44  5295.7  762.01  5303.6  760.83  5310.1  762.42  5314.3  761.55
#Mann=5,-1,0
  4491.0     0.1       0  4662.4    0.16       0  4944.8     0.1       0
  5001.4    0.07       0  5007.4     0.1       0
Bank Sta=5001.4,5007.4
Exp/Cntr=0.3,0.1

Type RM Length L Ch R = 1,2090,108,108,108
BEGIN DESCRIPTION:
Mapping XS 30df4d1e
END DESCRIPTION:
XS GIS Cut Line= 5
      2000800.76     13641167.26      2000913.62     13640908.74
      2001092.44     13640721.24      2001015.18     13640599.71
      2000842.70     13640429.09
#Sta/Elev= 30
  4503.0  760.08  4576.2  759.29  4605.1  759.59  4623.1  758.55  4636.4  758.49
  4675.3  755.07  4713.7  753.32  4824.1  749.40  4873.4  748.73  4923.1  748.90
  4965.6  748.08  4972.5  747.46  4984.5  747.74  4993.9  747.27  4997.8  746.02
  4998.3  745.22  5003.3  745.22  5003.8  746.02  5015.0  747.36  5022.2  747.47
  5036.4  746.14  5134.5  747.18  5162.4  748.02  5177.6  750.08  5198.7  750.75
  5248.2  754.19  5269.4  756.58  5333.1  759.04  5368.4  761.50  5430.8  764.04
#Mann=5,-1,0
  4503.0     0.1       0  4713.7    0.16       0  4984.5     0.1       0
  4997.8    0.07       0  5003.8     0.1       0
Bank Sta=4997.8,5003.8
Exp/Cntr=0.3,0.1

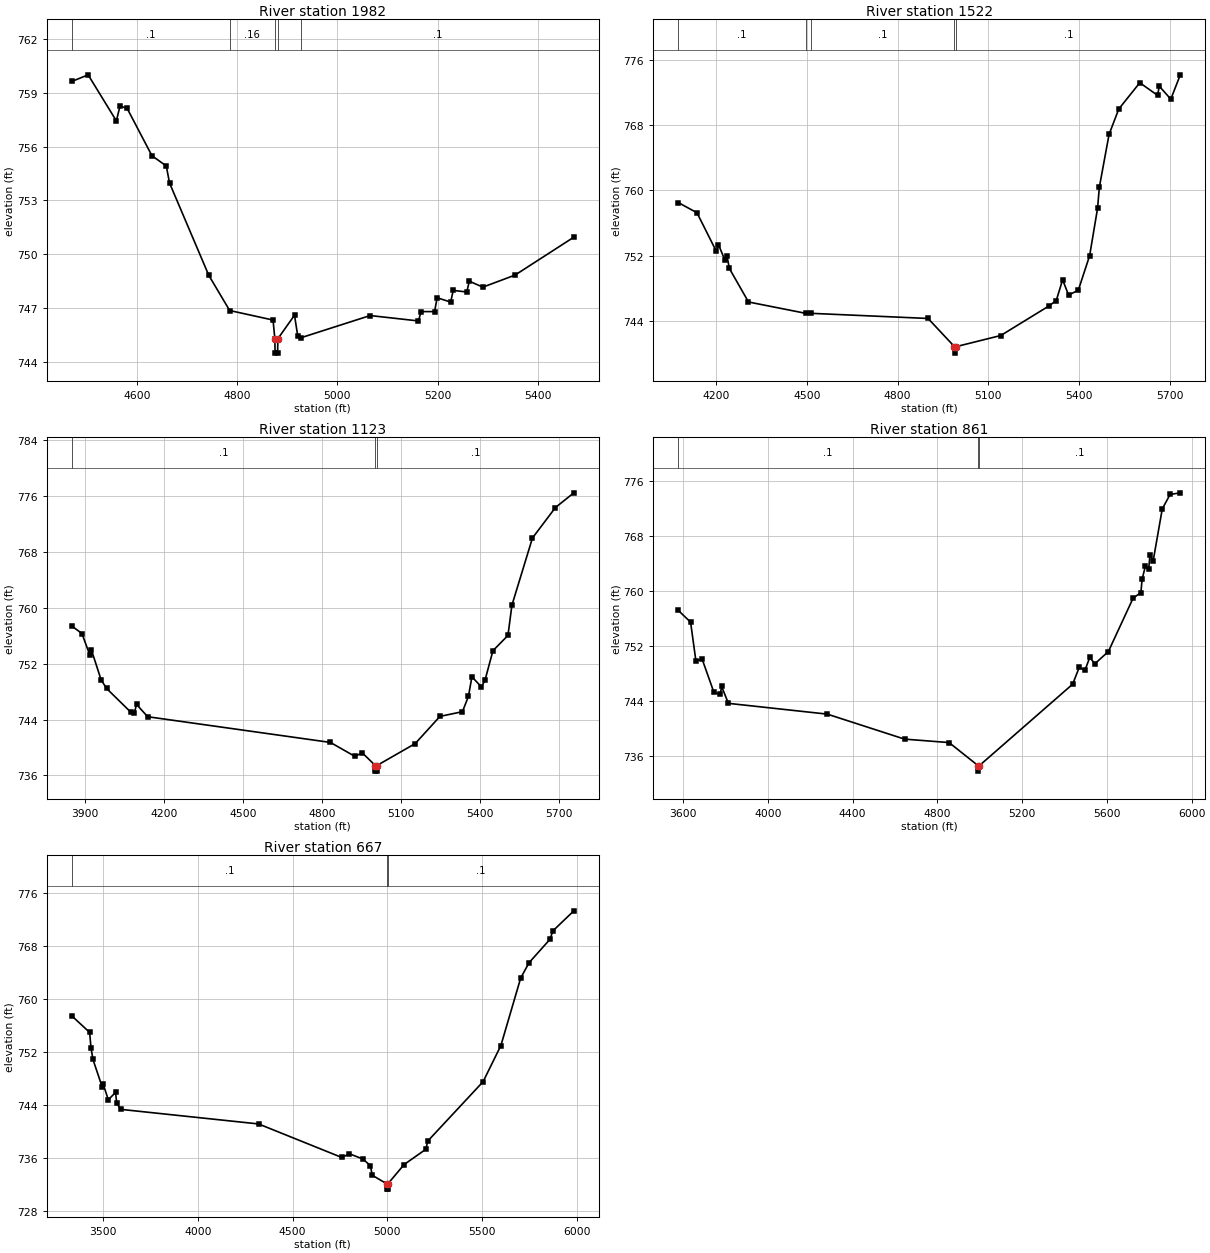
Type RM Length L Ch R = 1,1982,460,460,460
BEGIN DESCRIPTION:
Mapping XS a9c556f0
END DESCRIPTION:
XS GIS Cut Line= 3
      2000826.81     13641172.46      2001149.73     13640795.72
      2000995.22     13640314.83
#Sta/Elev= 30
  4470.2  759.62  4502.8  759.99  4559.1  757.43  4566.5  758.26  4580.7  758.12
  4630.1  755.49  4658.7  754.92  4665.2  753.97  4743.4  748.84  4785.1  746.88
  4871.6  746.35  4875.2  745.31  4875.7  744.51  4880.7  744.51  4881.2  745.31
  4914.4  746.62  4921.0  745.44  4927.7  745.37  5065.3  746.60  5161.6  746.30
  5166.8  746.82  5193.7  746.82  5198.9  747.59  5225.8  747.35  5231.0  748.00
  5257.9  747.91  5263.1  748.51  5290.0  748.18  5354.2  748.85  5471.5  750.96
#Mann=5,-1,0
  4470.2     0.1       0  4785.1    0.16       0  4875.2    0.07       0
  4881.2    0.16       0  4927.7     0.1       0
Bank Sta=4875.2,4881.2
Exp/Cntr=0.3,0.1

Type RM Length L Ch R = 1,1522,399,399,399
BEGIN DESCRIPTION:
UNT 113 in HW 2.0
END DESCRIPTION:
XS GIS Cut Line= 4
      2000870.40     13641178.16      2001285.15     13640795.72
      2001274.05     13640178.16      2001128.23     13639725.07
#Sta/Elev= 30
  4075.8  758.50  4137.7  757.25  4201.8  752.50  4208.6  753.34  4230.1  751.43
  4236.9  751.96  4244.3  750.44  4307.8  746.31  4498.0  744.91  4513.8  744.92
  4900.7  744.29  4987.7  740.84  4988.2  740.04  4993.7  740.84  5140.8  742.20
  5300.6  745.84  5324.0  746.49  5345.0  749.03  5364.7  747.16  5396.8  747.75
  5434.2  751.99  5460.5  757.83  5466.2  760.37  5498.3  766.85  5530.4  769.97
  5599.8  773.19  5658.7  771.64  5664.0  772.77  5702.2  771.18  5733.6  774.16
#Mann=5,-1,0
  4075.8     0.1       0  4498.0    0.16       0  4513.8     0.1       0
  4987.7    0.07       0  4993.7     0.1       0
Bank Sta=4987.7,4993.7
Exp/Cntr=0.3,0.1

Type RM Length L Ch R = 1,1123,262,262,262
BEGIN DESCRIPTION:
Mapping XS 426e3a6b
END DESCRIPTION:
XS GIS Cut Line= 4
      2000906.65     13641171.71      2001463.97     13640741.90
      2001547.27     13640077.96      2001250.42     13639632.69
#Sta/Elev= 30
  3849.3  757.39  3888.1  756.31  3917.1  753.30  3923.5  754.02  3960.6  749.70
  3981.5  748.45  4074.5  745.02  4087.4  745.00  4095.6  746.16  4137.7  744.40
  4832.2  740.72  4925.4  738.72  4953.1  739.24  5002.9  737.41  5003.4  736.61
  5008.4  736.61  5008.9  737.41  5154.7  740.56  5248.6  744.45  5334.0  745.12
  5356.8  747.32  5370.0  750.12  5406.1  748.67  5419.9  749.65  5449.9  753.85
  5507.0  756.04  5522.0  760.36  5600.1  769.99  5687.3  774.35  5757.4  776.46
#Mann=3,-1,0
  3849.3     0.1       0  5002.9    0.07       0  5008.9     0.1       0
Bank Sta=5002.9,5008.9
Exp/Cntr=0.3,0.1

Type RM Length L Ch R = 1,861,194,194,194
BEGIN DESCRIPTION:
Mapping XS 4041ad24
END DESCRIPTION:
XS GIS Cut Line= 4
      2000893.58     13641189.96      2001753.00     13640864.42
      2001760.81     13640218.59      2001344.62     13639529.27
#Sta/Elev= 30
  3576.7  757.23  3635.0  755.52  3659.8  749.93  3690.0  750.09  3745.0  745.30
  3775.1  744.98  3781.4  746.15  3813.5  743.69  4280.5  742.12  4645.1  738.48
  4855.2  737.98  4992.2  734.62  4992.7  733.82  4998.2  734.62  5438.5  746.48
  5469.5  748.92  5496.7  748.52  5519.6  750.40  5542.9  749.44  5607.3  751.24
  5723.8  759.00  5760.7  759.83  5766.5  761.77  5782.0  763.68  5797.5  763.22
  5803.4  765.25  5818.9  764.48  5861.6  772.01  5898.5  774.11  5946.8  774.35
#Mann=3,-1,0
  3576.7     0.1       0  4992.2    0.07       0  4998.2     0.1       0
Bank Sta=4992.2,4998.2
Exp/Cntr=0.3,0.1

Type RM Length L Ch R = 1,667,0,0,0
BEGIN DESCRIPTION:
UNT 113 in HW 1.0
END DESCRIPTION:
XS GIS Cut Line= 4
      2000867.83     13641206.80      2001911.85     13640890.46
      2001956.12     13640117.03      2001589.68     13639420.54
#Sta/Elev= 30
  3333.0  757.48  3427.4  754.99  3434.5  752.68  3445.0  750.90  3493.2  746.80
  3498.4  747.23  3526.1  744.83  3564.2  745.93  3570.4  744.32  3591.3  743.38
  4319.8  741.18  4759.9  736.12  4800.0  736.68  4870.1  735.90  4910.2  734.91
  4920.8  733.44  4997.3  732.15  4997.8  731.35  5002.8  731.35  5003.3  732.15
  5088.5  735.05  5202.6  737.34  5214.8  738.63  5506.0  747.55  5600.2  753.01
  5704.7  763.18  5748.8  765.49  5859.0  769.01  5875.4  770.31  5985.6  773.32
#Mann=3,-1,0
  3333.0     0.1       0  4997.3    0.07       0  5003.3     0.1       0
Bank Sta=4997.3,5003.3
Exp/Cntr=0.3,0.1

Chan Stop Cuts=-1