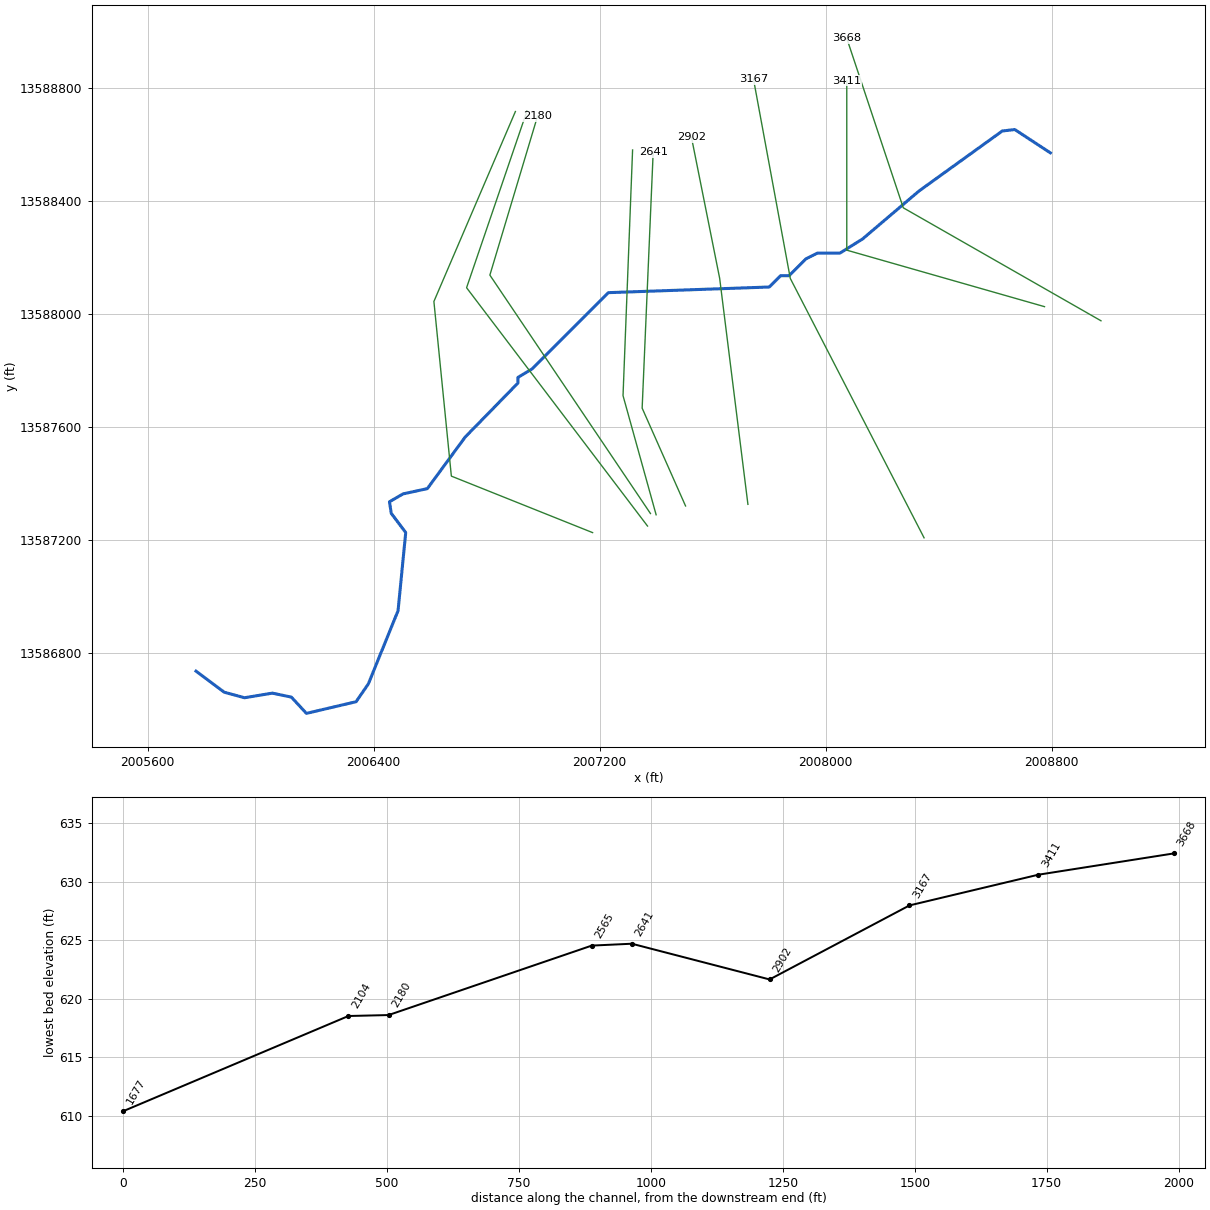
--- UNT 114 in HW.prj (project) ---

Proj Title=UNT 114 in HW Base Level Engineering
Current Plan=p01
Default Exp/Contr=0.3,0.1
English Units
Geom File=g01
Flow File=f01
Plan File=p01
BEGIN DESCRIPTION:
UNT 114 in HW
END DESCRIPTION:

--- UNT 114 in HW.p01 (plan) ---

Plan Title=Multiple Run
Short Identifier=Multiple
Geom File=g01
Flow File=f01
Subcritical Flow
K Sum by GR= 0
Std Step Tol= 0.01
Critical Tol= 0.01
Num of Std Step Trials= 20
Max Error Tol= 0.3
Flow Tol Ratio= 0.001
Split Flow NTrial= 30
Split Flow Tol= 0.02
Split Flow Ratio= 0.02
Log Output Level= 0
Friction Slope Method= 1
Unsteady Friction Slope Method= 2
Unsteady Bridges Friction Slope Method= 1
Parabolic Critical Depth
Global Vel Dist=  1 , 1 , 1
Global Log Level= 0
CheckData=True
Encroach Param= -1, 0, 0, 0
BEGIN DESCRIPTION:
Multiple Run
END DESCRIPTION:

--- UNT 114 in HW.f01 (steady flow) ---

Flow Title=Multiple
Number of Profiles=7
Profile Names=10-year,25-year,50-year,1pct_min,100-year,1pct_plu,500-year
River Rch & RM= UNT 114 in HW,Reach-1,3668
     234     309     367     217     433     863     601
Boundary for River Rch & Prof#=UNT 114 in HW,Reach-1,1
Up Type=0
Dn Type=3
Dn Slope=0.005
Boundary for River Rch & Prof#=UNT 114 in HW,Reach-1,2
Up Type=0
Dn Type=3
Dn Slope=0.005
Boundary for River Rch & Prof#=UNT 114 in HW,Reach-1,3
Up Type=0
Dn Type=3
Dn Slope=0.005
Boundary for River Rch & Prof#=UNT 114 in HW,Reach-1,4
Up Type=0
Dn Type=3
Dn Slope=0.005
Boundary for River Rch & Prof#=UNT 114 in HW,Reach-1,5
Up Type=0
Dn Type=3
Dn Slope=0.005
Boundary for River Rch & Prof#=UNT 114 in HW,Reach-1,6
Up Type=0
Dn Type=3
Dn Slope=0.005
Boundary for River Rch & Prof#=UNT 114 in HW,Reach-1,7
Up Type=0
Dn Type=3
Dn Slope=0.005

--- UNT 114 in HW.g01 (geometry) ---

Geom Title=Existing Conditions

River Reach=UNT 114 in HW,Reach-1
Reach XY= 30
      2008795.80     13588569.54      2008669.81     13588652.12
      2008625.54     13588646.91      2008330.80     13588434.54
      2008130.80     13588264.54      2008050.80     13588214.54
      2007970.80     13588214.54      2007930.80     13588194.54
      2007870.80     13588134.54      2007840.80     13588134.54
      2007800.80     13588094.54      2007230.80     13588074.54
      2006960.80     13587804.54      2006910.80     13587774.54
      2006910.80     13587754.54      2006723.98     13587563.36
      2006589.95     13587380.72      2006503.84     13587361.97
      2006455.92     13587334.19      2006462.17     13587293.22
      2006513.39     13587225.16      2006486.26     13586948.47
      2006381.01     13586689.14      2006337.61     13586626.21
      2006161.83     13586584.97      2006108.66     13586642.48
      2006041.38     13586656.59      2005942.64     13586640.31
      2005871.03     13586659.84      2005770.80     13586734.54

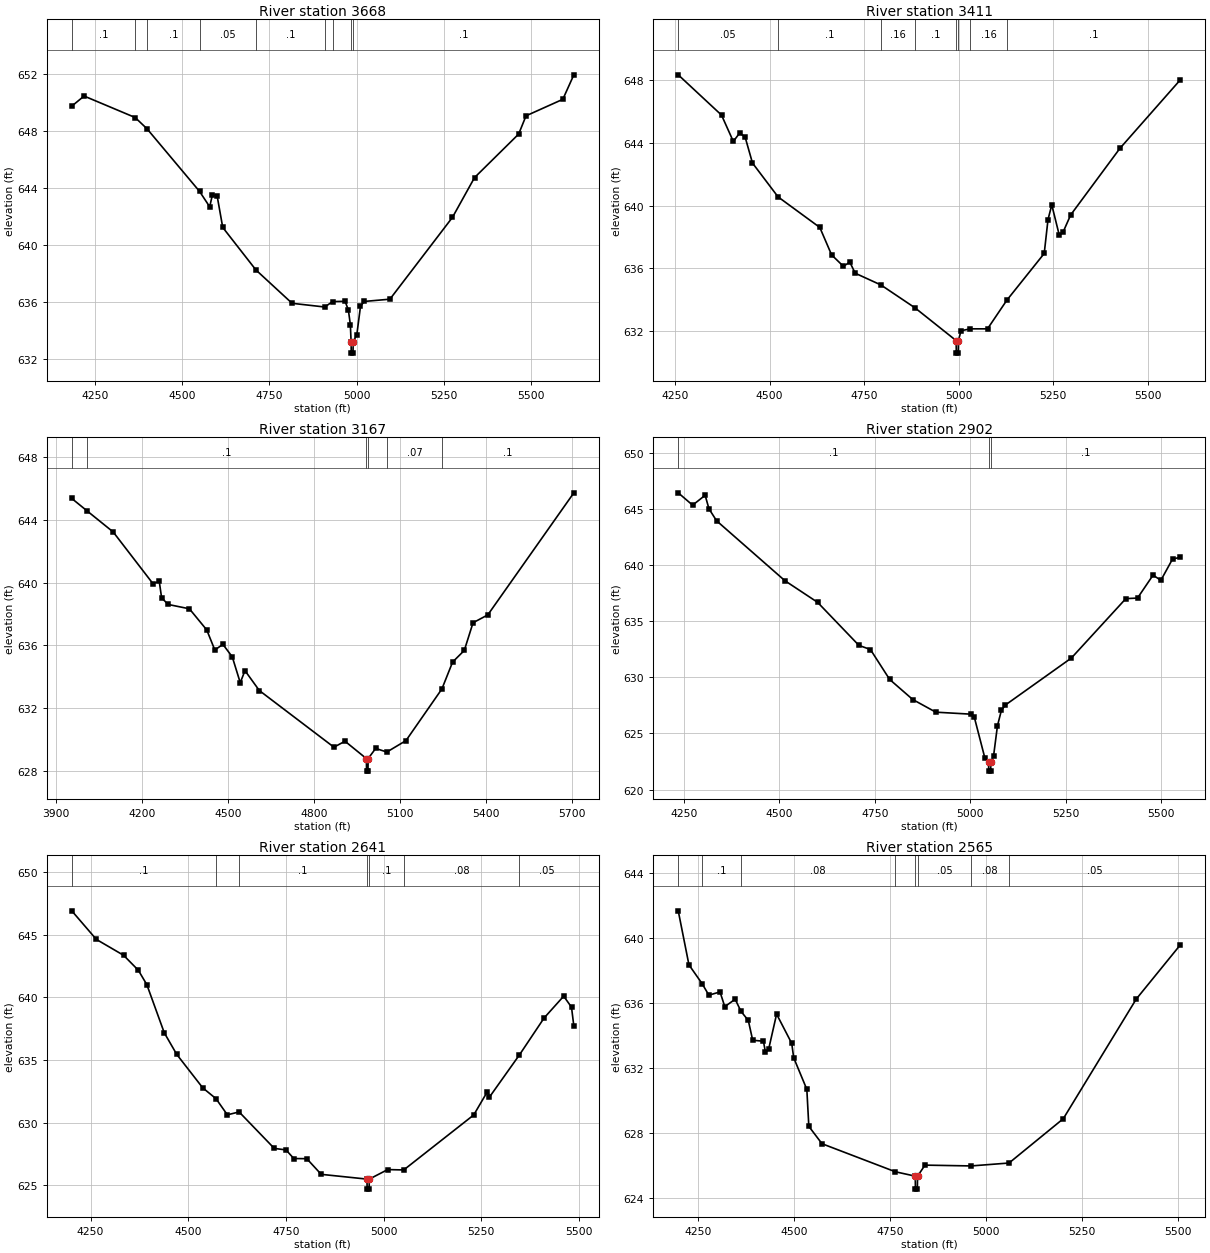
Type RM Length L Ch R = 1,3668,257,257,257
BEGIN DESCRIPTION:
UNT 114 in HW 7.0
END DESCRIPTION:
XS GIS Cut Line= 3
      2008975.02     13587974.99      2008275.00     13588375.00
      2008075.00     13588975.00
#Sta/Elev= 30
  4183.7  649.75  4219.0  650.46  4365.4  648.95  4399.3  648.16  4549.9  643.76
  4578.9  642.68  4586.8  643.53  4600.5  643.41  4616.3  641.23  4711.5  638.24
  4815.0  635.90  4908.6  635.64  4931.0  636.02  4966.9  636.04  4976.3  635.43
  4982.0  634.40  4984.1  633.20  4984.6  632.40  4989.6  632.40  4990.1  633.20
  5000.5  633.69  5011.0  635.68  5021.6  636.03  5095.4  636.19  5274.6  641.94
  5337.8  644.73  5464.3  647.79  5485.4  649.07  5590.8  650.23  5622.4  651.95
#Mann=9,-1,0
  4183.7     0.1       0  4365.4    0.05       0  4399.3     0.1       0
  4549.9    0.05       0  4711.5     0.1       0  4908.6    0.16       0
  4931.0     0.1       0  4984.1    0.07       0  4990.1     0.1       0
Bank Sta=4984.1,4990.1
Exp/Cntr=0.3,0.1

Type RM Length L Ch R = 1,3411,244,244,244
BEGIN DESCRIPTION:
UNT 114 in HW 6.0
END DESCRIPTION:
XS GIS Cut Line= 3
      2008775.05     13588024.99      2008075.00     13588225.00
      2008075.00     13588825.04
#Sta/Elev= 30
  4258.2  648.34  4372.7  645.77  4403.9  644.09  4420.8  644.63  4435.1  644.37
  4454.6  642.71  4522.3  640.55  4632.7  638.60  4663.9  636.85  4695.1  636.12
  4712.0  636.39  4726.3  635.68  4794.4  634.93  4884.5  633.47  4993.3  631.38
  4993.8  630.58  4998.8  630.58  4999.3  631.38  5006.3  632.01  5031.2  632.13
  5076.3  632.13  5127.5  633.96  5226.3  636.94  5236.3  639.10  5246.3  640.04
  5266.3  638.09  5276.3  638.31  5296.3  639.40  5426.3  643.64  5586.3  648.02
#Mann=8,-1,0
  4258.2    0.05       0  4522.3     0.1       0  4794.4    0.16       0
  4884.5     0.1       0  4993.3    0.07       0  4999.3     0.1       0
  5031.2    0.16       0  5127.5     0.1       0
Bank Sta=4993.3,4999.3
Exp/Cntr=0.3,0.1

Type RM Length L Ch R = 1,3167,265,265,265
BEGIN DESCRIPTION:
UNT 114 in HW 5.0
END DESCRIPTION:
XS GIS Cut Line= 3
      2008348.69     13587206.55      2007875.00     13588125.00
      2007744.66     13588830.76
#Sta/Elev= 30
  3954.8  645.38  4007.9  644.59  4099.2  643.24  4237.8  639.94  4259.9  640.08
  4268.1  639.04  4290.6  638.61  4365.1  638.33  4425.6  636.98  4453.7  635.70
  4481.9  636.06  4514.6  635.26  4542.4  633.61  4558.9  634.38  4608.9  633.11
  4869.1  629.49  4907.8  629.87  4982.4  628.76  4982.9  627.96  4987.9  627.96
  4988.4  628.76  5014.7  629.41  5053.7  629.18  5120.4  629.91  5245.7  633.21
  5283.1  634.93  5323.8  635.67  5354.3  637.44  5405.7  637.94  5705.9  645.74
#Mann=6,-1,0
  3954.8    0.05       0  4007.9     0.1       0  4982.4    0.07       0
  4988.4     0.1       0  5053.7    0.07       0  5245.7     0.1       0
Bank Sta=4982.4,4988.4
Exp/Cntr=0.3,0.1

Type RM Length L Ch R = 1,2902,261,261,261
BEGIN DESCRIPTION:
UNT 114 in HW 4.0
END DESCRIPTION:
XS GIS Cut Line= 3
      2007724.99     13587325.05      2007625.00     13588125.00
      2007525.00     13588625.02
#Sta/Elev= 30
  4234.6  646.47  4272.3  645.37  4305.1  646.25  4315.2  645.04  4335.3  643.97
  4514.2  638.63  4599.9  636.70  4708.2  632.86  4738.4  632.49  4788.8  629.82
  4849.3  628.03  4909.8  626.90  5003.0  626.72  5010.5  626.48  5038.3  622.82
  5048.0  622.44  5048.5  621.64  5053.5  621.64  5054.0  622.44  5061.2  623.00
  5071.4  625.69  5081.6  627.05  5091.8  627.53  5265.1  631.73  5407.9  637.03
  5438.5  637.08  5479.3  639.13  5499.7  638.66  5530.3  640.56  5550.7  640.72
#Mann=3,-1,0
  4234.6     0.1       0  5048.0    0.07       0  5054.0     0.1       0
Bank Sta=5048,5054
Exp/Cntr=0.3,0.1

Type RM Length L Ch R = 1,2641,76,76,76
BEGIN DESCRIPTION:
UNT 114 in HW 3.0
END DESCRIPTION:
XS GIS Cut Line= 3
      2007504.13     13587319.37      2007350.50     13587665.70
      2007389.52     13588570.99
#Sta/Elev= 30
  4201.9  646.90  4264.8  644.62  4334.6  643.35  4372.2  642.16  4394.0  641.01
  4438.6  637.17  4470.6  635.44  4537.2  632.77  4571.0  631.91  4600.1  630.62
  4630.2  630.85  4720.2  627.94  4750.2  627.82  4770.2  627.13  4803.4  627.12
  4840.3  625.87  4957.4  625.49  4957.9  624.69  4962.9  624.69  4963.4  625.49
  5010.5  626.25  5051.5  626.22  5230.7  630.61  5265.8  632.48  5270.8  632.03
  5347.8  635.41  5410.8  638.35  5460.9  640.09  5480.9  639.21  5486.9  637.70
#Mann=7,-1,0
  4201.9     0.1       0  4571.0    0.08       0  4630.2     0.1       0
  4957.4    0.07       0  4963.4     0.1       0  5051.5    0.08       0
  5347.8    0.05       0
Bank Sta=4957.4,4963.4
Exp/Cntr=0.3,0.1

Type RM Length L Ch R = 1,2565,385,385,385
BEGIN DESCRIPTION:
UNT 114 in HW 2.0
END DESCRIPTION:
XS GIS Cut Line= 3
      2007399.98     13587288.09      2007282.79     13587709.98
      2007316.64     13588579.76
#Sta/Elev= 30
  4197.3  641.69  4225.2  638.36  4259.5  637.20  4277.1  636.49  4306.2  636.69
  4318.6  635.78  4345.6  636.24  4360.9  635.49  4379.9  634.93  4391.3  633.71
  4419.3  633.65  4424.5  632.98  4432.8  633.15  4453.6  635.32  4493.0  633.52
  4498.2  632.63  4532.4  630.68  4537.6  628.40  4571.9  627.33  4763.1  625.60
  4814.9  625.33  4815.4  624.53  4820.4  624.53  4820.9  625.33  4840.3  626.01
  4960.5  625.96  5059.3  626.14  5200.6  628.87  5390.8  636.25  5505.6  639.59
#Mann=8,-1,0
  4197.3    0.08       0  4259.5     0.1       0  4360.9    0.08       0
  4763.1    0.05       0  4814.9    0.07       0  4820.9    0.05       0
  4960.5    0.08       0  5059.3    0.05       0
Bank Sta=4814.9,4820.9
Exp/Cntr=0.3,0.1

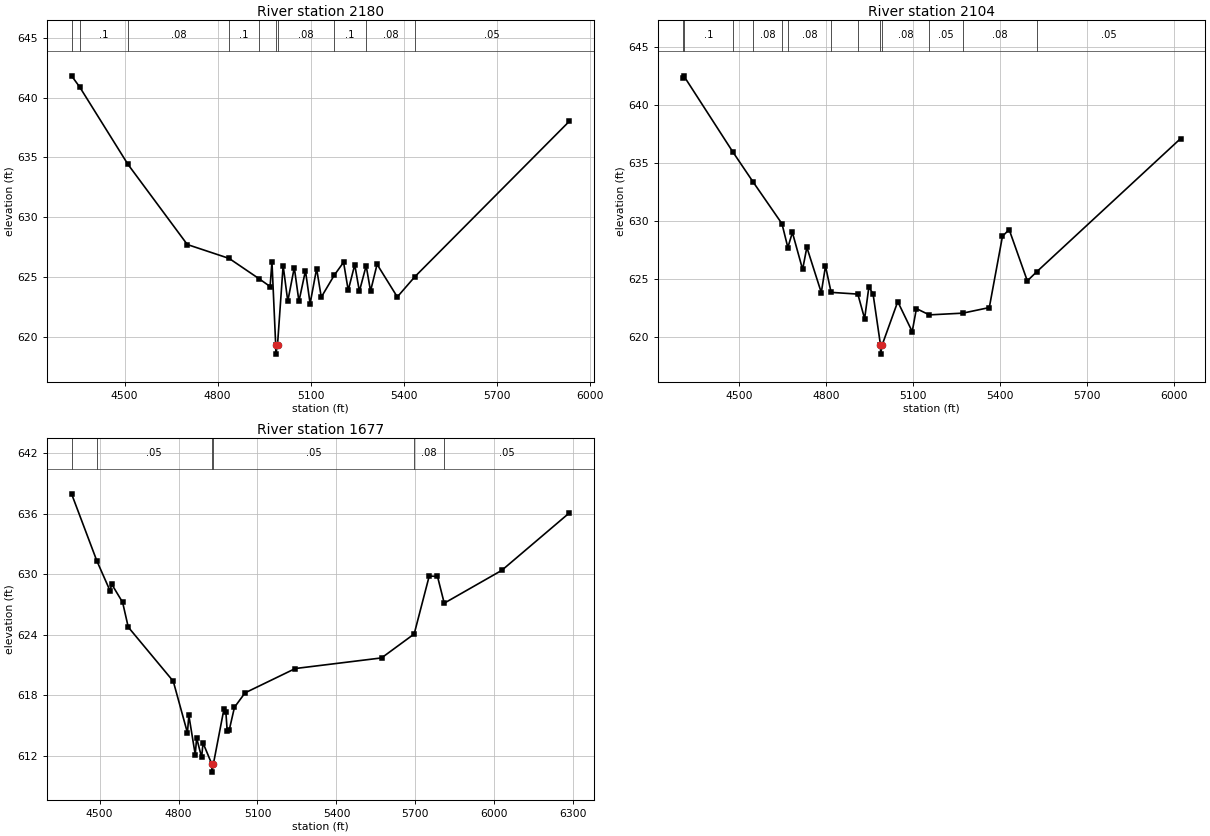
Type RM Length L Ch R = 1,2180,76,76,76
BEGIN DESCRIPTION:
Mapping XS 538c09ca
END DESCRIPTION:
XS GIS Cut Line= 3
      2007379.91     13587292.55      2006811.35     13588136.71
      2006980.17     13588699.45
#Sta/Elev= 30
  4329.2  641.81  4355.6  640.87  4510.9  634.43  4702.4  627.74  4837.4  626.58
  4933.0  624.90  4969.3  624.24  4975.3  626.30  4987.3  619.40  4987.8  618.60
  4993.3  619.40  5011.3  625.99  5026.3  623.01  5047.3  625.82  5062.3  623.00
  5083.3  625.56  5098.3  622.81  5119.3  625.73  5134.3  623.35  5176.4  625.19
  5206.2  626.26  5221.2  623.92  5242.2  626.06  5257.2  623.84  5279.0  625.97
  5293.2  623.86  5314.2  626.09  5379.4  623.37  5435.8  625.05  5934.5  638.03
#Mann=10,-1,0
  4329.2    0.08       0  4355.6     0.1       0  4510.9    0.08       0
  4837.4     0.1       0  4933.0    0.08       0  4987.3    0.07       0
  4993.3    0.08       0  5176.4     0.1       0  5279.0    0.08       0
  5435.8    0.05       0
Bank Sta=4987.3,4993.3
Exp/Cntr=0.3,0.1

Type RM Length L Ch R = 1,2104,427,427,427
BEGIN DESCRIPTION:
Mapping XS 252c4c63
END DESCRIPTION:
XS GIS Cut Line= 3
      2007369.48     13587248.29      2006728.88     13588092.01
      2006942.42     13588716.99
#Sta/Elev= 30
  4304.2  642.32  4308.1  642.49  4477.8  635.93  4546.8  633.38  4647.4  629.75
  4667.7  627.70  4683.4  629.00  4718.7  625.81  4733.3  627.72  4783.2  623.82
  4797.7  626.10  4817.1  623.84  4909.4  623.69  4932.9  621.57  4947.5  624.30
  4962.0  623.71  4987.6  619.32  4988.1  618.52  4993.6  619.32  5047.3  623.04
  5097.2  620.46  5111.8  622.44  5156.4  621.90  5272.0  622.05  5363.5  622.53
  5409.0  628.67  5432.1  629.25  5494.8  624.83  5527.6  625.62  6024.0  637.08
#Mann=13,-1,0
  4304.2    0.08       0  4308.1     0.1       0  4477.8    0.05       0
  4546.8    0.08       0  4647.4     0.1       0  4667.7    0.08       0
  4817.1    0.05       0  4909.4    0.08       0  4987.6    0.07       0
  4993.6    0.08       0  5156.4    0.05       0  5272.0    0.08       0
  5527.6    0.05       0
Bank Sta=4987.6,4993.6
Exp/Cntr=0.3,0.1

Type RM Length L Ch R = 1,1677,0,0,0
BEGIN DESCRIPTION:
UNT 114 in HW 1.0
END DESCRIPTION:
XS GIS Cut Line= 4
      2007175.00     13587225.00      2006675.00     13587425.00
      2006613.17     13588043.32      2006901.70     13588715.81
#Sta/Elev= 30
  4393.6  637.95  4489.5  631.32  4540.3  628.32  4545.7  629.02  4587.5  627.21
  4609.0  624.75  4780.0  619.39  4833.8  614.29  4839.2  616.01  4863.5  612.12
  4868.8  613.77  4887.7  611.85  4893.1  613.28  4926.4  611.19  4926.9  610.39
  4932.4  611.19  4972.3  616.60  4979.9  616.32  4984.9  614.48  4992.4  614.53
  5012.5  616.81  5052.7  618.24  5243.7  620.65  5571.3  621.70  5695.3  624.07
  5752.5  629.81  5783.9  629.77  5809.5  627.12  6028.0  630.37  6285.3  636.07
#Mann=6,-1,0
  4393.6     0.1       0  4489.5    0.05       0  4926.4   0.035       0
  4932.4    0.05       0  5695.3    0.08       0  5809.5    0.05       0
Bank Sta=4926.4,4932.4
Exp/Cntr=0.3,0.1

Chan Stop Cuts=-1