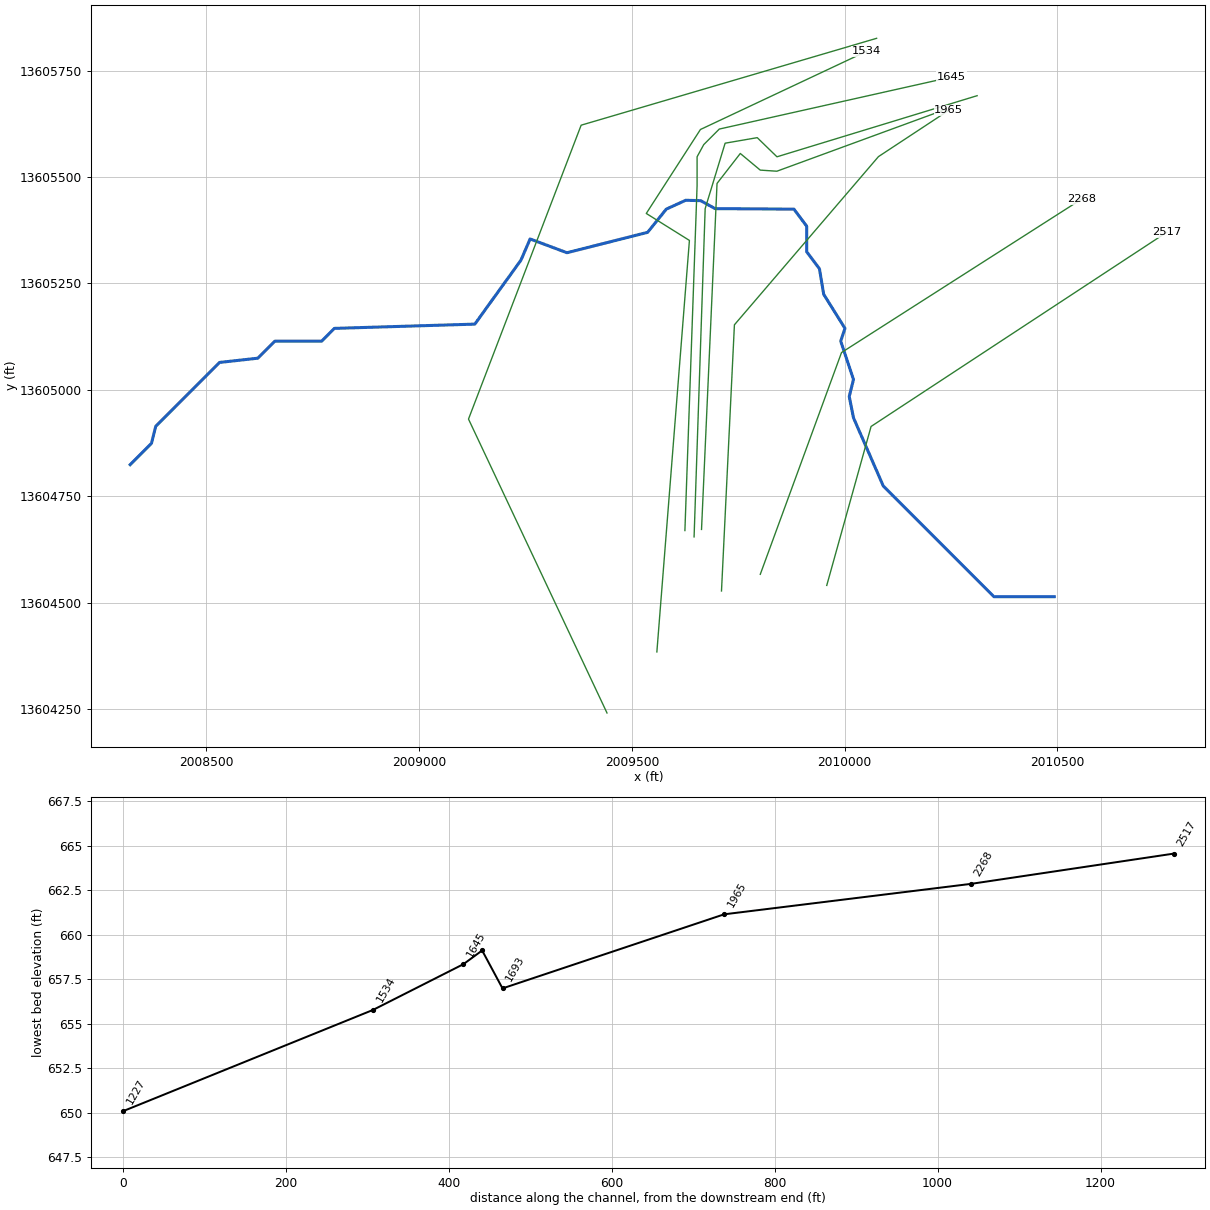
--- UNT 115 in HW.prj (project) ---

Proj Title=UNT 115 in HW Base Level Engineering
Current Plan=p01
Default Exp/Contr=0.3,0.1
English Units
Geom File=g01
Flow File=f01
Plan File=p01
BEGIN DESCRIPTION:
UNT 115 in HW
END DESCRIPTION:

--- UNT 115 in HW.p01 (plan) ---

Plan Title=Multiple Run
Short Identifier=Multiple
Geom File=g01
Flow File=f01
Subcritical Flow
K Sum by GR= 0
Std Step Tol= 0.01
Critical Tol= 0.01
Num of Std Step Trials= 20
Max Error Tol= 0.3
Flow Tol Ratio= 0.001
Split Flow NTrial= 30
Split Flow Tol= 0.02
Split Flow Ratio= 0.02
Log Output Level= 0
Friction Slope Method= 1
Unsteady Friction Slope Method= 2
Unsteady Bridges Friction Slope Method= 1
Parabolic Critical Depth
Global Vel Dist=  1 , 1 , 1
Global Log Level= 0
CheckData=True
Encroach Param= -1, 0, 0, 0
BEGIN DESCRIPTION:
Multiple Run
END DESCRIPTION:

--- UNT 115 in HW.f01 (steady flow) ---

Flow Title=Multiple
Number of Profiles=7
Profile Names=10-year,25-year,50-year,1pct_min,100-year,1pct_plu,500-year
River Rch & RM= UNT 115 in HW,Reach-1,2517
     339     464     565     342     682    1361     996
Boundary for River Rch & Prof#=UNT 115 in HW,Reach-1,1
Up Type=0
Dn Type=3
Dn Slope=0.005
Boundary for River Rch & Prof#=UNT 115 in HW,Reach-1,2
Up Type=0
Dn Type=3
Dn Slope=0.005
Boundary for River Rch & Prof#=UNT 115 in HW,Reach-1,3
Up Type=0
Dn Type=3
Dn Slope=0.005
Boundary for River Rch & Prof#=UNT 115 in HW,Reach-1,4
Up Type=0
Dn Type=3
Dn Slope=0.005
Boundary for River Rch & Prof#=UNT 115 in HW,Reach-1,5
Up Type=0
Dn Type=3
Dn Slope=0.005
Boundary for River Rch & Prof#=UNT 115 in HW,Reach-1,6
Up Type=0
Dn Type=3
Dn Slope=0.005
Boundary for River Rch & Prof#=UNT 115 in HW,Reach-1,7
Up Type=0
Dn Type=3
Dn Slope=0.005

--- UNT 115 in HW.g01 (geometry) ---

Geom Title=Existing Conditions

River Reach=UNT 115 in HW,Reach-1
Reach XY= 30
      2010492.59     13604514.54      2010350.80     13604514.54
      2010090.80     13604774.54      2010020.80     13604934.54
      2010010.80     13604984.54      2010020.80     13605024.54
      2009990.80     13605114.54      2010000.80     13605144.54
      2009950.80     13605224.54      2009940.80     13605284.54
      2009910.80     13605324.54      2009910.80     13605384.54
      2009880.80     13605424.54      2009695.59     13605425.75
      2009661.57     13605444.50      2009626.41     13605445.37
      2009580.80     13605424.54      2009536.97     13605370.09
      2009347.39     13605322.18      2009260.80     13605354.54
      2009239.05     13605304.47      2009130.80     13605154.54
      2008800.80     13605144.54      2008770.80     13605114.54
      2008660.80     13605114.54      2008620.80     13605074.54
      2008530.80     13605064.54      2008380.80     13604914.54
      2008370.80     13604874.54      2008320.80     13604824.54

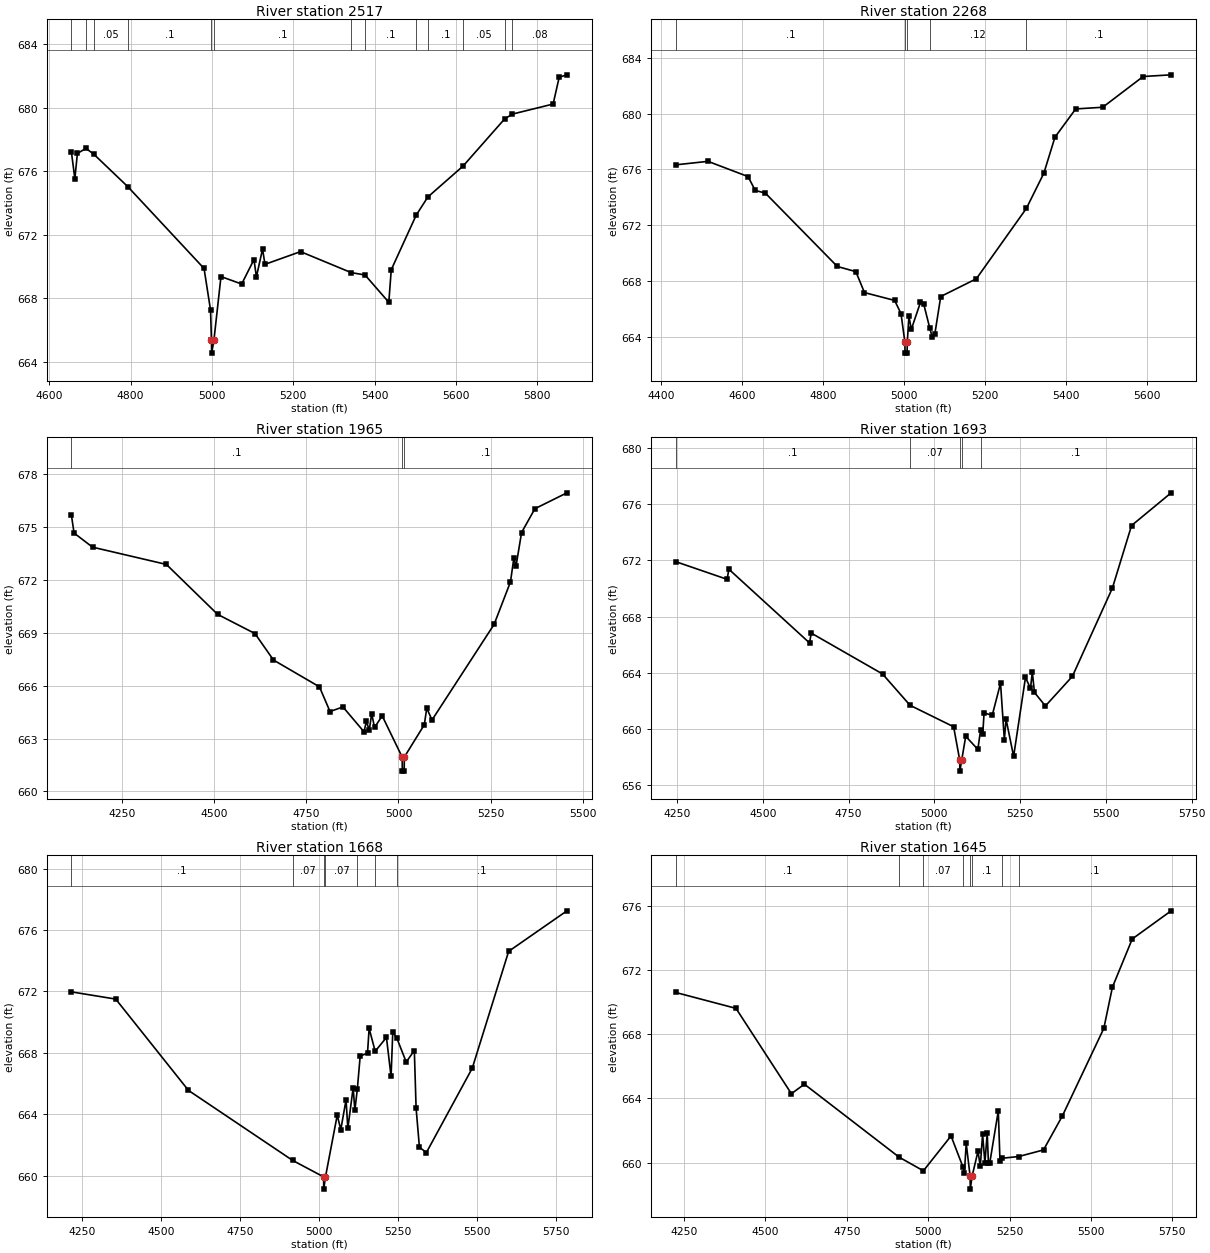
Type RM Length L Ch R = 1,2517,249,249,249
BEGIN DESCRIPTION:
UNT 115 in HW 5.0
END DESCRIPTION:
XS GIS Cut Line= 3
      2009957.98     13604540.98      2010062.14     13604914.22
      2010756.56     13605369.93
#Sta/Elev= 30
  4654.7  677.20  4663.1  675.54  4669.3  677.13  4690.4  677.45  4709.8  677.08
  4793.6  675.03  4980.7  669.89  4996.7  667.26  4998.9  665.36  4999.4  664.56
  5004.9  665.36  5022.3  669.38  5073.2  668.91  5103.4  670.45  5109.4  669.36
  5124.5  671.11  5130.5  670.15  5217.9  670.95  5342.3  669.63  5376.4  669.48
  5434.9  667.76  5440.9  669.81  5502.3  673.25  5530.9  674.39  5617.6  676.34
  5719.5  679.30  5738.9  679.61  5838.8  680.24  5853.8  681.93  5872.8  682.08
#Mann=13,-1,0
  4654.7    0.05       0  4690.4     0.1       0  4709.8    0.05       0
  4793.6     0.1       0  4998.9    0.07       0  5004.9     0.1       0
  5342.3    0.12       0  5376.4     0.1       0  5502.3    0.05       0
  5530.9     0.1       0  5617.6    0.05       0  5719.5     0.1       0
  5738.9    0.08       0
Bank Sta=4998.9,5004.9
Exp/Cntr=0.3,0.1

Type RM Length L Ch R = 1,2268,303,303,303
BEGIN DESCRIPTION:
UNT 115 in HW 4.0
END DESCRIPTION:
XS GIS Cut Line= 3
      2009801.74     13604567.05      2009992.70     13605087.84
      2010556.92     13605448.07
#Sta/Elev= 30
  4435.7  676.33  4515.6  676.58  4614.6  675.49  4632.3  674.50  4657.2  674.31
  4835.1  669.06  4880.9  668.69  4902.2  667.19  4976.7  666.63  4992.4  665.69
  5002.0  663.66  5002.5  662.86  5007.5  662.86  5008.0  663.66  5012.0  665.50
  5017.9  664.56  5040.6  666.50  5048.3  666.40  5063.7  664.63  5069.5  664.01
  5076.2  664.26  5090.6  666.91  5178.6  668.18  5302.1  673.21  5345.3  675.73
  5372.8  678.31  5424.0  680.33  5490.8  680.45  5590.7  682.65  5659.8  682.77
#Mann=5,-1,0
  4435.7     0.1       0  5002.0    0.07       0  5008.0     0.1       0
  5063.7    0.12       0  5302.1     0.1       0
Bank Sta=5002,5008
Exp/Cntr=0.3,0.1

Type RM Length L Ch R = 1,1965,272,272,272
BEGIN DESCRIPTION:
UNT 115 in HW 3.0
END DESCRIPTION:
XS GIS Cut Line= 4
      2009710.58     13604527.94      2009740.96     13605152.94
      2010079.51     13605547.90      2010244.47     13605656.44
#Sta/Elev= 30
  4113.3  675.65  4120.4  674.65  4170.4  673.85  4370.7  672.87  4509.5  670.04
  4610.9  668.95  4661.0  667.45  4785.7  665.93  4814.3  664.53  4849.4  664.79
  4906.5  663.38  4913.1  663.98  4920.7  663.46  4927.3  664.41  4935.0  663.63
  4955.9  664.28  5009.9  661.95  5010.4  661.15  5015.4  661.15  5015.9  661.95
  5070.0  663.78  5076.6  664.72  5090.9  664.05  5259.2  669.47  5303.6  671.88
  5312.7  673.22  5318.7  672.78  5333.7  674.68  5369.9  676.03  5456.7  676.93
#Mann=3,-1,0
  4113.3     0.1       0  5009.9    0.07       0  5015.9     0.1       0
Bank Sta=5009.9,5015.9
Exp/Cntr=0.3,0.1

Type RM Length L Ch R = 1,1693,25,25,25
BEGIN DESCRIPTION:
Mapping XS 714a8d79
END DESCRIPTION:
XS GIS Cut Line= 6
      2009663.65     13604672.44      2009700.11     13605484.95
      2009754.79     13605555.27      2009801.67     13605516.20
      2009840.73     13605513.60      2010239.13     13605659.42
#Sta/Elev= 30
  4245.8  671.91  4395.9  670.65  4400.9  671.37  4636.1  666.12  4641.1  666.82
  4848.9  663.91  4929.0  661.68  5056.1  660.15  5073.8  657.79  5074.3  656.99
  5079.8  657.79  5091.4  659.47  5126.7  658.54  5134.8  659.93  5141.1  659.65
  5144.9  661.14  5168.6  660.96  5192.9  663.25  5204.0  659.22  5209.0  660.69
  5231.0  658.04  5265.6  663.66  5280.2  662.88  5285.5  664.04  5291.8  662.59
  5323.7  661.63  5402.3  663.74  5519.0  670.03  5574.8  674.48  5690.2  676.81
#Mann=5,-1,0
  4245.8     0.1       0  4929.0    0.07       0  5073.8    0.07       0
  5079.8    0.07       0  5134.8     0.1       0
Bank Sta=5073.8,5079.8
Exp/Cntr=0.3,0.1

Type RM Length L Ch R = 1,1668,23,23,23
BEGIN DESCRIPTION:
Mapping XS 9c1fc29c
END DESCRIPTION:
XS GIS Cut Line= 6
      2009646.17     13604654.94      2009672.21     13605425.75
      2009719.09     13605579.40      2009794.61     13605592.42
      2009840.95     13605547.45      2010311.43     13605690.95
#Sta/Elev= 30
  4216.5  671.97  4356.6  671.50  4586.8  665.55  4916.3  660.99  5014.2  659.92
  5014.7  659.12  5020.2  659.92  5057.4  663.94  5068.6  662.99  5085.3  664.94
  5090.9  663.07  5107.7  665.72  5113.2  664.26  5121.0  665.65  5130.0  667.78
  5153.2  667.99  5158.3  669.59  5177.4  668.10  5213.1  669.00  5227.7  666.46
  5233.1  669.35  5245.5  668.98  5275.6  667.40  5301.3  668.15  5306.9  664.39
  5317.4  661.85  5339.4  661.50  5484.6  667.00  5599.7  674.61  5784.1  677.25
#Mann=7,-1,0
  4216.5     0.1       0  4916.3    0.07       0  5014.2    0.07       0
  5020.2    0.07       0  5121.0     0.1       0  5177.4    0.07       0
  5245.5     0.1       0
Bank Sta=5014.2,5020.2
Exp/Cntr=0.3,0.1

Type RM Length L Ch R = 1,1645,111,111,111
BEGIN DESCRIPTION:
Mapping XS bd008aa9
END DESCRIPTION:
XS GIS Cut Line= 6
      2009624.59     13604669.82      2009653.23     13605479.74
      2009653.23     13605547.45      2009668.86     13605576.10
      2009705.32     13605612.56      2010251.07     13605734.71
#Sta/Elev= 30
  4224.6  670.59  4409.9  669.60  4580.0  664.29  4620.0  664.88  4910.8  660.34
  4985.4  659.49  5070.3  661.66  5106.7  659.74  5111.3  659.37  5116.9  661.19
  5128.9  659.15  5129.4  658.35  5134.9  659.15  5153.1  660.71  5160.1  659.76
  5167.2  661.76  5174.3  659.99  5181.4  661.83  5185.1  659.99  5189.3  659.99
  5215.4  663.22  5220.6  660.11  5226.6  660.27  5278.3  660.38  5354.3  660.79
  5412.3  662.91  5539.4  668.35  5565.9  670.92  5626.8  673.92  5746.2  675.67
#Mann=8,-1,0
  4224.6     0.1       0  4910.8    0.12       0  4985.4    0.07       0
  5106.7     0.1       0  5128.9    0.07       0  5134.9     0.1       0
  5226.6    0.07       0  5278.3     0.1       0
Bank Sta=5128.9,5134.9
Exp/Cntr=0.3,0.1

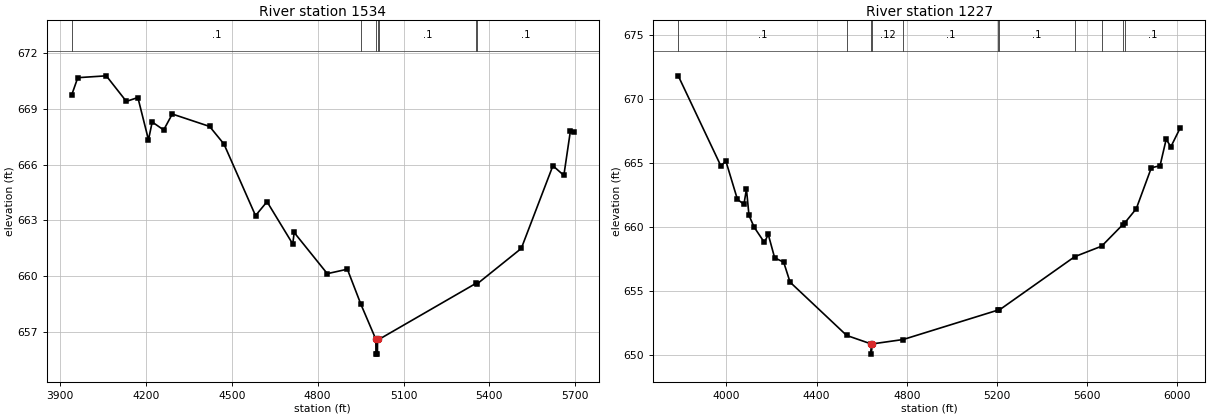
Type RM Length L Ch R = 1,1534,307,307,307
BEGIN DESCRIPTION:
UNT 115 in HW 2.0
END DESCRIPTION:
XS GIS Cut Line= 5
      2009558.68     13604384.76      2009635.19     13605351.08
      2009533.80     13605414.41      2009661.10     13605611.58
      2010051.25     13605795.00
#Sta/Elev= 30
  3940.6  669.77  3961.6  670.69  4061.2  670.79  4131.4  669.41  4171.6  669.62
  4208.7  667.34  4221.7  668.30  4261.8  667.87  4291.9  668.73  4422.3  668.06
  4472.5  667.11  4582.8  663.25  4623.0  664.00  4712.9  661.72  4717.9  662.34
  4833.6  660.12  4903.8  660.36  4951.0  658.47  5003.3  656.58  5003.8  655.78
  5008.8  655.78  5009.3  656.58  5015.8  656.59  5354.7  659.61  5357.5  659.57
  5511.6  661.48  5622.1  665.94  5660.4  665.42  5683.2  667.81  5695.3  667.75
#Mann=7,-1,0
  3940.6     0.1       0  4951.0    0.12       0  5003.3    0.07       0
  5009.3    0.12       0  5015.8     0.1       0  5354.7    0.07       0
  5357.5     0.1       0
Bank Sta=5003.3,5009.3
Exp/Cntr=0.3,0.1

Type RM Length L Ch R = 1,1227,0,0,0
BEGIN DESCRIPTION:
UNT 115 in HW 1.0
END DESCRIPTION:
XS GIS Cut Line= 4
      2009441.47     13604241.52      2009115.96     13604931.59
      2009380.72     13605621.69      2010075.15     13605825.68
#Sta/Elev= 30
  3786.9  671.82  3975.5  664.80  3998.3  665.15  4049.4  662.17  4078.2  661.79
  4089.3  662.98  4100.5  660.93  4123.2  660.01  4168.8  658.81  4186.0  659.44
  4214.3  657.61  4254.4  657.27  4282.7  655.71  4533.6  651.55  4641.7  650.89
  4642.2  650.09  4647.7  650.89  4783.9  651.23  5203.0  653.52  5210.6  653.54
  5544.7  657.70  5664.1  658.52  5756.6  660.18  5765.7  660.32  5817.5  661.44
  5884.3  664.64  5922.9  664.80  5950.1  666.86  5971.0  666.28  6012.8  667.77
#Mann=11,-1,0
  3786.9     0.1       0  4533.6    0.12       0  4641.7    0.07       0
  4647.7    0.12       0  4783.9     0.1       0  5203.0    0.12       0
  5210.6     0.1       0  5544.7    0.07       0  5664.1     0.1       0
  5756.6    0.12       0  5765.7     0.1       0
Bank Sta=4641.7,4647.7
Exp/Cntr=0.3,0.1

Chan Stop Cuts=-1