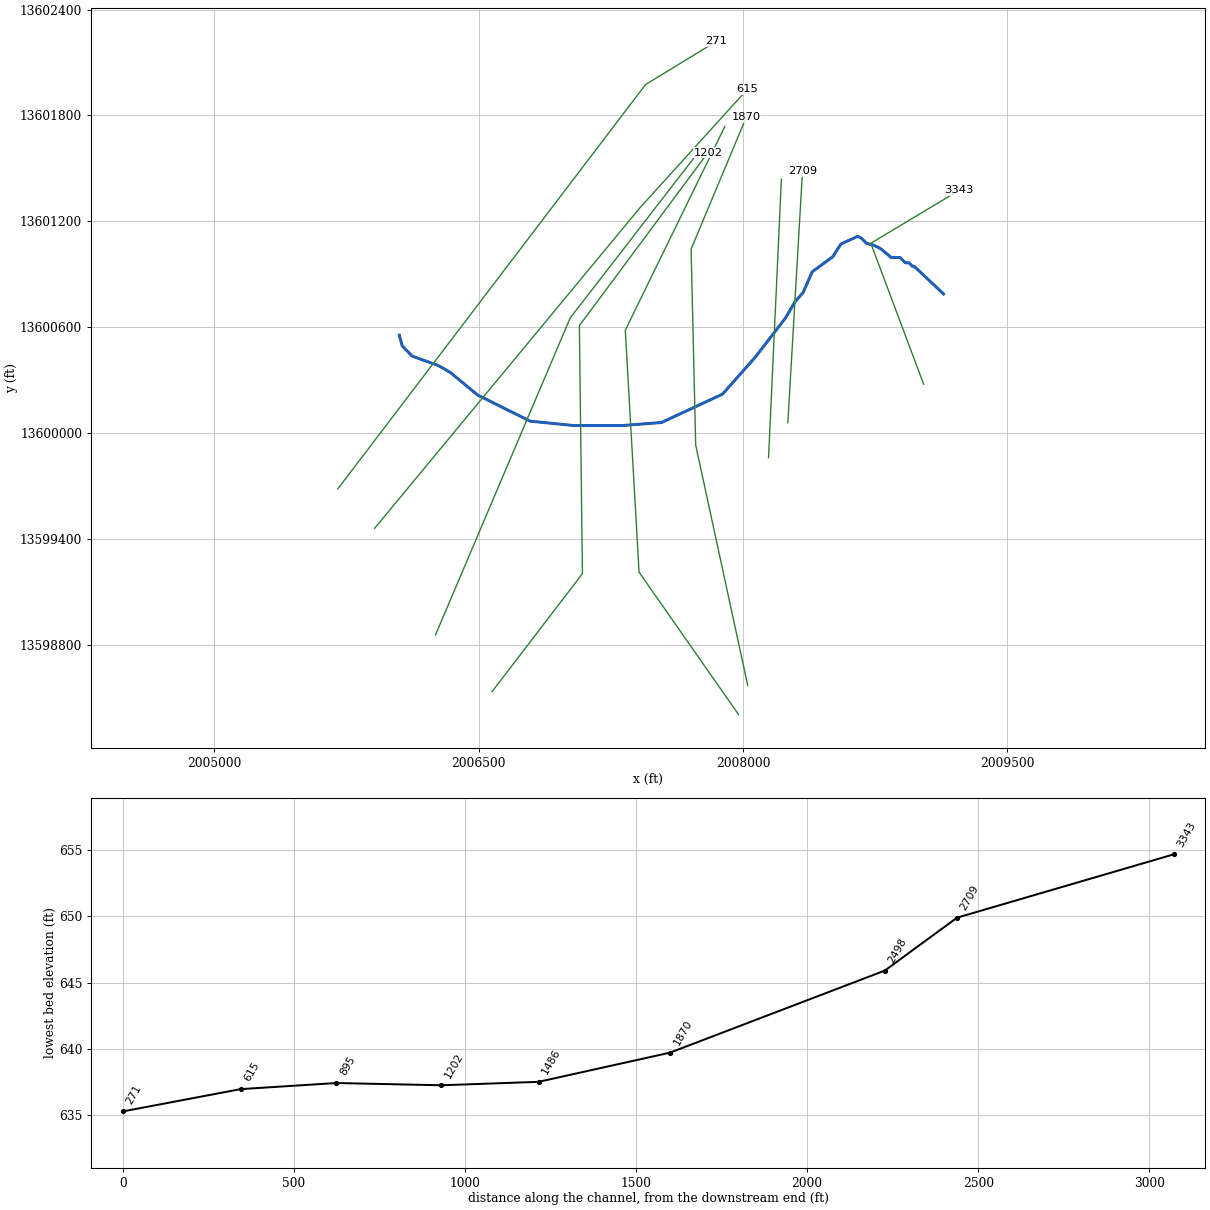
--- UNT 118 in HW.prj (project) ---

Proj Title=UNT 118 in HW Base Level Engineering
Current Plan=p01
Default Exp/Contr=0.3,0.1
English Units
Geom File=g01
Flow File=f01
Plan File=p01
BEGIN DESCRIPTION:
UNT 118 in HW
END DESCRIPTION:

--- UNT 118 in HW.p01 (plan) ---

Plan Title=Multiple Run
Short Identifier=Multiple
Geom File=g01
Flow File=f01
Subcritical Flow
K Sum by GR= 0
Std Step Tol= 0.01
Critical Tol= 0.01
Num of Std Step Trials= 20
Max Error Tol= 0.3
Flow Tol Ratio= 0.001
Split Flow NTrial= 30
Split Flow Tol= 0.02
Split Flow Ratio= 0.02
Log Output Level= 0
Friction Slope Method= 1
Unsteady Friction Slope Method= 2
Unsteady Bridges Friction Slope Method= 1
Parabolic Critical Depth
Global Vel Dist=  1 , 1 , 1
Global Log Level= 0
CheckData=True
Encroach Param= -1, 0, 0, 0
BEGIN DESCRIPTION:
Multiple Run
END DESCRIPTION:

--- UNT 118 in HW.f01 (steady flow) ---

Flow Title=Multiple
Number of Profiles=7
Profile Names=10-year,25-year,50-year,1pct_min,100-year,1pct_plu,500-year
River Rch & RM= UNT 118 in HW,Reach-1,3343
     517     725     899     552    1102    2198    1660
Boundary for River Rch & Prof#=UNT 118 in HW,Reach-1,1
Up Type=0
Dn Type=3
Dn Slope=0.005
Boundary for River Rch & Prof#=UNT 118 in HW,Reach-1,2
Up Type=0
Dn Type=3
Dn Slope=0.005
Boundary for River Rch & Prof#=UNT 118 in HW,Reach-1,3
Up Type=0
Dn Type=3
Dn Slope=0.005
Boundary for River Rch & Prof#=UNT 118 in HW,Reach-1,4
Up Type=0
Dn Type=3
Dn Slope=0.005
Boundary for River Rch & Prof#=UNT 118 in HW,Reach-1,5
Up Type=0
Dn Type=3
Dn Slope=0.005
Boundary for River Rch & Prof#=UNT 118 in HW,Reach-1,6
Up Type=0
Dn Type=3
Dn Slope=0.005
Boundary for River Rch & Prof#=UNT 118 in HW,Reach-1,7
Up Type=0
Dn Type=3
Dn Slope=0.005

--- UNT 118 in HW.g01 (geometry) ---

Geom Title=Existing Conditions

River Reach=UNT 118 in HW,Reach-1
Reach XY= 30
      2009137.47     13600787.87      2008970.80     13600944.54
      2008960.80     13600944.54      2008940.80     13600964.54
      2008920.80     13600964.54      2008890.80     13600994.54
      2008840.80     13600994.54      2008780.80     13601044.54
      2008740.80     13601064.54      2008700.80     13601074.54
      2008670.80     13601104.54      2008650.80     13601114.54
      2008555.56     13601071.21      2008508.69     13600998.29
      2008392.80     13600913.66      2008340.72     13600795.17
      2008296.45     13600745.69      2008240.46     13600650.64
      2008068.58     13600427.98      2007883.69     13600219.65
      2007537.50     13600058.94      2007317.76     13600041.89
      2007039.31     13600041.89      2006793.06     13600066.52
      2006494.83     13600215.00      2006336.84     13600345.21
      2006272.61     13600381.67      2006123.30     13600435.49
      2006067.75     13600492.78      2006050.80     13600554.54

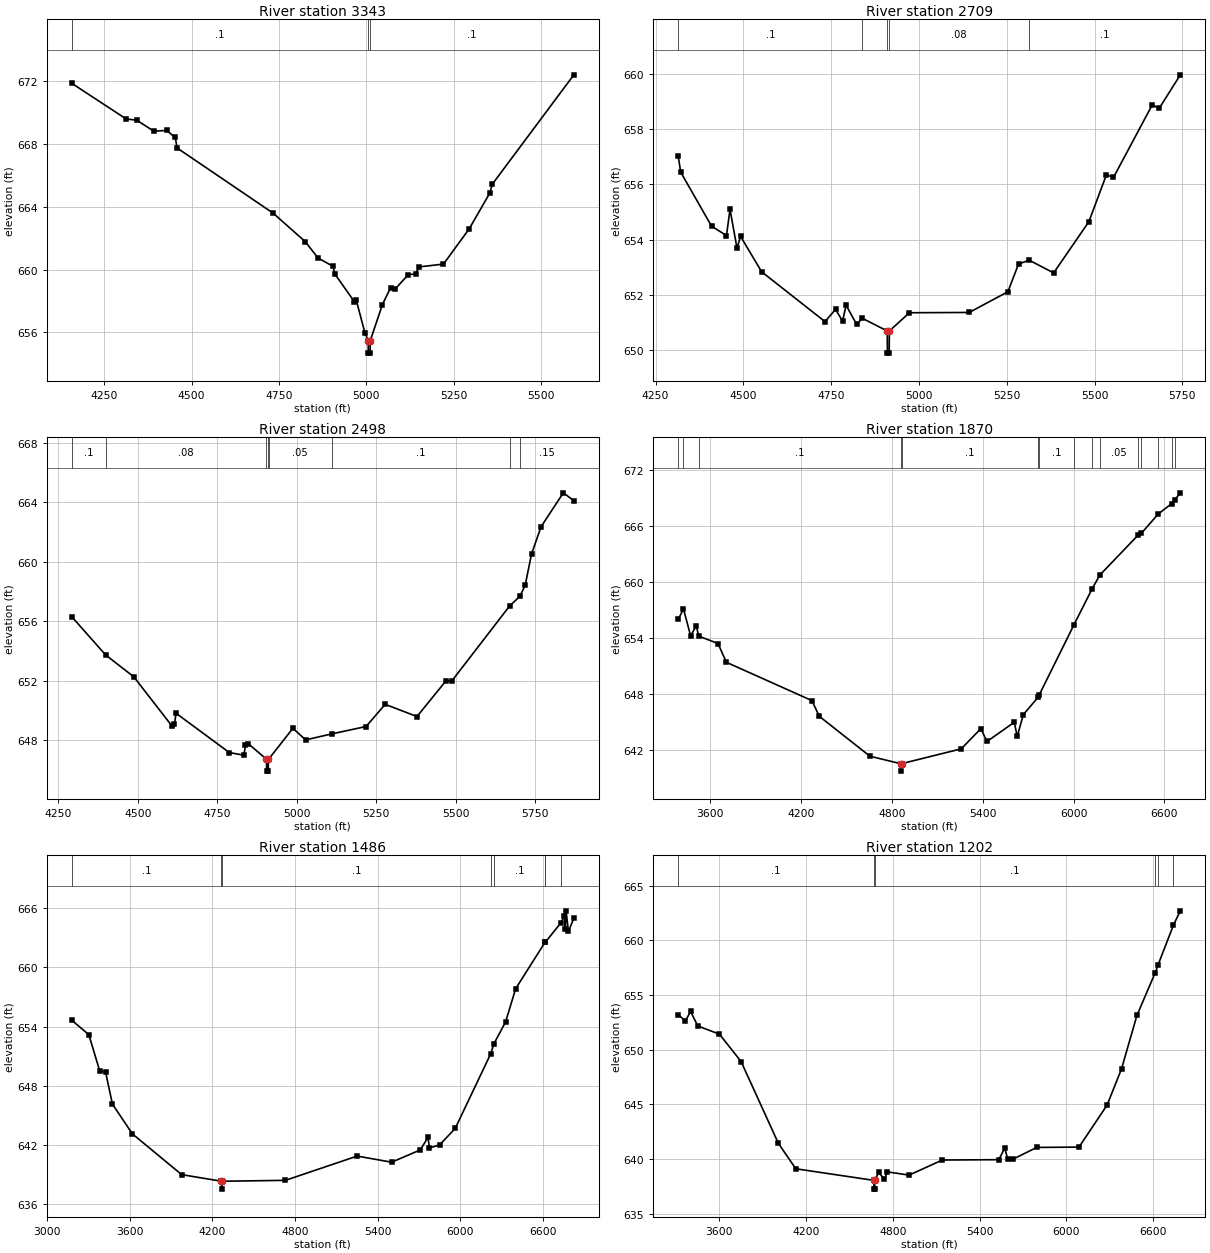
Type RM Length L Ch R = 1,3343,634,634,634
BEGIN DESCRIPTION:
UNT 118 in HW 7.0
END DESCRIPTION:
XS GIS Cut Line= 3
      2009024.99     13600275.02      2008725.00     13601075.00
      2009225.03     13601375.02
#Sta/Elev= 30
  4156.8  671.86  4312.5  669.59  4342.8  669.51  4391.7  668.81  4428.2  668.86
  4453.1  668.41  4458.5  667.74  4733.5  663.59  4825.2  661.78  4861.7  660.74
  4904.4  660.21  4910.6  659.70  4965.8  657.96  4971.1  658.07  4996.0  655.98
  5005.5  655.48  5006.0  654.68  5011.0  654.68  5011.5  655.48  5046.2  657.77
  5069.5  658.84  5083.1  658.77  5120.0  659.67  5141.4  659.73  5151.1  660.17
  5221.1  660.35  5294.9  662.60  5353.3  664.86  5361.0  665.44  5594.3  672.40
#Mann=3,-1,0
  4156.8     0.1       0  5005.5    0.07       0  5011.5     0.1       0
Bank Sta=5005.5,5011.5
Exp/Cntr=0.3,0.1

Type RM Length L Ch R = 1,2709,211,211,211
BEGIN DESCRIPTION:
Mapping XS 03563a1b
END DESCRIPTION:
XS GIS Cut Line= 2
      2008254.33     13600057.88      2008337.66     13601484.94
#Sta/Elev= 30
  4314.7  657.01  4321.8  656.44  4409.5  654.49  4452.1  654.15  4462.1  655.10
  4482.1  653.69  4492.1  654.12  4552.2  652.84  4732.5  651.04  4762.6  651.48
  4782.6  651.06  4792.6  651.63  4822.7  650.94  4838.8  651.16  4909.8  650.70
  4910.3  649.90  4915.3  649.90  4915.8  650.70  4972.9  651.36  5143.2  651.37
  5253.4  652.12  5283.5  653.12  5313.8  653.26  5383.6  652.80  5483.8  654.65
  5533.9  656.35  5553.9  656.25  5664.1  658.87  5684.2  658.75  5744.2  659.96
#Mann=5,-1,0
  4314.7     0.1       0  4838.8    0.08       0  4909.8    0.07       0
  4915.8    0.08       0  5313.8     0.1       0
Bank Sta=4909.8,4915.8
Exp/Cntr=0.3,0.1

Type RM Length L Ch R = 1,2498,628,628,628
BEGIN DESCRIPTION:
Mapping XS 4913895b
END DESCRIPTION:
XS GIS Cut Line= 2
      2008144.96     13599859.96      2008217.87     13601438.08
#Sta/Elev= 30
  4292.1  656.29  4398.7  653.72  4487.3  652.25  4607.5  648.94  4615.3  649.07
  4620.3  649.80  4787.7  647.16  4833.7  646.98  4838.7  647.65  4847.7  647.75
  4904.8  646.71  4905.3  645.91  4910.3  645.91  4910.8  646.71  4911.8  646.72
  4987.9  648.79  5027.9  648.01  5109.4  648.41  5218.1  648.91  5278.2  650.40
  5378.3  649.58  5468.4  651.95  5489.0  652.00  5669.7  657.01  5702.1  657.66
  5718.7  658.40  5738.7  660.50  5768.7  662.34  5838.8  664.62  5871.9  664.09
#Mann=8,-1,0
  4292.1     0.1       0  4398.7    0.08       0  4904.8    0.04       0
  4910.8    0.08       0  4911.8    0.05       0  5109.4     0.1       0
  5669.7    0.08       0  5702.1    0.15       0
Bank Sta=4904.8,4910.8
Exp/Cntr=0.3,0.1

Type RM Length L Ch R = 1,1870,384,384,384
BEGIN DESCRIPTION:
Mapping XS 50ccaa46
END DESCRIPTION:
XS GIS Cut Line= 4
      2008026.91     13598568.23      2007731.76     13599931.11
      2007705.72     13601042.22      2008018.22     13601788.76
#Sta/Elev= 30
  3389.8  655.99  3424.3  657.13  3471.6  654.23  3509.3  655.33  3524.5  654.21
  3652.5  653.41  3707.4  651.40  4272.2  647.29  4321.4  645.60  4655.6  641.32
  4858.3  640.52  4858.8  639.72  4864.3  640.52  5258.3  642.11  5388.3  644.28
  5428.3  642.90  5608.4  644.96  5628.4  643.45  5668.4  645.78  5766.5  647.66
  5772.7  647.87  6003.6  655.45  6122.1  659.26  6173.7  660.76  6426.3  665.04
  6447.0  665.22  6559.9  667.32  6647.8  668.42  6668.1  668.82  6705.0  669.58
#Mann=15,-1,0
  3389.8    0.08       0  3424.3    0.05       0  3524.5     0.1       0
  4858.3    0.07       0  4864.3     0.1       0  5766.5    0.05       0
  5772.7     0.1       0  6003.6    0.05       0  6122.1     0.1       0
  6173.7    0.05       0  6426.3     0.1       0  6447.0    0.05       0
  6559.9     0.1       0  6647.8    0.05       0  6668.1    0.08       0
Bank Sta=4858.3,4864.3
Exp/Cntr=0.3,0.1

Type RM Length L Ch R = 1,1486,284,284,284
BEGIN DESCRIPTION:
Mapping XS 7f40b48b
END DESCRIPTION:
XS GIS Cut Line= 4
      2007974.84     13598403.30      2007410.58     13599210.63
      2007332.46     13600582.15      2007896.68     13601736.64
#Sta/Elev= 30
  3178.9  654.64  3303.0  653.17  3380.8  649.54  3425.0  649.35  3473.8  646.14
  3618.9  643.12  3976.5  638.99  4265.4  638.32  4265.9  637.52  4271.4  638.32
  4729.2  638.41  5250.0  640.87  5500.4  640.25  5707.7  641.49  5764.4  642.76
  5774.5  641.69  5848.9  642.01  5961.5  643.67  6220.0  651.26  6242.6  652.26
  6327.3  654.47  6400.4  657.84  6614.3  662.56  6616.5  662.56  6727.9  664.50
  6754.0  665.20  6760.7  663.84  6766.3  665.73  6783.2  663.64  6822.6  664.97
#Mann=8,-1,0
  3178.9     0.1       0  4265.4    0.07       0  4271.4     0.1       0
  6220.0    0.05       0  6242.6     0.1       0  6614.3    0.05       0
  6616.5     0.1       0  6727.9    0.08       0
Bank Sta=4265.4,4271.4
Exp/Cntr=0.3,0.1

Type RM Length L Ch R = 1,1202,307,307,307
BEGIN DESCRIPTION:
Mapping XS c5cf9c00
END DESCRIPTION:
XS GIS Cut Line= 4
      2006577.23     13598533.52      2007089.40     13599201.95
      2007072.04     13600608.20      2007800.62     13601588.31
#Sta/Elev= 30
  3317.9  653.20  3367.8  652.63  3403.2  653.50  3453.0  652.17  3602.6  651.42
  3752.2  648.92  4009.7  641.45  4130.2  639.12  4670.1  638.06  4670.6  637.26
  4675.6  637.26  4676.1  638.06  4703.1  638.78  4743.1  638.15  4763.1  638.84
  4913.1  638.54  5143.1  639.92  5533.1  639.95  5574.1  641.01  5595.0  640.00
  5630.4  639.99  5795.2  641.07  6087.2  641.10  6281.3  644.93  6381.4  648.25
  6487.7  653.13  6614.6  657.05  6634.8  657.78  6740.3  661.39  6787.6  662.69
#Mann=6,-1,0
  3317.9     0.1       0  4670.1    0.07       0  4676.1     0.1       0
  6614.6    0.05       0  6634.8     0.1       0  6740.3    0.05       0
Bank Sta=4670.1,4676.1
Exp/Cntr=0.3,0.1

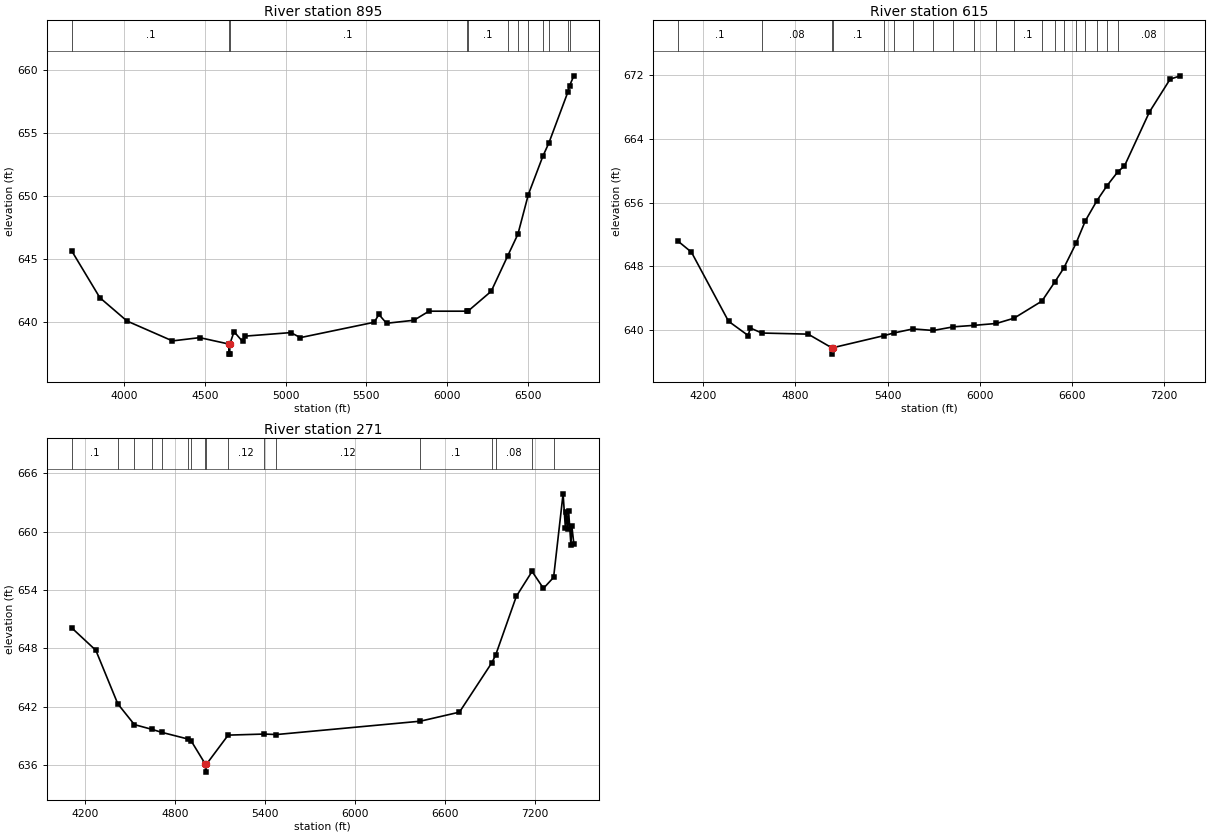
Type RM Length L Ch R = 1,895,280,280,280
BEGIN DESCRIPTION:
Mapping XS ffea1a43
END DESCRIPTION:
XS GIS Cut Line= 3
      2006256.07     13598854.72      2007019.96     13600651.60
      2007730.21     13601569.73
#Sta/Elev= 30
  3673.5  645.62  3847.7  641.91  4016.0  640.06  4297.8  638.48  4467.0  638.74
  4647.6  638.23  4648.1  637.43  4653.1  637.43  4653.6  638.23  4679.7  639.21
  4732.4  638.44  4749.5  638.86  5032.1  639.14  5090.6  638.74  5548.8  639.96
  5577.9  640.58  5625.1  639.88  5795.3  640.12  5888.5  640.84  6121.6  640.84
  6130.9  640.85  6274.3  642.42  6377.0  645.24  6440.0  646.96  6504.6  650.10
  6594.5  653.14  6632.3  654.21  6749.1  658.22  6760.0  658.74  6786.8  659.53
#Mann=12,-1,0
  3673.5     0.1       0  4647.6    0.07       0  4653.6     0.1       0
  6121.6    0.08       0  6130.9     0.1       0  6377.0    0.08       0
  6440.0     0.1       0  6504.6    0.05       0  6594.5     0.1       0
  6632.3    0.05       0  6749.1     0.1       0  6760.0    0.05       0
Bank Sta=4647.6,4653.6
Exp/Cntr=0.3,0.1

Type RM Length L Ch R = 1,615,344,344,344
BEGIN DESCRIPTION:
UNT 118 in HW 2.0
END DESCRIPTION:
XS GIS Cut Line= 3
      2005910.60     13599458.91      2007415.79     13601276.60
      2008025.20     13601948.51
#Sta/Elev= 30
  4037.5  651.14  4123.3  649.78  4364.7  641.10  4492.3  639.31  4506.6  640.25
  4581.3  639.62  4883.0  639.48  5036.3  637.77  5036.8  636.97  5042.3  637.77
  5373.5  639.28  5441.4  639.63  5565.4  640.14  5696.7  639.94  5828.1  640.40
  5959.4  640.58  6106.9  640.82  6222.1  641.48  6403.9  643.63  6488.5  646.05
  6545.4  647.75  6625.5  650.87  6687.0  653.73  6762.4  656.26  6828.5  658.15
  6899.3  659.91  6940.9  660.59  7103.7  667.39  7238.2  671.51  7304.6  671.93
#Mann=20,-1,0
  4037.5     0.1       0  4581.3    0.08       0  5036.3    0.07       0
  5042.3     0.1       0  5373.5    0.08       0  5441.4     0.1       0
  5565.4    0.08       0  5696.7    0.08       0  5828.1    0.08       0
  5959.4    0.08       0  6106.9    0.08       0  6222.1     0.1       0
  6403.9    0.08       0  6488.5     0.1       0  6545.4    0.05       0
  6625.5    0.08       0  6687.0    0.05       0  6762.4     0.1       0
  6828.5    0.05       0  6899.3    0.08       0
Bank Sta=5036.3,5042.3
Exp/Cntr=0.3,0.1

Type RM Length L Ch R = 1,271,0,0,0
BEGIN DESCRIPTION:
UNT 118 in HW 1.0
END DESCRIPTION:
XS GIS Cut Line= 3
      2005702.22     13599682.81      2007447.04     13601974.52
      2007848.10     13602219.32
#Sta/Elev= 30
  4109.0  650.10  4269.6  647.80  4416.2  642.30  4526.8  640.17  4646.9  639.67
  4708.2  639.38  4884.2  638.69  4907.5  638.45  5001.1  636.09  5001.6  635.29
  5007.1  636.09  5152.5  639.09  5392.4  639.20  5474.8  639.15  6434.5  640.52
  6695.8  641.45  6912.2  646.53  6937.6  647.32  7075.7  653.35  7180.4  655.90
  7256.4  654.16  7324.1  655.29  7387.4  663.87  7402.9  660.34  7408.7  662.05
  7418.3  660.30  7424.2  662.10  7439.7  658.63  7445.5  660.59  7459.2  658.74
#Mann=17,-1,0
  4109.0     0.1       0  4416.2    0.05       0  4526.8     0.1       0
  4646.9    0.05       0  4708.2     0.1       0  4884.2    0.05       0
  4907.5     0.1       0  5001.1    0.07       0  5007.1     0.1       0
  5152.5    0.12       0  5392.4    0.05       0  5474.8    0.12       0
  6434.5     0.1       0  6912.2    0.05       0  6937.6    0.08       0
  7180.4     0.1       0  7324.1    0.08       0
Bank Sta=5001.1,5007.1
Exp/Cntr=0.3,0.1

Chan Stop Cuts=-1