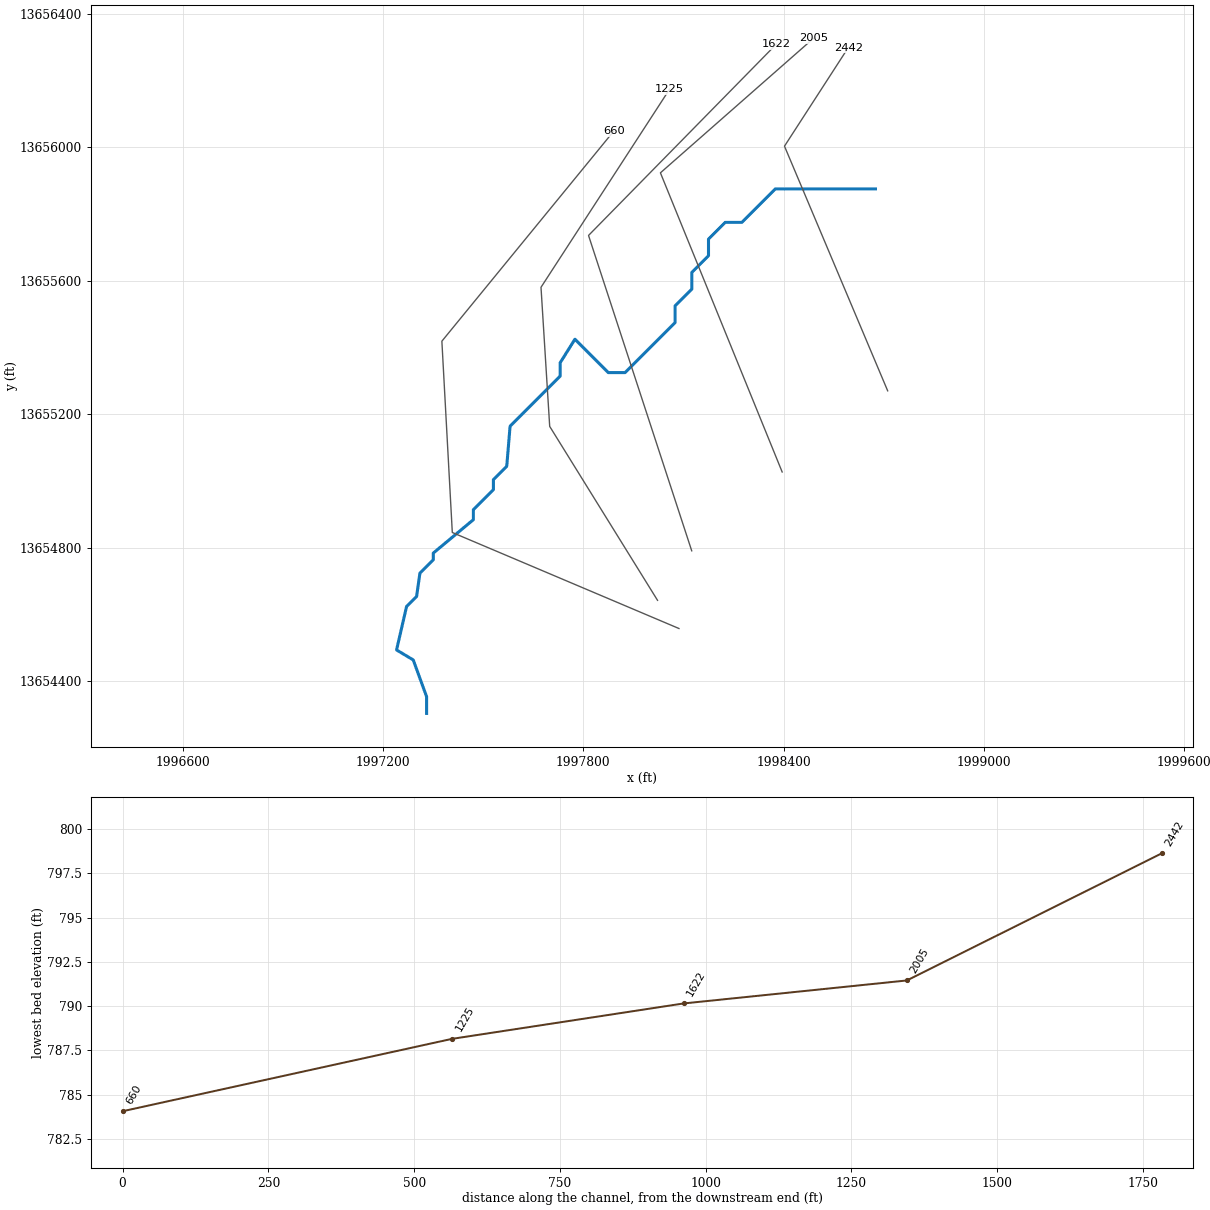
--- UNT 119 in HW.prj (project) ---

Proj Title=UNT 119 in HW Base Level Engineering
Current Plan=p01
Default Exp/Contr=0.3,0.1
English Units
Geom File=g01
Flow File=f01
Plan File=p01
BEGIN DESCRIPTION:
UNT 119 in HW
END DESCRIPTION:

--- UNT 119 in HW.p01 (plan) ---

Plan Title=Multiple Run
Short Identifier=Multiple
Geom File=g01
Flow File=f01
Subcritical Flow
K Sum by GR= 0
Std Step Tol= 0.01
Critical Tol= 0.01
Num of Std Step Trials= 20
Max Error Tol= 0.3
Flow Tol Ratio= 0.001
Split Flow NTrial= 30
Split Flow Tol= 0.02
Split Flow Ratio= 0.02
Log Output Level= 0
Friction Slope Method= 1
Unsteady Friction Slope Method= 2
Unsteady Bridges Friction Slope Method= 1
Parabolic Critical Depth
Global Vel Dist=  1 , 1 , 1
Global Log Level= 0
CheckData=True
Encroach Param= -1, 0, 0, 0
BEGIN DESCRIPTION:
Multiple Run
END DESCRIPTION:

--- UNT 119 in HW.f01 (steady flow) ---

Flow Title=Multiple
Number of Profiles=7
Profile Names=10-year,25-year,50-year,1pct_min,100-year,1pct_plu,500-year
River Rch & RM= UNT 119 in HW,Reach-1,2442
     159     205     240     140     280     558     378
Boundary for River Rch & Prof#=UNT 119 in HW,Reach-1,1
Up Type=0
Dn Type=3
Dn Slope=0.005
Boundary for River Rch & Prof#=UNT 119 in HW,Reach-1,2
Up Type=0
Dn Type=3
Dn Slope=0.005
Boundary for River Rch & Prof#=UNT 119 in HW,Reach-1,3
Up Type=0
Dn Type=3
Dn Slope=0.005
Boundary for River Rch & Prof#=UNT 119 in HW,Reach-1,4
Up Type=0
Dn Type=3
Dn Slope=0.005
Boundary for River Rch & Prof#=UNT 119 in HW,Reach-1,5
Up Type=0
Dn Type=3
Dn Slope=0.005
Boundary for River Rch & Prof#=UNT 119 in HW,Reach-1,6
Up Type=0
Dn Type=3
Dn Slope=0.005
Boundary for River Rch & Prof#=UNT 119 in HW,Reach-1,7
Up Type=0
Dn Type=3
Dn Slope=0.005

--- UNT 119 in HW.g01 (geometry) ---

Geom Title=Existing Conditions

River Reach=UNT 119 in HW,Reach-1
Reach XY= 30
      1998675.00     13655875.00      1998375.00     13655875.00
      1998275.00     13655775.00      1998225.00     13655775.00
      1998175.00     13655725.00      1998175.00     13655675.00
      1998125.00     13655625.00      1998125.00     13655575.00
      1998075.00     13655525.00      1998075.00     13655475.00
      1997925.00     13655325.00      1997875.00     13655325.00
      1997775.00     13655425.00      1997730.80     13655354.54
      1997730.80     13655314.54      1997580.80     13655164.54
      1997570.80     13655044.54      1997530.80     13655004.54
      1997530.80     13654974.54      1997470.80     13654914.54
      1997470.80     13654884.54      1997350.80     13654784.54
      1997350.80     13654764.54      1997310.80     13654724.54
      1997300.80     13654654.54      1997270.80     13654624.54
      1997240.80     13654494.54      1997290.80     13654464.54
      1997330.80     13654354.54      1997330.80     13654304.54

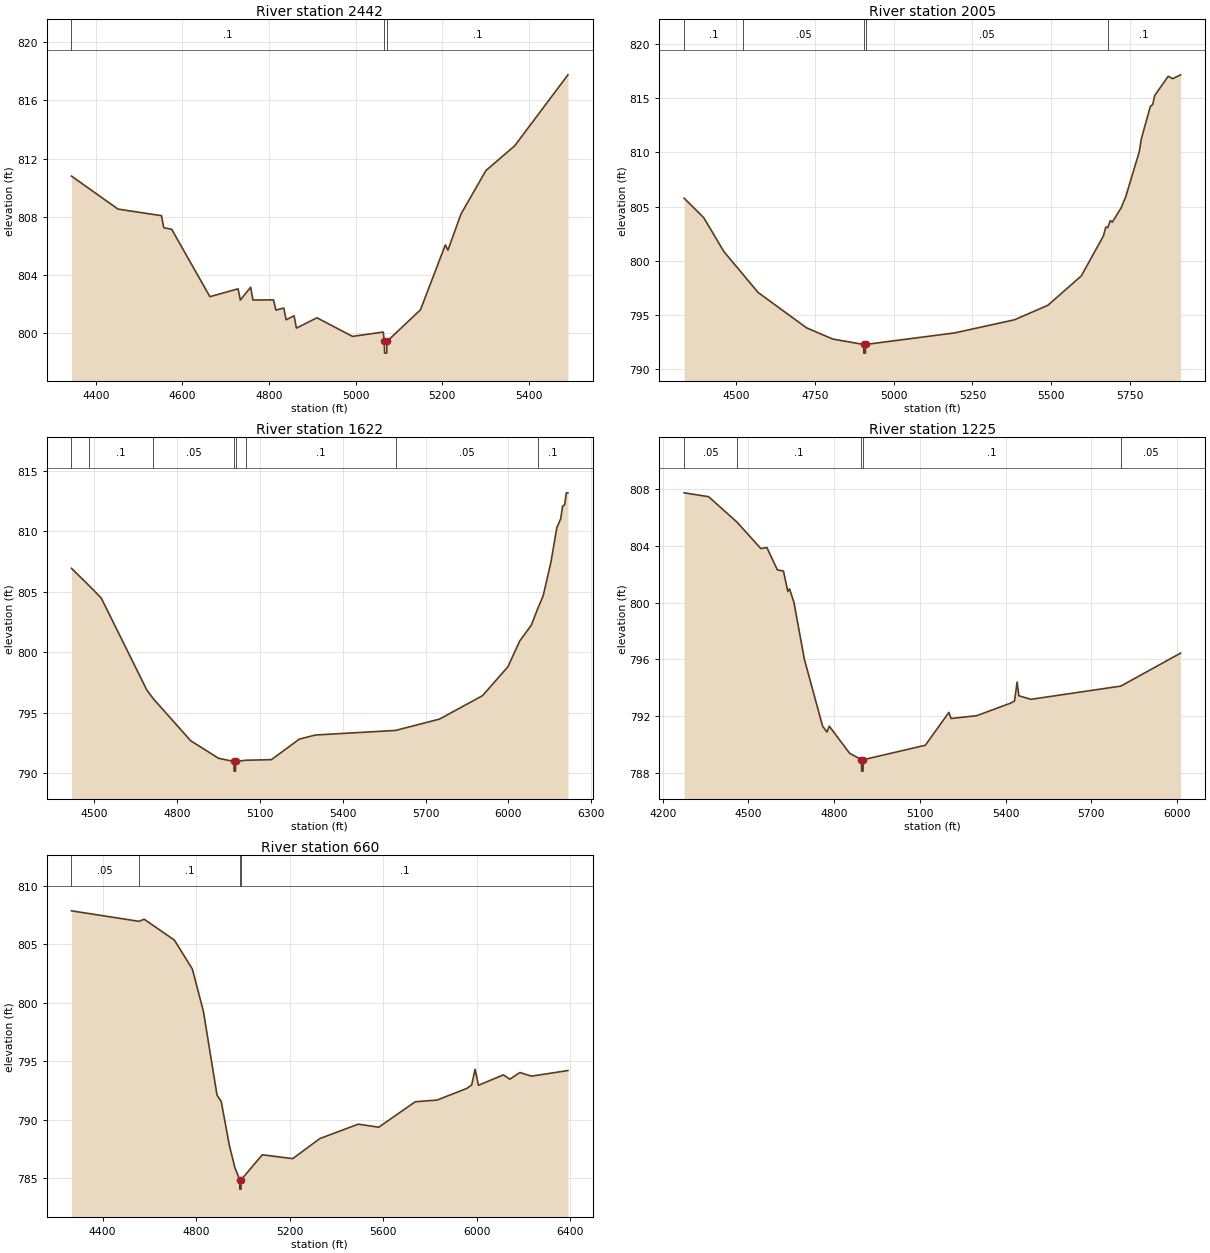
Type RM Length L Ch R = 1,2442,437,437,437
BEGIN DESCRIPTION:
UNT 119 in HW 2.0
END DESCRIPTION:
XS GIS Cut Line= 3
      1998711.57     13655270.48      1998402.53     13656003.13
      1998593.51     13656298.27
#Sta/Elev= 30
  4343.9  810.80  4451.4  808.53  4551.7  808.08  4557.1  807.25  4575.4  807.14
  4663.6  802.51  4728.6  803.05  4734.0  802.28  4757.7  803.16  4763.1  802.28
  4810.6  802.29  4816.0  801.59  4834.3  801.73  4839.7  800.92  4858.0  801.20
  4863.4  800.35  4910.9  801.06  4992.9  799.78  5064.0  800.08  5066.5  799.43
  5067.0  798.63  5072.0  798.63  5072.5  799.43  5150.0  801.61  5207.4  806.07
  5213.4  805.71  5243.7  808.20  5301.1  811.18  5367.6  812.88  5490.6  817.76
#Mann=3,-1,0
  4343.9     0.1       0  5066.5    0.07       0  5072.5     0.1       0
Bank Sta=5066.5,5072.5
Exp/Cntr=0.3,0.1

Type RM Length L Ch R = 1,2005,383,383,383
BEGIN DESCRIPTION:
UNT 119 in HW 3.0
END DESCRIPTION:
XS GIS Cut Line= 3
      1998395.60     13655027.42      1998031.01     13655923.27
      1998489.37     13656326.07
#Sta/Elev= 30
  4333.8  805.77  4396.0  803.97  4460.7  800.81  4521.6  798.70  4568.7  797.06
  4722.7  793.79  4806.2  792.75  4904.3  792.25  4904.8  791.45  4909.8  791.45
  4910.3  792.25  5193.5  793.32  5383.2  794.53  5489.5  795.87  5595.8  798.59
  5666.0  802.28  5673.6  803.10  5680.0  803.06  5687.8  803.70  5694.5  803.56
  5722.9  804.91  5737.2  805.93  5779.9  810.06  5786.5  811.26  5815.0  814.24
  5822.6  814.43  5829.2  815.27  5871.9  817.04  5886.1  816.81  5911.2  817.17
#Mann=5,-1,0
  4333.8     0.1       0  4521.6    0.05       0  4904.3   0.035       0
  4910.3    0.05       0  5680.0     0.1       0
Bank Sta=4904.3,4910.3
Exp/Cntr=0.3,0.1

Type RM Length L Ch R = 1,1622,397,397,397
BEGIN DESCRIPTION:
UNT 119 in HW 4.0
END DESCRIPTION:
XS GIS Cut Line= 3
      1998124.74     13654791.37      1997815.73     13655735.77
      1998378.25     13656308.71
#Sta/Elev= 30
  4418.6  806.94  4482.7  805.50  4526.3  804.48  4690.9  796.88  4714.4  796.15
  4850.2  792.66  4951.1  791.21  5006.5  790.95  5007.0  790.15  5012.0  790.15
  5012.5  790.95  5048.7  791.05  5142.2  791.10  5243.1  792.80  5301.5  793.14
  5591.7  793.52  5750.6  794.46  5906.2  796.40  5998.2  798.80  6040.6  800.92
  6083.0  802.25  6105.1  803.56  6125.5  804.66  6153.8  807.47  6174.9  810.30
  6189.1  811.05  6196.1  812.11  6203.2  812.19  6209.3  813.19  6215.2  813.19
#Mann=8,-1,0
  4418.6    0.05       0  4482.7     0.1       0  4714.4    0.05       0
  5006.5   0.035       0  5012.5    0.05       0  5048.7     0.1       0
  5591.7    0.05       0  6105.1     0.1       0
Bank Sta=5006.5,5012.5
Exp/Cntr=0.3,0.1

Type RM Length L Ch R = 1,1225,565,565,565
BEGIN DESCRIPTION:
UNT 119 in HW 5.0
END DESCRIPTION:
XS GIS Cut Line= 4
      1998022.37     13654643.08      1997699.45     13655163.91
      1997673.41     13655580.58      1998058.84     13656174.35
#Sta/Elev= 30
  4274.7  807.72  4360.2  807.45  4459.3  805.67  4543.3  803.80  4564.5  803.87
  4601.2  802.30  4622.4  802.22  4637.8  800.78  4643.7  800.97  4659.1  800.02
  4695.7  796.02  4759.4  791.32  4774.8  790.90  4782.9  791.31  4854.0  789.41
  4895.6  788.95  4896.1  788.15  4901.1  788.15  4901.6  788.95  5119.1  789.97
  5201.8  792.28  5209.2  791.85  5299.4  792.05  5417.6  792.93  5431.4  793.08
  5440.6  794.42  5446.5  793.45  5489.1  793.20  5803.8  794.13  6012.9  796.45
#Mann=5,-1,0
  4274.7    0.05       0  4459.3     0.1       0  4895.6    0.07       0
  4901.6     0.1       0  5803.8    0.05       0
Bank Sta=4895.6,4901.6
Exp/Cntr=0.3,0.1

Type RM Length L Ch R = 1,660,0,0,0
BEGIN DESCRIPTION:
UNT 119 in HW 1.0
END DESCRIPTION:
XS GIS Cut Line= 4
      1998086.57     13654558.68      1997407.78     13654846.20
      1997376.53     13655419.12      1997891.08     13656048.01
#Sta/Elev= 30
  4267.1  807.88  4555.8  806.98  4578.2  807.16  4707.5  805.37  4784.0  802.90
  4831.3  799.29  4889.5  792.12  4907.8  791.54  4942.3  787.81  4966.0  785.90
  4986.7  784.86  4987.2  784.06  4992.2  784.06  4992.7  784.86  5083.2  787.00
  5213.4  786.67  5329.7  788.39  5493.8  789.62  5581.3  789.36  5737.8  791.54
  5830.4  791.68  5958.2  792.68  5979.0  792.98  5993.4  794.32  6007.7  792.95
  6114.7  793.84  6142.0  793.47  6185.0  794.04  6234.6  793.73  6390.6  794.21
#Mann=4,-1,0
  4267.1    0.05       0  4555.8     0.1       0  4986.7    0.07       0
  4992.7     0.1       0
Bank Sta=4986.7,4992.7
Exp/Cntr=0.3,0.1

Chan Stop Cuts=-1