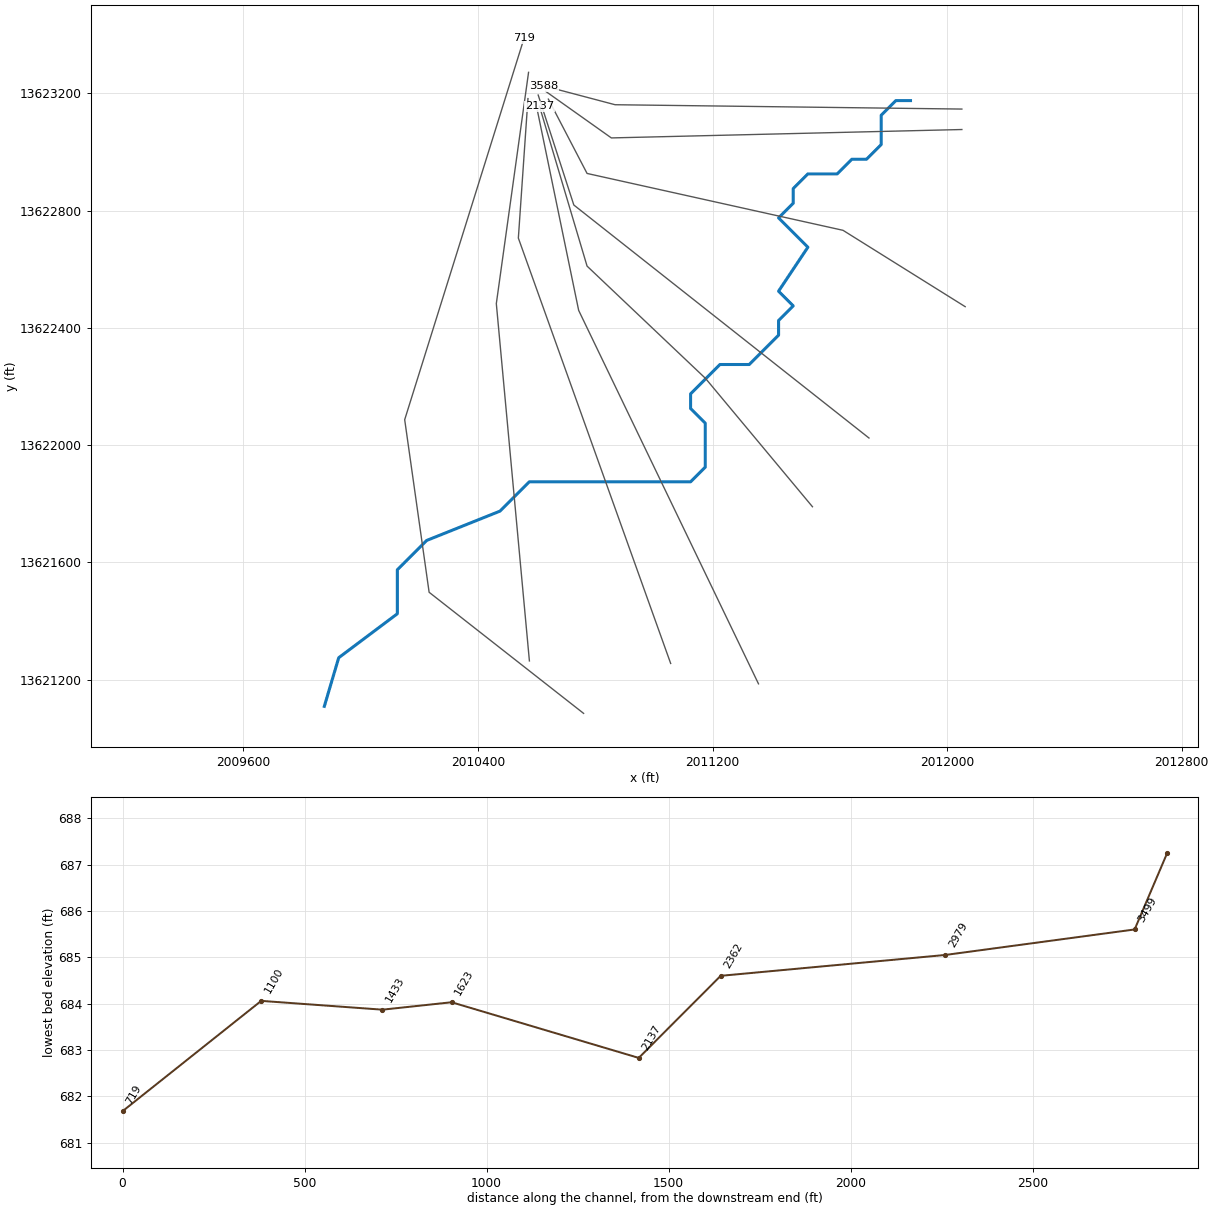
--- UNT 120 in HW.prj (project) ---

Proj Title=UNT 120 in HW Base Level Engineering
Current Plan=p01
Default Exp/Contr=0.3,0.1
English Units
Geom File=g01
Flow File=f01
Plan File=p01
BEGIN DESCRIPTION:
UNT 120 in HW
END DESCRIPTION:

--- UNT 120 in HW.p01 (plan) ---

Plan Title=Multiple Run
Short Identifier=Multiple
Geom File=g01
Flow File=f01
Subcritical Flow
K Sum by GR= 0
Std Step Tol= 0.01
Critical Tol= 0.01
Num of Std Step Trials= 20
Max Error Tol= 0.3
Flow Tol Ratio= 0.001
Split Flow NTrial= 30
Split Flow Tol= 0.02
Split Flow Ratio= 0.02
Log Output Level= 0
Friction Slope Method= 1
Unsteady Friction Slope Method= 2
Unsteady Bridges Friction Slope Method= 1
Parabolic Critical Depth
Global Vel Dist=  1 , 1 , 1
Global Log Level= 0
CheckData=True
Encroach Param= -1, 0, 0, 0
BEGIN DESCRIPTION:
Multiple Run
END DESCRIPTION:

--- UNT 120 in HW.f01 (steady flow) ---

Flow Title=Multiple
Number of Profiles=7
Profile Names=10-year,25-year,50-year,1pct_min,100-year,1pct_plu,500-year
River Rch & RM= UNT 120 in HW,Reach-1,3588
     123     155     178     102     204     407     268
Boundary for River Rch & Prof#=UNT 120 in HW,Reach-1,1
Up Type=0
Dn Type=3
Dn Slope=0.005
Boundary for River Rch & Prof#=UNT 120 in HW,Reach-1,2
Up Type=0
Dn Type=3
Dn Slope=0.005
Boundary for River Rch & Prof#=UNT 120 in HW,Reach-1,3
Up Type=0
Dn Type=3
Dn Slope=0.005
Boundary for River Rch & Prof#=UNT 120 in HW,Reach-1,4
Up Type=0
Dn Type=3
Dn Slope=0.005
Boundary for River Rch & Prof#=UNT 120 in HW,Reach-1,5
Up Type=0
Dn Type=3
Dn Slope=0.005
Boundary for River Rch & Prof#=UNT 120 in HW,Reach-1,6
Up Type=0
Dn Type=3
Dn Slope=0.005
Boundary for River Rch & Prof#=UNT 120 in HW,Reach-1,7
Up Type=0
Dn Type=3
Dn Slope=0.005

--- UNT 120 in HW.g01 (geometry) ---

Geom Title=Existing Conditions

River Reach=UNT 120 in HW,Reach-1
Reach XY= 30
      2011875.00     13623175.00      2011825.00     13623175.00
      2011775.00     13623125.00      2011775.00     13623025.00
      2011725.00     13622975.00      2011675.00     13622975.00
      2011625.00     13622925.00      2011525.00     13622925.00
      2011475.00     13622875.00      2011475.00     13622825.00
      2011425.00     13622775.00      2011525.00     13622675.00
      2011425.00     13622525.00      2011475.00     13622475.00
      2011425.00     13622425.00      2011425.00     13622375.00
      2011325.00     13622275.00      2011225.00     13622275.00
      2011125.00     13622175.00      2011125.00     13622125.00
      2011175.00     13622075.00      2011175.00     13621925.00
      2011125.00     13621875.00      2010575.00     13621875.00
      2010475.00     13621775.00      2010225.00     13621675.00
      2010125.00     13621575.00      2010125.00     13621425.00
      2009925.00     13621275.00      2009875.96     13621109.38

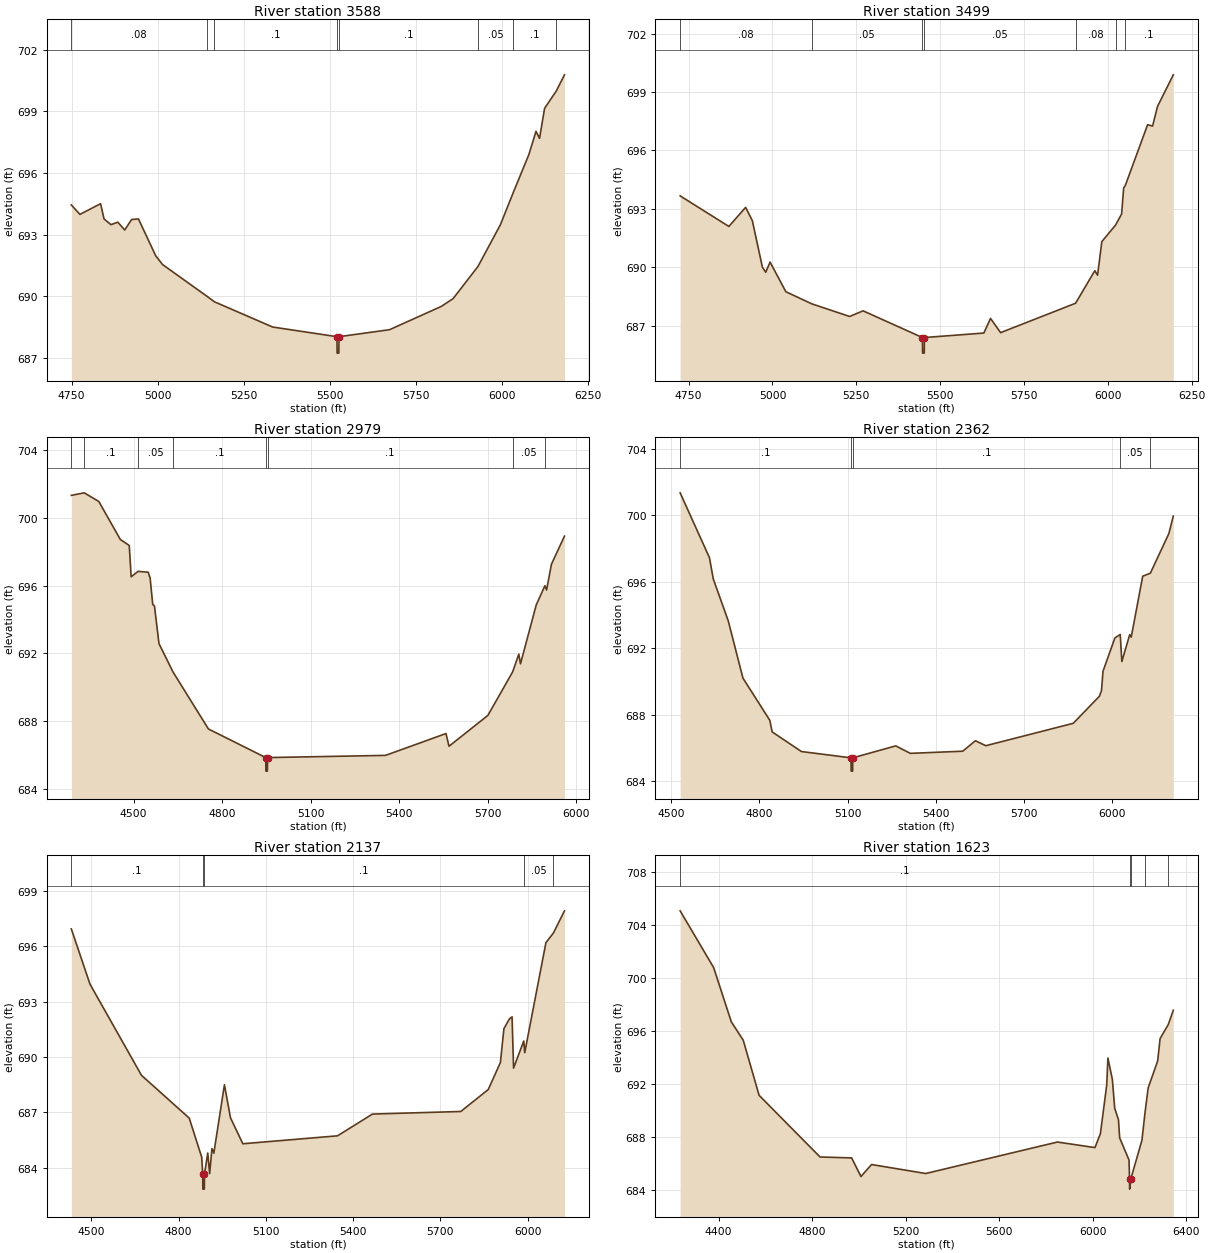
Type RM Length L Ch R = 1,3588,89,89,89
BEGIN DESCRIPTION:
UNT 120 in HW 2.0
END DESCRIPTION:
XS GIS Cut Line= 3
      2012050.14     13623146.12      2010867.45     13623160.92
      2010624.96     13623225.01
#Sta/Elev= 30
  4749.1  694.45  4774.2  693.99  4834.2  694.51  4844.2  693.77  4864.2  693.49
  4884.3  693.61  4904.3  693.23  4924.3  693.74  4944.3  693.77  4994.3  691.98
  5014.3  691.55  5143.9  690.00  5164.8  689.74  5334.3  688.51  5521.3  688.04
  5521.8  687.24  5526.8  687.24  5527.3  688.04  5674.3  688.38  5824.3  689.51
  5858.9  689.89  5931.4  691.46  5996.5  693.49  6034.0  695.06  6079.2  696.90
  6099.9  698.03  6110.3  697.69  6124.9  699.15  6158.8  699.99  6182.7  700.78
#Mann=8,-1,0
  4749.1    0.08       0  5143.9    0.05       0  5164.8     0.1       0
  5521.3    0.07       0  5527.3     0.1       0  5931.4    0.05       0
  6034.0     0.1       0  6158.8    0.05       0
Bank Sta=5521.3,5527.3
Exp/Cntr=0.3,0.1

Type RM Length L Ch R = 1,3499,520,520,520
BEGIN DESCRIPTION:
Mapping XS 381ef89f
END DESCRIPTION:
XS GIS Cut Line= 3
      2012050.12     13623076.37      2010854.78     13623047.72
      2010630.79     13623206.60
#Sta/Elev= 30
  4724.8  693.67  4870.0  692.10  4920.0  693.08  4940.0  692.40  4970.0  690.01
  4980.0  689.75  4992.9  690.27  5040.0  688.75  5117.0  688.13  5230.1  687.48
  5270.1  687.77  5447.1  686.40  5447.6  685.60  5452.6  685.60  5453.1  686.40
  5630.2  686.63  5650.2  687.38  5680.2  686.65  5903.8  688.16  5961.1  689.83
  5969.3  689.60  5982.0  691.32  6022.9  692.17  6041.0  692.74  6047.2  694.08
  6051.5  694.18  6118.5  697.32  6133.3  697.25  6148.1  698.26  6195.1  699.88
#Mann=7,-1,0
  4724.8    0.08       0  5117.0    0.05       0  5447.1    0.07       0
  5453.1    0.05       0  5903.8    0.08       0  6022.9    0.05       0
  6051.5     0.1       0
Bank Sta=5447.1,5453.1
Exp/Cntr=0.3,0.1

Type RM Length L Ch R = 1,2979,617,617,617
BEGIN DESCRIPTION:
Mapping XS 69467741
END DESCRIPTION:
XS GIS Cut Line= 4
      2012061.48     13622472.21      2011644.79     13622732.64
      2010771.94     13622926.59      2010640.03     13623179.99
#Sta/Elev= 30
  4288.9  701.34  4332.7  701.49  4382.0  700.98  4455.1  698.73  4485.2  698.38
  4491.7  696.53  4515.1  696.85  4549.5  696.80  4556.0  696.45  4564.8  694.90
  4570.7  694.80  4586.0  692.58  4633.4  690.91  4753.5  687.54  4947.8  685.85
  4948.3  685.05  4953.3  685.05  4953.8  685.85  5353.7  685.98  5558.6  687.27
  5568.8  686.52  5700.5  688.34  5784.4  690.91  5805.4  691.96  5811.1  691.39
  5864.3  694.86  5893.7  696.00  5899.5  695.75  5915.9  697.27  5960.1  698.93
#Mann=8,-1,0
  4288.9    0.05       0  4332.7     0.1       0  4515.1    0.05       0
  4633.4     0.1       0  4947.8    0.07       0  4953.8     0.1       0
  5784.4    0.05       0  5893.7     0.1       0
Bank Sta=4947.8,4953.8
Exp/Cntr=0.3,0.1

Type RM Length L Ch R = 1,2362,225,225,225
BEGIN DESCRIPTION:
Mapping XS d99e8b2f
END DESCRIPTION:
XS GIS Cut Line= 3
      2011733.32     13622024.32      2010726.80     13622818.95
      2010605.27     13623193.96
#Sta/Elev= 30
  4530.8  701.36  4630.5  697.45  4643.3  696.18  4694.3  693.65  4744.3  690.20
  4835.6  687.66  4843.7  686.96  4943.1  685.78  5111.7  685.40  5112.2  684.60
  5117.2  684.60  5117.7  685.40  5263.7  686.12  5313.4  685.67  5491.4  685.80
  5534.7  686.43  5569.9  686.13  5867.3  687.48  5956.2  689.11  5963.2  689.44
  5968.5  690.62  6008.8  692.62  6026.9  692.83  6032.5  691.20  6059.2  692.82
  6064.4  692.67  6103.4  696.34  6129.4  696.52  6192.4  698.91  6207.4  699.96
#Mann=5,-1,0
  4530.8     0.1       0  5111.7    0.07       0  5117.7     0.1       0
  6026.9    0.05       0  6129.4     0.1       0
Bank Sta=5111.7,5117.7
Exp/Cntr=0.3,0.1

Type RM Length L Ch R = 1,2137,514,514,514
BEGIN DESCRIPTION:
Mapping XS 9f6688b3
END DESCRIPTION:
XS GIS Cut Line= 4
      2011540.62     13621789.94      2011176.04     13622227.43
      2010771.94     13622610.61      2010609.60     13623156.09
#Sta/Elev= 30
  4431.5  696.94  4495.8  693.94  4672.8  689.00  4836.9  686.68  4879.8  684.56
  4883.3  683.63  4883.8  682.83  4888.8  682.83  4889.3  683.63  4900.6  684.79
  4907.1  683.67  4915.0  685.03  4921.5  684.78  4957.9  688.49  4978.7  686.70
  5021.2  685.29  5346.8  685.72  5466.9  686.90  5770.5  687.04  5865.0  688.23
  5906.8  689.70  5918.8  691.53  5938.1  692.07  5946.8  692.17  5952.0  689.39
  5987.0  690.86  5990.4  690.23  6063.3  696.20  6088.8  696.71  6127.0  697.92
#Mann=5,-1,0
  4431.5     0.1       0  4883.3    0.07       0  4889.3     0.1       0
  5987.0    0.05       0  6088.8     0.1       0
Bank Sta=4883.3,4889.3
Exp/Cntr=0.3,0.1

Type RM Length L Ch R = 1,1623,190,190,190
BEGIN DESCRIPTION:
Mapping XS a3f3b98a
END DESCRIPTION:
XS GIS Cut Line= 3
      2011356.58     13621186.02      2010743.30     13622459.57
      2010602.73     13623140.29
#Sta/Elev= 30
  4235.3  705.07  4378.5  700.78  4454.2  696.67  4505.0  695.29  4572.9  691.12
  4833.5  686.46  4968.6  686.39  5008.3  684.98  5053.6  685.89  5285.3  685.21
  5848.4  687.59  6008.9  687.17  6032.2  688.22  6059.2  691.90  6064.3  693.94
  6083.2  692.34  6093.4  690.14  6109.4  689.28  6114.6  687.90  6154.6  686.23
  6156.7  684.83  6157.2  684.03  6162.7  684.83  6210.0  687.74  6222.3  689.72
  6236.4  691.68  6277.2  693.73  6287.4  695.41  6322.3  696.47  6343.9  697.55
#Mann=5,-1,0
  4235.3     0.1       0  6156.7    0.07       0  6162.7     0.1       0
  6222.3    0.05       0  6322.3     0.1       0
Bank Sta=6156.7,6162.7
Exp/Cntr=0.3,0.1

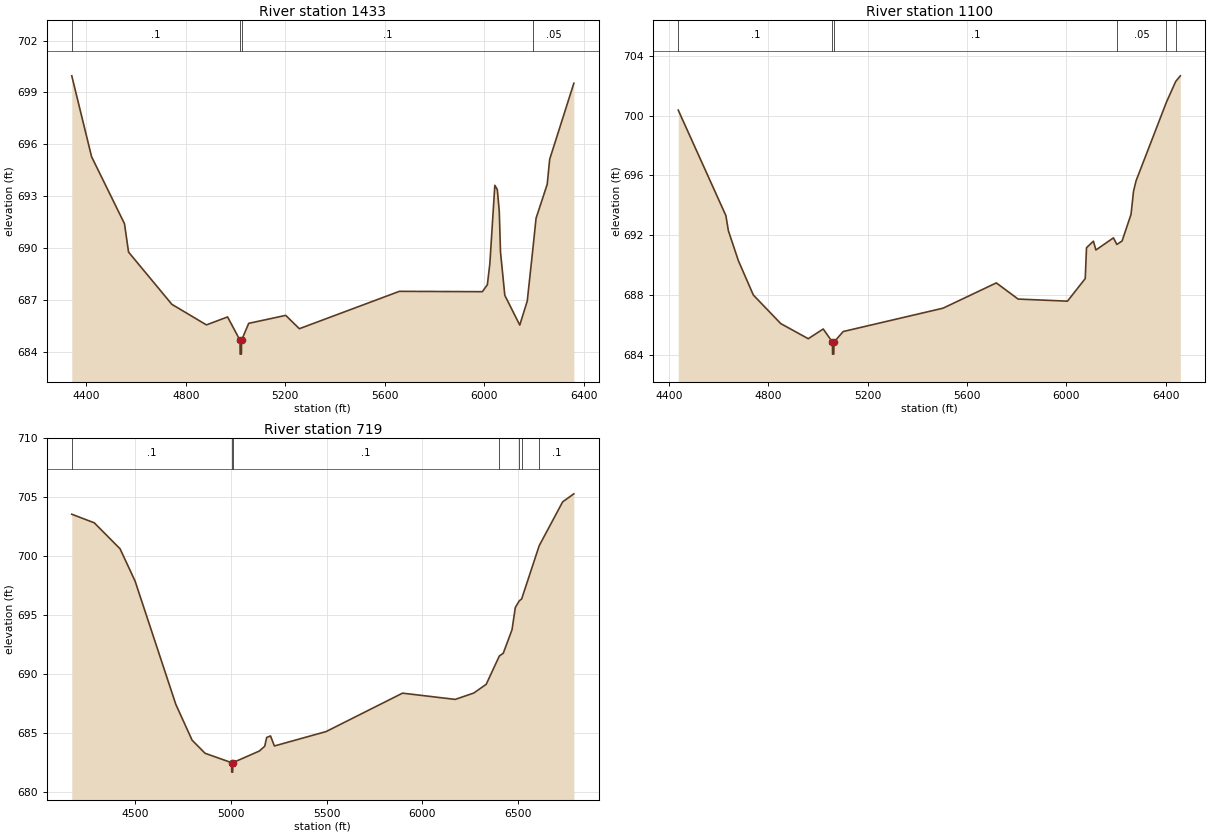
Type RM Length L Ch R = 1,1433,333,333,333
BEGIN DESCRIPTION:
Mapping XS 38e0be8f
END DESCRIPTION:
XS GIS Cut Line= 3
      2011057.08     13621255.52      2010537.63     13622706.19
      2010570.43     13623181.79
#Sta/Elev= 30
  4342.0  699.96  4421.7  695.28  4553.9  691.41  4570.2  689.77  4744.2  686.75
  4883.2  685.56  4968.1  686.02  5018.2  684.67  5018.7  683.87  5023.7  683.87
  5024.2  684.67  5053.1  685.65  5201.8  686.11  5256.6  685.34  5658.5  687.50
  5991.9  687.48  6012.0  687.88  6022.0  689.09  6042.1  693.63  6052.1  693.38
  6059.9  692.14  6064.9  689.77  6082.2  687.27  6142.3  685.55  6172.4  686.94
  6196.5  690.16  6207.7  691.72  6252.6  693.69  6262.6  695.14  6359.6  699.53
#Mann=4,-1,0
  4342.0     0.1       0  5018.2    0.07       0  5024.2     0.1       0
  6196.5    0.05       0
Bank Sta=5018.2,5024.2
Exp/Cntr=0.3,0.1

Type RM Length L Ch R = 1,1100,381,381,381
BEGIN DESCRIPTION:
Mapping XS f7c4ac3c
END DESCRIPTION:
XS GIS Cut Line= 3
      2010575.33     13621264.12      2010462.50     13622482.64
      2010572.44     13623271.39
#Sta/Elev= 30
  4438.2  700.37  4629.9  693.32  4639.9  692.31  4680.1  690.31  4740.4  688.01
  4850.8  686.10  4961.3  685.09  5021.6  685.74  5058.7  684.86  5059.2  684.06
  5064.2  684.06  5064.7  684.86  5101.9  685.57  5503.6  687.13  5718.0  688.82
  5805.7  687.74  6004.3  687.60  6075.8  689.11  6080.9  691.17  6108.6  691.61
  6118.7  691.02  6189.3  691.83  6202.9  691.39  6224.0  691.62  6260.0  693.40
  6270.1  694.95  6280.2  695.64  6402.7  700.91  6439.7  702.28  6458.3  702.66
#Mann=6,-1,0
  4438.2     0.1       0  5058.7    0.07       0  5064.7     0.1       0
  6202.9    0.05       0  6402.7     0.1       0  6439.7    0.05       0
Bank Sta=5058.7,5064.7
Exp/Cntr=0.3,0.1

Type RM Length L Ch R = 1,719,0,0,0
BEGIN DESCRIPTION:
UNT 120 in HW 1.0
END DESCRIPTION:
XS GIS Cut Line= 4
      2010760.12     13621085.28      2010233.33     13621498.27
      2010150.00     13622086.81      2010557.00     13623387.33
#Sta/Elev= 30
  4166.9  703.56  4284.7  702.83  4419.4  700.63  4498.1  697.89  4711.4  687.42
  4796.4  684.39  4864.2  683.28  5003.2  682.48  5003.7  681.68  5008.7  681.68
  5009.2  682.48  5148.2  683.47  5176.4  683.88  5186.5  684.62  5206.7  684.75
  5226.9  683.90  5497.3  685.12  5897.2  688.38  6172.7  687.85  6270.0  688.39
  6334.9  689.13  6403.6  691.53  6424.2  691.77  6470.0  693.76  6487.1  695.64
  6507.9  696.21  6520.3  696.37  6612.2  700.89  6734.9  704.61  6793.4  705.29
#Mann=7,-1,0
  4166.9     0.1       0  5003.2    0.07       0  5009.2     0.1       0
  6403.6    0.05       0  6507.9     0.1       0  6520.3    0.05       0
  6612.2     0.1       0
Bank Sta=5003.2,5009.2
Exp/Cntr=0.3,0.1

Chan Stop Cuts=-1