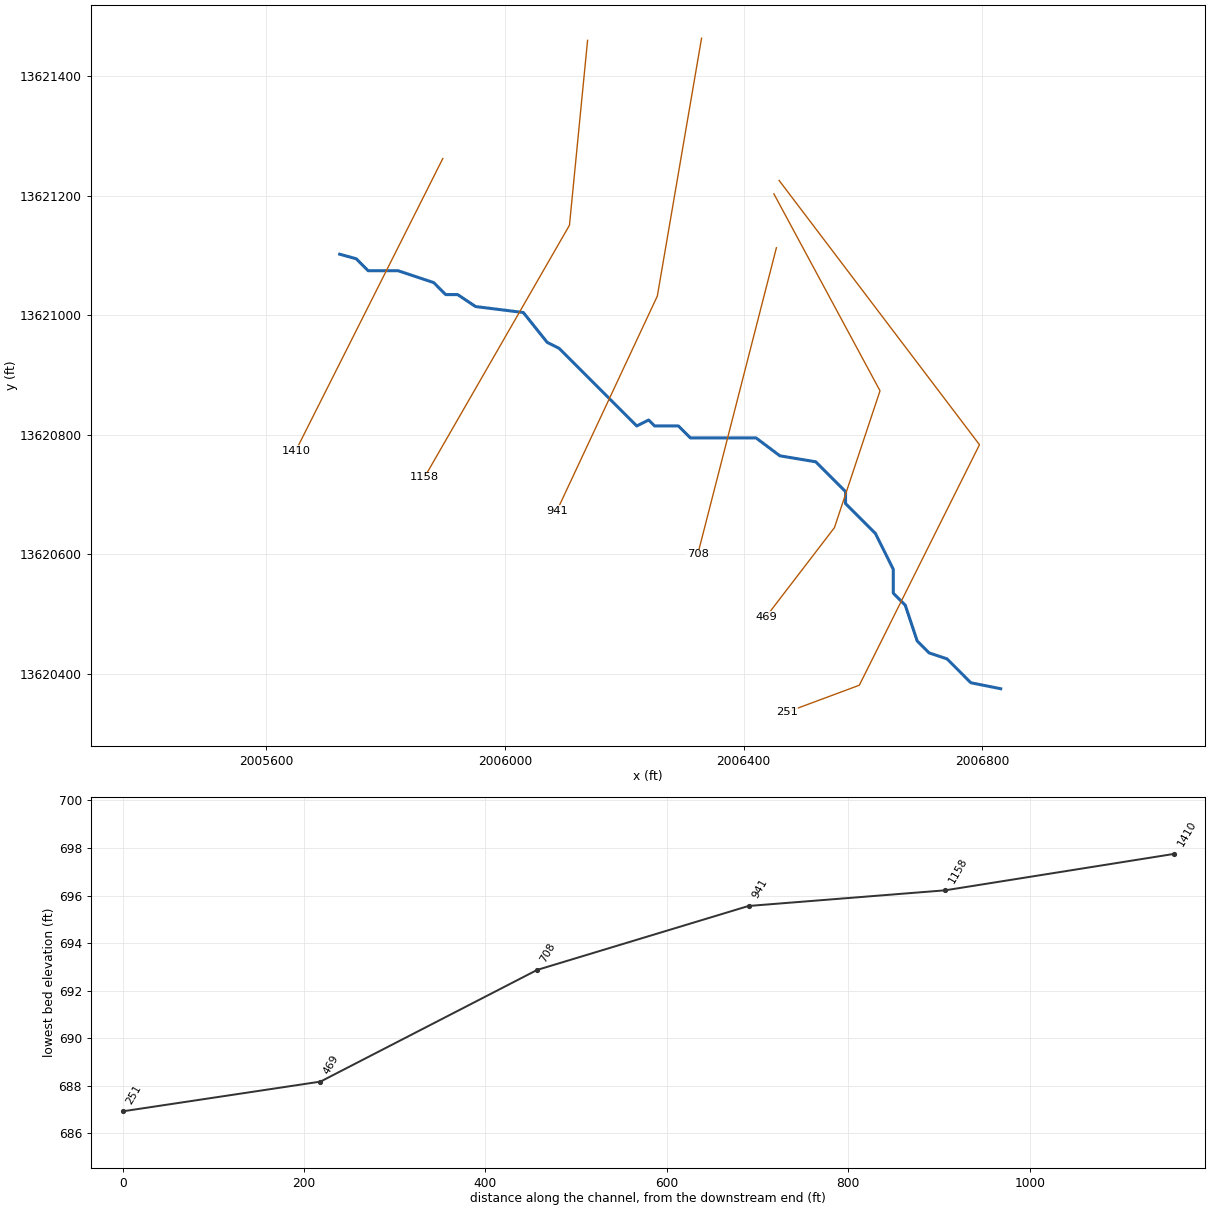
--- UNT 121 in HW.prj (project) ---

Proj Title=UNT 121 in HW Base Level Engineering
Current Plan=p01
Default Exp/Contr=0.3,0.1
English Units
Geom File=g01
Flow File=f01
Plan File=p01
BEGIN DESCRIPTION:
UNT 121 in HW
END DESCRIPTION:

--- UNT 121 in HW.p01 (plan) ---

Plan Title=Multiple Run
Short Identifier=Multiple
Geom File=g01
Flow File=f01
Subcritical Flow
K Sum by GR= 0
Std Step Tol= 0.01
Critical Tol= 0.01
Num of Std Step Trials= 20
Max Error Tol= 0.3
Flow Tol Ratio= 0.001
Split Flow NTrial= 30
Split Flow Tol= 0.02
Split Flow Ratio= 0.02
Log Output Level= 0
Friction Slope Method= 1
Unsteady Friction Slope Method= 2
Unsteady Bridges Friction Slope Method= 1
Parabolic Critical Depth
Global Vel Dist=  1 , 1 , 1
Global Log Level= 0
CheckData=True
Encroach Param= -1, 0, 0, 0
BEGIN DESCRIPTION:
Multiple Run
END DESCRIPTION:

--- UNT 121 in HW.f01 (steady flow) ---

Flow Title=Multiple
Number of Profiles=7
Profile Names=10-year,25-year,50-year,1pct_min,100-year,1pct_plu,500-year
River Rch & RM= UNT 121 in HW,Reach-1,1410
     521     730     905     555    1108    2210    1667
Boundary for River Rch & Prof#=UNT 121 in HW,Reach-1,1
Up Type=0
Dn Type=3
Dn Slope=0.005
Boundary for River Rch & Prof#=UNT 121 in HW,Reach-1,2
Up Type=0
Dn Type=3
Dn Slope=0.005
Boundary for River Rch & Prof#=UNT 121 in HW,Reach-1,3
Up Type=0
Dn Type=3
Dn Slope=0.005
Boundary for River Rch & Prof#=UNT 121 in HW,Reach-1,4
Up Type=0
Dn Type=3
Dn Slope=0.005
Boundary for River Rch & Prof#=UNT 121 in HW,Reach-1,5
Up Type=0
Dn Type=3
Dn Slope=0.005
Boundary for River Rch & Prof#=UNT 121 in HW,Reach-1,6
Up Type=0
Dn Type=3
Dn Slope=0.005
Boundary for River Rch & Prof#=UNT 121 in HW,Reach-1,7
Up Type=0
Dn Type=3
Dn Slope=0.005

--- UNT 121 in HW.g01 (geometry) ---

Geom Title=Existing Conditions

River Reach=UNT 121 in HW,Reach-1
Reach XY= 30
      2005723.17     13621102.17      2005750.80     13621094.54
      2005770.80     13621074.54      2005820.80     13621074.54
      2005880.80     13621054.54      2005900.80     13621034.54
      2005920.80     13621034.54      2005950.80     13621014.54
      2006030.80     13621004.54      2006070.80     13620954.54
      2006090.80     13620944.54      2006220.80     13620814.54
      2006240.80     13620824.54      2006250.80     13620814.54
      2006290.80     13620814.54      2006310.80     13620794.54
      2006420.80     13620794.54      2006460.80     13620764.54
      2006520.80     13620754.54      2006570.80     13620704.54
      2006570.80     13620684.54      2006620.80     13620634.54
      2006650.80     13620574.54      2006650.80     13620534.54
      2006670.80     13620514.54      2006690.80     13620454.54
      2006710.80     13620434.54      2006740.80     13620424.54
      2006780.80     13620384.54      2006830.80     13620374.54

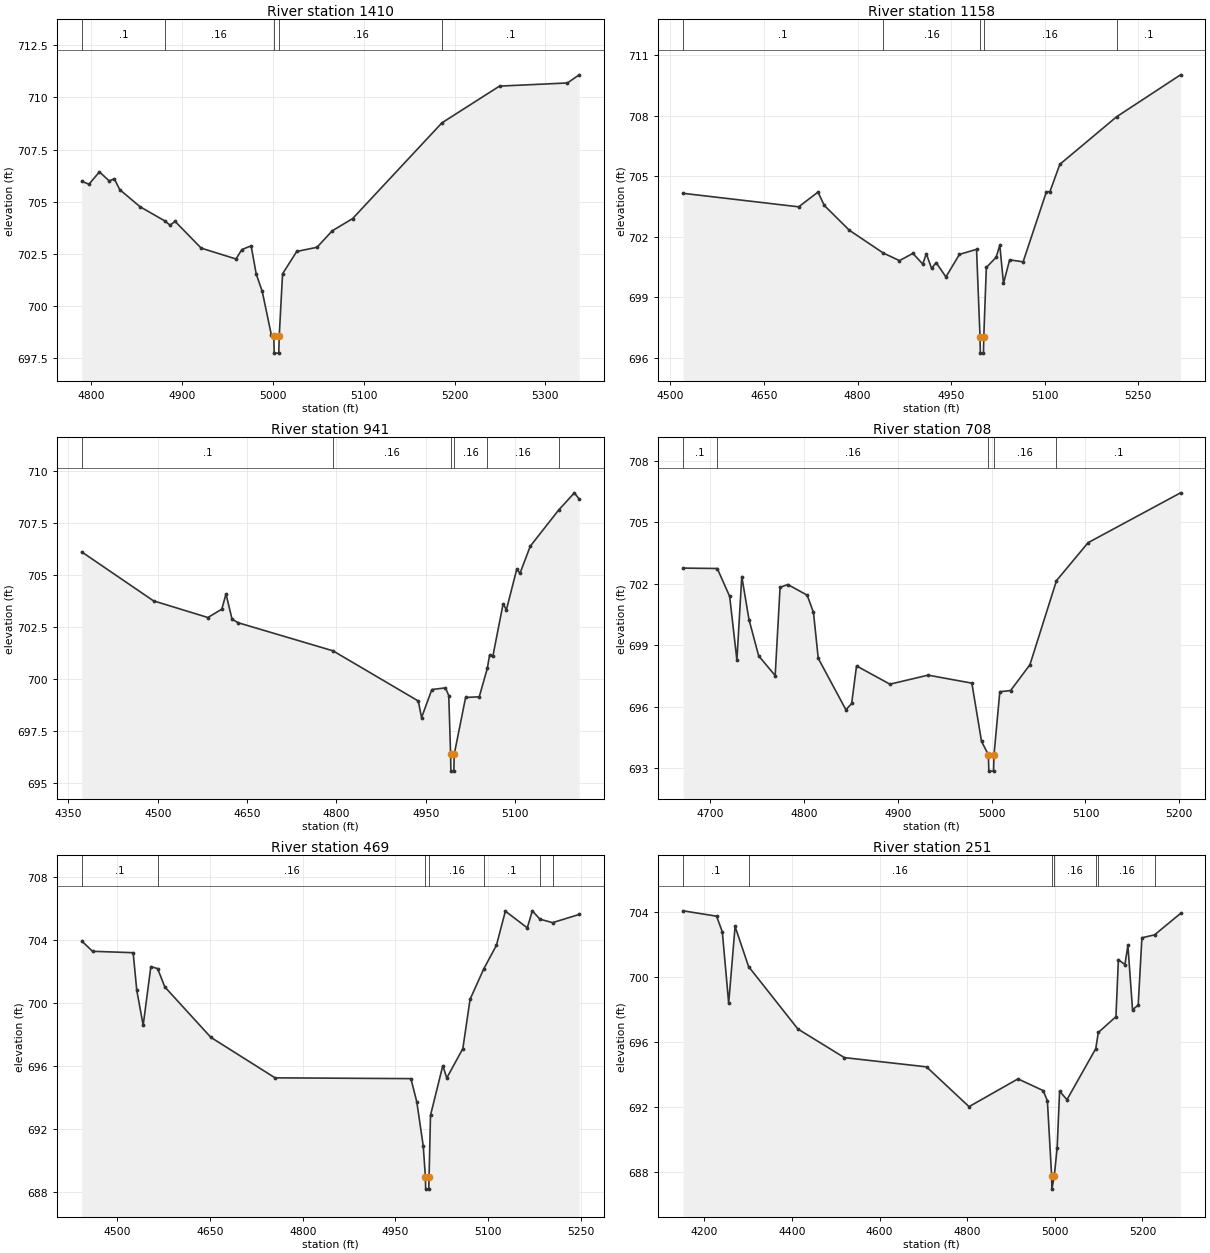
Type RM Length L Ch R = 1,1410,252,252,252
BEGIN DESCRIPTION:
UNT 121 in HW 1.0
END DESCRIPTION:
XS GIS Cut Line= 2
      2005895.91     13621262.37      2005649.67     13620773.37
#Sta/Elev= 30
  4789.7  705.98  4797.6  705.84  4809.1  706.43  4819.9  706.00  4825.5  706.10
  4831.5  705.58  4853.9  704.76  4881.2  704.08  4886.8  703.88  4892.4  704.06
  4921.1  702.78  4959.4  702.26  4965.9  702.71  4976.1  702.89  4981.7  701.54
  4988.3  700.71  4998.4  698.61  5001.0  698.55  5001.5  697.75  5006.5  697.75
  5007.0  698.55  5010.7  701.55  5026.3  702.62  5048.6  702.82  5065.4  703.61
  5087.7  704.19  5186.1  708.78  5249.5  710.54  5324.2  710.69  5337.2  711.08
#Mann=5,-1,0
  4789.7     0.1       0  4881.2    0.16       0  5001.0    0.07       0
  5007.0    0.16       0  5186.1     0.1       0
Bank Sta=5001,5007
Exp/Cntr=0.3,0.1

Type RM Length L Ch R = 1,1158,217,217,217
BEGIN DESCRIPTION:
UNT 121 in HW 2.0
END DESCRIPTION:
XS GIS Cut Line= 3
      2006138.50     13621460.27      2006108.14     13621150.69
      2005865.35     13620728.84
#Sta/Elev= 30
  4520.3  704.15  4705.6  703.48  4736.6  704.21  4746.7  703.55  4786.8  702.32
  4841.2  701.19  4867.3  700.81  4888.8  701.17  4904.6  700.64  4910.4  701.15
  4918.7  700.43  4926.2  700.71  4941.8  700.00  4963.5  701.12  4990.9  701.37
  4996.5  697.02  4997.0  696.22  5002.0  696.22  5002.5  697.02  5006.6  700.47
  5022.4  700.98  5028.2  701.58  5034.1  699.68  5044.0  700.85  5065.6  700.75
  5102.9  704.22  5108.7  704.24  5124.5  705.59  5215.6  707.95  5318.1  710.03
#Mann=5,-1,0
  4520.3     0.1       0  4841.2    0.16       0  4996.5    0.07       0
  5002.5    0.16       0  5215.6     0.1       0
Bank Sta=4996.5,5002.5
Exp/Cntr=0.3,0.1

Type RM Length L Ch R = 1,941,233,233,233
BEGIN DESCRIPTION:
UNT 121 in HW 3.0
END DESCRIPTION:
XS GIS Cut Line= 3
      2006329.47     13621463.75      2006255.38     13621032.07
      2006086.86     13620672.05
#Sta/Elev= 30
  4372.4  706.09  4492.9  703.74  4584.2  702.94  4607.6  703.34  4614.6  704.07
  4624.8  702.86  4634.9  702.69  4794.3  701.34  4937.6  698.93  4943.1  698.13
  4960.4  699.48  4983.2  699.56  4988.8  699.19  4991.9  696.36  4992.4  695.56
  4997.4  695.56  4997.9  696.36  5017.1  699.10  5040.0  699.13  5053.6  700.50
  5057.3  701.13  5062.8  701.07  5080.1  703.60  5085.6  703.31  5102.9  705.25
  5108.5  705.07  5125.8  706.37  5173.3  708.10  5199.8  708.93  5207.9  708.63
#Mann=6,-1,0
  4372.4     0.1       0  4794.3    0.16       0  4991.9    0.07       0
  4997.9    0.16       0  5053.6    0.16       0  5173.3     0.1       0
Bank Sta=4991.9,4997.9
Exp/Cntr=0.3,0.1

Type RM Length L Ch R = 1,708,239,239,239
BEGIN DESCRIPTION:
UNT 121 in HW 4.0
END DESCRIPTION:
XS GIS Cut Line= 2
      2006454.91     13621113.01      2006323.08     13620599.56
#Sta/Elev= 30
  4671.2  702.77  4707.6  702.75  4720.8  701.39  4728.5  698.28  4733.7  702.36
  4741.4  700.26  4751.7  698.49  4769.3  697.53  4774.5  701.83  4782.7  701.97
  4803.4  701.45  4810.1  700.61  4815.2  698.37  4844.7  695.86  4850.8  696.17
  4856.0  698.00  4891.6  697.11  4932.3  697.55  4978.9  697.16  4989.2  694.32
  4996.5  693.67  4997.0  692.87  5002.0  692.87  5002.5  693.67  5008.7  696.74
  5020.2  696.80  5040.8  698.06  5069.1  702.16  5102.8  704.01  5201.3  706.44
#Mann=5,-1,0
  4671.2     0.1       0  4707.6    0.16       0  4996.5    0.07       0
  5002.5    0.16       0  5069.1     0.1       0
Bank Sta=4996.5,5002.5
Exp/Cntr=0.3,0.1

Type RM Length L Ch R = 1,469,218,218,218
BEGIN DESCRIPTION:
UNT 121 in HW 5.0
END DESCRIPTION:
XS GIS Cut Line= 4
      2006450.66     13621203.27      2006628.53     13620873.45
      2006552.14     13620644.28      2006437.56     13620494.98
#Sta/Elev= 30
  4442.7  703.93  4460.1  703.28  4525.8  703.19  4531.6  700.81  4542.0  698.58
  4554.4  702.31  4565.3  702.18  4577.1  701.01  4651.5  697.81  4755.3  695.24
  4975.0  695.19  4984.5  693.72  4995.0  690.90  4998.4  688.97  4998.9  688.17
  5003.9  688.17  5004.4  688.97  5006.7  692.86  5026.6  696.02  5033.0  695.23
  5059.0  697.10  5070.7  700.23  5092.7  702.15  5113.3  703.66  5127.8  705.83
  5163.2  704.77  5171.4  705.85  5183.7  705.32  5204.2  705.10  5247.2  705.62
#Mann=7,-1,0
  4442.7     0.1       0  4565.3    0.16       0  4998.4    0.07       0
  5004.4    0.16       0  5092.7     0.1       0  5183.7    0.16       0
  5204.2     0.1       0
Bank Sta=4998.4,5004.4
Exp/Cntr=0.3,0.1

Type RM Length L Ch R = 1,251,0,0,0
BEGIN DESCRIPTION:
UNT 121 in HW 6.0
END DESCRIPTION:
XS GIS Cut Line= 4
      2006459.35     13621225.84      2006795.20     13620783.17
      2006593.81     13620380.39      2006472.29     13620335.26
#Sta/Elev= 30
  4151.4  704.06  4227.8  703.73  4240.9  702.76  4255.4  698.37  4270.0  703.10
  4300.8  700.63  4413.5  696.78  4519.6  695.02  4707.1  694.45  4804.1  692.00
  4915.9  693.71  4973.3  692.99  4983.0  692.36  4992.7  687.72  4993.2  686.92
  4998.7  687.72  5005.3  689.47  5010.9  692.95  5027.7  692.43  5093.4  695.57
  5099.3  696.57  5139.5  697.54  5145.1  701.05  5160.0  700.75  5166.8  701.93
  5177.4  697.97  5190.3  698.25  5198.8  702.40  5227.6  702.58  5287.0  703.90
#Mann=7,-1,0
  4151.4     0.1       0  4300.8    0.16       0  4992.7    0.07       0
  4998.7    0.16       0  5093.4     0.1       0  5099.3    0.16       0
  5227.6     0.1       0
Bank Sta=4992.7,4998.7
Exp/Cntr=0.3,0.1

Chan Stop Cuts=-1