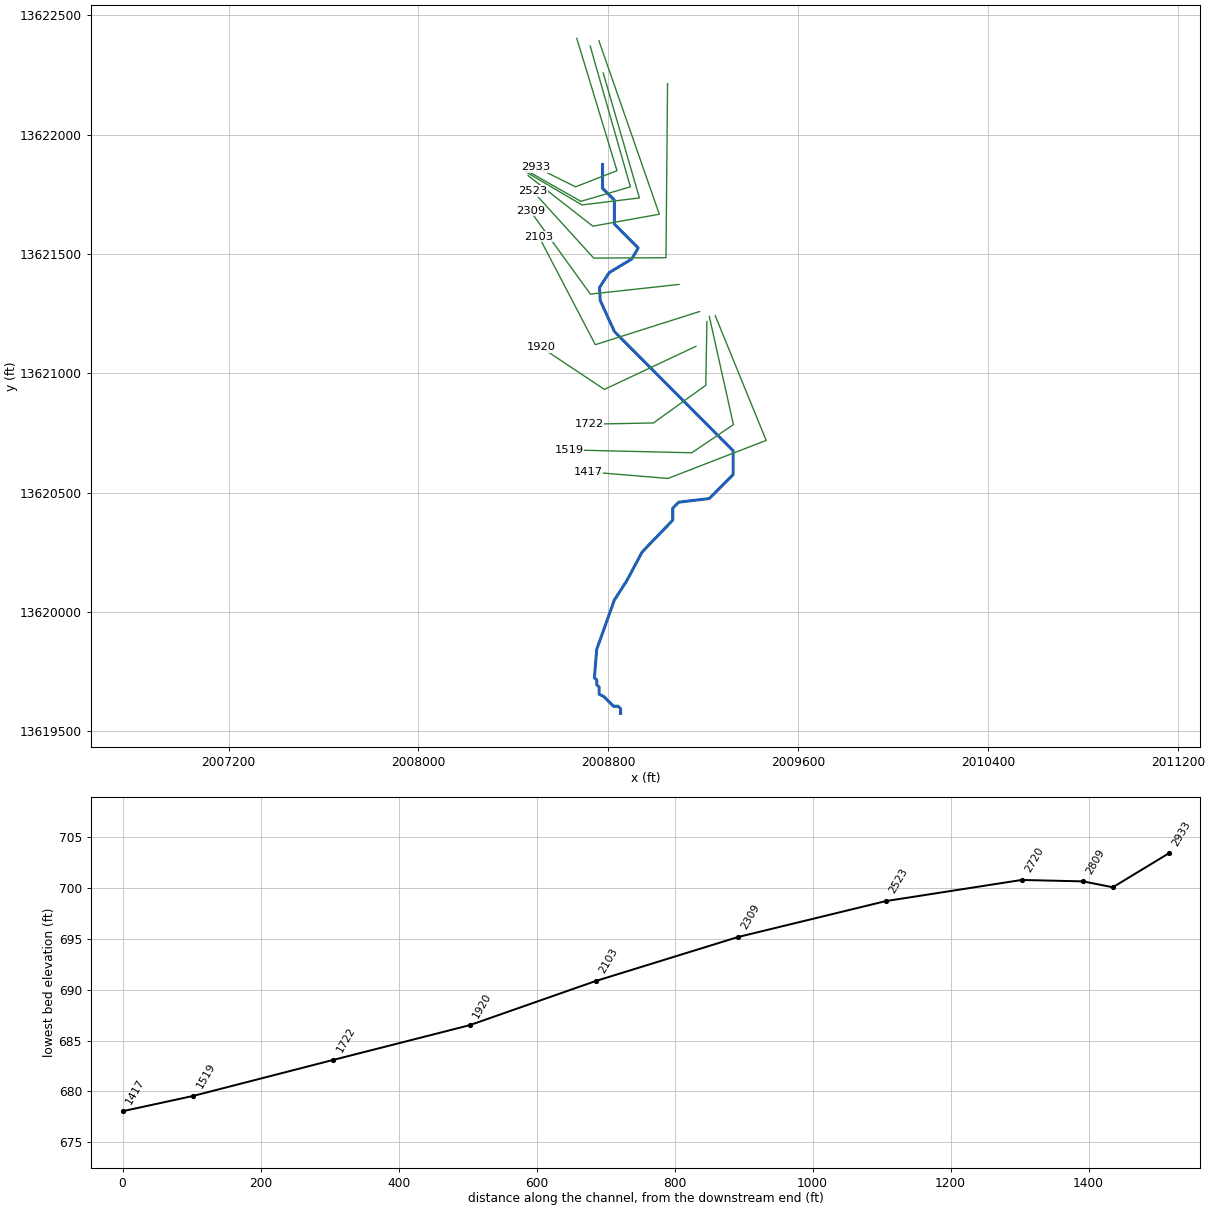
--- UNT 122 in HW.prj (project) ---

Proj Title=UNT 122 in HW Base Level Engineering
Current Plan=p01
Default Exp/Contr=0.3,0.1
English Units
Geom File=g01
Flow File=f01
Plan File=p01
BEGIN DESCRIPTION:
UNT 122 in HW
END DESCRIPTION:

--- UNT 122 in HW.p01 (plan) ---

Plan Title=Multiple Run
Short Identifier=Multiple
Geom File=g01
Flow File=f01
Subcritical Flow
K Sum by GR= 0
Std Step Tol= 0.01
Critical Tol= 0.01
Num of Std Step Trials= 20
Max Error Tol= 0.3
Flow Tol Ratio= 0.001
Split Flow NTrial= 30
Split Flow Tol= 0.02
Split Flow Ratio= 0.02
Log Output Level= 0
Friction Slope Method= 1
Unsteady Friction Slope Method= 2
Unsteady Bridges Friction Slope Method= 1
Parabolic Critical Depth
Global Vel Dist=  1 , 1 , 1
Global Log Level= 0
CheckData=True
Encroach Param= -1, 0, 0, 0
BEGIN DESCRIPTION:
Multiple Run
END DESCRIPTION:

--- UNT 122 in HW.f01 (steady flow) ---

Flow Title=Multiple
Number of Profiles=7
Profile Names=10-year,25-year,50-year,1pct_min,100-year,1pct_plu,500-year
River Rch & RM= UNT 122 in HW,Reach-1,2933
      84     103     117      66     132     263     167
Boundary for River Rch & Prof#=UNT 122 in HW,Reach-1,1
Up Type=0
Dn Type=3
Dn Slope=0.005
Boundary for River Rch & Prof#=UNT 122 in HW,Reach-1,2
Up Type=0
Dn Type=3
Dn Slope=0.005
Boundary for River Rch & Prof#=UNT 122 in HW,Reach-1,3
Up Type=0
Dn Type=3
Dn Slope=0.005
Boundary for River Rch & Prof#=UNT 122 in HW,Reach-1,4
Up Type=0
Dn Type=3
Dn Slope=0.005
Boundary for River Rch & Prof#=UNT 122 in HW,Reach-1,5
Up Type=0
Dn Type=3
Dn Slope=0.005
Boundary for River Rch & Prof#=UNT 122 in HW,Reach-1,6
Up Type=0
Dn Type=3
Dn Slope=0.005
Boundary for River Rch & Prof#=UNT 122 in HW,Reach-1,7
Up Type=0
Dn Type=3
Dn Slope=0.005

--- UNT 122 in HW.g01 (geometry) ---

Geom Title=Existing Conditions

River Reach=UNT 122 in HW,Reach-1
Reach XY= 30
      2008775.00     13621875.00      2008775.00     13621775.00
      2008825.00     13621725.00      2008825.00     13621625.00
      2008925.00     13621525.00      2008897.72     13621478.41
      2008803.31     13621421.99      2008762.08     13621359.05
      2008765.34     13621304.80      2008825.00     13621175.00
      2009325.00     13620675.00      2009325.00     13620575.00
      2009225.00     13620475.00      2009095.80     13620459.54
      2009070.80     13620434.54      2009070.80     13620384.54
      2008941.44     13620250.34      2008876.16     13620128.81
      2008824.77     13620049.64      2008750.47     13619842.70
      2008740.80     13619724.54      2008750.80     13619714.54
      2008750.80     13619694.54      2008760.80     13619684.54
      2008760.80     13619654.54      2008780.80     13619644.54
      2008820.80     13619604.54      2008840.80     13619604.54
      2008850.80     13619594.54      2008850.80     13619574.54

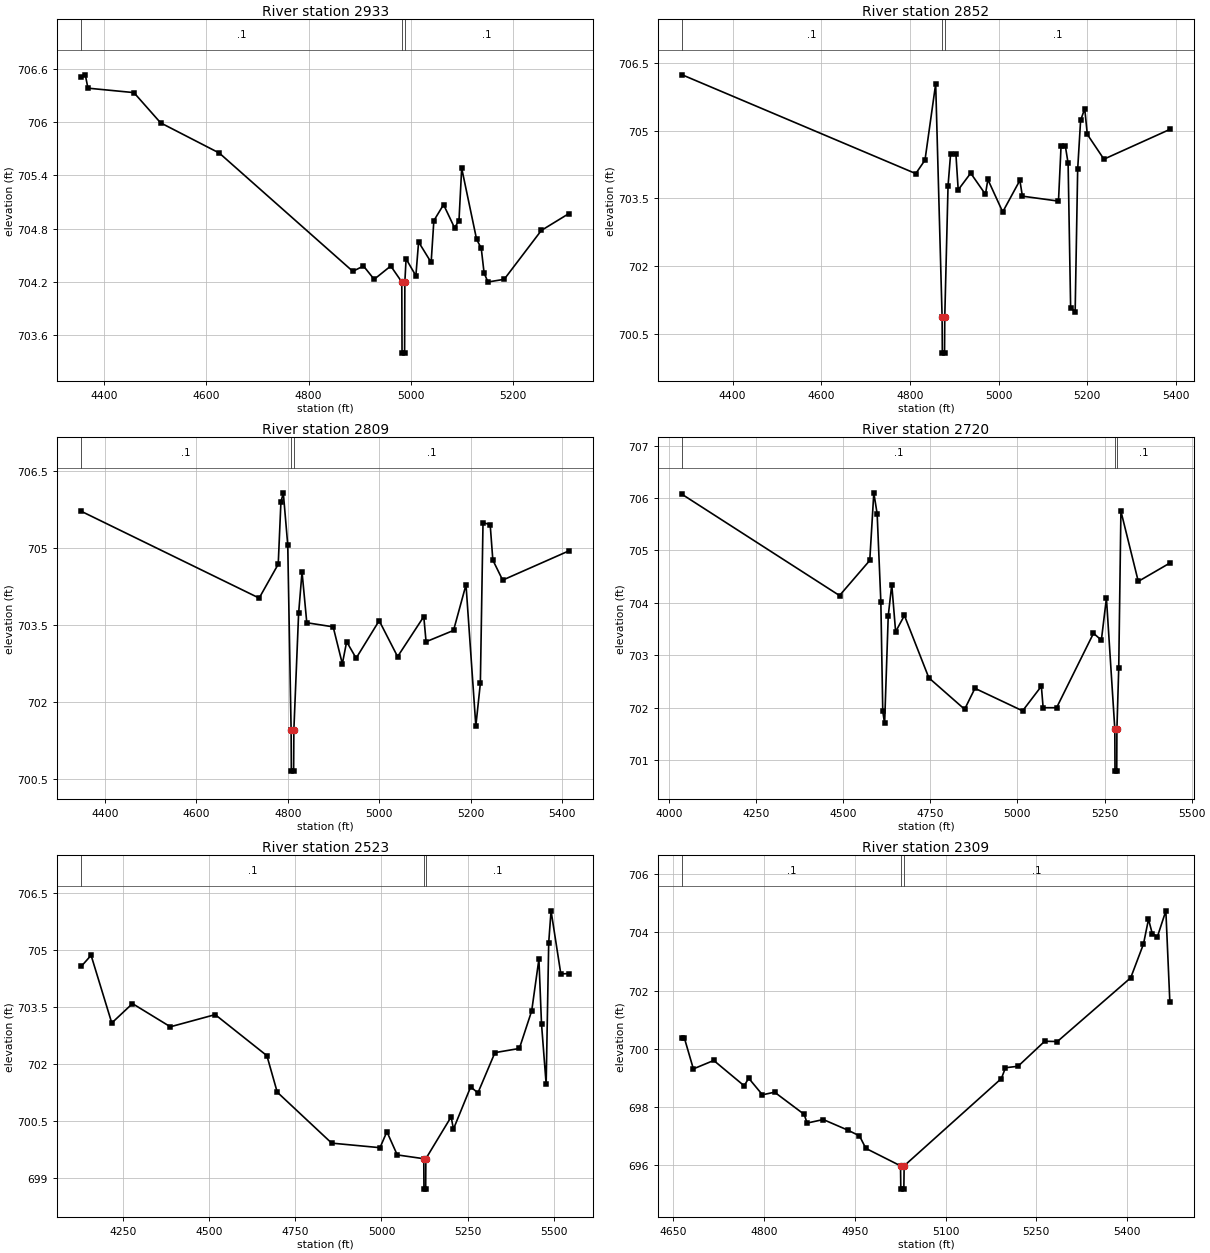
Type RM Length L Ch R = 1,2933,81,81,81
BEGIN DESCRIPTION:
UNT 122 in HW 1.0
END DESCRIPTION:
XS GIS Cut Line= 4
      2008666.52     13622403.55      2008835.78     13621848.89
      2008661.29     13621781.25      2008492.84     13621864.61
#Sta/Elev= 30
  4354.9  706.51  4362.7  706.53  4367.9  706.38  4457.9  706.33  4510.2  705.99
  4625.2  705.65  4886.6  704.32  4907.5  704.38  4928.4  704.23  4960.9  704.38
  4982.5  704.20  4983.0  703.40  4988.0  703.40  4988.5  704.20  4990.9  704.46
  5010.1  704.27  5015.4  704.65  5040.0  704.42  5045.3  704.89  5064.3  705.07
  5085.8  704.81  5094.5  704.89  5099.8  705.48  5129.0  704.68  5138.1  704.58
  5143.7  704.30  5151.3  704.20  5183.0  704.23  5255.8  704.78  5309.9  704.97
#Mann=3,-1,0
  4354.9     0.1       0  4982.5    0.07       0  4988.5     0.1       0
Bank Sta=4982.5,4988.5
Exp/Cntr=0.3,0.1

Type RM Length L Ch R = 1,2852,43,43,43
BEGIN DESCRIPTION:
UNT 122 in HW 13.0
END DESCRIPTION:
XS GIS Cut Line= 4
      2008722.93     13622371.48      2008892.21     13621781.18
      2008683.87     13621720.42      2008449.75     13621852.65
#Sta/Elev= 30
  4286.4  706.24  4813.3  704.05  4834.1  704.35  4858.2  706.04  4872.7  700.87
  4873.2  700.07  4878.2  700.07  4878.7  700.87  4886.1  703.78  4891.9  704.49
  4903.8  704.49  4909.0  703.69  4937.2  704.06  4970.5  703.59  4975.9  703.92
  5009.4  703.20  5048.1  703.90  5053.8  703.55  5135.2  703.44  5141.0  704.66
  5150.7  704.66  5156.9  704.28  5162.6  701.08  5172.8  700.99  5178.5  704.15
  5185.1  705.23  5194.4  705.49  5200.2  704.92  5237.7  704.37  5386.4  705.03
#Mann=3,-1,0
  4286.4     0.1       0  4872.7    0.07       0  4878.7     0.1       0
Bank Sta=4872.7,4878.7
Exp/Cntr=0.3,0.1

Type RM Length L Ch R = 1,2809,89,89,89
BEGIN DESCRIPTION:
Mapping XS b7e9f166
END DESCRIPTION:
XS GIS Cut Line= 4
      2008777.78     13622258.73      2008930.27     13621734.70
      2008688.30     13621705.41      2008448.75     13621845.68
#Sta/Elev= 30
  4348.2  705.71  4737.4  704.02  4779.1  704.68  4785.0  705.89  4790.2  706.07
  4799.9  705.06  4807.3  701.45  4807.8  700.65  4812.8  700.65  4813.3  701.45
  4823.7  703.72  4831.2  704.53  4841.6  703.54  4899.3  703.46  4919.4  702.74
  4928.8  703.17  4949.6  702.85  5000.0  703.58  5040.3  702.88  5097.6  703.66
  5102.6  703.17  5162.7  703.39  5190.0  704.28  5211.5  701.53  5221.4  702.36
  5227.2  705.49  5242.9  705.45  5248.7  704.76  5270.2  704.37  5415.3  704.94
#Mann=3,-1,0
  4348.2     0.1       0  4807.3    0.07       0  4813.3     0.1       0
Bank Sta=4807.3,4813.3
Exp/Cntr=0.3,0.1

Type RM Length L Ch R = 1,2720,197,197,197
BEGIN DESCRIPTION:
UNT 122 in HW 2.0
END DESCRIPTION:
XS GIS Cut Line= 4
      2008759.84     13622393.12      2009014.08     13621666.39
      2008734.20     13621616.32      2008461.66     13621828.11
#Sta/Elev= 30
  4038.0  706.07  4489.5  704.14  4576.3  704.81  4587.9  706.10  4597.5  705.70
  4608.1  704.02  4613.6  701.93  4618.9  701.70  4629.3  703.75  4639.4  704.35
  4650.5  703.45  4675.7  703.76  4745.8  702.57  4848.5  701.97  4878.1  702.37
  5014.9  701.94  5068.7  702.41  5073.8  702.00  5112.4  702.00  5218.3  703.42
  5240.9  703.29  5255.4  704.09  5279.5  701.59  5280.0  700.79  5285.0  700.79
  5285.5  701.59  5290.7  702.75  5297.0  705.75  5346.8  704.41  5437.4  704.76
#Mann=3,-1,0
  4038.0     0.1       0  5279.5    0.07       0  5285.5     0.1       0
Bank Sta=5279.5,5285.5
Exp/Cntr=0.3,0.1

Type RM Length L Ch R = 1,2523,214,214,214
BEGIN DESCRIPTION:
UNT 122 in HW 3.0
END DESCRIPTION:
XS GIS Cut Line= 4
      2009048.76     13622213.35      2009042.25     13621484.17
      2008737.67     13621482.64      2008480.76     13621763.86
#Sta/Elev= 30
  4129.2  704.57  4157.6  704.86  4217.6  703.08  4277.6  703.59  4387.6  702.98
  4517.6  703.30  4667.6  702.22  4697.6  701.26  4855.5  699.92  4995.7  699.80
  5015.7  700.22  5045.7  699.61  5122.7  699.51  5123.2  698.71  5128.2  698.71
  5128.7  699.51  5202.0  700.61  5208.8  700.29  5258.8  701.40  5279.7  701.24
  5329.1  702.30  5400.0  702.41  5435.8  703.40  5456.7  704.76  5464.2  703.06
  5477.7  701.47  5485.1  705.19  5491.9  706.03  5520.3  704.37  5543.9  704.38
#Mann=3,-1,0
  4129.2     0.1       0  5122.7    0.07       0  5128.7     0.1       0
Bank Sta=5122.7,5128.7
Exp/Cntr=0.3,0.1

Type RM Length L Ch R = 1,2309,206,206,206
BEGIN DESCRIPTION:
UNT 122 in HW 4.0
END DESCRIPTION:
XS GIS Cut Line= 3
      2009096.91     13621372.15      2008723.79     13621331.60
      2008470.50     13621680.30
#Sta/Elev= 30
  4664.6  700.38  4668.1  700.38  4683.1  699.31  4716.8  699.60  4767.1  698.73
  4774.6  698.99  4797.3  698.42  4817.4  698.51  4866.2  697.75  4871.2  697.45
  4897.9  697.57  4938.1  697.21  4957.7  697.01  4968.3  696.58  5025.6  695.98
  5026.1  695.18  5031.1  695.18  5031.6  695.98  5192.4  698.98  5199.1  699.35
  5219.9  699.40  5264.0  700.26  5284.9  700.25  5406.2  702.44  5427.3  703.60
  5435.6  704.45  5441.8  703.96  5450.3  703.85  5464.3  704.74  5470.9  701.61
#Mann=3,-1,0
  4664.6     0.1       0  5025.6    0.07       0  5031.6     0.1       0
Bank Sta=5025.6,5031.6
Exp/Cntr=0.3,0.1

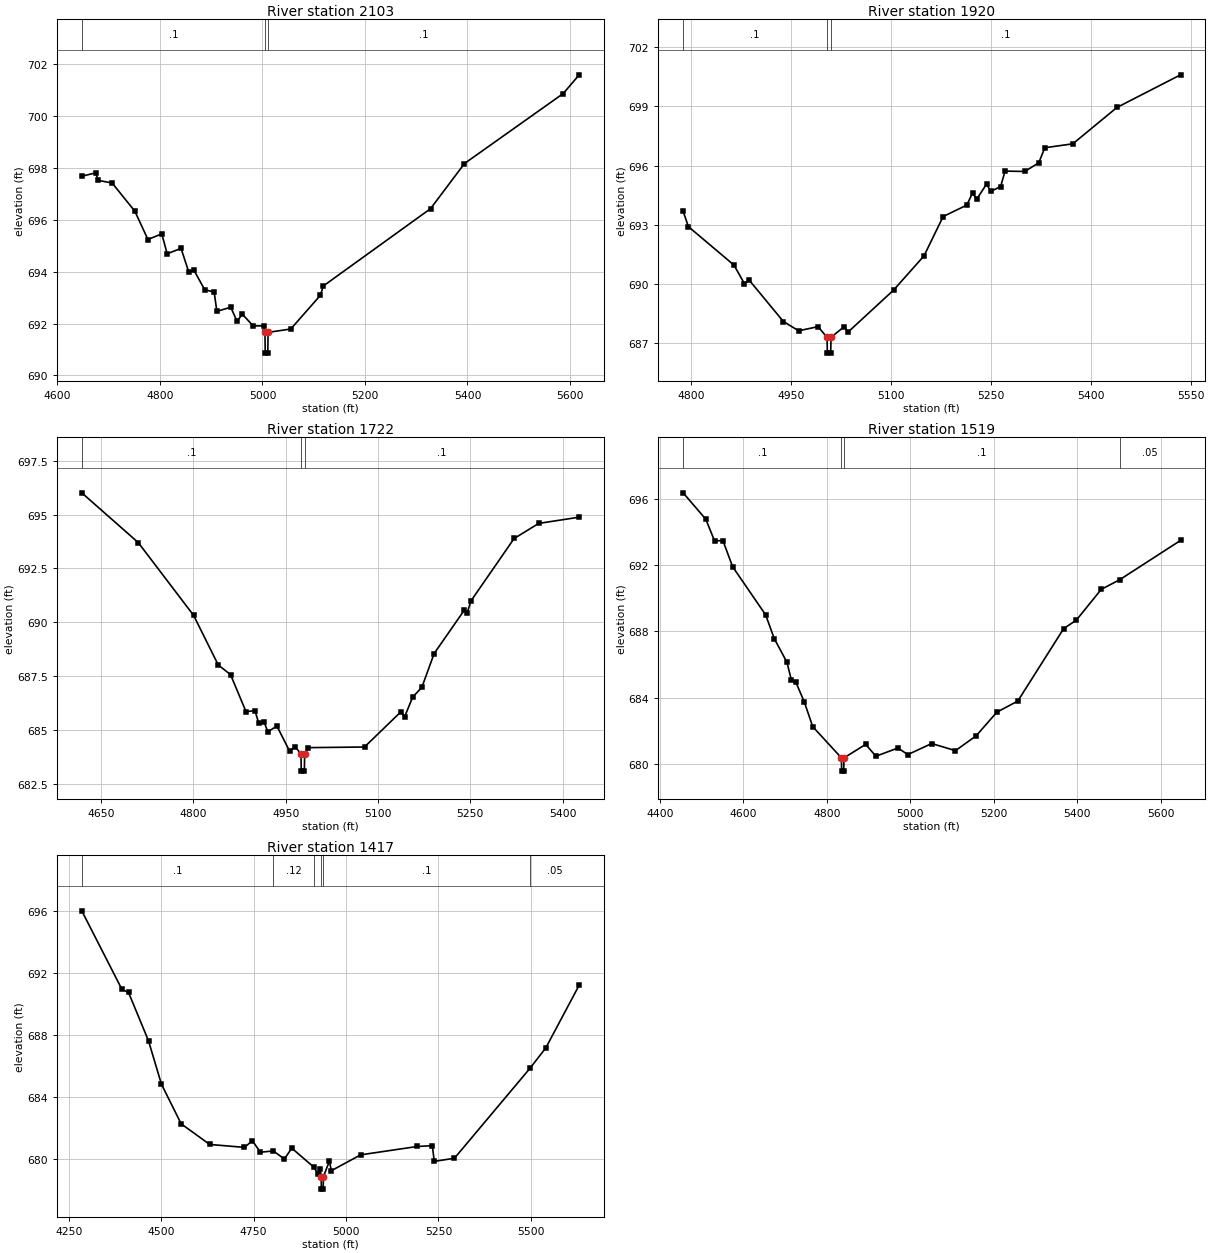
Type RM Length L Ch R = 1,2103,183,183,183
BEGIN DESCRIPTION:
UNT 122 in HW 5.0
END DESCRIPTION:
XS GIS Cut Line= 3
      2009183.82     13621258.67      2008744.62     13621119.80
      2008507.56     13621571.42
#Sta/Elev= 30
  4647.4  697.68  4674.3  697.81  4679.5  697.52  4706.6  697.42  4751.0  696.33
  4776.5  695.24  4803.5  695.46  4814.0  694.69  4841.1  694.90  4855.9  694.00
  4866.4  694.05  4887.4  693.30  4905.7  693.22  4911.0  692.47  4938.1  692.63
  4950.3  692.09  4960.8  692.36  4981.8  691.91  5002.7  691.91  5004.9  691.66
  5005.4  690.86  5010.4  690.86  5010.9  691.66  5055.2  691.79  5113.1  693.09
  5118.8  693.45  5328.0  696.43  5394.2  698.17  5587.0  700.87  5618.1  701.59
#Mann=3,-1,0
  4647.4     0.1       0  5004.9    0.07       0  5010.9     0.1       0
Bank Sta=5004.9,5010.9
Exp/Cntr=0.3,0.1

Type RM Length L Ch R = 1,1920,198,198,198
BEGIN DESCRIPTION:
UNT 122 in HW 6.0
END DESCRIPTION:
XS GIS Cut Line= 3
      2009168.25     13621112.86      2008782.81     13620932.30
      2008515.47     13621109.36
#Sta/Elev= 30
  4788.6  693.69  4796.5  692.91  4865.0  690.96  4880.5  690.03  4887.8  690.20
  4939.0  688.11  4961.9  687.64  4991.0  687.85  5004.5  687.31  5005.0  686.51
  5010.0  686.51  5010.5  687.31  5030.3  687.85  5035.9  687.57  5104.4  689.70
  5150.0  691.43  5178.7  693.42  5214.2  694.00  5222.9  694.62  5228.9  694.29
  5244.0  695.07  5249.9  694.69  5265.0  694.94  5271.6  695.72  5301.1  695.70
  5322.2  696.14  5331.2  696.90  5373.3  697.10  5439.5  698.94  5534.9  700.59
#Mann=3,-1,0
  4788.6     0.1       0  5004.5    0.07       0  5010.5     0.1       0
Bank Sta=5004.5,5010.5
Exp/Cntr=0.3,0.1

Type RM Length L Ch R = 1,1722,203,203,203
BEGIN DESCRIPTION:
UNT 122 in HW 7.0
END DESCRIPTION:
XS GIS Cut Line= 4
      2009214.56     13621216.77      2009209.90     13620949.66
      2008989.41     13620791.67      2008719.26     13620786.47
#Sta/Elev= 30
  4618.5  696.01  4710.3  693.70  4800.3  690.32  4840.3  688.02  4860.3  687.57
  4885.5  685.85  4900.0  685.90  4906.2  685.31  4914.8  685.37  4920.9  684.92
  4935.7  685.18  4956.5  684.01  4965.1  684.23  4974.8  683.89  4975.3  683.09
  4980.3  683.09  4980.8  683.89  4986.0  684.18  5078.1  684.21  5137.1  685.84
  5143.2  685.61  5156.5  686.53  5171.3  686.98  5191.3  688.55  5240.0  690.55
  5245.0  690.44  5251.3  691.00  5321.3  693.89  5361.3  694.59  5427.1  694.88
#Mann=3,-1,0
  4618.5     0.1       0  4974.8    0.07       0  4980.8     0.1       0
Bank Sta=4974.8,4980.8
Exp/Cntr=0.3,0.1

Type RM Length L Ch R = 1,1519,102,102,102
BEGIN DESCRIPTION:
UNT 122 in HW 8.0
END DESCRIPTION:
XS GIS Cut Line= 4
      2009224.55     13621238.04      2009326.22     13620784.73
      2009150.87     13620666.67      2008635.16     13620678.58
#Sta/Elev= 30
  4455.5  696.39  4509.9  694.79  4530.8  693.48  4550.8  693.50  4574.1  691.92
  4653.3  689.00  4673.8  687.57  4704.2  686.14  4714.8  685.07  4725.1  684.96
  4745.6  683.75  4766.1  682.24  4834.8  680.35  4835.3  679.55  4840.3  679.55
  4840.8  680.35  4892.9  681.17  4917.4  680.45  4970.1  680.95  4993.9  680.55
  5051.0  681.22  5108.0  680.79  5157.3  681.68  5207.3  683.12  5257.4  683.79
  5367.4  688.18  5397.4  688.68  5457.4  690.55  5501.4  691.13  5647.3  693.51
#Mann=4,-1,0
  4455.5     0.1       0  4834.8    0.07       0  4840.8     0.1       0
  5501.4    0.05       0
Bank Sta=4834.8,4840.8
Exp/Cntr=0.3,0.1

Type RM Length L Ch R = 1,1417,0,0,0
BEGIN DESCRIPTION:
UNT 122 in HW 9.0
END DESCRIPTION:
XS GIS Cut Line= 4
      2009249.29     13621241.94      2009464.13     13620718.51
      2009050.17     13620559.03      2008715.14     13620586.81
#Sta/Elev= 30
  4285.1  695.99  4393.8  690.92  4411.5  690.73  4465.6  687.61  4500.5  684.82
  4553.9  682.26  4631.2  680.93  4725.0  680.74  4746.6  681.17  4768.2  680.43
  4803.3  680.51  4833.1  679.99  4853.1  680.69  4912.2  679.48  4924.9  679.01
  4930.3  679.36  4932.7  678.85  4933.2  678.05  4938.2  678.05  4938.7  678.85
  4954.9  679.85  4960.3  679.24  5039.5  680.26  5192.9  680.80  5233.3  680.85
  5238.7  679.84  5293.2  680.04  5497.6  685.84  5540.5  687.16  5630.7  691.20
#Mann=6,-1,0
  4285.1     0.1       0  4803.3    0.12       0  4912.2     0.1       0
  4932.7    0.07       0  4938.7     0.1       0  5497.6    0.05       0
Bank Sta=4932.7,4938.7
Exp/Cntr=0.3,0.1

Chan Stop Cuts=-1