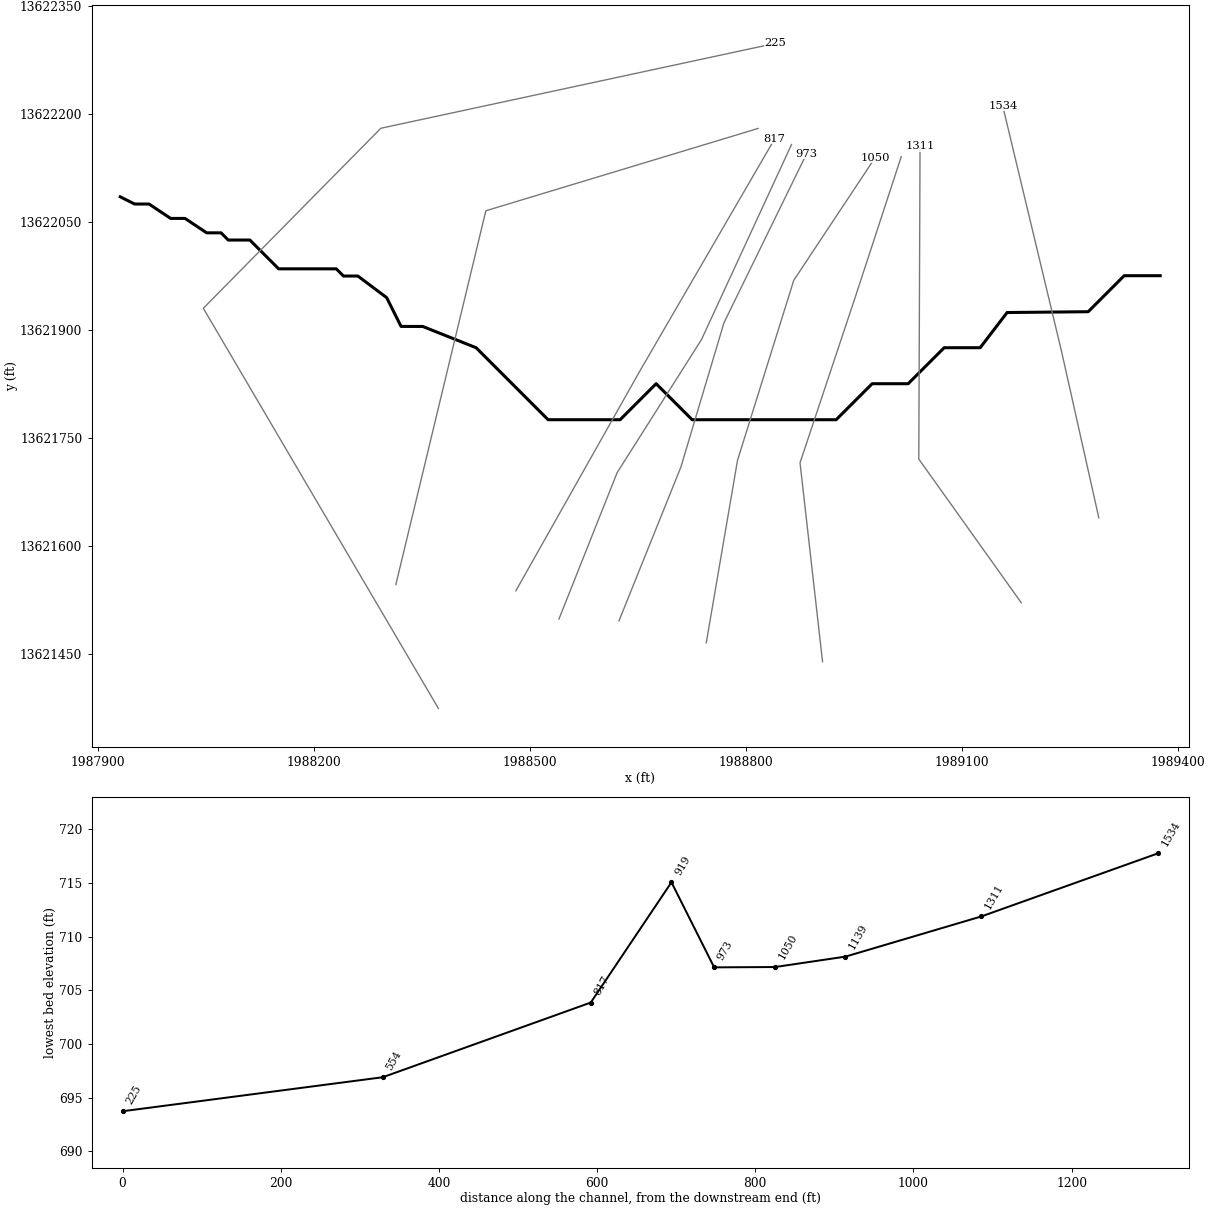
--- UNT 124 in HW.prj (project) ---

Proj Title=UNT 124 in HW Base Level Engineering
Current Plan=p01
Default Exp/Contr=0.3,0.1
English Units
Geom File=g01
Flow File=f01
Plan File=p01
BEGIN DESCRIPTION:
UNT 124 in HW
END DESCRIPTION:

--- UNT 124 in HW.p01 (plan) ---

Plan Title=Multiple Run
Short Identifier=Multiple
Geom File=g01
Flow File=f01
Subcritical Flow
K Sum by GR= 0
Std Step Tol= 0.01
Critical Tol= 0.01
Num of Std Step Trials= 20
Max Error Tol= 0.3
Flow Tol Ratio= 0.001
Split Flow NTrial= 30
Split Flow Tol= 0.02
Split Flow Ratio= 0.02
Log Output Level= 0
Friction Slope Method= 1
Unsteady Friction Slope Method= 2
Unsteady Bridges Friction Slope Method= 1
Parabolic Critical Depth
Global Vel Dist=  1 , 1 , 1
Global Log Level= 0
CheckData=True
Encroach Param= -1, 0, 0, 0
BEGIN DESCRIPTION:
Multiple Run
END DESCRIPTION:

--- UNT 124 in HW.f01 (steady flow) ---

Flow Title=Multiple
Number of Profiles=7
Profile Names=10-year,25-year,50-year,1pct_min,100-year,1pct_plu,500-year
River Rch & RM= UNT 124 in HW,Reach-1,1534
     108     135     155      89     177     354     231
Boundary for River Rch & Prof#=UNT 124 in HW,Reach-1,1
Up Type=0
Dn Type=3
Dn Slope=0.005
Boundary for River Rch & Prof#=UNT 124 in HW,Reach-1,2
Up Type=0
Dn Type=3
Dn Slope=0.005
Boundary for River Rch & Prof#=UNT 124 in HW,Reach-1,3
Up Type=0
Dn Type=3
Dn Slope=0.005
Boundary for River Rch & Prof#=UNT 124 in HW,Reach-1,4
Up Type=0
Dn Type=3
Dn Slope=0.005
Boundary for River Rch & Prof#=UNT 124 in HW,Reach-1,5
Up Type=0
Dn Type=3
Dn Slope=0.005
Boundary for River Rch & Prof#=UNT 124 in HW,Reach-1,6
Up Type=0
Dn Type=3
Dn Slope=0.005
Boundary for River Rch & Prof#=UNT 124 in HW,Reach-1,7
Up Type=0
Dn Type=3
Dn Slope=0.005

--- UNT 124 in HW.g01 (geometry) ---

Geom Title=Existing Conditions

River Reach=UNT 124 in HW,Reach-1
Reach XY= 30
      1989375.00     13621975.00      1989325.00     13621975.00
      1989275.00     13621925.00      1989162.39     13621923.86
      1989125.00     13621875.00      1989075.00     13621875.00
      1989025.00     13621825.00      1988975.00     13621825.00
      1988925.00     13621775.00      1988725.00     13621775.00
      1988675.00     13621825.00      1988625.00     13621775.00
      1988525.00     13621775.00      1988425.00     13621875.00
      1988350.80     13621904.54      1988320.80     13621904.54
      1988300.80     13621944.54      1988260.80     13621974.54
      1988240.80     13621974.54      1988230.80     13621984.54
      1988150.80     13621984.54      1988110.80     13622024.54
      1988080.80     13622024.54      1988070.80     13622034.54
      1988050.80     13622034.54      1988020.80     13622054.54
      1988000.80     13622054.54      1987970.80     13622074.54
      1987950.80     13622074.54      1987930.80     13622084.54

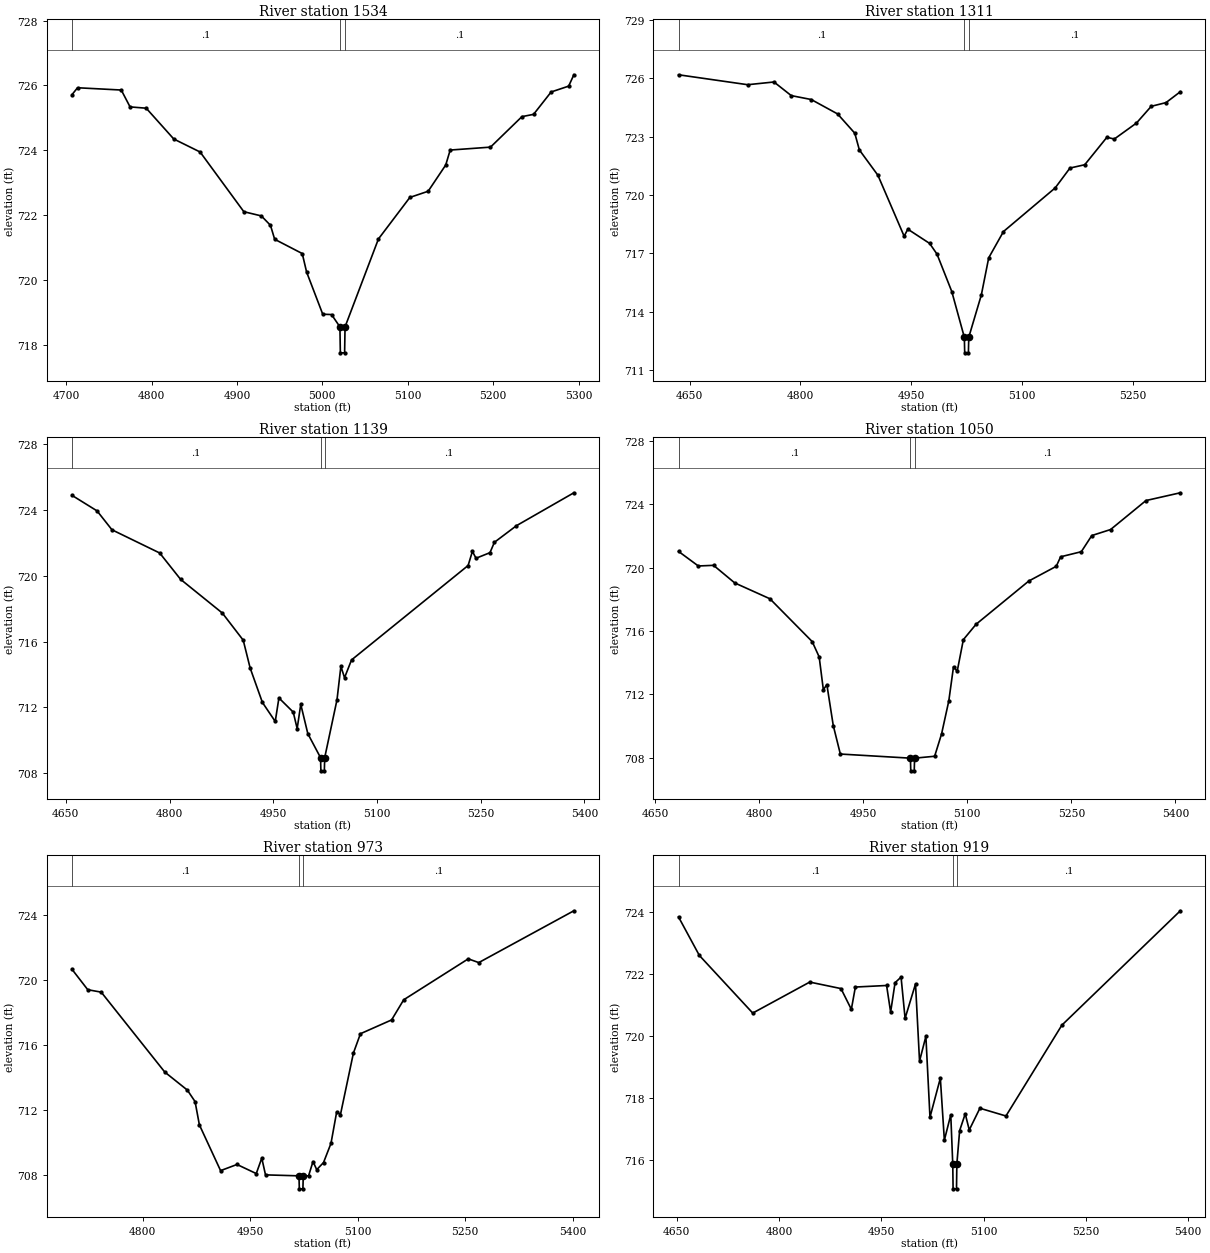
Type RM Length L Ch R = 1,1534,223,223,223
BEGIN DESCRIPTION:
UNT 124 in HW 4.0
END DESCRIPTION:
XS GIS Cut Line= 3
      1989289.76     13621638.77      1989237.85     13621870.49
      1989156.27     13622210.89
#Sta/Elev= 30
  4707.0  725.72  4713.4  725.93  4764.6  725.86  4774.9  725.34  4793.8  725.30
  4826.1  724.35  4856.9  723.95  4908.1  722.11  4928.6  721.98  4939.3  721.69
  4944.2  721.26  4976.5  720.82  4981.6  720.25  5000.5  718.95  5010.8  718.94
  5020.6  718.56  5021.1  717.76  5026.1  717.76  5026.6  718.56  5065.7  721.27
  5102.5  722.55  5123.9  722.74  5144.5  723.55  5149.7  724.01  5196.9  724.10
  5233.7  725.04  5247.3  725.11  5267.9  725.80  5288.4  725.98  5294.5  726.33
#Mann=3,-1,0
  4707.0     0.1       0  5020.6    0.07       0  5026.6     0.1       0
Bank Sta=5020.6,5026.6
Exp/Cntr=0.3,0.1

Type RM Length L Ch R = 1,1311,172,172,172
BEGIN DESCRIPTION:
Mapping XS cc39fa55
END DESCRIPTION:
XS GIS Cut Line= 3
      1989182.14     13621520.70      1989039.76     13621720.38
      1989041.49     13622154.43
#Sta/Elev= 30
  4634.9  726.17  4728.5  725.66  4764.1  725.80  4787.5  725.10  4814.5  724.90
  4850.2  724.16  4873.5  723.17  4879.7  722.31  4904.8  721.01  4940.3  717.88
  4945.3  718.24  4974.8  717.51  4984.8  716.96  5004.8  715.04  5021.8  712.69
  5022.3  711.89  5027.3  711.89  5027.8  712.69  5044.8  714.86  5054.8  716.77
  5074.8  718.12  5144.8  720.36  5164.8  721.38  5184.8  721.55  5214.8  722.96
  5224.8  722.87  5254.8  723.69  5274.8  724.55  5294.8  724.74  5314.2  725.30
#Mann=3,-1,0
  4634.9     0.1       0  5021.8    0.07       0  5027.8     0.1       0
Bank Sta=5021.8,5027.8
Exp/Cntr=0.3,0.1

Type RM Length L Ch R = 1,1139,89,89,89
BEGIN DESCRIPTION:
Mapping XS 33c67cda
END DESCRIPTION:
XS GIS Cut Line= 4
      1988906.08     13621439.10      1988874.83     13621715.18
      1988951.22     13621944.34      1989015.38     13622140.30
#Sta/Elev= 30
  4659.1  724.88  4695.2  723.94  4716.8  722.79  4785.8  721.38  4816.0  719.78
  4876.4  717.73  4906.6  716.08  4916.6  714.39  4934.3  712.30  4952.9  711.14
  4958.2  712.57  4978.9  711.71  4984.6  710.71  4989.8  712.18  5000.0  710.40
  5018.4  708.94  5018.9  708.14  5023.9  708.14  5024.4  708.94  5042.2  712.46
  5047.8  714.49  5053.1  713.80  5063.2  714.88  5231.8  720.62  5238.0  721.48
  5243.2  721.06  5263.4  721.40  5269.8  722.03  5301.7  723.04  5384.7  725.04
#Mann=3,-1,0
  4659.1     0.1       0  5018.4    0.07       0  5024.4     0.1       0
Bank Sta=5018.4,5024.4
Exp/Cntr=0.3,0.1

Type RM Length L Ch R = 1,1050,77,77,77
BEGIN DESCRIPTION:
Mapping XS 910931b1
END DESCRIPTION:
XS GIS Cut Line= 4
      1988744.62     13621465.18      1988788.02     13621718.65
      1988866.15     13621968.65      1988978.97     13622138.75
#Sta/Elev= 30
  4683.8  721.02  4712.3  720.10  4734.3  720.14  4764.8  719.03  4815.5  718.03
  4876.4  715.33  4886.5  714.36  4892.5  712.29  4897.6  712.61  4906.8  710.03
  4917.0  708.23  5018.0  707.97  5018.5  707.17  5023.5  707.17  5024.0  707.97
  5052.9  708.09  5062.9  709.50  5073.3  711.58  5080.1  713.74  5085.4  713.45
  5094.3  715.45  5112.6  716.42  5188.6  719.15  5228.2  720.08  5234.5  720.68
  5264.3  721.00  5279.4  722.02  5306.5  722.40  5357.5  724.23  5407.0  724.72
#Mann=3,-1,0
  4683.8     0.1       0  5018.0    0.07       0  5024.0     0.1       0
Bank Sta=5018,5024
Exp/Cntr=0.3,0.1

Type RM Length L Ch R = 1,973,54,54,54
BEGIN DESCRIPTION:
Mapping XS c369f5ef
END DESCRIPTION:
XS GIS Cut Line= 4
      1988623.43     13621495.71      1988709.38     13621709.27
      1988769.27     13621909.79      1988883.87     13622144.20
#Sta/Elev= 30
  4701.2  720.65  4723.1  719.40  4741.9  719.25  4830.6  714.33  4862.1  713.22
  4872.9  712.51  4878.9  711.08  4908.5  708.26  4931.4  708.64  4958.3  708.08
  4966.0  709.03  4971.2  708.00  5017.9  707.94  5018.4  707.14  5023.4  707.14
  5023.9  707.94  5031.3  707.94  5037.5  708.82  5042.7  708.32  5052.2  708.76
  5062.6  709.94  5070.6  711.89  5075.8  711.71  5093.9  715.50  5103.7  716.69
  5147.2  717.54  5164.1  718.78  5254.2  721.30  5268.9  721.07  5401.6  724.26
#Mann=3,-1,0
  4701.2     0.1       0  5017.9    0.07       0  5023.9     0.1       0
Bank Sta=5017.9,5023.9
Exp/Cntr=0.3,0.1

Type RM Length L Ch R = 1,919,102,102,102
BEGIN DESCRIPTION:
Mapping XS d69d6f07
END DESCRIPTION:
XS GIS Cut Line= 4
      1988540.09     13621498.29      1988620.83     13621701.46
      1988738.02     13621886.36      1988863.01     13622157.17
#Sta/Elev= 30
  4652.6  723.84  4683.1  722.60  4761.4  720.74  4845.0  721.74  4890.8  721.53
  4906.0  720.86  4911.9  721.58  4957.7  721.63  4963.6  720.77  4970.1  721.72
  4978.9  721.90  4984.8  720.57  5000.1  721.68  5006.0  719.19  5015.3  719.99
  5021.3  717.38  5036.5  718.64  5042.4  716.64  5051.8  717.46  5054.7  715.87
  5055.2  715.07  5060.2  715.07  5060.7  715.87  5064.8  716.95  5073.0  717.49
  5078.9  716.97  5094.5  717.67  5132.7  717.42  5214.7  720.35  5388.4  724.04
#Mann=3,-1,0
  4652.6     0.1       0  5054.7    0.07       0  5060.7     0.1       0
Bank Sta=5054.7,5060.7
Exp/Cntr=0.3,0.1

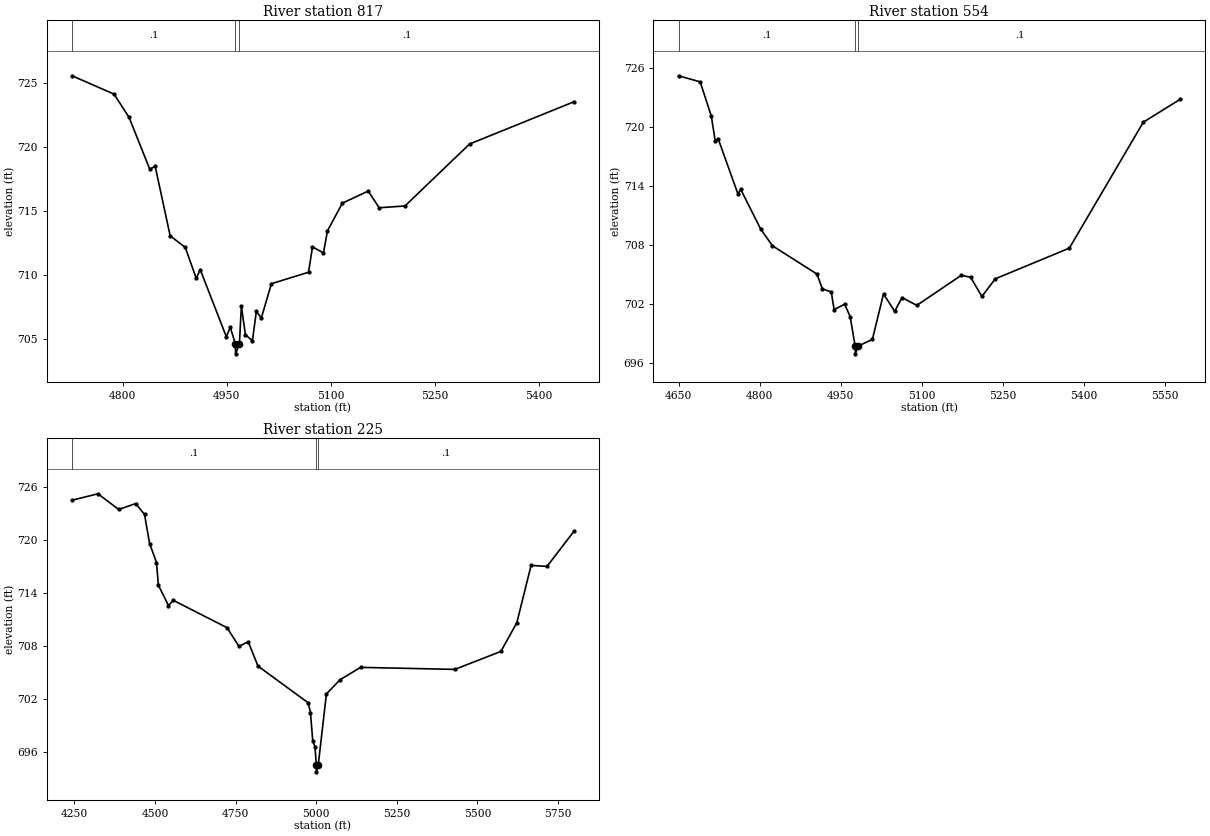
Type RM Length L Ch R = 1,817,263,263,263
BEGIN DESCRIPTION:
Mapping XS a796ed2b
END DESCRIPTION:
XS GIS Cut Line= 3
      1988480.21     13621537.40      1988652.08     13621842.09
      1988839.57     13622164.98
#Sta/Elev= 30
  4727.2  725.54  4787.7  724.11  4809.4  722.29  4839.3  718.24  4846.9  718.50
  4868.6  713.06  4890.3  712.16  4906.2  709.74  4911.9  710.43  4949.5  705.20
  4955.2  705.93  4962.4  704.66  4962.9  703.86  4968.4  704.66  4971.2  707.59
  4977.0  705.35  4987.1  704.88  4992.8  707.17  5000.0  706.66  5014.5  709.33
  5068.0  710.22  5073.7  712.20  5089.5  711.73  5095.3  713.45  5116.8  715.61
  5154.0  716.55  5169.8  715.25  5207.0  715.39  5300.1  720.22  5450.4  723.51
#Mann=3,-1,0
  4727.2     0.1       0  4962.4    0.07       0  4968.4     0.1       0
Bank Sta=4962.4,4968.4
Exp/Cntr=0.3,0.1

Type RM Length L Ch R = 1,554,329,329,329
BEGIN DESCRIPTION:
UNT 124 in HW 2.0
END DESCRIPTION:
XS GIS Cut Line= 3
      1988313.54     13621546.05      1988438.54     13622065.18
      1988816.67     13622179.52
#Sta/Elev= 30
  4649.6  725.18  4689.7  724.56  4710.2  721.10  4717.7  718.50  4722.8  718.80
  4759.6  713.16  4764.7  713.63  4801.5  709.61  4823.4  707.89  4905.7  705.02
  4915.9  703.51  4932.4  703.19  4937.6  701.40  4957.1  701.95  4967.4  700.68
  4976.5  697.70  4977.0  696.90  4982.5  697.70  5008.5  698.37  5029.1  703.00
  5049.7  701.22  5063.4  702.62  5090.8  701.83  5173.1  704.89  5190.3  704.69
  5211.2  702.74  5236.0  704.53  5373.1  707.65  5510.1  720.46  5578.6  722.80
#Mann=3,-1,0
  4649.6     0.1       0  4976.5    0.07       0  4982.5     0.1       0
Bank Sta=4976.5,4982.5
Exp/Cntr=0.3,0.1

Type RM Length L Ch R = 1,225,0,0,0
BEGIN DESCRIPTION:
UNT 124 in HW 1.0
END DESCRIPTION:
XS GIS Cut Line= 4
      1988372.59     13621374.16      1988046.18     13621929.76
      1988292.71     13622179.76      1988840.67     13622297.68
#Sta/Elev= 30
  4242.9  724.54  4323.1  725.27  4387.5  723.49  4440.3  724.16  4467.6  722.92
  4483.3  719.63  4504.7  717.47  4510.6  714.90  4541.9  712.59  4557.0  713.18
  4723.5  710.08  4760.6  707.95  4789.0  708.50  4819.3  705.73  4975.0  701.56
  4982.1  700.46  4989.2  697.25  4996.2  696.56  5000.3  694.53  5000.8  693.73
  5006.3  694.53  5031.6  702.57  5074.0  704.18  5137.6  705.58  5429.8  705.35
  5572.7  707.39  5622.1  710.65  5666.3  717.15  5715.6  717.03  5798.9  721.00
#Mann=3,-1,0
  4242.9     0.1       0  5000.3    0.07       0  5006.3     0.1       0
Bank Sta=5000.3,5006.3
Exp/Cntr=0.3,0.1

Chan Stop Cuts=-1