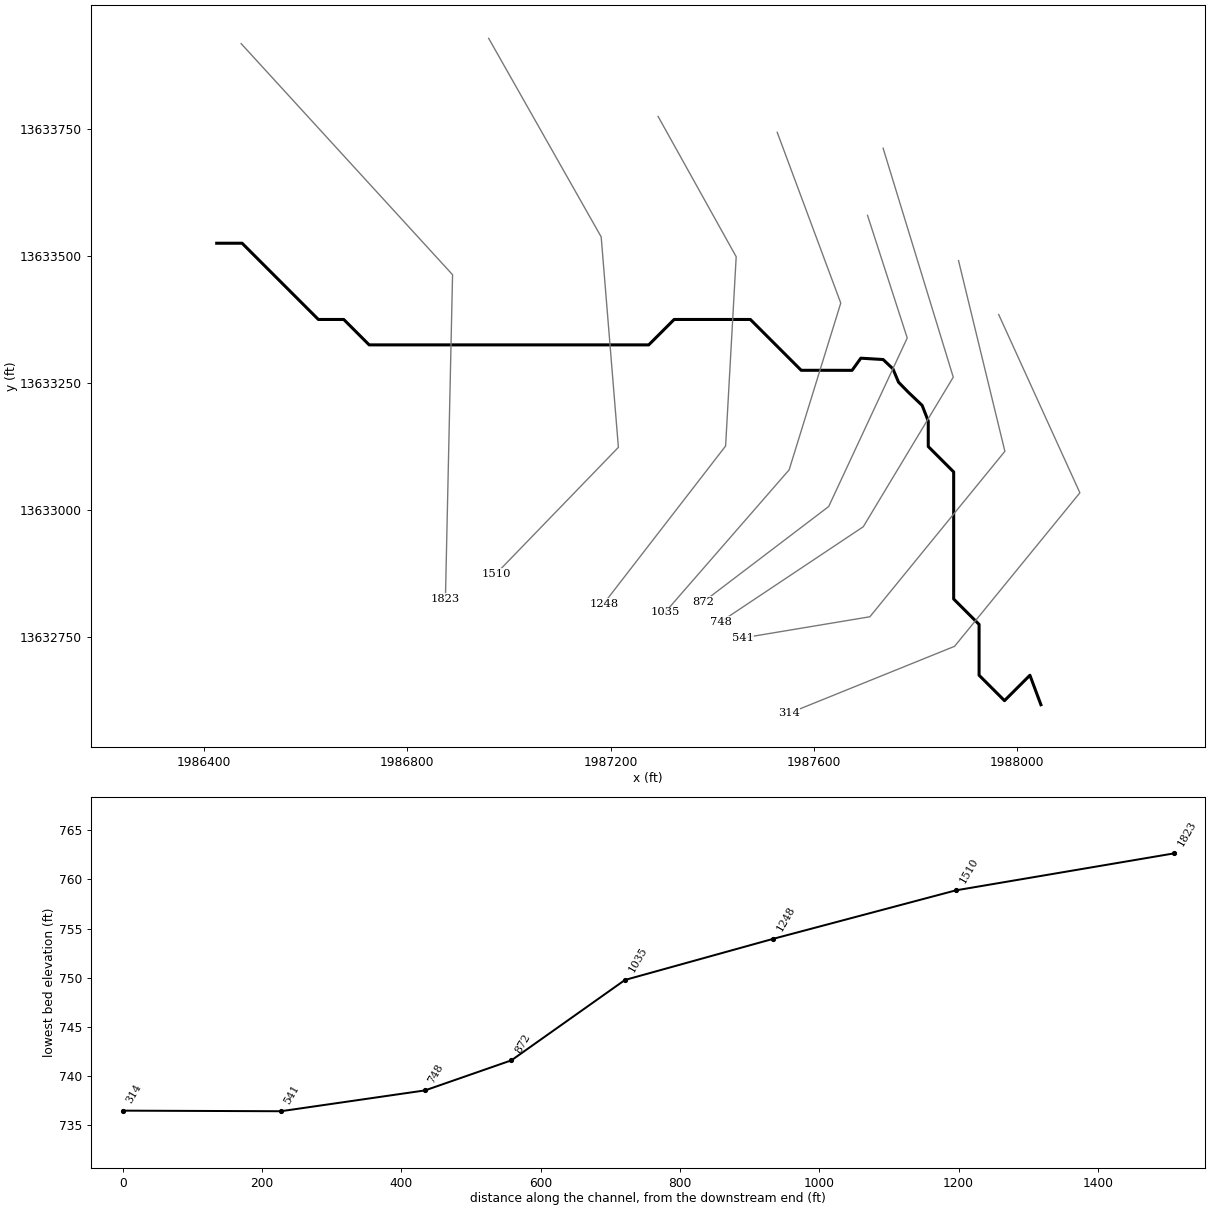
--- UNT 125 in HW.prj (project) ---

Proj Title=UNT 125 in HW Base Level Engineering
Current Plan=p01
Default Exp/Contr=0.3,0.1
English Units
Geom File=g01
Flow File=f01
Plan File=p01
BEGIN DESCRIPTION:
UNT 125 in HW
END DESCRIPTION:

--- UNT 125 in HW.p01 (plan) ---

Plan Title=Multiple Run
Short Identifier=Multiple
Geom File=g01
Flow File=f01
Subcritical Flow
K Sum by GR= 0
Std Step Tol= 0.01
Critical Tol= 0.01
Num of Std Step Trials= 20
Max Error Tol= 0.3
Flow Tol Ratio= 0.001
Split Flow NTrial= 30
Split Flow Tol= 0.02
Split Flow Ratio= 0.02
Log Output Level= 0
Friction Slope Method= 1
Unsteady Friction Slope Method= 2
Unsteady Bridges Friction Slope Method= 1
Parabolic Critical Depth
Global Vel Dist=  1 , 1 , 1
Global Log Level= 0
CheckData=True
Encroach Param= -1, 0, 0, 0
BEGIN DESCRIPTION:
Multiple Run
END DESCRIPTION:

--- UNT 125 in HW.f01 (steady flow) ---

Flow Title=Multiple
Number of Profiles=7
Profile Names=10-year,25-year,50-year,1pct_min,100-year,1pct_plu,500-year
River Rch & RM= UNT 125 in HW,Reach-1,1823
     201     267     318     190     378     755     533
Boundary for River Rch & Prof#=UNT 125 in HW,Reach-1,1
Up Type=0
Dn Type=3
Dn Slope=0.005
Boundary for River Rch & Prof#=UNT 125 in HW,Reach-1,2
Up Type=0
Dn Type=3
Dn Slope=0.005
Boundary for River Rch & Prof#=UNT 125 in HW,Reach-1,3
Up Type=0
Dn Type=3
Dn Slope=0.005
Boundary for River Rch & Prof#=UNT 125 in HW,Reach-1,4
Up Type=0
Dn Type=3
Dn Slope=0.005
Boundary for River Rch & Prof#=UNT 125 in HW,Reach-1,5
Up Type=0
Dn Type=3
Dn Slope=0.005
Boundary for River Rch & Prof#=UNT 125 in HW,Reach-1,6
Up Type=0
Dn Type=3
Dn Slope=0.005
Boundary for River Rch & Prof#=UNT 125 in HW,Reach-1,7
Up Type=0
Dn Type=3
Dn Slope=0.005

--- UNT 125 in HW.g01 (geometry) ---

Geom Title=Existing Conditions

River Reach=UNT 125 in HW,Reach-1
Reach XY= 26
      1986425.00     13633525.00      1986475.00     13633525.00
      1986625.00     13633375.00      1986675.00     13633375.00
      1986725.00     13633325.00      1987275.00     13633325.00
      1987325.00     13633375.00      1987475.00     13633375.00
      1987575.00     13633275.00      1987625.00     13633275.00
      1987675.09     13633274.91      1987692.33     13633298.81
      1987736.16     13633296.20      1987755.40     13633278.00
      1987766.55     13633251.50      1987786.08     13633231.53
      1987812.99     13633205.93      1987825.00     13633175.00
      1987825.00     13633125.00      1987875.00     13633075.00
      1987875.00     13632825.00      1987925.00     13632775.00
      1987925.00     13632675.00      1987975.00     13632625.00
      1988025.00     13632675.00      1988046.66     13632616.98

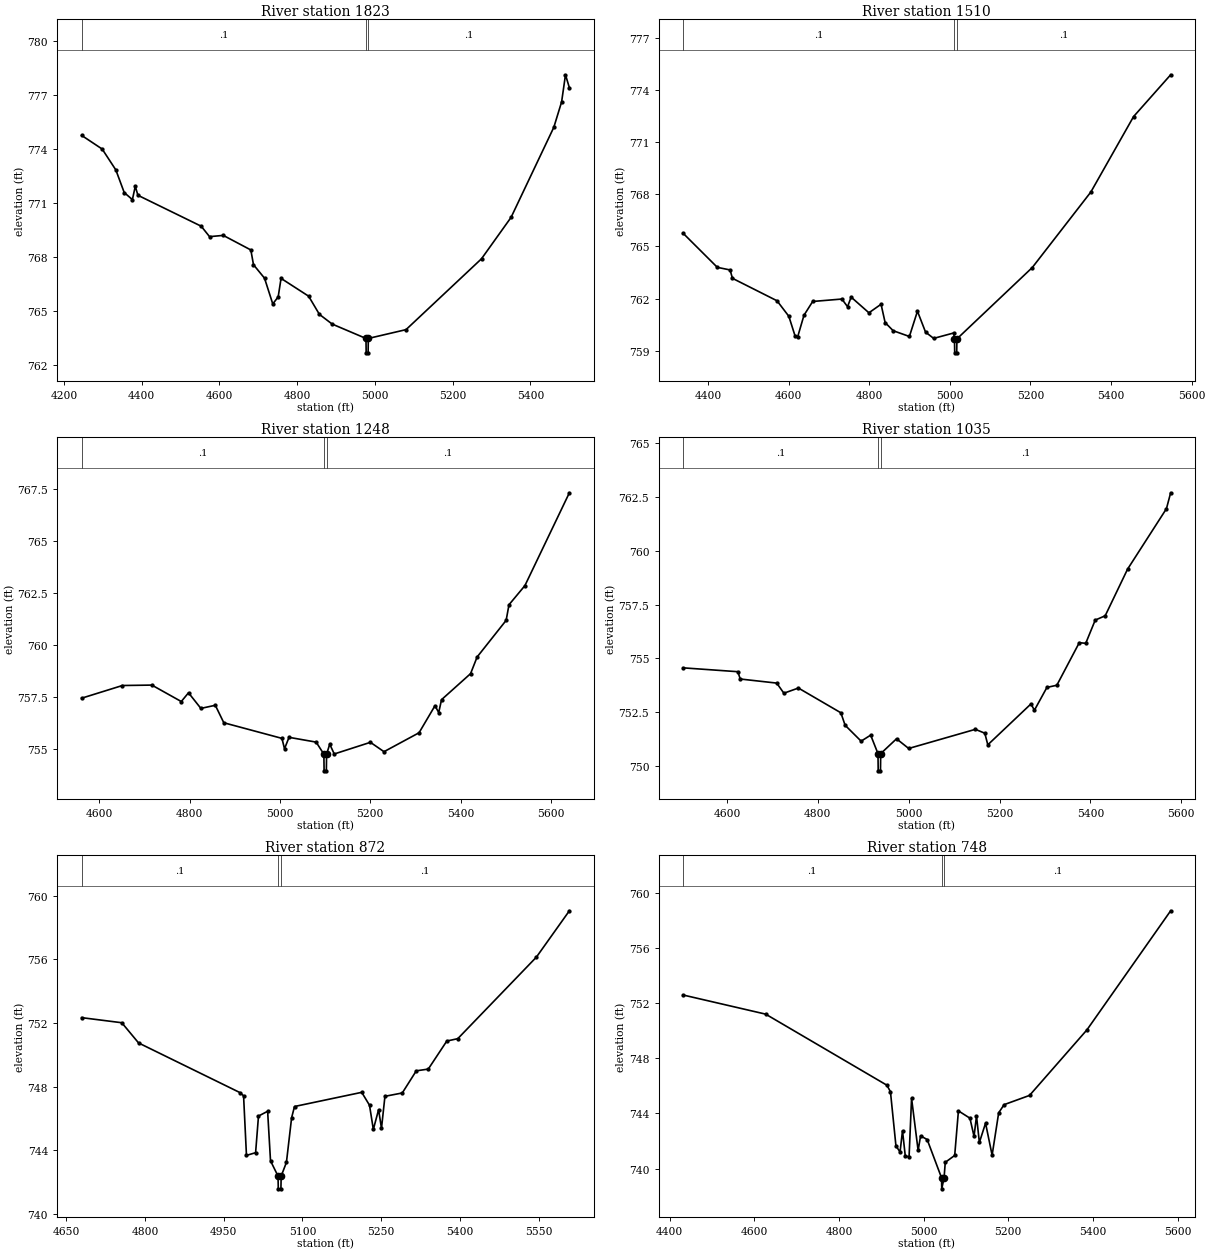
Type RM Length L Ch R = 1,1823,313,313,313
BEGIN DESCRIPTION:
UNT 125 in HW 3.0
END DESCRIPTION:
XS GIS Cut Line= 3
      1986473.12     13633917.71      1986889.06     13633463.02
      1986875.00     13632825.02
#Sta/Elev= 30
  4245.7  774.74  4298.6  773.98  4333.7  772.82  4355.3  771.56  4376.3  771.17
  4383.7  771.91  4390.5  771.41  4553.3  769.69  4574.7  769.11  4610.0  769.18
  4680.9  768.37  4687.7  767.55  4716.1  766.80  4737.3  765.37  4751.2  765.76
  4758.6  766.79  4829.5  765.80  4857.2  764.79  4890.0  764.25  4977.0  763.45
  4977.5  762.65  4982.5  762.65  4983.0  763.45  5080.0  763.94  5274.1  767.88
  5350.1  770.18  5460.1  775.19  5480.1  776.60  5490.1  778.11  5500.1  777.39
#Mann=3,-1,0
  4245.7     0.1       0  4977.0    0.07       0  4983.0     0.1       0
Bank Sta=4977,4983
Exp/Cntr=0.3,0.1

Type RM Length L Ch R = 1,1510,262,262,262
BEGIN DESCRIPTION:
UNT 125 in HW 2.0
END DESCRIPTION:
XS GIS Cut Line= 4
      1986960.11     13633928.13      1987181.48     13633537.47
      1987215.34     13633123.41      1986975.00     13632875.00
#Sta/Elev= 30
  4337.8  765.77  4423.2  763.80  4454.9  763.65  4460.7  763.17  4571.3  761.88
  4600.6  760.99  4616.5  759.83  4622.3  759.79  4638.2  761.05  4659.8  761.84
  4732.2  761.98  4746.3  761.54  4755.2  762.09  4799.3  761.19  4829.4  761.68
  4839.5  760.63  4859.5  760.16  4899.7  759.83  4919.7  761.28  4939.8  760.08
  4959.9  759.72  5009.5  760.03  5011.6  759.69  5012.1  758.89  5017.1  758.89
  5017.6  759.69  5204.6  763.79  5350.0  768.13  5455.9  772.46  5547.9  774.86
#Mann=3,-1,0
  4337.8     0.1       0  5011.6    0.07       0  5017.6     0.1       0
Bank Sta=5011.6,5017.6
Exp/Cntr=0.3,0.1

Type RM Length L Ch R = 1,1248,213,213,213
BEGIN DESCRIPTION:
Mapping XS cae1d3a5
END DESCRIPTION:
XS GIS Cut Line= 4
      1987293.47     13633774.43      1987447.11     13633498.41
      1987426.27     13633126.01      1987186.68     13632816.11
#Sta/Elev= 30
  4560.5  757.45  4650.9  758.06  4716.1  758.08  4781.3  757.29  4797.3  757.71
  4824.7  756.96  4856.7  757.11  4875.5  756.27  5004.3  755.52  5010.0  755.02
  5020.0  755.57  5080.1  755.34  5097.2  754.76  5097.7  753.96  5102.7  753.96
  5103.2  754.76  5110.2  755.24  5120.2  754.77  5200.3  755.33  5230.4  754.88
  5308.1  755.79  5343.4  757.09  5351.6  756.76  5357.9  757.38  5422.2  758.63
  5436.7  759.43  5501.0  761.19  5507.3  761.94  5542.6  762.86  5641.1  767.32
#Mann=3,-1,0
  4560.5     0.1       0  5097.2    0.07       0  5103.2     0.1       0
Bank Sta=5097.2,5103.2
Exp/Cntr=0.3,0.1

Type RM Length L Ch R = 1,1035,163,163,163
BEGIN DESCRIPTION:
Mapping XS 1172ae14
END DESCRIPTION:
XS GIS Cut Line= 4
      1987527.83     13633743.21      1987652.84     13633407.26
      1987551.27     13633079.14      1987307.39     13632798.94
#Sta/Elev= 30
  4503.1  754.56  4624.0  754.38  4629.3  754.04  4709.6  753.85  4725.3  753.38
  4757.3  753.62  4850.7  752.47  4860.1  751.89  4895.3  751.15  4916.3  751.43
  4932.4  750.57  4932.9  749.77  4937.9  749.77  4938.4  750.57  4973.2  751.26
  5000.0  750.81  5146.7  751.70  5167.5  751.52  5174.1  750.98  5269.0  752.88
  5276.7  752.59  5304.2  753.65  5326.0  753.75  5375.4  755.73  5389.6  755.70
  5410.5  756.78  5432.4  756.98  5481.7  759.15  5567.2  761.96  5576.5  762.70
#Mann=3,-1,0
  4503.1     0.1       0  4932.4    0.07       0  4938.4     0.1       0
Bank Sta=4932.4,4938.4
Exp/Cntr=0.3,0.1

Type RM Length L Ch R = 1,872,124,124,124
BEGIN DESCRIPTION:
Mapping XS bdfe1ea3
END DESCRIPTION:
XS GIS Cut Line= 4
      1987705.48     13633579.91      1987783.62     13633338.56
      1987629.10     13633006.96      1987382.93     13632819.73
#Sta/Elev= 30
  4679.5  752.34  4756.0  752.02  4788.0  750.75  4981.2  747.63  4987.9  747.43
  4993.4  743.69  5010.8  743.86  5016.3  746.16  5033.7  746.46  5039.2  743.35
  5053.5  742.39  5054.0  741.59  5059.0  741.59  5059.5  742.39  5069.5  743.25
  5079.4  746.06  5084.9  746.76  5212.9  747.65  5227.7  746.84  5235.0  745.32
  5245.0  746.56  5250.5  745.39  5257.1  747.40  5290.1  747.61  5316.8  749.00
  5339.6  749.11  5374.9  750.87  5395.8  751.02  5545.5  756.14  5608.3  759.05
#Mann=3,-1,0
  4679.5     0.1       0  5053.5    0.07       0  5059.5     0.1       0
Bank Sta=5053.5,5059.5
Exp/Cntr=0.3,0.1

Type RM Length L Ch R = 1,748,207,207,207
BEGIN DESCRIPTION:
Mapping XS 929dee17
END DESCRIPTION:
XS GIS Cut Line= 4
      1987736.18     13633711.92      1987874.19     13633261.43
      1987697.11     13632967.16      1987416.12     13632779.83
#Sta/Elev= 30
  4431.3  752.58  4626.8  751.19  4913.2  746.04  4921.6  745.57  4934.6  741.64
  4944.3  741.20  4950.1  742.74  4956.6  740.92  4965.6  740.84  4971.5  745.09
  4987.0  741.31  4992.8  742.37  5008.4  742.10  5042.3  739.33  5042.8  738.53
  5048.3  739.33  5051.1  740.45  5073.4  740.95  5082.2  744.18  5109.4  743.65
  5119.1  742.33  5124.9  743.81  5131.7  741.89  5146.3  743.29  5161.8  740.97
  5177.3  744.04  5190.1  744.63  5250.2  745.30  5385.8  750.05  5583.6  758.68
#Mann=3,-1,0
  4431.3     0.1       0  5042.3    0.07       0  5048.3     0.1       0
Bank Sta=5042.3,5048.3
Exp/Cntr=0.3,0.1

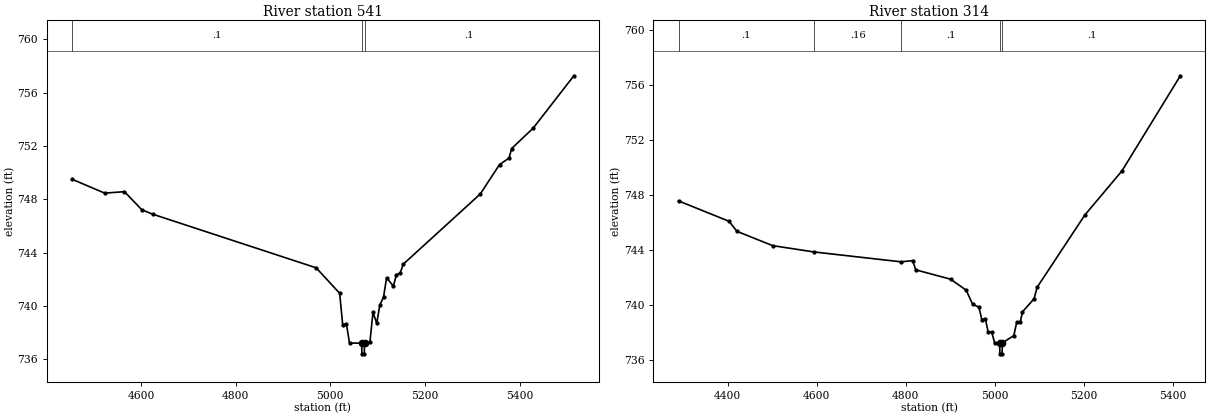
Type RM Length L Ch R = 1,541,227,227,227
BEGIN DESCRIPTION:
Mapping XS 6e286ce0
END DESCRIPTION:
XS GIS Cut Line= 4
      1987884.60     13633490.62      1987975.75     13633115.60
      1987710.13     13632790.07      1987460.16     13632748.41
#Sta/Elev= 30
  4454.7  749.50  4523.6  748.46  4565.4  748.57  4602.0  747.21  4625.1  746.88
  4970.1  742.86  5019.7  740.95  5026.1  738.59  5034.0  738.65  5040.5  737.22
  5066.2  737.21  5066.7  736.41  5071.7  736.41  5072.2  737.21  5083.6  737.28
  5090.0  739.52  5098.0  738.70  5104.4  740.06  5112.3  740.66  5118.8  742.11
  5133.1  741.49  5139.6  742.35  5147.5  742.46  5153.9  743.13  5316.7  748.40
  5357.2  750.60  5377.5  751.09  5382.7  751.80  5428.2  753.33  5514.2  757.26
#Mann=3,-1,0
  4454.7     0.1       0  5066.2    0.07       0  5072.2     0.1       0
Bank Sta=5066.2,5072.2
Exp/Cntr=0.3,0.1

Type RM Length L Ch R = 1,314,0,0,0
BEGIN DESCRIPTION:
UNT 125 in HW 1.0
END DESCRIPTION:
XS GIS Cut Line= 4
      1987963.59     13633384.71      1988123.32     13633034.00
      1987876.79     13632731.92      1987550.44     13632599.98
#Sta/Elev= 30
  4289.6  747.59  4403.1  746.11  4420.7  745.38  4500.8  744.34  4593.7  743.88
  4789.7  743.16  4815.7  743.25  4822.3  742.58  4900.6  741.90  4935.8  741.10
  4950.1  740.09  4964.5  739.86  4971.0  738.95  4978.9  739.03  4985.3  738.03
  4993.2  738.05  4999.7  737.27  5011.0  737.27  5011.5  736.47  5016.5  736.47
  5017.0  737.27  5042.8  737.79  5049.2  738.75  5057.1  738.76  5062.3  739.52
  5088.4  740.48  5095.2  741.31  5202.5  746.57  5285.7  749.77  5416.9  756.69
#Mann=5,-1,0
  4289.6     0.1       0  4593.7    0.16       0  4789.7     0.1       0
  5011.0    0.07       0  5017.0     0.1       0
Bank Sta=5011,5017
Exp/Cntr=0.3,0.1

Chan Stop Cuts=-1