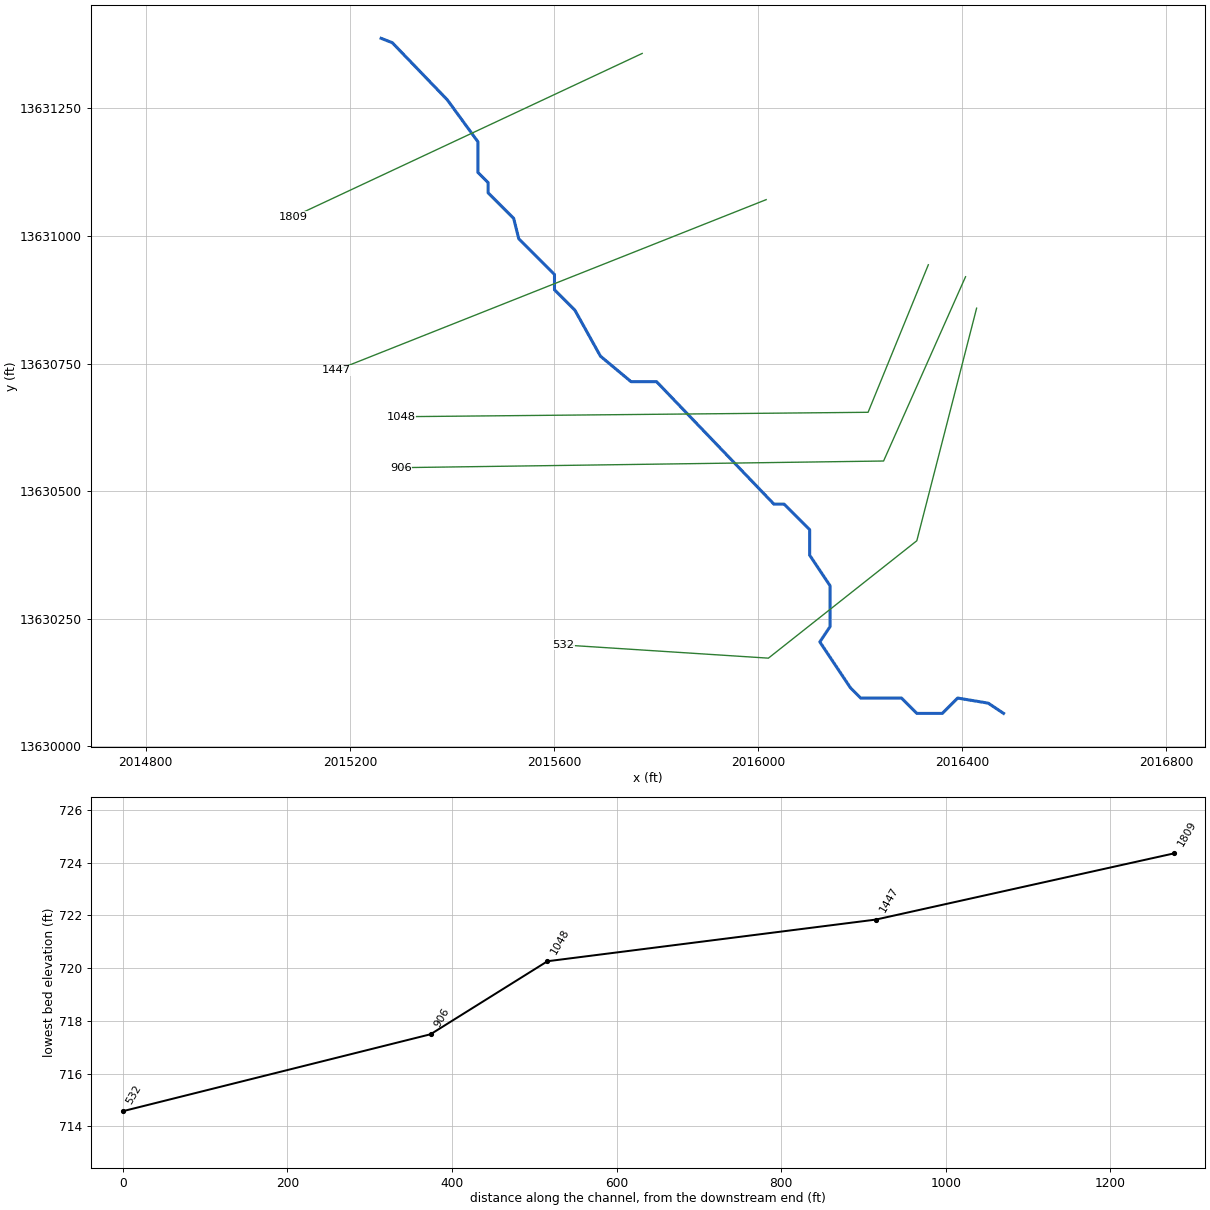
--- UNT 126 in HW.prj (project) ---

Proj Title=UNT 126 in HW Base Level Engineering
Current Plan=p01
Default Exp/Contr=0.3,0.1
English Units
Geom File=g01
Flow File=f01
Plan File=p01
BEGIN DESCRIPTION:
UNT 126 in HW
END DESCRIPTION:

--- UNT 126 in HW.p01 (plan) ---

Plan Title=Multiple Run
Short Identifier=Multiple
Geom File=g01
Flow File=f01
Subcritical Flow
K Sum by GR= 0
Std Step Tol= 0.01
Critical Tol= 0.01
Num of Std Step Trials= 20
Max Error Tol= 0.3
Flow Tol Ratio= 0.001
Split Flow NTrial= 30
Split Flow Tol= 0.02
Split Flow Ratio= 0.02
Log Output Level= 0
Friction Slope Method= 1
Unsteady Friction Slope Method= 2
Unsteady Bridges Friction Slope Method= 1
Parabolic Critical Depth
Global Vel Dist=  1 , 1 , 1
Global Log Level= 0
CheckData=True
Encroach Param= -1, 0, 0, 0
BEGIN DESCRIPTION:
Multiple Run
END DESCRIPTION:

--- UNT 126 in HW.f01 (steady flow) ---

Flow Title=Multiple
Number of Profiles=7
Profile Names=10-year,25-year,50-year,1pct_min,100-year,1pct_plu,500-year
River Rch & RM= UNT 126 in HW,Reach-1,1809
     235     308     364     214     426     851     585
Boundary for River Rch & Prof#=UNT 126 in HW,Reach-1,1
Up Type=0
Dn Type=3
Dn Slope=0.005
Boundary for River Rch & Prof#=UNT 126 in HW,Reach-1,2
Up Type=0
Dn Type=3
Dn Slope=0.005
Boundary for River Rch & Prof#=UNT 126 in HW,Reach-1,3
Up Type=0
Dn Type=3
Dn Slope=0.005
Boundary for River Rch & Prof#=UNT 126 in HW,Reach-1,4
Up Type=0
Dn Type=3
Dn Slope=0.005
Boundary for River Rch & Prof#=UNT 126 in HW,Reach-1,5
Up Type=0
Dn Type=3
Dn Slope=0.005
Boundary for River Rch & Prof#=UNT 126 in HW,Reach-1,6
Up Type=0
Dn Type=3
Dn Slope=0.005
Boundary for River Rch & Prof#=UNT 126 in HW,Reach-1,7
Up Type=0
Dn Type=3
Dn Slope=0.005

--- UNT 126 in HW.g01 (geometry) ---

Geom Title=Existing Conditions

River Reach=UNT 126 in HW,Reach-1
Reach XY= 30
      2015261.03     13631387.28      2015283.00     13631378.73
      2015390.80     13631266.75      2015450.80     13631184.54
      2015450.80     13631124.54      2015470.80     13631104.54
      2015470.80     13631084.54      2015520.80     13631034.54
      2015530.80     13630994.54      2015600.80     13630924.54
      2015600.80     13630894.54      2015640.80     13630854.54
      2015690.80     13630764.54      2015750.80     13630714.54
      2015800.80     13630714.54      2016030.80     13630474.54
      2016050.80     13630474.54      2016100.80     13630424.54
      2016100.80     13630374.54      2016140.80     13630314.54
      2016140.80     13630234.54      2016120.80     13630204.54
      2016180.80     13630114.54      2016200.80     13630094.54
      2016280.80     13630094.54      2016310.80     13630064.54
      2016360.80     13630064.54      2016390.80     13630094.54
      2016450.80     13630084.54      2016480.80     13630064.54

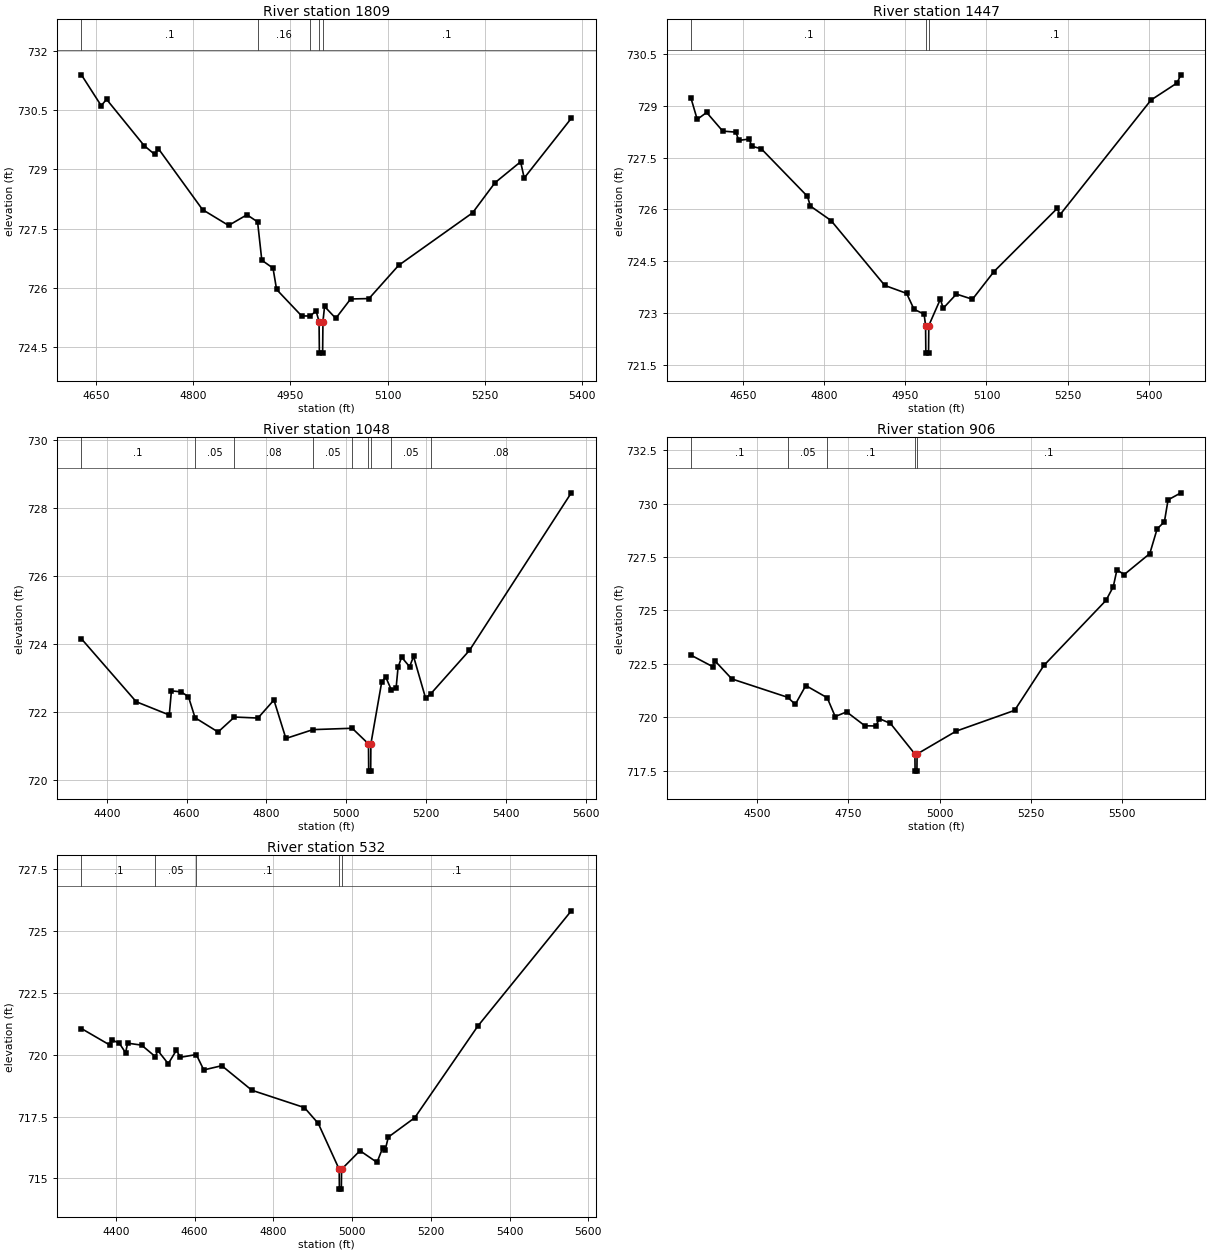
Type RM Length L Ch R = 1,1809,362,362,362
BEGIN DESCRIPTION:
UNT 126 in HW 1.0
END DESCRIPTION:
XS GIS Cut Line= 2
      2015772.60     13631357.66      2015088.42     13631037.22
#Sta/Elev= 30
  4627.8  731.39  4658.3  730.61  4666.6  730.77  4724.5  729.60  4740.6  729.38
  4746.6  729.52  4814.6  727.98  4854.8  727.58  4883.1  727.85  4899.5  727.67
  4906.0  726.70  4923.3  726.50  4928.8  725.96  4967.5  725.29  4981.0  725.29
  4989.6  725.42  4994.3  725.15  4994.8  724.35  4999.8  724.35  5000.3  725.15
  5002.8  725.53  5020.1  725.23  5043.0  725.72  5071.3  725.73  5117.0  726.57
  5231.1  727.90  5265.6  728.66  5305.1  729.19  5310.7  728.78  5383.3  730.29
#Mann=5,-1,0
  4627.8     0.1       0  4899.5    0.16       0  4981.0     0.1       0
  4994.3    0.07       0  5000.3     0.1       0
Bank Sta=4994.3,5000.3
Exp/Cntr=0.3,0.1

Type RM Length L Ch R = 1,1447,399,399,399
BEGIN DESCRIPTION:
UNT 126 in HW 2.0
END DESCRIPTION:
XS GIS Cut Line= 2
      2016015.62     13631071.19      2015173.62     13630736.99
#Sta/Elev= 30
  4553.7  729.22  4565.1  728.61  4582.6  728.81  4612.3  728.27  4636.6  728.24
  4642.0  728.00  4661.0  728.04  4666.3  727.83  4683.5  727.76  4769.0  726.38
  4774.3  726.10  4812.6  725.68  4912.0  723.80  4952.4  723.57  4966.0  723.11
  4984.7  722.97  4987.4  722.64  4987.9  721.84  4992.9  721.84  4993.4  722.64
  5014.7  723.40  5020.1  723.14  5044.4  723.55  5074.1  723.40  5113.8  724.20
  5230.7  726.03  5236.1  725.85  5404.3  729.17  5452.1  729.66  5459.6  729.90
#Mann=3,-1,0
  4553.7     0.1       0  4987.4    0.07       0  4993.4     0.1       0
Bank Sta=4987.4,4993.4
Exp/Cntr=0.3,0.1

Type RM Length L Ch R = 1,1048,142,142,142
BEGIN DESCRIPTION:
UNT 126 in HW 5.0
END DESCRIPTION:
XS GIS Cut Line= 3
      2016333.34     13630943.58      2016215.29     13630654.52
      2015299.77     13630645.85
#Sta/Elev= 30
  4336.6  724.15  4473.9  722.30  4556.8  721.91  4562.2  722.62  4586.2  722.59
  4604.8  722.45  4621.4  721.83  4679.1  721.41  4720.2  721.85  4779.1  721.82
  4819.1  722.35  4849.1  721.22  4916.9  721.48  5015.3  721.52  5056.1  721.06
  5056.6  720.26  5061.6  720.26  5062.1  721.06  5089.1  722.87  5099.1  723.03
  5113.7  722.64  5125.2  722.69  5130.2  723.31  5139.1  723.61  5159.1  723.33
  5169.1  723.63  5199.1  722.41  5212.0  722.53  5309.2  723.81  5564.4  728.44
#Mann=9,-1,0
  4336.6     0.1       0  4621.4    0.05       0  4720.2    0.08       0
  4916.9    0.05       0  5015.3    0.08       0  5056.1    0.04       0
  5062.1    0.08       0  5113.7    0.05       0  5212.0    0.08       0
Bank Sta=5056.1,5062.1
Exp/Cntr=0.3,0.1

Type RM Length L Ch R = 1,906,374,374,374
BEGIN DESCRIPTION:
UNT 126 in HW 4.0
END DESCRIPTION:
XS GIS Cut Line= 3
      2016406.27     13630920.17      2016245.67     13630559.04
      2015299.79     13630546.02
#Sta/Elev= 30
  4319.3  722.91  4379.1  722.37  4384.5  722.65  4431.0  721.80  4584.1  720.94
  4604.7  720.61  4633.5  721.49  4692.1  720.92  4714.0  720.04  4745.2  720.26
  4795.2  719.61  4825.2  719.60  4835.2  719.94  4865.2  719.72  4932.2  718.29
  4932.7  717.49  4937.7  717.49  4938.2  718.29  5045.2  719.36  5205.2  720.33
  5285.3  722.43  5455.3  725.47  5475.3  726.11  5485.3  726.90  5505.3  726.68
  5575.3  727.66  5595.3  728.81  5615.3  729.15  5625.3  730.17  5660.5  730.50
#Mann=5,-1,0
  4319.3     0.1       0  4584.1    0.05       0  4692.1     0.1       0
  4932.2    0.07       0  4938.2     0.1       0
Bank Sta=4932.2,4938.2
Exp/Cntr=0.3,0.1

Type RM Length L Ch R = 1,532,0,0,0
BEGIN DESCRIPTION:
UNT 126 in HW 3.0
END DESCRIPTION:
XS GIS Cut Line= 4
      2016427.96     13630858.54      2016310.77     13630402.79
      2016019.97     13630172.75      2015618.17     13630198.68
#Sta/Elev= 30
  4312.7  721.05  4384.2  720.39  4389.3  720.60  4409.3  720.45  4424.9  720.07
  4430.0  720.46  4465.6  720.38  4500.8  719.91  4506.3  720.17  4533.2  719.63
  4553.8  720.17  4564.2  719.89  4604.4  720.00  4623.4  719.38  4669.2  719.55
  4745.5  718.56  4879.0  717.86  4914.2  717.22  4967.3  715.37  4967.8  714.57
  4972.8  714.57  4973.3  715.37  5020.1  716.12  5063.3  715.65  5077.7  716.23
  5084.1  716.15  5092.1  716.67  5159.1  717.45  5319.4  721.15  5556.7  725.80
#Mann=5,-1,0
  4312.7     0.1       0  4500.8    0.05       0  4604.4     0.1       0
  4967.3    0.07       0  4973.3     0.1       0
Bank Sta=4967.3,4973.3
Exp/Cntr=0.3,0.1

Chan Stop Cuts=-1