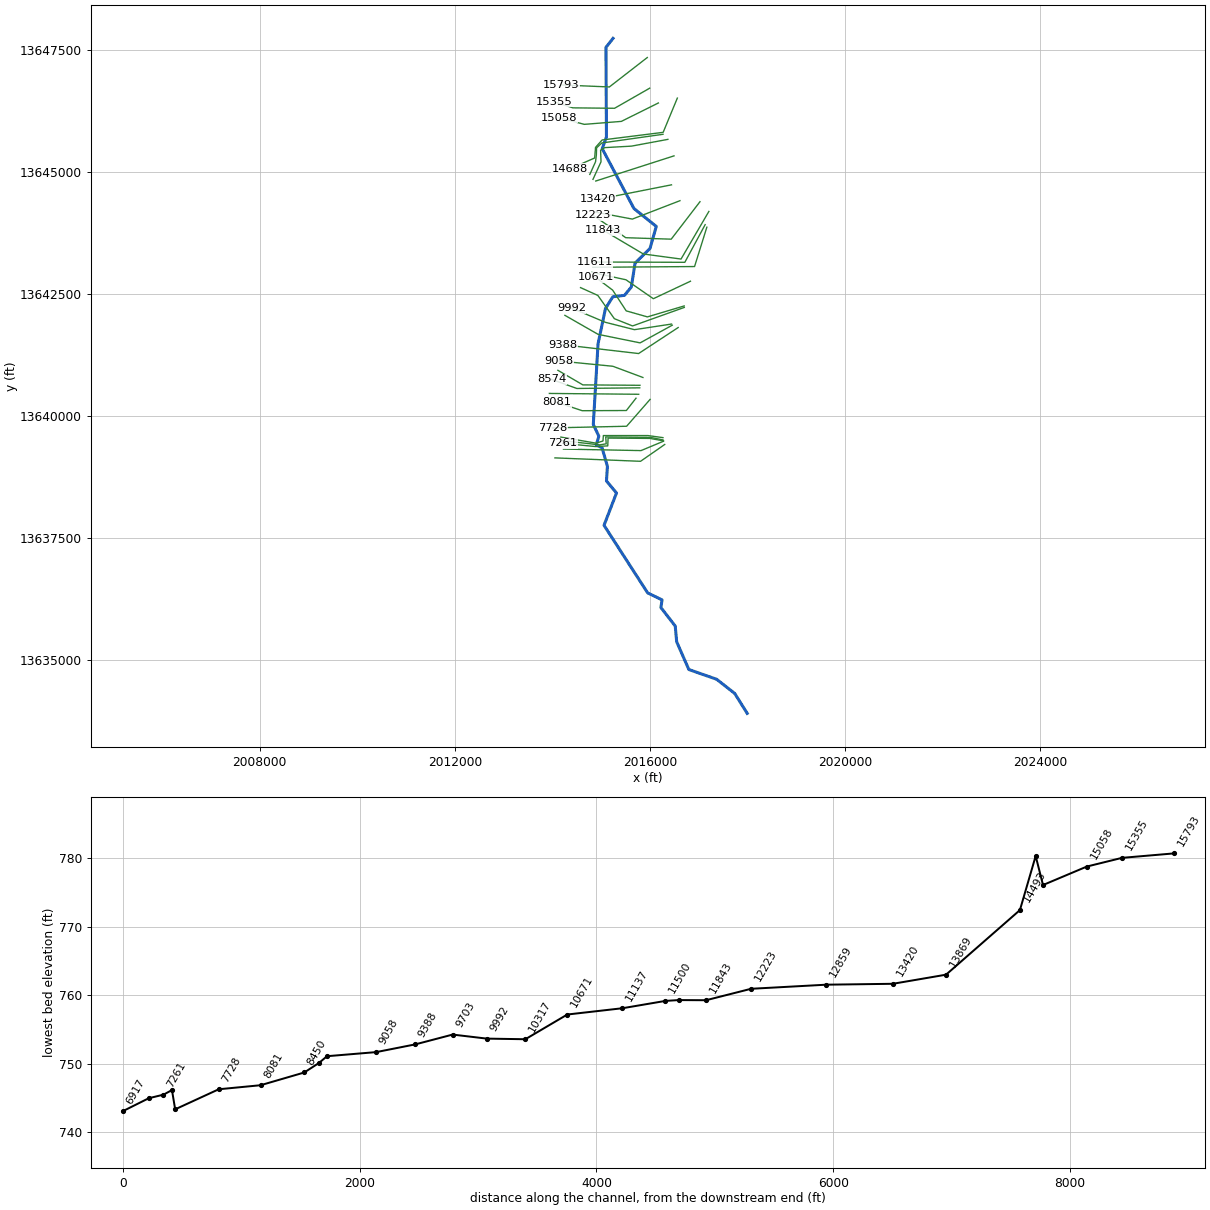
--- WP FORT EWELL CREEK.prj (project) ---

Proj Title=WP FORT EWELL CREEK Base Level Engineering
Current Plan=p01
Default Exp/Contr=0.3,0.1
English Units
Geom File=g01
Flow File=f01
Plan File=p01
Y Axis Title=Elevation
X Axis Title(PF)=Main Channel Distance
X Axis Title(XS)=Station
BEGIN DESCRIPTION:
WP FORT EWELL CREEK
END DESCRIPTION:
DSS Export Rating Curves= 0
DSS Export Rating Curve Sorted= 0
DSS Export Volume Flow Curves= 0
DXF OffsetX= 0
DXF OffsetY= 0
DXF ScaleX= 1
DXF ScaleY= 10

--- WP FORT EWELL CREEK.p01 (plan) ---

Plan Title=Multiple Run
Short Identifier=Multiple
Geom File=g01
Flow File=f01
Subcritical Flow
K Sum by GR= 0
Std Step Tol= 0.01
Critical Tol= 0.01
Num of Std Step Trials= 20
Max Error Tol= 0.3
Flow Tol Ratio= 0.001
Split Flow NTrial= 30
Split Flow Tol= 0.02
Split Flow Ratio= 0.02
Log Output Level= 0
Friction Slope Method= 1
Unsteady Friction Slope Method= 2
Unsteady Bridges Friction Slope Method= 1
Parabolic Critical Depth
Global Vel Dist=  1 , 1 , 1
Global Log Level= 0
CheckData=True
Encroach Param= -1, 0, 0, 0
BEGIN DESCRIPTION:
Multiple Run
END DESCRIPTION:

--- WP FORT EWELL CREEK.f01 (steady flow) ---

Flow Title=Multiple
Number of Profiles=7
Profile Names=10-year,25-year,50-year,1pct_min,100-year,1pct_plu,500-year
River Rch & RM= WP FORT EWELL CR,Reach-1,15793
     463     641     787     479     956    1907    1414
River Rch & RM= WP FORT EWELL CR,Reach-1,15058
     816    1164    1457     902    1800    3592    2759
River Rch & RM= WP FORT EWELL CR,Reach-1,8081
    1193    1732    2196    1375    2743    5472    4298
River Rch & RM= WP FORT EWELL CR,Reach-1,2628
    1330    1940    2467    1548    3089    6164    4867
Boundary for River Rch & Prof#=WP FORT EWELL CR,Reach-1,1
Up Type=0
Dn Type=3
Dn Slope=0.005
Boundary for River Rch & Prof#=WP FORT EWELL CR,Reach-1,2
Up Type=0
Dn Type=3
Dn Slope=0.005
Boundary for River Rch & Prof#=WP FORT EWELL CR,Reach-1,3
Up Type=0
Dn Type=3
Dn Slope=0.005
Boundary for River Rch & Prof#=WP FORT EWELL CR,Reach-1,4
Up Type=0
Dn Type=3
Dn Slope=0.005
Boundary for River Rch & Prof#=WP FORT EWELL CR,Reach-1,5
Up Type=0
Dn Type=3
Dn Slope=0.005
Boundary for River Rch & Prof#=WP FORT EWELL CR,Reach-1,6
Up Type=0
Dn Type=3
Dn Slope=0.005
Boundary for River Rch & Prof#=WP FORT EWELL CR,Reach-1,7
Up Type=0
Dn Type=3
Dn Slope=0.005

--- WP FORT EWELL CREEK.g01 (geometry) ---

Geom Title=Existing Conditions
Program Version=5.05

River Reach=WP FORT EWELL CR,Reach-1
Reach XY= 30
       2015245.8     13647749.54       2015100.8     13647564.54
      2015110.34     13645726.32       2015024.4     13645484.13
      2015674.14     13644257.57      2016132.48     13643889.08
      2016003.87     13643436.68      2015697.88     13643136.12
       2015620.8     13642644.54       2015480.8     13642474.54
       2015240.8     13642444.54       2015090.8     13642204.54
      2014938.33     13641479.22       2014840.8     13639824.54
      2014955.26      13639582.4      2014900.95     13639404.39
       2015020.8     13639344.54       2015130.8     13638964.54
       2015110.8     13638664.54      2015316.59     13638418.12
       2015060.8     13637754.54       2015955.7     13636367.34
       2016250.8     13636224.54      2016227.83     13636066.56
      2016521.67     13635686.26       2016550.8     13635364.54
       2016800.8     13634794.54       2017370.8     13634594.54
       2017740.8     13634304.54      2017998.06     13633894.59

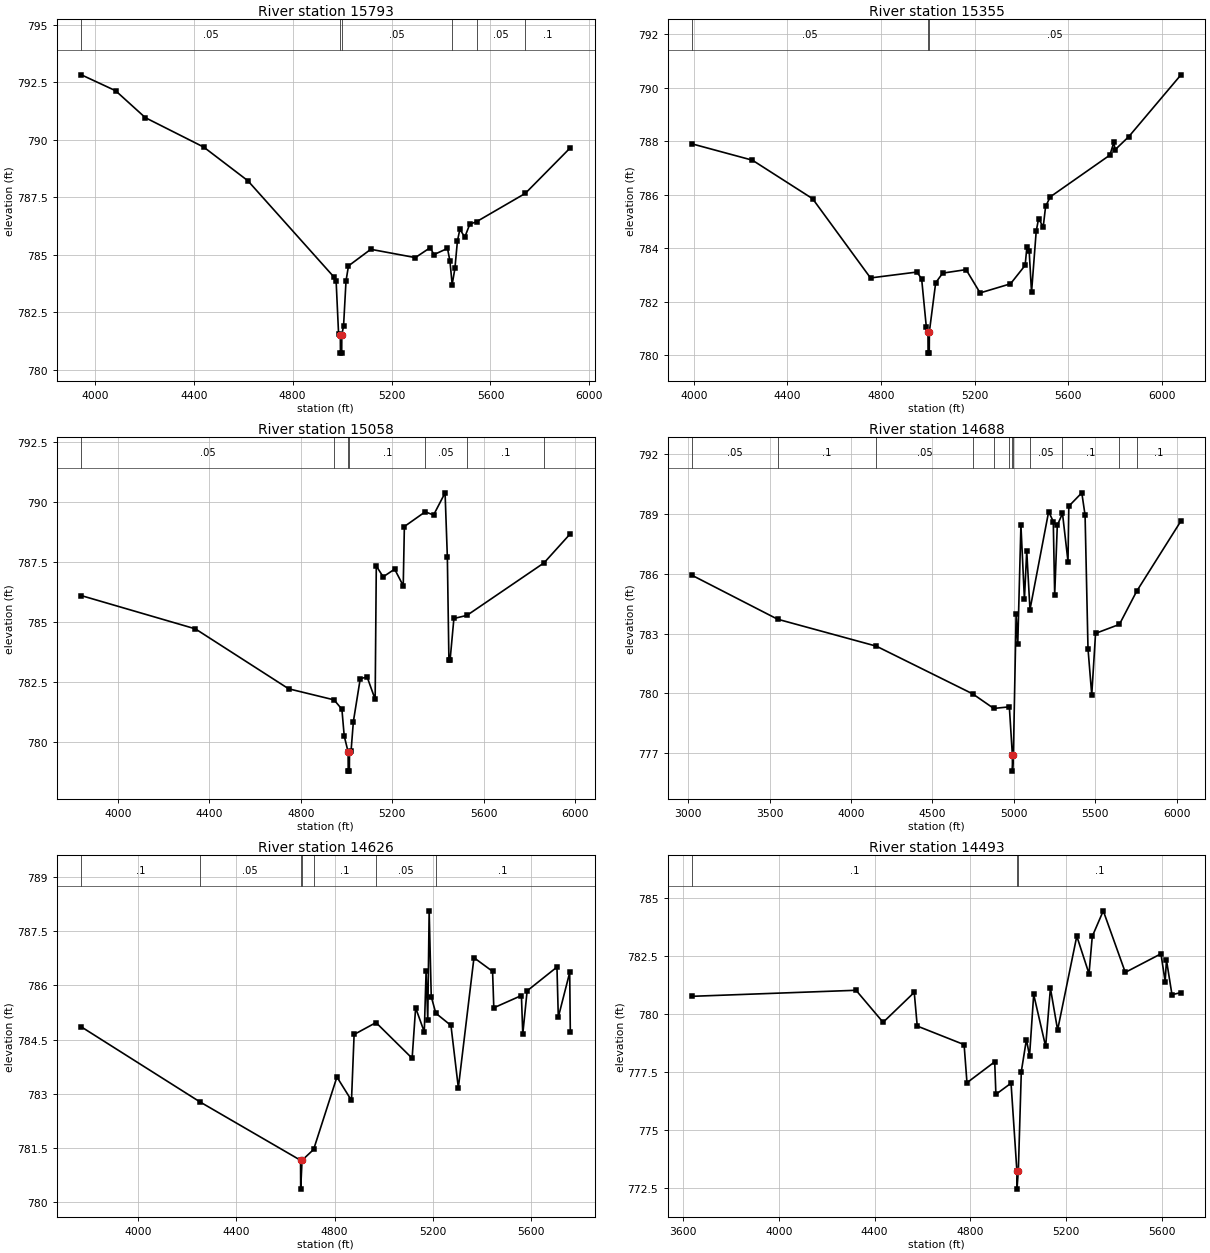
Type RM Length L Ch R = 1 ,15793   ,438,438,438
BEGIN DESCRIPTION:
WP FORT EWELL CREEK 23.0
END DESCRIPTION:
XS GIS Cut Line= 3
      2015948.16     13647355.63      2015170.41     13646751.49
      2014178.71      13646793.1
#Sta/Elev= 30
  3945.5  792.82  4083.8  792.13  4204.1  790.96  4440.4  789.68  4618.7  788.22
  4965.8  784.05  4975.8  783.86  4985.8  781.55  4992.8  781.53  4993.3  780.73
  4998.3  780.73  4998.8  781.53  5005.8   781.9  5015.8  783.87  5025.8  784.52
  5115.9  785.24  5296.1  784.88  5356.1  785.31  5371.5  785.01  5426.2  785.28
  5436.2  784.72  5445.1  783.71  5456.2  784.41  5466.2  785.59  5476.2  786.11
  5496.2  785.77  5516.3  786.33  5543.7  786.44  5740.9  787.67  5922.9  789.65
#Mann= 6 ,-1 , 0
  3945.5     .05       0  4992.8    .035       0  4998.8     .05       0
  5445.1     .08       0  5543.7     .05       0  5740.9      .1       0
Bank Sta=4992.8,4998.8
XS Rating Curve= 0 ,0
Exp/Cntr=0.3,0.1

Type RM Length L Ch R = 1 ,15355   ,297,297,297
BEGIN DESCRIPTION:
Mapping XS 6561a4d6
END DESCRIPTION:
XS GIS Cut Line= 4
      2015997.67     13646726.32      2015277.18     13646313.99
      2014422.14     13646322.67      2014035.85     13646448.54
#Sta/Elev= 30
  3991.6   787.9  4249.9  787.29  4507.5  785.85  4755.1  782.89  4953.9  783.11
  4973.9  782.85  4993.9  781.05  5000.9  780.88  5001.4  780.08  5006.4  780.08
  5006.9  780.88  5033.9  782.71  5063.9  783.07  5163.9   783.2  5223.9  782.33
  5353.9  782.67  5416.5  783.36  5423.9  784.03  5433.9  783.88  5443.9  782.35
  5463.9  784.64    5474   785.1    5494   784.8    5504  785.56    5524  785.92
    5779  787.48    5796  787.96  5801.3  787.68  5859.9  788.17  6083.1  790.48
#Mann= 3 ,-1 , 0
  3991.6     .05       0  5000.9    .035       0  5006.9     .05       0
Bank Sta=5000.9,5006.9
XS Rating Curve= 0 ,0
Exp/Cntr=0.3,0.1

Type RM Length L Ch R = 1 ,15058   ,370,370,370
BEGIN DESCRIPTION:
Mapping XS dee2caa8
END DESCRIPTION:
XS GIS Cut Line= 4
      2016175.63      13646422.5      2015416.07     13646044.89
      2014656.52     13645984.13      2014144.32     13646118.69
#Sta/Elev= 30
  3839.4   786.1  4338.1  784.72  4746.4  782.23  4945.2  781.77  4979.6  781.38
  4989.7  780.27  5006.7  779.61  5007.2  778.81  5012.3  778.81  5012.8  779.61
  5019.8  779.66  5029.8  780.87  5059.9  782.65    5090  782.72  5125.1  781.79
  5130.1  787.33  5160.2  786.88  5210.4   787.2    5248  786.51    5253  788.97
    5344  789.58  5380.9  789.45  5431.1  790.37  5441.1  787.69  5447.9  783.42
    5453  783.42  5469.7  785.15  5526.9  785.28  5864.1  787.46  5979.2  788.67
#Mann= 7 ,-1 , 0
  3839.4     .05       0  4945.2      .1       0  5006.7     .07       0
  5012.8      .1       0    5344     .05       0  5526.9      .1       0
  5864.1     .05       0
Bank Sta=5006.7,5012.8
XS Rating Curve= 0 ,0
Exp/Cntr=0.3,0.1

Type RM Length L Ch R = 1 ,14688   ,62,62,62
BEGIN DESCRIPTION:
Mapping XS 8560bead
END DESCRIPTION:
XS GIS Cut Line= 6
      2016564.58     13646523.09      2016273.79     13645819.98
       2015021.1     13645662.94      2014886.55     13645511.03
      2014869.19     13645294.02      2014358.52     13645068.98
#Sta/Elev= 30
  3023.7  785.92  3549.2  783.72  4155.9  782.37  4747.9  779.98  4877.3  779.25
  4973.1  779.33  4991.7  776.91  4992.2  776.11  4997.8  776.91  5014.8  783.96
  5024.8  782.47  5044.2  788.44  5065.7  784.71  5079.9  787.15  5099.8   784.2
  5214.6  789.11    5243  788.61  5251.6  784.92  5267.7  788.42  5299.6  789.02
  5333.4  786.61  5338.4  789.38  5418.2  790.05  5438.3  788.93  5456.3  782.24
  5479.3  779.93  5502.7  783.01  5649.2  783.46  5755.3  785.12  6027.4  788.64
#Mann= 12 ,-1 , 0
  3023.7     .05       0  3549.2      .1       0  4155.9     .05       0
  4747.9      .1       0  4877.3     .16       0  4973.1      .1       0
  4991.7     .07       0  4997.8      .1       0  5099.8     .05       0
  5299.6      .1       0  5649.2     .08       0  5755.3      .1       0
Bank Sta=4991.7,4997.8
XS Rating Curve= 0 ,0
Exp/Cntr=0.3,0.1

Type RM Length L Ch R = 1 ,14626   ,133,133,133
BEGIN DESCRIPTION:
Mapping XS 4a158660
END DESCRIPTION:
XS GIS Cut Line= 6
      2016271.06     13645780.13      2015016.76     13645602.18
      2014908.25     13645502.35      2014903.91     13645354.78
      2014886.55      13645215.9      2014769.67     13644956.15
#Sta/Elev= 30
  3771.1  784.85  4252.9  782.77  4661.8  781.15  4662.3  780.35  4667.9  781.15
  4714.9  781.45  4809.6  783.46  4868.8  782.81  4879.4  784.64  4968.4  784.97
  5115.2  783.98  5129.4  785.38  5164.6  784.71  5171.9  786.39  5178.7  785.05
  5184.4  788.07  5192.9  785.69  5211.4  785.23    5273  784.89    5303  783.16
  5366.5  786.77  5442.1  786.39  5447.1  785.38  5559.3  785.72  5564.8  784.65
  5582.5  785.85  5703.7  786.51  5709.2  785.12  5755.5  786.36    5758  784.71
#Mann= 7 ,-1 , 0
  3771.1      .1       0  4252.9     .05       0  4661.8    .035       0
  4667.9     .05       0  4714.9      .1       0  4968.4     .05       0
  5211.4      .1       0
Bank Sta=4661.8,4667.9
XS Rating Curve= 0 ,0
Exp/Cntr=0.3,0.1

Type RM Length L Ch R = 1 ,14493   ,624,624,624
BEGIN DESCRIPTION:
Mapping XS 8151c025
END DESCRIPTION:
XS GIS Cut Line= 6
      2016370.91     13645675.96       2015624.4     13645537.08
      2015077.53     13645506.69      2014990.72     13645454.61
       2014999.4      13645215.9      2014834.45     13644855.61
#Sta/Elev= 30
  3636.6  780.75  4322.1  781.01  4435.3  779.63  4565.4  780.92  4577.9  779.47
  4773.8  778.67  4785.8  777.03  4901.7  777.93  4906.7  776.53    4970  777.01
  4994.3  773.25  4994.8  772.45  5000.5  773.25  5012.9  777.51  5034.3  778.89
  5047.3  778.18  5064.6  780.83  5114.6  778.59  5134.6   781.1  5164.6   779.3
  5244.8  783.34  5295.9  781.72  5309.5  783.33  5355.5  784.43  5447.5  781.78
  5596.6  782.58  5614.1  781.38  5619.6  782.31  5642.6  780.82  5680.2  780.91
#Mann= 3 ,-1 , 0
  3636.6      .1       0  4994.3     .07       0  5000.5      .1       0
Bank Sta=4994.3,5000.5
XS Rating Curve= 0 ,0
Exp/Cntr=0.3,0.1

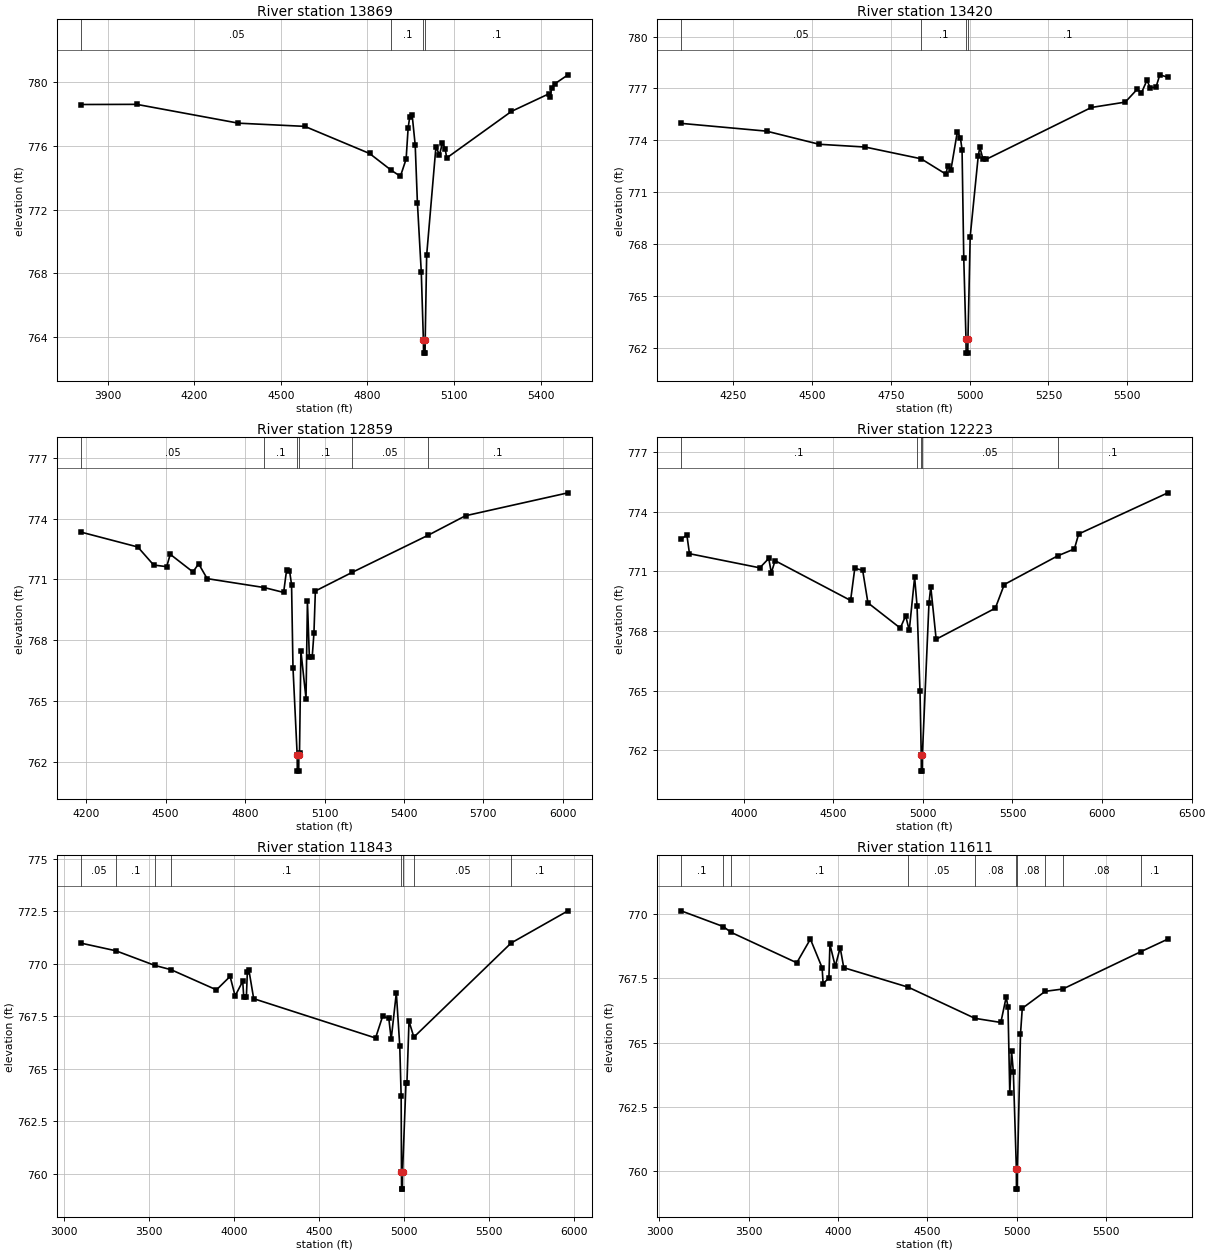
Type RM Length L Ch R = 1 ,13869   ,449,449,449
BEGIN DESCRIPTION:
Mapping XS e1bcdaca
END DESCRIPTION:
XS GIS Cut Line= 2
       2016496.8     13645337.43      2014890.91     13644820.94
#Sta/Elev= 30
  3808.1  778.59    4000   778.6    4353  777.42  4582.8  777.22  4807.4  775.52
  4883.2  774.46  4914.2  774.09    4934  775.17    4941  777.12  4946.3  777.78
    4955  777.92  4965.5  776.04  4973.1  772.44  4986.5   768.1  4993.9  763.81
  4994.4  763.01  4999.6  763.01  5000.1  763.81  5005.2  769.15  5037.3  775.94
  5049.5  775.43    5060  776.19  5069.4  775.81  5074.6  775.24  5299.2  778.16
  5427.6  779.25  5432.8  779.06  5438.2   779.6  5448.7  779.88    5495  780.45
#Mann= 4 ,-1 , 0
  3808.1     .05       0  4883.2      .1       0  4993.9     .07       0
  5000.1      .1       0
Bank Sta=4993.9,5000.1
XS Rating Curve= 0 ,0
Exp/Cntr=0.3,0.1

Type RM Length L Ch R = 1 ,13420   ,561,561,561
BEGIN DESCRIPTION:
Mapping XS 97927377
END DESCRIPTION:
XS GIS Cut Line= 2
      2016444.72     13644742.81      2014929.94     13644443.32
#Sta/Elev= 30
  4084.8  774.98  4355.9  774.53  4522.8  773.77  4668.5  773.61  4846.2  772.93
  4924.9  772.04  4930.6  772.51  4940.8  772.29  4961.2   774.5    4971  774.13
  4976.1  773.45  4981.5  767.19  4988.6  762.48  4989.1  761.68  4994.3  761.68
  4994.8  762.48  5001.9  768.43  5027.4  773.08  5032.5   773.6  5042.7   772.9
  5052.9   772.9  5386.2   775.9  5493.8  776.21    5532  776.96  5545.1  776.74
  5562.6  777.47  5572.8  777.05  5591.3  777.07  5603.4  777.79  5628.9  777.65
#Mann= 4 ,-1 , 0
  4084.8     .05       0  4846.2      .1       0  4988.6     .07       0
  4994.8      .1       0
Bank Sta=4988.6,4994.8
XS Rating Curve= 0 ,0
Exp/Cntr=0.3,0.1

Type RM Length L Ch R = 1 ,12859   ,636,636,636
BEGIN DESCRIPTION:
Mapping XS 60bea9b3
END DESCRIPTION:
XS GIS Cut Line= 3
      2016618.36      13644417.3      2015641.76     13644039.68
      2014864.82     13644187.26
#Sta/Elev= 30
  4181.4  773.33  4394.9   772.6  4454.8  771.71    4504  771.63  4517.4  772.24
  4603.1  771.37  4624.6  771.77  4656.8  771.04  4872.2   770.6  4945.6  770.36
    4957  771.49  4967.7  771.44  4975.5  770.75  4980.9  766.65  4996.7  762.35
  4997.2  761.55  5002.5  761.55    5003  762.35  5005.5  762.46  5010.8  767.47
  5030.1  765.13  5035.4  769.93  5042.7  767.17  5053.5  767.18    5060  768.35
  5065.4  770.43  5204.5  771.35  5491.4  773.18  5632.3  774.14  6019.3  775.27
#Mann= 6 ,-1 , 0
  4181.4     .05       0  4872.2      .1       0  4996.7     .07       0
    5003      .1       0  5204.5     .05       0  5491.4      .1       0
Bank Sta=4996.7,5003
XS Rating Curve= 0 ,0
Exp/Cntr=0.3,0.1

Type RM Length L Ch R = 1 ,12223   ,380,380,380
BEGIN DESCRIPTION:
Mapping XS af70c20d
END DESCRIPTION:
XS GIS Cut Line= 4
      2017029.01     13644396.39      2016438.84     13643627.47
      2015507.21     13643657.74       2014834.5     13644117.79
#Sta/Elev= 30
  3650.6  772.61  3682.8  772.82  3697.4  771.88  4089.8  771.17  4139.7  771.64
  4154.2  770.92    4175  771.53  4596.5  769.53  4619.9  771.14  4663.8  771.05
  4693.3  769.41  4873.9  768.14  4903.9  768.76  4923.9  768.02  4953.9   770.7
  4967.3  769.27  4983.9  764.96  4990.8  761.75  4991.3  760.95  4996.6  760.95
  4997.1  761.75    5034   769.4    5044  770.22    5074  767.58  5404.2  769.14
  5454.2  770.33  5751.9  771.77  5845.5  772.12  5869.3  772.87    6367  774.94
#Mann= 5 ,-1 , 0
  3650.6      .1       0  4967.3     .05       0  4990.8    .035       0
  4997.1     .05       0  5751.9      .1       0
Bank Sta=4990.8,4997.1
XS Rating Curve= 0 ,0
Exp/Cntr=0.3,0.1

Type RM Length L Ch R = 1 ,11843   ,232,232,232
BEGIN DESCRIPTION:
Mapping XS c2deb668
END DESCRIPTION:
XS GIS Cut Line= 4
      2017211.29     13644196.72      2016640.47      13643219.4
      2015867.46     13643323.53      2015048.55     13643808.81
#Sta/Elev= 30
  3099.8  770.98  3303.2  770.62  3533.7  769.92    3628  769.72  3895.3  768.76
  3975.5   769.4  4005.1  768.47  4049.9  769.17  4055.6  768.43  4071.3  768.43
  4077.1  769.62  4086.2   769.7  4114.3  768.34  4831.4  766.47  4872.8   767.5
  4909.2  767.41  4923.3  766.41  4953.5  768.62  4973.7   766.1  4981.9   763.7
  4983.8  760.08  4984.3  759.28  4989.6  759.28  4990.1  760.08  5010.3  764.32
  5015.9  764.32  5028.1  767.27  5056.6  766.51  5629.2  770.99  5963.5  772.52
#Mann= 8 ,-1 , 0
  3099.8     .05       0  3303.2      .1       0  3533.7     .05       0
    3628      .1       0  4983.8     .07       0  4990.1      .1       0
  5056.6     .05       0  5629.2      .1       0
Bank Sta=4983.8,4990.1
XS Rating Curve= 0 ,0
Exp/Cntr=0.3,0.1

Type RM Length L Ch R = 1 ,11611   ,111,111,111
BEGIN DESCRIPTION:
Mapping XS 6f17e195
END DESCRIPTION:
XS GIS Cut Line= 3
      2017135.01     13643925.06      2016718.35     13643152.51
      2014869.61      13643158.6
#Sta/Elev= 30
  3121.1  770.12  3356.5  769.51  3402.2  769.28  3769.1   768.1  3845.3  769.02
    3911  767.91  3916.6  767.29  3949.1  767.51  3954.7  768.82  3984.7  767.96
  4012.2  768.69  4032.2  767.91    4394  767.15  4767.1  765.94  4912.2  765.78
  4942.2  766.77  4952.2  766.38  4962.2  763.03  4972.2  764.66  4982.2  763.87
  4999.1   760.1  4999.6   759.3  5004.9   759.3  5005.4   760.1  5022.2  765.32
  5032.2  766.33  5160.8  766.99  5259.2  767.08    5696  768.53  5847.6  769.02
#Mann= 10 ,-1 , 0
  3121.1      .1       0  3356.5     .05       0  3402.2      .1       0
    4394     .05       0  4767.1     .08       0  4999.1     .07       0
  5005.4     .08       0  5160.8     .05       0  5259.2     .08       0
    5696      .1       0
Bank Sta=4999.1,5005.4
XS Rating Curve= 0 ,0
Exp/Cntr=0.3,0.1

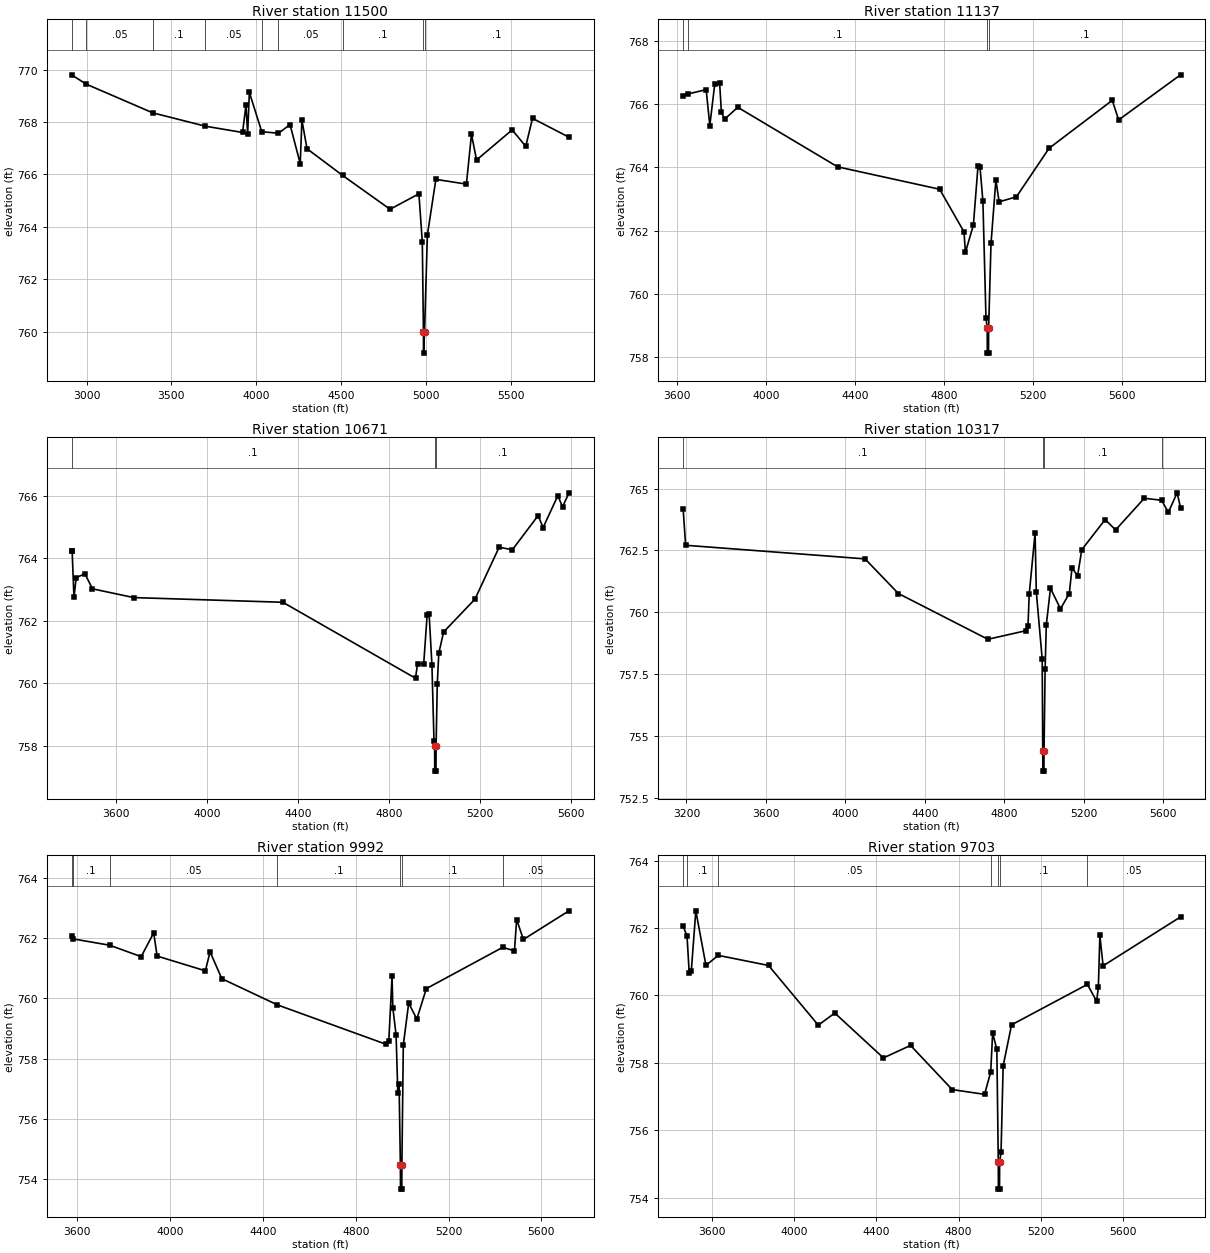
Type RM Length L Ch R = 1 ,11500   ,363,363,363
BEGIN DESCRIPTION:
Mapping XS 045e9ac0
END DESCRIPTION:
XS GIS Cut Line= 3
      2017169.75     13643873.02      2016918.01     13643065.71
      2014830.11      13643050.1
#Sta/Elev= 30
  2911.1   769.8  2999.3  769.44  3389.8  768.35  3700.4  767.84  3919.8   767.6
  3939.8  768.64  3949.8  767.56  3959.8  769.13  4032.9  767.63  4131.3  767.57
  4199.8   767.9  4259.8  766.41  4269.8  768.07  4299.8  766.98  4509.9  765.96
  4789.8  764.67  4959.8  765.26  4979.8  763.42  4986.6  759.98  4987.1  759.18
  4992.9  759.98  5009.8  763.69  5059.8  765.81  5239.8  765.63  5269.8  767.53
  5299.8  766.55  5509.8   767.7  5589.8  767.07  5629.8  768.14  5844.7  767.42
#Mann= 9 ,-1 , 0
  2911.1      .1       0  2999.3     .05       0  3389.8      .1       0
  3700.4     .05       0  4032.9     .08       0  4131.3     .05       0
  4509.9      .1       0  4986.6     .07       0  4992.9      .1       0
Bank Sta=4986.6,4992.9
XS Rating Curve= 0 ,0
Exp/Cntr=0.3,0.1

Type RM Length L Ch R = 1 ,11137   ,466,466,466
BEGIN DESCRIPTION:
Mapping XS 3505441d
END DESCRIPTION:
XS GIS Cut Line= 4
      2016833.68     13642764.25      2016072.21     13642405.56
      2015511.55     13642794.02      2014812.78     13642945.93
#Sta/Elev= 30
  3626.2  766.26  3646.1  766.33  3729.9  766.47  3746.3  765.33  3768.4  766.64
  3790.6  766.68  3798.3  765.76  3812.7  765.53  3872.1  765.91  4321.7  764.02
  4780.8  763.31  4890.3  761.96  4896.8  761.31  4932.6  762.17  4953.5  764.05
  4962.3  764.03  4975.5  762.93  4989.3  759.23  4994.9  758.91  4995.4  758.11
  5000.8  758.11  5001.3  758.91    5012  761.59  5033.9   763.6  5048.5  762.91
  5126.5  763.07  5273.3  764.61  5557.8  766.13  5586.5  765.51  5865.1  766.94
#Mann= 4 ,-1 , 0
  3626.2     .05       0  3646.1      .1       0  4994.9     .07       0
  5001.3      .1       0
Bank Sta=4994.9,5001.3
XS Rating Curve= 0 ,0
Exp/Cntr=0.3,0.1

Type RM Length L Ch R = 1 ,10671   ,354,354,354
BEGIN DESCRIPTION:
Mapping XS 63f4112b
END DESCRIPTION:
XS GIS Cut Line= 5
      2016705.15     13642257.25      2015950.88     13642032.29
      2015515.89       13642156.      2015238.12     13642581.35
      2014886.52     13642846.13
#Sta/Elev= 30
  3404.1  764.22  3406.8  764.22  3414.7  762.75  3424.7  763.38    3463   763.5
  3496.2  763.02  3677.6  762.74  4333.4  762.59  4916.9  760.16  4925.7  760.63
  4952.8  760.62  4967.9  762.18  4976.7  762.21    4989  760.59  4998.1  758.15
  5000.9  757.99  5001.4  757.19  5006.8  757.19  5007.3  757.99  5012.5  759.98
  5019.2  760.96  5040.3  761.64  5178.3  762.69  5284.5  764.35  5342.8  764.27
  5455.8  765.36  5478.1  764.98  5542.7     766  5563.5  765.64  5591.6  766.09
#Mann= 3 ,-1 , 0
  3404.1      .1       0  5000.9     .07       0  5007.3      .1       0
Bank Sta=5000.9,5007.3
XS Rating Curve= 0 ,0
Exp/Cntr=0.3,0.1

Type RM Length L Ch R = 1 ,10317   ,325,325,325
BEGIN DESCRIPTION:
Mapping XS 2d46cad3
END DESCRIPTION:
XS GIS Cut Line= 5
      2016706.88     13642226.43      2015646.75     13641846.61
      2015272.84     13641995.41       2014934.3     13642472.84
       2014579.2     13642633.07
#Sta/Elev= 30
  3183.7  764.19  3196.3  762.71  4099.2  762.16    4267  760.76  4717.5  758.91
  4910.7  759.26  4919.3  759.43  4925.4  760.72    4955  763.21  4961.1  760.83
  4990.7  758.12  4993.6  754.38  4994.1  753.58  4999.5  753.58    5000  754.38
  5005.4  757.69  5011.6   759.5  5032.5  760.97  5082.9  760.14  5127.2  760.76
  5140.8  761.79  5169.1  761.48    5190  762.53  5307.7  763.75  5360.3  763.33
  5504.6  764.61  5591.7  764.53  5625.7  764.04  5669.8  764.83  5687.1  764.23
#Mann= 4 ,-1 , 0
  3183.7      .1       0  4993.6     .07       0    5000      .1       0
  5591.7     .05       0
Bank Sta=4993.6,5000
XS Rating Curve= 0 ,0
Exp/Cntr=0.3,0.1

Type RM Length L Ch R = 1 ,9992    ,289,289,289
BEGIN DESCRIPTION:
Mapping XS 29f0cc93
END DESCRIPTION:
XS GIS Cut Line= 4
      2016445.22     13641885.34      2015685.56     13641769.84
      2015086.21     13641921.63      2014388.73     13642216.21
#Sta/Elev= 30
  3574.9  762.05  3580.4  761.97  3738.9  761.76    3875  761.38  3929.1  762.17
  3943.7   761.4  4151.7  760.91  4171.9  761.54  4222.5  760.65  4462.4  759.78
  4931.9  758.47  4942.2  758.58  4956.3  760.73  4959.6  759.69  4973.7  758.78
  4981.1  756.86  4986.6  757.15  4992.2  754.47  4992.7  753.67  4998.2  753.67
  4998.7  754.47  5004.8  758.45    5028  759.84  5063.1  759.31    5104  760.32
  5433.6  761.69  5483.9  761.57  5493.2  762.61  5522.4  761.95  5718.7   762.9
#Mann= 7 ,-1 , 0
  3574.9     .05       0  3580.4      .1       0  3738.9     .05       0
  4462.4      .1       0  4992.2     .07       0  4998.7      .1       0
  5433.6     .05       0
Bank Sta=4992.2,4998.7
XS Rating Curve= 0 ,0
Exp/Cntr=0.3,0.1

Type RM Length L Ch R = 1 ,9703    ,315,315,315
BEGIN DESCRIPTION:
Mapping XS 216c5ca1
END DESCRIPTION:
XS GIS Cut Line= 4
       2016460.4     13641861.64      2015801.09     13641498.99
      2014938.64     13641674.23      2014258.59     13642064.06
#Sta/Elev= 30
  3461.5  762.05  3480.4  761.77  3490.9  760.68  3501.3  760.73  3523.1  762.51
  3572.4  760.89  3631.9  761.19  3876.4  760.89  4118.2  759.12  4198.1  759.48
  4434.5  758.15  4566.3  758.52  4768.8  757.21  4925.8  757.07  4955.7  757.73
  4965.1  758.89  4985.5   758.4  4992.5  755.06    4993  754.26  4998.5  754.26
    4999  755.06  5005.9  755.36  5016.1  757.91  5056.9  759.13  5425.5  760.33
  5470.2  759.83  5478.6  760.24    5486  761.78  5501.7  760.88  5877.9  762.33
#Mann= 7 ,-1 , 0
  3461.5     .05       0  3480.4      .1       0  3631.9     .05       0
  4955.7      .1       0  4992.5     .07       0    4999      .1       0
  5425.5     .05       0
Bank Sta=4992.5,4999
XS Rating Curve= 0 ,0
Exp/Cntr=0.3,0.1

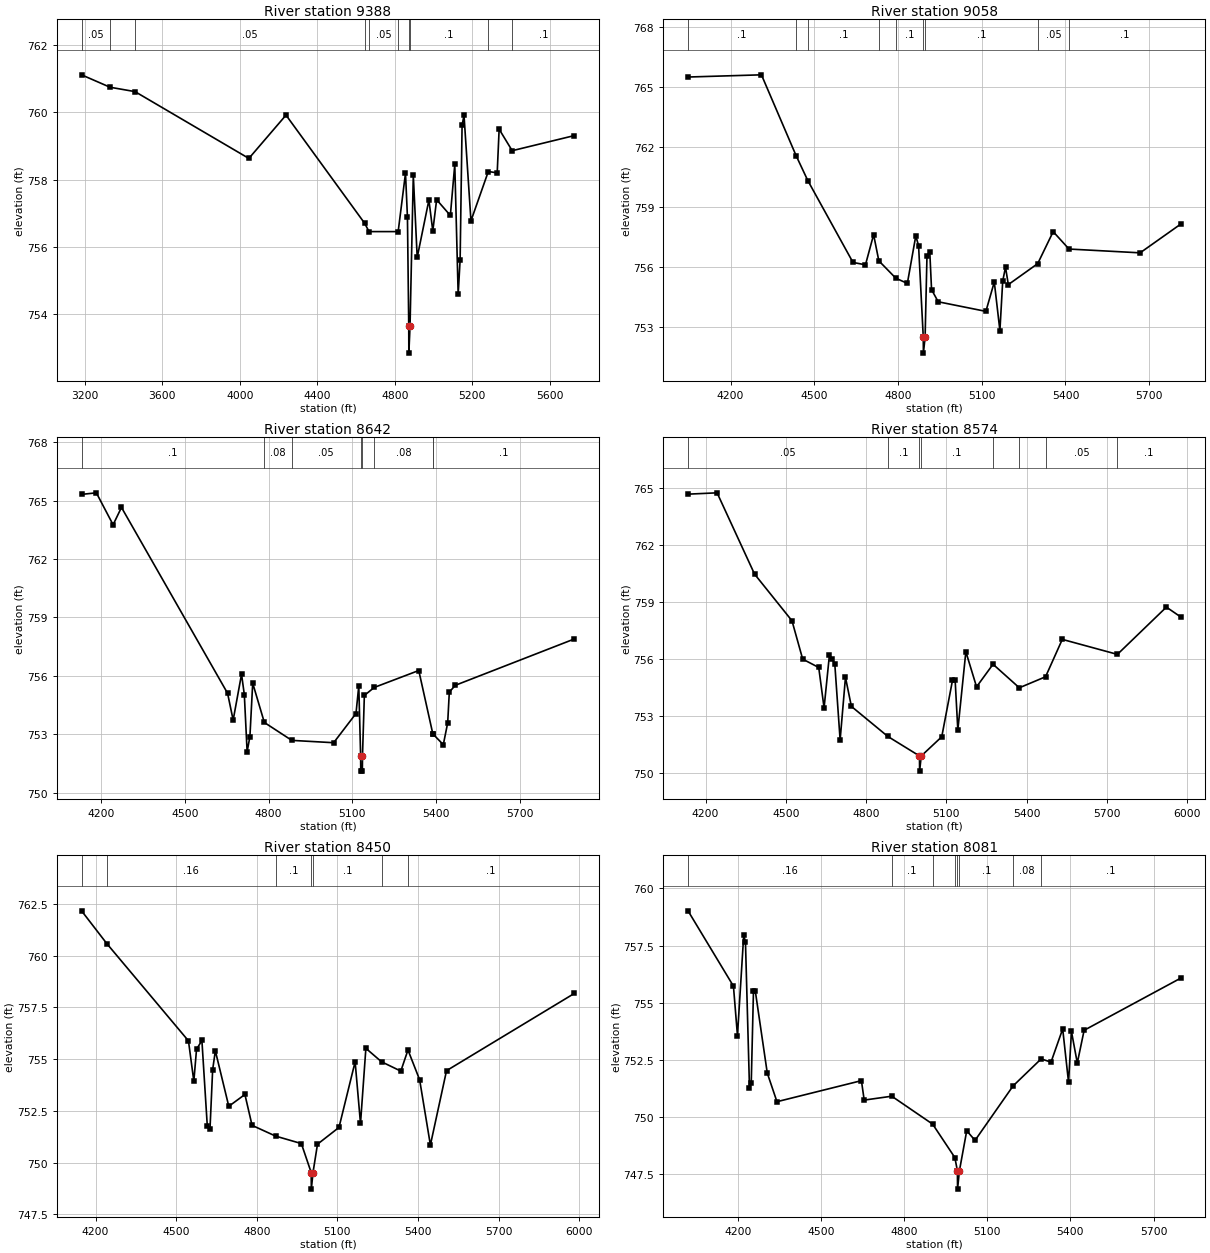
Type RM Length L Ch R = 1 ,9388    ,330,330,330
BEGIN DESCRIPTION:
Mapping XS 1b176142
END DESCRIPTION:
XS GIS Cut Line= 3
      2016581.97     13641813.92      2015770.32     13641280.05
      2014209.73     13641461.53
#Sta/Elev= 30
    3184  761.12  3331.2  760.75  3459.8  760.62  4047.3  758.63    4239  759.92
  4644.5   756.7  4667.5  756.45  4817.7  756.45  4855.5  758.19  4865.6  756.88
  4872.3  753.63  4872.8  752.83  4878.9  753.63  4895.8  758.13  4915.9  755.68
  4976.3  757.39  4996.4  756.47  5016.2   757.4    5087  756.93  5109.8  758.45
  5127.3  754.58  5137.4  755.61  5147.5  759.62  5157.5  759.91  5193.3  756.77
  5282.8  758.24  5328.7   758.2  5338.7   759.5  5406.1  758.86  5726.6  759.31
#Mann= 10 ,-1 , 0
    3184     .05       0  3331.2      .1       0  3459.8     .05       0
  4644.5      .1       0  4667.5     .05       0  4817.7      .1       0
  4872.3     .07       0  4878.9      .1       0  5282.8     .05       0
  5406.1      .1       0
Bank Sta=4872.3,4878.9
XS Rating Curve= 0 ,0
Exp/Cntr=0.3,0.1

Type RM Length L Ch R = 1 ,9058    ,416,416,416
BEGIN DESCRIPTION:
Mapping XS 10429fe0
END DESCRIPTION:
XS GIS Cut Line= 3
      2015858.77     13640788.82      2015242.46     13641018.85
      2014140.02     13641127.35
#Sta/Elev= 30
  4047.6  765.52  4310.7  765.63  4434.7  761.59  4476.7  760.34  4638.7  756.24
  4683.4  756.12  4712.6  757.63  4731.3  756.32  4792.2  755.45  4833.5  755.19
  4863.7  757.57  4873.7  757.08  4890.5   752.5    4891   751.7  4897.1   752.5
  4903.8  756.57  4913.9  756.76  4920.2  754.88    4944  754.27  5114.9  753.79
    5145  755.26  5165.1  752.83  5175.2  755.31  5185.2     756  5195.3  755.13
  5300.6  756.18    5356  757.78  5412.7  756.91  5667.5  756.72  5813.2  758.16
#Mann= 9 ,-1 , 0
  4047.6      .1       0  4434.7     .05       0  4476.7      .1       0
  4731.3     .05       0  4792.2      .1       0  4890.5     .07       0
  4897.1      .1       0  5300.6     .05       0  5412.7      .1       0
Bank Sta=4890.5,4897.1
XS Rating Curve= 0 ,0
Exp/Cntr=0.3,0.1

Type RM Length L Ch R = 1 ,8642    ,68,68,68
BEGIN DESCRIPTION:
Mapping XS 1a43c38a
END DESCRIPTION:
XS GIS Cut Line= 3
      2015798.04     13640628.22      2014626.14      13640636.9
        2014114.     13640936.37
#Sta/Elev= 30
  4129.8  765.32  4182.8   765.4  4242.8  763.76  4272.8  764.65  4652.9   755.1
  4672.9  753.72  4702.9  756.08  4712.9  755.03  4722.9   752.1  4732.9  752.87
  4742.9  755.62  4784.6   753.6    4883  752.68  5032.9  752.56  5112.9  754.06
  5122.9  755.48  5129.5   751.9    5130   751.1  5135.7   751.1  5136.2   751.9
  5142.9  754.99  5178.3   755.4  5337.8  756.27  5388.2  753.01  5388.4  753.01
  5425.7  752.46  5441.4  753.58  5447.2  755.16  5468.7  755.51    5895  757.89
#Mann= 8 ,-1 , 0
  4129.8      .1       0  4784.6     .08       0    4883     .05       0
  5129.5     .04       0  5136.2     .05       0  5178.3     .08       0
  5388.2     .05       0  5388.4      .1       0
Bank Sta=5129.5,5136.2
XS Rating Curve= 0 ,0
Exp/Cntr=0.3,0.1

Type RM Length L Ch R = 1 ,8574    ,124,124,124
BEGIN DESCRIPTION:
Mapping XS fdcf3faf
END DESCRIPTION:
XS GIS Cut Line= 3
       2015793.7     13640576.14      2014504.61     13640563.12
      2013983.79     13640749.74
#Sta/Elev= 30
  4134.3   764.7    4243  764.77    4383  760.49    4523  758.03    4563  756.01
    4623  755.57    4643  753.44    4663  756.23    4673  756.01    4683  755.77
    4703  751.75    4723  755.05  4745.1  753.52  4881.1  751.94  4999.7  750.91
  5000.2  750.11  5006.4  750.91    5083  751.92  5123.1  754.89  5133.1  754.89
  5143.1  752.28  5173.1   756.4  5213.1  754.55  5274.7  755.74    5373   754.5
  5471.1  755.08  5533.7  757.05  5739.7  756.26  5922.9  758.75  5976.7  758.23
#Mann= 8 ,-1 , 0
  4134.3     .05       0  4881.1      .1       0  4999.7     .07       0
  5006.4      .1       0  5274.7     .08       0    5373      .1       0
  5471.1     .05       0  5739.7      .1       0
Bank Sta=4999.7,5006.4
XS Rating Curve= 0 ,0
Exp/Cntr=0.3,0.1

Type RM Length L Ch R = 1 ,8450    ,369,369,369
BEGIN DESCRIPTION:
Mapping XS eecf2370
END DESCRIPTION:
XS GIS Cut Line= 2
      2015772.66     13640443.98      2013939.64     13640461.34
#Sta/Elev= 30
  4148.1  762.16  4242.5  760.57  4545.8  755.88  4565.8  753.93  4575.8  755.47
  4595.8   755.9  4615.8  751.78  4625.8   751.6  4635.8  754.49  4645.8   755.4
  4695.8  752.72  4755.8  753.29  4782.4   751.8  4870.2  751.28  4965.8  750.92
  5002.4  749.52  5002.9  748.72  5009.1  749.52  5025.8  750.89  5105.8   751.7
  5165.8  754.87  5185.8  751.89  5205.8  755.52    5264  754.87  5335.8  754.42
  5362.4  755.44  5405.8     754  5445.8  750.85  5505.8  754.44  5981.2  758.17
#Mann= 7 ,-1 , 0
  4148.1      .1       0  4242.5     .16       0  4870.2      .1       0
  5002.4     .07       0  5009.1      .1       0    5264     .08       0
  5362.4      .1       0
Bank Sta=5002.4,5009.1
XS Rating Curve= 0 ,0
Exp/Cntr=0.3,0.1

Type RM Length L Ch R = 1 ,8081    ,353,353,353
BEGIN DESCRIPTION:
Mapping XS bff7d03b
END DESCRIPTION:
XS GIS Cut Line= 4
      2015717.04     13640364.08      2015519.15     13640110.64
       2014612.9     13640107.17      2014090.49     13640280.15
#Sta/Elev= 30
  4020.1  759.02    4184  755.73  4198.5  753.57  4221.1  757.96  4227.4  757.65
  4241.9  751.28  4248.2  751.48  4256.3  755.53  4262.7  755.53  4306.1  751.93
    4341  750.68  4645.8   751.6  4655.8  750.75  4755.3  750.92  4902.8   749.7
  4982.9  748.24  4992.2  747.66  4992.7  746.86  4999.4  747.66  5025.8  749.41
  5055.8  748.99  5193.1  751.37  5294.3  752.55    5330  752.41  5372.1  753.86
  5393.2  751.53  5403.7  753.75  5424.8  752.37  5449.4   753.8  5798.2  756.08
#Mann= 8 ,-1 , 0
  4020.1     .16       0  4755.3      .1       0  4902.8     .16       0
  4982.9      .1       0  4992.2     .07       0  4999.4      .1       0
  5193.1     .08       0  5294.3      .1       0
Bank Sta=4992.2,4999.4
XS Rating Curve= 0 ,0
Exp/Cntr=0.3,0.1

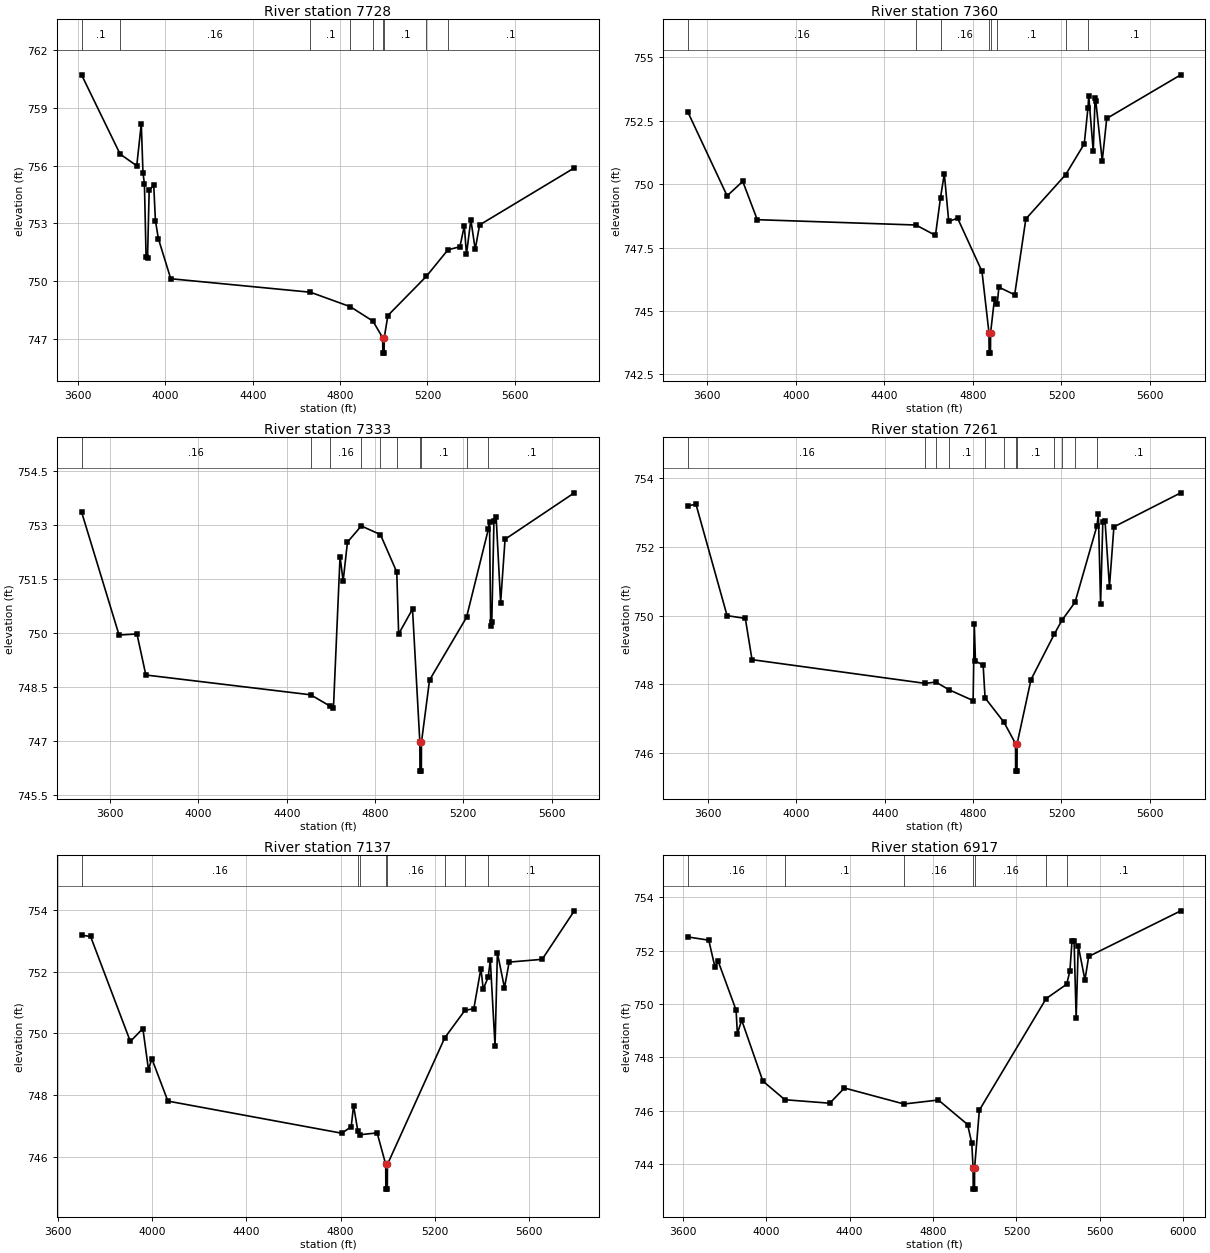
Type RM Length L Ch R = 1 ,7728    ,368,368,368
BEGIN DESCRIPTION:
Mapping XS 08cfb78d
END DESCRIPTION:
XS GIS Cut Line= 3
      2016006.56     13640340.02      2015524.36     13639787.73
      2014001.31     13639754.07
#Sta/Elev= 30
  3616.1  760.71  3792.5   756.6  3868.9  755.99  3889.7  758.18  3897.3  755.64
    3904  755.05  3911.6  751.24  3918.2  751.21  3925.8  754.72  3946.7  754.98
  3954.3  753.15  3967.9  752.21  4024.5  750.13  4664.1  749.43  4846.7  748.68
  4950.5  747.93  4995.1  747.07  4995.7  746.27  5001.9  746.27  5002.4  747.07
  5018.8  748.22  5195.6  750.26  5293.9  751.63  5348.9  751.79  5368.9  752.87
  5378.9   751.4  5398.9  753.19  5418.9  751.65  5438.9  752.92  5872.7  755.88
#Mann= 9 ,-1 , 0
  3616.1      .1       0  3792.5     .16       0  4664.1      .1       0
  4846.7     .16       0  4950.5      .1       0  4995.1     .07       0
  5002.4      .1       0  5195.6     .08       0  5293.9      .1       0
Bank Sta=4995.1,5002.4
XS Rating Curve= 0 ,0
Exp/Cntr=0.3,0.1

Type RM Length L Ch R = 1 ,7360    ,27,27,27
BEGIN DESCRIPTION:
Mapping XS 69fd4203
END DESCRIPTION:
XS GIS Cut Line= 6
      2016269.92     13639554.17      2015959.99     13639596.76
      2015046.93     13639596.76      2015039.98     13639485.64
      2014897.62     13639440.51       2014175.4     13639565.51
#Sta/Elev= 30
  3512.9  752.83  3689.5  749.54  3760.1  750.11  3825.7   748.6  4543.1  748.39
  4630.7  747.98  4653.6  749.47  4670.7  750.41  4690.7  748.53  4730.7  748.66
  4840.9  746.56  4872.5  744.14  4873.1  743.34  4879.3  743.34  4879.8  744.14
  4897.1  745.46  4909.3  745.26  4917.4  745.94  4988.6  745.64  5039.1  748.63
  5219.4  750.38    5303  751.59  5319.8  753.02  5323.3  753.47  5343.6   751.3
  5351.8  753.38  5354.9  753.29  5384.2  750.92  5404.5  752.59    5739  754.31
#Mann= 8 ,-1 , 0
  3512.9     .16       0  4543.1      .1       0  4653.6     .16       0
  4872.5     .07       0  4879.8     .16       0  4909.3      .1       0
  5219.4     .08       0  5319.8      .1       0
Bank Sta=4872.5,4879.8
XS Rating Curve= 0 ,0
Exp/Cntr=0.3,0.1

Type RM Length L Ch R = 1 ,7333    ,72,72,72
BEGIN DESCRIPTION:
Mapping XS 05e7c999
END DESCRIPTION:
XS GIS Cut Line= 6
      2016271.14     13639507.31        2016016.     13639558.79
      2015095.54     13639568.98      2015105.95     13639426.62
      2014970.54     13639405.78      2014203.19     13639492.59
#Sta/Elev= 30
  3470.1  753.35    3640  749.93  3721.2  749.96  3761.4  748.82  4508.4  748.27
  4597.7  747.95  4611.4  747.89  4641.4  752.11  4655.4  751.43  4674.9  752.51
  4737.6  752.96  4824.4  752.72  4898.4  751.68  4906.9  749.96  4969.8  750.65
    5003  746.95  5003.6  746.15  5009.8  746.15  5010.3  746.95  5046.9  748.68
  5214.4  750.42  5313.8  752.88  5318.7  753.08  5323.9  750.17  5328.9  750.28
  5338.8   753.1  5348.8   753.2    5369  750.83  5389.1  752.59  5702.9  753.88
#Mann= 10 ,-1 , 0
  3470.1     .16       0  4508.4      .1       0  4597.7     .16       0
  4737.6      .1       0  4824.4     .16       0  4898.4      .1       0
    5003     .07       0  5010.3      .1       0  5214.4     .08       0
  5313.8      .1       0
Bank Sta=5003,5010.3
XS Rating Curve= 0 ,0
Exp/Cntr=0.3,0.1

Type RM Length L Ch R = 1 ,7261    ,124,124,124
BEGIN DESCRIPTION:
Mapping XS c0957bd3
END DESCRIPTION:
XS GIS Cut Line= 6
       2016280.3     13639487.77      2016002.98     13639538.01
      2015144.15     13639544.67       2015137.2     13639384.95
       2014887.2     13639371.06      2014213.57     13639437.04
#Sta/Elev= 30
  3508.9  753.19  3544.8  753.24  3685.8     750  3768.4  749.92  3798.7  748.72
  4583.9  748.03  4631.1  748.07  4689.5  747.85  4800.1  747.53  4805.3  749.76
  4810.6  748.68  4845.5  748.56  4854.1  747.61  4939.8   746.9  4992.1  746.28
  4992.6  745.48  4998.8  745.48  4999.4  746.28  5062.2  748.14  5168.3  749.47
  5201.9  749.86  5261.7  750.39  5360.9  752.61  5367.3  752.95  5377.3  750.34
  5387.4  752.72  5397.4  752.76  5417.5  750.84  5437.6  752.58  5740.5  753.57
#Mann= 12 ,-1 , 0
  3508.9     .16       0  4583.9      .1       0  4631.1     .16       0
  4689.5      .1       0  4854.1     .16       0  4939.8      .1       0
  4992.1     .07       0  4999.4      .1       0  5168.3     .16       0
  5201.9      .1       0  5261.7     .08       0  5360.9      .1       0
Bank Sta=4992.1,4999.4
XS Rating Curve= 0 ,0
Exp/Cntr=0.3,0.1

Type RM Length L Ch R = 1 ,7137    ,220,220,220
BEGIN DESCRIPTION:
Mapping XS 7a03ecc0
END DESCRIPTION:
XS GIS Cut Line= 3
      2016280.34     13639479.98      2015819.89     13639287.99
      2014228.77     13639318.95
#Sta/Elev= 30
  3700.9  753.18  3739.2  753.14  3907.9  749.74    3961  750.16  3984.8  748.83
  3999.2  749.18  4067.1  747.81  4804.8  746.77  4844.8  746.98  4854.8  747.66
  4872.9  746.84  4880.2  746.72  4954.8  746.78  4991.2  745.76  4991.7  744.96
  4997.9  744.96  4998.5  745.76  5241.7  749.86  5327.3  750.75  5364.9   750.8
  5394.9   752.1  5404.9  751.44  5425.8  751.82  5434.9  752.37  5454.9  749.59
  5464.9  752.61  5494.9  751.48  5514.9  752.31  5654.9   752.4  5791.2  753.97
#Mann= 8 ,-1 , 0
  3700.9     .16       0  4872.9      .1       0  4880.2     .16       0
  4991.2     .07       0  4998.5     .16       0  5241.7      .1       0
  5327.3     .08       0  5425.8      .1       0
Bank Sta=4991.2,4998.5
XS Rating Curve= 0 ,0
Exp/Cntr=0.3,0.1

Type RM Length L Ch R = 1 ,6917    ,382,382,382
BEGIN DESCRIPTION:
Mapping XS 2de2550e
END DESCRIPTION:
XS GIS Cut Line= 3
      2016306.31     13639413.53       2015810.3     13639068.37
      2014053.88     13639138.42
#Sta/Elev= 30
  3625.6  752.51    3725  752.39  3754.7  751.38  3769.6  751.61    3856  749.77
  3862.1  748.89    3883  749.39  3984.3  747.11  4089.9  746.41  4305.2  746.28
  4375.3  746.85  4660.9  746.25  4825.7   746.4  4965.8  745.48  4985.8  744.78
  4992.1  743.86  4992.7  743.06  4998.9  743.06  4999.4  743.86  5022.2  746.02
  5342.3   750.2  5440.9  750.74  5456.2  751.24  5466.2  752.35  5476.2  752.37
  5486.2  749.46  5496.2  752.18  5528.3   750.9  5546.2  751.78  5987.7  753.49
#Mann= 7 ,-1 , 0
  3625.6     .16       0  4089.9      .1       0  4660.9     .16       0
  4992.1     .07       0  4999.4     .16       0  5342.3     .08       0
  5440.9      .1       0
Bank Sta=4992.1,4999.4
XS Rating Curve= 0 ,0
Exp/Cntr=0.3,0.1