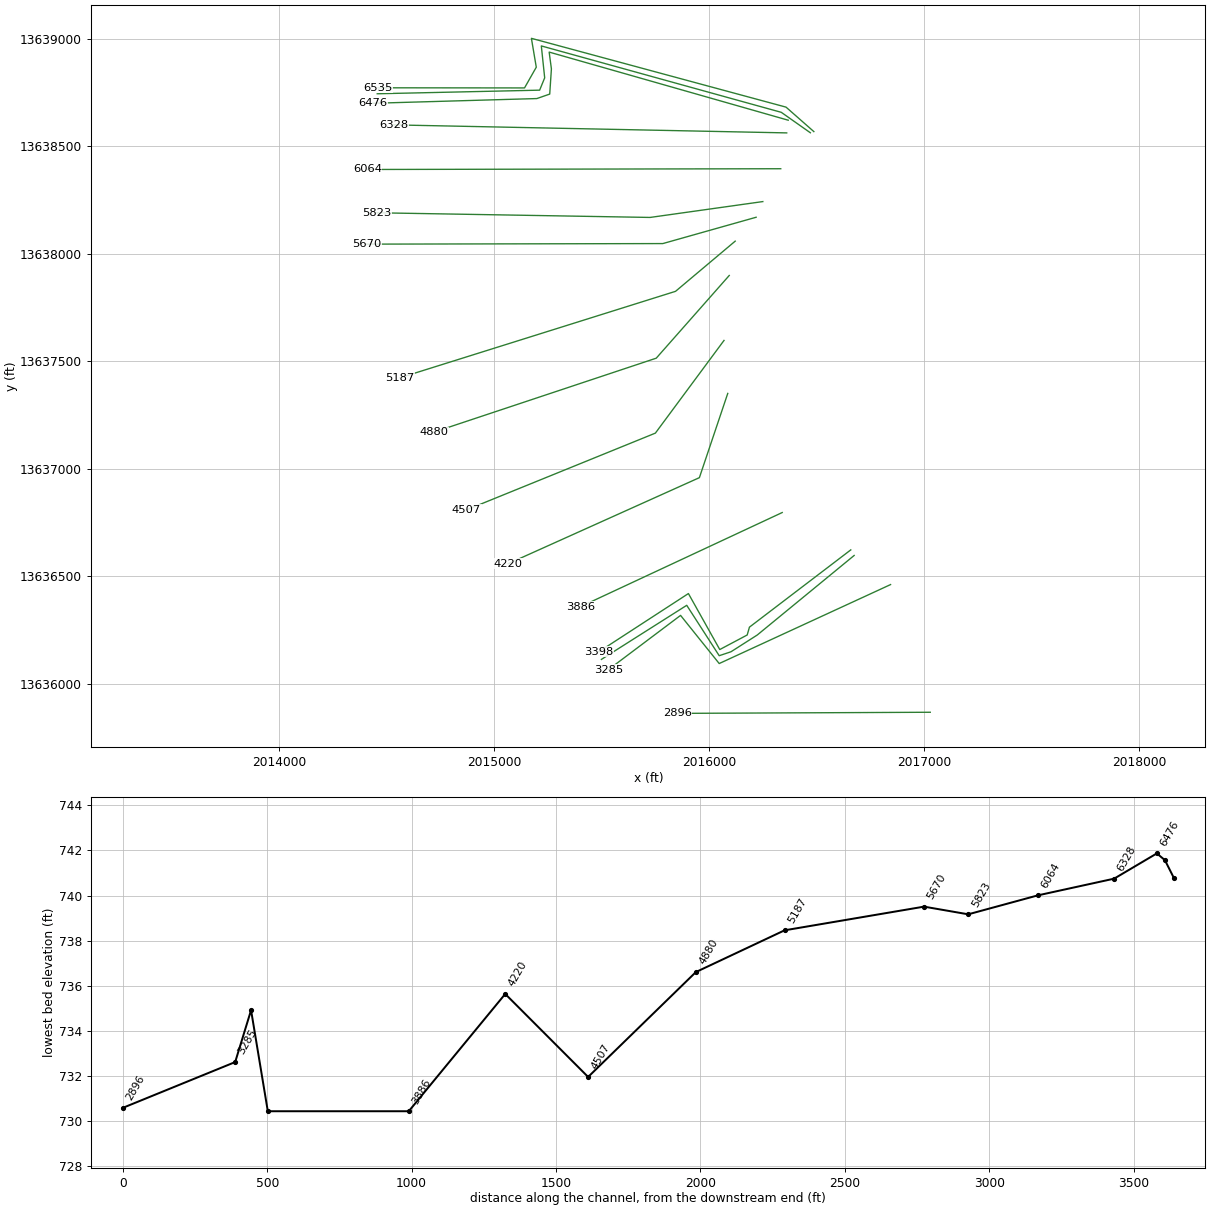
HEC-RAS study WP FORT EWELL CREEK.prj: WP FORT EWELL CREEK Base Level Engineering

--- WP FORT EWELL CREEK.g01 (geometry) --- (continued)

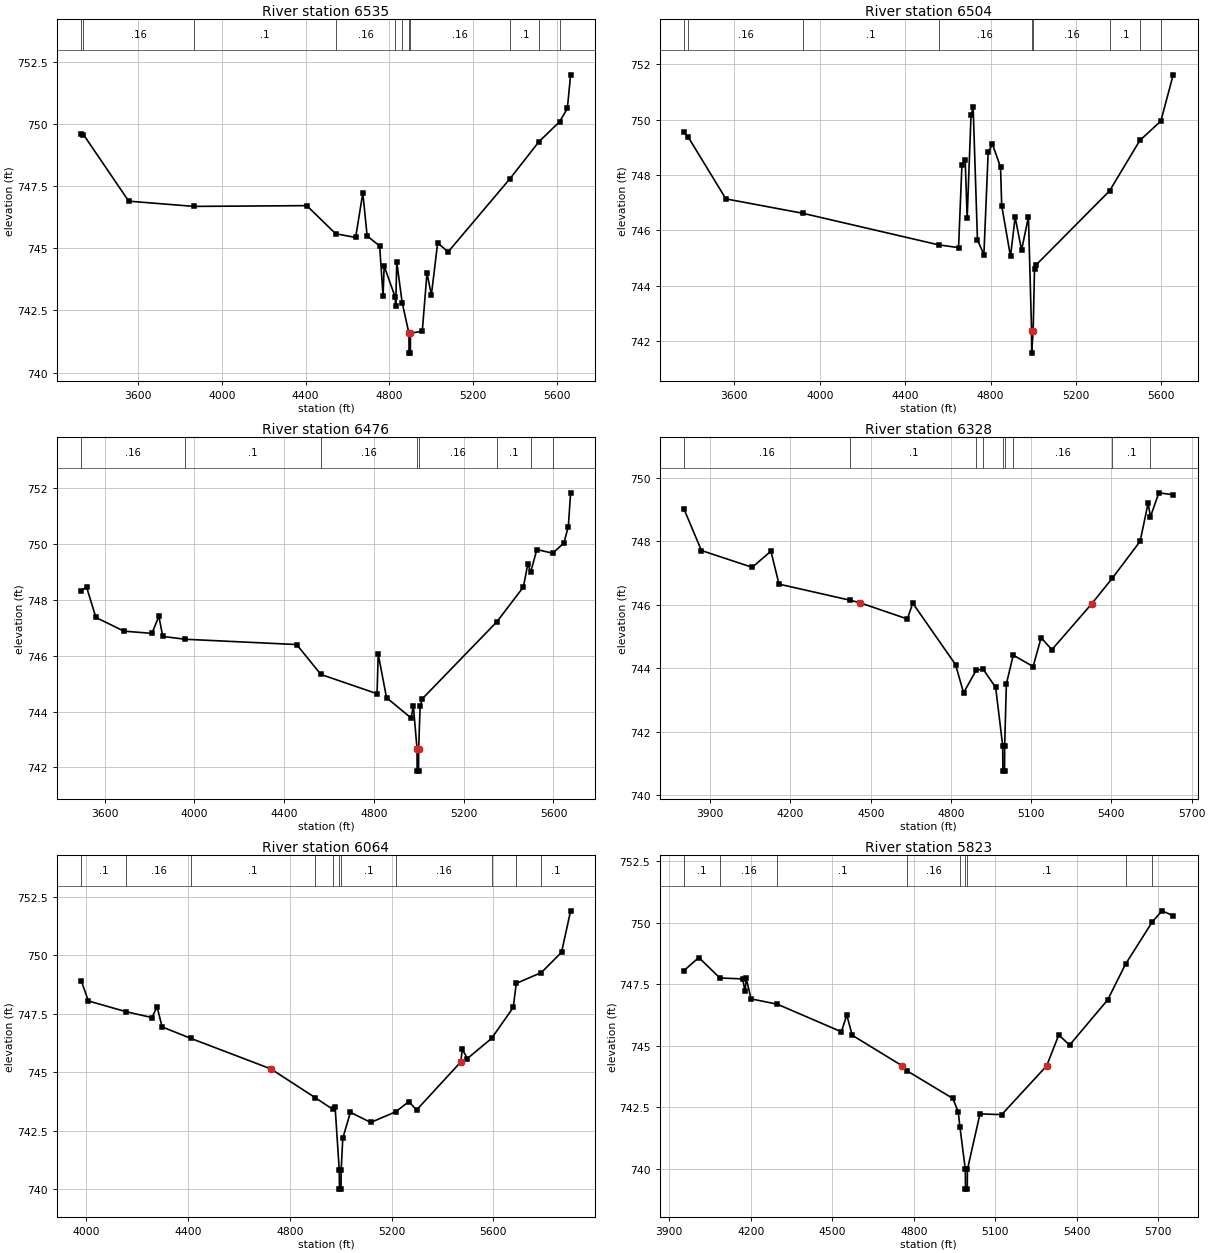
Type RM Length L Ch R = 1 ,6535    ,31,31,31
BEGIN DESCRIPTION:
Mapping XS b8f99c21
END DESCRIPTION:
XS GIS Cut Line= 6
      2016486.35     13638567.24      2016356.91     13638681.05
      2015172.66     13639001.01      2015195.36     13638866.72
      2015140.68     13638770.37      2014459.54     13638770.98
#Sta/Elev= 30
  3328.7  749.59  3338.4  749.57    3555  746.89    3867  746.68  4405.9  746.71
  4544.3  745.58  4639.6  745.43  4673.9  747.22  4694.6  745.49  4754.3  745.09
  4770.7  743.06  4775.8  744.28  4828.4  743.04  4831.1  742.68  4836.2  744.44
    4862  742.81  4894.3  741.58  4894.9  740.78  4901.1  740.78  4901.7  741.58
  4958.1  741.66  4980.6     744  5001.6  743.12  5031.6  745.21  5081.6  744.85
  5377.9   747.8  5515.6  749.28    5614  750.08  5651.6  750.62  5667.1  751.97
#Mann= 11 ,-1 , 0
  3328.7      .1       0  3338.4     .16       0    3867      .1       0
  4544.3     .16       0  4828.4      .1       0    4862     .16       0
  4894.3     .07       0  4901.7     .16       0  5377.9      .1       0
  5515.6     .05       0    5614      .1       0
Bank Sta=4894.3,4901.7
XS Rating Curve= 0 ,0
Exp/Cntr=0.3,0.1

Type RM Length L Ch R = 1 ,6504    ,28,28,28
BEGIN DESCRIPTION:
Mapping XS 40c7bfe0
END DESCRIPTION:
XS GIS Cut Line= 6
      2016470.06     13638561.82      2016334.83      13638656.9
       2015218.8     13638965.68      2015234.43     13638817.24
      2015210.99     13638759.95      2014455.65      13638743.2
#Sta/Elev= 30
  3364.5  749.54  3383.7  749.38  3560.8  747.14  3920.8  746.62  4556.8  745.48
  4650.2  745.38  4666.1  748.38  4681.3  748.55  4690.6  746.44  4708.6  750.16
  4718.6  750.45  4738.7  745.66  4768.9  745.13    4789  748.84  4809.1  749.11
  4846.8  748.29  4852.2   746.9  4893.5  745.06  4915.1  746.48  4945.3  745.29
  4977.4  746.49  4992.1  742.37  4992.6  741.57  4999.5  742.37  5005.9   744.6
    5014  744.76  5357.5  747.43    5499  749.25  5597.4  749.95  5655.3  751.62
#Mann= 9 ,-1 , 0
  3364.5      .1       0  3383.7     .16       0  3920.8      .1       0
  4556.8     .16       0  4992.1     .07       0  4999.5     .16       0
  5357.5      .1       0    5499     .05       0  5597.4      .1       0
Bank Sta=4992.1,4999.5
XS Rating Curve= 0 ,0
Exp/Cntr=0.3,0.1

Type RM Length L Ch R = 1 ,6476    ,148,148,148
BEGIN DESCRIPTION:
Mapping XS 8599187b
END DESCRIPTION:
XS GIS Cut Line= 6
      2016367.12     13638620.22      2015255.26     13638937.03
      2015265.68     13638858.91      2015257.86     13638741.72
      2015197.97     13638720.89      2014434.78     13638698.93
#Sta/Elev= 30
    3497  748.33    3520  748.46  3561.6  747.37  3686.4  746.88  3811.1   746.8
  3842.3  747.41  3859.5  746.69  3958.8  746.59  4455.8   746.4    4564  745.33
  4814.1  744.64  4819.2  746.06  4856.2   744.5  4965.8  743.77  4975.8  744.21
  4992.1  742.67  4992.6  741.87  4998.9  741.87  4999.5  742.67  5005.8  744.19
  5015.8  744.46  5348.4  747.22    5466  748.46    5486   749.3  5497.9  748.98
    5526   749.8  5596.2  749.67  5646.1  750.03  5666.1  750.62  5676.3  751.83
#Mann= 8 ,-1 , 0
    3497     .16       0  3958.8      .1       0    4564     .16       0
  4992.1     .07       0  4999.5     .16       0  5348.4      .1       0
  5497.9     .05       0  5596.2      .1       0
Bank Sta=4992.1,4999.5
XS Rating Curve= 0 ,0
Exp/Cntr=0.3,0.1

Type RM Length L Ch R = 1 ,6328    ,264,264,264
BEGIN DESCRIPTION:
Mapping XS 89c802a0
END DESCRIPTION:
XS GIS Cut Line= 2
      2016360.16      13638561.2      2014531.35     13638598.49
#Sta/Elev= 30
  3801.8  749.02    3867  747.71    4057  747.18    4127  747.69    4157  746.65
    4424  746.14 4461.52746.0569  4637.1  745.55  4657.1  746.05  4817.2  744.11
  4847.2  743.22  4894.7  743.94  4920.8  743.96  4967.2  743.39  4993.5  741.55
  4994.1  740.75  5000.4  740.75  5000.9  741.55  5007.2   743.5    5033  744.41
  5107.2  744.05  5137.2  744.96  5177.3  744.58 5325.71746.0229  5403.6  746.84
  5507.3     748  5537.3  749.21  5545.8  748.77  5577.3  749.53    5631  749.47
#Mann= 9 ,-1 , 0
  3801.8     .16       0    4424      .1       0  4894.7     .16       0
  4920.8      .1       0  4993.5     .07       0  5000.9      .1       0
    5033     .16       0  5403.6      .1       0  5545.8     .05       0
Bank Sta=4461.52,5325.71
XS Rating Curve= 0 ,0
Exp/Cntr=0.3,0.1

Type RM Length L Ch R = 1 ,6064    ,241,241,241
BEGIN DESCRIPTION:
Mapping XS 38ba2774
END DESCRIPTION:
XS GIS Cut Line= 2
      2016332.36     13638394.53      2014409.37     13638391.06
#Sta/Elev= 30
  3980.6   748.9    4008  748.05  4156.5  747.59    4258  747.34    4278   747.8
    4298  746.94  4410.9  746.45 4725.59745.1459  4900.8  743.91  4968.6  743.42
    4978   743.5  4994.3  740.81  4994.8  740.01  5001.1  740.01  5001.7  740.81
    5008  742.18    5038  743.29    5118  742.86  5215.4  743.31    5268  743.75
    5298  743.39 5471.82745.4423    5478  745.98    5498  745.59  5592.9  746.45
    5678  747.77    5690   748.8  5788.4  749.26    5868  750.13  5903.6   751.9
#Mann= 11 ,-1 , 0
  3980.6      .1       0  4156.5     .16       0  4410.9      .1       0
  4900.8     .16       0  4968.6      .1       0  4994.3     .07       0
  5001.7      .1       0  5215.4     .16       0  5592.9      .1       0
    5690     .05       0  5788.4      .1       0
Bank Sta=4725.59,5471.82
XS Rating Curve= 0 ,0
Exp/Cntr=0.3,0.1

Type RM Length L Ch R = 1 ,5823    ,153,153,153
BEGIN DESCRIPTION:
Mapping XS 651be483
END DESCRIPTION:
XS GIS Cut Line= 3
      2016249.04     13638241.75      2015724.73       13638168.
      2014453.89     13638189.67
#Sta/Elev= 30
  3953.9  748.06  4008.5  748.59  4085.9  747.76    4170  747.72  4178.5  747.21
  4183.5  747.74  4200.3  746.91  4297.9  746.69  4533.1  745.57  4553.1  746.25
  4573.1  745.43 4756.91744.1866  4775.1  743.98  4943.2  742.86  4963.2  742.32
  4969.4  741.71  4989.3  739.97  4989.9  739.17  4996.4  739.17  4997.1  739.97
  5043.2  742.23  5123.2   742.2 5288.57744.1829  5333.2  745.44  5373.2  745.03
  5513.3  746.87  5578.9  748.32  5677.4  750.04  5713.3  750.49  5754.4  750.29
#Mann= 9 ,-1 , 0
  3953.9      .1       0  4085.9     .16       0  4297.9      .1       0
  4775.1     .16       0  4969.4      .1       0  4989.3     .07       0
  4997.1      .1       0  5578.9     .08       0  5677.4      .1       0
Bank Sta=4756.91,5288.57
XS Rating Curve= 0 ,0
Exp/Cntr=0.3,0.1

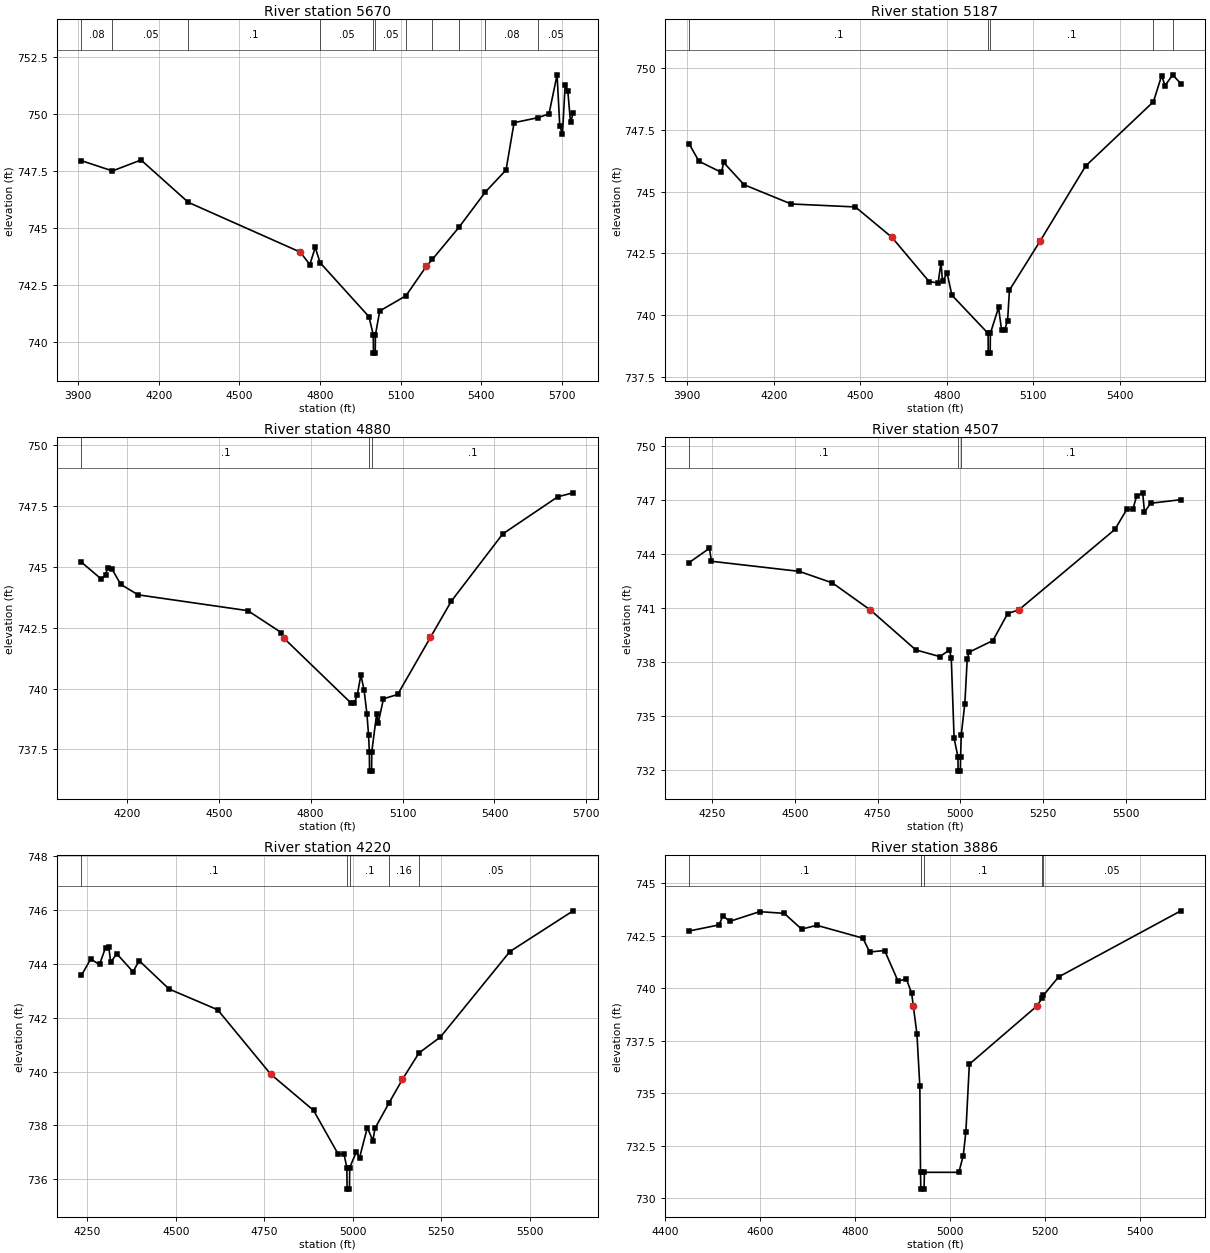
Type RM Length L Ch R = 1 ,5670    ,483,483,483
BEGIN DESCRIPTION:
Mapping XS f9c8ed96
END DESCRIPTION:
XS GIS Cut Line= 3
       2016217.8     13638168.83      2015783.77     13638046.42
      2014405.33     13638043.83
#Sta/Elev= 30
  3912.8  747.96    4028  747.51  4134.3  747.99  4310.4  746.13 4726.69743.9465
  4762.5   743.4  4782.5  744.15  4800.7  743.48  4982.5  741.11  4998.5  740.31
  4999.2  739.51  5005.8  739.51  5006.5  740.31  5022.5  741.36  5120.2  742.03
 5195.54743.3149  5218.6  743.63    5317  745.03  5415.4  746.58  5492.5  747.55
  5522.5  749.63  5612.2  749.85  5652.5  750.02  5682.5  751.73  5692.5  749.49
  5702.5  749.12  5712.5  751.29  5722.5  751.02  5732.5  749.64  5742.2  750.04
#Mann= 11 ,-1 , 0
  3912.8     .08       0    4028     .05       0  4310.4      .1       0
  4800.7     .05       0  4998.5     .04       0  5006.5     .05       0
  5120.2     .08       0  5218.6     .05       0    5317      .1       0
  5415.4     .08       0  5612.2     .05       0
Bank Sta=4726.69,5195.54
XS Rating Curve= 0 ,0
Exp/Cntr=0.3,0.1

Type RM Length L Ch R = 1 ,5187    ,307,307,307
BEGIN DESCRIPTION:
Mapping XS f3f8fe34
END DESCRIPTION:
XS GIS Cut Line= 3
      2016120.58     13638057.72      2015843.05      13637824.3
      2014561.56     13637422.31
#Sta/Elev= 30
  3906.6  746.93  3940.3  746.23  4018.4  745.78  4026.2  746.18  4096.8  745.28
  4260.3   744.5  4483.1  744.38 4610.11743.1469  4738.8  741.36  4770.3   741.3
  4780.1  742.13  4785.4  741.37  4801.7  741.69  4817.8  740.81  4943.5  739.26
  4944.1  738.46  4950.8  738.46  4951.5  739.26  4979.9  740.31  4990.4  739.39
  5000.8  739.39  5011.3  739.78  5017.6  741.01 5124.57743.0075  5282.2  746.04
  5517.2  748.64  5545.8   749.7  5557.4  749.29  5584.1  749.73  5612.3  749.37
#Mann= 5 ,-1 , 0
  3906.6      .1       0  4943.5     .07       0  4951.5      .1       0
  5517.2     .05       0  5584.1     .08       0
Bank Sta=4610.11,5124.57
XS Rating Curve= 0 ,0
Exp/Cntr=0.3,0.1

Type RM Length L Ch R = 1 ,4880    ,373,373,373
BEGIN DESCRIPTION:
Mapping XS 348832a7
END DESCRIPTION:
XS GIS Cut Line= 3
      2016092.83     13637898.04      2015753.36     13637513.43
      2014717.79     13637168.83
#Sta/Elev= 30
  4052.2  745.19  4116.6   744.5  4130.8  744.65  4137.5  744.97  4151.7  744.91
  4180.2  744.28  4237.1  743.85  4595.1   743.2  4704.2   742.3 4713.76742.0574
  4932.3   739.4  4942.9  739.42  4952.1  739.73    4964  740.56  4974.5  739.93
  4983.8  738.95    4989  738.09  4991.6  737.41  4992.2  736.61  4998.9  736.61
  4999.6  737.41  5015.4  738.96  5020.7   738.6  5037.7  739.58    5084  739.76
 5191.12742.1076  5259.1  743.59  5426.8  746.35  5606.8  747.88  5656.6  748.04
#Mann= 3 ,-1 , 0
  4052.2      .1       0  4991.6     .07       0  4999.6      .1       0
Bank Sta=4713.76,5191.12
XS Rating Curve= 0 ,0
Exp/Cntr=0.3,0.1

Type RM Length L Ch R = 1 ,4507    ,287,287,287
BEGIN DESCRIPTION:
Mapping XS b9b7b84c
END DESCRIPTION:
XS GIS Cut Line= 3
      2016068.52     13637595.95      2015749.27     13637164.82
      2014870.62     13636807.74
#Sta/Elev= 30
  4181.1  743.54  4242.1  744.33  4248.3  743.61  4513.4  743.05  4613.5  742.41
 4728.66 740.899  4865.5  738.69  4937.8  738.32  4967.2  738.68  4972.6  738.25
  4981.2  733.78  4992.7  732.76  4993.4  731.96  5000.1  731.96  5000.8  732.76
  5002.8  733.99  5013.6   735.7  5020.8  738.18  5026.2  738.56  5098.4  739.21
  5143.1  740.71 5176.77740.9137    5467  745.38  5502.7  746.49  5520.9  746.49
  5532.2  747.21  5550.8  747.41  5556.2  746.34  5574.9  746.83    5666  747.03
#Mann= 3 ,-1 , 0
  4181.1      .1       0  4992.7     .07       0  5000.8      .1       0
Bank Sta=4728.66,5176.77
XS Rating Curve= 0 ,0
Exp/Cntr=0.3,0.1

Type RM Length L Ch R = 1 ,4220    ,334,334,334
BEGIN DESCRIPTION:
Mapping XS b295d9a7
END DESCRIPTION:
XS GIS Cut Line= 3
      2016085.87     13637349.41      2015953.96     13636957.69
      2015065.03     13636557.73
#Sta/Elev= 30
    4234  743.57  4259.8  744.17  4284.9  743.97    4302   744.6  4311.1  744.62
  4316.4  744.05  4333.6  744.37  4379.4   743.7  4396.9  744.11  4481.3  743.06
  4618.5  742.29 4768.29739.9017  4889.2  738.56  4958.6  736.94  4975.2  736.94
  4983.2  736.44  4983.9  735.64  4990.6  735.64  4991.3  736.44  5010.4  737.03
    5019   736.8    5041  737.92  5056.7  737.44  5062.9   737.9  5102.5  738.84
 5140.12739.7097  5186.9  740.69  5247.4  741.28  5443.6  744.45  5622.1  745.96
#Mann= 5 ,-1 , 0
    4234      .1       0  4983.2     .07       0  4991.3      .1       0
  5102.5     .16       0  5186.9     .05       0
Bank Sta=4768.29,5140.12
XS Rating Curve= 0 ,0
Exp/Cntr=0.3,0.1

Type RM Length L Ch R = 1 ,3886    ,488,488,488
BEGIN DESCRIPTION:
Mapping XS 3fc506a3
END DESCRIPTION:
XS GIS Cut Line= 2
       2016339.2     13636795.45      2015401.76     13636357.97
#Sta/Elev= 30
  4451.3  742.73  4514.1  743.02  4522.2  743.45  4536.9  743.19  4599.4  743.65
  4651.2  743.57  4687.7  742.82  4719.8     743  4816.7  742.39  4831.1  741.73
  4862.5   741.8  4890.8  740.34  4908.2  740.45  4919.4  739.76 4922.85739.1601
  4930.5  737.83  4936.6  735.33    4938  731.24  4938.7  730.44  4945.5  730.44
  4946.2  731.24  5018.7  731.24    5028  732.04  5033.5  733.18  5040.8  736.39
 5183.02739.1595  5193.5  739.52  5196.4  739.66  5228.4  740.54  5485.8  743.69
#Mann= 5 ,-1 , 0
  4451.3      .1       0    4938     .07       0  4946.2      .1       0
  5193.5     .16       0  5196.4     .05       0
Bank Sta=4922.85,5183.02
XS Rating Curve= 0 ,0
Exp/Cntr=0.3,0.1

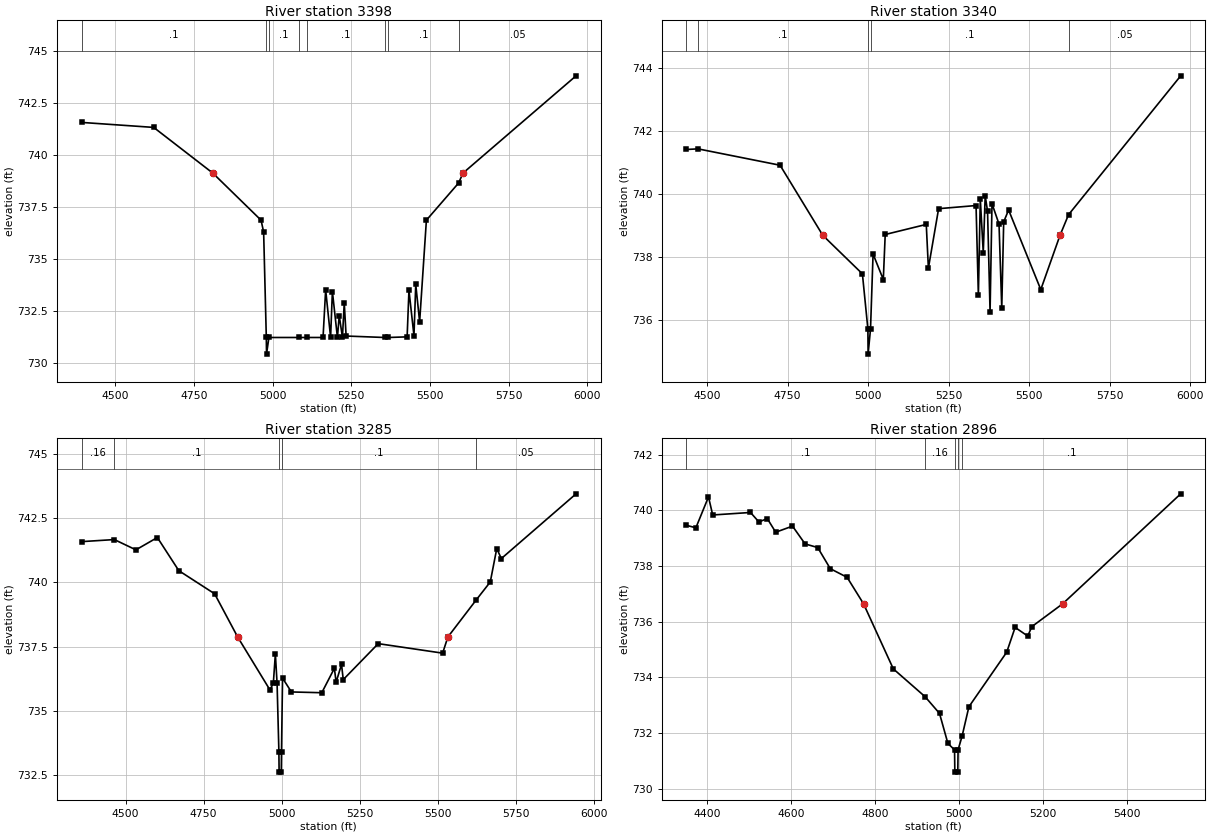
Type RM Length L Ch R = 1 ,3398    ,58,58,58
BEGIN DESCRIPTION:
Mapping XS 886fa5f4
END DESCRIPTION:
XS GIS Cut Line= 6
      2016658.11     13636621.76      2016186.77     13636262.39
      2016176.35     13636225.94      2016048.75     13636158.23
      2015902.92     13636418.64      2015486.25     13636147.81
#Sta/Elev= 30
  4393.6  741.58  4622.5  741.34 4810.22739.1436  4963.5  736.88  4971.7  736.31
  4980.2  731.24  4980.9  730.44  4988.4  731.24  5082.6  731.24  5110.2  731.24
  5160.4  731.24  5168.7  733.53  5184.4  731.25  5190.1  733.45  5206.1  731.24
  5211.8  732.29    5222  731.25  5227.8   732.9  5233.7  731.31  5356.2  731.24
  5367.5  731.24  5427.5  731.27  5433.3  733.51  5449.2  731.33  5454.9  733.79
  5467.2  731.99  5488.7  736.88  5591.2  738.67 5604.89739.1436  5964.1  743.82
#Mann= 8 ,-1 , 0
  4393.6      .1       0  4980.2     .07       0  4988.4      .1       0
  5082.6     .05       0  5110.2      .1       0  5356.2     .05       0
  5367.5      .1       0  5591.2     .05       0
Bank Sta=4810.22,5604.89
XS Rating Curve= 0 ,0
Exp/Cntr=0.3,0.1

Type RM Length L Ch R = 1 ,3340    ,55,55,55
BEGIN DESCRIPTION:
Mapping XS b7bf23c5
END DESCRIPTION:
XS GIS Cut Line= 6
      2016673.78     13636595.76      2016223.23     13636225.94
      2016100.83     13636147.81      2016046.15     13636129.58
       2015895.1     13636363.96       2015498.3     13636112.39
#Sta/Elev= 30
  4435.7  741.42    4472  741.44  4726.8  740.92 4859.49738.6921  4982.3  737.47
  4999.3  735.72    5000  734.92  5007.5  735.72  5015.4   738.1  5047.2  737.29
  5053.1  738.72  5180.5  739.04  5187.1  737.65  5218.8  739.54    5335  739.64
  5342.2  736.79  5348.2  739.85  5357.4  738.14  5363.4  739.95  5370.7  739.46
  5378.5  736.26  5384.5   739.7  5406.3  739.05  5414.8  736.39  5420.8  739.12
    5436   739.5  5535.9  736.97 5595.49738.6921  5622.1  739.35  5970.1  743.76
#Mann= 5 ,-1 , 0
  4435.7     .16       0    4472      .1       0  4999.3     .07       0
  5007.5      .1       0  5622.1     .05       0
Bank Sta=4859.49,5595.49
XS Rating Curve= 0 ,0
Exp/Cntr=0.3,0.1

Type RM Length L Ch R = 1 ,3285    ,389,389,389
BEGIN DESCRIPTION:
Mapping XS 8a7d4449
END DESCRIPTION:
XS GIS Cut Line= 4
      2016843.06     13636460.33      2016046.15     13636093.12
      2015866.46     13636317.08      2015530.51     13636064.47
#Sta/Elev= 30
  4358.9  741.59  4463.7  741.67  4532.9  741.27  4601.6  741.75  4670.4  740.46
  4785.2  739.56 4859.05737.8786  4962.5  735.82  4973.4  736.08  4979.9  737.22
  4985.4  736.07  4991.2  733.42  4991.9  732.62  4998.8  732.62  4999.6  733.42
  5002.9  736.28  5031.3  735.74  5128.7  735.71  5169.1  736.66  5174.6  736.12
    5192  736.81  5197.5  736.22  5309.7  737.62  5516.1  737.25 5532.89737.8785
    5623  739.31  5668.8  740.02  5689.6  741.32  5704.2  740.93  5943.8  743.45
#Mann= 5 ,-1 , 0
  4358.9     .16       0  4463.7      .1       0  4991.2     .07       0
  4999.6      .1       0    5623     .05       0
Bank Sta=4859.05,5532.89
XS Rating Curve= 0 ,0
Exp/Cntr=0.3,0.1

Type RM Length L Ch R = 1 ,2896    ,268,268,268
BEGIN DESCRIPTION:
Mapping XS ac930c4c
END DESCRIPTION:
XS GIS Cut Line= 2
      2017027.88     13635866.56      2015850.79     13635861.35
#Sta/Elev= 30
    4351  739.46  4373.9  739.37  4403.9  740.48  4413.9  739.83  4503.9  739.92
  4523.9  739.58  4543.9   739.7  4563.9  739.21  4603.9  739.43  4633.9  738.79
  4663.9  738.66  4693.9   737.9  4733.9  737.59  4773.1736.6372  4843.9   734.3
  4919.6   733.3  4953.9   732.7  4973.9  731.62  4989.7  731.39  4990.4  730.59
  4997.4  730.59  4998.1  731.39  5007.6  731.88  5023.9  732.94  5113.9   734.9
  5133.9  735.79  5163.9  735.48  5173.9  735.82 5247.01736.6373  5528.1  740.59
#Mann= 5 ,-1 , 0
    4351      .1       0  4919.6     .16       0  4989.7     .07       0
  4998.1     .16       0  5007.6      .1       0
Bank Sta=4773.1,5247.01
XS Rating Curve= 0 ,0
Exp/Cntr=0.3,0.1