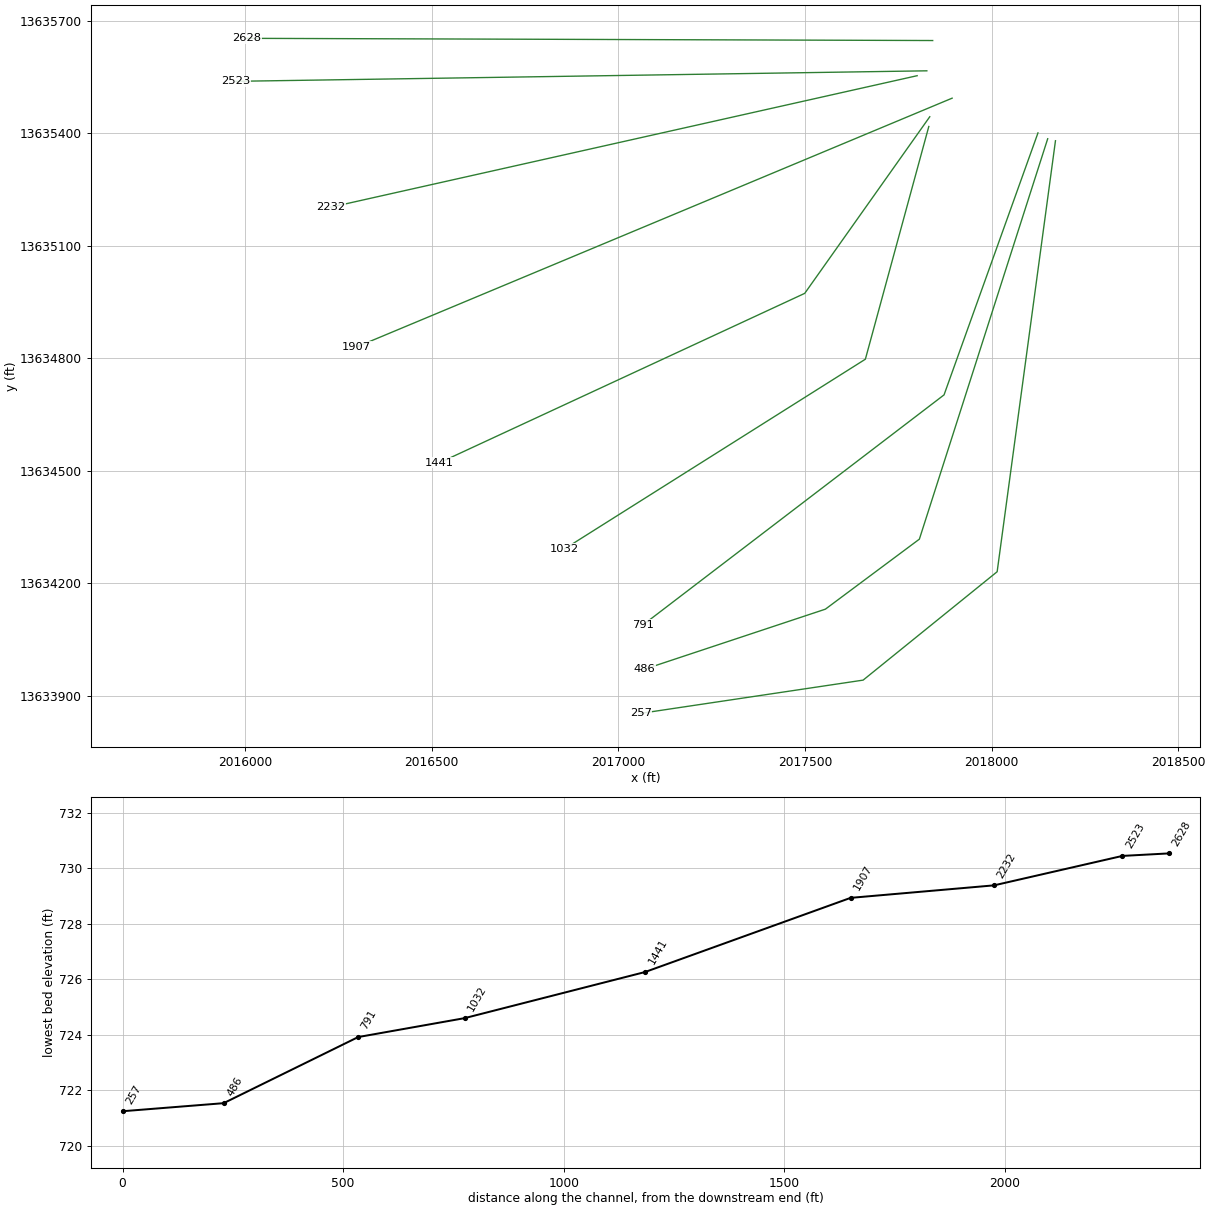
HEC-RAS study WP FORT EWELL CREEK.prj: WP FORT EWELL CREEK Base Level Engineering

--- WP FORT EWELL CREEK.g01 (geometry) --- (continued)

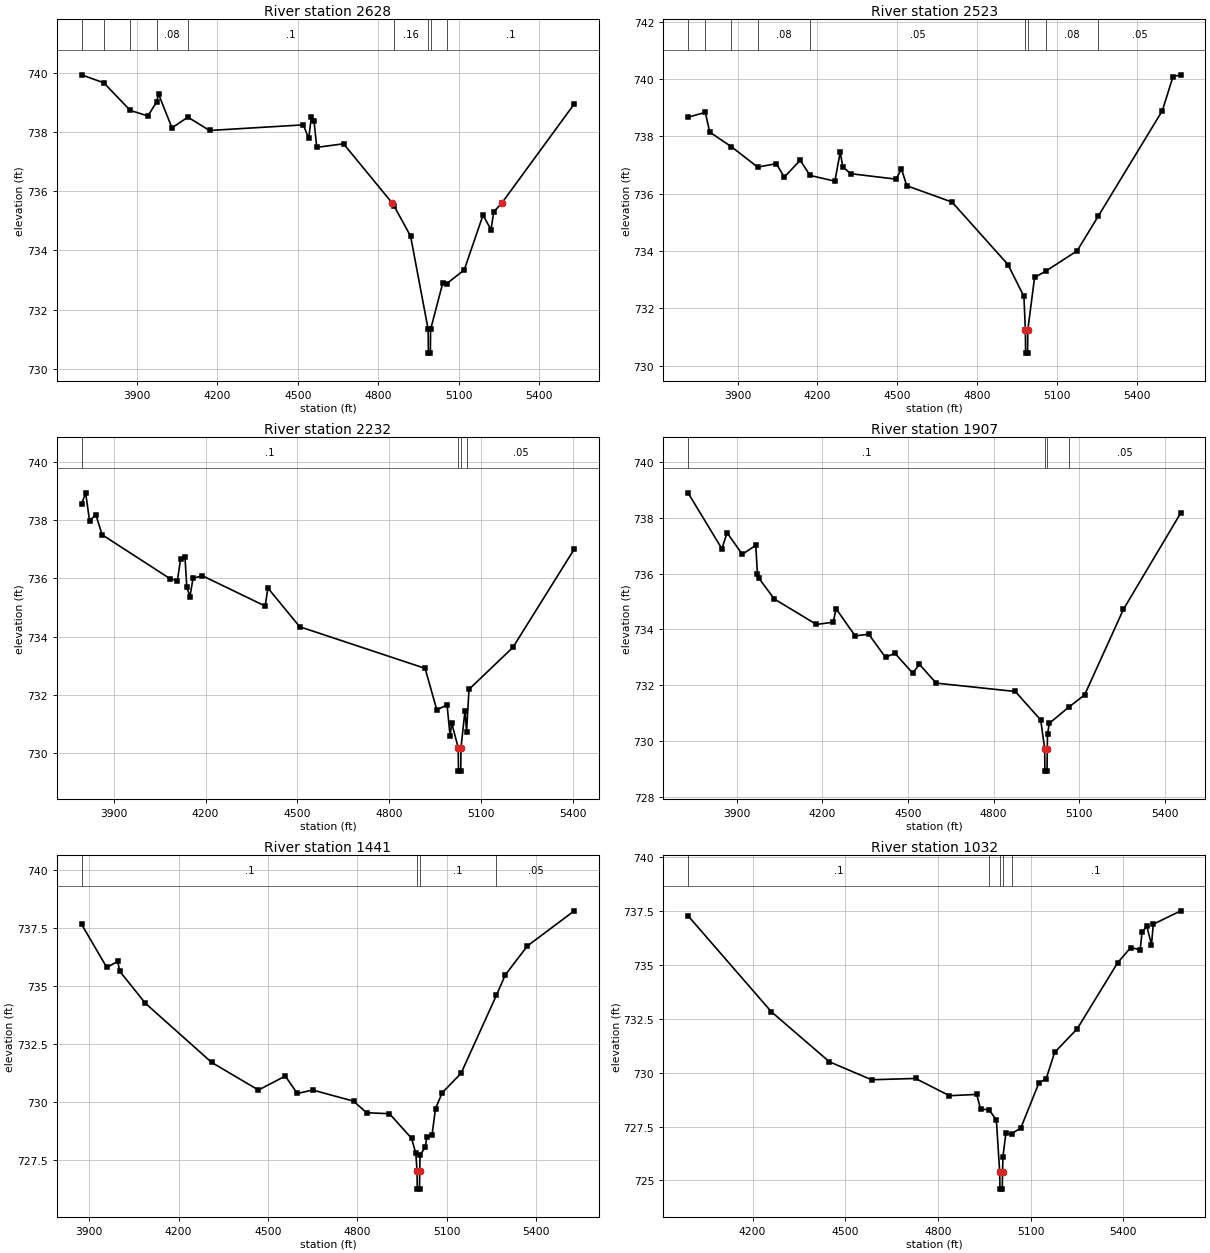
Type RM Length L Ch R = 1 ,2628    ,105,105,105
BEGIN DESCRIPTION:
Mapping XS 1b1d93ba
END DESCRIPTION:
XS GIS Cut Line= 2
      2017842.22     13635647.17      2016004.43     13635653.02
#Sta/Elev= 30
  3693.2  739.93  3776.2  739.66  3874.6  738.73  3940.4  738.54  3973.1  739.01
  3980.4  739.28  4030.4  738.14  4089.9   738.5  4170.4  738.05  4520.4  738.24
  4540.4  737.78  4550.4  738.52  4560.4  738.36  4570.4  737.48  4670.4   737.6
 4851.91735.5984  4858.8   735.5  4920.4  734.48  4985.9  731.33  4986.7  730.53
  4994.1  730.53    4995  731.33  5040.4   732.9  5055.6  732.88  5120.4  733.34
  5190.4  735.19  5220.4   734.7  5230.4   735.3 5259.74735.5881    5531  738.95
#Mann= 9 ,-1 , 0
  3693.2      .1       0  3776.2     .08       0  3874.6     .05       0
  3973.1     .08       0  4089.9      .1       0  4858.8     .16       0
  4985.9     .07       0    4995     .16       0  5055.6      .1       0
Bank Sta=4851.91,5259.74
XS Rating Curve= 0 ,0
Exp/Cntr=0.3,0.1

Type RM Length L Ch R = 1 ,2523    ,291,291,291
BEGIN DESCRIPTION:
Mapping XS 8970128e
END DESCRIPTION:
XS GIS Cut Line= 2
      2017826.62     13635566.44      2015975.84     13635538.44
#Sta/Elev= 30
    3714  738.67  3778.9  738.84  3795.6  738.15  3877.3  737.64  3975.6  736.93
  4045.7  737.05  4075.7  736.58  4135.3  737.17  4172.4  736.64  4265.7  736.44
  4285.7  737.45  4295.7  736.93  4325.7   736.7  4495.7  736.51  4515.7  736.87
  4535.7  736.28  4705.7  735.71  4915.8  733.53  4975.8  732.42  4981.2  731.24
  4982.1  730.44  4989.5  730.44  4990.3  731.24  5015.8  733.08  5057.7   733.3
  5175.8  734.01  5254.4  735.21  5495.8   738.9  5535.8  740.09    5565  740.15
#Mann= 9 ,-1 , 0
    3714      .1       0  3778.9     .08       0  3877.3     .05       0
  3975.6     .08       0  4172.4     .05       0  4981.2     .04       0
  4990.3     .05       0  5057.7     .08       0  5254.4     .05       0
Bank Sta=4981.2,4990.3
XS Rating Curve= 0 ,0
Exp/Cntr=0.3,0.1

Type RM Length L Ch R = 1 ,2232    ,325,325,325
BEGIN DESCRIPTION:
Mapping XS 25f3f589
END DESCRIPTION:
XS GIS Cut Line= 2
       2017800.6     13635553.42      2016229.17     13635202.66
#Sta/Elev= 30
  3794.9  738.55  3808.2  738.94  3821.1  737.98  3841.6  738.19  3862.1   737.5
  4084.2  735.99    4108  735.92  4118.3  736.65  4132.8  736.73  4138.8  735.71
    4149  735.37  4159.3  736.01    4190  736.09  4394.9  735.05  4403.7  735.67
  4507.6  734.34  4917.5  732.91  4955.8  731.48  4989.2  731.66  4999.2  730.57
  5004.3  731.04  5025.6  730.18  5026.5  729.38  5033.9  729.38  5034.7  730.18
  5047.8  731.46  5052.9  730.74  5060.9  732.19  5204.4  733.63    5405  737.01
#Mann= 4 ,-1 , 0
  3794.9      .1       0  5025.6     .07       0  5034.7      .1       0
  5052.9     .05       0
Bank Sta=5025.6,5034.7
XS Rating Curve= 0 ,0
Exp/Cntr=0.3,0.1

Type RM Length L Ch R = 1 ,1907    ,466,466,466
BEGIN DESCRIPTION:
Mapping XS e2904967
END DESCRIPTION:
XS GIS Cut Line= 2
       2017894.3     13635493.51      2016299.37     13634830.36
#Sta/Elev= 30
  3729.1  738.89  3847.7  736.89  3866.1  737.46  3919.2  736.69  3966.6  737.01
  3972.3     736  3977.8  735.83  4031.6  735.09  4179.4  734.18    4238  734.26
  4248.2  734.74  4314.9  733.77  4362.6  733.83  4421.5     733    4454  733.15
  4516.6  732.44  4540.4  732.75    4599  732.08  4876.3  731.78  4965.4  730.76
  4979.3  729.73  4980.1  728.93  4987.6  728.93  4988.5  729.73  4989.3  730.25
  4995.4  730.64  5063.8  731.22  5119.4  731.66  5255.4  734.72  5456.4  738.17
#Mann= 4 ,-1 , 0
  3729.1      .1       0  4979.3     .07       0  4988.5      .1       0
  5063.8     .05       0
Bank Sta=4979.3,4988.5
XS Rating Curve= 0 ,0
Exp/Cntr=0.3,0.1

Type RM Length L Ch R = 1 ,1441    ,409,409,409
BEGIN DESCRIPTION:
Mapping XS 1d4f8c5d
END DESCRIPTION:
XS GIS Cut Line= 3
      2017834.42     13635444.01      2017499.49     13634973.17
      2016521.81     13634521.93
#Sta/Elev= 30
  3874.1  737.67  3958.8  735.81  3995.6  736.07  4002.1  735.65  4088.2  734.27
  4310.8  731.72  4467.9  730.53  4558.2  731.13  4598.6  730.38    4650  730.53
  4787.3  730.05  4831.3  729.55  4907.9  729.51  4982.2  728.45  4996.5   727.8
  5000.6  727.06  5001.4  726.26  5008.9  726.26  5009.8  727.06  5010.7  727.73
  5028.1  728.06  5033.6  728.52  5051.1   728.6  5062.6  729.73    5085  730.41
  5148.4  731.25  5267.1  734.61    5297  735.49  5371.4  736.74  5528.7  738.25
#Mann= 4 ,-1 , 0
  3874.1      .1       0  5000.6     .07       0  5009.8      .1       0
  5267.1     .05       0
Bank Sta=5000.6,5009.8
XS Rating Curve= 0 ,0
Exp/Cntr=0.3,0.1

Type RM Length L Ch R = 1 ,1032    ,241,241,241
BEGIN DESCRIPTION:
Mapping XS 71ff6d39
END DESCRIPTION:
XS GIS Cut Line= 3
      2017831.84     13635418.02      2017661.95     13634797.66
      2016856.01     13634291.89
#Sta/Elev= 30
    3991  737.27  4260.8  732.82  4448.7   730.5  4585.1  729.67  4727.4  729.73
    4837  728.93  4925.3  728.99  4937.6  728.31  4965.7  728.28    4989  727.79
  4999.6   725.4  5000.5   724.6    5008   724.6  5008.9   725.4  5010.2   726.1
  5019.6  727.18    5038  727.17  5067.9  727.43  5126.5  729.52  5150.1  729.72
  5177.5  730.94  5250.5  732.03  5381.3  735.09  5423.7   735.8  5454.3  735.69
  5460.2   736.5  5475.6  736.79  5490.9  735.93  5496.8  736.88  5585.7   737.5
#Mann= 5 ,-1 , 0
    3991      .1       0  4965.7     .07       0  4999.6     .07       0
  5008.9     .07       0    5038      .1       0
Bank Sta=4999.6,5008.9
XS Rating Curve= 0 ,0
Exp/Cntr=0.3,0.1

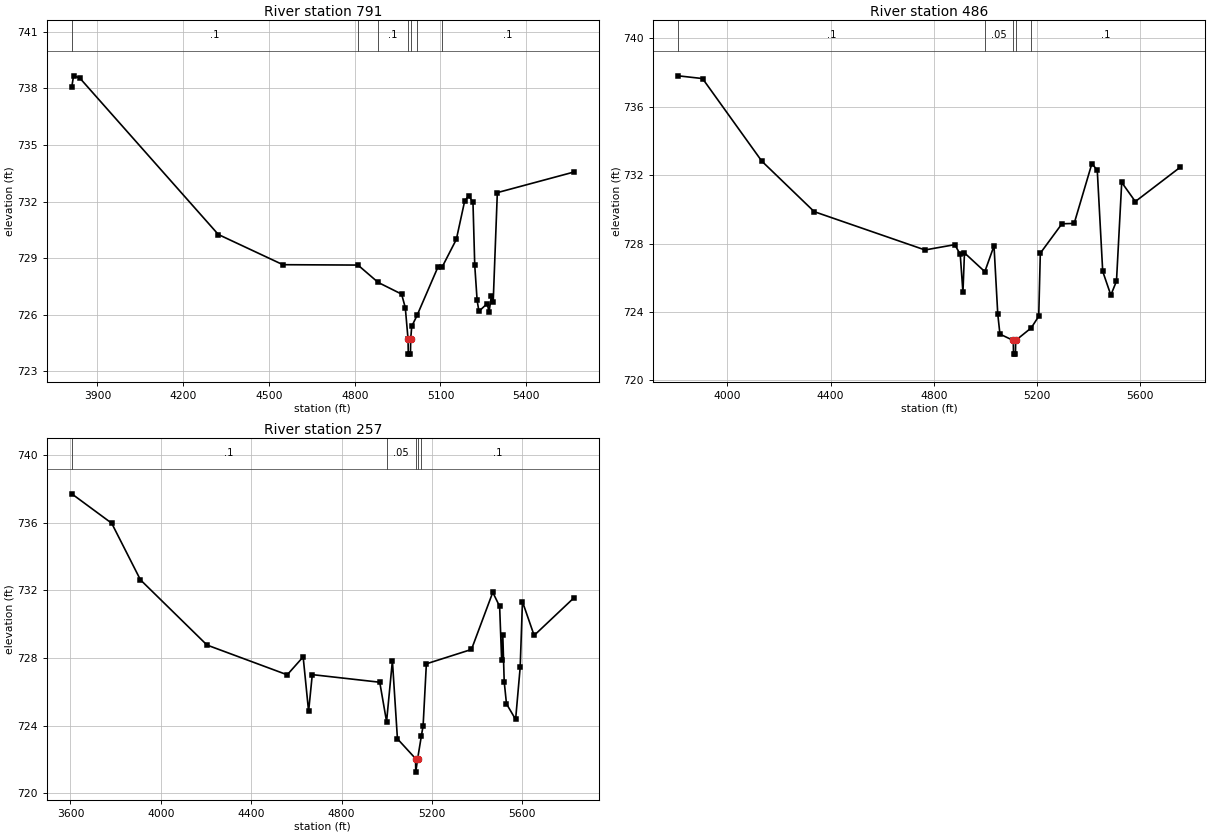
Type RM Length L Ch R = 1 ,791     ,305,305,305
BEGIN DESCRIPTION:
Mapping XS a66ab343
END DESCRIPTION:
XS GIS Cut Line= 3
      2018124.23     13635400.95      2017872.63     13634702.53
      2017065.77     13634088.98
#Sta/Elev= 30
  3810.4  738.08  3816.7  738.67    3838  738.56    4323  730.26  4548.8  728.66
  4811.4  728.64    4882  727.72    4964   727.1  4976.9  726.38  4986.5  724.72
  4987.4  723.92  4994.9  723.92  4995.8  724.72  4999.4  725.39    5018  725.97
  5090.9  728.53  5106.6  728.56  5155.4     730  5184.5  732.03    5199  732.32
  5213.6  731.96  5219.8  728.63  5228.1  726.77  5234.4  726.19  5263.5   726.6
  5269.7  726.15    5278  726.99  5284.3  726.67  5298.8  732.48  5566.4  733.57
#Mann= 7 ,-1 , 0
  3810.4      .1       0  4811.4     .07       0    4882      .1       0
  4986.5     .07       0  4995.8      .1       0    5018     .12       0
  5106.6      .1       0
Bank Sta=4986.5,4995.8
XS Rating Curve= 0 ,0
Exp/Cntr=0.3,0.1

Type RM Length L Ch R = 1 ,486     ,229,229,229
BEGIN DESCRIPTION:
Mapping XS 25f74407
END DESCRIPTION:
XS GIS Cut Line= 4
      2018150.28     13635385.36      2017806.56     13634317.95
      2017554.83     13634131.32      2017069.39     13633970.95
#Sta/Elev= 30
  3809.2  737.81  3903.4  737.65  4133.2  732.82  4336.1  729.87  4765.6  727.63
  4881.2  727.94  4902.2  727.37  4912.7  725.15  4918.6  727.46  4997.5  726.36
  5033.1  727.87  5047.7  723.87  5056.1  722.71  5107.8  722.34  5108.7  721.54
  5116.2  721.54  5117.1  722.34  5177.1  723.07  5206.4  723.75  5212.6  727.44
  5296.4  729.16  5343.8  729.18  5412.5  732.68  5433.3  732.29  5454.4  726.38
    5486  724.99  5507.8  725.81  5528.1  731.58  5580.8  730.46  5755.2  732.47
#Mann= 5 ,-1 , 0
  3809.2      .1       0  4997.5     .05       0  5107.8    .035       0
  5117.1     .05       0  5177.1      .1       0
Bank Sta=5107.8,5117.1
XS Rating Curve= 0 ,0
Exp/Cntr=0.3,0.1

Type RM Length L Ch R = 1 ,257     ,0,0,0
BEGIN DESCRIPTION:
WP FORT EWELL CREEK 1.0
END DESCRIPTION:
XS GIS Cut Line= 4
       2018171.1     13635380.09       2018014.9     13634231.14
       2017655.9     13633942.19      2017060.01     13633853.54
#Sta/Elev= 30
  3605.8  737.72  3782.5  735.98  3909.8  732.63  4204.6  728.77  4559.6  727.01
  4630.2  728.07  4654.3  724.84  4670.6  727.02  4969.3  726.57  4999.5  724.24
  5025.3  727.84  5047.6  723.22  5127.8  722.05  5128.7  721.25  5137.1  722.05
  5153.3  723.37  5161.3     724  5175.7  727.66  5375.3  728.51  5469.7  731.89
    5500  731.06    5509  727.87    5514  729.38  5520.3   726.6  5530.4  725.29
  5570.8  724.37    5591  727.45  5601.1  731.34  5652.8  729.34  5828.6  731.56
#Mann= 5 ,-1 , 0
  3605.8      .1       0  4999.5     .05       0  5127.8    .035       0
  5137.1     .05       0  5153.3      .1       0
Bank Sta=5127.8,5137.1
XS Rating Curve= 0 ,0
Exp/Cntr=0.3,0.1
LCMann Table=0

Chan Stop Cuts=-1
Use User Specified Reach Order=0
Composite Channel Slope=5