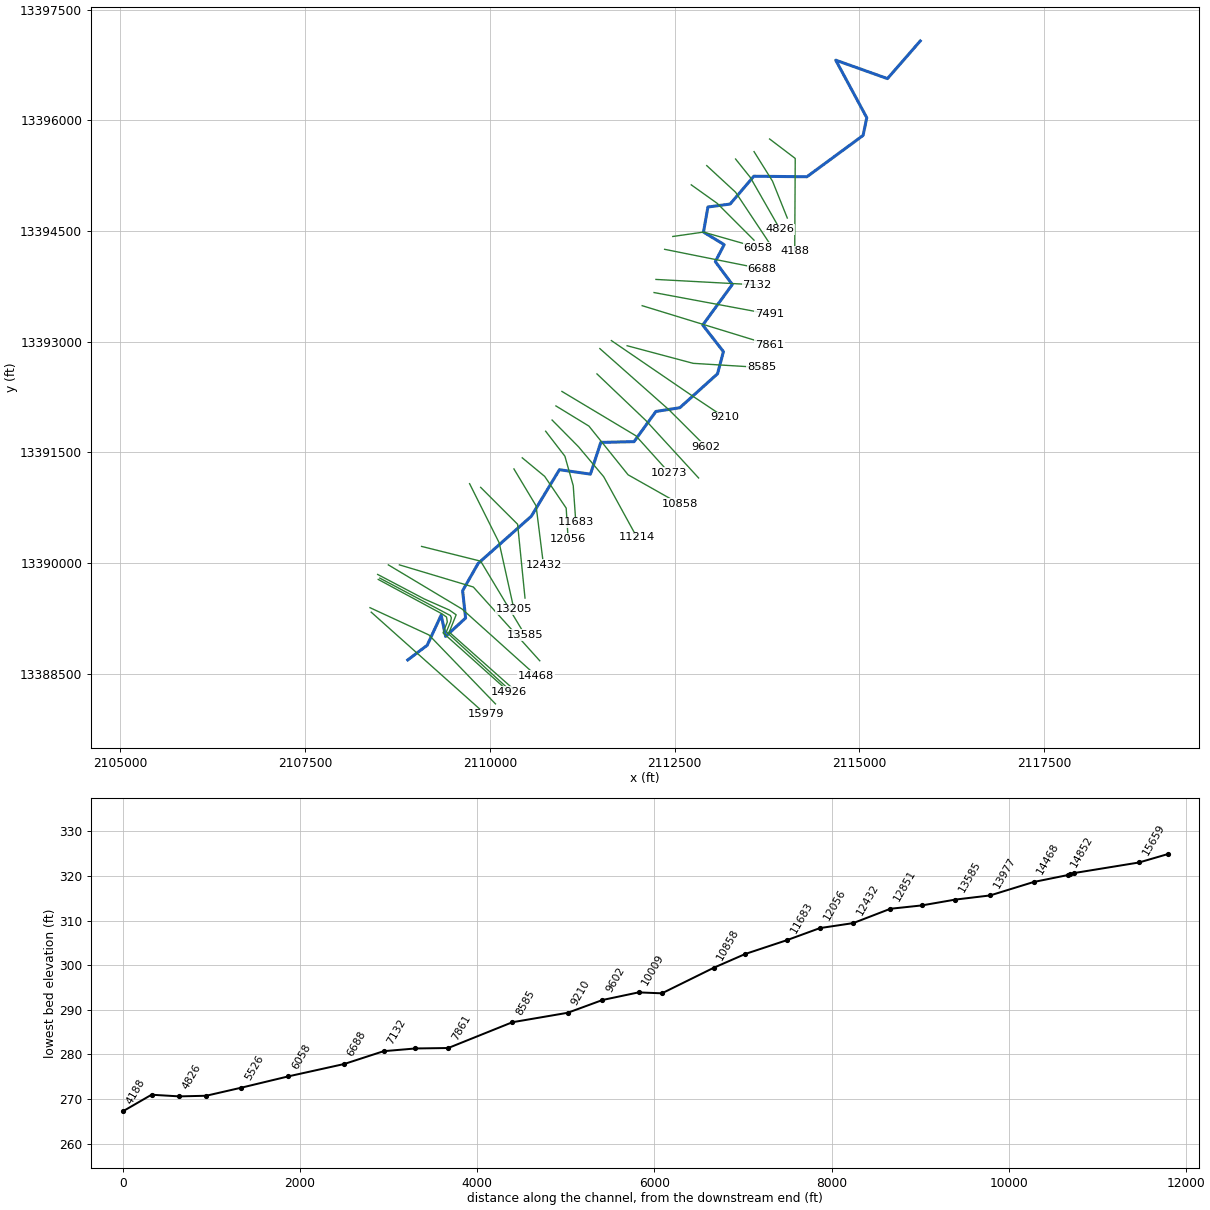
--- Bruce Branch.prj (project) ---

Proj Title=Bruce Branch Base Level Engineering
Current Plan=p01
Default Exp/Contr=0.3,0.1
English Units
Geom File=g01
Flow File=f01
Plan File=p01
BEGIN DESCRIPTION:
Bruce Branch
END DESCRIPTION:

--- Bruce Branch.p01 (plan) ---

Plan Title=Multiple Run
Short Identifier=Multiple
Geom File=g01
Flow File=f01
Subcritical Flow
K Sum by GR= 0
Std Step Tol= 0.01
Critical Tol= 0.01
Num of Std Step Trials= 20
Max Error Tol= 0.3
Flow Tol Ratio= 0.001
Split Flow NTrial= 30
Split Flow Tol= 0.02
Split Flow Ratio= 0.02
Log Output Level= 0
Friction Slope Method= 1
Unsteady Friction Slope Method= 2
Unsteady Bridges Friction Slope Method= 1
Parabolic Critical Depth
Global Vel Dist=  1 , 1 , 1
Global Log Level= 0
CheckData=True
Encroach Param= -1, 0, 0, 0
BEGIN DESCRIPTION:
Multiple Run
END DESCRIPTION:

--- Bruce Branch.f01 (steady flow) ---

Flow Title=Multiple
Number of Profiles=7
Profile Names=10-year,25-year,50-year,1pct_min,100-year,1pct_plu,500-year
River Rch & RM= Bruce Branch,Reach-1,15979
     209     291     360     222     444     886     684
River Rch & RM= Bruce Branch,Reach-1,15659
     296     417     518     322     642    1280     999
River Rch & RM= Bruce Branch,Reach-1,5526
     329     465     580     361     720    1437    1126
Boundary for River Rch & Prof#=Bruce Branch,Reach-1,1
Up Type=0
Dn Type=3
Dn Slope=0.005
Boundary for River Rch & Prof#=Bruce Branch,Reach-1,2
Up Type=0
Dn Type=3
Dn Slope=0.005
Boundary for River Rch & Prof#=Bruce Branch,Reach-1,3
Up Type=0
Dn Type=3
Dn Slope=0.005
Boundary for River Rch & Prof#=Bruce Branch,Reach-1,4
Up Type=0
Dn Type=3
Dn Slope=0.005
Boundary for River Rch & Prof#=Bruce Branch,Reach-1,5
Up Type=0
Dn Type=3
Dn Slope=0.005
Boundary for River Rch & Prof#=Bruce Branch,Reach-1,6
Up Type=0
Dn Type=3
Dn Slope=0.005
Boundary for River Rch & Prof#=Bruce Branch,Reach-1,7
Up Type=0
Dn Type=3
Dn Slope=0.005

--- Bruce Branch.g01 (geometry) ---

Geom Title=Existing Conditions

River Reach=Bruce Branch,Reach-1
Reach XY= 30
      2108888.26     13388686.90      2109150.80     13388884.54
      2109340.80     13389294.54      2109400.80     13389004.54
      2109670.80     13389254.54      2109630.80     13389624.54
      2109840.80     13389994.54      2110560.80     13390634.54
      2110940.80     13391264.54      2111360.80     13391204.54
      2111500.80     13391634.54      2111950.80     13391644.54
      2112246.37     13392053.78      2112570.80     13392104.54
      2113080.80     13392564.54      2113160.80     13392864.54
      2112880.80     13393224.54      2113280.80     13393774.54
      2113050.80     13394084.54      2113170.80     13394314.54
      2112890.80     13394484.54      2112950.80     13394824.54
      2113250.80     13394864.54      2113572.18     13395241.49
      2114290.80     13395234.54      2115050.80     13395794.54
      2115100.80     13396034.54      2114680.80     13396814.54
      2115380.80     13396564.54      2115825.00     13397075.00

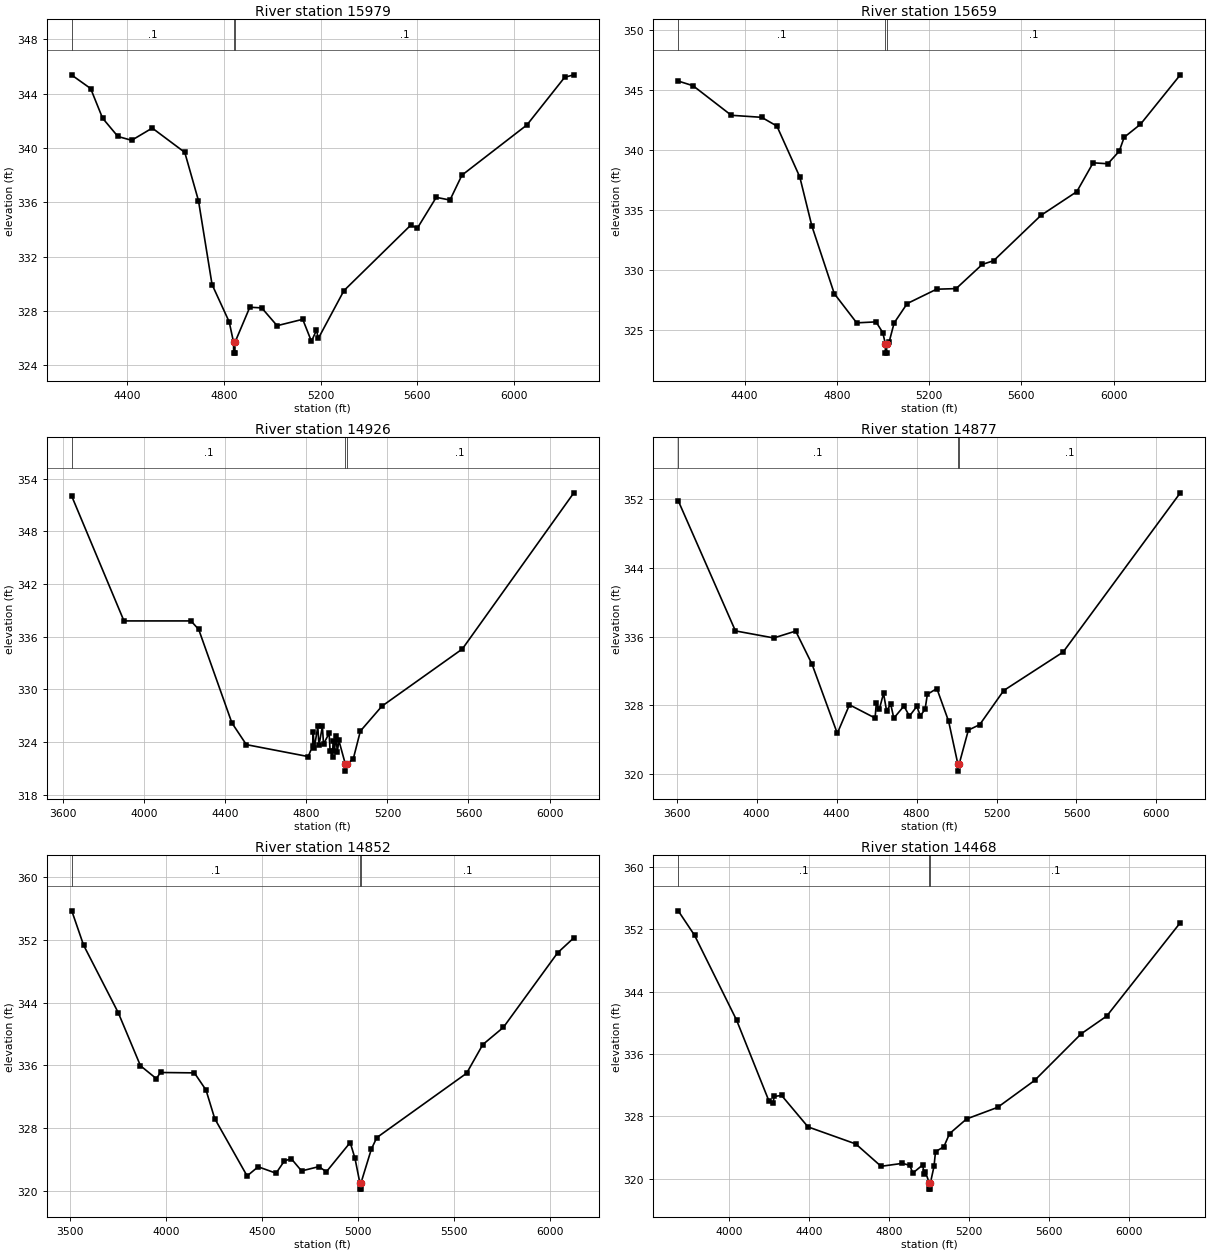
Type RM Length L Ch R = 1,15979,320,320,320
BEGIN DESCRIPTION:
Mapping XS 5e019d95
END DESCRIPTION:
XS GIS Cut Line= 2
      2108393.46     13389333.61      2109942.98     13387949.03
#Sta/Elev= 30
  4169.8  345.37  4247.9  344.38  4297.3  342.20  4360.8  340.85  4417.7  340.57
  4502.9  341.47  4637.5  339.68  4694.3  336.12  4750.4  329.95  4821.4  327.20
  4839.4  325.70  4839.9  324.90  4844.9  324.90  4845.4  325.70  4906.7  328.28
  4956.0  328.23  5019.6  326.92  5125.7  327.39  5161.7  325.77  5182.6  326.59
  5190.1  325.98  5296.2  329.50  5572.1  334.31  5600.5  334.11  5678.3  336.37
  5735.1  336.17  5784.5  338.00  6053.6  341.70  6209.9  345.21  6247.8  345.39
#Mann=3,-1,0
  4169.8     0.1       0  4839.4    0.07       0  4845.4     0.1       0
Bank Sta=4839.4,4845.4
Exp/Cntr=0.3,0.1

Type RM Length L Ch R = 1,15659,733,733,733
BEGIN DESCRIPTION:
Bruce Branch 32.0
END DESCRIPTION:
XS GIS Cut Line= 3
      2108376.79     13389394.64      2109175.00     13389025.00
      2110075.25     13388090.82
#Sta/Elev= 30
  4112.0  345.77  4176.1  345.38  4342.1  342.91  4473.7  342.74  4539.8  342.01
  4639.0  337.76  4691.4  333.66  4788.6  328.01  4885.8  325.57  4969.6  325.65
  4998.7  324.76  5009.9  323.84  5010.4  323.04  5015.4  323.04  5015.9  323.84
  5027.0  324.01  5048.1  325.56  5104.7  327.18  5232.1  328.38  5316.9  328.43
  5430.1  330.45  5479.5  330.76  5684.8  334.55  5840.2  336.53  5911.0  338.94
  5974.8  338.86  6024.2  339.91  6045.5  341.07  6116.3  342.16  6289.0  346.29
#Mann=3,-1,0
  4112.0     0.1       0  5009.9    0.07       0  5015.9     0.1       0
Bank Sta=5009.9,5015.9
Exp/Cntr=0.3,0.1

Type RM Length L Ch R = 1,14926,49,49,49
BEGIN DESCRIPTION:
Mapping XS 5c3adccd
END DESCRIPTION:
XS GIS Cut Line= 6
      2108488.50     13389777.51      2109355.71     13389308.75
      2109413.00     13389267.09      2109423.42     13389201.98
      2109366.12     13389053.55      2110254.17     13388256.65
#Sta/Elev= 30
  3642.5  352.00  3900.0  337.79  4230.7  337.79  4268.8  336.82  4432.5  326.17
  4503.8  323.69  4809.1  322.33  4830.7  323.52  4833.7  325.11  4839.2  323.30
  4856.4  325.76  4862.0  323.61  4879.1  325.76  4884.7  323.74  4912.3  325.00
  4917.1  322.97  4929.2  322.33  4931.9  324.11  4938.6  322.97  4946.1  324.71
  4952.8  322.85  4960.3  324.17  4992.4  321.47  4992.9  320.67  4998.4  321.47
  5031.3  322.05  5066.4  325.23  5172.6  328.07  5569.5  334.59  6119.8  352.39
#Mann=3,-1,0
  3642.5     0.1       0  4992.4    0.07       0  4998.4     0.1       0
Bank Sta=4992.4,4998.4
Exp/Cntr=0.3,0.1

Type RM Length L Ch R = 1,14877,25,25,25
BEGIN DESCRIPTION:
Mapping XS 78ba2700
END DESCRIPTION:
XS GIS Cut Line= 6
      2108509.33     13389795.74      2109465.08     13389287.92
      2109478.10     13389256.67      2109467.69     13389204.59
      2109410.39     13389066.57      2110287.60     13388259.64
#Sta/Elev= 30
  3607.7  351.80  3893.8  336.67  4085.6  335.85  4195.3  336.65  4277.4  332.78
  4403.4  324.76  4464.3  328.08  4592.5  326.54  4598.5  328.25  4613.6  327.56
  4634.7  329.41  4649.9  327.40  4671.0  328.13  4686.1  326.52  4736.8  327.94
  4764.3  326.76  4801.0  327.89  4819.0  326.82  4842.4  327.54  4854.0  329.30
  4901.5  329.97  4960.4  326.16  5006.8  321.17  5007.3  320.37  5012.8  321.17
  5059.1  325.14  5115.8  325.77  5236.1  329.74  5533.2  334.21  6119.4  352.72
#Mann=3,-1,0
  3607.7     0.1       0  5006.8    0.07       0  5012.8     0.1       0
Bank Sta=5006.8,5012.8
Exp/Cntr=0.3,0.1

Type RM Length L Ch R = 1,14852,384,384,384
BEGIN DESCRIPTION:
Mapping XS 395c6aef
END DESCRIPTION:
XS GIS Cut Line= 6
      2108480.72     13389845.20      2109113.52     13389511.88
      2109449.46     13389363.44      2109543.21     13389298.34
      2109449.46     13389063.96      2110319.25     13388290.52
#Sta/Elev= 30
  3507.6  355.69  3569.0  351.32  3749.5  342.71  3865.3  335.94  3947.7  334.30
  3969.8  335.08  4146.0  335.03  4206.5  332.85  4252.0  329.20  4420.6  321.89
  4478.1  323.06  4571.3  322.24  4614.4  323.79  4650.2  324.10  4704.2  322.53
  4794.7  323.08  4833.3  322.42  4957.4  326.15  4982.3  324.14  5007.7  321.01
  5008.2  320.21  5013.2  320.21  5013.7  321.01  5067.6  325.31  5096.0  326.78
  5563.5  334.98  5647.9  338.64  5755.0  340.83  6037.6  350.34  6122.0  352.25
#Mann=3,-1,0
  3507.6     0.1       0  5007.7    0.07       0  5013.7     0.1       0
Bank Sta=5007.7,5013.7
Exp/Cntr=0.3,0.1

Type RM Length L Ch R = 1,14468,491,491,491
BEGIN DESCRIPTION:
Bruce Branch 31.0
END DESCRIPTION:
XS GIS Cut Line= 3
      2108625.01     13389974.99      2109625.00     13389375.00
      2110624.97     13388475.03
#Sta/Elev= 30
  3745.3  354.39  3826.9  351.25  4036.8  340.38  4198.2  330.03  4219.5  329.71
  4225.4  330.56  4262.3  330.69  4394.5  326.65  4633.5  324.46  4759.9  321.59
  4866.8  321.97  4903.7  321.71  4918.6  320.72  4967.9  321.76  4975.4  320.64
  4982.1  320.85  5000.7  319.46  5001.2  318.66  5006.3  318.66  5006.8  319.46
  5024.7  321.57  5032.2  323.47  5074.0  324.10  5102.4  325.78  5187.7  327.67
  5343.1  329.16  5527.7  332.61  5760.9  338.60  5888.7  340.88  6256.8  352.87
#Mann=3,-1,0
  3745.3     0.1       0  5000.7    0.07       0  5006.8     0.1       0
Bank Sta=5000.7,5006.8
Exp/Cntr=0.3,0.1

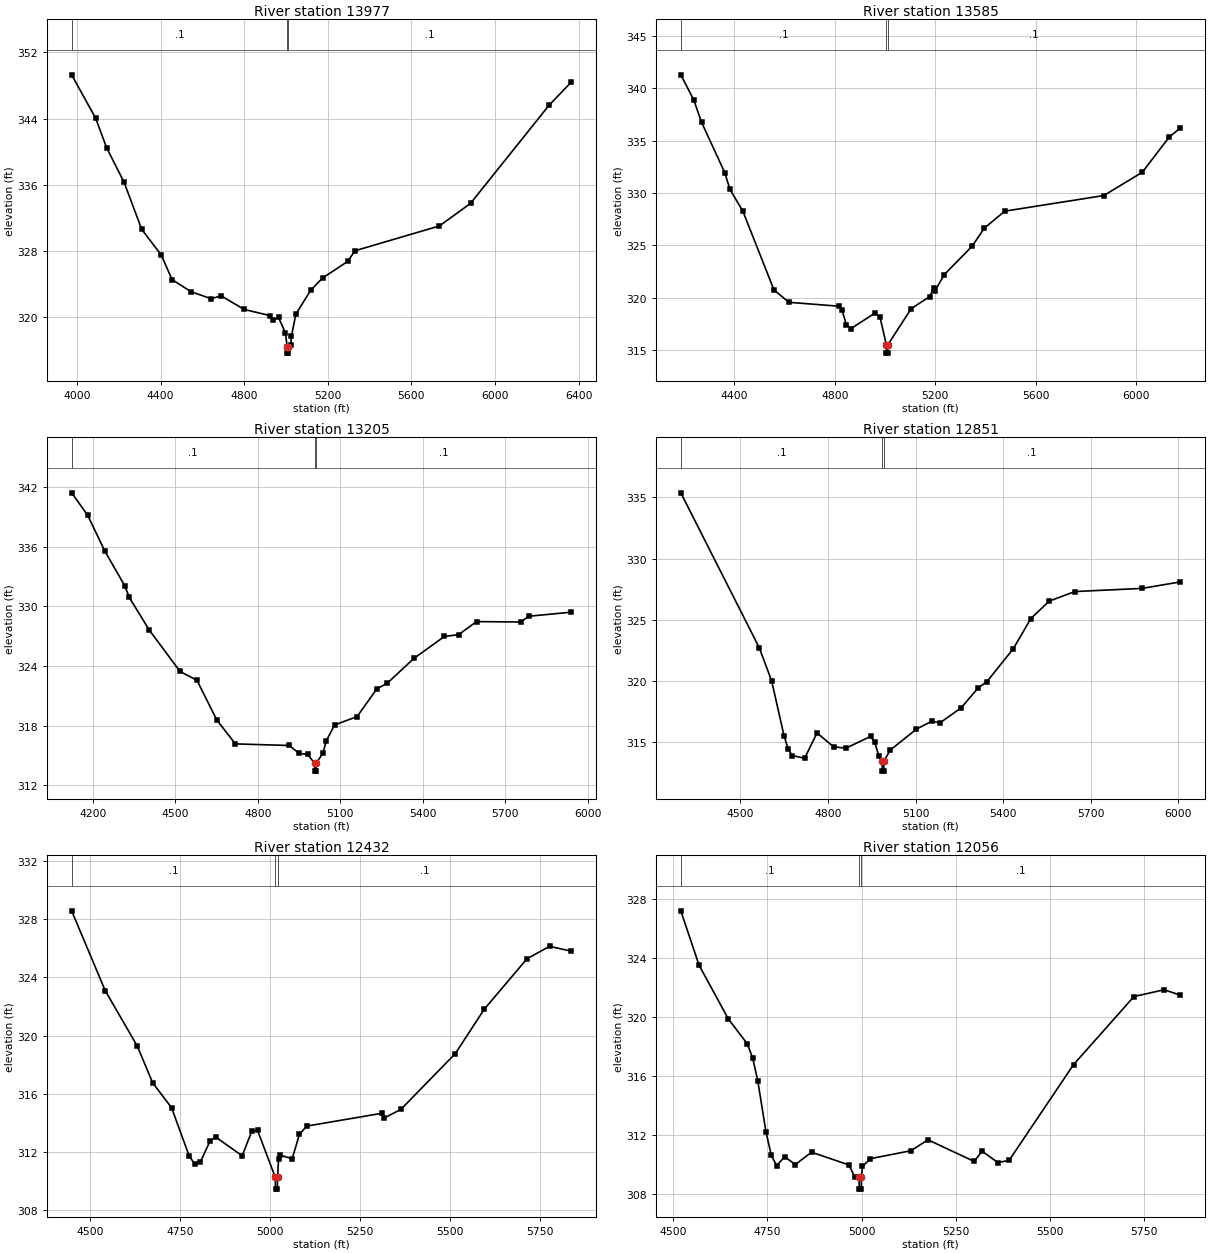
Type RM Length L Ch R = 1,13977,392,392,392
BEGIN DESCRIPTION:
Bruce Branch 30.0
END DESCRIPTION:
XS GIS Cut Line= 3
      2108774.97     13389975.01      2109775.00     13389675.00
      2110674.98     13388675.02
#Sta/Elev= 30
  3975.0  349.30  4089.9  344.05  4142.1  340.49  4225.6  336.32  4310.0  330.62
  4403.1  327.53  4455.3  324.54  4546.6  323.07  4643.2  322.22  4689.3  322.59
  4799.8  320.93  4925.1  320.18  4936.4  319.60  4964.3  319.96  4997.3  318.10
  5005.6  316.45  5006.1  315.65  5011.2  315.65  5011.7  316.45  5022.4  316.61
  5026.2  317.69  5047.1  320.35  5118.1  323.25  5174.9  324.73  5295.2  326.74
  5330.4  328.03  5734.0  331.03  5882.7  333.76  6257.9  345.61  6364.4  348.42
#Mann=3,-1,0
  3975.0     0.1       0  5005.6    0.07       0  5011.7     0.1       0
Bank Sta=5005.6,5011.7
Exp/Cntr=0.3,0.1

Type RM Length L Ch R = 1,13585,380,380,380
BEGIN DESCRIPTION:
Bruce Branch 29.0
END DESCRIPTION:
XS GIS Cut Line= 3
      2109074.99     13390225.00      2109875.00     13390025.00
      2110474.99     13389025.02
#Sta/Elev= 30
  4186.7  341.28  4238.2  338.89  4269.2  336.76  4361.9  331.94  4382.6  330.34
  4434.1  328.26  4557.8  320.76  4617.1  319.57  4815.5  319.20  4828.4  318.86
  4846.4  317.45  4864.4  317.06  4959.8  318.53  4980.4  318.15  5005.7  315.52
  5006.2  314.72  5011.3  314.72  5011.8  315.52  5104.6  318.96  5178.5  320.12
  5194.0  320.94  5199.9  320.68  5236.8  322.22  5347.6  324.93  5396.2  326.65
  5477.8  328.27  5872.4  329.76  6025.9  331.99  6132.8  335.34  6177.5  336.21
#Mann=3,-1,0
  4186.7     0.1       0  5005.7    0.07       0  5011.8     0.1       0
Bank Sta=5005.7,5011.8
Exp/Cntr=0.3,0.1

Type RM Length L Ch R = 1,13205,354,354,354
BEGIN DESCRIPTION:
Bruce Branch 28.0
END DESCRIPTION:
XS GIS Cut Line= 3
      2109725.01     13391074.97      2110125.00     13390275.00
      2110324.99     13389375.05
#Sta/Elev= 30
  4123.3  341.42  4182.0  339.14  4243.5  335.58  4316.1  332.08  4332.9  330.89
  4405.6  327.60  4517.4  323.44  4578.9  322.55  4651.5  318.53  4718.6  316.15
  4914.3  315.99  4950.6  315.19  4981.4  315.09  5006.3  314.21  5006.8  313.41
  5011.9  313.41  5012.4  314.21  5036.9  315.22  5048.4  316.42  5079.2  318.06
  5161.1  318.90  5232.8  321.69  5270.0  322.24  5367.3  324.75  5478.7  326.97
  5529.9  327.14  5595.2  328.46  5755.3  328.42  5786.0  329.00  5939.6  329.41
#Mann=3,-1,0
  4123.3     0.1       0  5006.3    0.07       0  5012.4     0.1       0
Bank Sta=5006.3,5012.4
Exp/Cntr=0.3,0.1

Type RM Length L Ch R = 1,12851,419,419,419
BEGIN DESCRIPTION:
Bruce Branch 27.0
END DESCRIPTION:
XS GIS Cut Line= 3
      2109874.97     13391025.03      2110375.00     13390525.00
      2110475.00     13389525.03
#Sta/Elev= 30
  4295.5  335.38  4564.2  322.74  4606.7  320.03  4649.1  315.56  4663.2  314.46
  4677.4  313.93  4719.8  313.71  4762.2  315.78  4818.8  314.65  4861.2  314.53
  4946.1  315.50  4960.2  315.00  4974.4  313.87  4985.5  313.46  4986.0  312.66
  4991.1  312.66  4991.6  313.46  5012.7  314.37  5103.1  316.09  5155.9  316.74
  5183.5  316.60  5256.4  317.83  5314.2  319.45  5344.3  319.96  5434.8  322.65
  5495.1  325.12  5557.9  326.54  5645.8  327.32  5877.0  327.58  6007.6  328.11
#Mann=3,-1,0
  4295.5     0.1       0  4985.5    0.07       0  4991.6     0.1       0
Bank Sta=4985.5,4991.6
Exp/Cntr=0.3,0.1

Type RM Length L Ch R = 1,12432,376,376,376
BEGIN DESCRIPTION:
Bruce Branch 26.0
END DESCRIPTION:
XS GIS Cut Line= 3
      2110325.01     13391274.99      2110625.00     13390775.00
      2110725.00     13389975.01
#Sta/Elev= 30
  4448.8  328.57  4542.1  323.09  4631.5  319.27  4674.2  316.75  4726.7  315.04
  4775.3  311.75  4790.9  311.17  4806.4  311.30  4833.6  312.75  4849.2  313.03
  4923.0  311.74  4950.2  313.46  4965.8  313.48  5015.2  310.25  5015.7  309.45
  5020.9  309.45  5021.4  310.25  5024.1  311.49  5029.0  311.78  5062.1  311.54
  5082.3  313.22  5102.4  313.78  5311.5  314.66  5316.6  314.32  5364.4  314.93
  5515.6  318.76  5596.2  321.81  5714.7  325.27  5777.6  326.13  5838.1  325.80
#Mann=3,-1,0
  4448.8     0.1       0  5015.2    0.07       0  5021.4     0.1       0
Bank Sta=5015.2,5021.4
Exp/Cntr=0.3,0.1

Type RM Length L Ch R = 1,12056,373,373,373
BEGIN DESCRIPTION:
Mapping XS e8f49655
END DESCRIPTION:
XS GIS Cut Line= 4
      2110437.70     13391425.64      2110741.56     13391173.88
      2111032.36     13390744.19      2111058.40     13390331.86
#Sta/Elev= 30
  4520.0  327.23  4568.4  323.54  4646.4  319.88  4696.5  318.20  4710.9  317.23
  4724.3  315.69  4746.0  312.24  4760.3  310.62  4774.7  309.92  4795.5  310.53
  4824.2  310.00  4867.1  310.84  4966.5  309.97  4981.4  309.17  4993.3  309.13
  4993.8  308.33  4999.0  308.33  4999.5  309.13  5002.4  309.87  5023.4  310.40
  5131.3  310.94  5176.2  311.68  5299.0  310.21  5320.0  310.91  5362.0  310.13
  5391.9  310.29  5562.9  316.79  5723.2  321.41  5803.4  321.87  5846.6  321.50
#Mann=3,-1,0
  4520.0     0.1       0  4993.3    0.07       0  4999.5     0.1       0
Bank Sta=4993.3,4999.5
Exp/Cntr=0.3,0.1

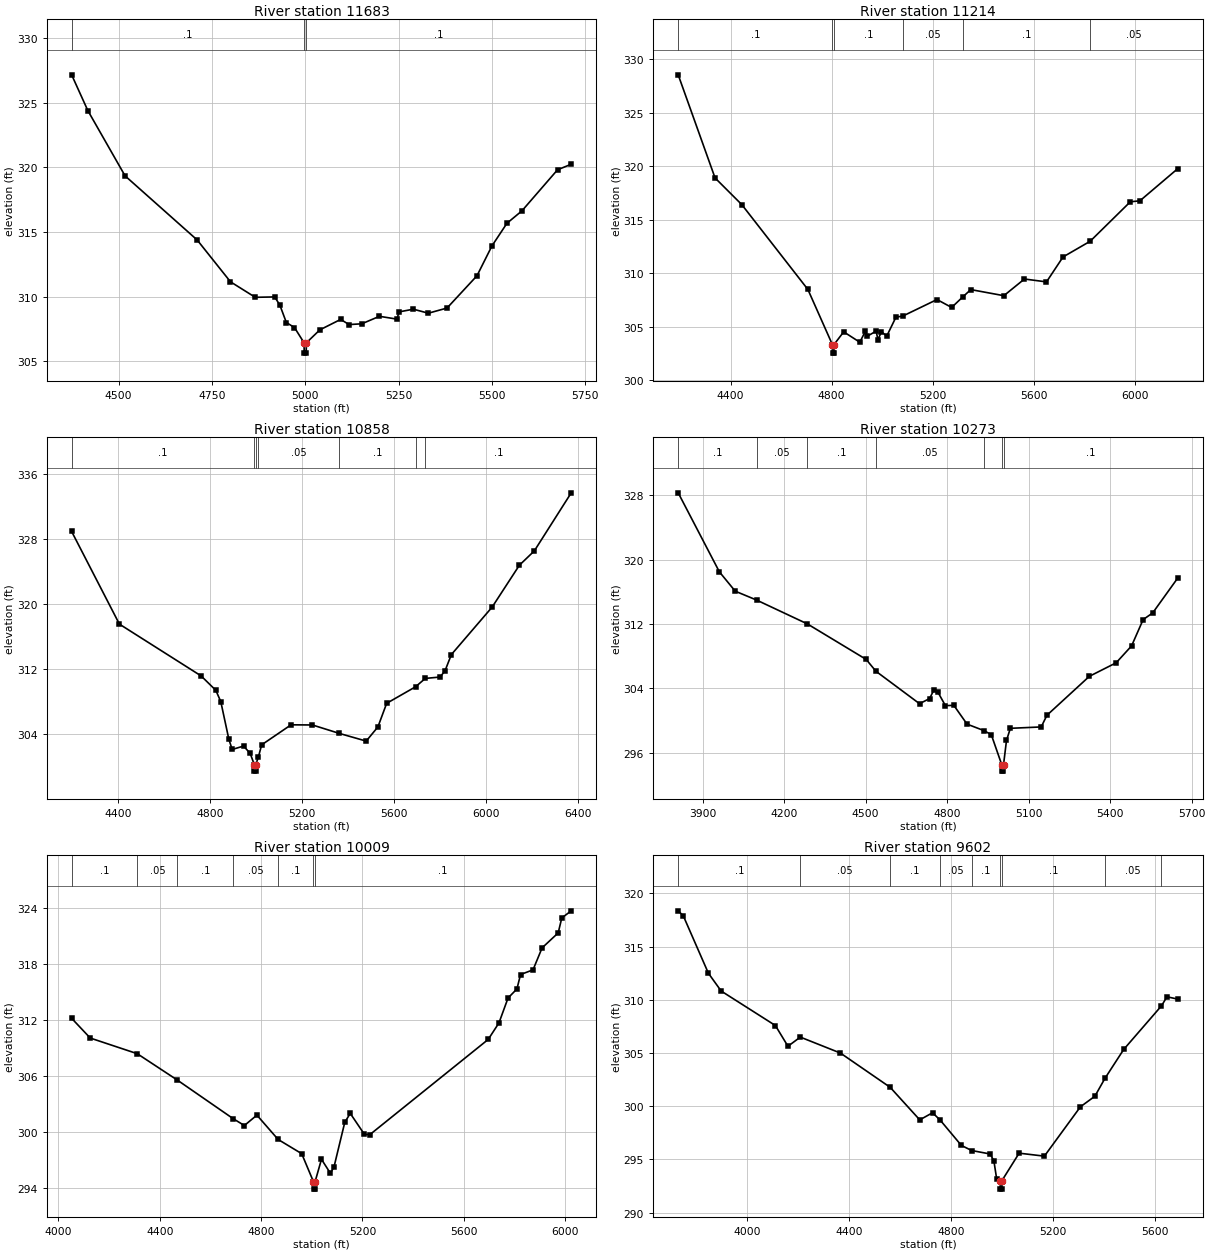
Type RM Length L Ch R = 1,11683,469,469,469
BEGIN DESCRIPTION:
Mapping XS 9cf13474
END DESCRIPTION:
XS GIS Cut Line= 4
      2110754.60     13391785.84      2111014.99     13391447.32
      2111127.84     13391048.01      2111162.56     13390553.26
#Sta/Elev= 30
  4374.5  327.16  4417.9  324.39  4517.6  319.34  4710.6  314.38  4799.9  311.14
  4866.3  309.94  4918.3  309.97  4932.1  309.34  4949.5  307.99  4971.3  307.60
  4996.9  306.42  4997.4  305.62  5002.7  305.62  5003.2  306.42  5039.2  307.42
  5095.0  308.23  5117.5  307.83  5151.5  307.89  5198.9  308.47  5246.0  308.25
  5251.0  308.81  5289.7  309.02  5329.8  308.71  5379.9  309.11  5460.1  311.61
  5500.2  313.92  5540.3  315.67  5580.4  316.63  5675.8  319.81  5712.5  320.24
#Mann=3,-1,0
  4374.5     0.1       0  4996.9    0.07       0  5003.2     0.1       0
Bank Sta=4996.9,5003.2
Exp/Cntr=0.3,0.1

Type RM Length L Ch R = 1,11214,356,356,356
BEGIN DESCRIPTION:
Mapping XS 4b9e9712
END DESCRIPTION:
XS GIS Cut Line= 4
      2110841.36     13391937.79      2111197.29     13391577.53
      2111540.17     13391169.54      2111990.80     13390346.27
#Sta/Elev= 30
  4192.8  328.55  4338.7  318.91  4444.8  316.41  4706.3  308.48  4803.2  303.33
  4803.7  302.53  4809.1  302.53  4809.6  303.33  4848.0  304.52  4911.8  303.55
  4933.9  304.58  4940.4  304.10  4976.8  304.59  4983.3  303.78  4997.6  304.53
  5018.4  304.12  5054.8  305.89  5082.4  306.00  5217.4  307.54  5275.4  306.80
  5319.7  307.79  5351.2  308.47  5482.1  307.90  5563.6  309.46  5650.9  309.19
  5716.3  311.52  5823.8  312.99  5982.8  316.68  6020.7  316.77  6170.7  319.78
#Mann=6,-1,0
  4192.8     0.1       0  4803.2    0.07       0  4809.6     0.1       0
  5082.4    0.05       0  5319.7     0.1       0  5823.8    0.05       0
Bank Sta=4803.2,4809.6
Exp/Cntr=0.3,0.1

Type RM Length L Ch R = 1,10858,585,585,585
BEGIN DESCRIPTION:
Mapping XS 61eb6316
END DESCRIPTION:
XS GIS Cut Line= 4
      2110893.47     13392128.74      2111340.52     13391855.30
      2111870.03     13391195.58      2112568.85     13390800.60
#Sta/Elev= 30
  4197.8  328.88  4405.5  317.50  4760.7  311.14  4824.8  309.37  4846.4  307.98
  4881.6  303.34  4896.0  302.10  4945.6  302.52  4974.4  301.61  4992.1  300.24
  4992.6  299.44  4998.0  299.44  4998.5  300.24  5010.3  301.21  5024.1  302.67
  5152.1  305.13  5244.9  305.11  5362.4  304.07  5478.8  303.13  5529.7  304.87
  5567.8  307.77  5693.4  309.80  5735.8  310.83  5800.1  311.00  5821.7  311.77
  5849.2  313.76  6026.7  319.60  6145.1  324.74  6210.1  326.50  6370.5  333.63
#Mann=7,-1,0
  4197.8     0.1       0  4992.1    0.07       0  4998.5     0.1       0
  5010.3    0.05       0  5362.4     0.1       0  5693.4    0.05       0
  5735.8     0.1       0
Bank Sta=4992.1,4998.5
Exp/Cntr=0.3,0.1

Type RM Length L Ch R = 1,10273,264,264,264
BEGIN DESCRIPTION:
Bruce Branch 22.0
END DESCRIPTION:
XS GIS Cut Line= 3
      2110975.01     13392325.00      2111975.00     13391725.00
      2112425.02     13391224.97
#Sta/Elev= 30
  3810.2  328.29  3961.8  318.47  4020.1  316.07  4098.5  314.97  4285.8  312.00
  4502.1  307.59  4538.0  306.12  4698.4  302.09  4735.4  302.72  4750.9  303.76
  4766.5  303.50  4793.7  301.85  4824.8  301.88  4873.4  299.55  4936.7  298.73
  4962.8  298.23  5001.1  294.51  5001.6  293.71  5007.2  293.71  5007.7  294.51
  5018.6  297.52  5032.8  299.03  5146.4  299.20  5167.4  300.65  5323.6  305.49
  5422.2  307.17  5479.0  309.27  5521.6  312.54  5556.8  313.37  5649.1  317.71
#Mann=7,-1,0
  3810.2     0.1       0  4098.5    0.05       0  4285.8     0.1       0
  4538.0    0.05       0  4936.7     0.1       0  5001.1    0.07       0
  5007.7     0.1       0
Bank Sta=5001.1,5007.7
Exp/Cntr=0.3,0.1

Type RM Length L Ch R = 1,10009,407,407,407
BEGIN DESCRIPTION:
Bruce Branch 21.0
END DESCRIPTION:
XS GIS Cut Line= 3
      2111449.03     13392562.76      2112113.09     13391929.09
      2112824.91     13391152.16
#Sta/Elev= 30
  4052.2  312.18  4125.6  310.07  4310.9  308.40  4469.7  305.57  4689.7  301.45
  4733.9  300.72  4783.3  301.83  4867.0  299.23  4960.1  297.71  5006.4  294.72
  5006.9  293.92  5012.5  293.92  5013.0  294.72  5038.1  297.11  5073.2  295.62
  5087.4  296.28  5130.0  301.05  5151.6  302.02  5207.7  299.77  5229.3  299.75
  5696.0  309.92  5738.6  311.69  5774.4  314.35  5809.5  315.32  5823.7  316.86
  5873.0  317.36  5908.8  319.71  5972.3  321.31  5986.5  322.91  6023.8  323.67
#Mann=7,-1,0
  4052.2     0.1       0  4310.9    0.05       0  4469.7     0.1       0
  4689.7    0.05       0  4867.0     0.1       0  5006.4    0.07       0
  5013.0     0.1       0
Bank Sta=5006.4,5013
Exp/Cntr=0.3,0.1

Type RM Length L Ch R = 1,9602,392,392,392
BEGIN DESCRIPTION:
Bruce Branch 20.0
END DESCRIPTION:
XS GIS Cut Line= 3
      2111488.07     13392905.66      2112425.00     13392075.00
      2112924.97     13391575.03
#Sta/Elev= 30
  3729.3  318.37  3749.1  317.91  3847.8  312.50  3897.9  310.83  4110.4  307.59
  4159.7  305.64  4208.2  306.50  4365.5  305.00  4560.6  301.78  4676.6  298.72
  4726.8  299.39  4757.0  298.69  4839.7  296.32  4880.0  295.84  4953.4  295.51
  4967.6  294.82  4978.1  293.19  4992.2  293.01  4992.7  292.21  4998.4  292.21
  4998.9  293.01  5066.3  295.59  5165.3  295.31  5306.7  299.95  5363.3  300.94
  5402.6  302.61  5476.4  305.34  5624.6  309.44  5646.1  310.29  5688.5  310.07
#Mann=9,-1,0
  3729.3     0.1       0  4208.2    0.05       0  4560.6     0.1       0
  4757.0    0.05       0  4880.0     0.1       0  4992.2    0.07       0
  4998.9     0.1       0  5402.6    0.05       0  5624.6     0.1       0
Bank Sta=4992.2,4998.9
Exp/Cntr=0.3,0.1

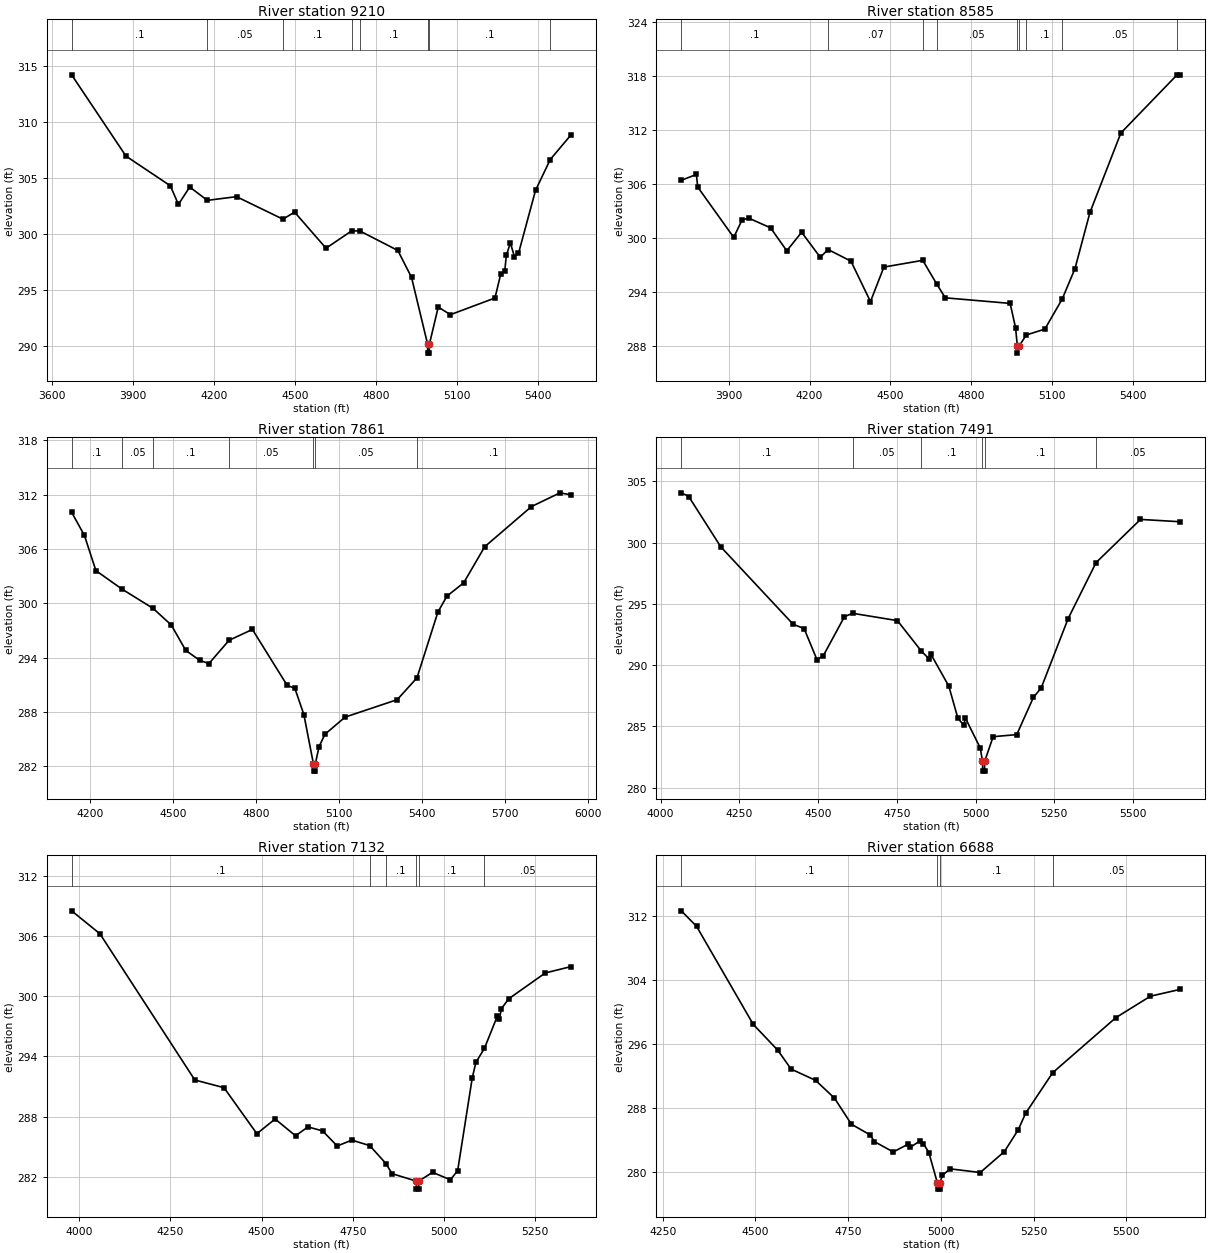
Type RM Length L Ch R = 1,9210,625,625,625
BEGIN DESCRIPTION:
Bruce Branch 19.0
END DESCRIPTION:
XS GIS Cut Line= 3
      2111644.36     13393014.14      2112725.00     13392275.00
      2113175.02     13391974.98
#Sta/Elev= 30
  3671.9  314.18  3873.3  306.93  4037.8  304.28  4067.7  302.62  4109.6  304.17
  4175.0  302.98  4283.0  303.31  4455.2  301.30  4498.3  301.93  4614.8  298.71
  4709.4  300.25  4739.3  300.26  4880.9  298.51  4931.7  296.11  4991.3  290.15
  4991.8  289.35  4997.5  289.35  4998.0  290.15  5030.7  293.46  5075.8  292.78
  5241.0  294.27  5262.1  296.38  5277.1  296.64  5283.1  298.07  5298.1  299.18
  5313.1  297.97  5328.2  298.25  5391.3  303.87  5445.8  306.62  5522.0  308.80
#Mann=8,-1,0
  3671.9     0.1       0  4175.0    0.05       0  4455.2     0.1       0
  4709.4    0.05       0  4739.3     0.1       0  4991.3    0.07       0
  4998.0     0.1       0  5445.8    0.05       0
Bank Sta=4991.3,4998
Exp/Cntr=0.3,0.1

Type RM Length L Ch R = 1,8585,724,724,724
BEGIN DESCRIPTION:
Mapping XS ce6715ab
END DESCRIPTION:
XS GIS Cut Line= 3
      2111857.04     13392944.70      2112751.11     13392706.00
      2113675.60     13392649.57
#Sta/Elev= 30
  3724.4  306.45  3780.3  307.10  3785.5  305.69  3918.9  300.10  3950.0  302.06
  3975.6  302.23  4055.7  301.16  4115.6  298.61  4170.8  300.67  4239.8  297.89
  4269.0  298.75  4353.7  297.46  4426.1  292.96  4475.9  296.80  4620.1  297.55
  4671.5  294.93  4703.8  293.38  4944.2  292.76  4964.3  290.06  4970.9  288.03
  4971.4  287.23  4977.7  288.03  5004.3  289.25  5073.0  289.90  5137.6  293.26
  5184.7  296.63  5240.2  302.87  5355.0  311.71  5563.5  318.18  5576.0  318.14
#Mann=9,-1,0
  3724.4     0.1       0  4269.0    0.07       0  4620.1     0.1       0
  4671.5    0.05       0  4970.9   0.035       0  4977.7    0.05       0
  5004.3     0.1       0  5137.6    0.05       0  5563.5     0.1       0
Bank Sta=4970.9,4977.7
Exp/Cntr=0.3,0.1

Type RM Length L Ch R = 1,7861,370,370,370
BEGIN DESCRIPTION:
Mapping XS 21f84255
END DESCRIPTION:
XS GIS Cut Line= 2
      2112060.96     13393487.26      2113784.14     13392957.72
#Sta/Elev= 30
  4133.7  310.06  4179.8  307.51  4221.4  303.61  4315.1  301.58  4428.2  299.43
  4493.6  297.60  4545.9  294.79  4597.0  293.68  4629.6  293.34  4702.3  295.91
  4786.5  297.11  4912.3  290.92  4939.8  290.61  4972.5  287.70  5007.0  282.25
  5007.5  281.45  5013.4  281.45  5013.9  282.25  5027.2  284.15  5048.4  285.52
  5121.3  287.42  5309.6  289.35  5380.9  291.76  5456.7  299.05  5489.4  300.80
  5549.6  302.26  5625.5  306.25  5794.3  310.69  5897.6  312.21  5936.4  311.99
#Mann=7,-1,0
  4133.7     0.1       0  4315.1    0.05       0  4428.2     0.1       0
  4702.3    0.05       0  5007.0   0.035       0  5013.9    0.05       0
  5380.9     0.1       0
Bank Sta=5007,5013.9
Exp/Cntr=0.3,0.1

Type RM Length L Ch R = 1,7491,359,359,359
BEGIN DESCRIPTION:
Mapping XS e5027c78
END DESCRIPTION:
XS GIS Cut Line= 2
      2112221.61     13393665.20      2113779.70     13393374.41
#Sta/Elev= 30
  4065.7  304.06  4089.2  303.76  4191.2  299.65  4420.6  293.34  4455.7  292.98
  4496.4  290.45  4516.7  290.77  4583.7  293.95  4609.6  294.23  4752.0  293.63
  4828.4  291.13  4852.2  290.52  4857.3  290.93  4915.1  288.29  4944.0  285.66
  4962.7  285.10  4967.8  285.68  5015.2  283.23  5022.1  282.15  5022.6  281.35
  5028.5  281.35  5029.0  282.15  5055.9  284.16  5130.9  284.33  5183.6  287.36
  5208.5  288.14  5294.1  293.80  5382.8  298.37  5523.8  301.89  5650.7  301.70
#Mann=6,-1,0
  4065.7     0.1       0  4609.6    0.05       0  4828.4     0.1       0
  5022.1    0.07       0  5029.0     0.1       0  5382.8    0.05       0
Bank Sta=5022.1,5029
Exp/Cntr=0.3,0.1

Type RM Length L Ch R = 1,7132,444,444,444
BEGIN DESCRIPTION:
Mapping XS 7ae6fc27
END DESCRIPTION:
XS GIS Cut Line= 2
      2112247.59     13393843.15      2113614.81     13393769.37
#Sta/Elev= 30
  3978.9  308.56  4056.4  306.27  4316.8  291.65  4396.9  290.88  4487.0  286.28
  4537.1  287.75  4593.1  286.07  4627.2  286.96  4667.3  286.56  4707.4  285.05
  4747.4  285.64  4796.6  285.09  4841.5  283.28  4857.6  282.29  4924.2  281.54
  4924.7  280.74  4930.6  280.74  4931.1  281.54  4969.0  282.42  5017.8  281.67
  5037.8  282.59  5077.9  291.88  5087.9  293.41  5111.3  294.82  5146.9  298.06
  5151.9  297.74  5158.0  298.79  5178.0  299.77  5278.2  302.35  5348.1  302.98
#Mann=6,-1,0
  3978.9     0.1       0  4796.6    0.05       0  4841.5     0.1       0
  4924.2    0.07       0  4931.1     0.1       0  5111.3    0.05       0
Bank Sta=4924.2,4931.1
Exp/Cntr=0.3,0.1

Type RM Length L Ch R = 1,6688,630,630,630
BEGIN DESCRIPTION:
Mapping XS a410eef3
END DESCRIPTION:
XS GIS Cut Line= 2
      2112364.77     13394251.15      2113684.27     13393986.38
#Sta/Elev= 30
  4300.3  312.69  4341.3  310.76  4494.3  298.48  4560.4  295.25  4596.3  292.89
  4662.3  291.48  4713.2  289.26  4759.0  285.99  4809.9  284.64  4820.7  283.82
  4871.7  282.52  4911.7  283.49  4916.8  283.08  4943.1  283.88  4953.3  283.54
  4967.7  282.45  4990.6  278.67  4991.1  277.87  4997.1  277.87  4997.6  278.67
  5004.3  279.59  5024.7  280.41  5106.3  279.95  5171.4  282.57  5208.3  285.26
  5228.7  287.36  5301.5  292.43  5471.8  299.32  5565.2  302.01  5646.1  302.87
#Mann=4,-1,0
  4300.3     0.1       0  4990.6    0.07       0  4997.6     0.1       0
  5301.5    0.05       0
Bank Sta=4990.6,4997.6
Exp/Cntr=0.3,0.1

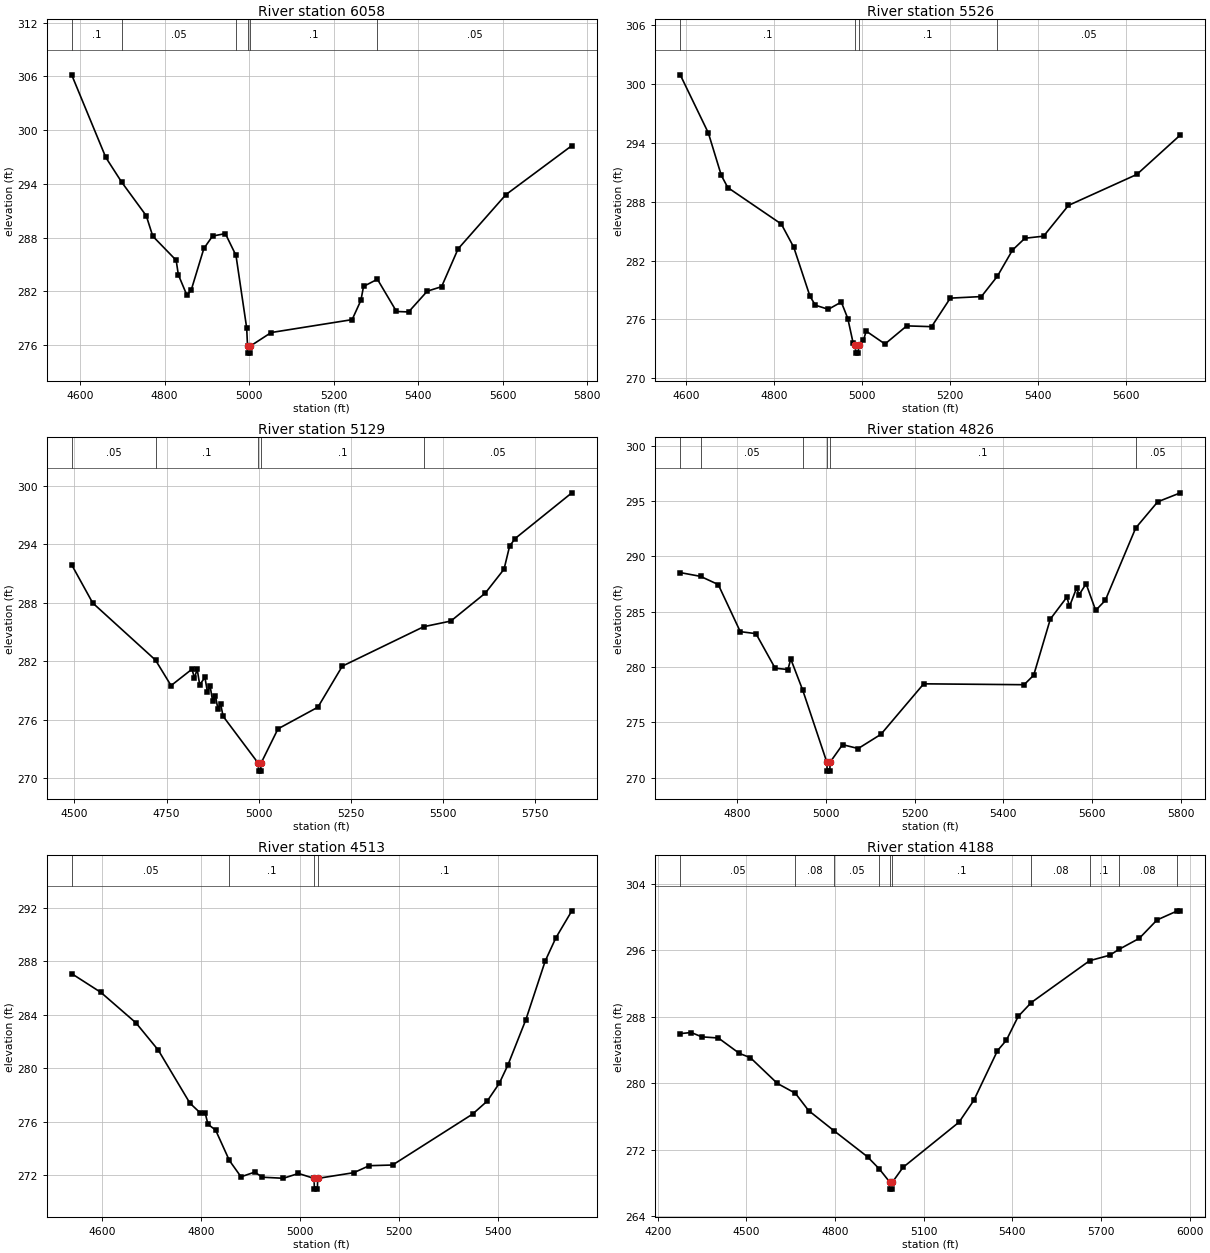
Type RM Length L Ch R = 1,6058,532,532,532
BEGIN DESCRIPTION:
Bruce Branch 12.0
END DESCRIPTION:
XS GIS Cut Line= 3
      2112475.04     13394425.01      2112890.80     13394484.54
      2113624.98     13394275.00
#Sta/Elev= 30
  4580.0  306.18  4660.8  296.95  4698.4  294.19  4756.5  290.44  4771.9  288.16
  4827.2  285.47  4832.5  283.84  4852.7  281.56  4862.8  282.13  4892.8  286.79
  4913.3  288.17  4943.6  288.45  4968.8  286.01  4994.1  277.91  4996.1  275.90
  4996.6  275.10  5002.6  275.10  5003.1  275.90  5052.1  277.40  5243.6  278.84
  5264.4  281.00  5270.6  282.55  5303.4  283.35  5348.6  279.75  5377.2  279.70
  5421.4  282.02  5455.3  282.52  5494.3  286.74  5607.5  292.80  5763.5  298.27
#Mann=6,-1,0
  4580.0     0.1       0  4698.4    0.05       0  4968.8     0.1       0
  4996.1    0.07       0  5003.1     0.1       0  5303.4    0.05       0
Bank Sta=4996.1,5003.1
Exp/Cntr=0.3,0.1

Type RM Length L Ch R = 1,5526,397,397,397
BEGIN DESCRIPTION:
Bruce Branch 11.0
END DESCRIPTION:
XS GIS Cut Line= 3
      2112725.01     13395125.00      2113075.00     13394875.00
      2113574.99     13394375.01
#Sta/Elev= 30
  4586.3  300.95  4650.2  295.02  4679.7  290.69  4694.4  289.45  4816.1  285.73
  4844.4  283.36  4881.2  278.37  4893.5  277.45  4923.0  277.03  4952.5  277.77
  4967.3  276.09  4979.5  273.57  4984.5  273.36  4985.1  272.56  4991.2  272.56
  4991.7  273.36  5002.9  273.86  5009.0  274.81  5051.8  273.49  5101.3  275.34
  5157.8  275.26  5200.3  278.17  5271.0  278.33  5307.3  280.40  5341.7  283.07
  5370.0  284.28  5412.4  284.49  5469.0  287.63  5624.5  290.79  5723.5  294.82
#Mann=4,-1,0
  4586.3     0.1       0  4984.5    0.07       0  4991.7     0.1       0
  5307.3    0.05       0
Bank Sta=4984.5,4991.7
Exp/Cntr=0.3,0.1

Type RM Length L Ch R = 1,5129,303,303,303
BEGIN DESCRIPTION:
Bruce Branch 10.0
END DESCRIPTION:
XS GIS Cut Line= 3
      2112934.68     13395385.57      2113325.00     13395025.00
      2113781.90     13394336.96
#Sta/Elev= 30
  4492.5  291.88  4549.6  287.97  4720.0  282.12  4762.2  279.51  4818.9  281.19
  4825.7  280.30  4833.1  281.19  4839.9  279.60  4854.1  280.34  4860.9  278.87
  4868.2  279.45  4875.0  277.94  4882.4  278.49  4889.2  277.15  4896.6  277.65
  4903.4  276.37  4999.0  271.55  4999.6  270.75  5005.7  270.75  5006.2  271.55
  5052.4  275.08  5160.7  277.30  5226.9  281.50  5447.8  285.54  5521.5  286.12
  5614.7  288.97  5665.8  291.43  5680.9  293.79  5695.9  294.57  5849.8  299.25
#Mann=5,-1,0
  4492.5    0.05       0  4720.0     0.1       0  4999.0    0.07       0
  5006.2     0.1       0  5447.8    0.05       0
Bank Sta=4999,5006.2
Exp/Cntr=0.3,0.1

Type RM Length L Ch R = 1,4826,313,313,313
BEGIN DESCRIPTION:
Bruce Branch 9.0
END DESCRIPTION:
XS GIS Cut Line= 3
      2113325.01     13395474.98      2113525.00     13395225.00
      2113925.02     13394524.97
#Sta/Elev= 30
  4672.4  288.53  4718.1  288.19  4758.0  287.45  4807.6  283.20  4842.9  283.02
  4886.1  279.90  4914.9  279.78  4921.3  280.73  4948.5  277.89  5002.6  271.41
  5003.2  270.61  5009.3  270.61  5009.8  271.41  5037.9  273.00  5073.2  272.65
  5124.3  273.93  5220.7  278.49  5446.8  278.41  5468.4  279.27  5505.8  284.33
  5543.2  286.32  5549.0  285.47  5564.8  287.12  5570.6  286.53  5586.4  287.52
  5608.0  285.12  5629.6  286.02  5698.2  292.56  5747.7  294.92  5798.8  295.73
#Mann=6,-1,0
  4672.4     0.1       0  4718.1    0.05       0  4948.5     0.1       0
  5002.6    0.07       0  5009.8     0.1       0  5698.2    0.05       0
Bank Sta=5002.6,5009.8
Exp/Cntr=0.3,0.1

Type RM Length L Ch R = 1,4513,325,325,325
BEGIN DESCRIPTION:
Bruce Branch 8.0
END DESCRIPTION:
XS GIS Cut Line= 3
      2113575.00     13395575.00      2113825.00     13395175.00
      2114025.00     13394675.01
#Sta/Elev= 30
  4538.2  287.07  4597.2  285.67  4667.9  283.40  4713.3  281.35  4777.0  277.40
  4798.2  276.66  4807.7  276.68  4813.5  275.82  4828.9  275.39  4856.7  273.12
  4880.2  271.90  4907.9  272.25  4923.2  271.87  4965.7  271.79  4996.3  272.15
  5027.8  271.78  5028.4  270.98  5034.5  270.98  5035.0  271.78  5108.2  272.21
  5139.1  272.73  5186.3  272.78  5347.8  276.58  5377.4  277.55  5401.7  278.87
  5419.2  280.24  5455.5  283.63  5494.6  288.01  5516.1  289.74  5548.4  291.76
#Mann=4,-1,0
  4538.2    0.05       0  4856.7     0.1       0  5027.8    0.07       0
  5035.0     0.1       0
Bank Sta=5027.8,5035
Exp/Cntr=0.3,0.1

Type RM Length L Ch R = 1,4188,162,162,162
BEGIN DESCRIPTION:
Bruce Branch 7.0
END DESCRIPTION:
XS GIS Cut Line= 3
      2113785.36     13395746.70      2114132.59     13395482.81
      2114125.64     13394225.85
#Sta/Elev= 30
  4275.8  285.96  4313.0  286.09  4348.7  285.57  4404.9  285.43  4476.3  283.57
  4513.0  283.07  4604.5  279.97  4665.6  278.78  4710.3  276.70  4796.3  274.27
  4909.7  271.14  4949.3  269.69  4986.1  268.05  4986.6  267.25  4992.8  267.25
  4993.3  268.05  5029.7  269.86  5219.7  275.31  5269.7  277.94  5349.7  283.91
  5379.7  285.16  5419.7  288.02  5464.2  289.70  5661.6  294.73  5729.7  295.39
  5760.3  296.08  5829.7  297.42  5889.7  299.63  5957.7  300.71  5968.9  300.73
#Mann=10,-1,0
  4275.8    0.05       0  4665.6    0.08       0  4796.3    0.05       0
  4949.3     0.1       0  4986.1    0.07       0  4993.3     0.1       0
  5464.2    0.08       0  5661.6     0.1       0  5760.3    0.08       0
  5957.7     0.1       0
Bank Sta=4986.1,4993.3
Exp/Cntr=0.3,0.1