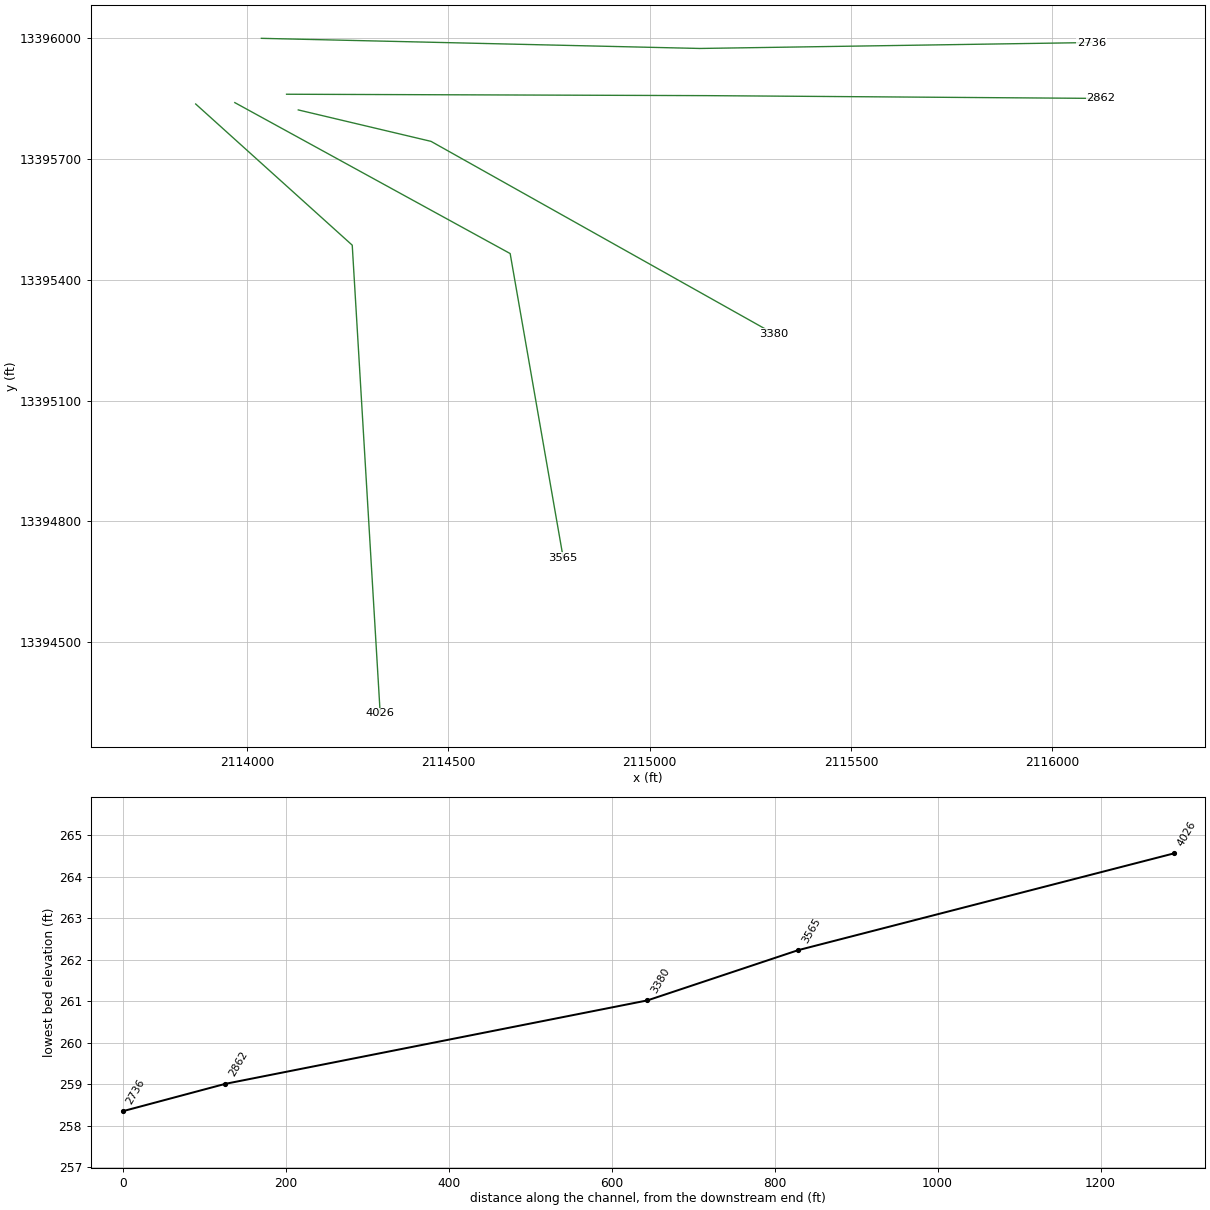
HEC-RAS study Bruce Branch.prj: Bruce Branch Base Level Engineering

--- Bruce Branch.g01 (geometry) --- (continued)

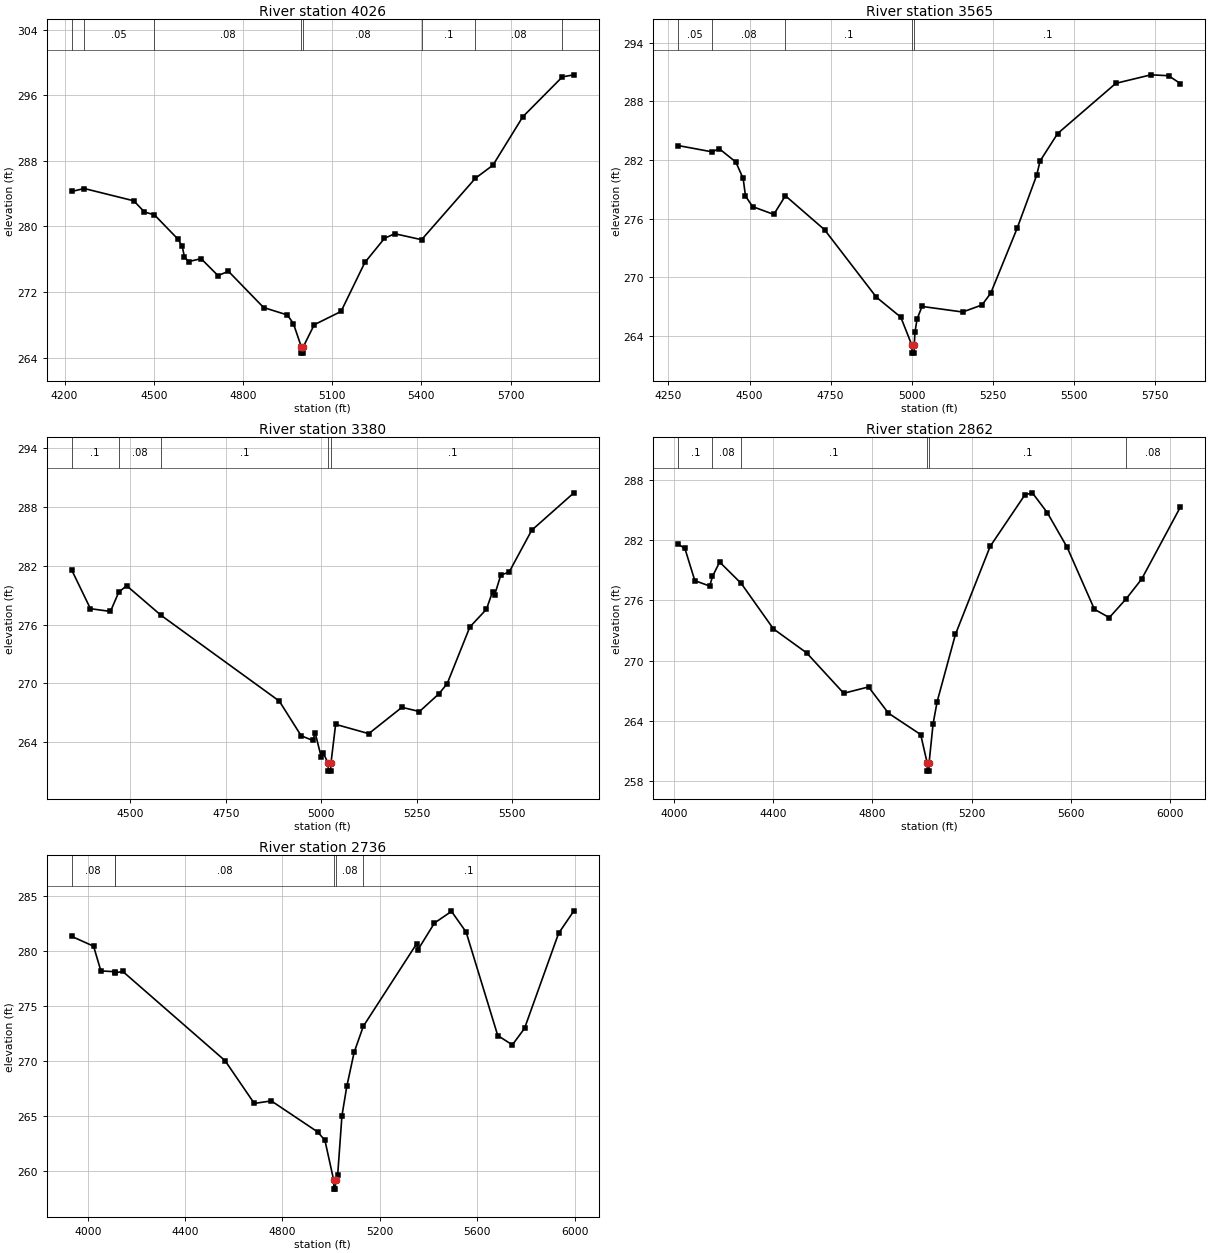
Type RM Length L Ch R = 1,4026,461,461,461
BEGIN DESCRIPTION:
Bruce Branch 6.0
END DESCRIPTION:
XS GIS Cut Line= 4
      2113872.13     13395837.01      2114261.06     13395486.28
      2114292.58     13394958.31      2114330.51     13394323.06
#Sta/Elev= 30
  4224.1  284.27  4265.9  284.63  4432.7  283.13  4468.5  281.77  4502.1  281.42
  4581.4  278.45  4595.6  277.58  4603.1  276.29  4617.3  275.72  4659.1  276.08
  4715.9  274.01  4751.0  274.54  4869.3  270.12  4949.4  269.21  4969.5  268.17
  4995.9  265.36  4996.4  264.56  5002.6  264.56  5003.2  265.36  5039.6  268.02
  5129.8  269.64  5209.9  275.61  5275.9  278.55  5310.1  279.12  5400.8  278.39
  5581.7  285.88  5640.7  287.47  5741.3  293.38  5874.3  298.24  5913.1  298.49
#Mann=8,-1,0
  4224.1    0.08       0  4265.9    0.05       0  4502.1    0.08       0
  4995.9    0.07       0  5003.2    0.08       0  5400.8     0.1       0
  5581.7    0.08       0  5874.3     0.1       0
Bank Sta=4995.9,5003.2
Exp/Cntr=0.3,0.1

Type RM Length L Ch R = 1,3565,185,185,185
BEGIN DESCRIPTION:
Bruce Branch 5.0
END DESCRIPTION:
XS GIS Cut Line= 3
      2113969.38     13395840.45      2114653.42     13395465.45
      2114785.24     13394709.24
#Sta/Elev= 30
  4280.1  283.48  4385.3  282.83  4406.1  283.17  4457.6  281.80  4480.4  280.11
  4487.6  278.31  4509.4  277.23  4574.8  276.43  4610.6  278.34  4731.3  274.86
  4890.9  267.96  4966.3  265.91  5000.5  263.03  5001.1  262.23  5007.3  262.23
  5007.8  263.03  5009.9  264.38  5016.4  265.71  5031.7  267.01  5156.9  266.44
  5216.5  267.16  5243.4  268.36  5324.6  274.99  5385.0  280.43  5395.6  281.90
  5449.7  284.71  5629.1  289.85  5737.4  290.72  5791.5  290.63  5827.8  289.83
#Mann=5,-1,0
  4280.1    0.05       0  4385.3    0.08       0  4610.6     0.1       0
  5000.5    0.07       0  5007.8     0.1       0
Bank Sta=5000.5,5007.8
Exp/Cntr=0.3,0.1

Type RM Length L Ch R = 1,3380,518,518,518
BEGIN DESCRIPTION:
Mapping XS 9d747b91
END DESCRIPTION:
XS GIS Cut Line= 3
      2114127.02     13395822.31      2114456.84     13395744.19
      2115307.57     13395266.74
#Sta/Elev= 30
  4346.9  281.56  4395.7  277.62  4448.2  277.34  4469.8  279.30  4490.5  279.97
  4581.0  276.93  4890.1  268.18  4947.5  264.63  4978.3  264.15  4984.0  264.95
  5000.0  262.44  5005.7  262.84  5018.0  261.82  5018.5  261.02  5024.8  261.02
  5025.4  261.82  5037.6  265.80  5124.4  264.85  5211.2  267.54  5257.1  267.11
  5308.0  268.92  5329.7  269.96  5389.0  275.75  5432.4  277.56  5448.4  279.35
  5454.1  279.04  5470.0  281.06  5491.7  281.35  5551.0  285.64  5661.4  289.46
#Mann=5,-1,0
  4346.9     0.1       0  4469.8    0.08       0  4581.0     0.1       0
  5018.0    0.07       0  5025.4     0.1       0
Bank Sta=5018,5025.4
Exp/Cntr=0.3,0.1

Type RM Length L Ch R = 1,2862,126,126,126
BEGIN DESCRIPTION:
Bruce Branch 4.0
END DESCRIPTION:
XS GIS Cut Line= 3
      2114097.90     13395861.28      2115143.00     13395857.81
      2116121.07     13395850.87
#Sta/Elev= 30
  4017.1  281.60  4044.2  281.17  4084.2  277.97  4144.2  277.43  4155.3  278.39
  4184.2  279.82  4271.2  277.69  4400.8  273.17  4534.2  270.79  4684.2  266.76
  4784.2  267.39  4864.2  264.78  4994.2  262.65  5020.5  259.81  5021.1  259.01
  5027.4  259.01  5028.0  259.81  5044.2  263.72  5060.7  265.94  5134.2  272.62
  5274.2  281.38  5414.2  286.51  5444.2  286.71  5504.2  284.74  5584.2  281.29
  5694.2  275.12  5754.2  274.29  5821.8  276.15  5884.2  278.11  6040.3  285.28
#Mann=6,-1,0
  4017.1     0.1       0  4155.3    0.08       0  4271.2     0.1       0
  5020.5    0.07       0  5028.0     0.1       0  5821.8    0.08       0
Bank Sta=5020.5,5028
Exp/Cntr=0.3,0.1

Type RM Length L Ch R = 1,2736,0,0,0
BEGIN DESCRIPTION:
Bruce Branch 3.0
END DESCRIPTION:
XS GIS Cut Line= 3
      2114035.38     13396000.17      2115125.00     13395975.00
      2116097.88     13395989.75
#Sta/Elev= 30
  3934.3  281.35  4023.9  280.46  4053.9  278.21  4110.2  278.14  4113.9  278.05
  4144.0  278.16  4564.1  270.04  4684.1  266.15  4754.1  266.38  4944.2  263.56
  4974.2  262.80  5010.5  259.15  5011.1  258.35  5017.4  258.35  5018.0  259.15
  5026.7  259.63  5044.2  265.02  5064.2  267.70  5094.2  270.79  5132.0  273.17
  5351.6  280.70  5356.6  280.14  5424.3  282.57  5494.3  283.63  5554.3  281.75
  5684.3  272.33  5744.3  271.48  5794.3  272.98  5934.3  281.63  5997.2  283.68
#Mann=6,-1,0
  3934.3    0.08       0  4110.2     0.1       0  4113.9    0.08       0
  5010.5    0.07       0  5018.0    0.08       0  5132.0     0.1       0
Bank Sta=5010.5,5018
Exp/Cntr=0.3,0.1

Chan Stop Cuts=-1