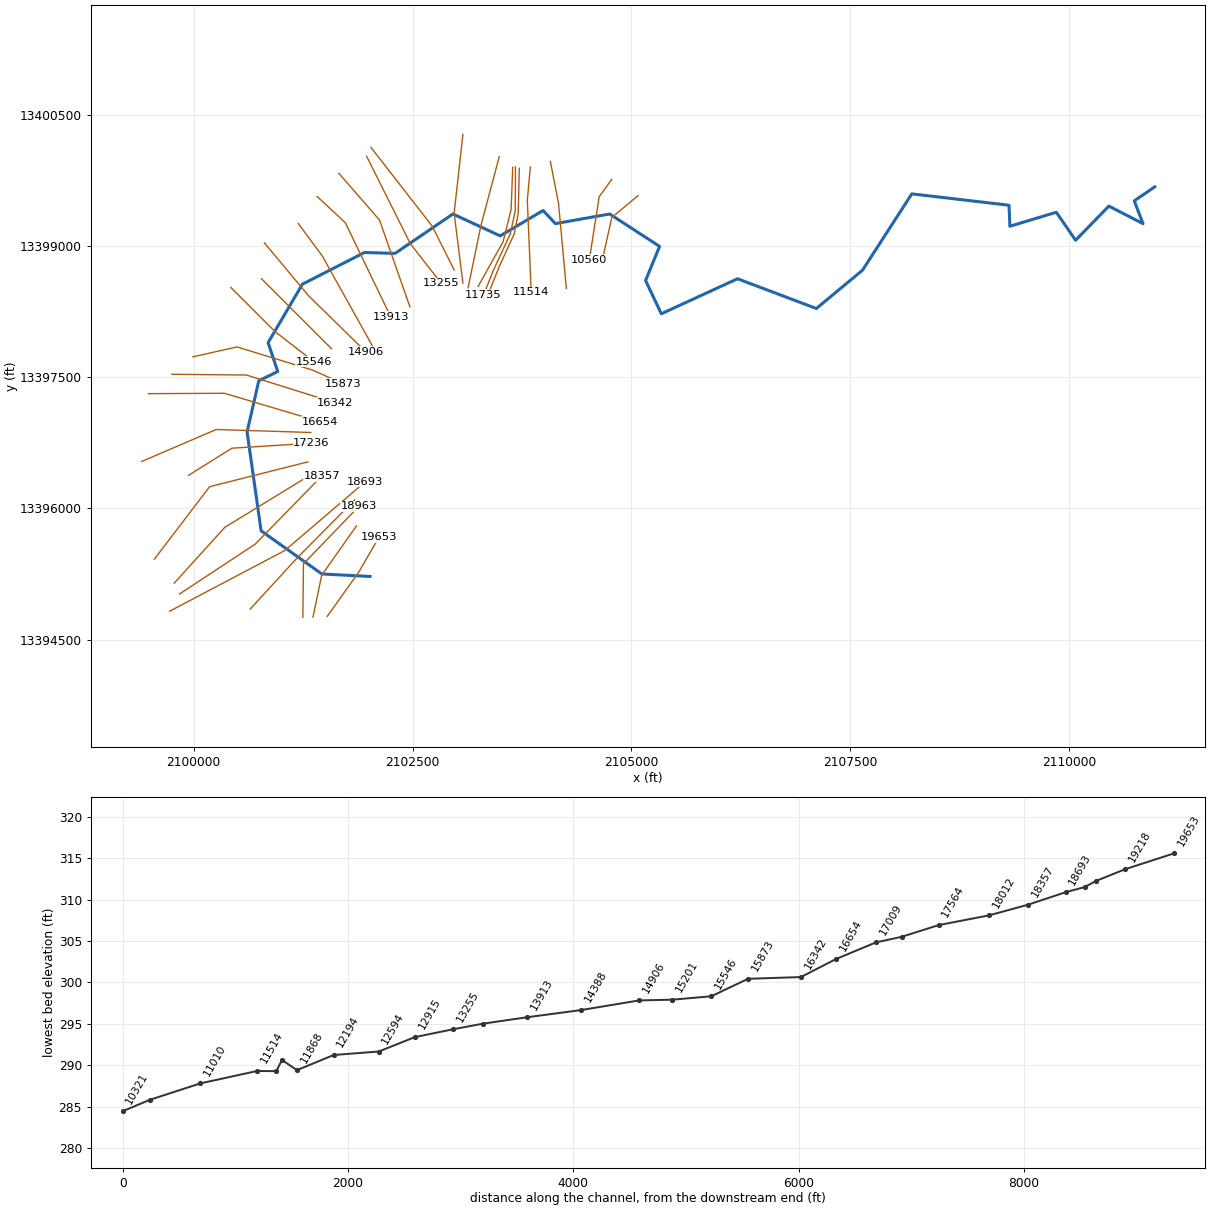
--- Far Live Oak Creek.prj (project) ---

Proj Title=Far Live Oak Creek Base Level Engineering
Current Plan=p01
Default Exp/Contr=0.3,0.1
English Units
Geom File=g01
Flow File=f01
Plan File=p01
Y Axis Title=Elevation
X Axis Title(PF)=Main Channel Distance
X Axis Title(XS)=Station
BEGIN DESCRIPTION:
Far Live Oak Creek
END DESCRIPTION:
DSS Export Rating Curves= 0
DSS Export Rating Curve Sorted= 0
DSS Export Volume Flow Curves= 0
DXF OffsetX= 0
DXF OffsetY= 0
DXF ScaleX= 1
DXF ScaleY= 10

--- Far Live Oak Creek.p01 (plan) ---

Plan Title=Multiple Run
Short Identifier=Multiple
Geom File=g01
Flow File=f01
Subcritical Flow
K Sum by GR= 0
Std Step Tol= 0.01
Critical Tol= 0.01
Num of Std Step Trials= 20
Max Error Tol= 0.3
Flow Tol Ratio= 0.001
Split Flow NTrial= 30
Split Flow Tol= 0.02
Split Flow Ratio= 0.02
Log Output Level= 0
Friction Slope Method= 1
Unsteady Friction Slope Method= 2
Unsteady Bridges Friction Slope Method= 1
Parabolic Critical Depth
Global Vel Dist=  1 , 1 , 1
Global Log Level= 0
CheckData=True
Encroach Param= -1, 0, 0, 0
BEGIN DESCRIPTION:
Multiple Run
END DESCRIPTION:

--- Far Live Oak Creek.f01 (steady flow) ---

Flow Title=Multiple
Program Version=5.05
Number of Profiles= 7
Profile Names=10-year,25-year,50-year,1pct_min,100-year,1pct_plu,500-year
River Rch & RM=Far Live Oak Cre,Reach-1         ,19653
     188     259     317     194     388     773     588
River Rch & RM=Far Live Oak Cre,Reach-1         ,17564
     296     418     521     324     646    1288    1008
River Rch & RM=Far Live Oak Cre,Reach-1         ,15201
     376     535     670     418     834    1664    1314
River Rch & RM=Far Live Oak Cre,Reach-1         ,10560
     442     633     796     498     993    1981    1572
River Rch & RM=Far Live Oak Cre,Reach-1         ,3932
     552     797    1008     634    1265    2525    2025
Boundary for River Rch & Prof#=Far Live Oak Cre,Reach-1         , 1
Up Type= 0
Dn Type= 3
Dn Slope=0.005
Boundary for River Rch & Prof#=Far Live Oak Cre,Reach-1         , 2
Up Type= 0
Dn Type= 3
Dn Slope=0.005
Boundary for River Rch & Prof#=Far Live Oak Cre,Reach-1         , 3
Up Type= 0
Dn Type= 3
Dn Slope=0.005
Boundary for River Rch & Prof#=Far Live Oak Cre,Reach-1         , 4
Up Type= 0
Dn Type= 3
Dn Slope=0.005
Boundary for River Rch & Prof#=Far Live Oak Cre,Reach-1         , 5
Up Type= 0
Dn Type= 3
Dn Slope=0.005
Boundary for River Rch & Prof#=Far Live Oak Cre,Reach-1         , 6
Up Type= 0
Dn Type= 3
Dn Slope=0.005
Boundary for River Rch & Prof#=Far Live Oak Cre,Reach-1         , 7
Up Type= 0
Dn Type= 3
Dn Slope=0.005
DSS Import GetInterval= 0
DSS Import GetPeak= 0
DSS Import FillOption= 0

--- Far Live Oak Creek.g01 (geometry) ---

Geom Title=Existing Conditions
Program Version=5.05

River Reach=Far Live Oak Cre,Reach-1
Reach XY= 30
      2102014.33     13395223.01      2101464.38     13395251.34
       2100770.8     13395744.54       2100610.8     13396874.54
      2100744.21     13397458.53       2100960.8     13397564.54
       2100850.8     13397894.54      2101242.57     13398562.61
       2101950.8     13398924.54       2102300.8     13398914.54
       2102960.8     13399364.54       2103500.8     13399114.54
       2103990.8     13399404.54       2104130.8     13399254.54
       2104750.8     13399364.54       2105320.8     13398994.54
       2105160.8     13398604.54       2105340.8     13398224.54
       2106210.8     13398624.54       2107110.8     13398284.54
      2107638.28     13398722.93       2108200.8     13399594.54
       2109310.8     13399464.54       2109320.8     13399224.54
       2109850.8     13399384.54       2110070.8     13399064.54
       2110450.8     13399454.54       2110840.8     13399254.54
       2110740.8     13399514.54        2110975.       13399675.

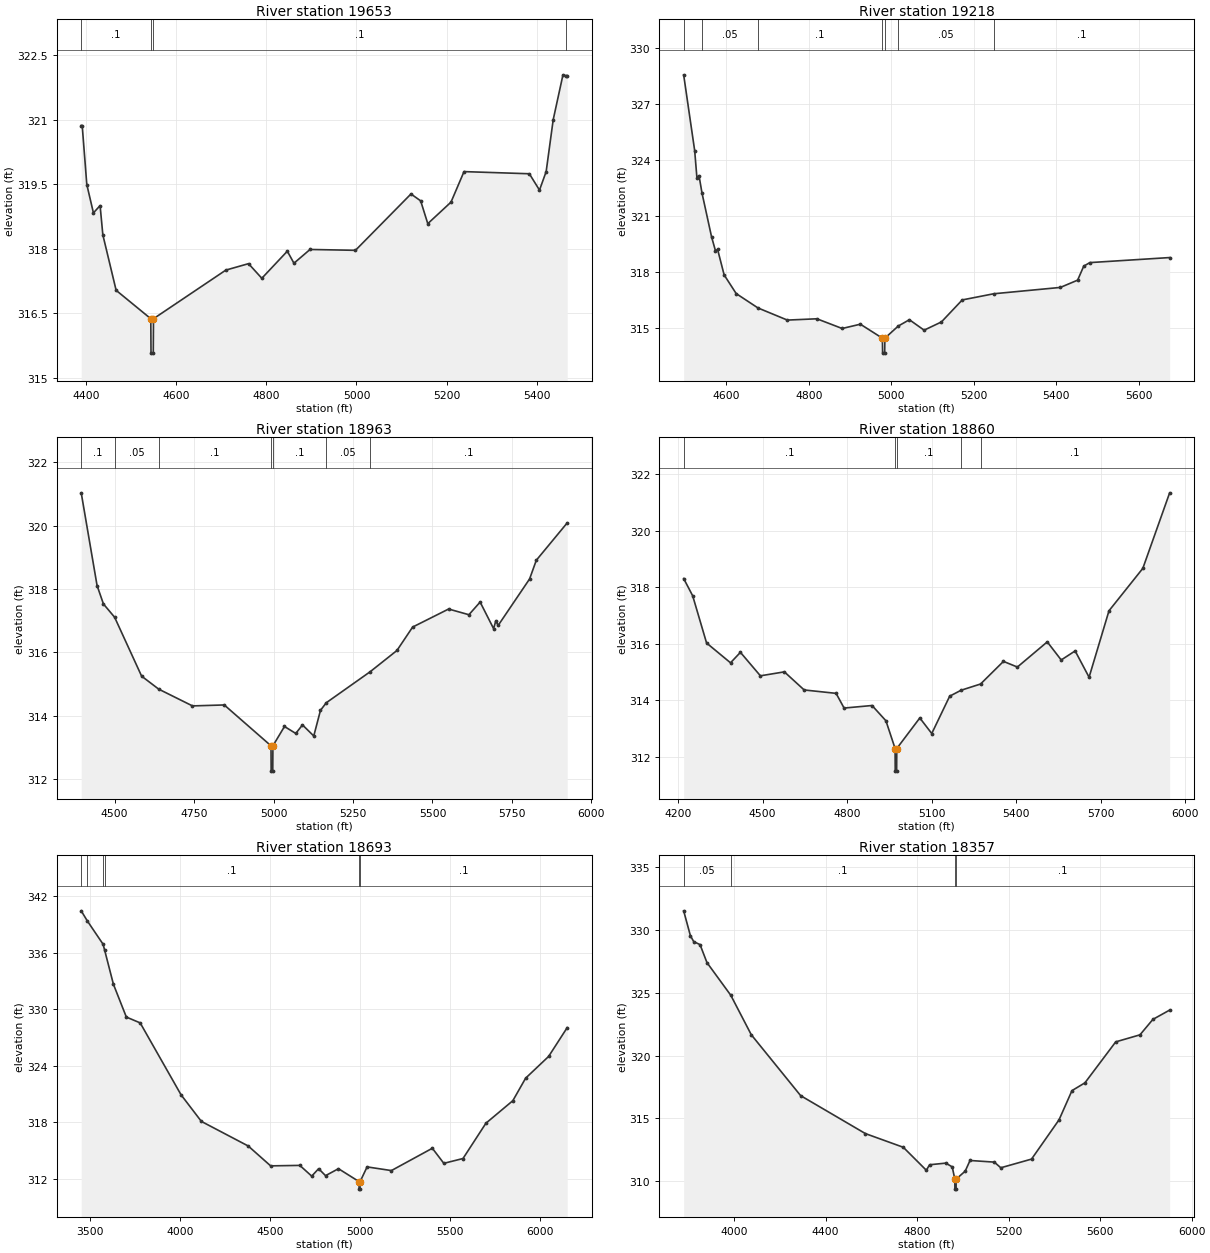
Type RM Length L Ch R = 1 ,19653   ,435,435,435
BEGIN DESCRIPTION:
Mapping XS e9bd132a
END DESCRIPTION:
XS GIS Cut Line= 3
      2101525.33     13394766.42      2101883.98     13395269.46
       2102114.7     13395668.22
#Sta/Elev= 30
  4389.1  320.86  4391.3  320.86  4401.5  319.49  4416.2  318.83    4431     319
  4437.1  318.32  4466.6  317.03  4543.5  316.37    4544  315.57    4549  315.57
  4549.5  316.37    4710   317.5  4760.4  317.65  4789.9  317.31  4846.5  317.94
  4861.2  317.66  4896.9  317.98  4997.7  317.96  5120.9  319.27  5142.4  319.11
  5158.2  318.58  5209.7  319.08  5238.6  319.79  5383.6  319.74  5406.1  319.36
  5420.9  319.79  5436.6     321  5458.2  322.04  5464.8  322.02  5467.6  322.02
#Mann= 4 ,-1 , 0
  4389.1      .1       0  4543.5     .07       0  4549.5      .1       0
  5464.8     .05       0
Bank Sta=4543.5,4549.5
XS Rating Curve= 0 ,0
Exp/Cntr=0.3,0.1

Type RM Length L Ch R = 1 ,19218   ,255,255,255
BEGIN DESCRIPTION:
Mapping XS 9918ac7a
END DESCRIPTION:
XS GIS Cut Line= 3
      2101363.43     13394758.91      2101462.54     13395236.82
      2101859.56     13395800.69
#Sta/Elev= 30
    4497  328.56  4523.7   324.5  4529.1  323.05  4534.2  323.16  4541.5  322.22
  4564.5  319.89  4574.1  319.13  4579.2  319.21  4595.1  317.84  4624.3  316.84
  4677.1  316.07  4748.3  315.42  4819.8  315.49  4881.1  314.97  4925.2   315.2
  4978.6  314.45  4979.1  313.65  4984.1  313.65  4984.6  314.45    5017   315.1
    5044  315.44  5079.7  314.88  5121.6  315.32  5172.1   316.5  5248.3  316.83
  5409.9  317.17  5451.7  317.56  5466.5  318.31  5481.3   318.5  5674.7  318.77
#Mann= 7 ,-1 , 0
    4497      .1       0  4541.5     .05       0  4677.1      .1       0
  4978.6     .07       0  4984.6      .1       0    5017     .05       0
  5248.3      .1       0
Bank Sta=4978.6,4984.6
XS Rating Curve= 0 ,0
Exp/Cntr=0.3,0.1

Type RM Length L Ch R = 1 ,18963   ,103,103,103
BEGIN DESCRIPTION:
Mapping XS a9b3cc6d
END DESCRIPTION:
XS GIS Cut Line= 3
      2101247.36     13394755.05      2101254.36     13395367.58
      2101890.22     13396027.12
#Sta/Elev= 30
  4395.1  321.04    4445  318.11    4465  317.53  4500.2  317.11  4585.1  315.25
  4638.8  314.84  4745.1  314.31  4845.1  314.34  4992.1  313.05  4992.6  312.25
  4997.6  312.25  4998.1  313.05  5034.5  313.66    5070  313.44  5091.1  313.71
  5126.6  313.36  5147.7  314.17    5166  314.41  5304.1  315.39  5388.2  316.06
  5437.6   316.8  5550.8  317.37  5614.6  317.19  5649.9  317.59  5692.3  316.75
  5699.3     317  5706.5  316.85  5805.5  318.32  5826.6  318.91  5923.8  320.09
#Mann= 7 ,-1 , 0
  4395.1      .1       0  4500.2     .05       0  4638.8      .1       0
  4992.1     .07       0  4998.1      .1       0    5166     .05       0
  5304.1      .1       0
Bank Sta=4992.1,4998.1
XS Rating Curve= 0 ,0
Exp/Cntr=0.3,0.1

Type RM Length L Ch R = 1 ,18860   ,167,167,167
BEGIN DESCRIPTION:
Mapping XS 7106e410
END DESCRIPTION:
XS GIS Cut Line= 3
      2100645.23     13394849.79      2101180.81     13395433.08
      2101838.26     13396096.37
#Sta/Elev= 30
  4219.7  318.31  4251.7   317.7  4301.1  316.03  4386.1  315.33  4421.3   315.7
  4492.2  314.87  4577.3  315.01  4647.6  314.37    4761  314.25  4789.4  313.73
  4888.7  313.82    4938  313.28  4970.5   312.3    4971   311.5    4976   311.5
  4976.5   312.3  5058.3  313.38  5100.7  312.83  5164.4  314.15  5204.9  314.36
    5274  314.58  5355.3  315.38  5404.8  315.18  5510.9  316.07  5560.4  315.43
  5609.9  315.75  5659.4  314.82  5730.1  317.17  5850.3  318.67  5945.5  321.34
#Mann= 5 ,-1 , 0
  4219.7      .1       0  4970.5     .07       0  4976.5      .1       0
  5204.9     .05       0    5274      .1       0
Bank Sta=4970.5,4976.5
XS Rating Curve= 0 ,0
Exp/Cntr=0.3,0.1

Type RM Length L Ch R = 1 ,18693   ,336,336,336
BEGIN DESCRIPTION:
Far Live Oak Creek 39.0
END DESCRIPTION:
XS GIS Cut Line= 3
      2099724.96     13394824.98      2101041.47     13395519.15
      2101960.36     13396305.28
#Sta/Elev= 30
  3451.6  340.44  3484.4   339.4  3573.1  336.89  3581.3  336.29  3630.4  332.64
  3702.1  329.16  3778.9  328.54  4005.6  320.91  4118.6  318.08  4378.6  315.47
    4503  313.36    4665  313.41  4731.1  312.27  4769.4  313.06  4807.8  312.32
  4879.6  313.06  4993.7  311.69  4994.2  310.89  4999.2  310.89  4999.7  311.69
  5038.4  313.25  5173.4  312.86  5400.6  315.23  5464.3  313.63  5570.8  314.14
  5698.1  317.89  5847.4  320.28  5918.4  322.67  6046.1  324.98  6149.2  328.04
#Mann= 6 ,-1 , 0
  3451.6     .05       0  3484.4      .1       0  3573.1     .05       0
  3581.3      .1       0  4993.7     .07       0  4999.7      .1       0
Bank Sta=4993.7,4999.7
XS Rating Curve= 0 ,0
Exp/Cntr=0.3,0.1

Type RM Length L Ch R = 1 ,18357   ,345,345,345
BEGIN DESCRIPTION:
Mapping XS 75db49d5
END DESCRIPTION:
XS GIS Cut Line= 3
      2099838.38     13395021.78      2100702.93     13395592.07
      2101463.03     13396370.39
#Sta/Elev= 30
  3780.2  331.52  3809.7  329.54  3824.1  329.07  3851.8  328.83    3882   327.4
  3986.1   324.8  4075.6  321.66  4291.4  316.81  4574.4  313.79    4740   312.7
  4840.6  310.87  4854.8  311.31  4925.5  311.44  4953.8  311.14    4965  310.17
  4965.5  309.37  4970.5  309.37    4971  310.17  5010.4   310.8  5031.5  311.65
  5137.7  311.52    5166  311.07  5300.3  311.76  5420.6  314.89    5477  317.21
  5533.6  317.83  5668.1  321.09  5774.1  321.65  5830.6  322.88  5903.8  323.62
#Mann= 4 ,-1 , 0
  3780.2     .05       0  3986.1      .1       0    4965     .07       0
    4971      .1       0
Bank Sta=4965,4971
XS Rating Curve= 0 ,0
Exp/Cntr=0.3,0.1

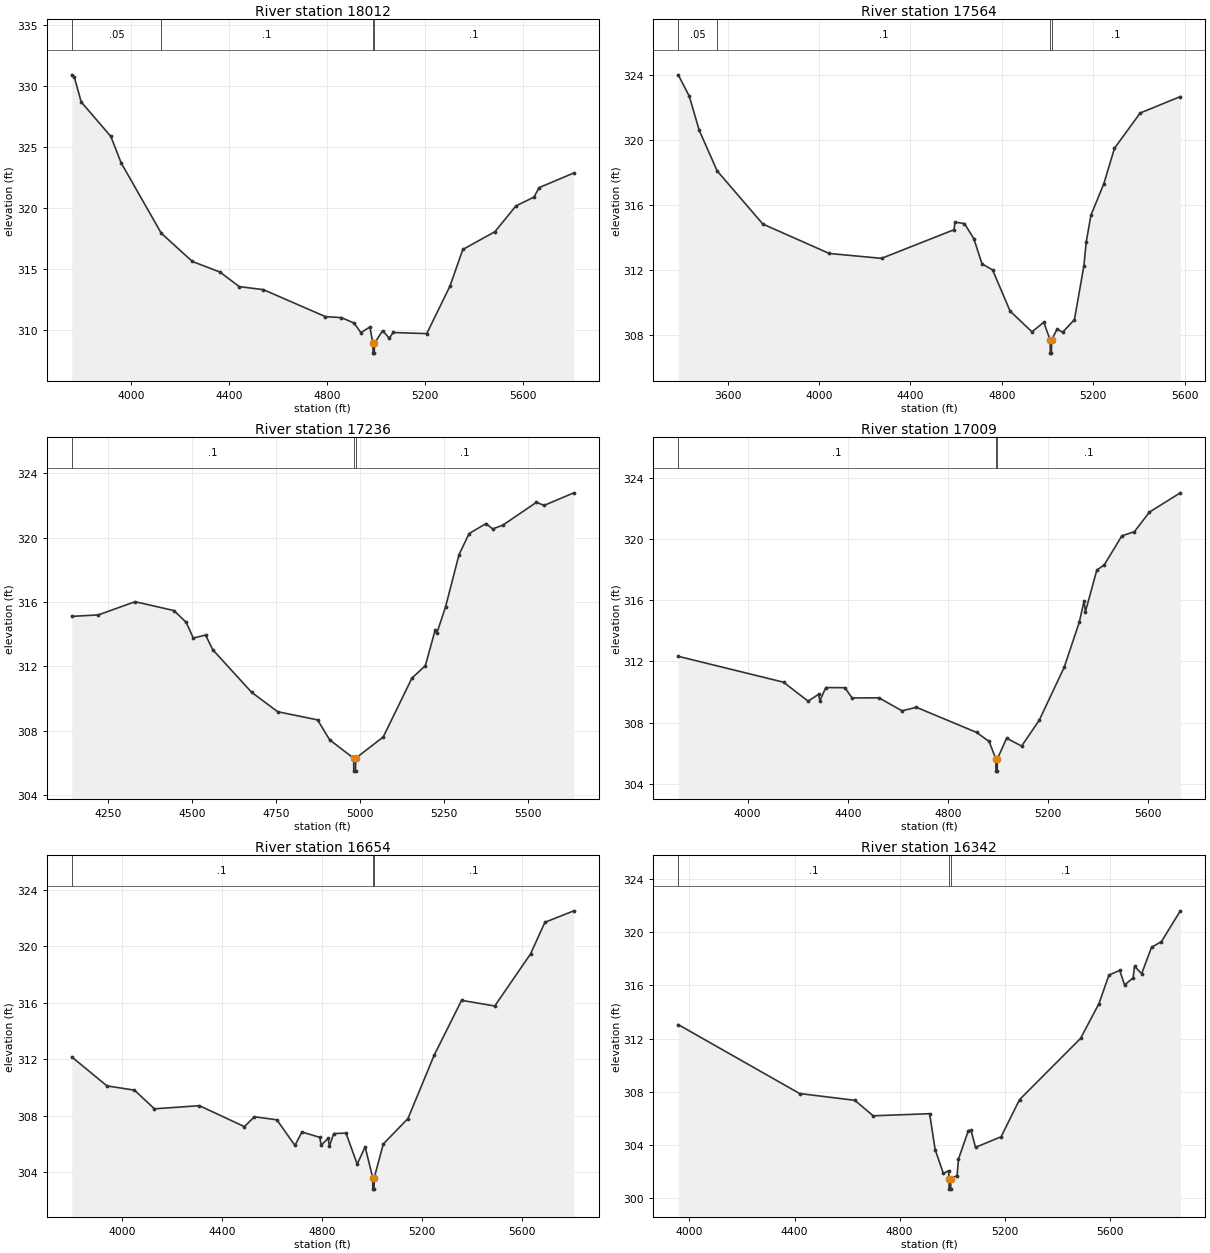
Type RM Length L Ch R = 1 ,18012   ,448,448,448
BEGIN DESCRIPTION:
Mapping XS 14424acd
END DESCRIPTION:
XS GIS Cut Line= 3
      2099778.44     13395146.74      2100356.57     13395784.77
       2101369.6     13396404.57
#Sta/Elev= 30
  3758.9  330.89  3769.7  330.68  3797.4  328.67  3918.4  325.84  3960.3  323.68
  4124.2  317.91  4250.9   315.6  4363.8  314.73  4442.2  313.54  4540.8  313.29
  4793.9  311.08  4859.1     311  4911.1  310.55  4938.5  309.77  4975.2  310.23
  4987.7  308.89  4988.2  308.09  4993.2  308.09  4993.7  308.89  5027.4  309.93
  5054.6  309.31    5070  309.78  5207.4  309.69  5302.2  313.59  5354.4  316.58
  5485.6  318.04  5571.2  320.15  5644.6  320.87    5666  321.65  5807.5  322.85
#Mann= 4 ,-1 , 0
  3758.9     .05       0  4124.2      .1       0  4987.7     .07       0
  4993.7      .1       0
Bank Sta=4987.7,4993.7
XS Rating Curve= 0 ,0
Exp/Cntr=0.3,0.1

Type RM Length L Ch R = 1 ,17564   ,328,328,328
BEGIN DESCRIPTION:
Mapping XS 1bba7443
END DESCRIPTION:
XS GIS Cut Line= 3
      2099551.91     13395420.22       2100182.1     13396248.32
      2101304.45     13396532.16
#Sta/Elev= 30
  3383.1  324.03  3431.3  322.72  3474.9  320.62  3553.5  318.12  3753.5  314.85
  4044.6  313.04  4273.3  312.74  4590.2   314.5  4595.3  314.97  4636.3  314.88
  4677.4  313.95  4713.2   312.4  4759.4  312.03  4836.3  309.49  4932.1  308.22
  4983.7  308.81  5011.6  307.71  5012.1  306.91  5017.2  306.91  5017.7  307.71
  5041.4  308.38  5066.2   308.2  5117.8  308.97  5159.1  312.27  5169.6  313.76
    5190  315.39  5246.5  317.33  5293.1  319.51  5405.5  321.68  5581.4  322.69
#Mann= 4 ,-1 , 0
  3383.1     .05       0  3553.5      .1       0  5011.6     .07       0
  5017.7      .1       0
Bank Sta=5011.6,5017.7
XS Rating Curve= 0 ,0
Exp/Cntr=0.3,0.1

Type RM Length L Ch R = 1 ,17236   ,227,227,227
BEGIN DESCRIPTION:
Mapping XS deeda43f
END DESCRIPTION:
XS GIS Cut Line= 3
      2099942.48      13396378.5       2100437.3     13396688.42
      2101346.14     13396745.71
#Sta/Elev= 30
  4142.1  315.11    4221   315.2  4330.6  316.02  4446.2  315.47  4482.7  314.74
  4503.9  313.76  4540.4  313.95  4561.7  313.04  4677.2   310.4  4754.9  309.19
    4874  308.68  4909.5  307.45  4981.1   306.3  4981.6   305.5  4986.7   305.5
  4987.2   306.3  5069.2  307.62  5154.5  311.27  5194.6  312.05  5223.8  314.26
  5228.8  314.07  5254.7   315.7  5294.8  318.94  5324.8  320.25  5374.9  320.87
    5395  320.54    5425  320.77  5525.2  322.19  5548.1     322  5636.6  322.78
#Mann= 3 ,-1 , 0
  4142.1      .1       0  4981.1     .07       0  4987.2      .1       0
Bank Sta=4981.1,4987.2
XS Rating Curve= 0 ,0
Exp/Cntr=0.3,0.1

Type RM Length L Ch R = 1 ,17009   ,355,355,355
BEGIN DESCRIPTION:
Mapping XS fea15998
END DESCRIPTION:
XS GIS Cut Line= 3
      2099408.65     13396537.37      2100257.62     13396901.96
      2101338.34     13396868.11
#Sta/Elev= 30
  3722.7  312.33  4143.2  310.64  4241.4   309.4    4283  309.85  4288.5  309.43
    4312  310.29  4388.1  310.28  4417.1  309.61  4524.1  309.62  4616.5  308.77
    4674     309  4914.2  307.36  4964.2  306.77  4991.1  305.63  4991.6  304.83
  4996.7  304.83  4997.2  305.63  5034.2  306.98  5094.2  306.47  5164.3  308.15
  5264.3  311.62  5324.4  314.56  5343.7  315.96  5348.7  315.23  5394.4  317.96
  5424.4  318.31  5494.4   320.2  5544.5  320.47  5604.5  321.75  5727.9  323.01
#Mann= 3 ,-1 , 0
  3722.7      .1       0  4991.1     .07       0  4997.2      .1       0
Bank Sta=4991.1,4997.2
XS Rating Curve= 0 ,0
Exp/Cntr=0.3,0.1

Type RM Length L Ch R = 1 ,16654   ,312,312,312
BEGIN DESCRIPTION:
Mapping XS 05aebf37
END DESCRIPTION:
XS GIS Cut Line= 3
      2099484.22     13397311.68      2100352.23     13397316.02
      2101445.99      13396990.5
#Sta/Elev= 30
  3799.6  312.17  3940.4  310.12  4050.4  309.82  4130.4   308.5  4310.4  308.72
  4490.4  307.24  4530.4  307.94  4620.4  307.72  4692.7  305.91  4720.6  306.86
  4792.2  306.48  4797.4  305.92  4825.4  306.42  4830.6  305.86  4847.9  306.75
    4897  306.78  4941.8  304.59  4973.7  305.81  5003.9  303.62  5004.4  302.82
  5009.5  302.82    5010  303.62  5046.1  306.01  5144.9  307.81  5249.6  312.28
  5359.6  316.17  5492.3  315.77  5635.4  319.45    5693  321.69  5808.8   322.5
#Mann= 3 ,-1 , 0
  3799.6      .1       0  5003.9     .07       0    5010      .1       0
Bank Sta=5003.9,5010
XS Rating Curve= 0 ,0
Exp/Cntr=0.3,0.1

Type RM Length L Ch R = 1 ,16342   ,469,469,469
BEGIN DESCRIPTION:
Mapping XS d9b74268
END DESCRIPTION:
XS GIS Cut Line= 3
      2099753.26     13397533.04      2100603.97     13397524.36
      2101615.24     13397207.52
#Sta/Elev= 30
  3957.4  313.05  4419.2  307.85  4629.2  307.34  4699.2  306.17    4914  306.33
    4935  303.62  4966.4  301.82  4986.1  302.03  4987.8  301.44  4988.3  300.64
  4994.2  300.64  4994.7  301.44  5018.5  301.66  5023.7   302.9  5061.4  305.06
  5071.2   305.1  5088.6  303.79    5186  304.59  5256.1  307.39  5488.4  312.01
  5558.5  314.64  5596.2  316.78  5637.1  317.14  5655.9  316.04  5688.3  316.57
  5693.6  317.45  5720.8  316.89  5758.4  318.88  5796.1  319.31  5867.9  321.63
#Mann= 3 ,-1 , 0
  3957.4      .1       0  4987.8     .07       0  4994.7      .1       0
Bank Sta=4987.8,4994.7
XS Rating Curve= 0 ,0
Exp/Cntr=0.3,0.1

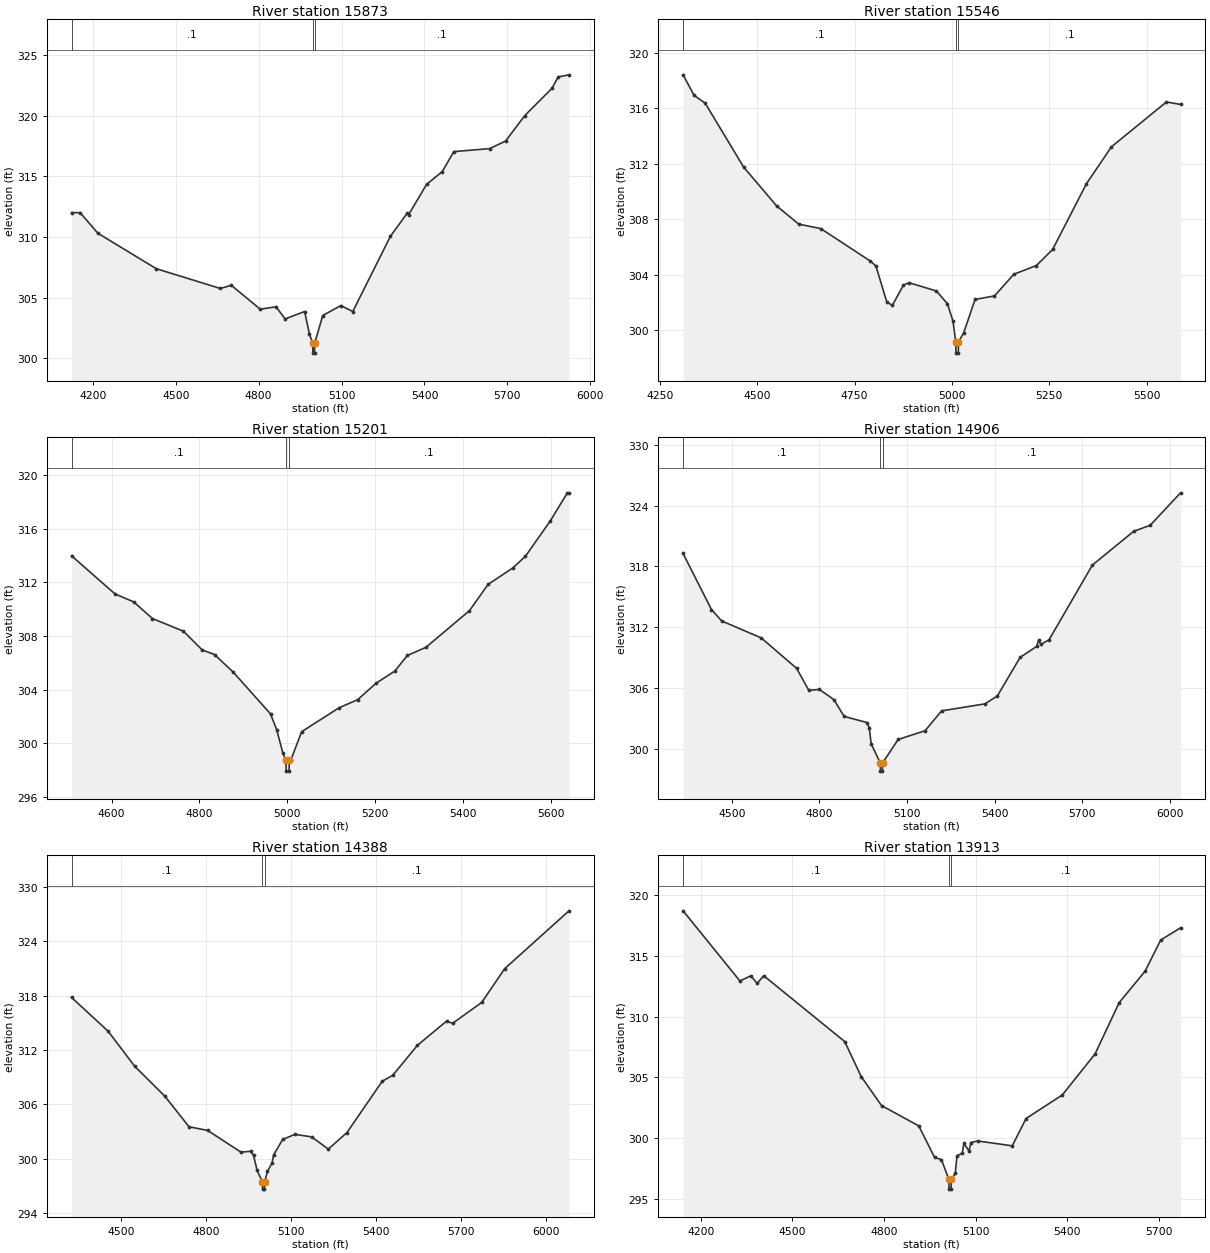
Type RM Length L Ch R = 1 ,15873   ,327,327,327
BEGIN DESCRIPTION:
Mapping XS 7d478931
END DESCRIPTION:
XS GIS Cut Line= 4
      2099991.95     13397732.68      2100495.46     13397845.54
      2101359.18     13397580.78      2101706.36     13397424.55
#Sta/Elev= 30
  4122.8  312.01  4153.9  312.01  4218.2  310.31  4429.4  307.39  4661.1  305.76
  4701.1  306.02  4805.7  304.05  4862.8  304.25  4895.6  303.25  4966.3  303.86
  4983.5  302.02  4995.6  301.23  4996.1  300.43    5002  300.43  5002.5  301.23
  5031.8  303.53  5097.3  304.35  5140.5  303.86  5276.7  310.06    5337  311.95
  5342.2  311.83  5407.7  314.34  5464.6   315.4    5506  317.04  5636.2  317.29
  5693.5  317.91  5762.9  320.01    5861  322.25  5884.1   323.2  5922.9  323.37
#Mann= 3 ,-1 , 0
  4122.8      .1       0  4995.6     .07       0  5002.5      .1       0
Bank Sta=4995.6,5002.5
XS Rating Curve= 0 ,0
Exp/Cntr=0.3,0.1

Type RM Length L Ch R = 1 ,15546   ,345,345,345
BEGIN DESCRIPTION:
Far Live Oak Creek 32.0
END DESCRIPTION:
XS GIS Cut Line= 3
      2100425.01     13398524.99        2100925.       13398025.
      2101375.02     13397674.98
#Sta/Elev= 30
  4309.7  318.43    4338  316.94  4366.2  316.39  4465.2  311.76  4550.1  308.95
  4606.7  307.64  4663.2  307.32  4790.5  304.97  4804.7  304.62  4832.9     302
  4847.1  301.78  4875.4  303.23  4889.5  303.41  4960.2  302.81  4988.5  301.88
  5002.6  300.64  5009.8  299.12  5010.3  298.32  5016.2  298.32  5016.7  299.12
  5030.4  299.81  5059.3   302.2  5109.1  302.45  5158.9  304.02  5216.8  304.65
  5258.4  305.81  5345.3  310.56  5409.5  313.23  5550.7  316.47  5586.9  316.29
#Mann= 3 ,-1 , 0
  4309.7      .1       0  5009.8     .07       0  5016.7      .1       0
Bank Sta=5009.8,5016.7
XS Rating Curve= 0 ,0
Exp/Cntr=0.3,0.1

Type RM Length L Ch R = 1 ,15201   ,295,295,295
BEGIN DESCRIPTION:
Far Live Oak Creek 31.0
END DESCRIPTION:
XS GIS Cut Line= 3
      2100774.99     13398625.01        2101125.       13398275.
      2101575.01     13397824.99
#Sta/Elev= 30
  4509.1  313.98  4608.1  311.13  4650.5  310.54    4693   309.3  4763.7  308.35
  4806.1  306.96  4834.4  306.61  4876.8   305.3  4961.7  302.18  4975.8  300.99
  4989.9  299.24  4996.8  298.71  4997.4  297.91  5003.8  297.91  5004.4  298.71
  5007.6  298.71  5032.4  300.85  5117.2  302.63  5159.7  303.24  5202.1  304.48
  5244.5  305.38  5272.8  306.54  5315.2  307.15  5414.2  309.89  5456.6  311.85
  5513.2  313.08  5541.5  313.95  5598.1  316.59  5636.9  318.68  5640.5  318.68
#Mann= 3 ,-1 , 0
  4509.1      .1       0  4996.8     .07       0  5004.4      .1       0
Bank Sta=4996.8,5004.4
XS Rating Curve= 0 ,0
Exp/Cntr=0.3,0.1

Type RM Length L Ch R = 1 ,14906   ,518,518,518
BEGIN DESCRIPTION:
Mapping XS 571c3d94
END DESCRIPTION:
XS GIS Cut Line= 3
      2100807.98     13399034.76      2101311.44     13398431.47
      2101966.35     13397789.57
#Sta/Elev= 30
  4333.2  319.27  4430.3  313.74  4465.4  312.62  4600.8  310.95  4721.8  307.95
  4763.5  305.78  4799.9  305.87  4849.4  304.87  4884.5  303.21  4962.6  302.61
  4970.4  302.11  4976.9  300.52  5008.3  298.62  5008.9  297.82  5015.3  297.82
  5015.9  298.62  5069.3  300.94  5161.4   301.8    5218  303.76  5366.5  304.45
  5408.9  305.23  5486.8  309.03  5543.3  310.11  5550.3  310.73  5557.5  310.31
  5585.8  310.76  5734.2  318.13  5875.7  321.46  5932.2  322.05    6036  325.25
#Mann= 3 ,-1 , 0
  4333.2      .1       0  5008.3     .07       0  5015.9      .1       0
Bank Sta=5008.3,5015.9
XS Rating Curve= 0 ,0
Exp/Cntr=0.3,0.1

Type RM Length L Ch R = 1 ,14388   ,475,475,475
BEGIN DESCRIPTION:
Mapping XS ede89324
END DESCRIPTION:
XS GIS Cut Line= 3
      2101194.28     13399256.09      2101467.69      13398887.2
      2102100.71     13397751.24
#Sta/Elev= 30
  4323.4  317.79    4453  314.06    4547  310.19  4653.4   306.9  4738.9  303.53
  4805.1  303.12  4922.5  300.73  4957.1  300.82  4967.4  300.36  4979.7  298.72
  4998.7  297.45  4999.3  296.65  5005.8  296.65  5006.4  297.45  5016.5  298.62
  5032.5  299.52  5038.3  300.42  5070.2  302.13  5113.7  302.69  5173.1  302.41
  5231.6  301.06  5297.7  302.89  5422.3  308.54    5460  309.21  5546.9  312.51
  5649.8  315.17  5671.5  314.94  5774.4  317.24  5855.5  320.96    6083  327.34
#Mann= 3 ,-1 , 0
  4323.4      .1       0  4998.7     .07       0  5006.4      .1       0
Bank Sta=4998.7,5006.4
XS Rating Curve= 0 ,0
Exp/Cntr=0.3,0.1

Type RM Length L Ch R = 1 ,13913   ,394,394,394
BEGIN DESCRIPTION:
Mapping XS 2fc0af1e
END DESCRIPTION:
XS GIS Cut Line= 3
      2101411.27     13399564.28      2101732.44     13399264.81
      2102248.93     13398192.77
#Sta/Elev= 30
  4142.4  318.73  4328.4  312.95    4364  313.37    4385  312.75  4406.5  313.38
  4671.9  307.95  4725.6  305.07  4792.2  302.68  4914.3     301  4965.9  298.41
  4988.5  298.22  5012.8  296.59  5013.5  295.79    5020  295.79  5020.6  296.59
  5033.8  297.08  5039.3  298.55  5056.4  298.73    5062  299.57    5079  298.93
  5084.6  299.63  5107.2  299.76  5220.3  299.36  5265.5  301.61  5384.2  303.55
  5491.5  306.93  5570.7  311.17  5655.6  313.76  5706.4  316.32  5771.5  317.33
#Mann= 3 ,-1 , 0
  4142.4      .1       0  5012.8     .07       0  5020.6      .1       0
Bank Sta=5012.8,5020.6
XS Rating Curve= 0 ,0
Exp/Cntr=0.3,0.1

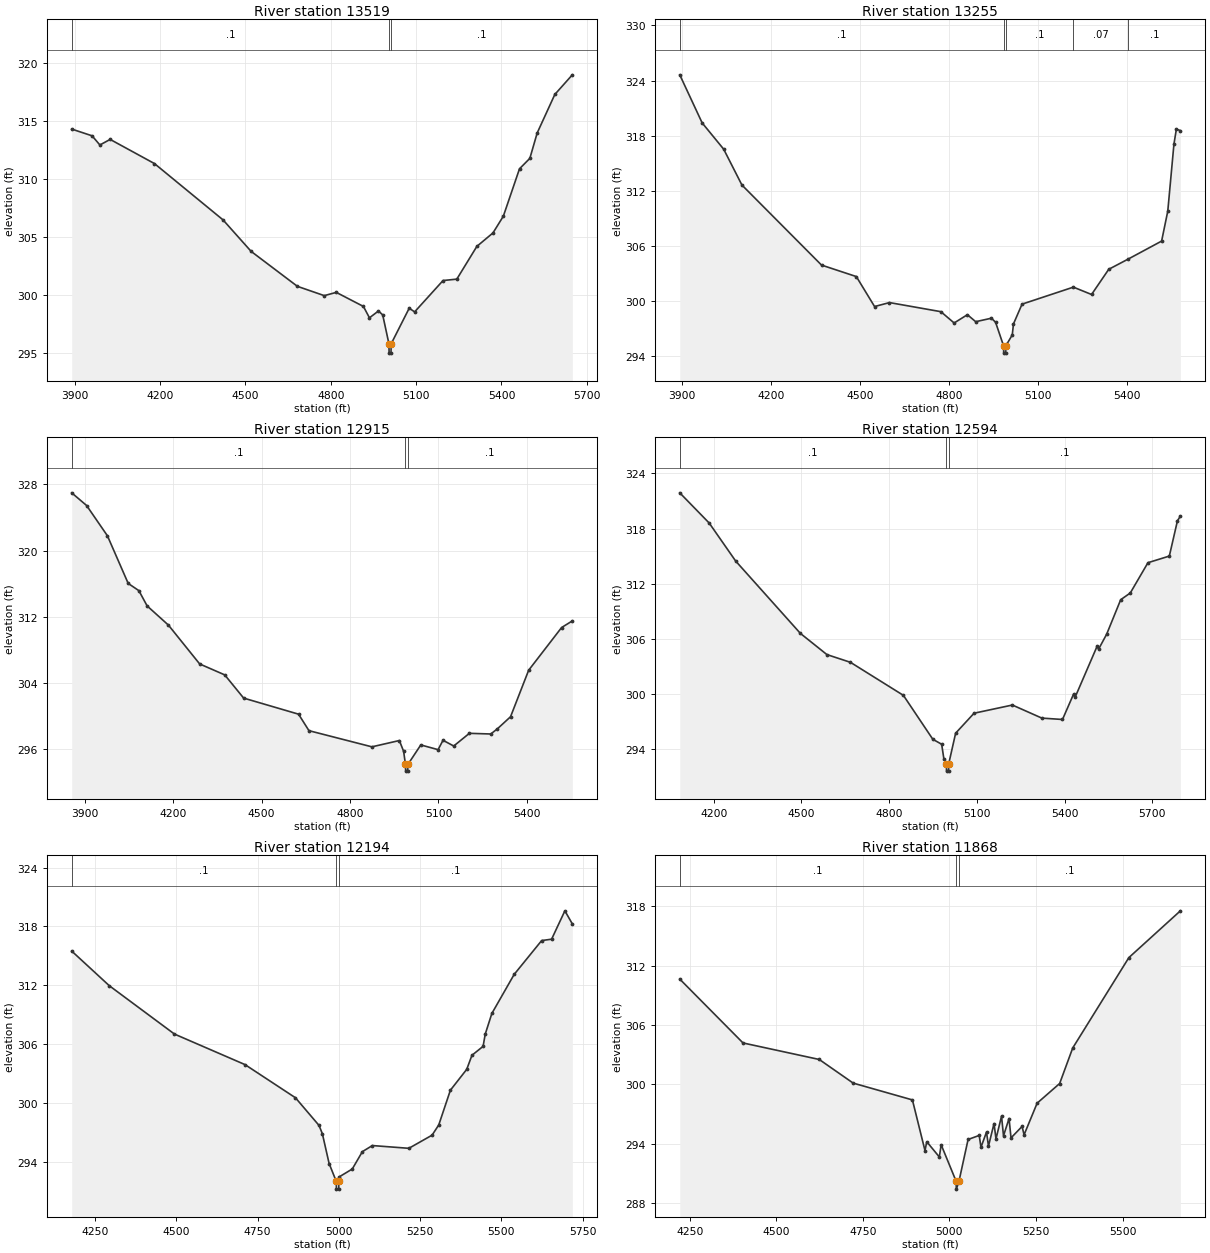
Type RM Length L Ch R = 1 ,13519   ,264,264,264
BEGIN DESCRIPTION:
Mapping XS 24f6a004
END DESCRIPTION:
XS GIS Cut Line= 3
      2101658.66     13399829.05      2102123.07     13399295.19
      2102470.15     13398301.66
#Sta/Elev= 30
  3889.2   314.3  3960.8  313.72  3988.3  312.93  4024.4  313.41  4180.1  311.33
  4421.3  306.48    4520  303.77  4682.7  300.76  4777.1  299.96  4819.4  300.24
  4914.8  299.03    4936  298.05  4967.7  298.64  4982.6   298.3  5004.5  295.81
  5005.1  295.01  5011.7  295.01  5012.3  295.81  5075.8  298.88  5094.8  298.56
  5194.7  301.26  5243.1  301.38  5313.6   304.2  5370.3  305.36  5406.7   306.8
  5463.5  310.88  5499.9  311.78  5525.6  313.96  5587.7  317.28  5649.2  318.97
#Mann= 3 ,-1 , 0
  3889.2      .1       0  5004.5     .07       0  5012.3      .1       0
Bank Sta=5004.5,5012.3
XS Rating Curve= 0 ,0
Exp/Cntr=0.3,0.1

Type RM Length L Ch R = 1 ,13255   ,340,340,340
BEGIN DESCRIPTION:
Far Live Oak Creek 26.0
END DESCRIPTION:
XS GIS Cut Line= 3
        2101975.     13400025.01        2102475.       13399025.
      2102824.98     13398575.02
#Sta/Elev= 30
  3892.2  324.62  3967.7  319.39  4040.3  316.53  4101.8  312.63  4370.2  303.92
  4487.6  302.67  4549.1  299.41  4599.4  299.84  4772.7  298.85  4817.4  297.62
  4862.1  298.52  4890.1  297.76  4943.2  298.14  4957.1   297.7    4984  295.14
  4984.6  294.34  4991.2  294.34  4991.8  295.14  5013.4  296.32  5017.5  297.52
  5046.4  299.67  5219.5  301.52  5280.8  300.72  5338.7  303.46  5404.1  304.57
    5517  306.53  5537.8  309.79  5558.6  317.09  5566.8  318.71  5580.3  318.55
#Mann= 5 ,-1 , 0
  3892.2      .1       0    4984     .07       0  4991.8      .1       0
  5219.5     .07       0  5404.1      .1       0
Bank Sta=4984,4991.8
XS Rating Curve= 0 ,0
Exp/Cntr=0.3,0.1

Type RM Length L Ch R = 1 ,12915   ,321,321,321
BEGIN DESCRIPTION:
Far Live Oak Creek 25.0
END DESCRIPTION:
XS GIS Cut Line= 3
      2102025.03     13400124.97        2102725.       13399225.
      2102975.02     13398724.96
#Sta/Elev= 30
  3855.2  326.96  3905.8  325.43  3976.4  321.78    4047  316.03  4083.2  315.16
  4111.2  313.32  4183.6     311  4289.5  306.32  4374.6     305  4438.8   302.2
  4625.2  300.26  4660.5  298.27  4874.1  296.32  4967.3  297.08  4981.8  295.78
  4988.1  294.19  4988.8  293.39  4995.5  293.39  4996.2  294.19  5040.1  296.55
  5098.8  295.98  5115.5  297.11  5151.9  296.42    5205  297.95  5277.6  297.87
    5300  298.49  5344.7  299.95  5406.2  305.56    5518  310.71  5554.4  311.51
#Mann= 3 ,-1 , 0
  3855.2      .1       0  4988.1     .07       0  4996.2      .1       0
Bank Sta=4988.1,4996.2
XS Rating Curve= 0 ,0
Exp/Cntr=0.3,0.1

Type RM Length L Ch R = 1 ,12594   ,400,400,400
BEGIN DESCRIPTION:
Far Live Oak Creek 24.0
END DESCRIPTION:
XS GIS Cut Line= 3
        2103075.     13400275.02        2102975.       13399375.
        2103075.     13398574.98
#Sta/Elev= 30
  4083.9  321.88  4184.5   318.6  4275.1  314.47  4496.4  306.61    4587  304.31
  4667.5  303.47  4848.6  299.88  4949.2  295.11  4979.4  294.57  4986.9  293.01
  4995.4  292.45  4996.1  291.65  5002.9  291.65  5003.6  292.45  5027.2  295.77
  5090.2  297.94  5221.2  298.83    5322  297.41  5392.6  297.26  5430.4  300.01
  5435.4  299.65    5511  305.22    5516   304.9  5543.7  306.53  5591.6  310.27
  5624.4     311  5684.8  314.29  5757.9  315.01  5785.6  318.84  5795.7  319.35
#Mann= 3 ,-1 , 0
  4083.9      .1       0  4995.4     .07       0  5003.6      .1       0
Bank Sta=4995.4,5003.6
XS Rating Curve= 0 ,0
Exp/Cntr=0.3,0.1

Type RM Length L Ch R = 1 ,12194   ,326,326,326
BEGIN DESCRIPTION:
Mapping XS 2c29acc9
END DESCRIPTION:
XS GIS Cut Line= 3
      2103490.24     13400019.97      2103281.92     13399238.77
      2103134.35     13398522.62
#Sta/Elev= 30
  4178.5  315.49  4294.1  311.96  4494.6  307.03  4711.5  303.92  4866.7  300.54
  4939.2  297.72  4949.5  296.87  4970.2  293.84  4992.1  292.03  4992.8  291.23
  4999.6  291.23  5000.3  292.03  5001.3  292.48  5041.4  293.28  5072.5  295.05
  5103.2  295.67  5215.5  295.39  5286.9  296.73  5307.4  297.77  5343.2  301.31
  5393.5  303.44  5409.5  304.87  5443.8  305.78  5450.3  307.02  5470.7  309.13
  5539.3  313.11  5623.9  316.56  5654.5   316.7  5695.3  319.59  5718.2  318.26
#Mann= 3 ,-1 , 0
  4178.5      .1       0  4992.1     .07       0  5000.3      .1       0
Bank Sta=4992.1,5000.3
XS Rating Curve= 0 ,0
Exp/Cntr=0.3,0.1

Type RM Length L Ch R = 1 ,11868   ,133,133,133
BEGIN DESCRIPTION:
Mapping XS fb6b058e
END DESCRIPTION:
XS GIS Cut Line= 4
       2103643.9     13399897.62      2103625.67     13399418.45
      2103534.53     13399048.66      2103249.02     13398537.34
#Sta/Elev= 30
  4221.1  310.64  4403.8  304.18    4624  302.51    4722  300.12  4893.1  298.42
  4929.4   293.3  4934.6  294.19  4970.9  292.65  4976.1  293.89  5019.3   290.2
    5020   289.4  5027.6   290.2  5053.9  294.42  5086.1  294.83  5091.1  293.63
  5107.1  295.17  5112.8  293.75  5128.8  296.03  5134.5  294.48  5150.5  296.78
  5156.2  294.79  5172.2  296.54  5177.9  294.58  5209.9  295.74  5215.6  294.89
  5253.3  298.09  5318.4  300.08  5356.1  303.67  5518.3  312.81  5667.1  317.54
#Mann= 3 ,-1 , 0
  4221.1      .1       0  5019.3     .07       0  5027.6      .1       0
Bank Sta=5019.3,5027.6
XS Rating Curve= 0 ,0
Exp/Cntr=0.3,0.1

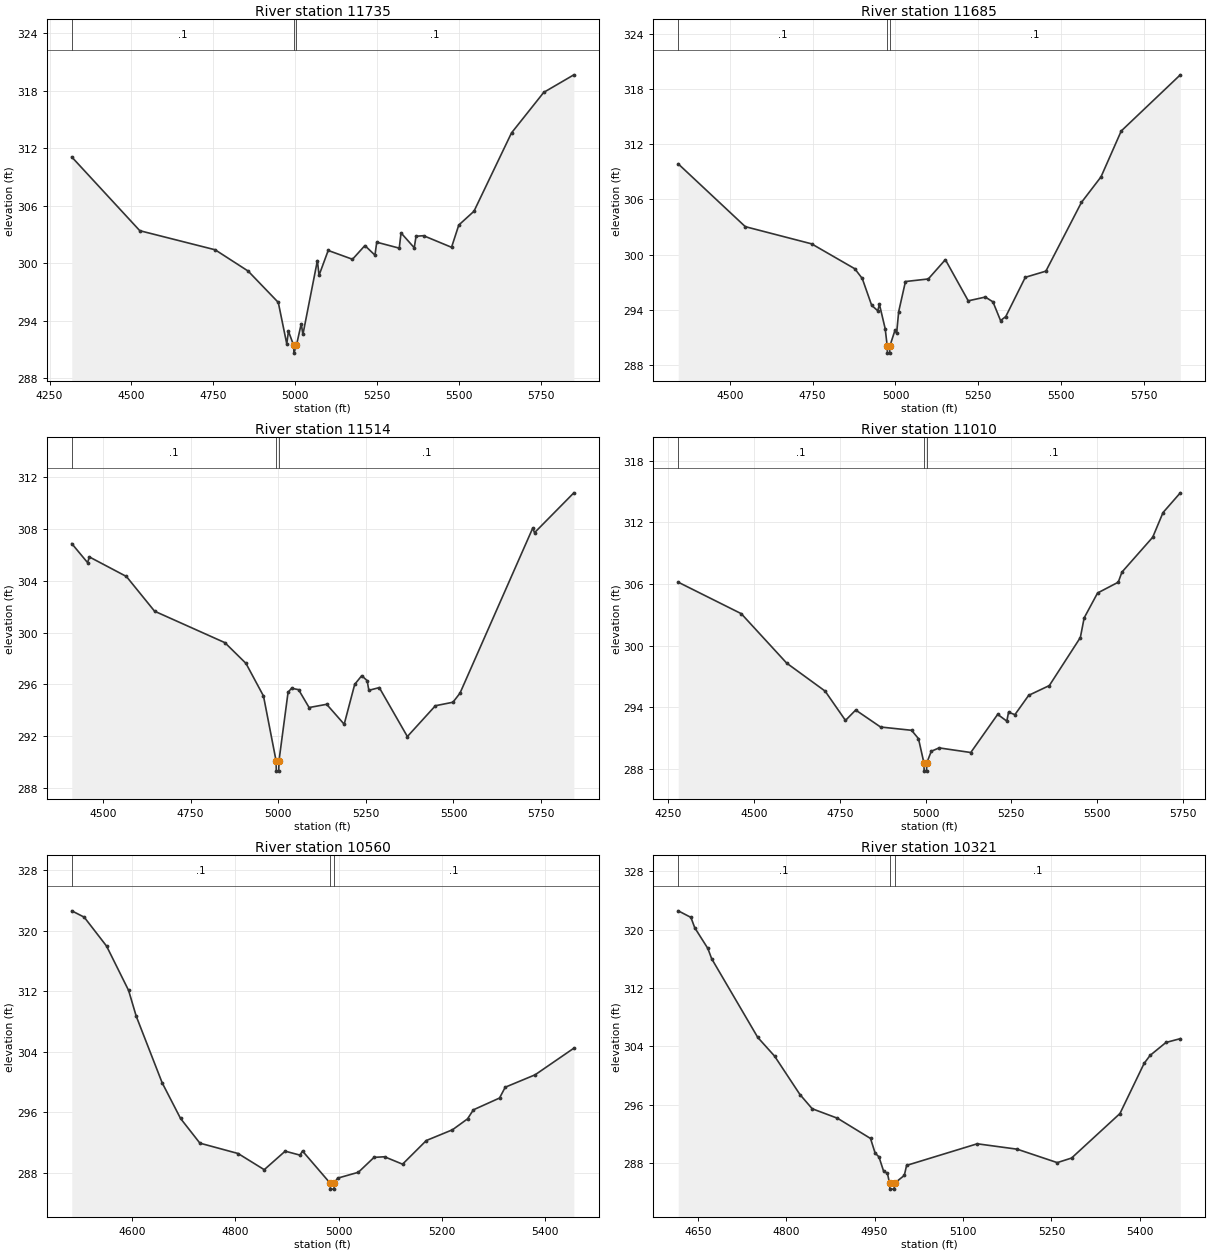
Type RM Length L Ch R = 1 ,11735   ,50,50,50
BEGIN DESCRIPTION:
Mapping XS 7c60827b
END DESCRIPTION:
XS GIS Cut Line= 5
      2103675.15     13399902.79      2103672.55     13399400.22
      2103615.26      13399134.6      2103425.15     13398725.75
      2103310.72     13398439.68
#Sta/Elev= 30
  4317.7  311.09  4525.5   303.4  4755.5  301.41  4856.3  299.19  4948.4  295.92
  4974.3  291.59  4979.4  292.92  4995.4  291.43  4996.1  290.63  5003.7  291.43
  5018.5  293.69  5023.6  292.58  5067.8  300.28  5072.9  298.75  5100.8  301.34
    5175  300.42  5212.9  301.85  5243.6  300.85  5249.1   302.2  5317.8  301.58
  5323.3  303.17  5363.6  301.62  5369.1  302.82    5392  302.88  5477.5  301.67
  5499.6  303.99    5546  305.43  5660.6   313.6  5759.1  317.83    5851  319.66
#Mann= 3 ,-1 , 0
  4317.7      .1       0  4995.4     .07       0  5003.7      .1       0
Bank Sta=4995.4,5003.7
XS Rating Curve= 0 ,0
Exp/Cntr=0.3,0.1

Type RM Length L Ch R = 1 ,11685   ,171,171,171
BEGIN DESCRIPTION:
Mapping XS ca0d6596
END DESCRIPTION:
XS GIS Cut Line= 5
      2103719.42     13399887.19       2103706.4     13399368.97
      2103662.13     13399139.81      2103492.86     13398770.02
      2103360.19     13398439.63
#Sta/Elev= 30
  4344.7  309.87    4547  303.04    4747  301.17  4877.3  298.46  4899.8   297.4
  4928.2  294.48  4946.5  293.89  4951.6  294.59    4969  291.93    4975  290.08
  4975.8  289.28  4982.6  289.28  4983.3  290.08  4998.4  291.75  5003.4  291.43
  5009.7   293.8  5030.1  297.07    5099  297.35  5150.5  299.45  5219.5  294.97
    5271  295.38    5294  294.86    5317  292.82  5332.7  293.26  5391.6  297.53
  5453.7   298.2  5560.8  305.67    5620  308.46    5681  313.45  5859.2  319.56
#Mann= 3 ,-1 , 0
  4344.7      .1       0    4975     .07       0  4983.3      .1       0
Bank Sta=4975,4983.3
XS Rating Curve= 0 ,0
Exp/Cntr=0.3,0.1

Type RM Length L Ch R = 1 ,11514   ,504,504,504
BEGIN DESCRIPTION:
Mapping XS 9ffb046a
END DESCRIPTION:
XS GIS Cut Line= 3
      2103844.42     13399900.25      2103810.57     13399520.02
      2103854.84     13398470.49
#Sta/Elev= 30
  4411.1  306.87  4456.2   305.4  4461.3  305.84    4567  304.33  4647.3  301.65
  4847.9  299.22    4908  297.62    4958   295.1  4993.9   290.1  4994.6   289.3
  5001.4   289.3  5002.2   290.1  5028.1  295.39  5038.1   295.7  5058.1  295.59
  5088.1  294.21  5138.2  294.46  5188.2  292.92  5218.2     296  5238.2  296.67
  5253.6  296.29  5258.6  295.54  5288.3  295.75  5368.4  291.97  5448.4  294.35
  5498.5  294.62  5518.5  295.32  5726.1  308.07  5731.1  307.71  5843.3  310.79
#Mann= 3 ,-1 , 0
  4411.1      .1       0  4993.9     .07       0  5002.2      .1       0
Bank Sta=4993.9,5002.2
XS Rating Curve= 0 ,0
Exp/Cntr=0.3,0.1

Type RM Length L Ch R = 1 ,11010   ,450,450,450
BEGIN DESCRIPTION:
Mapping XS 8bc552db
END DESCRIPTION:
XS GIS Cut Line= 3
      2104073.59     13399965.35      2104167.34     13399483.56
      2104255.88     13398514.82
#Sta/Elev= 30
  4279.2  306.17  4462.9  303.11  4595.4   298.3  4707.4  295.58  4766.7  292.73
  4796.5  293.74    4869  292.09  4959.4  291.77  4979.5  290.96  4995.4   288.6
  4996.1   287.8    5003   287.8  5003.7   288.6  5016.8  289.73  5039.7  290.06
    5132  289.61  5210.4  293.32  5237.1  292.66  5242.1  293.53  5260.6  293.29
  5300.8  295.17    5361  296.12  5451.4  300.79  5462.5   302.7  5501.6  305.12
  5561.9  306.17  5572.6  307.15  5662.3  310.54  5692.4  312.94  5742.8  314.86
#Mann= 3 ,-1 , 0
  4279.2      .1       0  4995.4     .07       0  5003.7      .1       0
Bank Sta=4995.4,5003.7
XS Rating Curve= 0 ,0
Exp/Cntr=0.3,0.1

Type RM Length L Ch R = 1 ,10560   ,239,239,239
BEGIN DESCRIPTION:
Mapping XS 74f68d5e
END DESCRIPTION:
XS GIS Cut Line= 3
       2104774.1     13399759.58      2104630.88     13399561.68
       2104518.9     13398842.94
#Sta/Elev= 30
  4483.5  322.62  4507.6  321.78  4550.9  317.95  4593.5  312.09  4608.2  308.69
  4658.4  299.88    4694  295.16  4731.5  291.89  4805.4  290.52    4856  288.38
  4896.5  290.83  4925.1  290.31  4930.1  290.85  4983.4  286.61  4984.1  285.81
  4991.1  285.81  4991.8  286.61    4998  287.26  5038.2  288.04  5068.5  290.01
  5088.8  290.09  5123.7  289.11  5169.7  292.24  5220.3  293.66  5249.4   295.1
  5260.8   296.3  5311.4  297.86  5322.4  299.29  5380.2  300.93  5455.2  304.45
#Mann= 3 ,-1 , 0
  4483.5      .1       0  4983.4     .07       0  4991.8      .1       0
Bank Sta=4983.4,4991.8
XS Rating Curve= 0 ,0
Exp/Cntr=0.3,0.1

Type RM Length L Ch R = 1 ,10321   ,353,353,353
BEGIN DESCRIPTION:
Far Live Oak Creek 18.0
END DESCRIPTION:
XS GIS Cut Line= 3
      2105075.03     13399575.02        2104775.       13399325.
      2104675.01     13398875.02
#Sta/Elev= 30
    4617  322.56  4638.5  321.66    4645  320.24  4667.2  317.41  4673.7     316
  4751.8  305.23  4780.4  302.66  4823.4   297.4  4844.2  295.45  4887.1  294.15
  4943.1  291.38  4950.9  289.38  4957.4  288.86  4965.2  286.92  4971.8   286.6
  4975.4  285.24  4976.1  284.44  4983.1  284.44  4983.8  285.24  5000.4  286.32
  5004.3  287.69  5124.1  290.65  5191.9  289.91  5259.8  288.07  5284.1   288.7
  5366.1  294.79  5407.1  301.66  5417.3  302.76  5444.2  304.53  5468.5  305.05
#Mann= 3 ,-1 , 0
    4617      .1       0  4975.4     .07       0  4983.8      .1       0
Bank Sta=4975.4,4983.8
XS Rating Curve= 0 ,0
Exp/Cntr=0.3,0.1