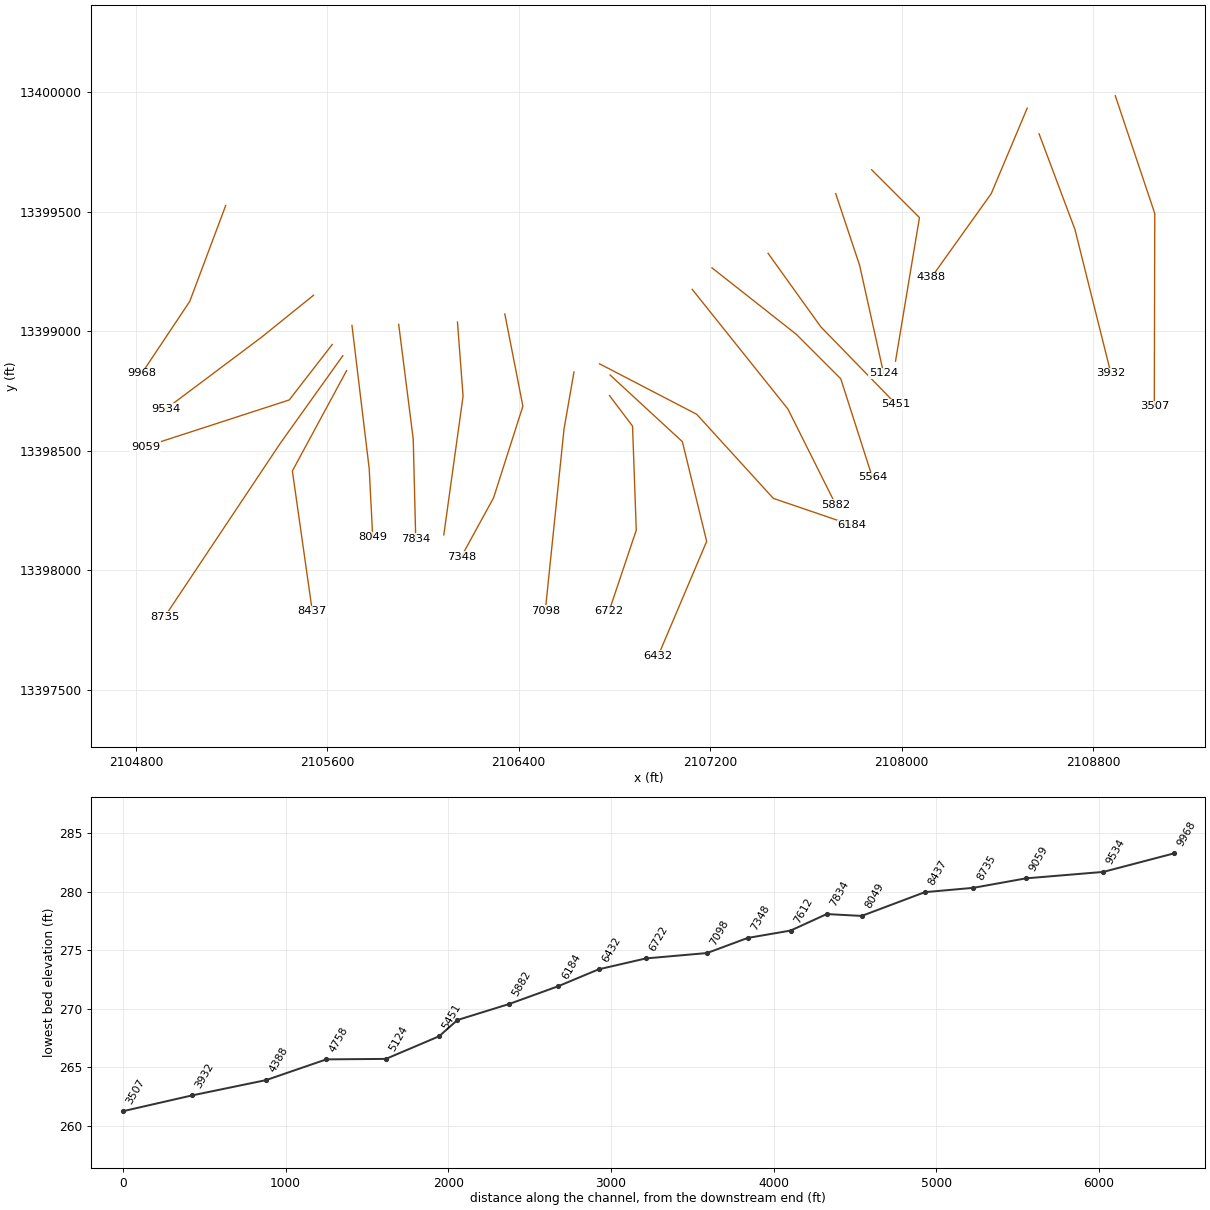
HEC-RAS study Far Live Oak Creek.prj: Far Live Oak Creek Base Level Engineering

--- Far Live Oak Creek.g01 (geometry) --- (continued)

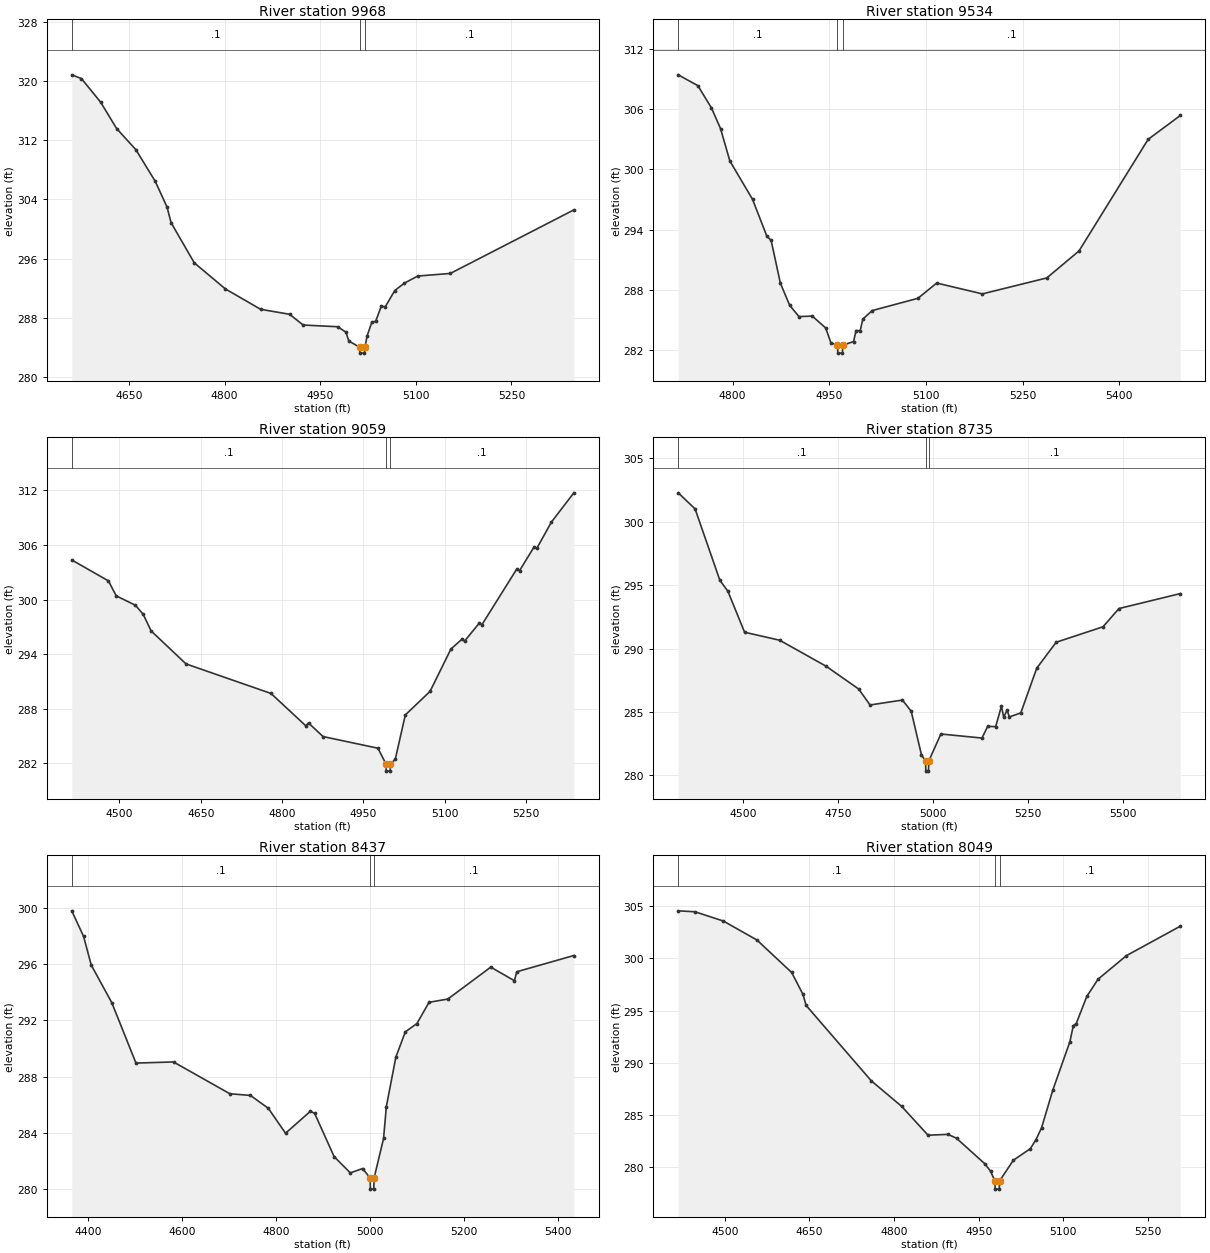
Type RM Length L Ch R = 1 ,9968    ,434,434,434
BEGIN DESCRIPTION:
Far Live Oak Creek 17.0
END DESCRIPTION:
XS GIS Cut Line= 3
      2105175.01     13399525.02        2105025.       13399125.
      2104824.99     13398824.98
#Sta/Elev= 30
  4560.2  320.81  4575.4   320.3  4605.6  317.11  4630.5  313.57  4660.8  310.71
  4691.1  306.46  4709.7  302.97    4716  300.87  4752.5  295.44  4801.4  291.92
  4856.6  289.18    4902  288.51  4923.3  287.06  4977.6  286.83  4990.4  286.09
  4994.9  284.91  5011.7  284.07  5012.5  283.27  5019.5  283.27  5020.2  284.07
  5023.5  285.56    5031  287.44    5037  287.56    5046  289.62    5052  289.51
    5067  291.71  5082.1  292.71  5103.1  293.67  5154.2  294.02    5348  302.59
#Mann= 3 ,-1 , 0
  4560.2      .1       0  5011.7     .07       0  5020.2      .1       0
Bank Sta=5011.7,5020.2
XS Rating Curve= 0 ,0
Exp/Cntr=0.3,0.1

Type RM Length L Ch R = 1 ,9534    ,475,475,475
BEGIN DESCRIPTION:
Far Live Oak Creek 16.0
END DESCRIPTION:
XS GIS Cut Line= 3
      2105542.32     13399150.35        2105325.       13398975.
      2104925.04     13398675.03
#Sta/Elev= 30
  4715.5  309.41    4746  308.33  4766.9  306.13  4781.2  304.05  4795.6  300.83
  4830.8  297.01  4853.2  293.31  4859.6  292.94    4874  288.66  4888.4  286.46
  4902.8  285.33  4923.6  285.38  4944.4  284.19  4952.4  282.72  4962.5  282.49
  4963.2  281.69  4970.2  281.69    4971  282.49  4987.6  282.84  4991.5  283.93
  4997.9  283.93    5002  285.08  5016.6  285.93  5087.5  287.15  5116.6  288.67
  5187.5  287.59  5287.5  289.18  5337.5  291.87  5444.7  302.98  5494.7  305.36
#Mann= 3 ,-1 , 0
  4715.5      .1       0  4962.5     .07       0    4971      .1       0
Bank Sta=4962.5,4971
XS Rating Curve= 0 ,0
Exp/Cntr=0.3,0.1

Type RM Length L Ch R = 1 ,9059    ,324,324,324
BEGIN DESCRIPTION:
Mapping XS 26b98c13
END DESCRIPTION:
XS GIS Cut Line= 3
      2105620.44     13398944.47      2105440.78     13398712.72
       2104839.6     13398517.54
#Sta/Elev= 30
  4412.4  304.36  4479.9  302.06  4494.4  300.41  4529.7  299.38  4544.1  298.38
  4558.6  296.56  4622.9  292.93  4779.6  289.68  4843.6  286.13  4848.8  286.43
  4875.5  284.94  4976.7  283.66  4991.3  281.94  4992.1  281.14  4999.1  281.14
  4999.8  281.94  5008.6  282.44  5027.1  287.32  5072.6   289.9  5111.2  294.57
  5131.2  295.63  5136.5  295.45  5163.2   297.4  5168.4  297.25  5232.4  303.35
  5237.6  303.18  5264.3  305.78  5269.6  305.65  5296.3  308.52  5337.7  311.74
#Mann= 3 ,-1 , 0
  4412.4      .1       0  4991.3     .07       0  4999.8      .1       0
Bank Sta=4991.3,4999.8
XS Rating Curve= 0 ,0
Exp/Cntr=0.3,0.1

Type RM Length L Ch R = 1 ,8735    ,298,298,298
BEGIN DESCRIPTION:
Mapping XS 32f9824c
END DESCRIPTION:
XS GIS Cut Line= 3
      2105664.73     13398897.61      2105404.32     13398533.04
      2104919.97     13397806.51
#Sta/Elev= 30
  4329.3  302.29  4373.7  301.02  4438.8  295.39  4459.7  294.54  4503.9  291.29
  4596.1  290.66  4717.8  288.62  4804.1  286.81  4834.1  285.55  4919.2  285.94
  4942.3  285.06  4969.3  281.62  4980.1  281.13  4980.8  280.33  4987.8  280.33
  4988.6  281.13  5020.4  283.26  5128.6  282.94  5143.6  283.86  5164.6  283.84
  5179.7  285.45  5185.7  284.59  5194.7  285.14  5200.7  284.61  5230.7  284.92
  5272.8  288.46  5323.9   290.5  5447.1  291.72  5489.1  293.16  5650.5  294.34
#Mann= 3 ,-1 , 0
  4329.3      .1       0  4980.1     .07       0  4988.6      .1       0
Bank Sta=4980.1,4988.6
XS Rating Curve= 0 ,0
Exp/Cntr=0.3,0.1

Type RM Length L Ch R = 1 ,8437    ,388,388,388
BEGIN DESCRIPTION:
Mapping XS e635b7ad
END DESCRIPTION:
XS GIS Cut Line= 3
      2105680.38     13398835.16       2105453.8     13398415.85
      2105537.12     13397829.96
#Sta/Elev= 30
  4365.7  299.83  4390.9     298  4407.1  295.96  4450.9  293.27  4502.3  288.96
  4582.2  289.04  4702.1  286.77  4745.9  286.65    4784  285.73  4820.6  283.95
  4873.5  285.52  4882.5  285.37    4924  282.28  4958.4  281.12  4984.6  281.43
  5000.5  280.76  5001.2  279.96  5008.3  279.96  5009.1  280.76  5029.2  283.58
  5035.1  285.85  5055.3  289.38  5075.5  291.19  5100.1  291.78    5126   293.3
  5165.9  293.53  5257.3  295.81  5307.6  294.84  5312.7  295.48  5434.1  296.64
#Mann= 3 ,-1 , 0
  4365.7      .1       0  5000.5     .07       0  5009.1      .1       0
Bank Sta=5000.5,5009.1
XS Rating Curve= 0 ,0
Exp/Cntr=0.3,0.1

Type RM Length L Ch R = 1 ,8049    ,215,215,215
BEGIN DESCRIPTION:
Far Live Oak Creek 13.0
END DESCRIPTION:
XS GIS Cut Line= 3
      2105702.89     13399024.52        2105775.       13398425.
      2105789.68     13398139.52
#Sta/Elev= 30
  4417.5  304.56  4447.2  304.47  4497.6  303.58  4556.9  301.77  4618.5  298.66
  4638.6  296.56  4644.1  295.51  4759.5   288.3  4813.4  285.85  4860.2  283.09
  4895.6  283.17  4910.6   282.8  4960.9  280.35    4971  279.64  4978.4  278.73
  4979.2  277.93  4986.3  277.93  4987.1  278.73  5011.3  280.69  5041.4   281.8
  5051.4  282.66  5061.4  283.81  5081.4  287.43  5111.5  292.03  5117.6  293.57
  5122.6  293.75  5141.5  296.37  5161.5  298.02  5211.6  300.27  5307.2  303.09
#Mann= 3 ,-1 , 0
  4417.5      .1       0  4978.4     .07       0  4987.1      .1       0
Bank Sta=4978.4,4987.1
XS Rating Curve= 0 ,0
Exp/Cntr=0.3,0.1

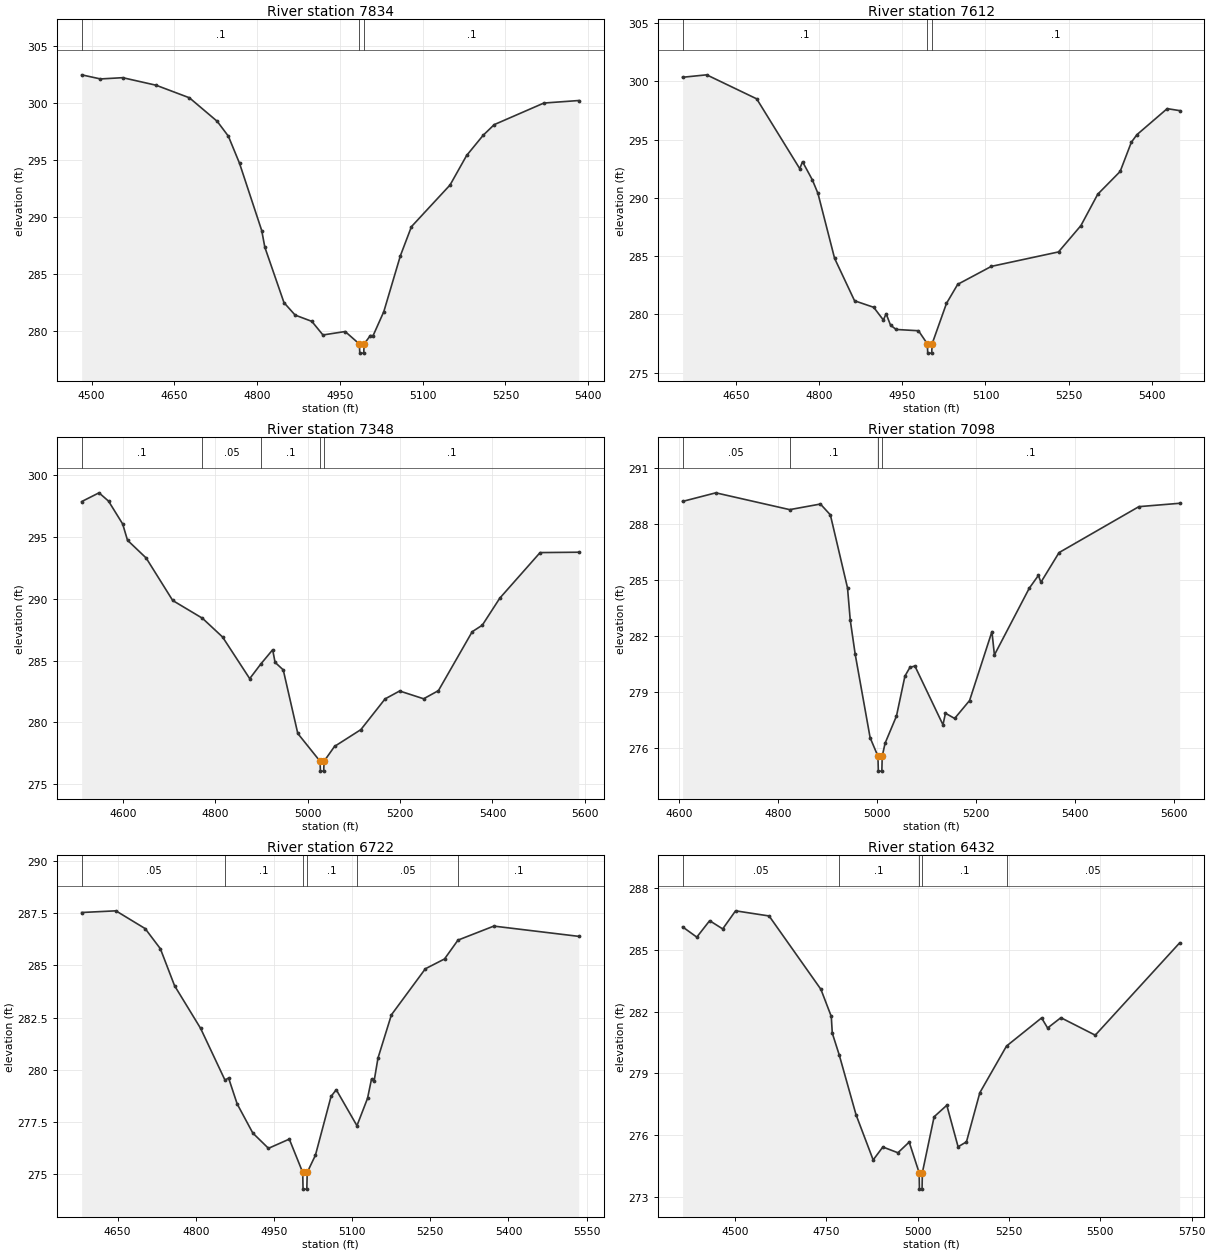
Type RM Length L Ch R = 1 ,7834    ,222,222,222
BEGIN DESCRIPTION:
Far Live Oak Creek 12.0
END DESCRIPTION:
XS GIS Cut Line= 3
      2105898.21     13399028.79      2105959.01     13398548.66
      2105969.42     13398131.96
#Sta/Elev= 30
  4481.9  302.45    4516  302.09  4556.3   302.2  4616.8  301.54  4677.2  300.44
  4727.6  298.38  4747.8  297.08    4768  294.71  4808.3  288.81  4813.9  287.36
  4848.6  282.51  4868.8  281.42  4899.1  280.87  4919.2  279.68  4959.5  279.98
  4985.2  278.89    4986  278.09  4993.1  278.09  4993.9  278.89  5005.1  279.63
  5010.1  279.62  5029.5  281.72  5059.6  286.62  5079.6  289.16  5149.6  292.81
  5179.6  295.39  5209.6  297.16  5229.6  298.09  5319.6  299.98  5382.7   300.2
#Mann= 3 ,-1 , 0
  4481.9      .1       0  4985.2     .07       0  4993.9      .1       0
Bank Sta=4985.2,4993.9
XS Rating Curve= 0 ,0
Exp/Cntr=0.3,0.1

Type RM Length L Ch R = 1 ,7612    ,264,264,264
BEGIN DESCRIPTION:
Mapping XS 81cabdac
END DESCRIPTION:
XS GIS Cut Line= 3
       2106143.9     13399038.27      2106167.34     13398728.35
      2106086.78     13398148.82
#Sta/Elev= 30
  4554.1  300.34  4597.5  300.55  4687.7  298.49  4765.3   292.5  4770.3   293.1
    4788  291.54  4798.1  290.38  4828.1  284.81  4864.1  281.17  4898.6  280.61
    4916  279.52    4921  280.06  4928.9  279.08    4939  278.71  4979.3   278.6
  4995.2  277.48    4996  276.68  5003.1  276.68  5003.9  277.48  5029.8  280.95
    5050  282.58  5110.6  284.12  5231.7  285.36  5272.1  287.62  5302.4  290.31
  5342.8  292.26    5363  294.77  5373.1  295.42  5427.6  297.65    5450  297.48
#Mann= 3 ,-1 , 0
  4554.1      .1       0  4995.2     .07       0  5003.9      .1       0
Bank Sta=4995.2,5003.9
XS Rating Curve= 0 ,0
Exp/Cntr=0.3,0.1

Type RM Length L Ch R = 1 ,7348    ,250,250,250
BEGIN DESCRIPTION:
Far Live Oak Creek 11.0
END DESCRIPTION:
XS GIS Cut Line= 4
      2106341.82     13399072.11      2106417.34     13398686.68
      2106294.94     13398303.87      2106159.76     13398056.91
#Sta/Elev= 30
  4510.5  297.88  4548.1  298.59  4568.7  297.92  4599.3  296.07  4609.8  294.75
  4650.2  293.31  4707.7  289.87  4772.1  288.43  4815.7  286.91  4874.4  283.54
  4898.3  284.72  4924.1  285.88  4929.3  284.86    4947  284.25  4978.5   279.1
  5026.7  276.85  5027.5  276.05  5034.6  276.05  5035.4  276.85    5058  278.05
    5115  279.41  5167.5   281.9    5199  282.54    5251  281.91    5283  282.57
  5356.1  287.34    5378  287.87  5415.9  290.06  5503.1  293.75  5586.7  293.78
#Mann= 5 ,-1 , 0
  4510.5      .1       0  4772.1     .05       0  4898.3      .1       0
  5026.7     .07       0  5035.4      .1       0
Bank Sta=5026.7,5035.4
XS Rating Curve= 0 ,0
Exp/Cntr=0.3,0.1

Type RM Length L Ch R = 1 ,7098    ,376,376,376
BEGIN DESCRIPTION:
Mapping XS c6e80048
END DESCRIPTION:
XS GIS Cut Line= 3
      2106630.88     13398829.88      2106589.21     13398590.33
      2106511.09      13397832.5
#Sta/Elev= 30
  4607.2   289.2  4674.4  289.66  4823.8  288.76  4885.9  289.06    4906  288.48
  4940.7  284.57  4946.2  282.85  4956.2  281.02  4986.4  276.55  5002.2  275.56
    5003  274.76  5010.1  274.76  5010.9  275.56  5016.6  276.25  5039.7  277.71
  5056.8  279.85  5066.8  280.31  5076.9  280.39  5133.7  277.24  5138.7  277.86
  5157.3  277.58  5187.5  278.54  5232.7  282.23  5237.7  280.98  5308.1  284.55
  5326.7  285.24  5331.7  284.87  5368.4  286.46  5529.8  288.92  5612.2   289.1
#Mann= 4 ,-1 , 0
  4607.2     .05       0  4823.8      .1       0  5002.2     .07       0
  5010.9      .1       0
Bank Sta=5002.2,5010.9
XS Rating Curve= 0 ,0
Exp/Cntr=0.3,0.1

Type RM Length L Ch R = 1 ,6722    ,290,290,290
BEGIN DESCRIPTION:
Mapping XS a678fbc0
END DESCRIPTION:
XS GIS Cut Line= 4
       2106779.3     13398730.97      2106875.67     13398603.35
       2106891.3     13398168.45      2106777.15     13397828.61
#Sta/Elev= 30
  4581.1  287.52  4646.8   287.6    4703  286.75  4732.1  285.79  4759.4  284.02
  4809.4  281.98  4856.1  279.51    4863  279.61  4879.5  278.37  4909.5  276.98
  4939.5  276.25  4979.5  276.69  5005.2   275.1  5005.9   274.3  5013.1   274.3
  5013.9   275.1  5029.6  275.92  5059.6  278.73  5069.6  279.05  5109.3  277.33
  5129.6  278.64  5137.3  279.57  5142.4  279.49  5149.6  280.56  5175.4  282.63
  5240.5  284.83  5277.3   285.3  5303.1   286.2  5371.9  286.87  5534.7  286.38
#Mann= 6 ,-1 , 0
  4581.1     .05       0  4856.1      .1       0  5005.2     .07       0
  5013.9      .1       0  5109.3     .05       0  5303.1      .1       0
Bank Sta=5005.2,5013.9
XS Rating Curve= 0 ,0
Exp/Cntr=0.3,0.1

Type RM Length L Ch R = 1 ,6432    ,248,248,248
BEGIN DESCRIPTION:
Mapping XS f1edd5f8
END DESCRIPTION:
XS GIS Cut Line= 4
      2106781.92     13398816.89      2107084.01     13398538.25
      2107185.57     13398121.58      2106982.43     13397642.39
#Sta/Elev= 30
  4356.9  286.13  4395.8  285.63    4431  286.43  4466.7  286.03  4501.9  286.91
  4593.7  286.66  4735.5  283.09  4763.9  281.77  4766.6  280.96  4785.6   279.9
  4831.6  276.99  4878.5  274.79    4905  275.42  4946.2  275.14  4977.1  275.66
  5004.3  274.17  5005.1  273.37  5012.3  273.37  5013.1  274.17  5045.3  276.89
    5080  277.45  5110.9  275.43  5133.8  275.67  5170.4  278.06  5243.4  280.33
  5339.4   281.7  5355.9  281.21  5392.2  281.71  5486.3  280.86  5717.2  285.35
#Mann= 5 ,-1 , 0
  4356.9     .05       0  4785.6      .1       0  5004.3     .07       0
  5013.1      .1       0  5243.4     .05       0
Bank Sta=5004.3,5013.1
XS Rating Curve= 0 ,0
Exp/Cntr=0.3,0.1

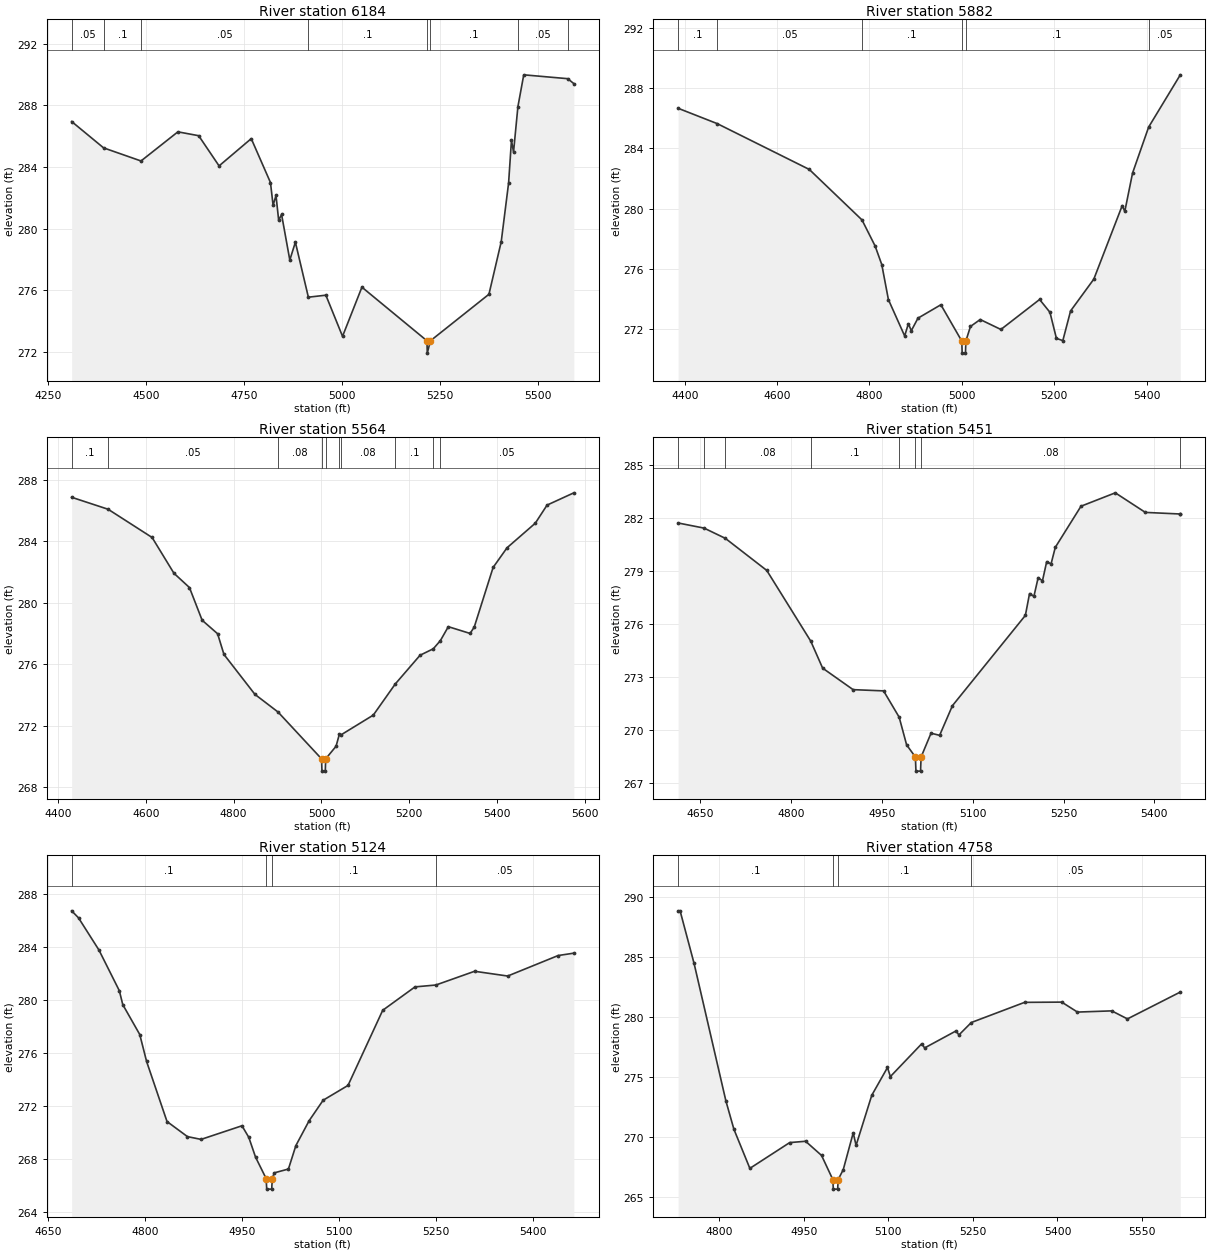
Type RM Length L Ch R = 1 ,6184    ,302,302,302
BEGIN DESCRIPTION:
Mapping XS 242450a9
END DESCRIPTION:
XS GIS Cut Line= 4
      2106737.65     13398863.77       2107143.9     13398652.83
      2107464.21     13398301.27      2107792.38     13398189.27
#Sta/Elev= 30
    4311  286.96  4392.4  285.25  4487.8   284.4  4581.8  286.29  4634.8  286.04
  4686.8  284.08  4768.8  285.85  4817.8     283  4824.5  281.52  4831.9  282.16
  4838.7  280.55  4846.1  280.93  4867.1  277.97  4881.3  279.13  4914.4  275.56
    4959  275.69  5001.5  273.02  5050.9  276.21  5216.7  272.73  5217.5  271.93
  5225.5  272.73  5374.7  275.75    5406  279.16  5424.8  282.97  5432.1  285.74
  5437.4  284.98  5448.5  287.92  5463.4  289.99  5575.5  289.74  5591.1  289.42
#Mann= 8 ,-1 , 0
    4311     .05       0  4392.4      .1       0  4487.8     .05       0
  4914.4      .1       0  5216.7     .07       0  5225.5      .1       0
  5448.5     .05       0  5575.5      .1       0
Bank Sta=5216.7,5225.5
XS Rating Curve= 0 ,0
Exp/Cntr=0.3,0.1

Type RM Length L Ch R = 1 ,5882    ,318,318,318
BEGIN DESCRIPTION:
Far Live Oak Creek 9.0
END DESCRIPTION:
XS GIS Cut Line= 3
      2107125.03     13399174.97        2107525.       13398675.
      2107725.01     13398274.99
#Sta/Elev= 30
  4385.6  286.66  4470.4  285.64  4669.7   282.6  4783.8  279.25  4812.2  277.52
  4826.6  276.29    4841  273.96  4876.2  271.55  4884.2  272.36  4890.6   271.9
    4905  272.73  4954.6  273.62  4999.9  271.21  5000.7  270.41  5007.9  270.41
  5008.7  271.21  5018.7  272.18  5039.8  272.64  5084.6  271.98  5168.4  273.97
  5190.8  273.12  5204.8  271.39  5218.7  271.24  5235.5  273.21  5285.8  275.32
  5347.3   280.2  5352.9  279.82  5369.7  282.36  5404.5  285.41  5473.1  288.88
#Mann= 6 ,-1 , 0
  4385.6      .1       0  4470.4     .05       0  4783.8      .1       0
  4999.9     .07       0  5008.7      .1       0  5404.5     .05       0
Bank Sta=4999.9,5008.7
XS Rating Curve= 0 ,0
Exp/Cntr=0.3,0.1

Type RM Length L Ch R = 1 ,5564    ,113,113,113
BEGIN DESCRIPTION:
Mapping XS c5fe78c7
END DESCRIPTION:
XS GIS Cut Line= 4
      2107207.87      13399264.8      2107560.31     13398987.02
      2107746.07     13398801.26      2107877.97     13398389.95
#Sta/Elev= 30
  4431.2  286.88  4514.2   286.1  4614.4  284.26  4664.1  281.93  4699.4     281
  4728.3  278.87  4763.5  277.99    4778  276.64  4848.5  274.04  4901.1  272.89
  5000.2  269.84  5001.1  269.04  5008.7  269.04  5009.6  269.84  5033.2  270.66
  5040.8  271.45  5044.4   271.4    5118  272.69  5168.1  274.72  5224.5  276.59
  5254.6  277.01  5270.7  277.54  5288.8  278.45  5338.3  278.01  5347.8  278.42
  5390.8  282.31  5422.5  283.59  5486.8  285.19  5513.6  286.37  5574.6  287.17
#Mann= 10 ,-1 , 0
  4431.2      .1       0  4514.2     .05       0  4901.1     .08       0
  5000.2     .07       0  5009.6     .08       0  5040.8     .05       0
  5044.4     .08       0  5168.1      .1       0  5254.6     .08       0
  5270.7     .05       0
Bank Sta=5000.2,5009.6
XS Rating Curve= 0 ,0
Exp/Cntr=0.3,0.1

Type RM Length L Ch R = 1 ,5451    ,327,327,327
BEGIN DESCRIPTION:
Far Live Oak Creek 8.0
END DESCRIPTION:
XS GIS Cut Line= 3
      2107442.27     13399325.54      2107662.74     13399018.27
      2107977.01     13398695.32
#Sta/Elev= 30
  4613.9  281.72  4656.7  281.43  4691.8  280.85  4760.2  279.03  4832.8  275.02
  4852.4  273.49  4902.7  272.27    4953   272.2  4978.7  270.71    4991  269.14
  5005.5  268.45  5006.4  267.65    5014  267.65  5014.9  268.45  5031.3   269.8
  5045.5  269.68  5066.6  271.36    5187  276.48  5193.9  277.72  5201.1  277.56
  5208.1  278.62  5215.2  278.44  5222.2  279.53  5229.4   279.4  5236.4  280.34
  5278.8  282.67  5335.4  283.43    5385  282.32  5442.3  282.23  5442.7  282.23
#Mann= 8 ,-1 , 0
  4613.9     .08       0  4656.7     .05       0  4691.8     .08       0
  4832.8      .1       0  4978.7     .08       0  5005.5     .07       0
  5014.9     .08       0  5442.3     .05       0
Bank Sta=5005.5,5014.9
XS Rating Curve= 0 ,0
Exp/Cntr=0.3,0.1

Type RM Length L Ch R = 1 ,5124    ,366,366,366
BEGIN DESCRIPTION:
Far Live Oak Creek 7.0
END DESCRIPTION:
XS GIS Cut Line= 3
      2107724.99     13399575.03        2107825.       13399275.
      2107924.99     13398825.03
#Sta/Elev= 30
  4686.7  286.76  4697.3  286.23  4728.9   283.8  4760.5  280.72  4765.8  279.67
  4792.1  277.41  4802.7  275.37  4834.3  270.83  4865.9  269.69    4887  269.48
  4950.3  270.51  4960.8  269.64  4971.3  268.14  4987.7  266.52  4988.6  265.72
  4996.3  265.72  4997.2  266.52  5000.3  266.95  5022.2  267.24  5033.7  269.01
  5054.2  270.89  5075.9  272.44  5114.4  273.56  5168.1  279.24  5218.1  281.01
  5250.3  281.15  5310.3  282.19  5361.5  281.83  5439.6  283.38  5463.9  283.56
#Mann= 4 ,-1 , 0
  4686.7      .1       0  4987.7     .07       0  4997.2      .1       0
  5250.3     .05       0
Bank Sta=4987.7,4997.2
XS Rating Curve= 0 ,0
Exp/Cntr=0.3,0.1

Type RM Length L Ch R = 1 ,4758    ,370,370,370
BEGIN DESCRIPTION:
Far Live Oak Creek 6.0
END DESCRIPTION:
XS GIS Cut Line= 3
      2107875.02     13399674.98        2108075.       13399475.
        2107975.     13398874.99
#Sta/Elev= 30
  4726.9  288.88  4730.4  288.88  4755.2   284.5  4811.7  273.03  4825.9  270.67
  4854.2  267.41  4924.9  269.56  4953.1  269.67  4981.4  268.49  5001.4  266.48
  5002.3  265.68    5010  265.68  5010.9  266.48  5019.9   267.3  5037.6  270.37
  5042.7  269.33  5070.5   273.5  5098.4  275.82  5103.5  275.06  5159.2   277.8
  5164.3  277.45  5220.1  278.87  5225.1  278.53  5247.2  279.57  5341.7  281.25
  5407.6  281.27  5435.5  280.44  5496.3  280.54  5524.2  279.87    5618  282.11
#Mann= 4 ,-1 , 0
  4726.9      .1       0  5001.4     .07       0  5010.9      .1       0
  5247.2     .05       0
Bank Sta=5001.4,5010.9
XS Rating Curve= 0 ,0
Exp/Cntr=0.3,0.1

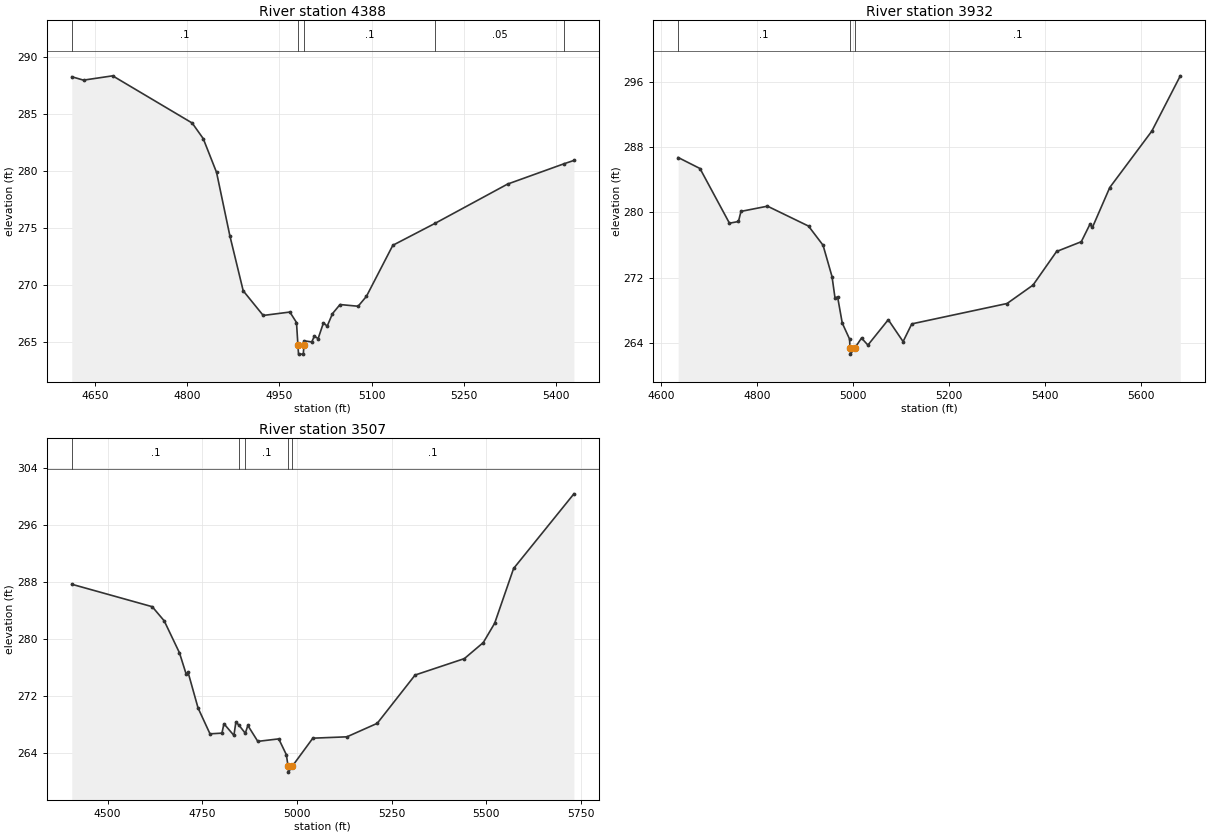
Type RM Length L Ch R = 1 ,4388    ,456,456,456
BEGIN DESCRIPTION:
Far Live Oak Creek 5.0
END DESCRIPTION:
XS GIS Cut Line= 3
      2108525.42     13399932.36        2108375.       13399575.
      2108125.03     13399225.04
#Sta/Elev= 30
  4611.7   288.3  4630.8     288  4678.3  288.38  4807.8  284.23  4825.8  282.86
  4847.5  279.89  4869.2  274.31  4890.9  269.48  4923.5  267.31  4966.9  267.61
  4977.7  266.69    4980  264.71    4981  263.91  4988.8  263.91  4989.8  264.71
  4990.3  265.08  5002.5  264.98  5006.8  265.49  5012.9  265.27  5021.6  266.66
  5027.7  266.37  5036.3  267.47  5048.6  268.27  5078.1  268.12  5091.6  268.99
  5134.6  273.48  5203.4  275.41  5321.4  278.86    5413  280.64  5429.5  280.94
#Mann= 5 ,-1 , 0
  4611.7      .1       0    4980     .07       0  4989.8      .1       0
  5203.4     .05       0    5413      .1       0
Bank Sta=4980,4989.8
XS Rating Curve= 0 ,0
Exp/Cntr=0.3,0.1

Type RM Length L Ch R = 1 ,3932    ,425,425,425
BEGIN DESCRIPTION:
Far Live Oak Creek 4.0
END DESCRIPTION:
XS GIS Cut Line= 3
        2108575.     13399824.99        2108725.       13399425.
      2108875.01     13398824.95
#Sta/Elev= 30
  4636.4  286.72  4681.8  285.37  4743.2  278.66  4761.9  278.87  4767.2  280.11
  4822.4  280.75  4907.8  278.31  4938.1  275.96  4956.8  272.11    4963  269.49
  4968.4  269.62  4978.1  266.41  4993.3  264.45  4994.2   263.4  4995.1   262.6
  5004.8   263.4  5018.2  264.57  5031.5  263.71  5073.9  266.82  5104.8  264.14
  5122.9  266.31  5321.3  268.81  5375.4  271.07  5424.4  275.19  5475.9  276.39
  5493.9  278.53  5499.1  278.15  5535.2  283.04  5622.8  289.96  5682.1  296.74
#Mann= 3 ,-1 , 0
  4636.4      .1       0  4994.2     .07       0  5004.8      .1       0
Bank Sta=4994.2,5004.8
XS Rating Curve= 0 ,0
Exp/Cntr=0.3,0.1

Type RM Length L Ch R = 1 ,3507    ,292,292,292
BEGIN DESCRIPTION:
Far Live Oak Creek 3.0
END DESCRIPTION:
XS GIS Cut Line= 3
      2108893.46     13399984.45      2109058.61     13399492.04
      2109056.66     13398685.81
#Sta/Elev= 30
  4405.5   287.7  4617.9  284.54  4649.5  282.55  4689.7  278.06  4707.3  275.08
  4712.6  275.29  4738.9  270.28  4770.4  266.64  4801.9  266.74  4807.2  268.06
  4833.5  266.42  4838.8   268.3    4847  267.85  4863.6  266.72  4870.3  267.82
  4896.6  265.58  4951.9  265.93  4971.9  263.71  4976.6  262.05  4977.5  261.25
  4987.2  262.05  5041.9  266.03  5131.9  266.22  5211.9  268.12  5311.9  274.92
  5441.9  277.23  5491.9  279.49  5521.9  282.21  5571.9  289.92  5731.1  300.43
#Mann= 5 ,-1 , 0
  4405.5      .1       0    4847     .05       0  4863.6      .1       0
  4976.6     .07       0  4987.2      .1       0
Bank Sta=4976.6,4987.2
XS Rating Curve= 0 ,0
Exp/Cntr=0.3,0.1