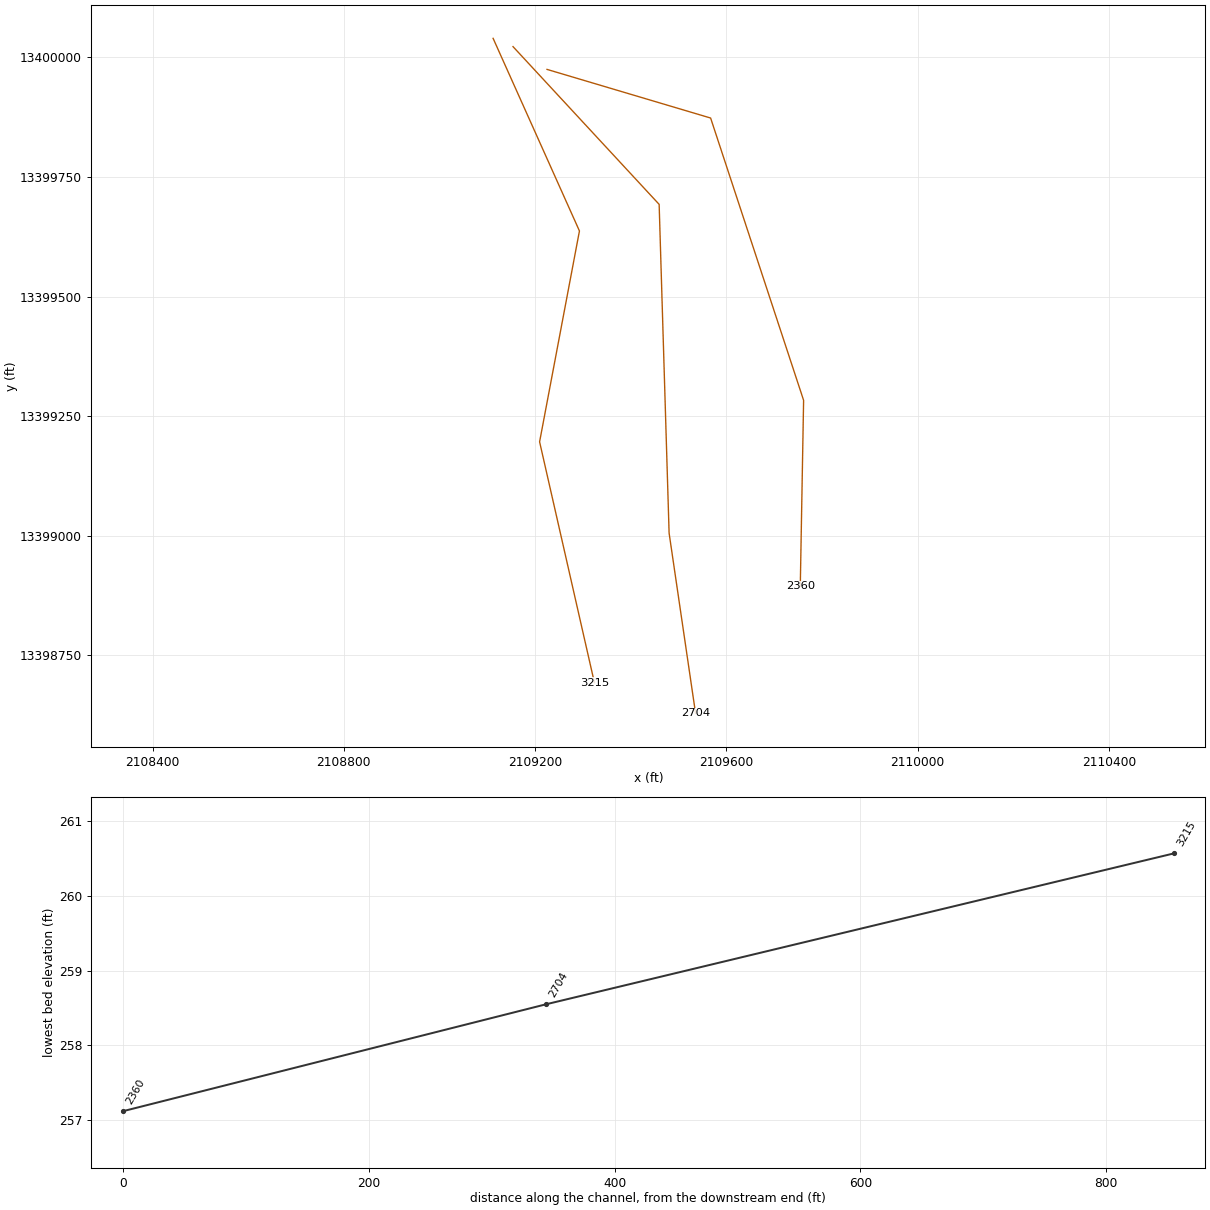
HEC-RAS study Far Live Oak Creek.prj: Far Live Oak Creek Base Level Engineering

--- Far Live Oak Creek.g01 (geometry) --- (continued)

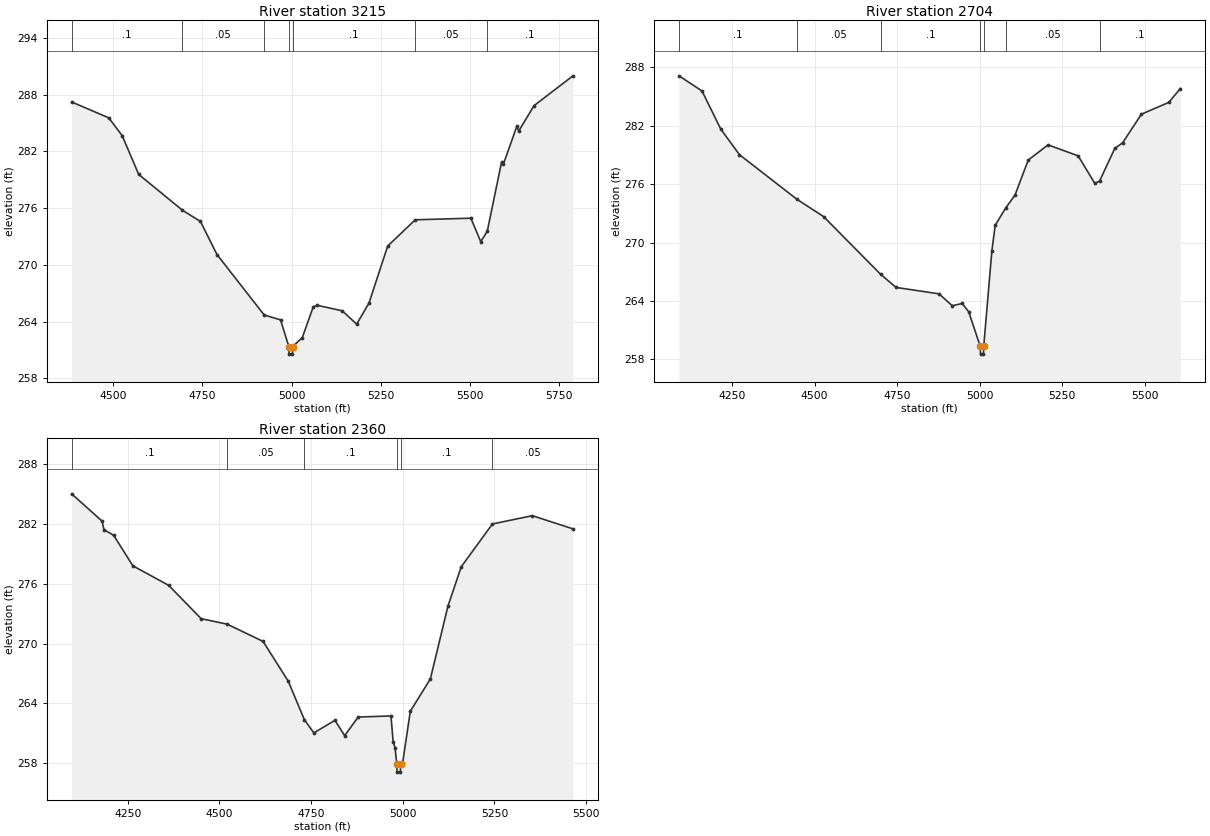
Type RM Length L Ch R = 1 ,3215    ,511,511,511
BEGIN DESCRIPTION:
Mapping XS 2c38fb77
END DESCRIPTION:
XS GIS Cut Line= 4
      2109112.22     13400039.97      2109292.77      13399637.2
      2109209.44     13399196.23      2109324.02     13398692.76
#Sta/Elev= 30
  4382.9  287.23    4487  285.55  4524.7  283.67  4571.1  279.57  4693.8  275.78
  4744.3   274.6  4790.7   271.1  4923.1  264.71    4969  264.19  4992.3  261.37
  4993.2  260.57  5002.1  260.57  5002.9  261.37  5030.1  262.31  5060.6  265.55
  5070.8  265.74    5142  265.15  5182.7  263.74  5217.3  265.98  5269.6  271.99
  5346.9  274.77    5503  274.94  5530.7  272.46    5549  273.56  5589.1  280.87
  5594.2  280.65  5632.1  284.67  5637.2  284.15  5680.3  286.84  5789.4  289.99
#Mann= 7 ,-1 , 0
  4382.9      .1       0  4693.8     .05       0  4923.1      .1       0
  4992.3     .07       0  5002.9      .1       0  5346.9     .05       0
    5549      .1       0
Bank Sta=4992.3,5002.9
XS Rating Curve= 0 ,0
Exp/Cntr=0.3,0.1

Type RM Length L Ch R = 1 ,2704    ,344,344,344
BEGIN DESCRIPTION:
Mapping XS ce65a747
END DESCRIPTION:
XS GIS Cut Line= 4
      2109153.87     13400022.64      2109459.44     13399692.76
      2109480.27     13399005.26       2109535.6     13398628.38
#Sta/Elev= 30
  4089.3  287.13  4159.1  285.57  4215.8  281.66  4272.5  279.03  4446.9  274.44
  4527.1  272.68  4699.8  266.75  4746.8   265.4  4876.9  264.74  4916.9  263.52
  4946.9  263.75  4966.9  262.89  5001.6  259.35  5002.5  258.55  5011.4  258.55
  5012.2  259.35  5036.9  269.16    5047  271.78    5079  273.57    5107  274.89
    5147  278.48    5207  280.04  5298.3  278.91  5348.3   276.1  5362.9  276.31
    5409  279.67  5432.8  280.25  5489.8  283.19  5572.5   284.4  5607.7  285.82
#Mann= 7 ,-1 , 0
  4089.3      .1       0  4446.9     .05       0  4699.8      .1       0
  5001.6     .07       0  5012.2      .1       0    5079     .05       0
  5362.9      .1       0
Bank Sta=5001.6,5012.2
XS Rating Curve= 0 ,0
Exp/Cntr=0.3,0.1

Type RM Length L Ch R = 1 ,2360    ,0,0,0
BEGIN DESCRIPTION:
Far Live Oak Creek 2.0
END DESCRIPTION:
XS GIS Cut Line= 4
      2109224.97     13399975.01      2109567.08     13399873.32
      2109761.52     13399283.04      2109754.58     13398894.18
#Sta/Elev= 30
  4096.9  285.01  4179.9  282.28  4185.1  281.42  4211.7  280.85  4263.8   277.8
  4361.6  275.84  4450.1   272.5  4520.9  271.95  4619.1  270.22  4687.9  266.22
  4731.5  262.39  4757.4  261.05    4815  262.31  4841.5  260.78  4878.5  262.64
  4967.9  262.75  4973.9  260.13  4979.1  259.57  4983.7  257.92  4984.5  257.12
  4993.4  257.12  4994.3  257.92  4999.5  257.99  5020.6  263.22  5075.3  266.46
  5123.3  273.76  5159.5   277.7  5244.6  281.99  5353.4  282.82  5464.2   281.5
#Mann= 6 ,-1 , 0
  4096.9      .1       0  4520.9     .05       0  4731.5      .1       0
  4983.7     .07       0  4994.3      .1       0  5244.6     .05       0
Bank Sta=4983.7,4994.3
XS Rating Curve= 0 ,0
Exp/Cntr=0.3,0.1
LCMann Table=0

Chan Stop Cuts=-1
Use User Specified Reach Order=0
Composite Channel Slope=5