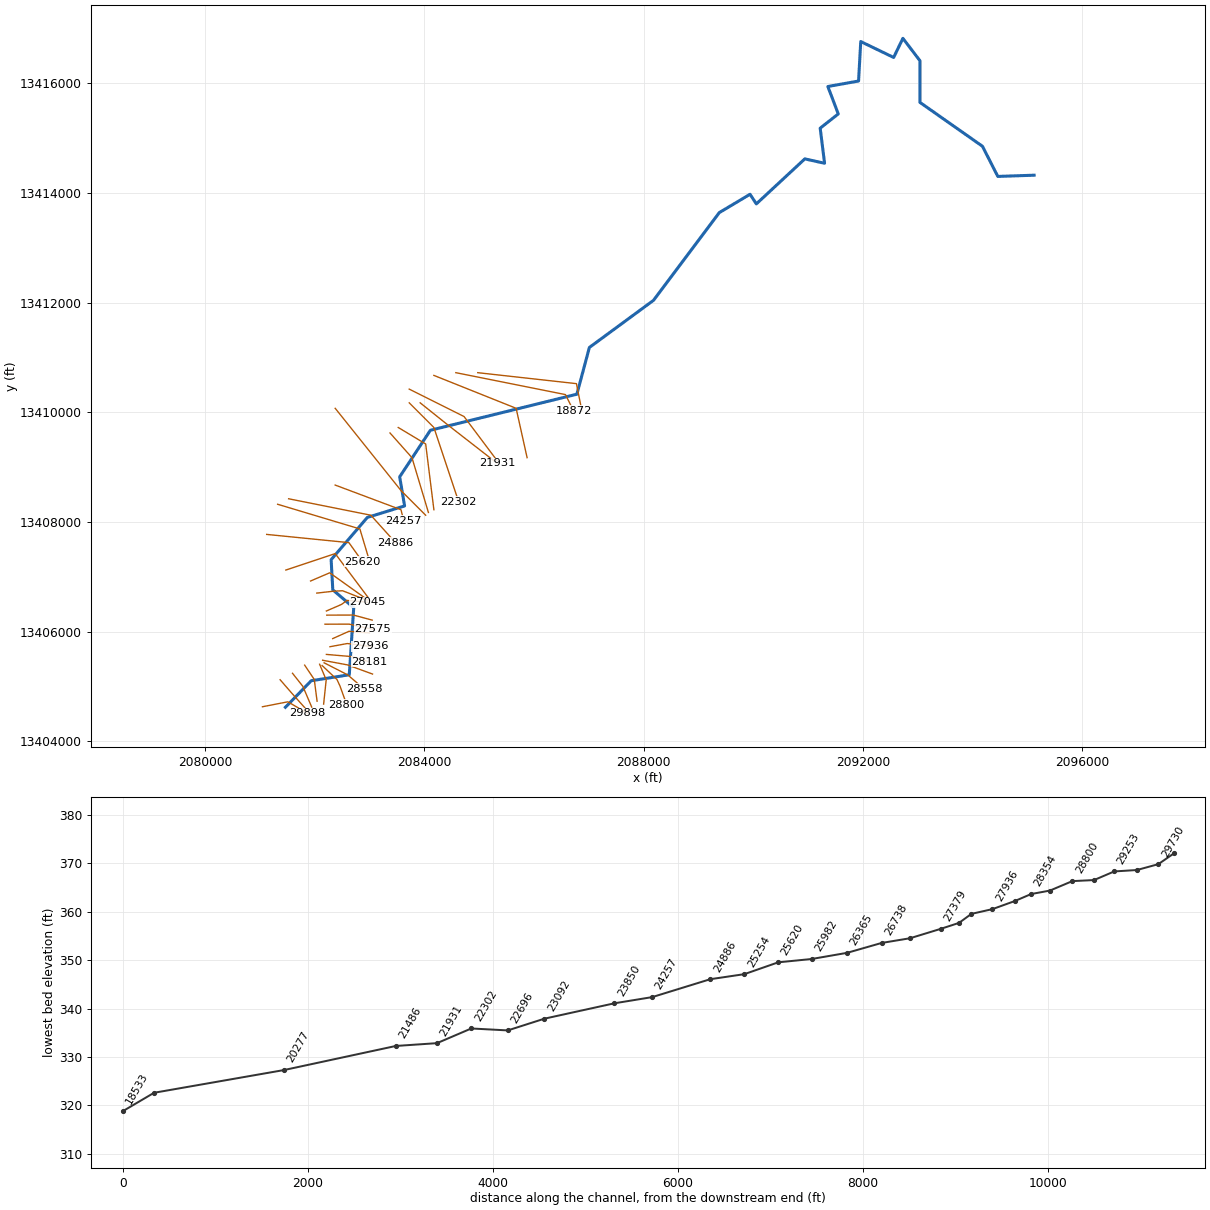
--- Fox Creek.prj (project) ---

Proj Title=Fox Creek Base Level Engineering
Current Plan=p01
Default Exp/Contr=0.3,0.1
English Units
Geom File=g01
Flow File=f01
Plan File=p01
Y Axis Title=Elevation
X Axis Title(PF)=Main Channel Distance
X Axis Title(XS)=Station
BEGIN DESCRIPTION:
Fox Creek
END DESCRIPTION:
DSS Export Rating Curves= 0
DSS Export Rating Curve Sorted= 0
DSS Export Volume Flow Curves= 0
DXF OffsetX= 0
DXF OffsetY= 0
DXF ScaleX= 1
DXF ScaleY= 10

--- Fox Creek.p01 (plan) ---

Plan Title=Multiple Run
Short Identifier=Multiple
Geom File=g01
Flow File=f01
Subcritical Flow
K Sum by GR= 0
Std Step Tol= 0.01
Critical Tol= 0.01
Num of Std Step Trials= 20
Max Error Tol= 0.3
Flow Tol Ratio= 0.001
Split Flow NTrial= 30
Split Flow Tol= 0.02
Split Flow Ratio= 0.02
Log Output Level= 0
Friction Slope Method= 1
Unsteady Friction Slope Method= 2
Unsteady Bridges Friction Slope Method= 1
Parabolic Critical Depth
Global Vel Dist=  1 , 1 , 1
Global Log Level= 0
CheckData=True
Encroach Param= -1, 0, 0, 0
BEGIN DESCRIPTION:
Multiple Run
END DESCRIPTION:

--- Fox Creek.f01 (steady flow) ---

Flow Title=Multiple
Program Version=5.05
Number of Profiles= 7
Profile Names=10-year,25-year,50-year,1pct_min,100-year,1pct_plu,500-year
River Rch & RM=Fox Creek,Reach-1         ,29898
     269     375     464     286     571    1140     878
River Rch & RM=Fox Creek,Reach-1         ,18872
     356     504     630     392     781    1559    1222
River Rch & RM=Fox Creek,Reach-1         ,16423
     415     590     738     460     917    1830    1439
River Rch & RM=Fox Creek,Reach-1         ,5992
     449     640     801     499     996    1987    1564
Boundary for River Rch & Prof#=Fox Creek,Reach-1         , 1
Up Type= 0
Dn Type= 3
Dn Slope=0.005
Boundary for River Rch & Prof#=Fox Creek,Reach-1         , 2
Up Type= 0
Dn Type= 3
Dn Slope=0.005
Boundary for River Rch & Prof#=Fox Creek,Reach-1         , 3
Up Type= 0
Dn Type= 3
Dn Slope=0.005
Boundary for River Rch & Prof#=Fox Creek,Reach-1         , 4
Up Type= 0
Dn Type= 3
Dn Slope=0.005
Boundary for River Rch & Prof#=Fox Creek,Reach-1         , 5
Up Type= 0
Dn Type= 3
Dn Slope=0.005
Boundary for River Rch & Prof#=Fox Creek,Reach-1         , 6
Up Type= 0
Dn Type= 3
Dn Slope=0.005
Boundary for River Rch & Prof#=Fox Creek,Reach-1         , 7
Up Type= 0
Dn Type= 3
Dn Slope=0.005
DSS Import GetInterval= 0
DSS Import GetPeak= 0
DSS Import FillOption= 0

--- Fox Creek.g01 (geometry) ---

Geom Title=Existing Conditions
Program Version=5.05

River Reach=Fox Creek       ,Reach-1
Reach XY= 30
      2081466.79     13404621.97      2081937.93     13405106.15
       2082631.6     13405214.67      2082712.63     13406437.38
       2082330.8     13406764.54       2082300.8     13407314.54
       2082960.8     13408084.54       2083640.8     13408294.54
       2083550.8     13408824.54       2084110.8     13409674.54
        2086783.     13410332.44       2087010.8     13411184.54
       2088180.8     13412044.54       2089380.8     13413644.54
      2089941.29      13413979.3      2090056.39     13413803.26
       2090940.8     13414624.54       2091300.8     13414544.54
       2091220.8     13415184.54       2091550.8     13415444.54
       2091360.8     13415944.54       2091920.8     13416044.54
       2091960.8     13416764.54       2092560.8     13416474.54
      2092729.64     13416823.31       2093040.8     13416414.54
       2093040.8     13415654.54       2094180.8     13414854.54
       2094460.8     13414304.54      2095123.13     13414326.87

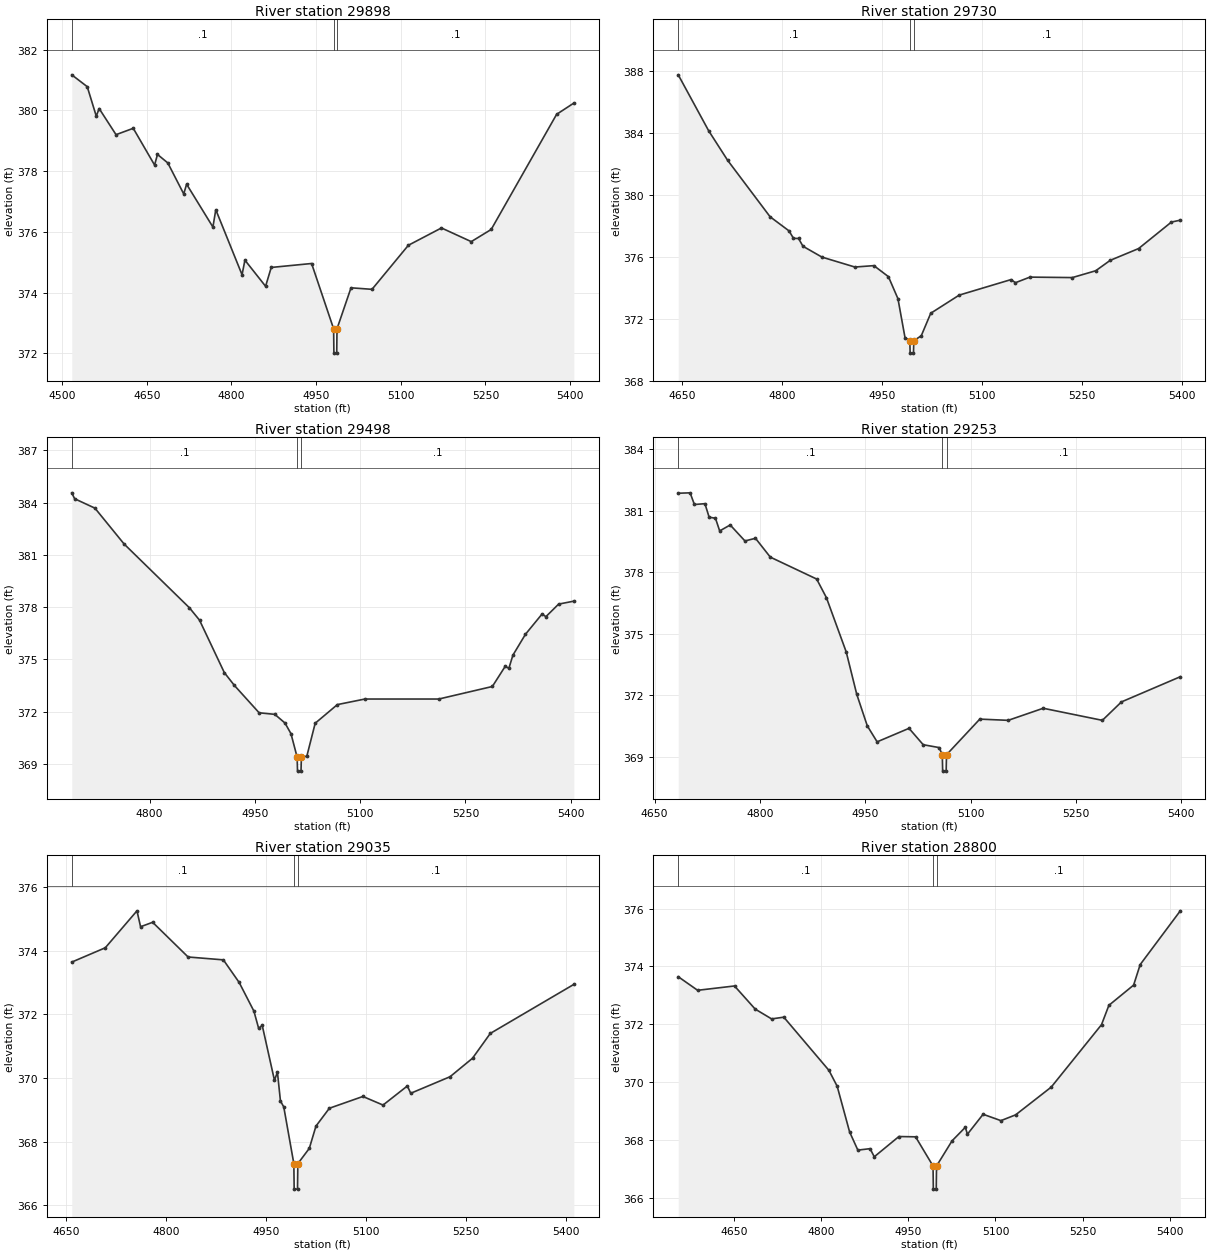
Type RM Length L Ch R = 1 ,29898   ,168,168,168
BEGIN DESCRIPTION:
Mapping XS f8b6e939
END DESCRIPTION:
XS GIS Cut Line= 3
      2081048.06     13404631.59      2081511.77     13404721.81
      2081871.28     13404510.72
#Sta/Elev= 30
  4517.2  381.17  4544.6  380.78  4560.6  379.81  4565.7  380.06  4595.6   379.2
  4626.1  379.41  4663.9   378.2    4669  378.55  4687.3  378.27  4715.5  377.25
  4720.6  377.57  4767.2  376.16  4772.3  376.73  4818.8  374.59  4823.9  375.07
  4860.5  374.21  4870.5  374.83    4942  374.96    4981  372.81  4981.5  372.01
  4986.5  372.01    4987  372.81  5011.8  374.16    5049  374.11  5113.4  375.56
    5172  376.13  5224.8  375.68  5260.1  376.08    5376  379.87  5406.5  380.24
#Mann= 3 ,-1 , 0
  4517.2      .1       0    4981     .07       0    4987      .1       0
Bank Sta=4981,4987
XS Rating Curve= 0 ,0
Exp/Cntr=0.3,0.1

Type RM Length L Ch R = 1 ,29730   ,232,232,232
BEGIN DESCRIPTION:
Mapping XS c6c97350
END DESCRIPTION:
XS GIS Cut Line= 3
      2081369.97     13405124.37      2081595.24     13404865.47
      2081868.74     13404560.01
#Sta/Elev= 30
  4644.8  387.73  4690.5  384.12  4718.9  382.22  4782.6  378.58    4811  377.67
  4817.7  377.19  4825.3  377.18  4831.9  376.68  4860.4  375.98  4909.8  375.34
  4938.3  375.43  4960.1  374.72  4974.4   373.3    4985  370.79  4992.2  370.59
  4992.7  369.79  4997.7  369.79  4998.2  370.59  5009.4  370.91  5023.6  372.36
  5066.3  373.53    5144  374.53  5150.7  374.33  5172.4  374.69    5236  374.66
  5271.1   375.1  5292.8  375.77  5335.4  376.53  5384.7  378.24    5398  378.36
#Mann= 3 ,-1 , 0
  4644.8      .1       0  4992.2     .07       0  4998.2      .1       0
Bank Sta=4992.2,4998.2
XS Rating Curve= 0 ,0
Exp/Cntr=0.3,0.1

Type RM Length L Ch R = 1 ,29498   ,245,245,245
BEGIN DESCRIPTION:
Mapping XS 1a018912
END DESCRIPTION:
XS GIS Cut Line= 3
      2081596.36     13405241.86      2081784.93      13405003.6
       2081946.4     13404625.16
#Sta/Elev= 30
  4689.2  384.56  4693.3  384.22  4722.2  383.68  4763.8  381.62  4856.8  377.96
  4871.2  377.25  4906.5  374.24  4920.9   373.5  4956.1  371.93  4978.5  371.84
    4993  371.34  5001.5  370.73  5010.3  369.38  5010.8  368.58  5015.8  368.58
  5016.3  369.38  5024.1  369.44    5036  371.33  5067.6   372.4  5106.8  372.72
  5212.1  372.72  5288.4  373.44  5306.6  374.59    5312  374.49  5317.7  375.24
  5335.6  376.44  5359.2   377.6  5364.7  377.45  5382.8  378.17  5404.5  378.34
#Mann= 3 ,-1 , 0
  4689.2      .1       0  5010.3     .07       0  5016.3      .1       0
Bank Sta=5010.3,5016.3
XS Rating Curve= 0 ,0
Exp/Cntr=0.3,0.1

Type RM Length L Ch R = 1 ,29253   ,218,218,218
BEGIN DESCRIPTION:
Mapping XS 2efbe65c
END DESCRIPTION:
XS GIS Cut Line= 3
      2081818.13     13405390.41      2081992.98     13405128.82
      2082044.56      13404731.9
#Sta/Elev= 30
  4683.6  381.86  4700.5  381.88  4706.6  381.31  4721.6  381.35  4727.6  380.69
  4736.6  380.64  4742.6  380.02  4757.6  380.31  4778.6  379.53  4793.6  379.66
  4814.7  378.74  4880.7  377.67  4894.6  376.76  4922.8  374.11  4937.8  372.04
  4952.8   370.5  4966.8  369.72  5012.2  370.38  5032.4  369.58  5055.1  369.44
  5059.6  369.09  5060.1  368.29  5065.1  368.29  5065.6  369.09    5113  370.83
  5153.4  370.77  5203.3  371.36  5287.5  370.77  5314.7  371.67  5398.5   372.9
#Mann= 3 ,-1 , 0
  4683.6      .1       0  5059.6     .07       0  5065.6      .1       0
Bank Sta=5059.6,5065.6
XS Rating Curve= 0 ,0
Exp/Cntr=0.3,0.1

Type RM Length L Ch R = 1 ,29035   ,235,235,235
BEGIN DESCRIPTION:
Mapping XS dd673f20
END DESCRIPTION:
XS GIS Cut Line= 3
      2082090.64     13405406.79      2082210.59     13405121.69
      2082163.84     13404680.36
#Sta/Elev= 30
  4658.7  373.64    4709  374.09  4756.5  375.25  4761.9  374.75    4780  374.89
  4833.2   373.8  4886.1  373.71  4909.8     373  4931.9   372.1    4939  371.56
  4944.4  371.65  4962.7  369.93  4967.2  370.18  4971.7  369.28  4976.7  369.09
  4991.8  367.31  4992.3  366.51  4997.3  366.51  4997.8  367.31    5015  367.79
    5025  368.49  5045.1  369.05  5095.4  369.42  5125.6  369.15  5162.1  369.75
  5167.1  369.52  5226.1  370.04  5259.8  370.62  5286.5   371.4  5411.8  372.94
#Mann= 3 ,-1 , 0
  4658.7      .1       0  4991.8     .07       0  4997.8      .1       0
Bank Sta=4991.8,4997.8
XS Rating Curve= 0 ,0
Exp/Cntr=0.3,0.1

Type RM Length L Ch R = 1 ,28800   ,242,242,242
BEGIN DESCRIPTION:
Mapping XS 5eafd174
END DESCRIPTION:
XS GIS Cut Line= 4
       2082136.5     13405383.61      2082407.55     13405127.48
      2082460.58     13405013.44      2082585.05     13404669.35
#Sta/Elev= 30
  4553.7  373.64  4587.1  373.17  4650.6  373.32  4686.2  372.52  4714.5  372.18
  4735.5  372.24  4813.2   370.4  4827.4  369.85  4848.8  368.27    4863  367.64
    4884  367.69  4891.3  367.41  4933.7  368.11  4962.4   368.1  4992.5  367.09
    4993  366.29    4998  366.29  4998.5  367.09  5025.2  367.96  5048.1  368.43
  5051.7  368.19  5078.7  368.88  5109.4  368.66  5134.7  368.86    5196  369.82
  5282.6  371.98  5295.3  372.65  5337.9  373.35  5349.2  374.06  5418.3  375.92
#Mann= 3 ,-1 , 0
  4553.7      .1       0  4992.5     .07       0  4998.5      .1       0
Bank Sta=4992.5,4998.5
XS Rating Curve= 0 ,0
Exp/Cntr=0.3,0.1

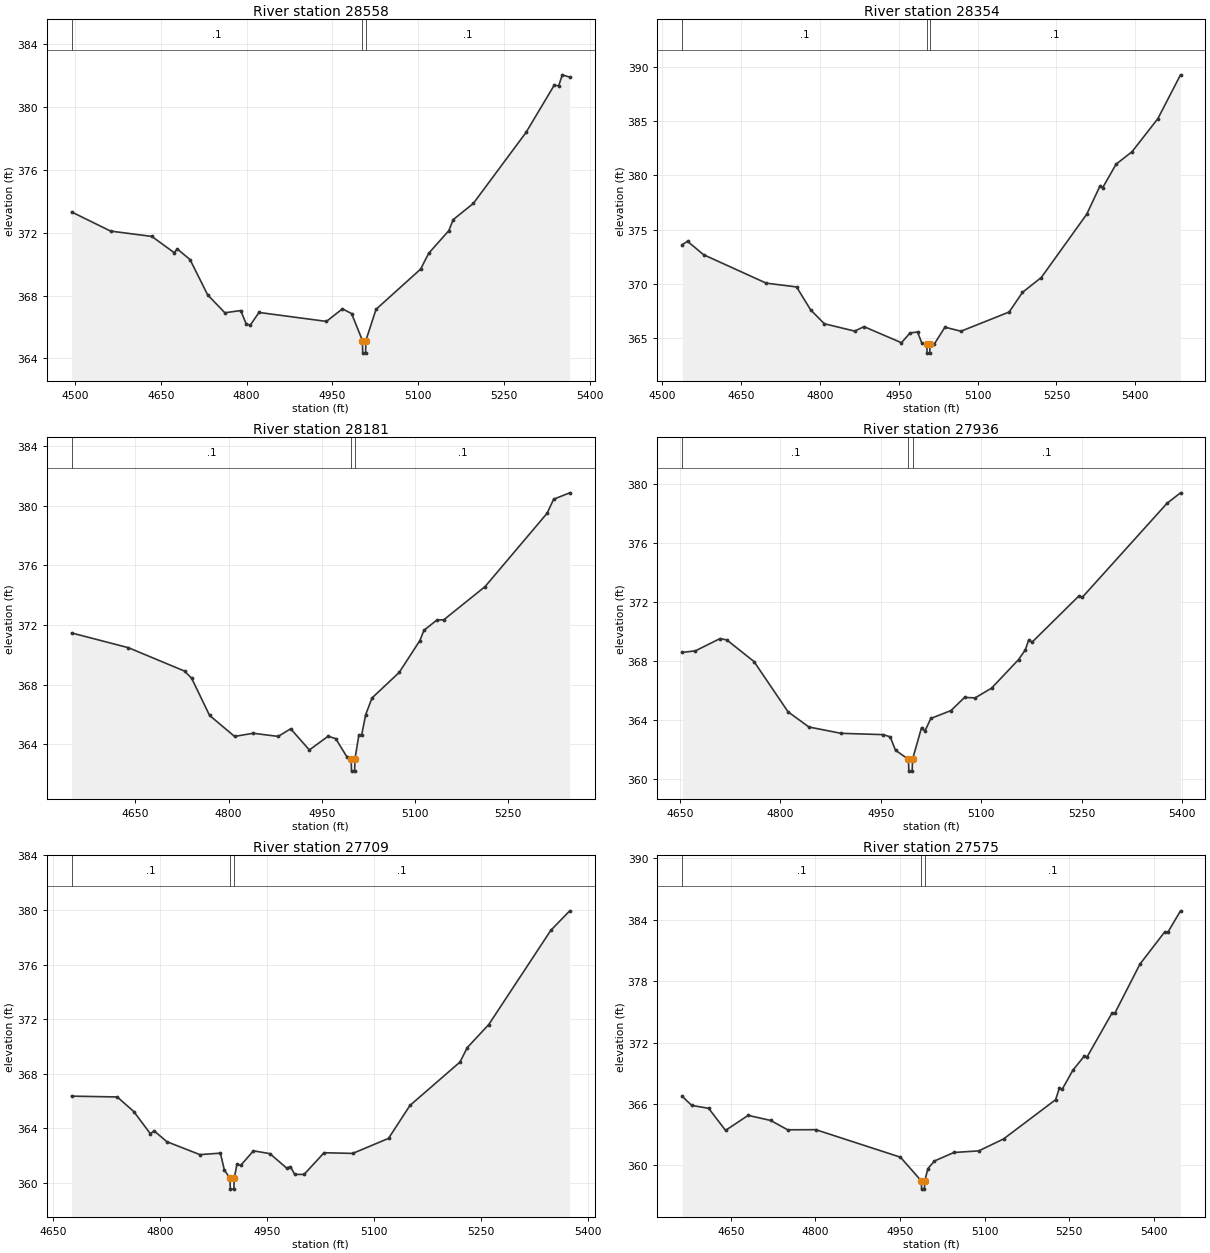
Type RM Length L Ch R = 1 ,28558   ,204,204,204
BEGIN DESCRIPTION:
Mapping XS f13550cd
END DESCRIPTION:
XS GIS Cut Line= 3
      2082173.01     13405433.02      2082601.98     13405213.72
      2082898.19     13404960.29
#Sta/Elev= 30
  4493.8  373.33  4562.1  372.11  4634.3  371.77  4673.2  370.74  4678.8  370.97
    4701   370.3  4731.9  368.05    4762  366.91  4789.8  367.05  4799.3   366.2
  4806.4  366.12  4821.7  366.93  4939.7  366.36  4967.7  367.16  4983.7  366.86
  5002.7  365.14  5003.2  364.34  5008.2  364.34  5008.7  365.14  5026.5  367.13
  5104.5  369.69  5118.7   370.7  5153.9  372.14  5161.5  372.84  5196.7  373.87
  5288.9  378.39  5338.3   381.4    5346  381.36  5352.5  382.06  5365.4  381.91
#Mann= 3 ,-1 , 0
  4493.8      .1       0  5002.7     .07       0  5008.7      .1       0
Bank Sta=5002.7,5008.7
XS Rating Curve= 0 ,0
Exp/Cntr=0.3,0.1

Type RM Length L Ch R = 1 ,28354   ,173,173,173
BEGIN DESCRIPTION:
Mapping XS a35b5da5
END DESCRIPTION:
XS GIS Cut Line= 3
      2082145.33     13405479.67      2082596.85     13405395.38
      2083055.46     13405228.07
#Sta/Elev= 30
  4538.4  373.62  4548.2  373.93  4578.8  372.69  4697.9  370.07  4755.7  369.72
  4782.2  367.62  4808.4  366.33  4866.1  365.65  4883.9  366.06  4955.1  364.58
  4971.5  365.48  4985.7  365.57  4994.2  364.51  5003.4  364.42  5003.9  363.62
  5008.9  363.62  5009.4  364.42  5017.9  364.48  5037.8  366.01  5068.4  365.64
    5160  367.41  5185.3  369.22  5221.1  370.59  5307.5  376.42  5332.7  379.02
    5338  378.88  5363.3  381.03  5393.8  382.19  5442.8  385.23  5485.9  389.27
#Mann= 3 ,-1 , 0
  4538.4      .1       0  5003.4     .07       0  5009.4      .1       0
Bank Sta=5003.4,5009.4
XS Rating Curve= 0 ,0
Exp/Cntr=0.3,0.1

Type RM Length L Ch R = 1 ,28181   ,245,245,245
BEGIN DESCRIPTION:
Mapping XS 5f6702a0
END DESCRIPTION:
XS GIS Cut Line= 3
      2082213.81     13405586.28      2082678.84     13405546.17
       2082999.8     13405451.11
#Sta/Elev= 30
  4547.5  371.47    4639  370.48  4729.4  368.91  4740.7  368.43  4769.5  365.94
  4809.7  364.53  4839.8  364.74  4879.9  364.53    4900  365.04  4930.1  363.62
  4960.2  364.54  4972.5  364.38  4990.3  363.17  4997.4     363  4997.9   362.2
  5002.9   362.2  5003.4     363  5009.8  364.64  5014.3  364.64  5020.7  365.99
  5030.9  367.11  5074.6  368.82  5107.9  370.96  5114.5  371.65  5135.4  372.34
  5146.3  372.35  5212.8  374.58  5312.6   379.5  5323.1  380.44    5349  380.87
#Mann= 3 ,-1 , 0
  4547.5      .1       0  4997.4     .07       0  5003.4      .1       0
Bank Sta=4997.4,5003.4
XS Rating Curve= 0 ,0
Exp/Cntr=0.3,0.1

Type RM Length L Ch R = 1 ,27936   ,227,227,227
BEGIN DESCRIPTION:
Mapping XS 9d67f125
END DESCRIPTION:
XS GIS Cut Line= 3
      2082279.73     13405726.64      2082595.66      13405784.7
      2083014.98     13405731.47
#Sta/Elev= 30
  4653.8  368.58  4673.4  368.69    4710  369.52  4720.2  369.43  4760.8  367.96
  4811.7  364.54  4842.8  363.51  4890.8  363.08  4954.1  362.99  4964.2  362.84
  4972.1  361.93  4991.5  361.31    4992  360.51    4997  360.51  4997.5  361.31
    5011  363.47    5016  363.23  5024.8  364.09    5055  364.63  5075.2  365.52
    5091  365.49  5115.5  366.15  5155.8  368.09  5165.9  368.75    5171  369.43
  5176.1  369.28    5246  372.42  5251.1  372.33  5377.6  378.72  5397.7  379.43
#Mann= 3 ,-1 , 0
  4653.8      .1       0  4991.5     .07       0  4997.5      .1       0
Bank Sta=4991.5,4997.5
XS Rating Curve= 0 ,0
Exp/Cntr=0.3,0.1

Type RM Length L Ch R = 1 ,27709   ,134,134,134
BEGIN DESCRIPTION:
Mapping XS 376c3e42
END DESCRIPTION:
XS GIS Cut Line= 3
      2082329.66     13405874.72      2082627.05     13406008.01
      2082998.14       13405978.
#Sta/Elev= 30
  4676.2  366.35  4740.2  366.29  4763.4  365.22  4786.5   363.6    4792   363.8
  4809.7  363.01  4856.1  362.06  4884.8  362.17  4890.3  360.94  4898.2  360.33
  4898.7  359.53  4903.7  359.53  4904.2  360.33  4907.9  361.34  4913.4  361.28
  4931.1  362.34  4954.3  362.13  4977.5  361.08    4983  361.18  4988.9  360.61
  5002.1  360.61  5030.1   362.2  5070.3  362.15  5120.4  363.25  5150.5  365.67
  5220.6  368.85  5230.8  369.91  5260.9   371.6  5347.9  378.51  5374.4  379.94
#Mann= 3 ,-1 , 0
  4676.2      .1       0  4898.2     .07       0  4904.2      .1       0
Bank Sta=4898.2,4904.2
XS Rating Curve= 0 ,0
Exp/Cntr=0.3,0.1

Type RM Length L Ch R = 1 ,27575   ,196,196,196
BEGIN DESCRIPTION:
Mapping XS 1e433ae0
END DESCRIPTION:
XS GIS Cut Line= 3
      2082188.42     13406137.31      2082627.41     13406138.65
      2083061.45     13406045.11
#Sta/Elev= 30
  4564.2  366.73  4580.8  365.85  4610.8  365.57  4640.8  363.41  4680.8  364.88
  4720.8  364.38  4750.8  363.47  4800.8  363.48  4950.8  360.79  4987.8  358.47
  4988.3  357.67  4993.3  357.67  4993.8  358.47  4999.5  359.68    5011  360.42
  5045.5  361.25  5089.7  361.41  5133.7  362.58  5225.8  366.41  5232.5  367.54
  5237.6  367.44  5256.5   369.3  5276.7  370.68  5281.8  370.61    5326   374.9
  5331.1   374.9  5375.3  379.66  5419.5  382.83  5424.6  382.76  5447.2  384.87
#Mann= 3 ,-1 , 0
  4564.2      .1       0  4987.8     .07       0  4993.8      .1       0
Bank Sta=4987.8,4993.8
XS Rating Curve= 0 ,0
Exp/Cntr=0.3,0.1

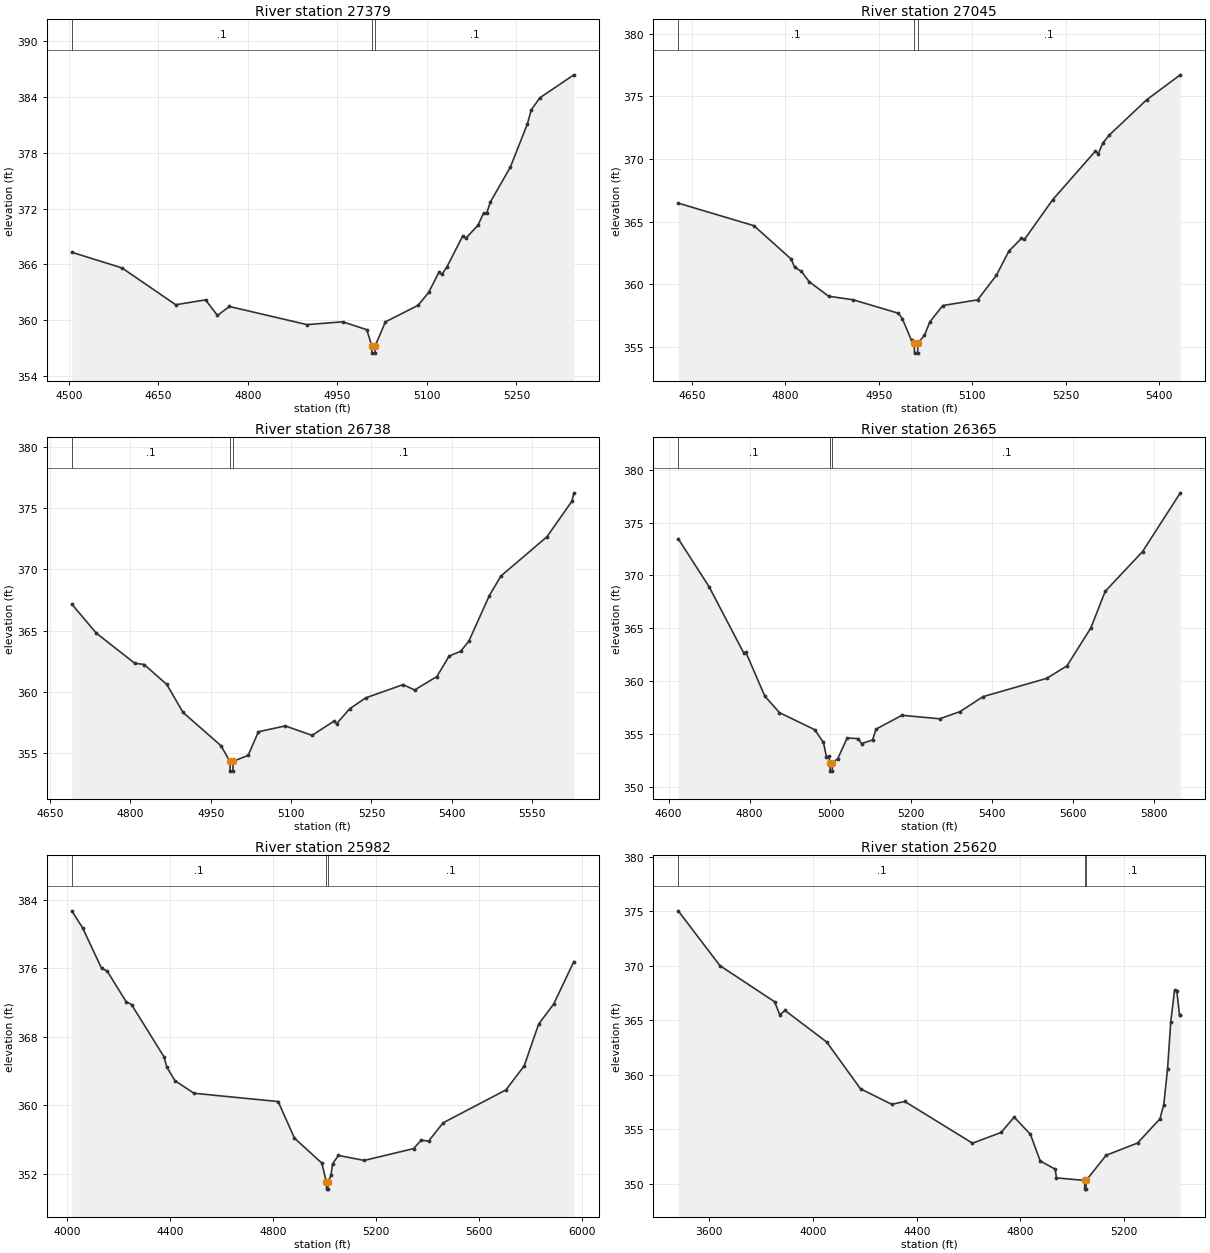
Type RM Length L Ch R = 1 ,27379   ,334,334,334
BEGIN DESCRIPTION:
Mapping XS 76440748
END DESCRIPTION:
XS GIS Cut Line= 3
       2082220.8     13406302.66      2082706.31     13406304.13
      2083050.11     13406211.75
#Sta/Elev= 30
  4504.8  367.31    4589  365.62    4679  361.66    4729  362.18    4749  360.51
    4769  361.47    4899  359.52    4959  359.82  4999.3  358.97  5007.5  357.25
    5008  356.45    5013  356.45  5013.5  357.25  5030.4  359.81  5085.3   361.6
  5102.9  362.98  5120.1  365.15  5125.3  364.93  5133.9  365.77  5160.1  369.07
  5165.3  368.82  5185.7  370.22  5194.9  371.52  5200.1  371.49  5206.4  372.72
    5240  376.49  5268.5  381.13  5274.8  382.62  5289.2  383.93  5346.3  386.41
#Mann= 3 ,-1 , 0
  4504.8      .1       0  5007.5     .07       0  5013.5      .1       0
Bank Sta=5007.5,5013.5
XS Rating Curve= 0 ,0
Exp/Cntr=0.3,0.1

Type RM Length L Ch R = 1 ,27045   ,307,307,307
BEGIN DESCRIPTION:
Mapping XS 18fdc7b1
END DESCRIPTION:
XS GIS Cut Line= 4
      2082213.68     13406377.91      2082490.43     13406498.14
      2082590.98     13406571.11        2082969.     13406538.52
#Sta/Elev= 30
  4628.1  366.47  4749.5  364.67  4809.2  362.01  4814.9  361.35  4825.8  361.02
  4838.1   360.2  4869.4  359.04  4908.5  358.76  4981.4  357.68  4987.6  357.25
  5002.3  355.51  5006.6   355.3  5007.1   354.5  5012.1   354.5  5012.6   355.3
  5023.1  355.92  5031.7  356.99  5052.5   358.3  5108.3  358.75  5138.4  360.71
  5158.5  362.64  5178.5  363.65  5183.5  363.57  5228.7  366.74  5296.9   370.6
    5302  370.42    5309  371.25  5319.1  371.88  5379.3  374.71  5433.5  376.71
#Mann= 3 ,-1 , 0
  4628.1      .1       0  5006.6     .07       0  5012.6      .1       0
Bank Sta=5006.6,5012.6
XS Rating Curve= 0 ,0
Exp/Cntr=0.3,0.1

Type RM Length L Ch R = 1 ,26738   ,373,373,373
BEGIN DESCRIPTION:
Mapping XS 3ca932b5
END DESCRIPTION:
XS GIS Cut Line= 4
      2082038.59      13406704.4      2082343.11     13406739.07
      2082510.28     13406747.36      2082941.81     13406578.11
#Sta/Elev= 30
  4690.5  367.16  4736.1   364.8  4807.7  362.34  4825.6  362.23    4868   360.6
  4898.2  358.32  4968.7  355.62  4985.8  354.33  4986.3  353.53  4991.3  353.53
  4991.8  354.33  5019.9  354.82  5038.9  356.74    5089  357.22  5139.1  356.45
  5179.7   357.6    5185  357.41  5209.5  358.62  5239.3  359.51  5309.1  360.59
  5330.6  360.15  5372.2  361.25    5395  362.92  5416.5  363.31  5431.8  364.13
  5470.2  367.86  5491.7  369.45  5577.6  372.65  5624.3  375.56  5627.9  376.24
#Mann= 3 ,-1 , 0
  4690.5      .1       0  4985.8     .07       0  4991.8      .1       0
Bank Sta=4985.8,4991.8
XS Rating Curve= 0 ,0
Exp/Cntr=0.3,0.1

Type RM Length L Ch R = 1 ,26365   ,383,383,383
BEGIN DESCRIPTION:
Fox Creek 46.0
END DESCRIPTION:
XS GIS Cut Line= 3
      2081925.02     13406925.01        2082275.       13407075.
        2082975.       13406575.
#Sta/Elev= 30
  4623.8  373.47  4699.9  368.94  4785.2   362.7  4790.6  362.76  4837.7  358.59
    4874  357.02  4961.1  355.41  4982.8   354.2  4990.1  352.86  4995.5  352.89
  4998.9  352.29  4999.4  351.49  5004.4  351.49  5004.9  352.29  5018.1  352.67
  5041.4  354.63  5068.5  354.56  5077.1  354.09  5104.1  354.44  5112.7  355.46
  5176.6  356.77    5270  356.44  5320.4  357.12  5376.9  358.53  5534.2  360.26
  5584.6  361.44  5643.6  365.03  5679.2   368.5  5771.4  372.25  5864.8  377.81
#Mann= 3 ,-1 , 0
  4623.8      .1       0  4998.9     .07       0  5004.9      .1       0
Bank Sta=4998.9,5004.9
XS Rating Curve= 0 ,0
Exp/Cntr=0.3,0.1

Type RM Length L Ch R = 1 ,25982   ,362,362,362
BEGIN DESCRIPTION:
Fox Creek 45.0
END DESCRIPTION:
XS GIS Cut Line= 3
      2081475.03     13407125.01        2082375.       13407425.
      2082975.03     13406624.97
#Sta/Elev= 30
  4018.3   382.7  4060.4  380.71  4134.2  375.98  4155.3  375.69  4229.1   372.1
  4250.2  371.76  4376.7  365.64  4387.2  364.46  4418.8  362.88  4492.6  361.41
  4819.4  360.44  4882.6  356.17  4988.8  353.26  5006.7  351.02  5007.2  350.22
  5012.2  350.22  5012.7  351.02  5024.2  351.83  5030.5  353.18  5053.4  354.15
  5153.4  353.57  5345.1  354.95  5374.2  355.93  5403.4  355.83  5459.7  357.96
  5703.4   361.8  5774.2   364.6  5830.5  369.49  5888.8  371.82    5967  376.78
#Mann= 3 ,-1 , 0
  4018.3      .1       0  5006.7     .07       0  5012.7      .1       0
Bank Sta=5006.7,5012.7
XS Rating Curve= 0 ,0
Exp/Cntr=0.3,0.1

Type RM Length L Ch R = 1 ,25620   ,366,366,366
BEGIN DESCRIPTION:
Fox Creek 44.0
END DESCRIPTION:
XS GIS Cut Line= 3
      2081125.04       13407775.        2082625.       13407625.
      2082875.02     13407274.97
#Sta/Elev= 30
  3479.7  375.03  3640.5  370.01  3851.5   366.7  3871.6  365.51  3891.7   365.9
  4052.5  363.01  4183.2  358.72  4303.8   357.3    4354  357.56  4615.3  353.74
  4725.8  354.72  4776.1  356.13  4838.9  354.55  4876.6  352.11  4934.4  351.36
  4939.4  350.56    5048  350.33  5048.5  349.53  5053.5  349.53    5054  350.33
  5130.9  352.63  5252.6  353.76  5338.6  355.97  5353.4  357.26  5368.1  360.55
  5380.4  364.85  5395.1  367.76  5403.7  367.71  5414.2  365.48  5417.3  365.48
#Mann= 3 ,-1 , 0
  3479.7      .1       0    5048     .07       0    5054      .1       0
Bank Sta=5048,5054
XS Rating Curve= 0 ,0
Exp/Cntr=0.3,0.1

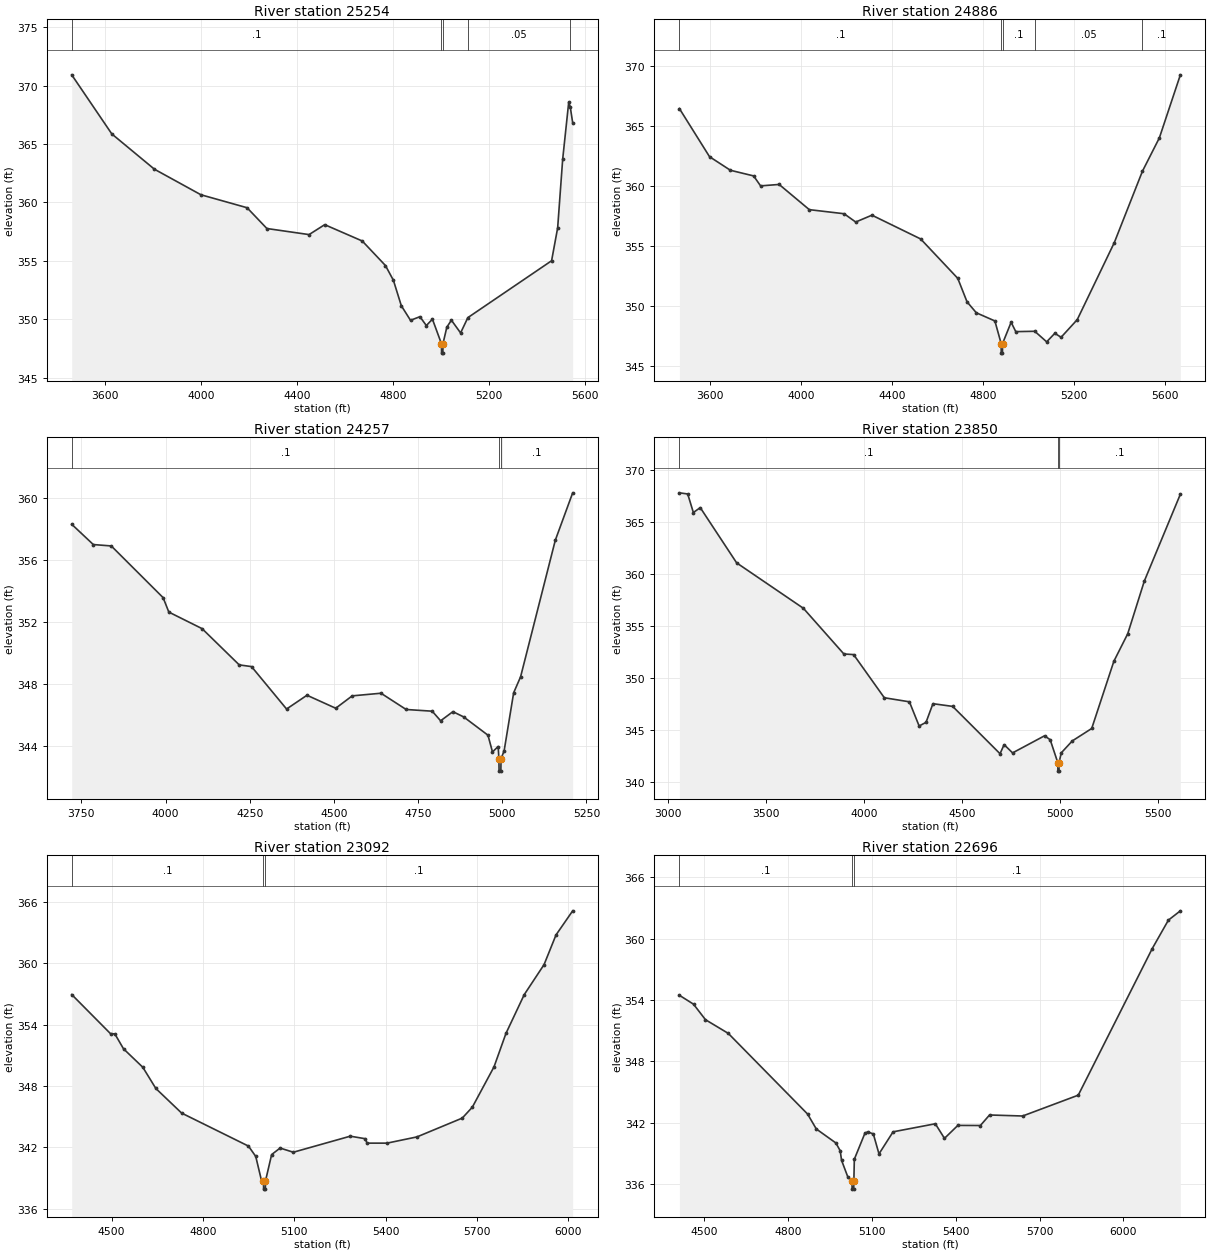
Type RM Length L Ch R = 1 ,25254   ,368,368,368
BEGIN DESCRIPTION:
Fox Creek 43.0
END DESCRIPTION:
XS GIS Cut Line= 3
      2081324.95     13408325.01        2082825.       13407875.
        2082975.     13407375.01
#Sta/Elev= 30
    3461  370.92  3628.1  365.86  3805.6  362.84  3999.6  360.65  4191.9  359.54
  4274.5  357.76  4450.3  357.24  4515.5  358.09  4672.1  356.69  4768.7  354.59
  4801.8  353.33  4834.8  351.15  4873.1   349.9  4912.3  350.21  4939.2  349.45
  4964.5     350  5002.2  347.89  5002.7  347.09  5007.9  347.09  5008.4  347.89
  5024.5  349.31  5043.6  349.91  5081.9  348.82  5112.2  350.13  5461.2     355
  5486.5  357.82  5507.4  363.69  5532.6  368.58    5539  368.17  5549.1  366.82
#Mann= 5 ,-1 , 0
    3461      .1       0  5002.2     .07       0  5008.4      .1       0
  5112.2     .05       0    5539     .07       0
Bank Sta=5002.2,5008.4
XS Rating Curve= 0 ,0
Exp/Cntr=0.3,0.1

Type RM Length L Ch R = 1 ,24886   ,629,629,629
BEGIN DESCRIPTION:
Fox Creek 42.0
END DESCRIPTION:
XS GIS Cut Line= 3
      2081525.04     13408424.99        2083025.       13408125.
      2083474.97     13407625.04
#Sta/Elev= 30
  3465.9  366.42  3598.4  362.41  3690.2  361.28  3792.2  360.81  3822.8  359.98
  3904.4   360.1    4037     358  4189.9  357.66  4240.9  356.97  4312.3  357.54
  4526.5  355.56  4689.6  352.28  4730.4  350.32  4771.2  349.41  4852.8  348.73
  4880.3  346.85  4880.8  346.05    4886  346.05  4886.5  346.85  4924.2  348.62
  4944.6  347.84  5028.1  347.87  5080.4  346.99  5116.3   347.7  5143.9  347.37
  5214.9  348.84  5377.9  355.26  5501.4   361.2  5575.9  363.98  5668.2  369.23
#Mann= 5 ,-1 , 0
  3465.9      .1       0  4880.3     .07       0  4886.5      .1       0
  5028.1     .05       0  5501.4      .1       0
Bank Sta=4880.3,4886.5
XS Rating Curve= 0 ,0
Exp/Cntr=0.3,0.1

Type RM Length L Ch R = 1 ,24257   ,407,407,407
BEGIN DESCRIPTION:
Fox Creek 41.0
END DESCRIPTION:
XS GIS Cut Line= 3
        2082375.       13408675.        2083575.       13408225.
      2083625.01     13408024.96
#Sta/Elev= 30
  3721.3  358.29  3785.4  356.98  3838.8  356.89  3992.8  353.55  4009.7  352.62
  4108.5  351.55  4218.8  349.21  4255.3   349.1  4359.4  346.36    4420  347.25
  4505.4  346.41  4554.3  347.21  4639.8  347.38  4714.5  346.33    4792  346.22
  4816.9   345.6  4853.4  346.19  4885.4  345.85  4957.5  344.67  4970.9  343.59
  4987.8  343.94    4990  343.15  4990.5  342.35  4995.8  342.35  4996.3  343.15
  5005.5  343.66  5033.8  347.41  5054.4  348.44  5157.5  357.26  5209.1  360.32
#Mann= 3 ,-1 , 0
  3721.3      .1       0    4990     .07       0  4996.3      .1       0
Bank Sta=4990,4996.3
XS Rating Curve= 0 ,0
Exp/Cntr=0.3,0.1

Type RM Length L Ch R = 1 ,23850   ,758,758,758
BEGIN DESCRIPTION:
Fox Creek 40.0
END DESCRIPTION:
XS GIS Cut Line= 3
      2082374.99     13410075.02        2083575.       13408575.
      2084025.03     13408124.97
#Sta/Elev= 30
  3056.7  367.78  3099.1  367.67    3128  365.89  3163.2  366.36  3348.9  361.06
  3689.8   356.7  3896.3  352.32    3946  352.26  4102.8  348.12  4230.9  347.73
  4280.5  345.41  4315.7  345.76    4351  347.55  4451.8  347.29  4693.5  342.75
  4714.3  343.62  4757.6  342.83  4920.8  344.47  4949.6  344.09  4988.6  341.88
  4989.1  341.08  4994.4  341.08  4994.9  341.88  5005.9  342.83  5062.5  343.98
  5161.5  345.17  5274.6  351.62  5345.4  354.26  5430.2  359.32  5614.1  367.65
#Mann= 3 ,-1 , 0
  3056.7      .1       0  4988.6     .07       0  4994.9      .1       0
Bank Sta=4988.6,4994.9
XS Rating Curve= 0 ,0
Exp/Cntr=0.3,0.1

Type RM Length L Ch R = 1 ,23092   ,396,396,396
BEGIN DESCRIPTION:
Fox Creek 39.0
END DESCRIPTION:
XS GIS Cut Line= 3
        2083375.       13409625.        2083775.       13409175.
        2084075.     13408175.01
#Sta/Elev= 30
  4368.8  356.94  4496.3  353.11  4510.5  353.09    4539  351.63  4602.5  349.82
  4645.2  347.75    4730  345.34  4949.6  342.11  4973.5   341.1  4992.6  338.71
  4998.9   338.7  4999.4   337.9    5005   337.9  5005.5   338.7  5025.7  341.28
  5053.5  341.92    5097  341.51  5284.1  343.08  5333.7  342.83  5338.9   342.4
    5405   342.4  5503.3  343.01  5652.1  344.85  5685.2  345.92  5756.5  349.87
  5795.7  353.14  5855.7  356.93  5920.9  359.87  5960.1  362.77  6014.9  365.13
#Mann= 3 ,-1 , 0
  4368.8      .1       0  4998.9     .07       0  5005.5      .1       0
Bank Sta=4998.9,5005.5
XS Rating Curve= 0 ,0
Exp/Cntr=0.3,0.1

Type RM Length L Ch R = 1 ,22696   ,394,394,394
BEGIN DESCRIPTION:
Fox Creek 38.0
END DESCRIPTION:
XS GIS Cut Line= 3
        2083525.       13409725.        2084025.       13409425.
        2084175.     13408225.03
#Sta/Elev= 30
  4411.3  354.46  4461.8  353.59  4504.6  352.07  4586.2  350.73    4870  342.83
  4901.1  341.37  4971.1     340  4986.6  339.24  4991.5   338.3  5014.5  336.63
  5028.8  336.28  5029.3  335.48    5035  335.48  5035.5  336.28  5037.2  338.41
    5075  340.95  5085.1  341.09  5105.2  340.88  5125.4  338.93  5175.8  341.09
    5327  341.88  5359.7  340.45  5407.6  341.72  5488.2  341.71    5521  342.74
  5639.4  342.64  5838.4  344.68    6103  359.03  6160.9  361.82  6203.7  362.73
#Mann= 3 ,-1 , 0
  4411.3      .1       0  5028.8     .07       0  5035.5      .1       0
Bank Sta=5028.8,5035.5
XS Rating Curve= 0 ,0
Exp/Cntr=0.3,0.1

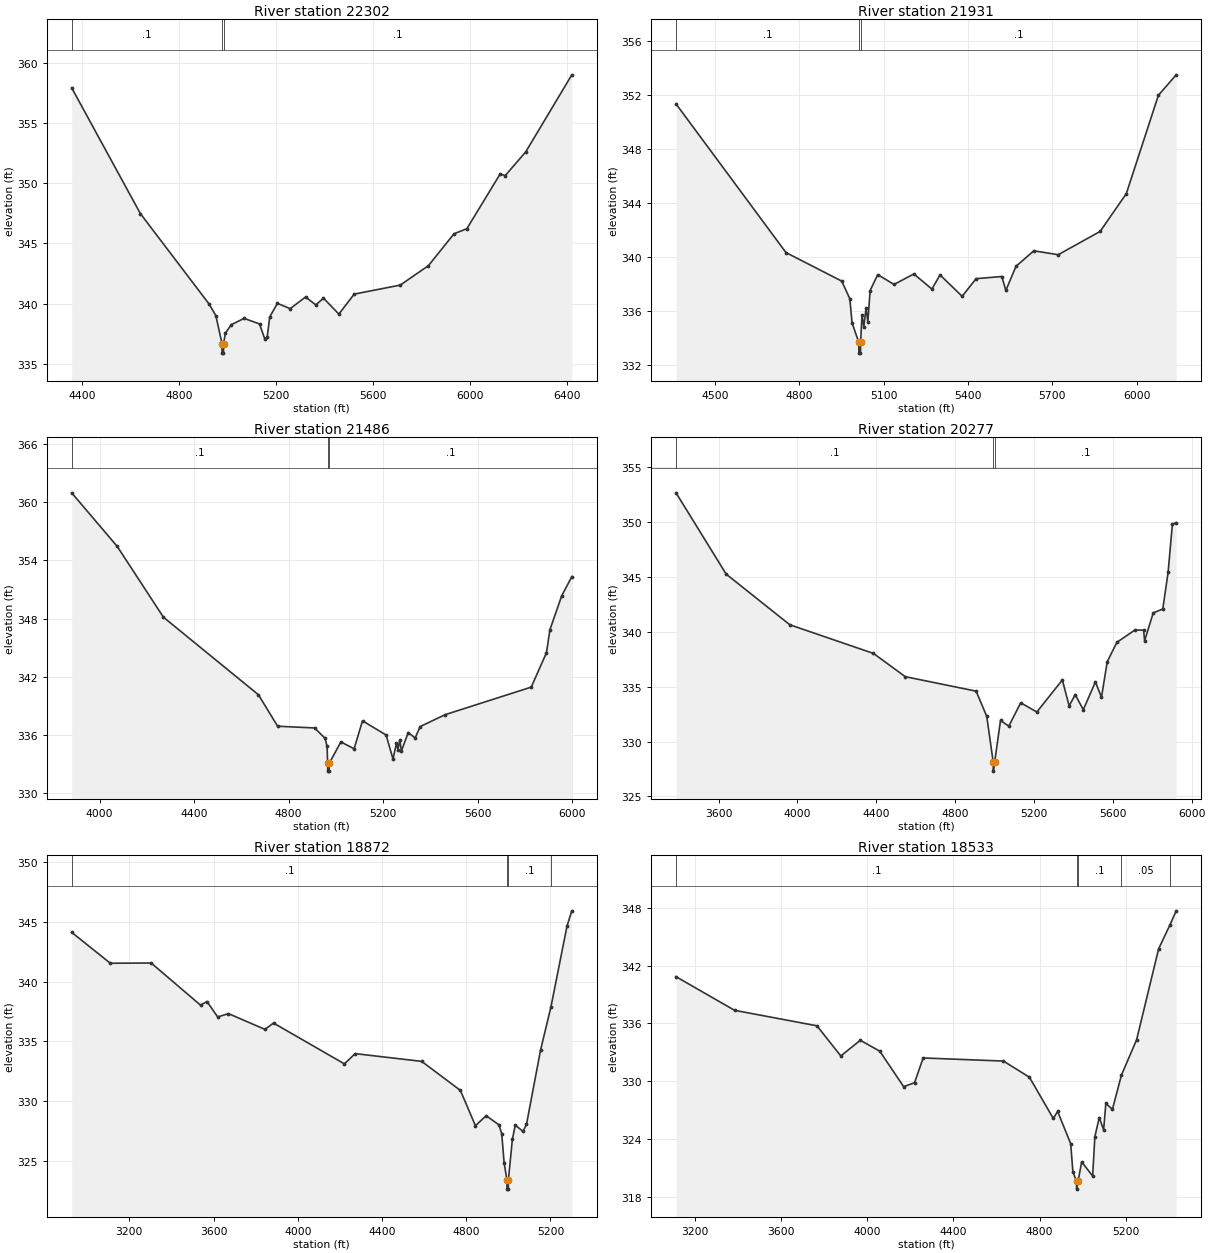
Type RM Length L Ch R = 1 ,22302   ,371,371,371
BEGIN DESCRIPTION:
Fox Creek 37.0
END DESCRIPTION:
XS GIS Cut Line= 3
      2083725.03     13410174.97        2084175.       13409725.
      2084625.01     13408374.98
#Sta/Elev= 30
  4358.7  357.95  4641.5  347.49  4924.3  339.97  4952.6  338.99  4977.6  336.68
  4978.1  335.88  4983.8  335.88  4984.3  336.68  4991.5  337.54  5016.1  338.25
  5068.8  338.77  5132.1  338.31  5153.2  337.09  5163.7  337.21  5174.2  338.89
  5205.9  340.02  5258.6  339.58  5321.8  340.55    5364  339.89  5395.6  340.45
  5458.9  339.13  5522.1  340.79  5711.8  341.54  5827.8  343.16  5933.2  345.81
  5985.9  346.23  6122.9  350.78    6144  350.65  6228.3  352.62  6418.1  359.03
#Mann= 3 ,-1 , 0
  4358.7      .1       0  4977.6     .07       0  4984.3      .1       0
Bank Sta=4977.6,4984.3
XS Rating Curve= 0 ,0
Exp/Cntr=0.3,0.1

Type RM Length L Ch R = 1 ,21931   ,445,445,445
BEGIN DESCRIPTION:
Fox Creek 36.0
END DESCRIPTION:
XS GIS Cut Line= 3
      2083924.99     13410175.01        2084425.       13409775.
        2085325.       13409075.
#Sta/Elev= 30
  4360.7  351.36  4752.1  340.32  4950.6   338.2  4979.4  336.89  4987.4   335.1
  5011.2  333.65  5011.7  332.85  5017.4  332.85  5017.9  333.65  5022.7  335.71
  5029.1   334.8  5037.2   336.2  5043.6  335.18  5051.7   337.5  5078.8  338.68
  5136.8  337.95  5207.3  338.73  5271.6  337.61  5300.5  338.66  5379.3  337.07
    5429  338.38  5520.4  338.54  5534.9  337.51  5571.1   339.3  5634.5  340.45
  5721.3  340.16  5870.6  341.89  5963.8   344.7  6077.9     352  6141.2  353.52
#Mann= 3 ,-1 , 0
  4360.7      .1       0  5011.2     .07       0  5017.9      .1       0
Bank Sta=5011.2,5017.9
XS Rating Curve= 0 ,0
Exp/Cntr=0.3,0.1

Type RM Length L Ch R = 1 ,21486   ,1209,1209,1209
BEGIN DESCRIPTION:
Fox Creek 35.0
END DESCRIPTION:
XS GIS Cut Line= 3
      2083725.01     13410424.99        2084725.       13409925.
      2085324.99     13409125.02
#Sta/Elev= 30
  3881.4  360.96  4074.2  355.44  4269.9  348.14  4672.4  340.14  4753.5   336.9
    4910  336.72  4954.7  335.65  4963.1  334.81  4965.3  333.07  4965.8  332.27
  4971.5  332.27    4972  333.07  5021.3  335.28  5077.5  334.58    5113  337.46
    5213  335.99  5242.1  333.52  5256.7  335.13    5263  334.49  5271.3   335.5
  5277.5  334.33  5306.7  336.25  5335.9  335.68  5356.7  336.86    5463  338.09
  5827.5  340.93  5892.1  344.48  5906.7  346.85  5956.7  350.35  5999.4  352.32
#Mann= 3 ,-1 , 0
  3881.4      .1       0  4965.3     .07       0    4972      .1       0
Bank Sta=4965.3,4972
XS Rating Curve= 0 ,0
Exp/Cntr=0.3,0.1

Type RM Length L Ch R = 1 ,20277   ,1405,1405,1405
BEGIN DESCRIPTION:
Fox Creek 34.0
END DESCRIPTION:
XS GIS Cut Line= 3
      2084175.02     13410674.99        2085675.       13410075.
        2085875.     13409174.98
#Sta/Elev= 30
    3384  352.67  3638.4  345.26  3961.5  340.64  4385.6  338.03  4547.2  335.91
  4906.6  334.59  4960.5  332.29  4993.4   328.1  4993.9   327.3  5000.3   328.1
  5030.3  331.92  5072.5   331.4  5132.7  333.53  5214.6  332.69    5344  335.61
  5378.6  333.24  5409.3  334.27  5450.3   332.9  5511.7  335.43  5542.5  334.04
  5571.9  337.28  5620.6  339.04  5712.8  340.17  5756.3  340.15  5761.4  339.19
    5805  341.72  5853.6  342.08  5880.5  345.41  5902.3  349.81  5921.5  349.95
#Mann= 3 ,-1 , 0
    3384      .1       0  4993.4     .07       0  5000.3      .1       0
Bank Sta=4993.4,5000.3
XS Rating Curve= 0 ,0
Exp/Cntr=0.3,0.1

Type RM Length L Ch R = 1 ,18872   ,339,339,339
BEGIN DESCRIPTION:
Fox Creek 33.0
END DESCRIPTION:
XS GIS Cut Line= 3
      2084574.97     13410725.01        2086575.       13410325.
      2086725.02     13410024.96
#Sta/Elev= 30
  2926.3  344.12  3109.9  341.53  3303.7  341.55  3538.2  338.02  3568.8  338.32
  3619.8  337.03  3670.8  337.31  3844.2  335.99  3884.9  336.52  4221.5   333.1
  4272.5  333.96  4588.6  333.31  4772.2  330.88  4843.6  327.92  4894.6  328.76
  4955.7  327.99  4968.7  327.23  4979.9  324.81  4993.1  323.41  4993.6  322.61
  4999.7  322.61  5000.3  323.41    5019  326.77    5033  327.98  5069.4  327.44
  5086.1  328.03  5153.2  334.28  5202.1  337.86    5279  344.68  5301.4  345.92
#Mann= 4 ,-1 , 0
  2926.3      .1       0  4993.1     .07       0  5000.3      .1       0
  5202.1     .05       0
Bank Sta=4993.1,5000.3
XS Rating Curve= 0 ,0
Exp/Cntr=0.3,0.1

Type RM Length L Ch R = 1 ,18533   ,408,408,408
BEGIN DESCRIPTION:
Fox Creek 32.0
END DESCRIPTION:
XS GIS Cut Line= 3
      2084975.02       13410725.        2086775.       13410525.
      2086875.01     13410024.96
#Sta/Elev= 30
  3112.6  340.86  3384.2  337.37  3766.6  335.76  3877.3  332.63  3967.8  334.26
  4058.4  333.12    4169  329.44  4219.4  329.85  4259.6  332.42  4631.9   332.1
  4752.6  330.42  4863.3  326.14  4883.4  326.87  4944.1  323.52  4954.3  320.61
  4971.1   319.6  4971.6   318.8  4978.3   319.6    4995  321.63    5046  320.16
  5056.2  324.24  5076.6  326.23    5097  324.96  5107.2   327.7  5137.8  327.09
  5179.6  330.64    5250  334.31    5352  343.74  5404.9  346.25  5433.6   347.7
#Mann= 5 ,-1 , 0
  3112.6      .1       0  4971.1     .07       0  4978.3      .1       0
  5179.6     .05       0  5404.9      .1       0
Bank Sta=4971.1,4978.3
XS Rating Curve= 0 ,0
Exp/Cntr=0.3,0.1