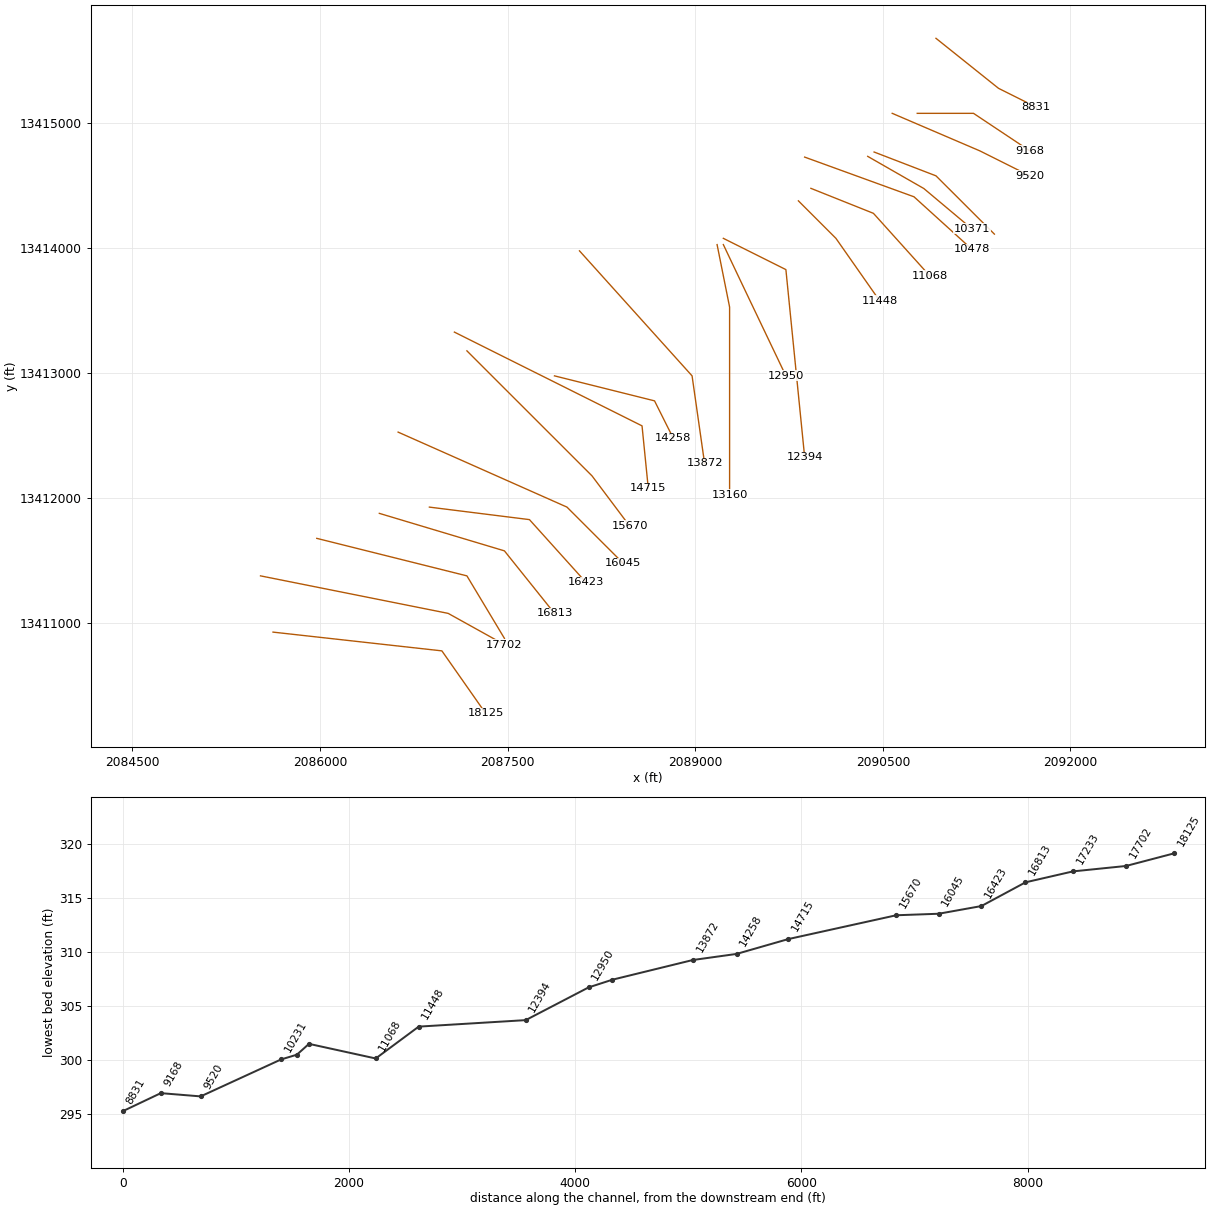
HEC-RAS study Fox Creek.prj: Fox Creek Base Level Engineering

--- Fox Creek.g01 (geometry) --- (continued)

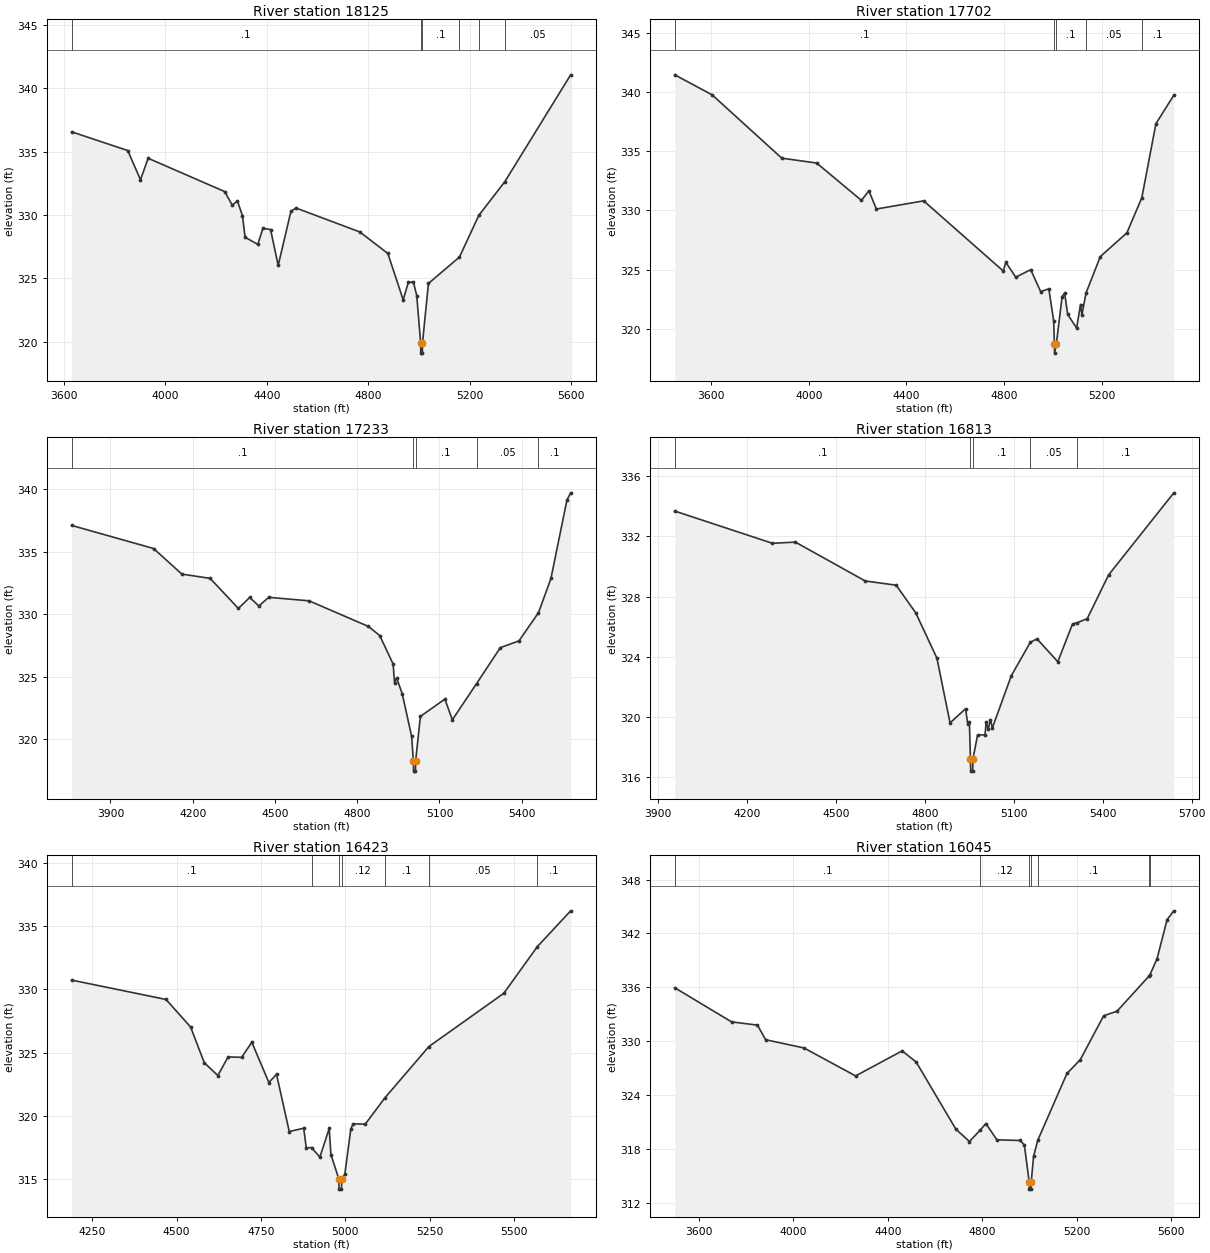
Type RM Length L Ch R = 1 ,18125   ,423,423,423
BEGIN DESCRIPTION:
Fox Creek 31.0
END DESCRIPTION:
XS GIS Cut Line= 3
      2085624.98       13410925.        2086975.       13410775.
      2087325.03     13410274.96
#Sta/Elev= 30
    3630  336.57  3851.4  335.09  3901.7  332.78  3931.9  334.48  4233.7  331.85
  4263.9  330.77    4284  331.11  4304.1  329.94  4314.2  328.24  4364.5  327.68
  4384.6  328.95  4414.8  328.85    4445  326.02  4495.3   330.3  4515.4  330.55
    4767  328.66  4877.6  326.96    4938  323.29  4958.1  324.67  4978.3  324.71
  4991.4  323.64  5006.9  319.89  5007.5  319.09  5013.7  319.09  5014.2  319.89
  5037.6  324.59  5160.1  326.68  5236.4  329.97  5339.3  332.64  5598.7  341.07
#Mann= 6 ,-1 , 0
    3630      .1       0  5006.9     .07       0  5014.2      .1       0
  5160.1     .05       0  5236.4      .1       0  5339.3     .05       0
Bank Sta=5006.9,5014.2
XS Rating Curve= 0 ,0
Exp/Cntr=0.3,0.1

Type RM Length L Ch R = 1 ,17702   ,469,469,469
BEGIN DESCRIPTION:
Fox Creek 30.0
END DESCRIPTION:
XS GIS Cut Line= 3
      2085525.02       13411375.        2087025.       13411075.
      2087475.03     13410824.99
#Sta/Elev= 30
    3451  341.47    3604  339.78  3889.5  334.42  4032.3  334.01  4215.8  330.85
  4246.4  331.66    4277  330.12  4470.8  330.81  4797.1  324.87  4807.3  325.62
  4848.1  324.35  4909.3  324.99  4950.1  323.13  4983.5  323.37  5003.6  320.63
  5006.3  318.73    5007  317.93  5014.5  318.73  5037.9   322.7  5048.2  323.02
  5060.8   321.2  5097.4  320.05  5113.4  322.04  5119.1  321.16  5135.7     323
  5194.6   326.1  5303.3   328.1  5364.5  331.07  5422.3  337.34  5495.5  339.74
#Mann= 5 ,-1 , 0
    3451      .1       0  5006.3     .07       0  5014.5      .1       0
  5135.7     .05       0  5364.5      .1       0
Bank Sta=5006.3,5014.5
XS Rating Curve= 0 ,0
Exp/Cntr=0.3,0.1

Type RM Length L Ch R = 1 ,17233   ,420,420,420
BEGIN DESCRIPTION:
Fox Creek 29.0
END DESCRIPTION:
XS GIS Cut Line= 3
        2085975.       13411675.        2087175.       13411375.
      2087474.98     13410875.03
#Sta/Elev= 30
  3758.5  337.11  4057.4  335.26  4160.5  333.21  4263.6  332.87  4366.7  330.46
  4407.9  331.34  4441.4  330.66  4477.5  331.35  4624.4  331.07  4840.8  329.02
  4882.1  328.29    4931  326.01  4936.2  324.52  4943.9  324.89  4964.5  323.61
  4998.4  320.22  5004.9  318.23  5005.6  317.43  5012.4  317.43  5013.1  318.23
  5030.4  321.81  5119.8   323.2    5147  321.54  5235.3  324.44    5322  327.32
    5390  327.86  5461.2  330.12  5506.6  332.86  5564.9  339.14  5578.5  339.72
#Mann= 5 ,-1 , 0
  3758.5      .1       0  5004.9     .07       0  5013.1      .1       0
  5235.3     .05       0  5461.2      .1       0
Bank Sta=5004.9,5013.1
XS Rating Curve= 0 ,0
Exp/Cntr=0.3,0.1

Type RM Length L Ch R = 1 ,16813   ,390,390,390
BEGIN DESCRIPTION:
Fox Creek 28.0
END DESCRIPTION:
XS GIS Cut Line= 3
      2086475.02     13411874.99        2087475.       13411575.
      2087874.99     13411075.02
#Sta/Elev= 30
  3955.4  333.68  4285.1  331.54  4362.5  331.62  4598.3  329.04  4702.7  328.76
  4768.9  326.92  4840.2  323.92  4884.6  319.62  4936.8  320.56  4944.6  319.52
  4949.8  319.67  4953.5  317.22  4954.2  316.42    4961  316.42  4961.7  317.22
  4977.7  318.83  5002.6  318.82  5006.6  319.69    5013  319.19    5021  319.83
  5027.4  319.29  5091.5  322.76  5155.5  324.97  5177.9   325.2  5248.3  323.68
    5298  326.19  5314.1  326.27  5347.6  326.54  5419.6  329.44  5639.7  334.89
#Mann= 5 ,-1 , 0
  3955.4      .1       0  4953.5     .07       0  4961.7      .1       0
  5155.5     .05       0  5314.1      .1       0
Bank Sta=4953.5,4961.7
XS Rating Curve= 0 ,0
Exp/Cntr=0.3,0.1

Type RM Length L Ch R = 1 ,16423   ,378,378,378
BEGIN DESCRIPTION:
Fox Creek 27.0
END DESCRIPTION:
XS GIS Cut Line= 3
      2086874.99       13411925.        2087675.       13411825.
      2088124.99     13411325.02
#Sta/Elev= 30
  4188.9  330.74  4468.6  329.21  4541.6  327.03  4581.9  324.22  4622.3   323.2
  4652.5  324.67  4692.8  324.64    4723  325.83  4773.4  322.65  4796.1   323.3
  4833.9  318.78  4876.7  319.04  4884.3  317.49  4899.9  317.51  4924.6  316.76
  4952.3  319.02  4957.3  316.96  4980.8  315.03  4981.5  314.23  4988.6  314.23
  4989.4  315.03  4998.5   315.4  5016.4     319  5023.2  319.39    5059  319.36
  5117.3  321.44  5247.6  325.49  5469.4  329.69    5569  333.38  5667.8  336.21
#Mann= 7 ,-1 , 0
  4188.9      .1       0  4899.9     .12       0  4980.8     .07       0
  4989.4     .12       0  5117.3      .1       0  5247.6     .05       0
    5569      .1       0
Bank Sta=4980.8,4989.4
XS Rating Curve= 0 ,0
Exp/Cntr=0.3,0.1

Type RM Length L Ch R = 1 ,16045   ,375,375,375
BEGIN DESCRIPTION:
Fox Creek 26.0
END DESCRIPTION:
XS GIS Cut Line= 3
      2086625.02     13412524.99        2087975.       13411925.
        2088425.       13411475.
#Sta/Elev= 30
  3497.1  335.95  3737.8  332.15  3847.3  331.79  3882.1  330.16  4044.2  329.25
  4263.1  326.13  4460.1  328.92  4519.6  327.68  4687.8   320.2  4745.3  318.82
  4790.5  320.09    4815  320.82  4861.6  319.01    4960  318.94  4977.9  318.44
  4998.4  314.32  4999.1  313.52  5006.2  313.52    5007  314.32  5016.8  317.17
  5034.9  318.98  5158.3   326.4  5214.8  327.94  5313.8  332.83  5370.4  333.34
  5507.8  337.31  5509.1  337.35  5540.1   339.2  5582.5  343.54  5610.8  344.52
#Mann= 7 ,-1 , 0
  3497.1      .1       0  4790.5     .12       0  4998.4     .07       0
    5007     .12       0  5034.9      .1       0  5507.8     .05       0
  5509.1      .1       0
Bank Sta=4998.4,5007
XS Rating Curve= 0 ,0
Exp/Cntr=0.3,0.1

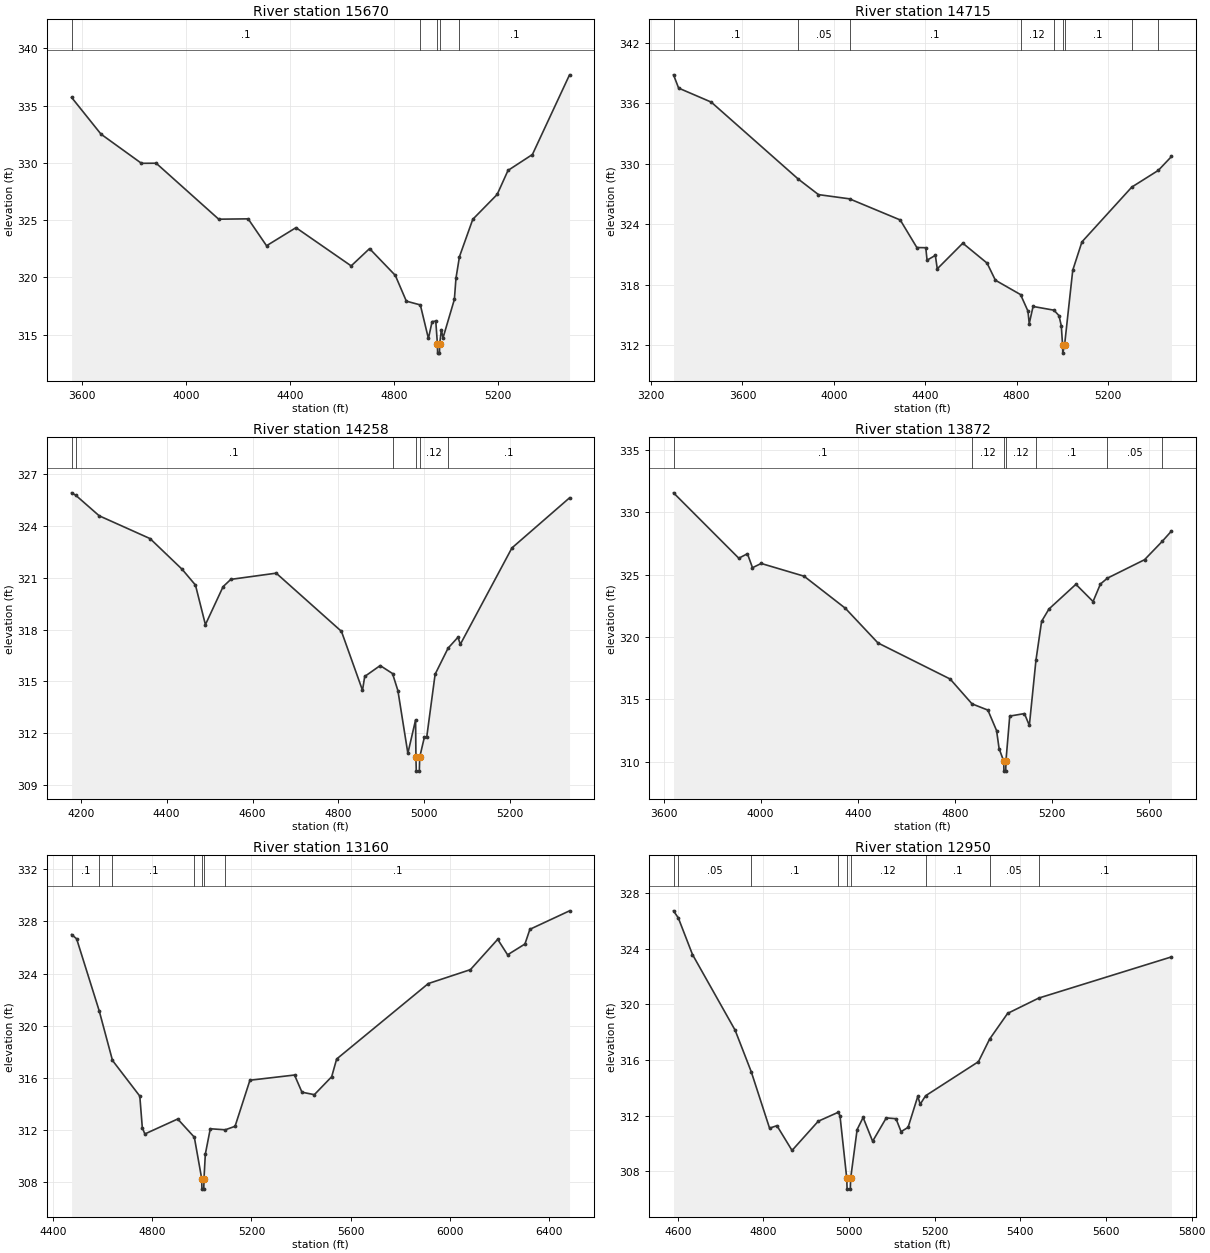
Type RM Length L Ch R = 1 ,15670   ,955,955,955
BEGIN DESCRIPTION:
Fox Creek 25.0
END DESCRIPTION:
XS GIS Cut Line= 3
      2087175.03     13413174.97        2088175.       13412175.
      2088475.02     13411774.98
#Sta/Elev= 30
  3559.5  335.72  3672.6  332.51  3828.2  329.96  3884.7  329.97  4125.1  325.08
  4238.3  325.11    4309  322.76  4422.1  324.34  4634.3     321    4705  322.51
    4804  320.17  4846.4  317.92  4900.2  317.59  4931.2  314.66  4945.4  316.13
  4959.5  316.18  4965.8  314.18  4966.6  313.38  4973.7  313.38  4974.5  314.18
    4981  315.43  4987.2   314.7    5031  318.07  5037.2  319.93  5050.6  321.81
  5101.8  325.07  5195.5  327.24  5237.2  329.34    5331  330.73  5473.7  337.69
#Mann= 5 ,-1 , 0
  3559.5      .1       0  4900.2     .12       0  4965.8     .07       0
  4974.5     .12       0  5050.6      .1       0
Bank Sta=4965.8,4974.5
XS Rating Curve= 0 ,0
Exp/Cntr=0.3,0.1

Type RM Length L Ch R = 1 ,14715   ,457,457,457
BEGIN DESCRIPTION:
Fox Creek 24.0
END DESCRIPTION:
XS GIS Cut Line= 3
      2087074.97     13413325.02        2088575.       13412575.
        2088625.     13412074.98
#Sta/Elev= 30
  3298.4  338.85  3320.8  337.53  3463.3  336.14  3844.7  328.48  3932.9  326.94
  4068.8  326.52  4290.7  324.42  4363.4  321.68  4402.5  321.66  4408.1  320.42
  4444.4   320.9  4452.8  319.56  4564.6  322.11  4670.8  320.13  4707.2  318.43
  4817.4     317  4849.7  315.36  4855.3  314.11  4872.1  315.82  4963.5  315.45
  4985.5  314.91  4995.6  313.91  5001.3  311.98  5002.1  311.18    5010  311.98
  5045.8  319.42    5086  322.24  5304.3  327.69  5420.3  329.35    5478  330.73
#Mann= 9 ,-1 , 0
  3298.4      .1       0  3844.7     .05       0  4068.8      .1       0
  4817.4     .12       0  4963.5      .1       0  5001.3     .07       0
    5010      .1       0  5304.3     .05       0  5420.3      .1       0
Bank Sta=5001.3,5010
XS Rating Curve= 0 ,0
Exp/Cntr=0.3,0.1

Type RM Length L Ch R = 1 ,14258   ,386,386,386
BEGIN DESCRIPTION:
Fox Creek 23.0
END DESCRIPTION:
XS GIS Cut Line= 3
      2087875.04     13412974.99        2088675.       13412775.
        2088825.     13412474.99
#Sta/Elev= 30
  4178.5  325.92  4188.2  325.78  4242.9  324.59  4361.4  323.27  4436.2  321.49
  4467.1  320.58  4490.3  318.29  4531.5  320.49  4549.5  320.91  4655.2  321.27
  4807.2   317.9  4856.2  314.49  4861.4  315.29  4897.4  315.92  4926.1  315.46
  4938.7  314.47  4961.9  310.84  4979.9  312.78  4980.7  310.61  4981.5  309.81
  4988.6  309.81  4989.4  310.61  5000.5  311.79  5005.9  311.79  5025.4  315.42
  5055.6  316.93  5078.6  317.56  5084.1  317.15  5204.3  322.73  5338.5  325.63
#Mann= 6 ,-1 , 0
  4178.5     .05       0  4188.2      .1       0  4926.1     .12       0
  4980.7     .07       0  4989.4     .12       0  5055.6      .1       0
Bank Sta=4980.7,4989.4
XS Rating Curve= 0 ,0
Exp/Cntr=0.3,0.1

Type RM Length L Ch R = 1 ,13872   ,712,712,712
BEGIN DESCRIPTION:
Fox Creek 22.0
END DESCRIPTION:
XS GIS Cut Line= 3
        2088075.       13413975.        2088975.       13412975.
        2089075.     13412274.97
#Sta/Elev= 30
  3640.9  331.55    3910  326.31  3945.5  326.67  3966.4  325.55  4002.3  325.89
    4179  324.87  4349.1   322.3  4483.6  319.52  4781.1  316.63  4871.2  314.64
  4936.6  314.14  4972.4   312.5  4982.9  311.05  5001.9  310.05  5002.8  309.25
  5010.2  309.25    5011  310.05  5026.7  313.66  5087.3  313.86  5107.5  312.91
  5134.7  318.13    5158  321.25  5188.3  322.24  5299.4  324.22  5370.1  322.84
  5400.4  324.24    5429  324.71  5582.3  326.19  5654.7  327.65  5693.4  328.49
#Mann= 7 ,-1 , 0
  3640.9      .1       0  4871.2     .12       0  5001.9     .07       0
    5011     .12       0  5134.7      .1       0    5429     .05       0
  5654.7      .1       0
Bank Sta=5001.9,5011
XS Rating Curve= 0 ,0
Exp/Cntr=0.3,0.1

Type RM Length L Ch R = 1 ,13160   ,210,210,210
BEGIN DESCRIPTION:
Fox Creek 21.0
END DESCRIPTION:
XS GIS Cut Line= 3
      2089174.99     13414025.04        2089275.       13413525.
        2089275.     13412025.04
#Sta/Elev= 30
  4473.8     327  4494.2  326.67  4585.1  321.15    4639  317.32  4749.2  314.58
  4759.4  312.14  4769.6  311.67  4902.2  312.82  4969.3  311.42  4999.1  308.23
    5000  307.43  5007.4  307.43  5008.3  308.23  5013.7  310.12  5033.7  312.07
  5094.3  311.99  5133.7  312.26  5193.7   315.8  5373.7   316.2  5403.7  314.88
  5453.7  314.69  5523.7  316.07  5543.7  317.43  5913.7  323.23  6083.7   324.3
  6193.7  326.63  6233.7  325.44  6303.7  326.27  6323.7   327.4  6483.7  328.82
#Mann= 7 ,-1 , 0
  4473.8      .1       0  4585.1     .05       0    4639      .1       0
  4969.3     .12       0  4999.1     .07       0  5008.3     .12       0
  5094.3      .1       0
Bank Sta=4999.1,5008.3
XS Rating Curve= 0 ,0
Exp/Cntr=0.3,0.1

Type RM Length L Ch R = 1 ,12950   ,556,556,556
BEGIN DESCRIPTION:
Fox Creek 20.0
END DESCRIPTION:
XS GIS Cut Line= 3
      2089224.98     13414025.04       2089400.8     13413654.54
      2089724.99     13412975.01
#Sta/Elev= 30
  4589.9  326.72  4601.1  326.21  4634.2  323.58  4733.8  318.14  4771.5  315.15
  4814.2   311.1  4831.4  311.28  4866.7   309.5  4927.9   311.6  4975.1  312.25
  4978.8  311.96  4994.4  307.52  4995.3  306.72  5002.8  306.72  5003.7  307.52
  5018.7     311  5032.7  311.87  5054.9  310.16  5086.8  311.84  5109.5  311.78
  5121.4  310.85  5137.7  311.16  5160.4  313.39    5166  312.82  5178.6  313.43
  5302.1  315.88  5327.9  317.49  5370.2  319.35  5442.9  320.45  5752.9  323.41
#Mann= 9 ,-1 , 0
  4589.9      .1       0  4601.1     .05       0  4771.5      .1       0
  4975.1     .12       0  4994.4     .07       0  5003.7     .12       0
  5178.6      .1       0  5327.9     .05       0  5442.9      .1       0
Bank Sta=4994.4,5003.7
XS Rating Curve= 0 ,0
Exp/Cntr=0.3,0.1

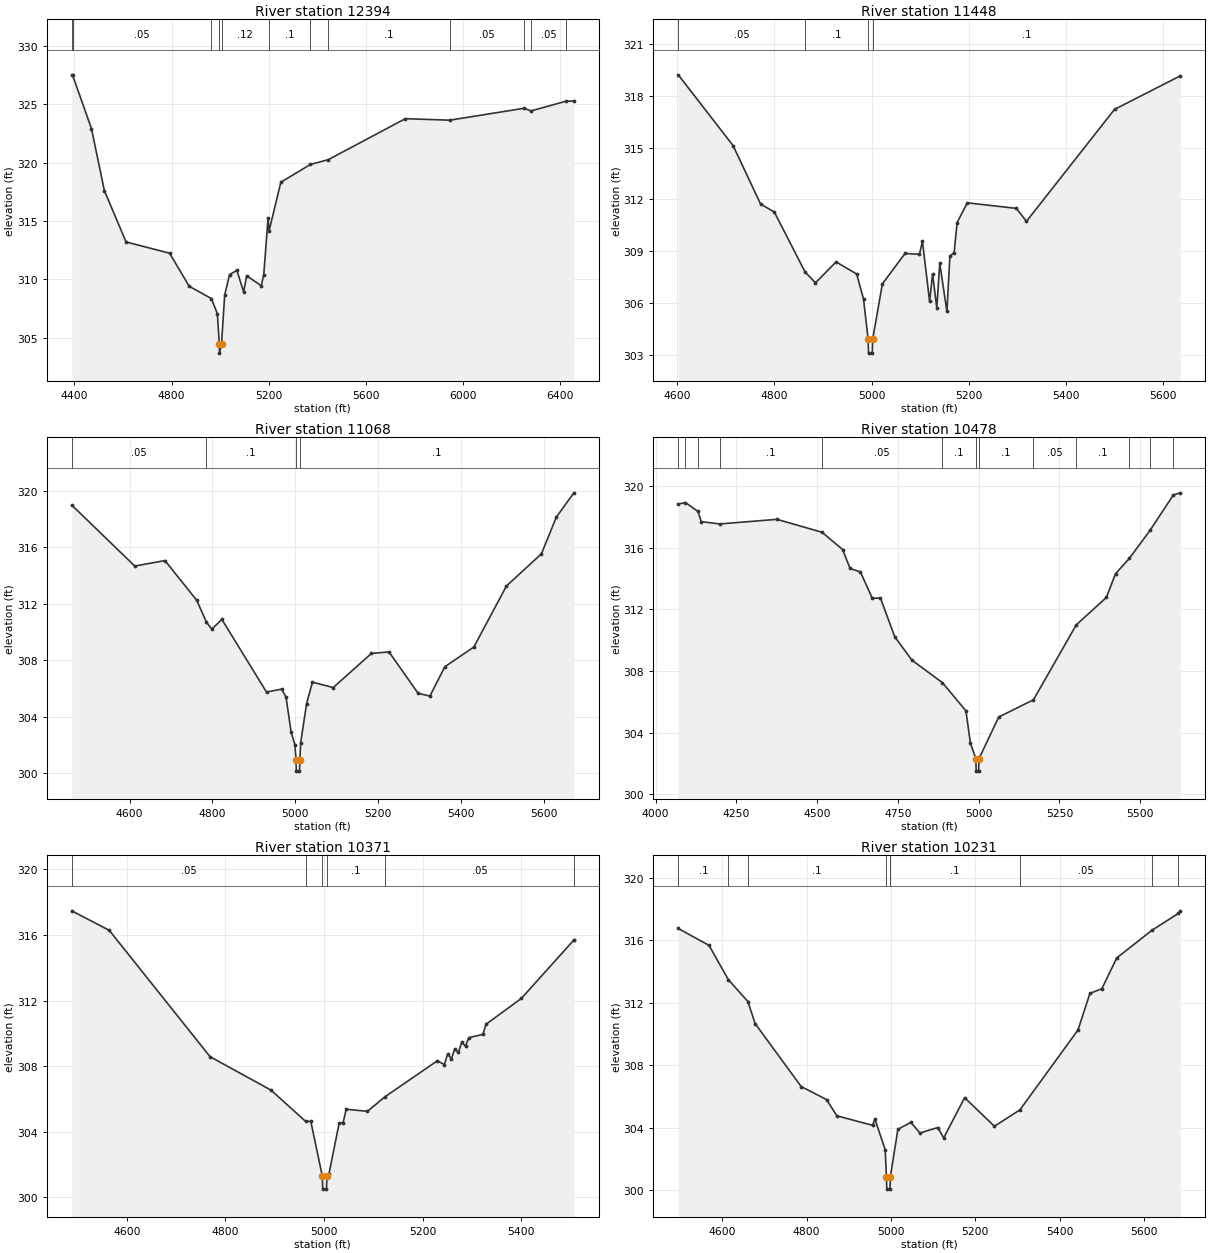
Type RM Length L Ch R = 1 ,12394   ,946,946,946
BEGIN DESCRIPTION:
Fox Creek 19.0
END DESCRIPTION:
XS GIS Cut Line= 3
        2089225.       13414075.        2089725.       13413825.
        2089875.       13412325.
#Sta/Elev= 30
  4389.4  327.51  4392.7  327.48  4470.5  322.91  4523.6   317.6    4613  313.21
  4791.9  312.25  4872.9  309.42  4963.9  308.37  4988.6  307.08  4996.5   304.5
  4997.4   303.7  5005.8   304.5  5018.8  308.67  5038.9  310.42    5069  310.78
  5096.7  308.94  5109.2  310.31  5169.5  309.47  5179.6  310.41  5197.2  315.23
  5201.8  314.18  5249.9  318.32  5371.3  319.84  5445.1  320.25  5762.5  323.76
  5944.7  323.63  6251.7  324.65  6279.2  324.42  6423.4  325.25  6455.9  325.27
#Mann= 12 ,-1 , 0
  4389.4      .1       0  4392.7     .05       0  4963.9     .12       0
  4996.5     .07       0  5005.8     .12       0  5201.8      .1       0
  5371.3     .05       0  5445.1      .1       0  5944.7     .05       0
  6251.7      .1       0  6279.2     .05       0  6423.4      .1       0
Bank Sta=4996.5,5005.8
XS Rating Curve= 0 ,0
Exp/Cntr=0.3,0.1

Type RM Length L Ch R = 1 ,11448   ,380,380,380
BEGIN DESCRIPTION:
Fox Creek 18.0
END DESCRIPTION:
XS GIS Cut Line= 3
      2089825.01     13414374.99        2090125.       13414075.
      2090475.01     13413574.98
#Sta/Elev= 30
  4601.7  319.21  4714.8  315.11  4771.4  311.73  4799.7  311.27    4863   307.8
  4884.5  307.17    4927  308.38  4969.4  307.68  4983.5  306.23    4993   303.9
  4993.9   303.1  5001.4   303.1  5002.3   303.9  5022.4  307.11  5069.1  308.87
  5098.8  308.82  5104.9  309.58  5119.7  306.09  5125.8  307.68  5134.5  305.72
  5140.6   308.3  5155.4  305.51  5161.5  308.72  5170.2  308.92  5176.4  310.66
  5197.3   311.8  5298.4  311.48  5319.3  310.73  5500.7  317.21  5636.3  319.15
#Mann= 4 ,-1 , 0
  4601.7     .05       0    4863      .1       0    4993     .07       0
  5002.3      .1       0
Bank Sta=4993,5002.3
XS Rating Curve= 0 ,0
Exp/Cntr=0.3,0.1

Type RM Length L Ch R = 1 ,11068   ,590,590,590
BEGIN DESCRIPTION:
Fox Creek 17.0
END DESCRIPTION:
XS GIS Cut Line= 3
      2089925.03     13414474.99        2090425.       13414275.
      2090875.02     13413774.97
#Sta/Elev= 30
  4460.6  318.97  4612.7  314.66  4685.4  315.05  4762.1  312.24  4785.5  310.69
  4798.5   310.2  4822.7  310.89  4930.4  305.75  4966.8  305.96  4977.5   305.4
  4989.7  302.93  4999.1     302  5001.5  300.96  5002.4  300.16  5009.9  300.16
  5010.8  300.96  5012.9  302.18  5027.1  304.94  5041.3  306.45  5091.4  306.07
  5183.3  308.48  5225.9  308.59  5296.2  305.66  5324.6  305.47  5360.5  307.54
  5430.7  308.94  5509.2  313.25  5593.7  315.53  5629.5  318.12  5671.8  319.84
#Mann= 4 ,-1 , 0
  4460.6     .05       0  4785.5      .1       0  5001.5     .07       0
  5010.8      .1       0
Bank Sta=5001.5,5010.8
XS Rating Curve= 0 ,0
Exp/Cntr=0.3,0.1

Type RM Length L Ch R = 1 ,10478   ,107,107,107
BEGIN DESCRIPTION:
Fox Creek 16.0
END DESCRIPTION:
XS GIS Cut Line= 3
        2089875.       13414725.       2090749.1     13414407.43
      2091211.49     13413987.82
#Sta/Elev= 30
    4070  318.84  4092.4  318.94  4131.2  318.36  4141.2   317.7  4198.2  317.55
  4375.4  317.85  4515.4  317.01  4578.9  315.89    4602  314.66  4633.9  314.44
  4670.7  312.73    4696  312.74  4740.3  310.23  4793.5  308.71    4888  307.25
  4960.8  305.42  4974.4  303.34  4991.5  302.31  4992.4  301.51    5000  301.51
  5000.9  302.31  5062.2  305.02  5169.8  306.14  5302.3     311  5395.4  312.78
  5423.8  314.32  5466.4  315.31  5530.6  317.13  5602.9  319.43  5624.4  319.57
#Mann= 13 ,-1 , 0
    4070     .05       0  4092.4      .1       0  4131.2     .05       0
  4198.2      .1       0  4515.4     .05       0    4888      .1       0
  4991.5     .07       0  5000.9      .1       0  5169.8     .05       0
  5302.3      .1       0  5466.4     .08       0  5530.6      .1       0
  5602.9     .05       0
Bank Sta=4991.5,5000.9
XS Rating Curve= 0 ,0
Exp/Cntr=0.3,0.1

Type RM Length L Ch R = 1 ,10371   ,140,140,140
BEGIN DESCRIPTION:
Mapping XS 9bf38e87
END DESCRIPTION:
XS GIS Cut Line= 3
      2090378.99      13414730.9      2090827.73     13414473.57
      2091211.47     13414151.45
#Sta/Elev= 30
  4488.5  317.47  4564.6  316.28    4769  308.58  4892.7  306.54  4962.8  304.64
  4973.3  304.64  4996.6  301.31  4997.5  300.51  5005.1  300.51    5006  301.31
    5010  301.42  5030.9  304.54  5038.7  304.55  5045.2  305.38  5088.1  305.25
  5123.8  306.14  5229.9  308.33  5244.2   308.1  5250.7  308.73  5258.5  308.46
    5265  309.04  5272.8  308.85  5279.3  309.45  5287.1  309.23  5293.6  309.74
  5322.3  309.94  5328.8  310.56  5400.3  312.13  5506.5  315.68  5506.8  315.69
#Mann= 6 ,-1 , 0
  4488.5     .05       0  4962.8      .1       0  4996.6     .07       0
    5006      .1       0  5123.8     .05       0  5506.5     .08       0
Bank Sta=4996.6,5006
XS Rating Curve= 0 ,0
Exp/Cntr=0.3,0.1

Type RM Length L Ch R = 1 ,10231   ,711,711,711
BEGIN DESCRIPTION:
Fox Creek 15.0
END DESCRIPTION:
XS GIS Cut Line= 3
      2090430.24      13414765.6        2090925.       13414575.
      2091391.74     13414108.79
#Sta/Elev= 30
  4495.9  316.74  4568.9  315.66  4614.6  313.47    4661  312.07  4678.1  310.66
  4787.3  306.63  4847.3   305.8  4871.9  304.76  4956.5  304.15  4961.9  304.56
  4986.5  302.58  4989.3  300.87  4990.2  300.07  4997.8  300.07  4998.7  300.87
  5016.5   303.9  5047.3  304.34  5068.5  303.66  5110.9  304.01  5125.1  303.35
  5174.6  305.92  5245.3  304.09  5305.7  305.14  5443.3  310.25  5471.6  312.59
  5499.9  312.89  5535.2  314.86  5619.3  316.64  5681.5  317.71  5685.8  317.87
#Mann= 8 ,-1 , 0
  4495.9      .1       0  4614.6     .05       0    4661      .1       0
  4989.3     .07       0  4998.7      .1       0  5305.7     .05       0
  5619.3     .08       0  5681.5     .05       0
Bank Sta=4989.3,4998.7
XS Rating Curve= 0 ,0
Exp/Cntr=0.3,0.1

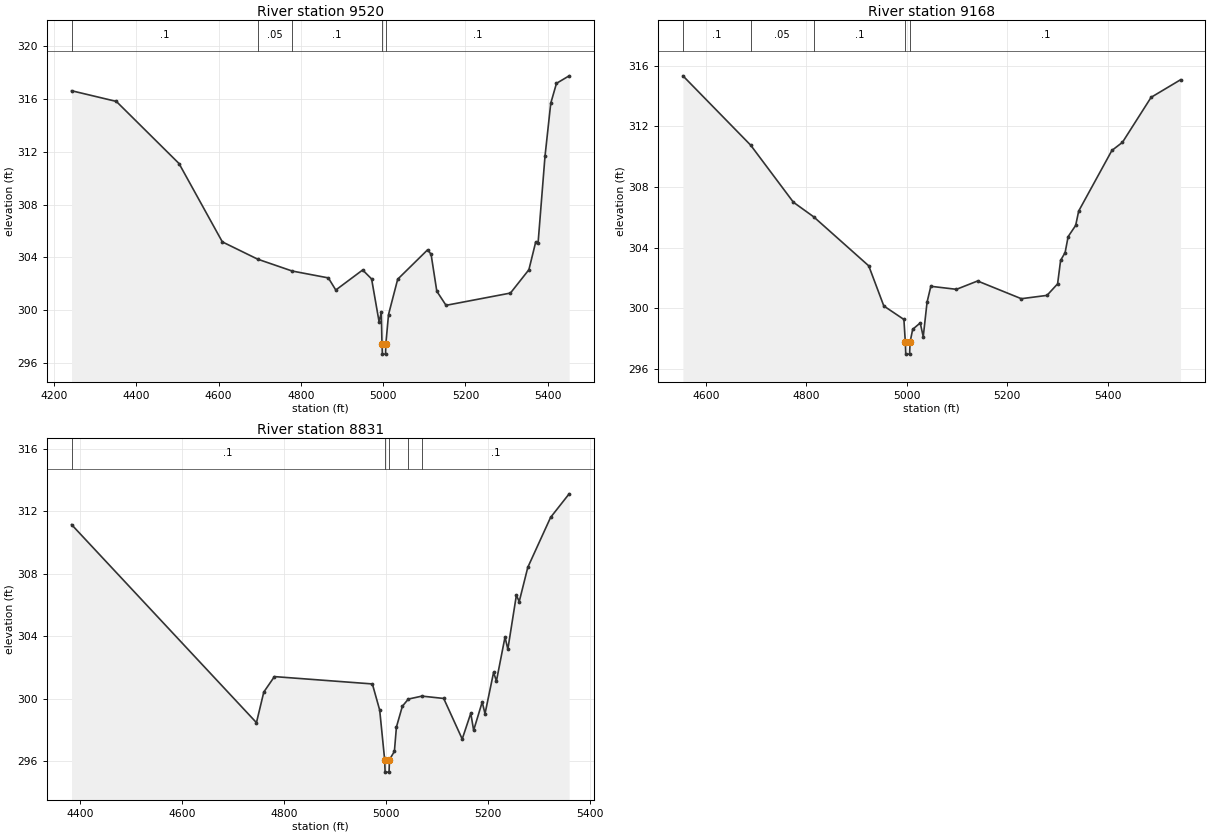
Type RM Length L Ch R = 1 ,9520    ,352,352,352
BEGIN DESCRIPTION:
Fox Creek 14.0
END DESCRIPTION:
XS GIS Cut Line= 3
      2090575.01       13415075.        2091275.       13414775.
      2091675.01     13414574.99
#Sta/Elev= 30
    4243  316.63  4351.8  315.82  4504.1  311.11  4609.3  305.17  4695.1  303.86
    4779  302.96  4866.8  302.44  4884.9  301.52  4950.2  303.04  4971.9  302.36
  4990.1  299.11  4995.5  299.85  4997.1  297.46  4998.1  296.66  5005.7  296.66
  5006.6  297.46    5013  299.66  5035.3  302.34    5108  304.57  5116.4  304.23
  5130.3  301.43  5152.7  300.36  5309.2  301.29    5354  303.06  5370.7  305.18
  5376.3  305.08  5393.1  311.65  5407.1  315.68    5421  317.19  5451.8  317.76
#Mann= 5 ,-1 , 0
    4243      .1       0  4695.1     .05       0    4779      .1       0
  4997.1     .07       0  5006.6      .1       0
Bank Sta=4997.1,5006.6
XS Rating Curve= 0 ,0
Exp/Cntr=0.3,0.1

Type RM Length L Ch R = 1 ,9168    ,337,337,337
BEGIN DESCRIPTION:
Fox Creek 13.0
END DESCRIPTION:
XS GIS Cut Line= 3
        2090775.       13415075.        2091225.       13415075.
      2091674.97     13414775.02
#Sta/Elev= 30
  4554.2  315.34  4689.1  310.76  4774.2  306.99  4814.5  306.03  4924.2  302.79
  4954.2  300.14  4994.2  299.25    4997  297.76  4997.9  296.96  5005.5  296.96
  5006.5  297.76  5011.7   298.6  5026.7  299.02  5032.7  298.11  5040.3  300.39
  5047.8  301.44  5098.8  301.24  5140.9  301.79    5228  300.62  5279.1  300.84
  5300.2   301.6  5306.2  303.15  5315.2  303.67  5321.2  304.72  5336.2  305.46
  5342.2  306.41  5408.3  310.41  5429.4  310.95  5486.4  313.92    5545  315.08
#Mann= 5 ,-1 , 0
  4554.2      .1       0  4689.1     .05       0  4814.5      .1       0
    4997     .07       0  5006.5      .1       0
Bank Sta=4997,5006.5
XS Rating Curve= 0 ,0
Exp/Cntr=0.3,0.1

Type RM Length L Ch R = 1 ,8831    ,372,372,372
BEGIN DESCRIPTION:
Fox Creek 12.0
END DESCRIPTION:
XS GIS Cut Line= 3
      2090924.98     13415675.02        2091425.       13415275.
      2091725.04     13415124.98
#Sta/Elev= 30
  4383.1  311.15  4745.7  298.46  4760.1  300.42  4780.9  301.41    4973  300.94
  4987.4  299.26  4997.1  296.09    4998  295.29  5005.7  295.29  5006.6  296.09
  5016.2  296.62  5020.2  298.18  5031.8  299.51  5043.5  299.97  5070.2  300.16
  5112.9  300.01  5149.2  297.41    5166  299.06  5171.6  297.97  5188.4  299.78
  5193.9  299.03  5210.7  301.68  5216.3  301.13  5233.1  303.94  5238.7  303.17
  5255.4  306.62    5261  306.22  5277.8  308.41  5322.5  311.61  5358.9  313.12
#Mann= 5 ,-1 , 0
  4383.1      .1       0  4997.1     .07       0  5006.6      .1       0
  5043.5     .12       0  5070.2      .1       0
Bank Sta=4997.1,5006.6
XS Rating Curve= 0 ,0
Exp/Cntr=0.3,0.1