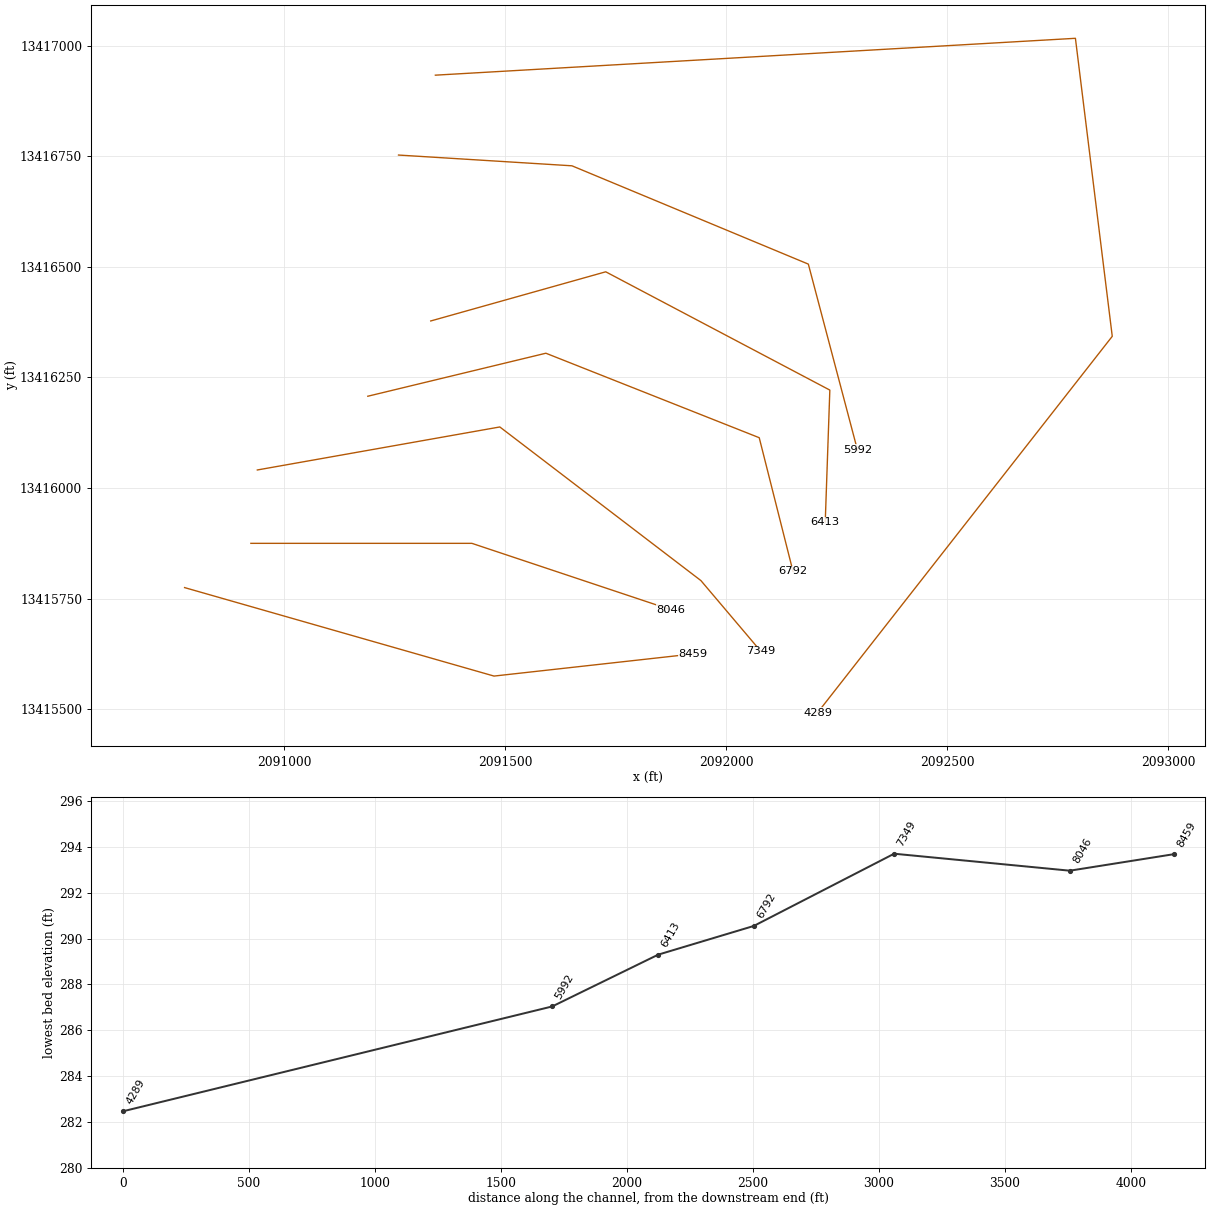
HEC-RAS study Fox Creek.prj: Fox Creek Base Level Engineering

--- Fox Creek.g01 (geometry) --- (continued)

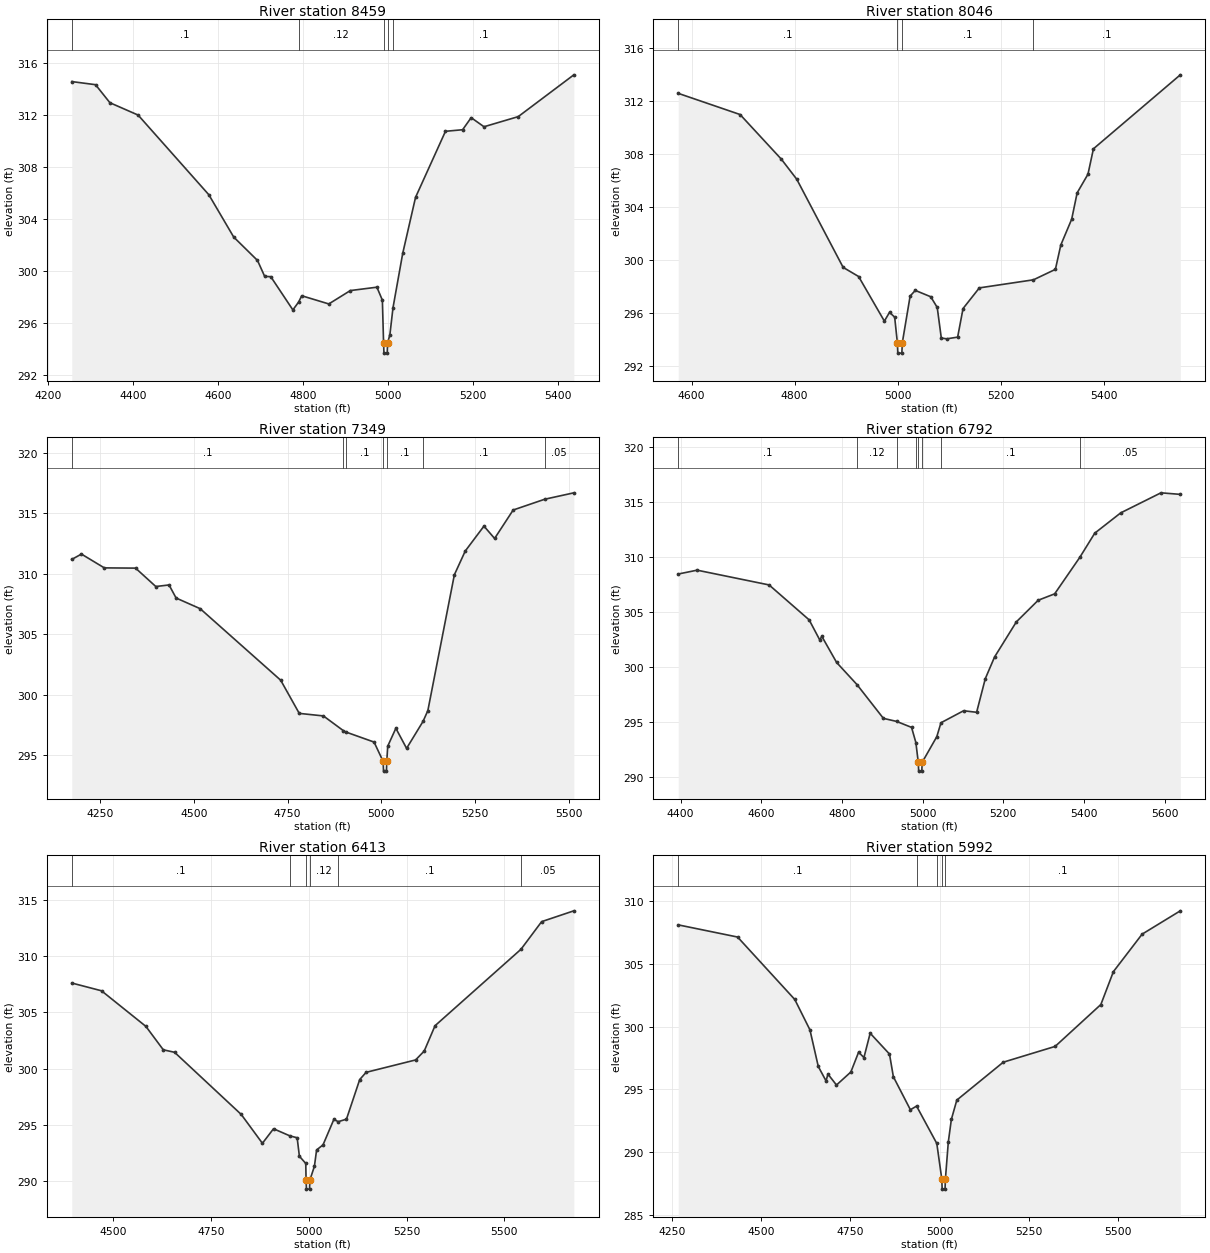
Type RM Length L Ch R = 1 ,8459    ,413,413,413
BEGIN DESCRIPTION:
Fox Creek 11.0
END DESCRIPTION:
XS GIS Cut Line= 3
      2090775.01       13415775.        2091475.       13415575.
      2091925.03       13415625.
#Sta/Elev= 30
  4256.1   314.6    4312  314.36  4345.8  312.97  4412.1  312.02  4578.5  305.88
    4637  302.62  4692.9  300.82  4709.8  299.59  4724.1  299.57  4776.1  297.01
  4789.7  297.62  4796.9   298.1  4860.6  297.47  4911.3   298.5  4973.7  298.76
  4986.6  297.76  4989.4  294.48  4990.3  293.68    4998  293.68  4998.9  294.48
  5004.2  295.08  5011.6  297.18  5034.4  301.36  5064.6  305.68    5135  310.77
  5175.3  310.89  5195.4  311.82  5225.6  311.12  5306.1   311.9  5436.9  315.12
#Mann= 5 ,-1 , 0
  4256.1      .1       0  4789.7     .12       0  4989.4     .07       0
  4998.9     .12       0  5011.6      .1       0
Bank Sta=4989.4,4998.9
XS Rating Curve= 0 ,0
Exp/Cntr=0.3,0.1

Type RM Length L Ch R = 1 ,8046    ,697,697,697
BEGIN DESCRIPTION:
Fox Creek 10.0
END DESCRIPTION:
XS GIS Cut Line= 3
        2090925.       13415875.        2091425.       13415875.
      2091874.96     13415725.01
#Sta/Elev= 30
  4574.2  312.59  4694.2  310.99  4774.2  307.62  4804.2   306.1  4894.2  299.44
  4924.2  298.75  4974.2  295.38  4984.2  296.04  4994.2  295.68  4999.4  293.76
  5000.3  292.96  5008.1  292.96  5009.1  293.76  5024.2  297.27  5034.2   297.7
  5064.2  297.22  5076.8  296.41  5084.7   294.1  5095.3  294.04  5116.4  294.17
  5126.9  296.33  5158.5  297.89  5263.5   298.5  5306.1  299.29  5316.6  301.13
  5337.7  303.08  5348.3  305.07  5369.3  306.48  5379.9   308.4  5548.5  313.99
#Mann= 4 ,-1 , 0
  4574.2      .1       0  4999.4     .07       0  5009.1      .1       0
  5263.5      .1       0
Bank Sta=4999.4,5009.1
XS Rating Curve= 0 ,0
Exp/Cntr=0.3,0.1

Type RM Length L Ch R = 1 ,7349    ,557,557,557
BEGIN DESCRIPTION:
Mapping XS 3e907dfa
END DESCRIPTION:
XS GIS Cut Line= 4
      2090939.56     13416040.84      2091488.16     13416138.06
      2091943.02     13415790.84      2092078.44     13415631.11
#Sta/Elev= 30
  4174.5  311.19  4200.3  311.63  4261.3  310.49  4344.6  310.47  4398.6  308.95
  4433.9  309.08  4452.7     308  4516.9  307.12  4731.6  301.21  4781.1  298.47
  4845.5  298.26  4898.4  297.05  4905.5  296.93  4980.6   296.1  5004.8   294.5
  5005.8   293.7  5013.6   293.7  5014.5   294.5    5017  295.76  5038.7  297.24
  5067.3  295.58  5111.2  297.81    5124   298.7  5194.7  309.92  5223.7  311.88
  5273.6  313.94    5302  312.92  5351.5  315.27  5435.5  316.16  5513.3  316.69
#Mann= 7 ,-1 , 0
  4174.5      .1       0  4898.4     .12       0  4905.5      .1       0
  5004.8     .07       0  5014.5      .1       0  5111.2      .1       0
  5435.5     .05       0
Bank Sta=5004.8,5014.5
XS Rating Curve= 0 ,0
Exp/Cntr=0.3,0.1

Type RM Length L Ch R = 1 ,6792    ,379,379,379
BEGIN DESCRIPTION:
Mapping XS 93ecffb3
END DESCRIPTION:
XS GIS Cut Line= 4
       2091189.5      13416207.5      2091592.32     13416304.73
      2092074.96     13416113.76      2092151.34      13415811.7
#Sta/Elev= 30
    4394  308.44  4440.8  308.79  4619.3  307.45  4718.6  304.28  4744.9  302.46
  4750.1  302.78  4786.8  300.41  4837.1  298.41  4902.7  295.34  4935.6  295.06
  4972.6  294.52  4983.3  293.14  4989.2  291.35  4990.2  290.55    4998  290.55
  4998.9  291.35  5035.2  293.68  5045.5  294.94  5101.6  296.03  5133.9  295.89
  5155.4  298.94  5178.4  300.91  5232.5   304.1  5286.6  306.06  5327.4  306.64
  5389.7  309.95  5426.9  312.15  5491.2  313.99    5591  315.81    5639  315.67
#Mann= 8 ,-1 , 0
    4394      .1       0  4837.1     .12       0  4935.6      .1       0
  4983.3     .12       0  4989.2     .07       0  4998.9     .12       0
  5045.5      .1       0  5389.7     .05       0
Bank Sta=4989.2,4998.9
XS Rating Curve= 0 ,0
Exp/Cntr=0.3,0.1

Type RM Length L Ch R = 1 ,6413    ,421,421,421
BEGIN DESCRIPTION:
Mapping XS a0cda1f5
END DESCRIPTION:
XS GIS Cut Line= 4
      2091331.86     13416377.63      2091727.74     13416488.76
      2092234.69      13416221.4      2092224.27     13415922.78
#Sta/Elev= 30
  4394.3   307.6  4470.3  306.91  4583.7  303.75  4628.2  301.67    4657  301.45
  4827.4  295.93  4881.5  293.37  4909.9  294.66  4951.6  294.03  4970.3  293.86
    4976  292.22  4992.3  291.58  4993.1   290.1  4994.1   289.3  5001.9   289.3
  5002.8   290.1  5014.4  291.33    5020  292.78  5036.4  293.23  5064.1  295.49
  5075.2  295.29  5096.3  295.51  5130.2  299.03  5146.5  299.67    5273  300.77
    5295  301.56  5322.7  303.81  5542.4   310.6  5595.1  313.05  5677.4  314.01
#Mann= 6 ,-1 , 0
  4394.3      .1       0  4951.6     .12       0  4993.1     .07       0
  5002.8     .12       0  5075.2      .1       0  5542.4     .05       0
Bank Sta=4993.1,5002.8
XS Rating Curve= 0 ,0
Exp/Cntr=0.3,0.1

Type RM Length L Ch R = 1 ,5992    ,1703,1703,1703
BEGIN DESCRIPTION:
Mapping XS 63a73e6d
END DESCRIPTION:
XS GIS Cut Line= 4
      2091258.99     13416752.65      2091651.35     13416728.34
      2092186.07     13416506.12       2092297.2     13416085.94
#Sta/Elev= 30
  4267.8  308.11  4434.1  307.14  4594.4  302.16  4636.8  299.74  4660.2  296.82
  4681.9  295.67  4687.3  296.21  4711.2  295.34  4751.5  296.38  4773.2  297.96
  4788.1  297.53  4805.6  299.47  4859.7  297.81  4870.6     296  4918.3  293.37
  4935.6  293.66  4992.3  290.68  5006.3  287.84  5007.3  287.04  5015.4  287.04
  5016.4  287.84  5024.5  290.79  5033.1   292.6  5048.4  294.14  5178.5  297.16
  5323.9  298.42    5452  301.76  5487.1  304.38  5567.6  307.37  5674.6  309.23
#Mann= 5 ,-1 , 0
  4267.8      .1       0  4935.6     .12       0  4992.3      .1       0
  5006.3     .07       0  5016.4      .1       0
Bank Sta=5006.3,5016.4
XS Rating Curve= 0 ,0
Exp/Cntr=0.3,0.1

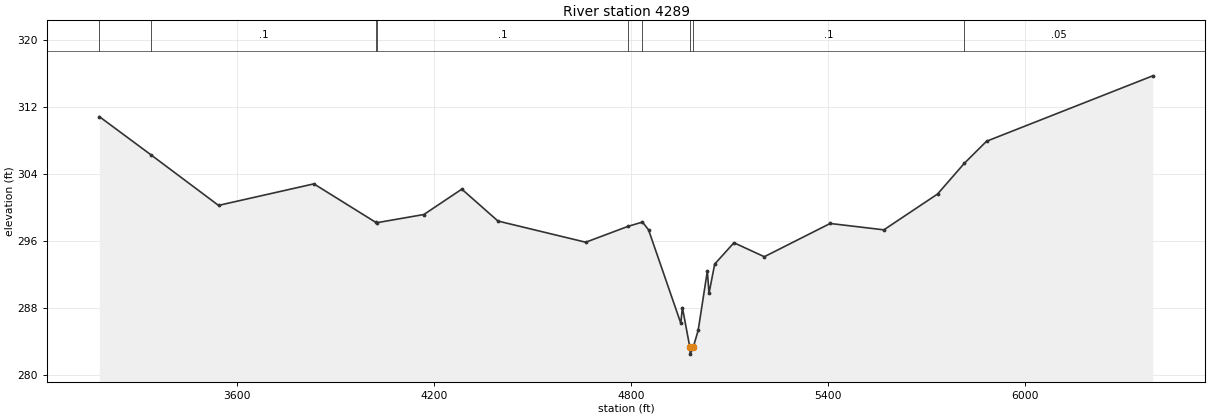
Type RM Length L Ch R = 1 ,4289    ,0,0,0
BEGIN DESCRIPTION:
Fox Creek 9.0
END DESCRIPTION:
XS GIS Cut Line= 4
      2091342.35      13416933.2      2092790.24     13417016.53
      2092873.57     13416342.92      2092206.93     13415492.25
#Sta/Elev= 30
  3180.1  310.83  3336.3   306.3  3543.3  300.23  3833.8   302.8    4023  298.19
  4025.3  298.16    4169  299.14  4284.6  302.17  4394.8  298.36  4662.2  295.83
  4791.3  297.73    4835  298.24  4853.6  297.31  4951.8  286.17  4956.8  288.03
  4979.5  283.27  4980.5  282.47  4989.6  283.27  5004.8  285.31  5032.8   292.4
  5037.8  289.72  5055.1  293.22  5113.8  295.77  5206.3   294.1    5407  298.07
  5570.6  297.31  5734.3  301.59  5815.9  305.26  5883.5  307.89  6389.9   315.7
#Mann= 9 ,-1 , 0
  3180.1     .05       0  3336.3      .1       0    4023     .05       0
  4025.3      .1       0  4791.3     .05       0    4835      .1       0
  4979.5     .07       0  4989.6      .1       0  5815.9     .05       0
Bank Sta=4979.5,4989.6
XS Rating Curve= 0 ,0
Exp/Cntr=0.3,0.1
LCMann Table=0

Chan Stop Cuts=-1
Use User Specified Reach Order=0
Composite Channel Slope=5