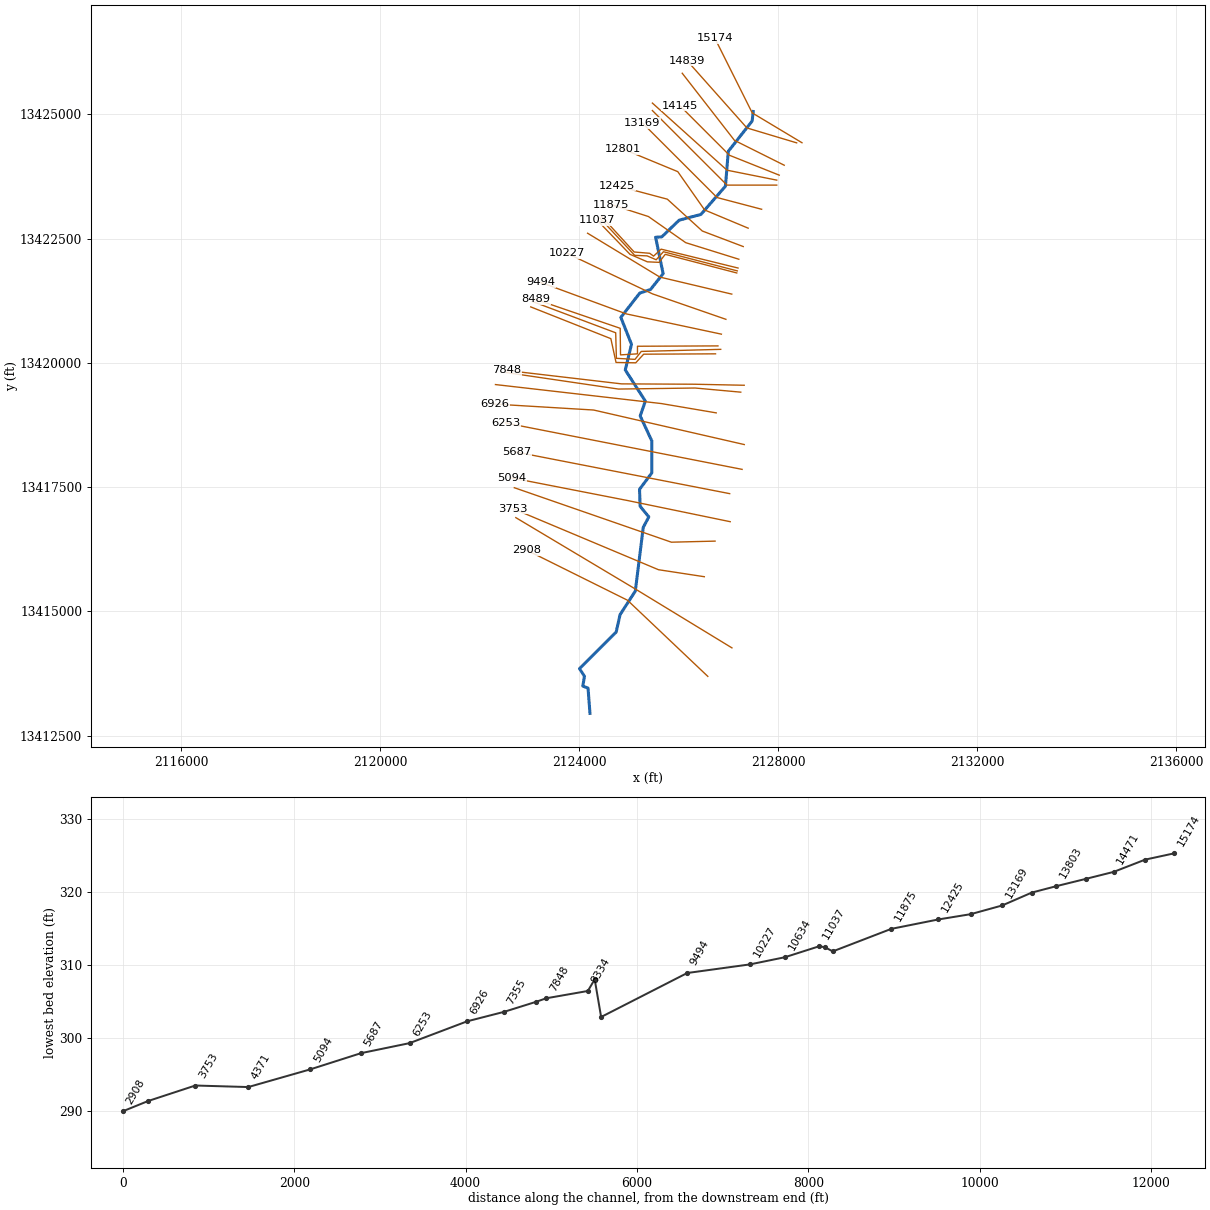
--- Hog Creek.prj (project) ---

Proj Title=Hog Creek Base Level Engineering
Current Plan=p01
Default Exp/Contr=0.3,0.1
English Units
Geom File=g01
Flow File=f01
Plan File=p01
Y Axis Title=Elevation
X Axis Title(PF)=Main Channel Distance
X Axis Title(XS)=Station
BEGIN DESCRIPTION:
Hog Creek
END DESCRIPTION:
DSS Export Rating Curves= 0
DSS Export Rating Curve Sorted= 0
DSS Export Volume Flow Curves= 0
DXF OffsetX= 0
DXF OffsetY= 0
DXF ScaleX= 1
DXF ScaleY= 10

--- Hog Creek.p01 (plan) ---

Plan Title=Multiple Run
Short Identifier=Multiple
Geom File=g01
Flow File=f01
Subcritical Flow
K Sum by GR= 0
Std Step Tol= 0.01
Critical Tol= 0.01
Num of Std Step Trials= 20
Max Error Tol= 0.3
Flow Tol Ratio= 0.001
Split Flow NTrial= 30
Split Flow Tol= 0.02
Split Flow Ratio= 0.02
Log Output Level= 0
Friction Slope Method= 1
Unsteady Friction Slope Method= 2
Unsteady Bridges Friction Slope Method= 1
Parabolic Critical Depth
Global Vel Dist=  1 , 1 , 1
Global Log Level= 0
CheckData=True
Encroach Param= -1, 0, 0, 0
BEGIN DESCRIPTION:
Multiple Run
END DESCRIPTION:

--- Hog Creek.f01 (steady flow) ---

Flow Title=Multiple
Program Version=5.05
Number of Profiles= 7
Profile Names=10-year,25-year,50-year,1pct_min,100-year,1pct_plu,500-year
River Rch & RM=Hog Creek,Reach-1         ,15174
     155     208     250     150     299     598     436
River Rch & RM=Hog Creek,Reach-1         ,14471
     250     343     419     256     510    1017     765
River Rch & RM=Hog Creek,Reach-1         ,10634
     297     410     503     308     614    1224     927
River Rch & RM=Hog Creek,Reach-1         ,4371
     368     514     636     391     780    1557    1194
River Rch & RM=Hog Creek,Reach-1         ,3202
     461     651     811     502    1002    1999    1554
River Rch & RM=Hog Creek,Reach-1         ,2908
     461     651     811     502    1002    1999    1554
River Rch & RM=Hog Creek,Reach-1         ,2213
     461     651     811     502    1002    1999    1554
Boundary for River Rch & Prof#=Hog Creek,Reach-1         , 1
Up Type= 0
Dn Type= 3
Dn Slope=0.005
Boundary for River Rch & Prof#=Hog Creek,Reach-1         , 2
Up Type= 0
Dn Type= 3
Dn Slope=0.005
Boundary for River Rch & Prof#=Hog Creek,Reach-1         , 3
Up Type= 0
Dn Type= 3
Dn Slope=0.005
Boundary for River Rch & Prof#=Hog Creek,Reach-1         , 4
Up Type= 0
Dn Type= 3
Dn Slope=0.005
Boundary for River Rch & Prof#=Hog Creek,Reach-1         , 5
Up Type= 0
Dn Type= 3
Dn Slope=0.005
Boundary for River Rch & Prof#=Hog Creek,Reach-1         , 6
Up Type= 0
Dn Type= 3
Dn Slope=0.005
Boundary for River Rch & Prof#=Hog Creek,Reach-1         , 7
Up Type= 0
Dn Type= 3
Dn Slope=0.005
DSS Import GetInterval= 0
DSS Import GetPeak= 0
DSS Import FillOption= 0

--- Hog Creek.g01 (geometry) ---

Geom Title=Existing Conditions

River Reach=Hog Creek,Reach-1
Reach XY= 30
      2127500.80     13425055.69      2127480.80     13424864.54
      2127000.80     13424254.54      2126943.64     13423553.46
      2126449.89     13422984.71      2126014.47     13422870.13
      2125663.26     13422533.58      2125540.00     13422525.77
      2125690.80     13421794.54      2125437.56     13421475.42
      2125221.42     13421403.37      2124840.80     13420914.54
      2125055.16     13420372.82      2124930.38     13419856.33
      2125333.94     13419230.49      2125229.78     13418932.31
      2125464.15     13418428.40      2125462.89     13417785.26
      2125216.80     13417455.83      2125228.52     13417114.69
      2125403.00     13416901.15      2125291.02     13416690.21
      2125132.17     13415408.96      2124826.18     13414936.30
      2124746.66     13414583.26      2124009.86     13413848.37
      2124110.55     13413694.72      2124075.83     13413498.54
      2124181.73     13413456.01      2124220.80     13412949.06

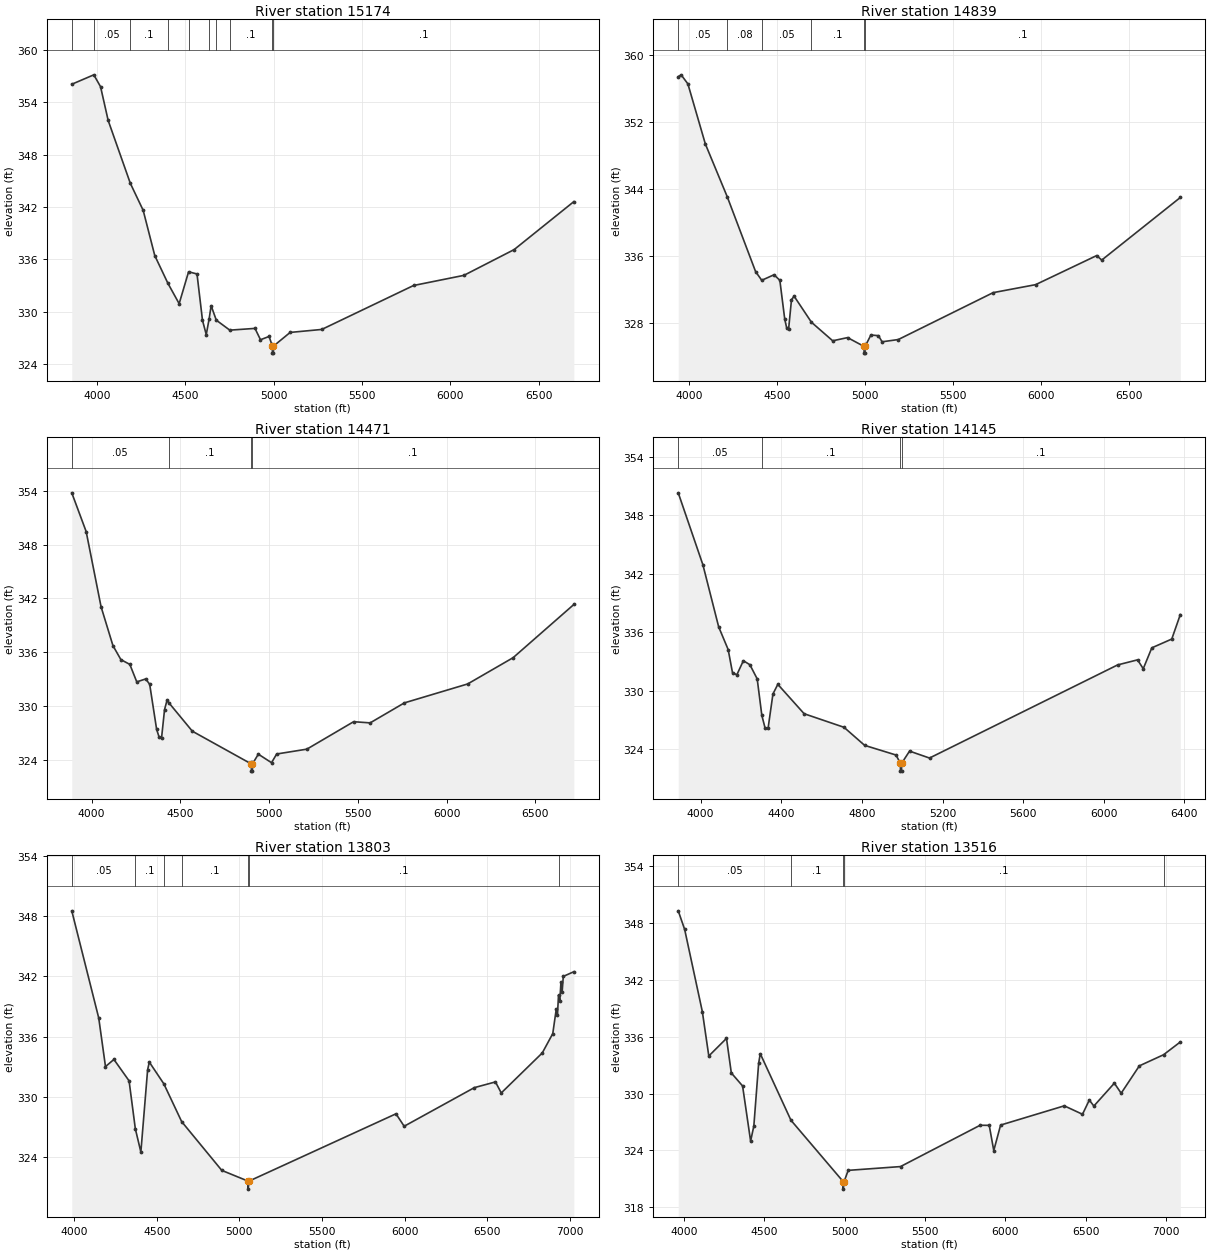
Type RM Length L Ch R = 1,15174,335,335,335
BEGIN DESCRIPTION:
Hog Creek 27.0
END DESCRIPTION:
XS GIS Cut Line= 3
      2128481.77     13424427.34      2127481.77     13425027.34
      2126731.79     13426527.31
#Sta/Elev= 30
  3856.0  356.04  3980.8  357.12  4019.0  355.76  4062.1  351.90  4187.7  344.70
  4260.4  341.61  4326.1  336.43  4400.7  333.25  4464.1  330.93  4517.5  334.58
  4565.2  334.33  4596.3  329.02  4617.6  327.39  4634.2  329.23  4645.2  330.70
  4674.5  329.04  4751.0  327.90  4893.6  328.10  4924.7  326.80  4973.3  327.18
  4992.1  326.07  4992.6  325.27  4997.6  325.27  4998.1  326.07  5092.7  327.64
  5271.6  327.98  5791.5  333.01  6076.6  334.17  6361.2  337.12  6699.2  342.61
#Mann=10,-1,0
  3856.0     0.1       0  3980.8    0.05       0  4187.7     0.1       0
  4400.7    0.05       0  4517.5    0.08       0  4634.2    0.05       0
  4674.5    0.08       0  4751.0     0.1       0  4992.1    0.07       0
  4998.1     0.1       0
Bank Sta=4992.1,4998.1
Exp/Cntr=0.3,0.1

Type RM Length L Ch R = 1,14839,368,368,368
BEGIN DESCRIPTION:
Hog Creek 26.0
END DESCRIPTION:
XS GIS Cut Line= 3
      2128374.96     13424425.01      2127375.00     13424725.00
      2126175.02     13426074.98
#Sta/Elev= 30
  3939.2  357.37  3955.7  357.59  3994.0  356.51  4093.1  349.35  4218.3  343.01
  4378.5  334.13  4413.3  333.10  4482.9  333.76  4516.0  333.10  4543.8  328.47
  4555.1  327.40  4565.6  327.25  4582.1  330.78  4596.9  331.21  4695.4  328.10
  4816.1  325.89  4900.5  326.27  4994.0  325.22  4994.5  324.42  4999.5  324.42
  5000.0  325.22  5032.9  326.58  5075.6  326.50  5096.5  325.77  5188.5  326.04
  5727.0  331.63  5967.8  332.58  6314.9  336.05  6343.3  335.51  6789.4  342.97
#Mann=6,-1,0
  3939.2    0.05       0  4218.3    0.08       0  4413.3    0.05       0
  4695.4     0.1       0  4994.0    0.07       0  5000.0     0.1       0
Bank Sta=4994,5000
Exp/Cntr=0.3,0.1

Type RM Length L Ch R = 1,14471,326,326,326
BEGIN DESCRIPTION:
Hog Creek 25.0
END DESCRIPTION:
XS GIS Cut Line= 3
      2128125.04     13423974.98      2127125.00     13424475.00
      2126075.03     13425824.96
#Sta/Elev= 30
  3888.4  353.77  3969.5  349.45  4053.4  341.07  4120.4  336.73  4165.2  335.17
  4215.5  334.64  4254.6  332.69  4304.9  333.02  4327.3  332.42  4366.4  327.40
  4380.4  326.53  4394.4  326.48  4411.1  329.61  4425.1  330.64  4434.6  330.38
  4567.7  327.19  4900.1  323.54  4900.6  322.74  4905.6  322.74  4906.1  323.54
  4939.4  324.63  5013.7  323.68  5042.7  324.65  5212.8  325.19  5476.1  328.25
  5569.3  328.12  5762.1  330.35  6118.6  332.46  6374.7  335.39  6716.7  341.32
#Mann=4,-1,0
  3888.4    0.05       0  4434.6     0.1       0  4900.1    0.07       0
  4906.1     0.1       0
Bank Sta=4900.1,4906.1
Exp/Cntr=0.3,0.1

Type RM Length L Ch R = 1,14145,342,342,342
BEGIN DESCRIPTION:
Hog Creek 24.0
END DESCRIPTION:
XS GIS Cut Line= 3
      2128025.04     13423774.98      2127025.00     13424175.00
      2126024.99     13425175.01
#Sta/Elev= 30
  3888.7  350.29  4011.3  342.90  4089.3  336.56  4136.5  334.23  4158.0  331.86
  4179.5  331.65  4211.9  333.09  4244.2  332.68  4280.5  331.23  4303.6  327.48
  4319.6  326.20  4334.4  326.15  4358.6  329.68  4382.8  330.67  4513.4  327.66
  4711.3  326.27  4813.6  324.42  4969.3  323.43  4991.0  322.58  4991.5  321.78
  4996.6  321.78  4997.1  322.58  5036.5  323.83  5135.5  323.12  6068.9  332.66
  6167.9  333.18  6196.1  332.27  6238.6  334.41  6337.6  335.31  6380.0  337.82
#Mann=4,-1,0
  3888.7    0.05       0  4303.6     0.1       0  4991.0    0.07       0
  4997.1     0.1       0
Bank Sta=4991,4997.1
Exp/Cntr=0.3,0.1

Type RM Length L Ch R = 1,13803,287,287,287
BEGIN DESCRIPTION:
Hog Creek 23.0
END DESCRIPTION:
XS GIS Cut Line= 3
      2127975.01     13423675.00      2126975.00     13423875.00
      2125474.97     13425225.03
#Sta/Elev= 30
  3986.1  348.54  4149.3  337.85  4190.1  333.01  4241.1  333.72  4332.8  331.59
  4370.8  326.80  4404.2  324.49  4445.0  332.68  4455.2  333.46  4543.2  331.29
  4651.1  327.52  4893.7  322.66  5052.6  321.59  5053.1  320.79  5058.7  321.59
  5947.7  328.30  5997.4  327.06  6421.9  330.91  6549.7  331.48  6584.8  330.38
  6833.0  334.37  6896.5  336.30  6917.4  338.72  6924.9  338.16  6931.2  340.14
  6939.1  339.55  6945.9  341.40  6953.3  340.47  6960.1  342.00  7024.0  342.47
#Mann=7,-1,0
  3986.1    0.05       0  4370.8     0.1       0  4543.2    0.05       0
  4651.1     0.1       0  5052.6    0.07       0  5058.7     0.1       0
  6931.2    0.08       0
Bank Sta=5052.6,5058.7
Exp/Cntr=0.3,0.1

Type RM Length L Ch R = 1,13516,347,347,347
BEGIN DESCRIPTION:
Hog Creek 22.0
END DESCRIPTION:
XS GIS Cut Line= 3
      2127974.97     13423575.00      2126975.00     13423575.00
      2125475.00     13425075.00
#Sta/Elev= 30
  3965.8  349.28  4005.8  347.31  4115.8  338.63  4155.8  333.96  4265.8  335.82
  4295.8  332.17  4365.8  330.80  4415.8  324.98  4435.8  326.57  4465.8  333.21
  4475.8  334.20  4666.5  327.18  4991.0  320.71  4991.5  319.91  4997.1  320.71
  5022.3  321.89  5347.6  322.29  5842.6  326.65  5899.2  326.64  5927.4  323.98
  5969.9  326.67  6365.8  328.70  6479.0  327.81  6521.4  329.31  6549.7  328.68
  6677.0  331.09  6719.4  330.03  6832.5  332.92  6982.7  334.09  7087.1  335.44
#Mann=5,-1,0
  3965.8    0.05       0  4666.5     0.1       0  4991.0    0.07       0
  4997.1     0.1       0  6982.7    0.08       0
Bank Sta=4991,4997.1
Exp/Cntr=0.3,0.1

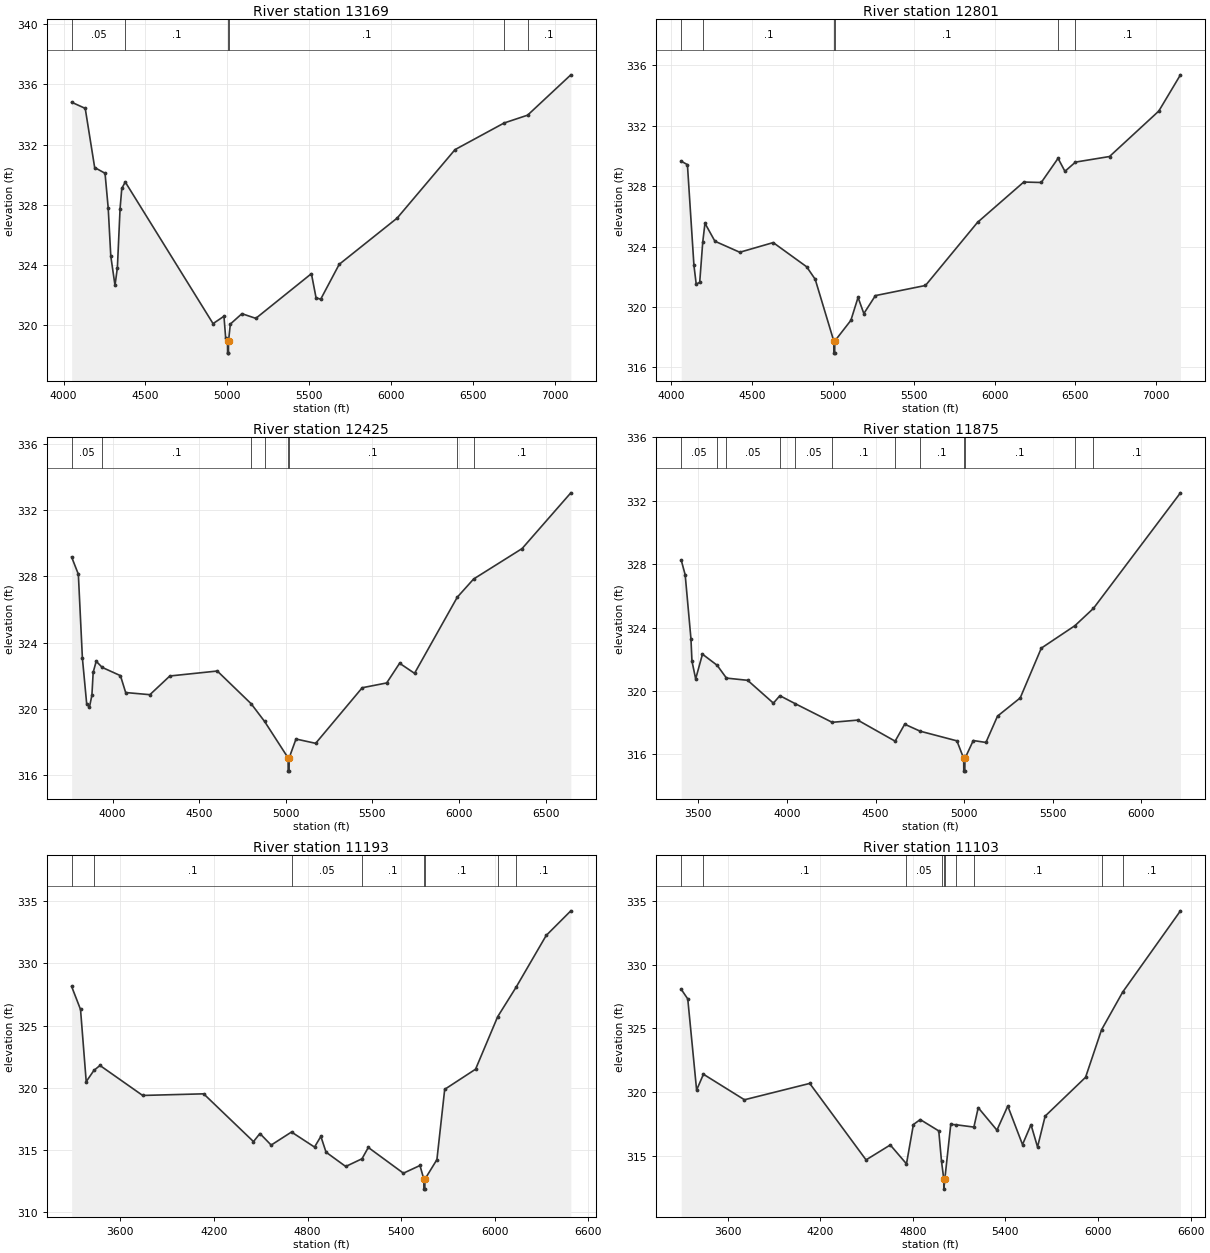
Type RM Length L Ch R = 1,13169,368,368,368
BEGIN DESCRIPTION:
Hog Creek 21.0
END DESCRIPTION:
XS GIS Cut Line= 3
      2127671.07     13423089.08      2126775.00     13423325.00
      2125275.02     13424824.98
#Sta/Elev= 30
  4049.1  334.81  4132.1  334.40  4189.8  330.47  4253.1  330.09  4272.5  327.77
  4288.2  324.59  4313.9  322.64  4328.5  323.82  4344.9  327.74  4355.3  329.08
  4376.5  329.51  4912.6  320.10  4979.2  320.59  4989.8  319.12  5000.9  318.94
  5001.4  318.14  5006.5  318.14  5007.0  318.94  5018.1  320.07  5088.8  320.76
  5173.7  320.45  5513.1  323.42  5541.4  321.82  5569.7  321.72  5682.8  324.04
  6036.4  327.11  6389.9  331.66  6689.7  333.43  6833.1  333.95  7097.0  336.63
#Mann=6,-1,0
  4049.1    0.05       0  4376.5     0.1       0  5000.9    0.07       0
  5007.0     0.1       0  6689.7    0.08       0  6833.1     0.1       0
Bank Sta=5000.9,5007
Exp/Cntr=0.3,0.1

Type RM Length L Ch R = 1,12801,376,376,376
BEGIN DESCRIPTION:
Hog Creek 20.0
END DESCRIPTION:
XS GIS Cut Line= 4
      2127400.25     13422708.86      2126525.00     13423075.00
      2125985.52     13423845.69      2124879.65     13424302.52
#Sta/Elev= 30
  4063.3  329.66  4101.5  329.43  4141.7  322.77  4155.7  321.53  4177.4  321.63
  4196.0  324.28  4209.9  325.55  4271.5  324.36  4425.1  323.63  4631.8  324.27
  4838.4  322.67  4891.4  321.84  5006.3  317.75  5006.8  316.95  5011.9  316.95
  5012.4  317.75  5111.9  319.12  5156.3  320.64  5192.1  319.57  5263.6  320.76
  5573.1  321.43  5894.8  325.61  6180.6  328.28  6288.8  328.25  6392.7  329.85
  6435.2  328.99  6500.3  329.60  6710.7  329.97  7015.4  332.98  7149.3  335.38
#Mann=6,-1,0
  4063.3    0.05       0  4196.0     0.1       0  5006.3    0.07       0
  5012.4     0.1       0  6392.7    0.08       0  6500.3     0.1       0
Bank Sta=5006.3,5012.4
Exp/Cntr=0.3,0.1

Type RM Length L Ch R = 1,12425,550,550,550
BEGIN DESCRIPTION:
Mapping XS 593f50d0
END DESCRIPTION:
XS GIS Cut Line= 4
      2127301.26     13422339.08      2126478.33     13422651.59
      2125775.20     13423292.21      2124759.76     13423563.00
#Sta/Elev= 30
  3763.7  329.17  3802.5  328.13  3825.9  323.06  3850.7  320.29  3866.7  320.10
  3880.8  320.82  3888.1  322.20  3905.6  322.87  3940.1  322.50  4045.6  322.00
  4075.7  320.98  4215.6  320.85  4330.8  321.98  4604.7  322.28  4800.5  320.30
  4878.0  319.23  5013.6  317.03  5014.1  316.23  5019.2  316.23  5019.7  317.03
  5059.2  318.17  5172.7  317.91  5441.6  321.27  5582.9  321.56  5657.5  322.75
  5743.6  322.14  5990.3  326.74  6084.6  327.84  6364.6  329.68  6646.1  333.05
#Mann=8,-1,0
  3763.7    0.05       0  3940.1     0.1       0  4800.5    0.05       0
  4878.0     0.1       0  5013.6    0.07       0  5019.7     0.1       0
  5990.3    0.08       0  6084.6     0.1       0
Bank Sta=5013.6,5019.7
Exp/Cntr=0.3,0.1

Type RM Length L Ch R = 1,11875,682,682,682
BEGIN DESCRIPTION:
Mapping XS 52fb0cb9
END DESCRIPTION:
XS GIS Cut Line= 4
      2127212.73     13422083.87      2126144.99     13422417.21
      2125394.99     13422943.26      2124650.23     13423182.83
#Sta/Elev= 30
  3403.7  328.25  3425.9  327.33  3458.4  323.30  3464.2  321.88  3485.1  320.76
  3523.4  322.32  3606.1  321.62  3658.8  320.81  3778.5  320.67  3923.7  319.23
  3960.2  319.70  4047.9  319.19  4255.3  318.02  4399.6  318.16  4610.6  316.83
  4664.6  317.90  4751.9  317.46  4959.2  316.85  4997.6  315.74  4998.1  314.94
  5004.0  314.94  5004.5  315.74  5051.6  316.87  5123.0  316.75  5188.4  318.41
  5316.5  319.56  5435.5  322.70  5625.5  324.12  5729.8  325.21  6220.7  332.50
#Mann=12,-1,0
  3403.7    0.05       0  3606.1     0.1       0  3658.8    0.05       0
  3960.2     0.1       0  4047.9    0.05       0  4255.3     0.1       0
  4610.6    0.05       0  4751.9     0.1       0  4997.6    0.07       0
  5004.5     0.1       0  5625.5    0.08       0  5729.8     0.1       0
Bank Sta=4997.6,5004.5
Exp/Cntr=0.3,0.1

Type RM Length L Ch R = 1,11193,90,90,90
BEGIN DESCRIPTION:
Mapping XS 8653d0c2
END DESCRIPTION:
XS GIS Cut Line= 6
      2127197.12     13421906.79      2125650.20     13422287.01
      2125499.16     13422146.38      2125421.04     13422203.67
      2125108.54     13422229.71      2124458.77     13422941.90
#Sta/Elev= 30
  3287.8  328.15  3344.9  326.30  3381.3  320.50  3430.5  321.40  3469.5  321.80
  3743.1  319.39  4134.2  319.52  4453.6  315.68  4494.8  316.33  4566.9  315.40
  4697.3  316.45  4844.9  315.24  4885.5  316.10  4918.7  314.83  5044.8  313.68
  5149.2  314.30  5189.6  315.21  5414.7  313.14  5520.8  313.76  5545.5  312.66
  5546.0  311.86  5552.0  311.86  5552.5  312.66  5629.4  314.23  5679.3  319.88
  5877.2  321.50  6018.9  325.72  6137.0  328.09  6329.9  332.25  6487.9  334.23
#Mann=8,-1,0
  3287.8    0.05       0  3430.5     0.1       0  4697.3    0.05       0
  5149.2     0.1       0  5545.5   0.035       0  5552.5     0.1       0
  6018.9    0.08       0  6137.0     0.1       0
Bank Sta=5545.5,5552.5
Exp/Cntr=0.3,0.1

Type RM Length L Ch R = 1,11103,66,66,66
BEGIN DESCRIPTION:
Mapping XS 39106fcf
END DESCRIPTION:
XS GIS Cut Line= 6
      2127181.41     13421849.52      2125697.08     13422234.92
      2125551.24     13422073.46      2125368.95     13422151.59
      2125118.95     13422162.01      2124421.93     13422911.04
#Sta/Elev= 30
  3298.9  328.06  3341.1  327.31  3398.5  320.17  3442.7  321.41  3708.5  319.41
  4131.7  320.69  4496.7  314.70  4653.7  315.87  4758.7  314.39  4803.6  317.47
  4847.8  317.86  4968.0  316.97  4985.7  314.59  5000.4  313.21  5000.9  312.41
  5007.4  313.21  5045.7  317.48  5081.4  317.45  5195.6  317.27  5223.7  318.79
  5345.0  317.03  5415.2  318.92  5510.7  315.90  5565.7  317.46  5608.1  315.71
  5657.5  318.13  5919.4  321.17  6022.9  324.89  6160.2  327.85  6534.4  334.21
#Mann=10,-1,0
  3298.9    0.05       0  3442.7     0.1       0  4758.7    0.05       0
  4985.7     0.1       0  5000.4    0.07       0  5007.4     0.1       0
  5081.4    0.05       0  5195.6     0.1       0  6022.9    0.08       0
  6160.2     0.1       0
Bank Sta=5000.4,5007.4
Exp/Cntr=0.3,0.1

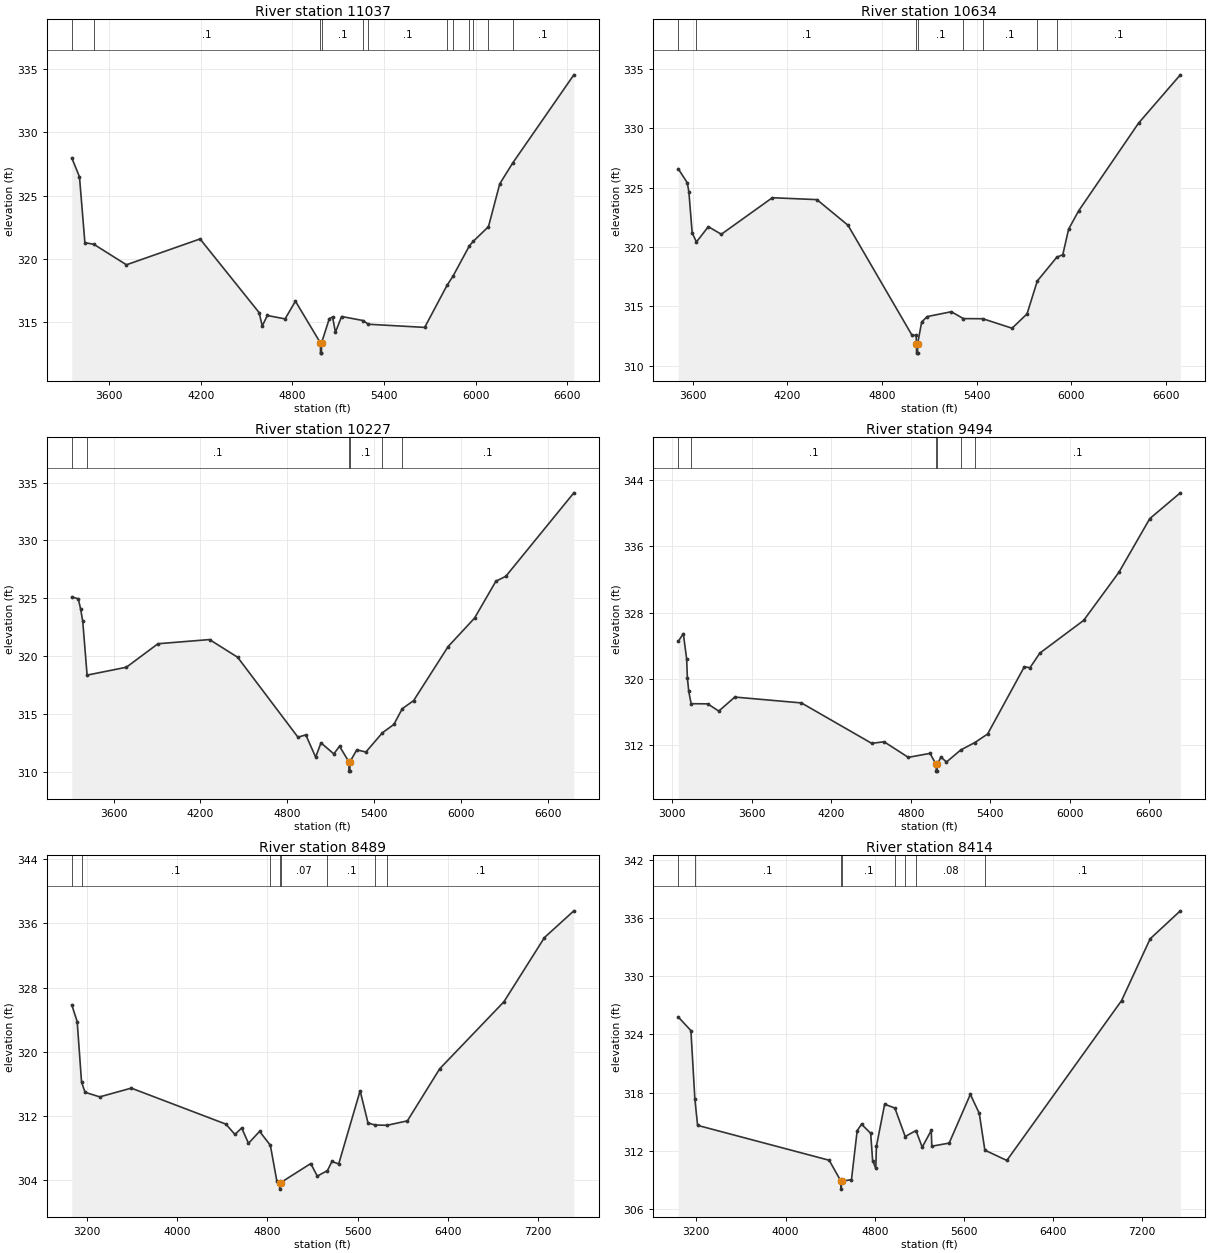
Type RM Length L Ch R = 1,11037,403,403,403
BEGIN DESCRIPTION:
Mapping XS 6779f859
END DESCRIPTION:
XS GIS Cut Line= 6
      2127171.07     13421807.83      2125733.54     13422182.84
      2125608.54     13422021.38      2125374.16     13422031.80
      2125025.20     13422182.84      2124369.48     13422864.58
#Sta/Elev= 30
  3356.8  327.98  3407.3  326.48  3442.6  321.29  3502.4  321.15  3714.5  319.54
  4196.2  321.58  4582.6  315.77  4603.2  314.71  4636.3  315.54  4752.5  315.27
  4820.3  316.67  4984.0  313.37  4984.5  312.57  4990.5  312.57  4991.0  313.37
  5041.9  315.29  5063.2  315.42  5082.1  314.22  5122.2  315.46  5263.3  315.14
  5297.4  314.85  5666.0  314.60  5812.7  317.93  5850.6  318.63  5959.1  321.05
  5983.6  321.39  6083.4  322.55  6157.3  325.93  6240.7  327.55  6642.0  334.53
#Mann=12,-1,0
  3356.8    0.05       0  3502.4     0.1       0  4984.0    0.07       0
  4991.0     0.1       0  5263.3    0.05       0  5297.4     0.1       0
  5812.7    0.08       0  5850.6     0.1       0  5959.1    0.08       0
  5983.6     0.1       0  6083.4    0.08       0  6240.7     0.1       0
Bank Sta=4984,4991
Exp/Cntr=0.3,0.1

Type RM Length L Ch R = 1,10634,407,407,407
BEGIN DESCRIPTION:
Hog Creek 18.0
END DESCRIPTION:
XS GIS Cut Line= 3
      2127070.87     13421382.40      2125625.00     13421725.00
      2124172.88     13422607.01
#Sta/Elev= 30
  3506.9  326.60  3564.3  325.42  3574.6  324.63  3595.2  321.21  3622.3  320.43
  3697.9  321.72  3780.1  321.08  4103.8  324.16  4386.5  324.00  4583.8  321.84
  4990.2  312.56  5016.0  312.56  5018.3  311.86  5018.8  311.06  5024.9  311.06
  5025.5  311.86  5051.3  313.69  5086.4  314.14  5239.0  314.55  5315.9  313.97
  5438.7  313.96  5624.7  313.16  5719.6  314.37  5784.5  317.14  5908.1  319.14
  5946.3  319.36  5983.2  321.51  6047.1  323.06  6427.0  330.45  6691.8  334.52
#Mann=8,-1,0
  3506.9    0.05       0  3622.3     0.1       0  5018.3    0.07       0
  5025.5     0.1       0  5315.9    0.05       0  5438.7     0.1       0
  5784.5    0.08       0  5908.1     0.1       0
Bank Sta=5018.3,5025.5
Exp/Cntr=0.3,0.1

Type RM Length L Ch R = 1,10227,733,733,733
BEGIN DESCRIPTION:
Hog Creek 17.0
END DESCRIPTION:
XS GIS Cut Line= 3
      2126952.77     13420875.48      2125477.11     13421387.40
      2123759.21     13422202.97
#Sta/Elev= 30
  3312.1  325.12  3356.9  324.96  3373.2  324.08  3388.0  323.00  3417.8  318.37
  3688.8  319.05  3906.7  321.08  4262.4  321.44  4456.5  319.91  4872.5  313.01
  4926.5  313.21  4994.6  311.29  5031.3  312.52  5119.9  311.57  5159.3  312.23
  5223.9  310.88  5224.4  310.08  5230.5  310.08  5231.1  310.88  5278.4  311.92
  5341.1  311.73  5455.0  313.39  5534.0  314.11  5591.9  315.47  5670.4  316.17
  5908.7  320.84  6090.5  323.29  6238.0  326.48  6306.2  326.90  6775.7  334.11
#Mann=6,-1,0
  3312.1    0.05       0  3417.8     0.1       0  5223.9    0.07       0
  5231.1     0.1       0  5455.0    0.08       0  5591.9     0.1       0
Bank Sta=5223.9,5231.1
Exp/Cntr=0.3,0.1

Type RM Length L Ch R = 1,9494,1005,1005,1005
BEGIN DESCRIPTION:
Hog Creek 16.0
END DESCRIPTION:
XS GIS Cut Line= 3
      2126862.51     13420576.85      2124950.80     13420984.54
      2123230.60     13421618.51
#Sta/Elev= 30
  3045.3  324.54  3083.7  325.48  3108.8  322.42  3114.3  320.15  3124.6  318.51
  3142.8  317.03  3267.7  317.01  3351.3  316.14  3472.2  317.83  3974.8  317.12
  4504.9  312.25  4598.4  312.44  4781.0  310.56  4944.6  311.04  4991.6  309.70
  4992.1  308.90  4998.4  308.90  4999.0  309.70  5027.5  310.59  5069.2  310.00
  5176.6  311.45  5282.5  312.34  5379.2  313.37  5656.8  321.49  5698.9  321.36
  5773.5  323.13  6103.9  327.07  6370.0  332.87  6602.9  339.34  6833.3  342.45
#Mann=6,-1,0
  3045.3    0.05       0  3142.8     0.1       0  4991.6    0.07       0
  4999.0     0.1       0  5176.6    0.08       0  5282.5     0.1       0
Bank Sta=4991.6,4999
Exp/Cntr=0.3,0.1

Type RM Length L Ch R = 1,8489,75,75,75
BEGIN DESCRIPTION:
Mapping XS 57477cd1
END DESCRIPTION:
XS GIS Cut Line= 6
      2126793.12     13420340.74      2125175.03     13420333.79
      2125175.03     13420181.02      2124834.75     13420160.18
      2124827.81     13420694.91      2123128.19     13421277.63
#Sta/Elev= 30
  3063.8  325.86  3111.9  323.76  3150.7  316.22  3181.9  314.95  3311.9  314.38
  3591.9  315.47  4431.9  310.98  4511.9  309.69  4571.9  310.51  4631.9  308.59
  4730.7  310.08  4826.3  308.34  4883.4  303.92  4909.3  303.68  4909.8  302.88
  4916.7  303.68  5184.6  306.07  5242.8  304.50  5332.8  305.19  5372.8  306.33
  5432.8  306.02  5622.9  315.14  5692.9  311.12  5757.1  310.87  5862.1  310.84
  6042.3  311.39  6329.0  317.88  6899.3  326.24  7258.7  334.24  7519.6  337.57
#Mann=8,-1,0
  3063.8    0.05       0  3150.7     0.1       0  4826.3    0.07       0
  4909.3    0.07       0  4916.7    0.07       0  5332.8     0.1       0
  5757.1    0.08       0  5862.1     0.1       0
Bank Sta=4909.3,4916.7
Exp/Cntr=0.3,0.1

Type RM Length L Ch R = 1,8414,80,80,80
BEGIN DESCRIPTION:
Mapping XS 6ffe1893
END DESCRIPTION:
XS GIS Cut Line= 6
      2126848.67     13420271.30      2125251.42     13420229.63
      2125126.42     13420069.91      2124751.42     13420090.74
      2124737.53     13420604.63      2123058.48     13421236.00
#Sta/Elev= 30
  3037.5  325.80  3151.2  324.39  3186.9  317.30  3211.2  314.61  4391.6  311.01
  4498.0  308.83  4498.5  308.03  4505.4  308.83  4591.7  309.02  4642.8  314.07
  4681.8  314.73  4763.9  313.79  4781.4  310.98  4809.8  310.17  4815.3  312.44
  4889.2  316.79  4980.9  316.40  5073.5  313.46  5170.2  314.07  5226.4  312.36
  5307.4  314.09  5312.4  312.46  5468.0  312.78  5658.1  317.81  5738.2  315.85
  5788.2  312.05  5985.3  310.99  7014.9  327.49  7271.0  333.86  7541.7  336.75
#Mann=8,-1,0
  3037.5    0.05       0  3186.9     0.1       0  4498.0    0.07       0
  4505.4     0.1       0  4980.9    0.07       0  5073.5     0.1       0
  5170.2    0.08       0  5788.2     0.1       0
Bank Sta=4498,4505.4
Exp/Cntr=0.3,0.1

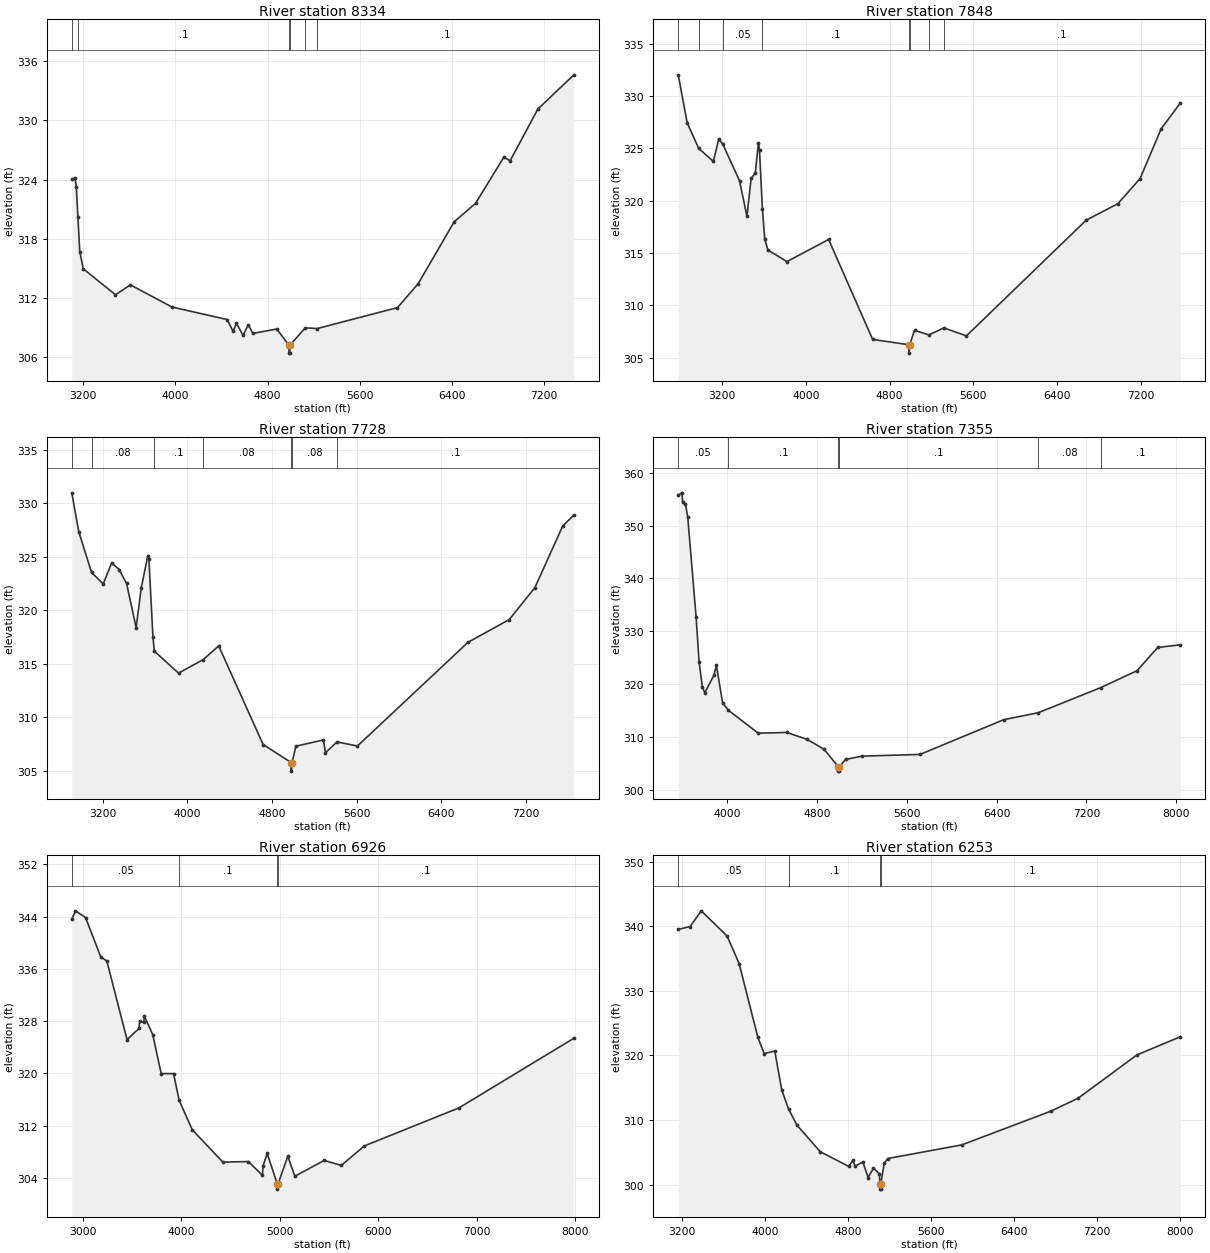
Type RM Length L Ch R = 1,8334,486,486,486
BEGIN DESCRIPTION:
Mapping XS 925930d0
END DESCRIPTION:
XS GIS Cut Line= 6
      2126744.47     13420181.02      2125300.03     13420174.07
      2125140.31     13420000.46      2124744.47     13420007.41
      2124640.31     13420486.57      2123029.56     13421125.32
#Sta/Elev= 30
  3101.1  324.04  3130.6  324.14  3140.6  323.24  3154.3  320.19  3170.6  316.72
  3200.6  314.98  3480.6  312.35  3610.6  313.35  3970.6  311.11  4450.6  309.84
  4500.6  308.65  4530.6  309.47  4587.2  308.24  4633.8  309.32  4672.5  308.44
  4880.2  308.88  4986.4  307.24  4987.0  306.44  4993.3  306.44  4993.9  307.24
  5128.4  309.00  5230.8  308.93  5928.1  311.05  6108.3  313.48  6420.3  319.74
  6606.0  321.61  6851.8  326.29  6905.9  325.92  7146.3  331.15  7458.9  334.62
#Mann=6,-1,0
  3101.1    0.05       0  3154.3     0.1       0  4986.4    0.07       0
  4993.9     0.1       0  5128.4    0.08       0  5230.8     0.1       0
Bank Sta=4986.4,4993.9
Exp/Cntr=0.3,0.1

Type RM Length L Ch R = 1,7848,120,120,120
BEGIN DESCRIPTION:
Mapping XS 3b07c598
END DESCRIPTION:
XS GIS Cut Line= 4
      2127320.83     13419549.07      2126306.97     13419569.91
      2124855.59     13419576.85      2122543.07     13419847.69
#Sta/Elev= 30
  2781.6  332.01  2867.5  327.41  2977.3  324.98  3117.5  323.74  3167.5  325.87
  3208.3  325.37  3367.6  321.87  3437.6  318.50  3477.6  322.12  3517.6  322.65
  3547.6  325.53  3557.6  324.82  3585.0  319.24  3607.6  316.34  3637.6  315.29
  3819.0  314.18  4217.7  316.29  4637.7  306.75  4983.9  306.24  4984.5  305.44
  4991.4  306.24  5037.7  307.62  5174.5  307.18  5317.6  307.85  5533.3  307.09
  6677.4  318.14  6979.4  319.71  7190.9  322.10  7392.2  326.85  7575.4  329.32
#Mann=8,-1,0
  2781.6    0.05       0  2977.3     0.1       0  3208.3    0.05       0
  3585.0     0.1       0  4983.9    0.07       0  4991.4     0.1       0
  5174.5    0.08       0  5317.6     0.1       0
Bank Sta=4983.9,4991.4
Exp/Cntr=0.3,0.1

Type RM Length L Ch R = 1,7728,373,373,373
BEGIN DESCRIPTION:
Mapping XS 57c37239
END DESCRIPTION:
XS GIS Cut Line= 4
      2127251.46     13419410.18      2126334.75     13419493.52
      2124793.09     13419472.68      2122529.58     13419805.96
#Sta/Elev= 30
  2905.1  330.98  2971.8  327.33  3092.3  323.53  3202.8  322.46  3283.1  324.44
  3353.4  323.80  3423.7  322.50  3514.1  318.38  3562.5  322.10  3624.5  325.11
  3634.6  324.83  3673.0  317.51  3686.3  316.17  3915.3  314.12  4148.5  315.38
  4295.4  316.66  4715.4  307.44  4981.7  305.75  4982.3  304.95  4989.2  305.75
  5025.4  307.28  5285.5  307.87  5305.5  306.67  5413.3  307.68  5608.0  307.30
  6653.8  317.00  7043.4  319.12  7285.9  322.10  7549.8  327.87  7655.3  328.90
#Mann=7,-1,0
  2905.1    0.05       0  3092.3    0.08       0  3686.3     0.1       0
  4148.5    0.08       0  4981.7    0.07       0  4989.2    0.08       0
  5413.3     0.1       0
Bank Sta=4981.7,4989.2
Exp/Cntr=0.3,0.1

Type RM Length L Ch R = 1,7355,429,429,429
BEGIN DESCRIPTION:
Mapping XS 664c99c1
END DESCRIPTION:
XS GIS Cut Line= 3
      2126758.38     13418993.51      2125654.20     13419181.02
      2122320.90     13419562.96
#Sta/Elev= 30
  3561.2  355.75  3595.0  356.18  3600.0  354.50  3625.5  354.10  3645.8  351.61
  3720.6  332.67  3747.2  324.23  3775.8  319.55  3797.9  318.39  3879.1  321.69
  3901.5  323.56  3956.7  316.50  4006.4  315.11  4274.6  310.75  4528.2  310.89
  4710.6  309.58  4861.6  307.70  4988.6  304.38  4989.2  303.58  4995.6  303.58
  4996.2  304.38  5052.8  305.79  5199.0  306.41  5717.1  306.74  6462.0  313.30
  6771.4  314.63  7328.5  319.38  7649.7  322.55  7835.3  326.96  8036.3  327.45
#Mann=6,-1,0
  3561.2    0.05       0  4006.4     0.1       0  4988.6    0.07       0
  4996.2     0.1       0  6771.4    0.08       0  7328.5     0.1       0
Bank Sta=4988.6,4996.2
Exp/Cntr=0.3,0.1

Type RM Length L Ch R = 1,6926,673,673,673
BEGIN DESCRIPTION:
Mapping XS c1f89d91
END DESCRIPTION:
XS GIS Cut Line= 3
      2127321.73     13418356.36      2124294.39     13419050.81
      2122308.75     13419170.16
#Sta/Elev= 30
  2890.2  343.56  2927.9  344.88  3030.5  343.84  3184.4  337.83  3245.9  337.21
  3451.1  325.17  3573.2  326.89  3578.4  328.02  3621.2  327.82  3626.4  328.78
  3712.1  325.92  3797.9  319.97  3923.1  319.97  3979.9  315.88  4113.5  311.36
  4423.9  306.42  4682.3  306.51  4825.2  304.39  4830.4  305.77  4873.3  307.75
  4975.9  303.09  4976.5  302.29  4983.8  303.09  5082.4  307.32  5154.2  304.26
  5451.2  306.68  5626.2  305.92  5857.7  308.89  6819.0  314.72  7985.4  325.38
#Mann=4,-1,0
  2890.2    0.05       0  3979.9     0.1       0  4975.9    0.07       0
  4983.8     0.1       0
Bank Sta=4975.9,4983.8
Exp/Cntr=0.3,0.1

Type RM Length L Ch R = 1,6253,566,566,566
BEGIN DESCRIPTION:
Mapping XS 06b3a238
END DESCRIPTION:
XS GIS Cut Line= 2
      2127278.33     13417857.23      2122526.75     13418790.19
#Sta/Elev= 30
  3161.8  339.52  3276.1  339.95  3384.0  342.39  3634.0  338.46  3749.1  334.22
  3929.5  322.81  3990.7  320.28  4092.6  320.69  4160.6  314.63  4225.9  311.71
  4306.6  309.21  4530.8  305.10  4805.9  302.82  4846.7  303.78  4867.1  302.86
  4942.2  303.50  4993.6  301.09  5045.0  302.56  5101.6  301.67  5107.6  300.10
  5108.3  299.30  5115.0  299.30  5115.7  300.10  5147.9  303.29  5183.0  304.04
  5896.4  306.15  6757.5  311.38  7019.7  313.39  7585.4  320.08  8004.1  322.89
#Mann=4,-1,0
  3161.8    0.05       0  4225.9     0.1       0  5107.6    0.07       0
  5115.7     0.1       0
Bank Sta=5107.6,5115.7
Exp/Cntr=0.3,0.1

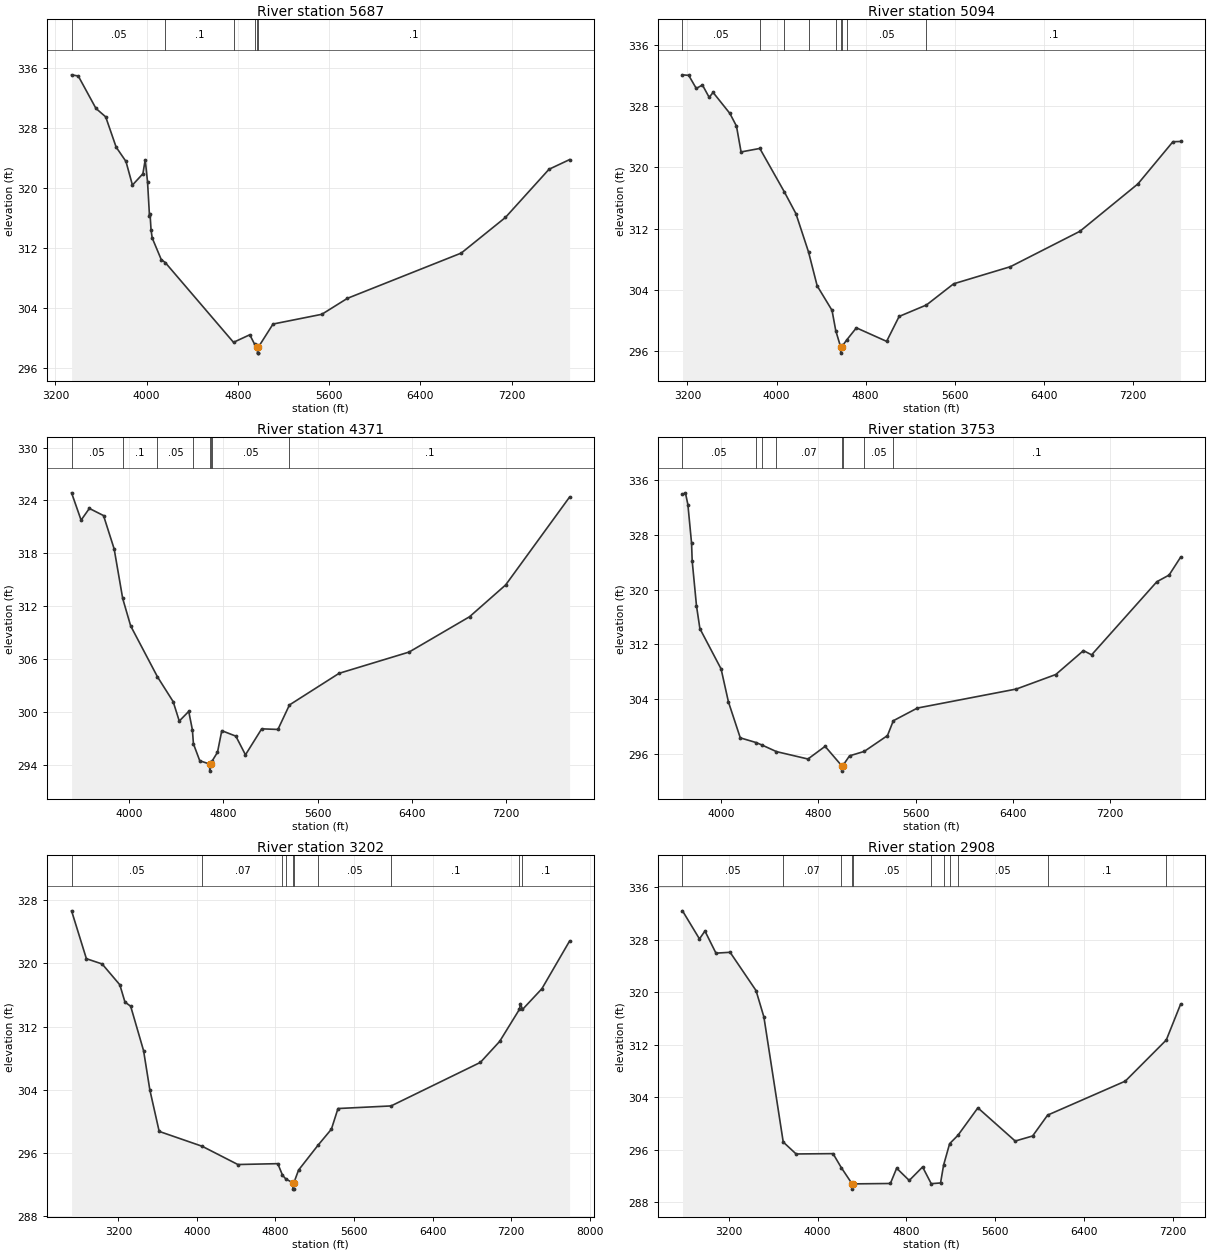
Type RM Length L Ch R = 1,5687,593,593,593
BEGIN DESCRIPTION:
Mapping XS 51242c04
END DESCRIPTION:
XS GIS Cut Line= 2
      2127028.80     13417368.94      2122742.78     13418204.45
#Sta/Elev= 30
  3342.0  335.06  3400.9  334.90  3555.7  330.58  3641.3  329.45  3733.0  325.41
  3818.8  323.51  3875.7  320.35  3967.4  321.86  3987.7  323.72  4008.1  320.78
  4025.2  316.26  4030.3  316.47  4038.7  314.41  4048.9  313.30  4128.4  310.41
  4163.2  310.02  4761.9  299.37  4904.7  300.38  4946.1  299.14  4971.9  298.73
  4972.6  297.93  4979.3  297.93  4980.0  298.73  5108.4  301.81  5536.3  303.11
  5760.5  305.24  6758.9  311.28  7146.1  316.03  7528.4  322.46  7708.7  323.75
#Mann=6,-1,0
  3342.0    0.05       0  4163.2     0.1       0  4761.9    0.05       0
  4946.1     0.1       0  4971.9    0.07       0  4980.0     0.1       0
Bank Sta=4971.9,4980
Exp/Cntr=0.3,0.1

Type RM Length L Ch R = 1,5094,723,723,723
BEGIN DESCRIPTION:
Mapping XS a1e05ac7
END DESCRIPTION:
XS GIS Cut Line= 3
      2127039.65     13416804.71      2124988.83     13417227.89
      2122655.95     13417683.62
#Sta/Elev= 30
  3155.7  332.12  3211.5  332.05  3279.4  330.34  3334.7  330.79  3395.3  329.17
  3430.2  329.82  3581.0  327.07  3640.3  325.41  3681.5  322.03  3849.8  322.49
  4068.7  316.84  4174.0  313.96  4287.2  308.94  4364.8  304.51  4498.0  301.31
  4531.6  298.65  4575.6  296.51  4576.3  295.71  4583.8  296.51  4632.6  297.48
  4716.7  299.02  4988.2  297.25  5100.5  300.51  5346.0  302.01  5589.9  304.78
  6099.8  307.02  6723.5  311.65  7244.2  317.85  7558.6  323.37  7626.7  323.40
#Mann=9,-1,0
  3155.7    0.05       0  3849.8     0.1       0  4068.7    0.05       0
  4287.2     0.1       0  4531.6    0.07       0  4575.6   0.035       0
  4583.8    0.07       0  4632.6    0.05       0  5346.0     0.1       0
Bank Sta=4575.6,4583.8
Exp/Cntr=0.3,0.1

Type RM Length L Ch R = 1,4371,618,618,618
BEGIN DESCRIPTION:
Mapping XS c1049a7e
END DESCRIPTION:
XS GIS Cut Line= 3
      2126735.77     13416414.09      2125856.89     13416392.39
      2122699.70     13417488.18
#Sta/Elev= 30
  3515.4  324.87  3596.2  321.77  3666.2  323.10  3786.3  322.29  3876.3  318.51
  3948.8  312.88  4016.3  309.77  4243.5  303.99  4376.4  301.18  4428.3  298.97
  4508.5  300.07  4539.6  297.97  4548.3  296.39  4601.9  294.47  4685.8  294.09
  4686.5  293.29  4694.0  294.09  4706.5  294.43  4752.2  295.43  4788.6  297.88
  4907.8  297.26  4989.3  295.14  5126.9  298.09  5264.5  298.02  5362.1  300.80
  5783.2  304.39  6376.0  306.80  6888.7  310.81  7194.7  314.42  7736.5  324.39
#Mann=8,-1,0
  3515.4    0.05       0  3948.8     0.1       0  4243.5    0.05       0
  4548.3    0.12       0  4685.8   0.035       0  4694.0    0.12       0
  4706.5    0.05       0  5362.1     0.1       0
Bank Sta=4685.8,4694
Exp/Cntr=0.3,0.1

Type RM Length L Ch R = 1,3753,551,551,551
BEGIN DESCRIPTION:
Mapping XS 7cc6c19c
END DESCRIPTION:
XS GIS Cut Line= 3
      2126518.77     13415697.95      2125596.47     13415839.00
      2122678.86     13417064.62
#Sta/Elev= 30
  3682.9  333.91  3706.9  334.14  3727.2  332.43  3757.5  326.78  3762.6  324.20
  3798.0  317.64  3826.0  314.31  4000.3  308.43  4061.0  303.60  4158.3  298.36
  4287.2  297.68  4335.9  297.32  4455.9  296.35  4715.1  295.27  4856.2  297.12
  4992.3  294.30  4993.2  293.50  5002.0  294.30  5057.1  295.73  5178.3  296.38
  5369.3  298.69  5417.7  300.86  5615.4  302.71  6430.1  305.49  6754.3  307.61
  6982.0  311.10  7049.1  310.48  7585.9  321.16  7686.4  322.13  7780.5  324.72
#Mann=8,-1,0
  3682.9    0.05       0  4287.2     0.1       0  4335.9    0.05       0
  4455.9    0.07       0  4992.3    0.07       0  5002.0    0.07       0
  5178.3    0.05       0  5417.7     0.1       0
Bank Sta=4992.3,5002
Exp/Cntr=0.3,0.1

Type RM Length L Ch R = 1,3202,294,294,294
BEGIN DESCRIPTION:
Hog Creek 4.0
END DESCRIPTION:
XS GIS Cut Line= 3
      2127073.91     13414266.52      2125175.00     13415425.00
      2122730.13     13416886.32
#Sta/Elev= 30
  2722.8  326.67  2873.8  320.60  3034.3  319.93  3214.4  317.29  3266.7  315.10
  3324.8  314.57  3456.4  308.93  3520.3  303.95  3615.2  298.70  4053.9  296.81
  4416.7  294.50  4823.3  294.61  4871.3  293.15  4905.1  292.67  4977.3  292.18
  4978.2  291.38  4986.1  291.38  4987.1  292.18  5034.7  293.79  5233.3  296.95
  5369.3  298.98  5436.5  301.60  5977.5  301.93  6886.8  307.45  7083.2  310.11
  7285.2  314.19  7295.3  314.90  7315.6  314.16  7513.2  316.79  7795.5  322.84
#Mann=10,-1,0
  2722.8    0.05       0  4053.9    0.07       0  4871.3    0.05       0
  4905.1    0.07       0  4977.3    0.07       0  4987.1    0.07       0
  5233.3    0.05       0  5977.5     0.1       0  7285.2    0.05       0
  7315.6     0.1       0
Bank Sta=4977.3,4987.1
Exp/Cntr=0.3,0.1

Type RM Length L Ch R = 1,2908,310,310,310
BEGIN DESCRIPTION:
Hog Creek 3.0
END DESCRIPTION:
XS GIS Cut Line= 3
      2126588.99     13413693.16      2124975.00     13415225.00
      2122952.82     13416230.35
#Sta/Elev= 30
  2783.5  332.40  2936.2  328.12  2985.6  329.32  3084.7  325.95  3212.1  326.08
  3445.5  320.25  3516.3  316.22  3690.3  297.16  3806.3  295.34  4138.8  295.39
  4212.6  293.27  4310.7  290.78  4311.6  289.98  4320.5  290.78  4655.0  290.84
  4711.6  293.17  4824.8  291.30  4945.0  293.36  5022.7  290.81  5106.7  290.92
  5134.1  293.64  5188.4  296.91  5263.1  298.18  5442.7  302.37  5778.7  297.31
  5935.5  298.08  6070.5  301.26  6769.8  306.44  7138.9  312.71  7267.0  318.14
#Mann=11,-1,0
  2783.5    0.05       0  3690.3    0.07       0  4212.6    0.05       0
  4310.7   0.033       0  4320.5    0.05       0  5022.7    0.07       0
  5134.1    0.05       0  5188.4    0.07       0  5263.1    0.05       0
  6070.5     0.1       0  7138.9    0.05       0
Bank Sta=4310.7,4320.5
Exp/Cntr=0.3,0.1