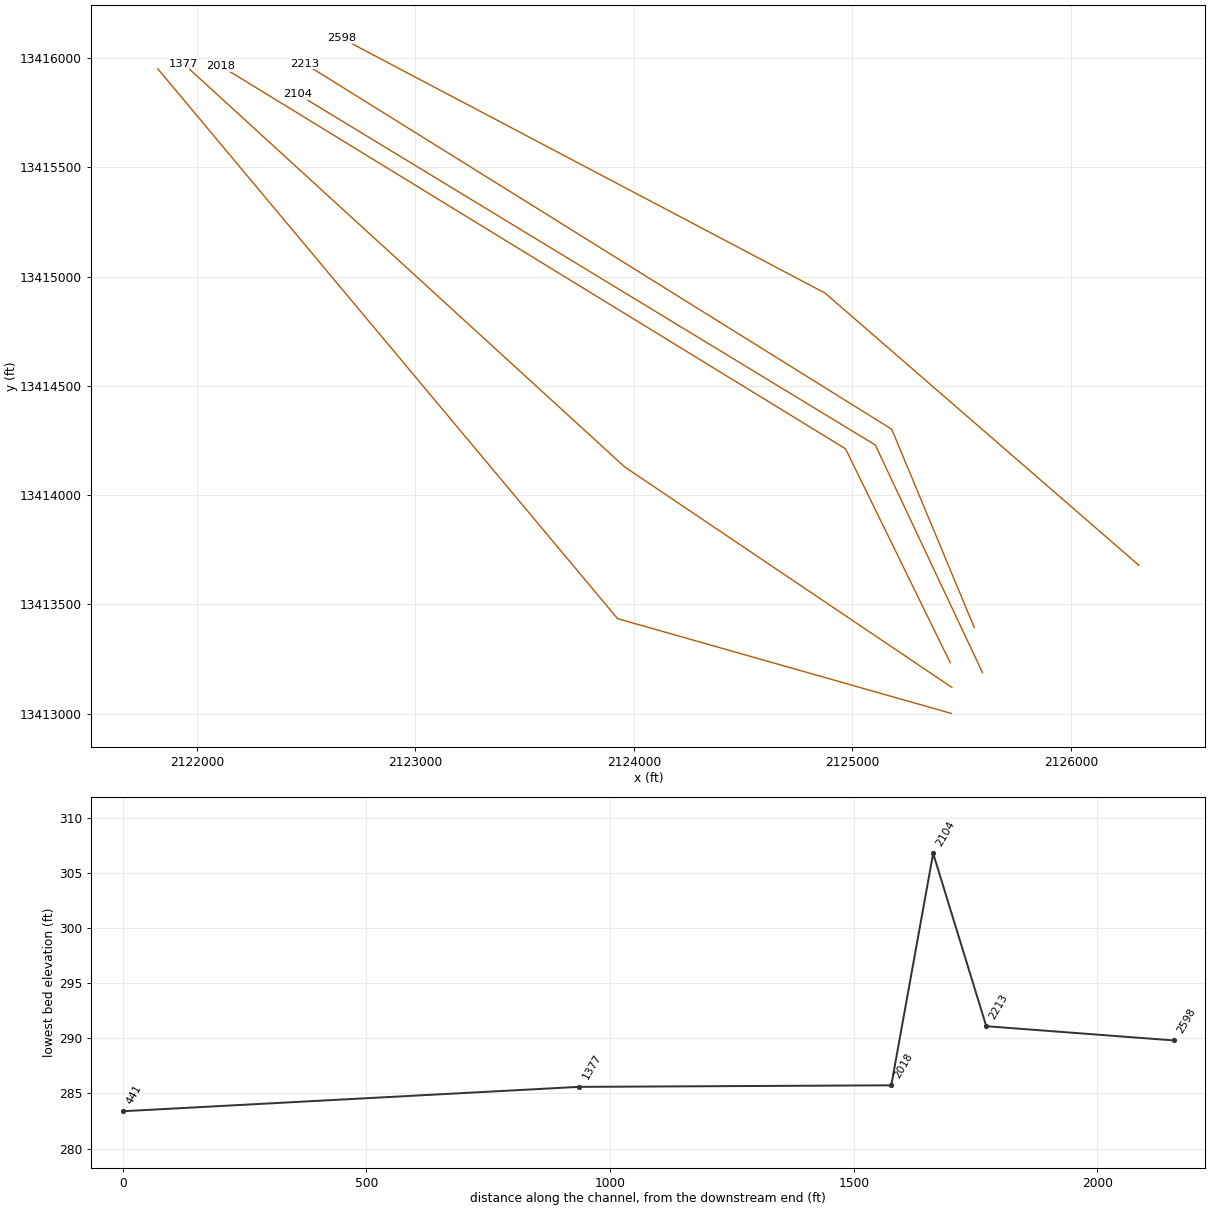
HEC-RAS study Hog Creek.prj: Hog Creek Base Level Engineering

--- Hog Creek.g01 (geometry) --- (continued)

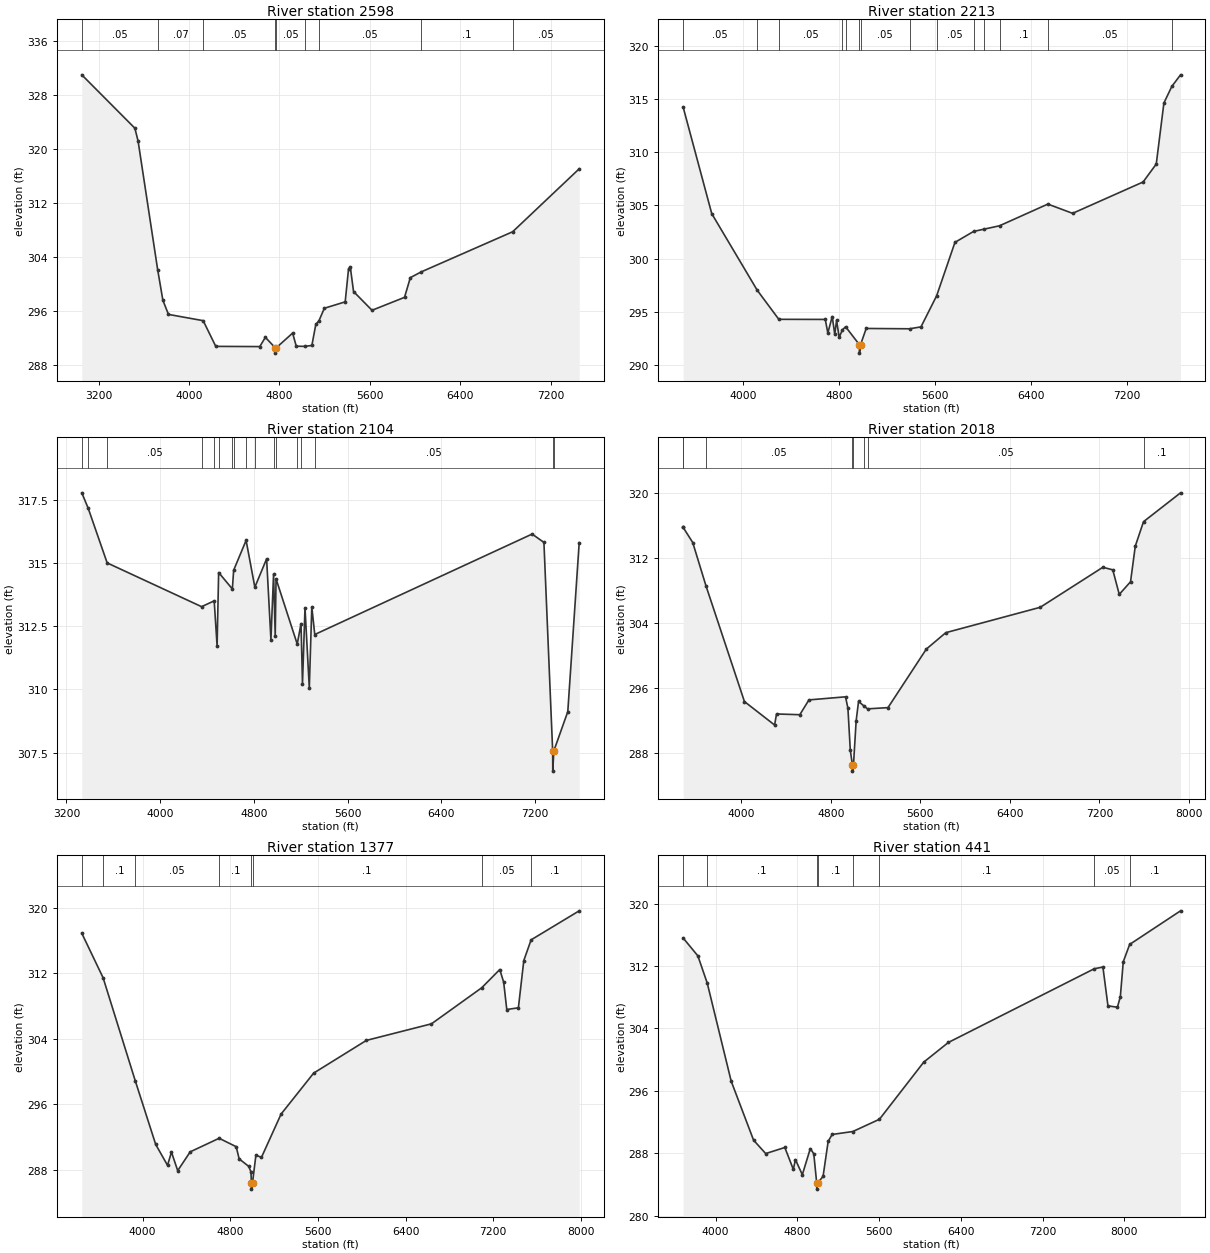
Type RM Length L Ch R = 1,2598,385,385,385
BEGIN DESCRIPTION:
Hog Creek 2.0
END DESCRIPTION:
XS GIS Cut Line= 3
      2126311.25     13413679.23      2124875.00     13414925.00
      2122663.10     13416090.87
#Sta/Elev= 30
  3050.5  331.06  3520.1  323.15  3548.6  321.26  3722.2  302.15  3768.0  297.65
  3817.3  295.55  4124.7  294.62  4236.2  290.81  4625.5  290.78  4674.9  292.15
  4762.0  290.61  4763.0  289.81  4772.0  290.61  4916.1  292.78  4948.4  290.84
  5025.5  290.81  5086.5  290.95  5121.3  294.06  5149.4  294.61  5196.6  296.46
  5381.3  297.41  5411.2  302.33  5426.5  302.58  5455.3  298.94  5618.7  296.16
  5906.5  298.08  5957.8  301.00  6054.0  301.85  6863.3  307.80  7452.1  317.13
#Mann=9,-1,0
  3050.5    0.05       0  3722.2    0.07       0  4124.7    0.05       0
  4762.0   0.033       0  4772.0    0.05       0  5025.5    0.07       0
  5149.4    0.05       0  6054.0     0.1       0  6863.3    0.05       0
Bank Sta=4762,4772
Exp/Cntr=0.3,0.1

Type RM Length L Ch R = 1,2213,109,109,109
BEGIN DESCRIPTION:
Mapping XS c8ac83ed
END DESCRIPTION:
XS GIS Cut Line= 3
      2125557.66     13413394.73      2125180.06     13414301.84
      2122494.33     13415974.56
#Sta/Elev= 30
  3498.6  314.25  3737.2  304.22  4116.1  297.02  4296.3  294.28  4683.6  294.27
  4704.9  292.99  4741.5  294.54  4762.7  292.87  4778.0  294.19  4799.3  292.58
  4826.4  293.29  4853.1  293.58  4967.8  291.90  4968.8  291.10  4977.8  291.90
  5024.7  293.42  5386.7  293.39  5481.4  293.57  5611.8  296.49  5764.6  301.52
  5920.2  302.55  6006.5  302.76  6136.2  303.08  6538.9  305.12  6745.4  304.25
  7333.1  307.20  7442.8  308.89  7506.5  314.63  7572.5  316.19  7645.2  317.28
#Mann=14,-1,0
  3498.6    0.05       0  4116.1    0.07       0  4296.3    0.05       0
  4826.4     0.1       0  4853.1    0.05       0  4967.8   0.033       0
  4977.8    0.05       0  5386.7    0.07       0  5611.8    0.05       0
  5920.2     0.1       0  6006.5    0.05       0  6136.2     0.1       0
  6538.9    0.05       0  7572.5     0.1       0
Bank Sta=4967.8,4977.8
Exp/Cntr=0.3,0.1

Type RM Length L Ch R = 1,2104,86,86,86
BEGIN DESCRIPTION:
Mapping XS 5b6f37bc
END DESCRIPTION:
XS GIS Cut Line= 3
      2125595.44     13413188.10      2125104.97     13414229.79
      2122461.75     13415835.69
#Sta/Elev= 30
  3331.6  317.77  3386.3  317.16  3548.1  315.00  4353.8  313.27  4461.3  313.50
  4486.1  311.72  4499.3  314.62  4616.4  313.97  4627.4  314.71  4733.6  315.89
  4808.2  314.04  4908.6  315.16  4945.4  311.97  4967.9  314.55  4982.2  312.13
  4989.1  314.37  5170.0  311.79  5202.2  312.60  5214.7  310.22  5236.1  313.23
  5272.9  310.06  5294.2  313.26  5319.4  312.17  7174.0  316.14  7274.8  315.81
  7349.3  307.57  7350.3  306.77  7359.3  307.57  7478.4  309.12  7575.8  315.80
#Mann=17,-1,0
  3331.6    0.05       0  3386.3     0.1       0  3548.1    0.05       0
  4353.8     0.1       0  4461.3    0.05       0  4499.3     0.1       0
  4616.4    0.05       0  4627.4     0.1       0  4733.6    0.05       0
  4808.2     0.1       0  4967.9    0.05       0  4989.1     0.1       0
  5170.0    0.05       0  5202.2     0.1       0  5319.4    0.05       0
  7349.3    0.07       0  7359.3    0.05       0
Bank Sta=7349.3,7359.3
Exp/Cntr=0.3,0.1

Type RM Length L Ch R = 1,2018,641,641,641
BEGIN DESCRIPTION:
Mapping XS 8e7f7bcc
END DESCRIPTION:
XS GIS Cut Line= 3
      2125447.84     13413233.29      2124968.69     13414212.43
      2122109.96     13415963.90
#Sta/Elev= 30
  3481.6  315.71  3482.2  315.71  3567.3  313.86  3685.7  308.53  4029.0  294.30
  4298.7  291.41  4315.7  292.77  4523.8  292.68  4605.3  294.50  4932.2  294.88
  4953.5  293.46  4974.8  288.29  4993.2  286.54  4994.2  285.74  5003.2  286.54
  5027.0  291.93  5048.3  294.31  5098.9  293.73  5129.2  293.40  5311.3  293.55
  5653.6  300.75  5827.7  302.77  6671.0  305.89  7230.0  310.81  7318.9  310.50
  7377.0  307.48  7477.6  309.03  7520.2  313.42  7593.6  316.42  7924.3  319.97
#Mann=8,-1,0
  3481.6    0.05       0  3482.2     0.1       0  3685.7    0.05       0
  4993.2   0.035       0  5003.2    0.05       0  5098.9     0.1       0
  5129.2    0.05       0  7593.6     0.1       0
Bank Sta=4993.2,5003.2
Exp/Cntr=0.3,0.1

Type RM Length L Ch R = 1,1377,936,936,936
BEGIN DESCRIPTION:
Mapping XS 1715b98e
END DESCRIPTION:
XS GIS Cut Line= 3
      2125455.33     13413120.34      2123957.93     13414129.45
      2121939.84     13415973.94
#Sta/Elev= 30
  3444.4  316.90  3639.0  311.45  3934.1  298.78  4118.9  291.07  4226.9  288.51
  4262.8  290.13  4319.8  287.86  4433.8  290.16  4698.0  291.82  4853.5  290.79
  4880.6  289.30  4967.5  288.39  4988.5  287.71  4992.2  286.40  4993.1  285.60
  5002.8  286.40  5033.4  289.75  5084.4  289.49  5263.3  294.78  5560.5  299.79
  6041.5  303.79  6636.0  305.82  7094.5  310.23  7259.1  312.46  7294.7  310.92
  7323.1  307.57  7429.1  307.78  7478.5  313.56  7545.2  316.09  7984.1  319.64
#Mann=8,-1,0
  3444.4    0.05       0  3639.0     0.1       0  3934.1    0.05       0
  4698.0     0.1       0  4992.2    0.07       0  5002.8     0.1       0
  7094.5    0.05       0  7545.2     0.1       0
Bank Sta=4992.2,5002.8
Exp/Cntr=0.3,0.1

Type RM Length L Ch R = 1,441,0,0,0
BEGIN DESCRIPTION:
Hog Creek 1.0
END DESCRIPTION:
XS GIS Cut Line= 3
      2125452.21     13413001.49      2123925.38     13413435.01
      2121821.37     13415951.15
#Sta/Elev= 30
  3683.0  315.60  3827.4  313.30  3919.1  309.80  4153.3  297.23  4372.3  289.67
  4490.9  287.95  4678.1  288.73  4761.2  285.92  4782.0  287.17  4849.3  285.24
  4927.5  288.59  4961.4  287.92  4990.0  284.19  4990.9  283.39  5000.6  284.19
  5052.3  285.03  5102.2  289.52  5141.3  290.40  5343.8  290.78  5603.9  292.35
  6037.6  299.68  6278.3  302.20  7705.5  311.65  7790.5  311.87  7839.9  306.89
  7932.3  306.72  7960.9  308.05  7989.6  312.55  8052.2  314.77  8550.1  319.08
#Mann=8,-1,0
  3683.0    0.05       0  3919.1     0.1       0  4990.0    0.07       0
  5000.6     0.1       0  5343.8    0.05       0  5603.9     0.1       0
  7705.5    0.05       0  8052.2     0.1       0
Bank Sta=4990,5000.6
Exp/Cntr=0.3,0.1

Chan Stop Cuts=-1