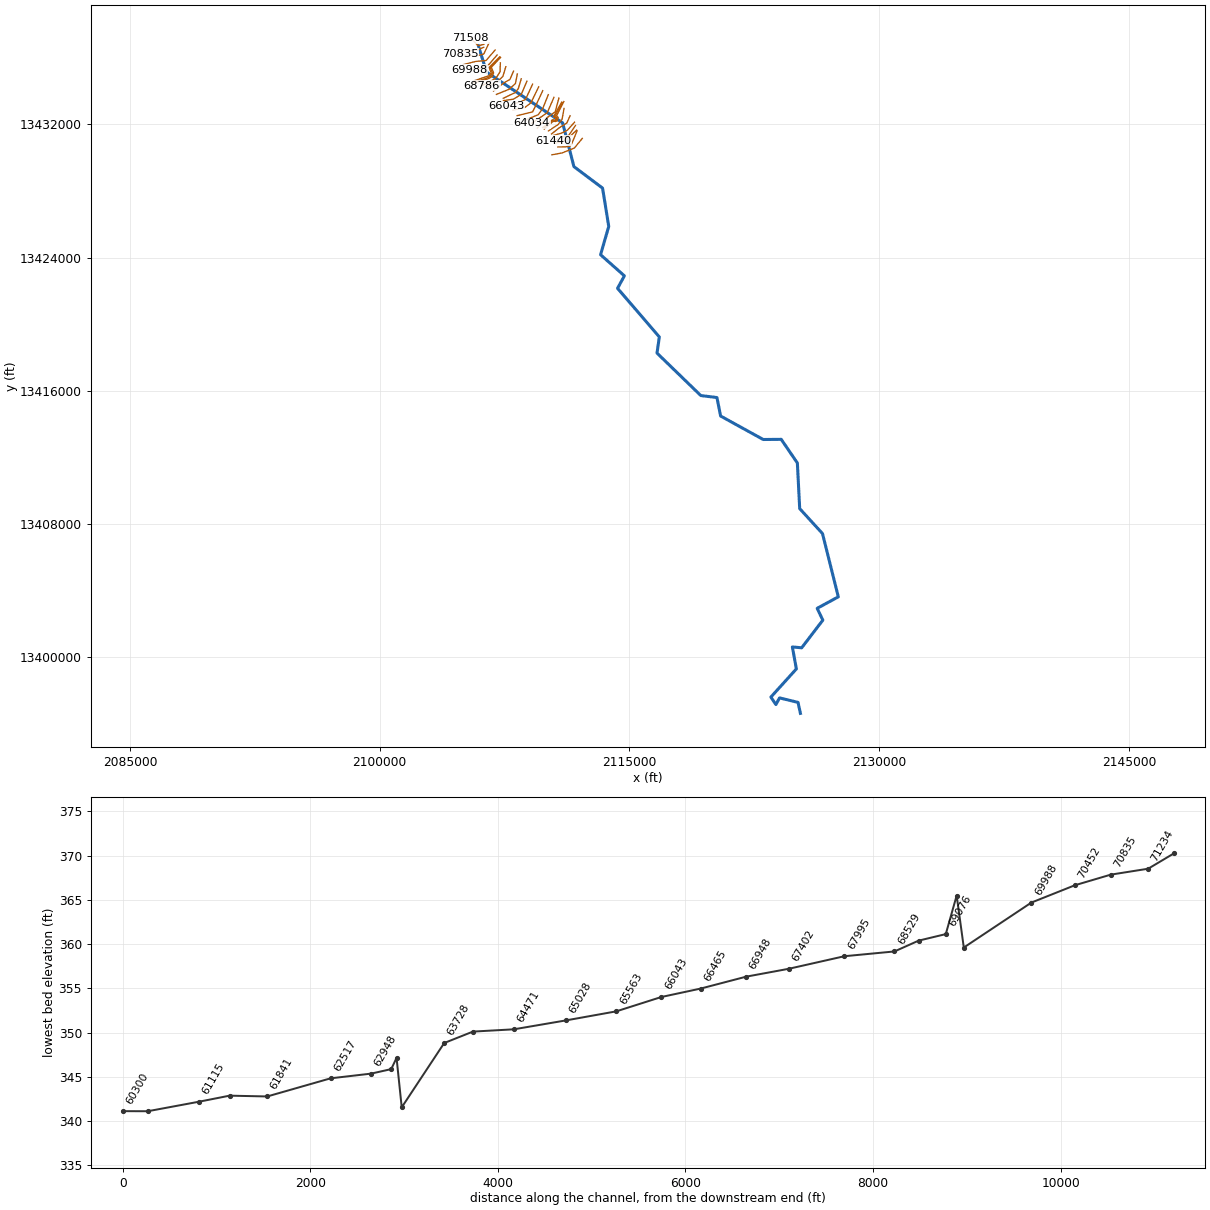
--- La Jarita Creek.prj (project) ---

Proj Title=La Jarita Creek Base Level Engineering
Current Plan=p01
Default Exp/Contr=0.3,0.1
English Units
Geom File=g01
Flow File=f01
Plan File=p01
Y Axis Title=Elevation
X Axis Title(PF)=Main Channel Distance
X Axis Title(XS)=Station
BEGIN DESCRIPTION:
La Jarita Creek
END DESCRIPTION:
DSS Export Rating Curves= 0
DSS Export Rating Curve Sorted= 0
DSS Export Volume Flow Curves= 0
DXF OffsetX= 0
DXF OffsetY= 0
DXF ScaleX= 1
DXF ScaleY= 10

--- La Jarita Creek.p01 (plan) ---

Plan Title=Multiple Run
Short Identifier=Multiple
Geom File=g01
Flow File=f01
Subcritical Flow
K Sum by GR= 0
Std Step Tol= 0.01
Critical Tol= 0.01
Num of Std Step Trials= 20
Max Error Tol= 0.3
Flow Tol Ratio= 0.001
Split Flow NTrial= 30
Split Flow Tol= 0.02
Split Flow Ratio= 0.02
Log Output Level= 0
Friction Slope Method= 1
Unsteady Friction Slope Method= 2
Unsteady Bridges Friction Slope Method= 1
Parabolic Critical Depth
Global Vel Dist=  1 , 1 , 1
Global Log Level= 0
CheckData=True
Encroach Param= -1, 0, 0, 0
BEGIN DESCRIPTION:
Multiple Run
END DESCRIPTION:

--- La Jarita Creek.f01 (steady flow) ---

Flow Title=Multiple
Program Version=5.05
Number of Profiles= 7
Profile Names=10-year,25-year,50-year,1pct_min,100-year,1pct_plu,500-year
River Rch & RM=La Jarita Creek,Reach-1         ,71508
     108     142     168      99     198     396     280
River Rch & RM=La Jarita Creek,Reach-1         ,71234
     179     242     292     176     352     701     516
River Rch & RM=La Jarita Creek,Reach-1         ,69268
     217     295     359     217     434     865     643
River Rch & RM=La Jarita Creek,Reach-1         ,66465
     234     320     390     237     472     942     703
River Rch & RM=La Jarita Creek,Reach-1         ,63728
     262     360     440     268     535    1068     803
River Rch & RM=La Jarita Creek,Reach-1         ,63275
     274     377     462     281     562    1121     844
River Rch & RM=La Jarita Creek,Reach-1         ,59681
     304     421     517     316     630    1258     952
River Rch & RM=La Jarita Creek,Reach-1         ,55204
     530     752     939     583    1163    2319    1811
River Rch & RM=La Jarita Creek,Reach-1         ,54723
     530     752     939     583    1163    2319    1811
River Rch & RM=La Jarita Creek,Reach-1         ,53761
     570     812    1016     632    1261    2515    1972
River Rch & RM=La Jarita Creek,Reach-1         ,53177
     627     895    1122     699    1395    2783    2189
River Rch & RM=La Jarita Creek,Reach-1         ,51260
     627     895    1122     699    1395    2783    2189
River Rch & RM=La Jarita Creek,Reach-1         ,46308
     646     922    1157     721    1439    2871    2261
River Rch & RM=La Jarita Creek,Reach-1         ,44953
     667     953    1197     746    1488    2969    2338
River Rch & RM=La Jarita Creek,Reach-1         ,43996
     806    1159    1461     914    1823    3637    2885
River Rch & RM=La Jarita Creek,Reach-1         ,38582
     835    1202    1517     950    1895    3780    3003
River Rch & RM=La Jarita Creek,Reach-1         ,34395
     884    1276    1612    1011    2017    4025    3208
River Rch & RM=La Jarita Creek,Reach-1         ,31329
     881    1270    1604    1005    2005    4000    3182
River Rch & RM=La Jarita Creek,Reach-1         ,28554
    1119    1628    2067    1302    2598    5183    4167
River Rch & RM=La Jarita Creek,Reach-1         ,24183
    1158    1685    2143    1350    2694    5376    4329
River Rch & RM=La Jarita Creek,Reach-1         ,21855
    1147    1669    2120    1335    2663    5314    4272
River Rch & RM=La Jarita Creek,Reach-1         ,21515
    1242    1810    2302    1451    2896    5777    4654
River Rch & RM=La Jarita Creek,Reach-1         ,19936
    1242    1810    2302    1451    2896    5777    4654
River Rch & RM=La Jarita Creek,Reach-1         ,13281
    1239    1804    2293    1445    2882    5751    4627
River Rch & RM=La Jarita Creek,Reach-1         ,9561
    1482    2167    2762    1745    3481    6946    5616
Boundary for River Rch & Prof#=La Jarita Creek,Reach-1         , 1
Up Type= 0
Dn Type= 3
Dn Slope=0.00054
Boundary for River Rch & Prof#=La Jarita Creek,Reach-1         , 2
Up Type= 0
Dn Type= 3
Dn Slope=0.00054
Boundary for River Rch & Prof#=La Jarita Creek,Reach-1         , 3
Up Type= 0
Dn Type= 3
Dn Slope=0.00054
Boundary for River Rch & Prof#=La Jarita Creek,Reach-1         , 4
Up Type= 0
Dn Type= 3
Dn Slope=0.00054
Boundary for River Rch & Prof#=La Jarita Creek,Reach-1         , 5
Up Type= 0
Dn Type= 3
Dn Slope=0.00054
Boundary for River Rch & Prof#=La Jarita Creek,Reach-1         , 6
Up Type= 0
Dn Type= 3
Dn Slope=0.00054
Boundary for River Rch & Prof#=La Jarita Creek,Reach-1         , 7
Up Type= 0
Dn Type= 3
Dn Slope=0.00054
DSS Import GetInterval= 0
DSS Import GetPeak= 0
DSS Import FillOption= 0

--- La Jarita Creek.g01 (geometry) ---

Geom Title=Existing Conditions

River Reach=La Jarita Creek,Reach-1
Reach XY= 30
      2105925.00     13436750.00      2106419.07     13435144.87
      2110990.80     13432094.54      2111670.80     13429464.54
      2113390.80     13428174.54      2113761.80     13425873.16
      2113270.80     13424174.54      2114700.80     13422904.54
      2114290.80     13422154.54      2116800.80     13419234.54
      2116660.80     13418264.54      2119290.80     13415714.54
      2120260.80     13415594.54      2120480.80     13414484.54
      2123040.80     13413074.54      2124120.80     13413084.54
      2125090.80     13411664.54      2125230.80     13408924.54
      2126600.80     13407424.54      2127550.80     13403624.54
      2126280.80     13402934.54      2126620.80     13402224.54
      2125350.80     13400564.54      2124790.80     13400614.54
      2125030.80     13399294.54      2123500.80     13397604.54
      2123800.80     13397154.54      2124020.80     13397554.54
      2125130.80     13397284.54      2125275.00     13396625.00

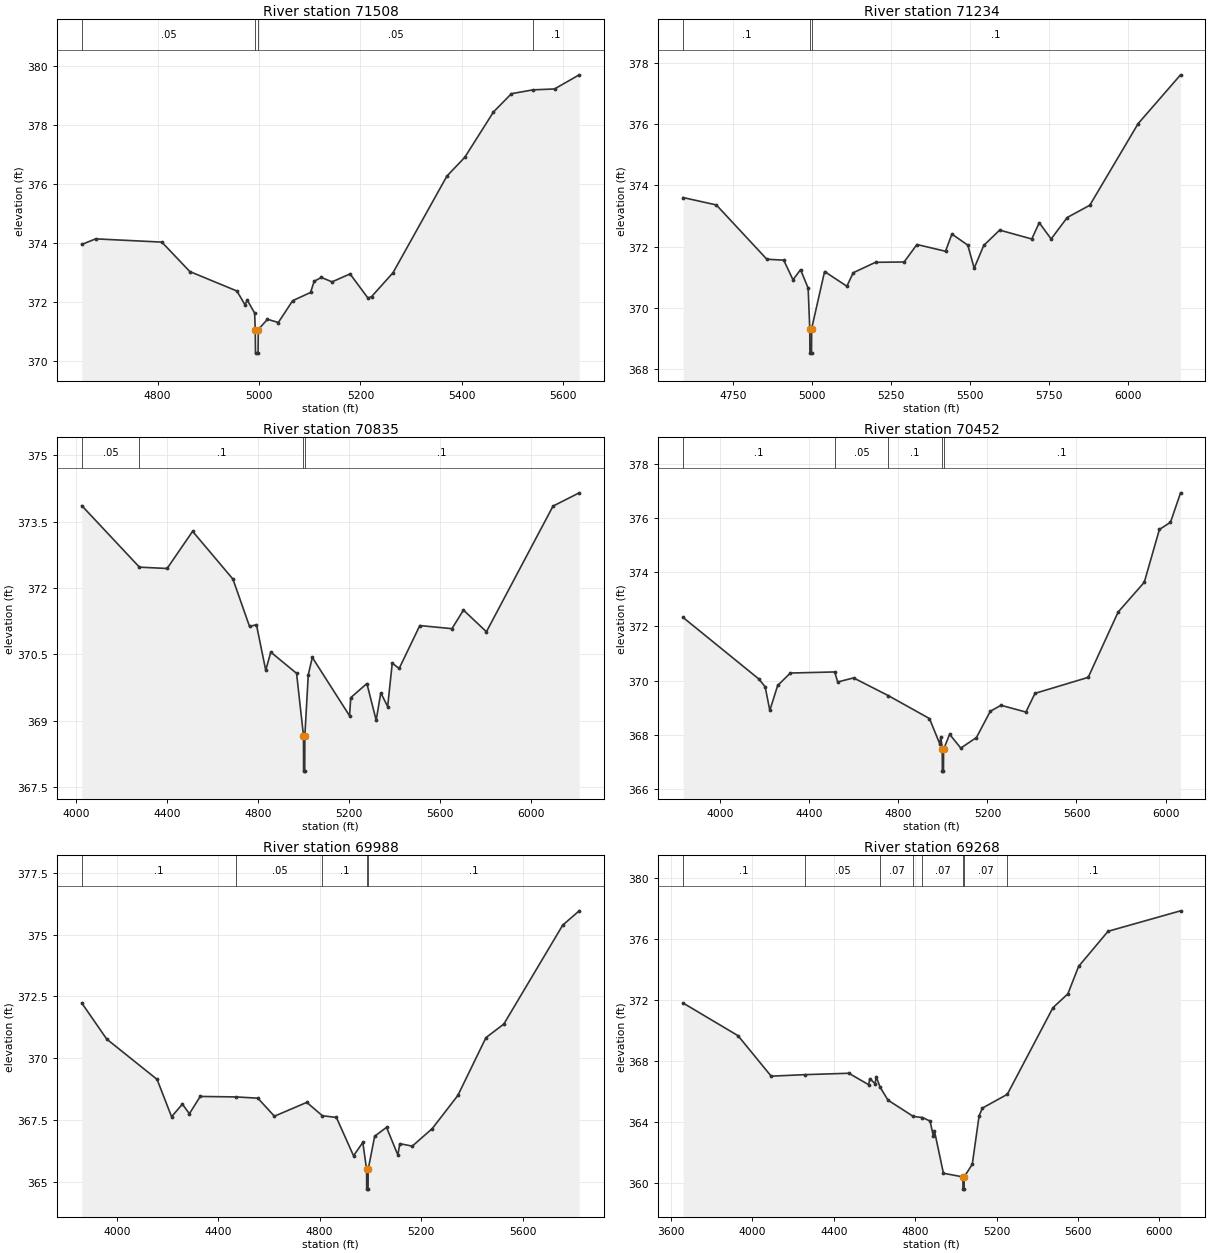
Type RM Length L Ch R = 1,71508,274,274,274
BEGIN DESCRIPTION:
La Jarita Creek 103.0
END DESCRIPTION:
XS GIS Cut Line= 3
      2106261.41     13436809.26      2105931.08     13436725.26
      2105471.10     13437170.04
#Sta/Elev= 30
  4650.7  373.95  4678.0  374.14  4808.5  374.03  4863.7  373.03  4956.5  372.37
  4972.2  371.91  4977.3  372.05  4991.5  371.62  4992.7  371.06  4993.2  370.26
  4998.2  370.26  4998.7  371.06  5016.8  371.41  5038.2  371.30  5066.4  372.04
  5101.7  372.32  5108.9  372.70  5123.0  372.83  5144.1  372.68  5179.6  372.95
  5214.9  372.13  5222.1  372.18  5264.3  372.99  5370.5  376.27  5405.8  376.91
  5462.4  378.45  5497.8  379.07  5540.5  379.20  5582.7  379.23  5631.4  379.71
#Mann=4,-1,0
  4650.7    0.05       0  4992.7    0.03       0  4998.7    0.05       0
  5540.5     0.1       0
Bank Sta=4992.7,4998.7
Exp/Cntr=0.3,0.1

Type RM Length L Ch R = 1,71234,399,399,399
BEGIN DESCRIPTION:
Mapping XS 85ee3f4c
END DESCRIPTION:
XS GIS Cut Line= 4
      2106252.29     13436631.96      2105876.82     13436477.86
      2105262.67     13436399.74      2104723.41     13436510.11
#Sta/Elev= 30
  4592.3  373.60  4697.4  373.36  4857.5  371.59  4910.9  371.56  4940.3  370.92
  4964.2  371.25  4988.2  370.65  4993.4  369.33  4993.9  368.53  4998.9  368.53
  4999.4  369.33  5040.3  371.19  5110.9  370.71  5131.0  371.15  5201.6  371.49
  5292.3  371.50  5332.7  372.07  5423.4  371.85  5443.5  372.41  5493.9  372.05
  5514.1  371.30  5544.4  372.04  5594.8  372.54  5696.5  372.25  5720.2  372.78
  5757.8  372.25  5808.8  372.95  5880.3  373.35  6033.4  376.01  6167.7  377.60
#Mann=3,-1,0
  4592.3     0.1       0  4993.4    0.07       0  4999.4     0.1       0
Bank Sta=4993.4,4999.4
Exp/Cntr=0.3,0.1

Type RM Length L Ch R = 1,70835,383,383,383
BEGIN DESCRIPTION:
Mapping XS c48ea927
END DESCRIPTION:
XS GIS Cut Line= 4
      2106574.03     13436894.80      2106254.57     13436228.11
      2105733.73     13436096.16      2104830.99     13436228.10
#Sta/Elev= 30
  4023.9  373.86  4277.6  372.47  4399.3  372.44  4511.6  373.28  4689.0  372.20
  4762.1  371.13  4792.4  371.17  4833.4  370.14  4855.6  370.55  4969.1  370.07
  4999.5  368.66  5000.0  367.86  5005.0  367.86  5005.5  368.66  5020.6  370.04
  5038.3  370.43  5202.3  369.11  5207.4  369.52  5278.5  369.84  5319.4  369.01
  5339.6  369.63  5369.9  369.32  5390.1  370.30  5420.5  370.18  5511.4  371.15
  5652.9  371.08  5703.4  371.50  5804.5  371.01  6097.6  373.85  6212.8  374.15
#Mann=4,-1,0
  4023.9    0.05       0  4277.6     0.1       0  4999.5    0.07       0
  5005.5     0.1       0
Bank Sta=4999.5,5005.5
Exp/Cntr=0.3,0.1

Type RM Length L Ch R = 1,70452,464,464,464
BEGIN DESCRIPTION:
Mapping XS 7d283762
END DESCRIPTION:
XS GIS Cut Line= 4
      2106935.13     13436464.22      2106393.46     13435839.22
      2105775.40     13435783.66      2105013.02     13435589.60
#Sta/Elev= 30
  3833.2  372.33  4173.3  370.06  4201.8  369.77  4222.6  368.90  4257.8  369.82
  4314.8  370.28  4514.1  370.32  4527.5  369.95  4598.8  370.10  4754.0  369.45
  4939.8  368.60  4985.8  367.67  4990.9  367.93  4997.1  367.46  4997.6  366.66
  5002.6  366.66  5003.1  367.46  5030.2  368.02  5080.4  367.51  5150.7  367.90
  5213.0  368.87  5261.1  369.09  5372.8  368.84  5413.7  369.53  5652.7  370.12
  5787.1  372.53  5904.6  373.63  5972.6  375.58  6022.2  375.84  6067.5  376.93
#Mann=5,-1,0
  3833.2     0.1       0  4514.1    0.05       0  4754.0     0.1       0
  4997.1    0.07       0  5003.1     0.1       0
Bank Sta=4997.1,5003.1
Exp/Cntr=0.3,0.1

Type RM Length L Ch R = 1,69988,720,720,720
BEGIN DESCRIPTION:
Mapping XS d32e5ff7
END DESCRIPTION:
XS GIS Cut Line= 4
      2107053.17     13436165.59      2106574.01     13435610.05
      2106053.18     13435380.89      2105400.43     13435297.56
#Sta/Elev= 30
  3862.4  372.23  3960.7  370.77  4159.2  369.14  4216.3  367.63  4259.0  368.14
  4286.5  367.75  4329.3  368.45  4471.4  368.43  4556.4  368.38  4621.6  367.65
  4749.3  368.21  4810.7  367.67  4866.0  367.60  4933.6  366.05  4970.2  366.59
  4985.0  365.50  4985.5  364.70  4990.8  364.70  4991.3  365.50  5016.9  366.84
  5063.6  367.20  5108.4  366.08  5115.7  366.54  5165.1  366.44  5243.9  367.15
  5344.7  368.49  5455.6  370.83  5526.1  371.38  5758.0  375.38  5823.1  375.96
#Mann=5,-1,0
  3862.4     0.1       0  4471.4    0.05       0  4810.7     0.1       0
  4985.0    0.07       0  4991.3     0.1       0
Bank Sta=4985,4991.3
Exp/Cntr=0.3,0.1

Type RM Length L Ch R = 1,69268,76,76,76
BEGIN DESCRIPTION:
Mapping XS b326ba41
END DESCRIPTION:
XS GIS Cut Line= 6
      2107204.19     13436047.53      2106579.22     13435427.76
      2106636.51     13435255.89      2106704.22     13435089.22
      2106563.60     13434922.55      2105631.28     13434604.84
#Sta/Elev= 30
  3659.3  371.81  3929.2  369.67  4091.9  367.02  4259.5  367.12  4473.7  367.21
  4571.1  366.46  4576.4  366.85  4602.8  366.53  4608.0  366.99  4627.1  366.30
  4666.0  365.45  4790.5  364.38  4835.4  364.31  4872.7  364.08  4889.1  363.08
  4894.5  363.42  4938.4  360.66  5034.1  360.42  5034.6  359.62  5039.9  359.62
  5040.4  360.42  5080.2  361.25  5113.7  364.42  5130.0  364.93  5252.3  365.83
  5476.8  371.51  5549.8  372.41  5602.7  374.21  5747.4  376.51  6103.6  377.85
#Mann=8,-1,0
  3659.3     0.1       0  4259.5    0.05       0  4627.1    0.07       0
  4790.5    0.05       0  4835.4    0.07       0  5034.1    0.07       0
  5040.4    0.07       0  5252.3     0.1       0
Bank Sta=5034.1,5040.4
Exp/Cntr=0.3,0.1

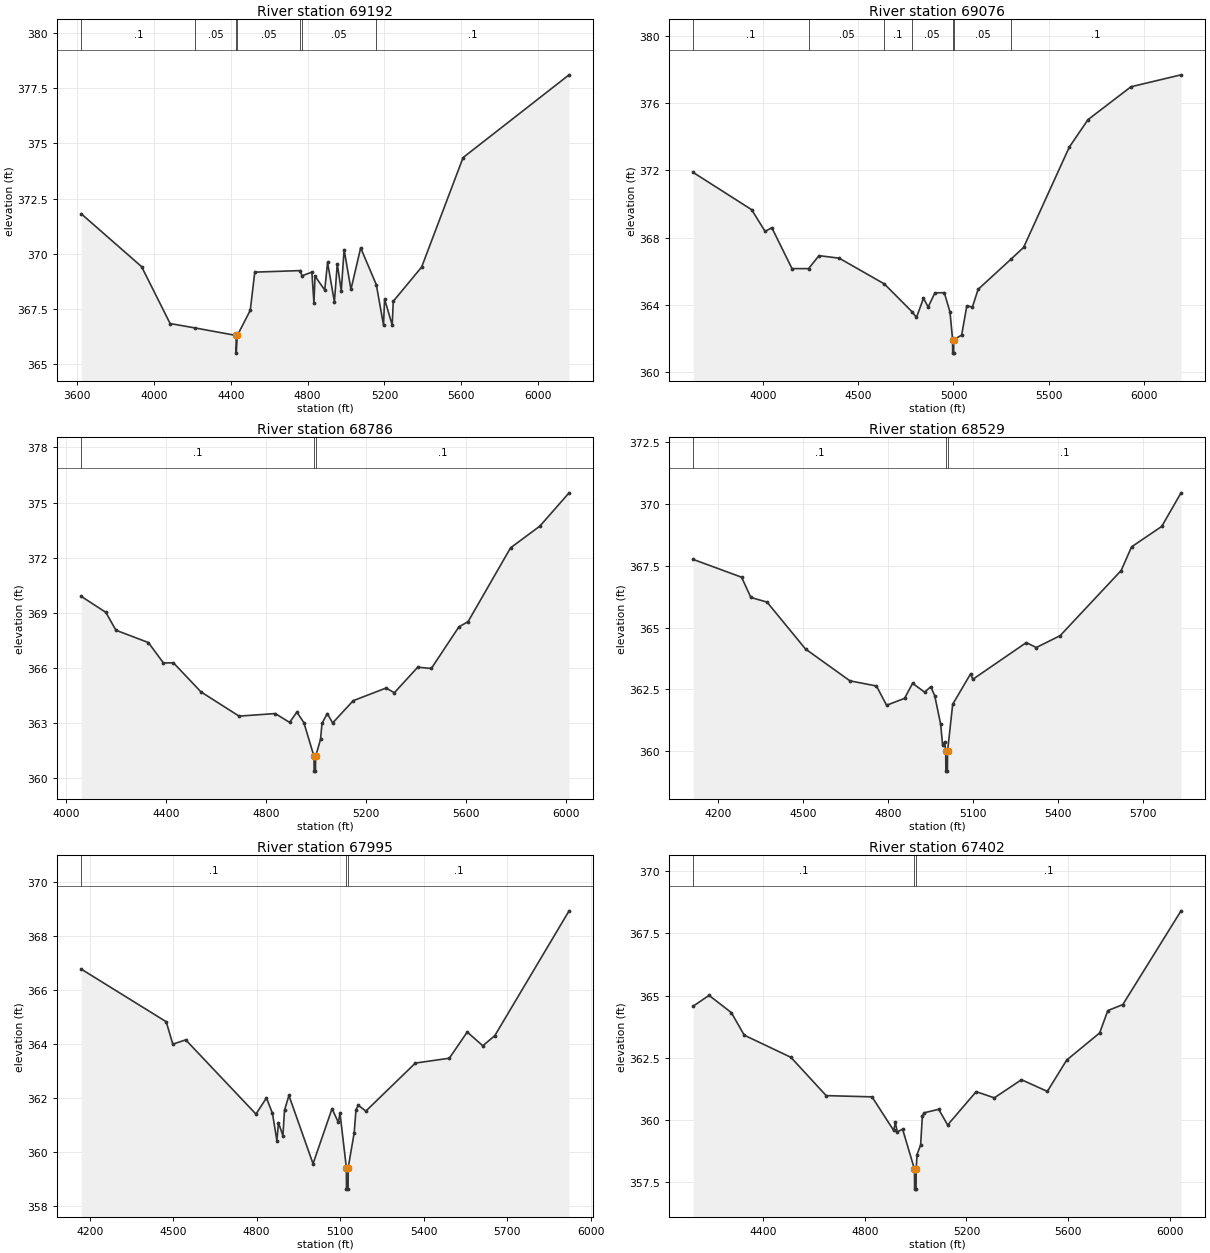
Type RM Length L Ch R = 1,69192,116,116,116
BEGIN DESCRIPTION:
Mapping XS ed44ecaa
END DESCRIPTION:
XS GIS Cut Line= 6
      2107226.77     13436026.70      2106636.51     13435422.55
      2106782.35     13435089.22      2106629.57     13434873.94
      2106400.40     13434762.83      2105622.59     13434533.65
#Sta/Elev= 30
  3622.5  371.81  3936.1  369.42  4084.7  366.84  4215.4  366.64  4428.0  366.30
  4428.5  365.50  4434.3  366.30  4501.7  367.44  4525.1  369.17  4762.5  369.24
  4770.0  369.00  4822.2  369.17  4833.0  367.77  4838.6  368.99  4889.1  368.36
  4903.9  369.61  4939.5  367.82  4954.3  369.54  4975.2  368.33  4990.0  370.19
  5025.6  368.39  5076.1  370.27  5157.6  368.60  5195.1  366.77  5200.6  367.95
  5240.2  366.77  5245.8  367.85  5393.4  369.40  5609.0  374.36  6160.5  378.11
#Mann=7,-1,0
  3622.5     0.1       0  4215.4    0.05       0  4428.0   0.035       0
  4434.3    0.05       0  4762.5    0.07       0  4770.0    0.05       0
  5157.6     0.1       0
Bank Sta=4428,4434.3
Exp/Cntr=0.3,0.1

Type RM Length L Ch R = 1,69076,290,290,290
BEGIN DESCRIPTION:
Mapping XS 955dd0e6
END DESCRIPTION:
XS GIS Cut Line= 6
      2107261.54     13436021.54      2106709.43     13435432.97
      2106844.85     13435099.64      2106766.72     13434896.51
      2106563.60     13434755.89      2105672.93     13434490.25
#Sta/Elev= 30
  3633.8  371.87  3940.3  369.66  4011.1  368.37  4046.3  368.59  4152.3  366.16
  4239.2  366.16  4293.9  366.93  4399.9  366.78  4637.1  365.25  4782.3  363.60
  4805.7  363.26  4842.5  364.40  4867.1  363.88  4902.5  364.72  4951.8  364.73
  4981.8  363.58  4995.3  361.94  4995.8  361.14  5001.1  361.14  5001.6  361.94
  5042.9  362.21  5069.9  363.94  5099.6  363.88  5129.4  364.93  5303.8  366.74
  5368.2  367.42  5608.2  373.38  5706.5  375.01  5931.7  376.96  6194.7  377.67
#Mann=7,-1,0
  3633.8     0.1       0  4239.2    0.05       0  4637.1     0.1       0
  4782.3    0.05       0  4995.3   0.035       0  5001.6    0.05       0
  5303.8     0.1       0
Bank Sta=4995.3,5001.6
Exp/Cntr=0.3,0.1

Type RM Length L Ch R = 1,68786,257,257,257
BEGIN DESCRIPTION:
Mapping XS 7e29cd06
END DESCRIPTION:
XS GIS Cut Line= 4
      2107251.10     13435693.39      2107235.47     13435162.14
      2106980.26     13434771.51      2106138.24     13434324.51
#Sta/Elev= 30
  4061.5  369.90  4159.9  369.03  4199.9  368.06  4330.0  367.39  4390.0  366.28
  4430.0  366.29  4540.1  364.71  4692.7  363.39  4837.6  363.53  4894.8  363.05
  4924.0  363.61  4952.1  363.03  4992.5  361.20  4993.0  360.40  4998.4  360.40
  4998.9  361.20  5018.6  362.13  5024.5  363.00  5045.6  363.53  5067.0  363.02
  5149.3  364.23  5281.2  364.92  5313.8  364.66  5407.4  366.05  5461.8  365.98
  5572.0  368.24  5609.0  368.53  5778.8  372.54  5896.1  373.72  6012.9  375.53
#Mann=3,-1,0
  4061.5     0.1       0  4992.5    0.07       0  4998.9     0.1       0
Bank Sta=4992.5,4998.9
Exp/Cntr=0.3,0.1

Type RM Length L Ch R = 1,68529,534,534,534
BEGIN DESCRIPTION:
Mapping XS 1d51aa2c
END DESCRIPTION:
XS GIS Cut Line= 4
      2107579.23     13435464.24      2107402.14     13434880.89
      2107053.18     13434552.76      2106485.46     13434271.51
#Sta/Elev= 30
  4112.8  367.76  4283.4  367.04  4316.2  366.22  4373.3  366.03  4509.1  364.13
  4666.0  362.84  4759.7  362.63  4795.4  361.85  4858.9  362.13  4887.2  362.74
  4929.7  362.38  4951.1  362.60  4965.3  362.24  4986.3  361.08  4993.2  360.23
  5000.5  360.36  5004.2  359.98  5004.7  359.18  5010.1  359.18  5010.6  359.98
  5028.8  361.89  5092.3  363.13  5099.6  362.90  5288.7  364.39  5324.0  364.19
  5408.1  364.67  5623.5  367.31  5660.4  368.27  5766.9  369.10  5835.0  370.46
#Mann=3,-1,0
  4112.8     0.1       0  5004.2    0.07       0  5010.6     0.1       0
Bank Sta=5004.2,5010.6
Exp/Cntr=0.3,0.1

Type RM Length L Ch R = 1,67995,593,593,593
BEGIN DESCRIPTION:
Mapping XS 1769b4c0
END DESCRIPTION:
XS GIS Cut Line= 4
      2108042.78     13435198.62      2107824.01     13434698.59
      2107464.64     13434495.47      2106839.81     13434006.02
#Sta/Elev= 30
  4170.0  366.79  4475.2  364.84  4498.6  364.01  4545.1  364.17  4797.5  361.42
  4835.1  362.02  4856.7  361.45  4872.6  360.44  4878.4  361.10  4894.3  360.62
  4900.0  361.56  4915.9  362.11  5002.5  359.58  5070.7  361.62  5093.5  361.11
  5099.3  361.46  5122.2  359.44  5122.7  358.64  5128.4  358.64  5128.9  359.44
  5150.4  360.73  5156.8  361.58  5164.9  361.75  5192.1  361.53  5370.2  363.31
  5492.2  363.49  5556.4  364.46  5612.5  363.95  5655.8  364.33  5922.3  368.95
#Mann=3,-1,0
  4170.0     0.1       0  5122.2    0.07       0  5128.9     0.1       0
Bank Sta=5122.2,5128.9
Exp/Cntr=0.3,0.1

Type RM Length L Ch R = 1,67402,454,454,454
BEGIN DESCRIPTION:
Mapping XS 01d2c53b
END DESCRIPTION:
XS GIS Cut Line= 4
      2108271.92     13435031.89      2108157.35     13434453.80
      2107771.93     13434110.05      2107018.39     13433803.44
#Sta/Elev= 30
  4124.9  364.58  4187.1  365.01  4274.6  364.32  4325.6  363.41  4509.1  362.52
  4647.9  360.98  4828.2  360.93  4913.5  359.58  4920.2  359.90  4927.7  359.52
  4948.6  359.63  4995.4  358.02  4995.9  357.22  5001.6  357.22  5002.1  358.02
  5005.4  358.61  5019.6  359.00  5026.3  360.16  5033.9  360.29  5090.7  360.43
  5125.8  359.80  5238.2  361.14  5309.4  360.89  5416.4  361.62  5518.1  361.15
  5594.4  362.41  5724.0  363.50  5756.2  364.40  5815.1  364.64  6044.2  368.41
#Mann=3,-1,0
  4124.9     0.1       0  4995.4    0.07       0  5002.1     0.1       0
Bank Sta=4995.4,5002.1
Exp/Cntr=0.3,0.1

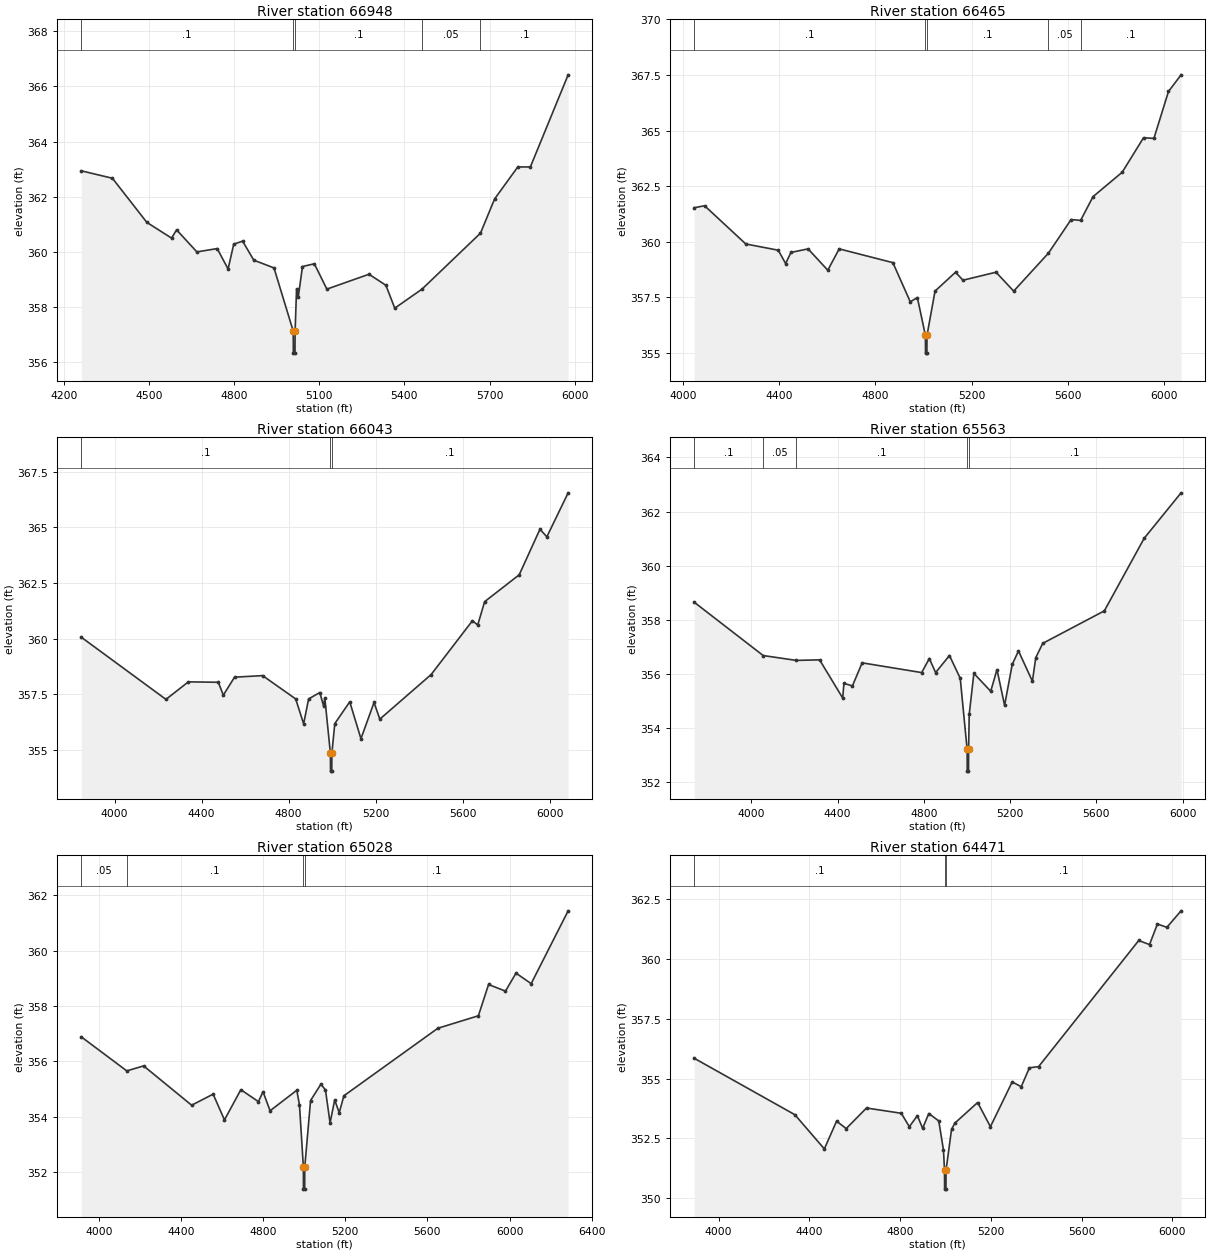
Type RM Length L Ch R = 1,66948,483,483,483
BEGIN DESCRIPTION:
Mapping XS c0fcac79
END DESCRIPTION:
XS GIS Cut Line= 4
      2108506.30     13434740.24      2108334.43     13434162.14
      2108157.35     13433917.34      2107424.70     13433569.21
#Sta/Elev= 30
  4260.8  362.94  4370.6  362.67  4492.0  361.07  4579.2  360.50  4596.8  360.80
  4668.4  360.00  4740.0  360.12  4778.4  359.38  4798.3  360.28  4829.6  360.39
  4869.0  359.70  4940.2  359.42  5008.0  357.13  5008.5  356.33  5014.2  356.33
  5014.7  357.13  5019.8  358.66  5026.0  358.38  5040.7  359.47  5082.5  359.57
  5126.6  358.65  5275.1  359.19  5334.7  358.79  5366.0  357.96  5462.0  358.65
  5668.2  360.68  5717.9  361.92  5799.7  363.08  5844.0  363.08  5977.2  366.42
#Mann=5,-1,0
  4260.8     0.1       0  5008.0    0.07       0  5014.7     0.1       0
  5462.0    0.05       0  5668.2     0.1       0
Bank Sta=5008,5014.7
Exp/Cntr=0.3,0.1

Type RM Length L Ch R = 1,66465,422,422,422
BEGIN DESCRIPTION:
Mapping XS 9289b735
END DESCRIPTION:
XS GIS Cut Line= 4
      2108844.86     13434594.47      2108511.51     13433807.97
      2108037.55     13433516.30      2107433.34     13433427.75
#Sta/Elev= 30
  4047.5  361.53  4090.7  361.62  4261.8  359.90  4396.5  359.62  4427.1  359.02
  4449.3  359.52  4520.3  359.68  4602.2  358.72  4649.5  359.68  4872.4  359.06
  4944.6  357.30  4974.1  357.49  5007.4  355.79  5007.9  354.99  5013.6  354.99
  5014.1  355.79  5047.4  357.78  5132.6  358.63  5163.4  358.27  5300.6  358.63
  5374.0  357.78  5518.4  359.49  5612.4  361.00  5651.8  360.96  5703.4  362.03
  5824.7  363.13  5913.0  364.68  5956.1  364.65  6016.7  366.76  6068.9  367.51
#Mann=5,-1,0
  4047.5     0.1       0  5007.4    0.07       0  5014.1     0.1       0
  5518.4    0.05       0  5651.8     0.1       0
Bank Sta=5007.4,5014.1
Exp/Cntr=0.3,0.1

Type RM Length L Ch R = 1,66043,480,480,480
BEGIN DESCRIPTION:
Mapping XS c9516ba1
END DESCRIPTION:
XS GIS Cut Line= 4
      2109183.41     13434412.18      2108761.51     13433495.47
      2108490.68     13433370.47      2107607.11     13433079.41
#Sta/Elev= 30
  3846.9  360.06  4236.2  357.26  4339.2  358.05  4476.9  358.03  4499.8  357.45
  4551.3  358.26  4680.4  358.33  4832.4  357.28  4868.9  356.16  4891.8  357.28
  4943.2  357.57  4960.7  356.96  4966.2  357.33  4992.0  354.83  4992.5  354.03
  4998.2  354.03  4998.7  354.83  5012.1  356.17  5080.9  357.15  5132.3  355.49
  5192.5  357.12  5219.0  356.37  5455.1  358.38  5644.6  360.80  5669.1  360.61
  5700.8  361.66  5859.7  362.87  5955.0  364.92  5986.8  364.58  6084.6  366.56
#Mann=3,-1,0
  3846.9     0.1       0  4992.0    0.07       0  4998.7     0.1       0
Bank Sta=4992,4998.7
Exp/Cntr=0.3,0.1

Type RM Length L Ch R = 1,65563,535,535,535
BEGIN DESCRIPTION:
Mapping XS 651d5855
END DESCRIPTION:
XS GIS Cut Line= 4
      2109553.16     13434255.84      2109084.43     13433292.34
      2108730.26     13433021.51      2108008.17     13432855.27
#Sta/Elev= 30
  3734.9  358.65  4054.9  356.68  4208.4  356.50  4316.6  356.52  4423.8  355.11
  4429.4  355.65  4468.9  355.56  4514.0  356.41  4790.2  356.05  4825.6  356.57
  4854.7  356.05  4918.9  356.68  4968.9  355.84  5000.9  353.21  5001.4  352.41
  5007.2  352.41  5007.7  353.21  5010.6  354.51  5032.2  356.02  5110.3  355.36
  5139.4  356.16  5174.7  354.84  5210.1  356.35  5239.1  356.85  5303.7  355.73
  5319.2  356.60  5351.6  357.13  5637.3  358.33  5822.0  361.01  5993.2  362.69
#Mann=5,-1,0
  3734.9     0.1       0  4054.9    0.05       0  4208.4     0.1       0
  5000.9    0.07       0  5007.7     0.1       0
Bank Sta=5000.9,5007.7
Exp/Cntr=0.3,0.1

Type RM Length L Ch R = 1,65028,557,557,557
BEGIN DESCRIPTION:
Mapping XS 22e0d1d1
END DESCRIPTION:
XS GIS Cut Line= 4
      2109797.96     13434026.69      2109381.30     13433136.09
      2109188.60     13432750.68      2108258.11     13432527.15
#Sta/Elev= 30
  3914.4  356.89  4136.1  355.66  4218.1  355.84  4452.0  354.42  4556.6  354.82
  4611.8  353.89  4691.5  354.98  4777.3  354.55  4799.5  354.91  4834.0  354.22
  4964.0  354.96  4977.1  354.43  4996.0  352.19  4996.5  351.39  5002.4  351.39
  5002.9  352.19  5031.1  354.59  5081.4  355.18  5103.7  354.97  5126.1  353.78
  5148.5  354.61  5170.8  354.15  5193.2  354.76  5651.1  357.20  5848.4  357.65
  5897.9  358.78  5980.2  358.54  6031.6  359.19  6105.4  358.81  6285.5  361.44
#Mann=4,-1,0
  3914.4    0.05       0  4136.1     0.1       0  4996.0    0.07       0
  5002.9     0.1       0
Bank Sta=4996,5002.9
Exp/Cntr=0.3,0.1

Type RM Length L Ch R = 1,64471,437,437,437
BEGIN DESCRIPTION:
Mapping XS c7dbae43
END DESCRIPTION:
XS GIS Cut Line= 4
      2110131.29     13433787.10      2109797.97     13432953.80
      2109527.14     13432584.01      2108799.01     13432277.16
#Sta/Elev= 30
  3892.7  355.85  4336.5  353.49  4466.4  352.06  4520.3  353.22  4562.7  352.91
  4652.2  353.77  4805.5  353.55  4841.0  352.99  4876.5  353.45  4899.6  352.92
  4926.7  353.54  4970.7  353.23  4991.5  352.01  4996.0  351.18  4996.5  350.38
  5002.4  350.38  5002.9  351.18  5027.1  352.88  5041.7  353.14  5142.1  354.00
  5198.4  352.99  5294.3  354.86  5334.2  354.66  5370.2  355.45  5410.8  355.50
  5852.1  360.77  5899.6  360.60  5934.5  361.46  5976.2  361.32  6038.7  362.01
#Mann=3,-1,0
  3892.7     0.1       0  4996.0    0.07       0  5002.9     0.1       0
Bank Sta=4996,5002.9
Exp/Cntr=0.3,0.1

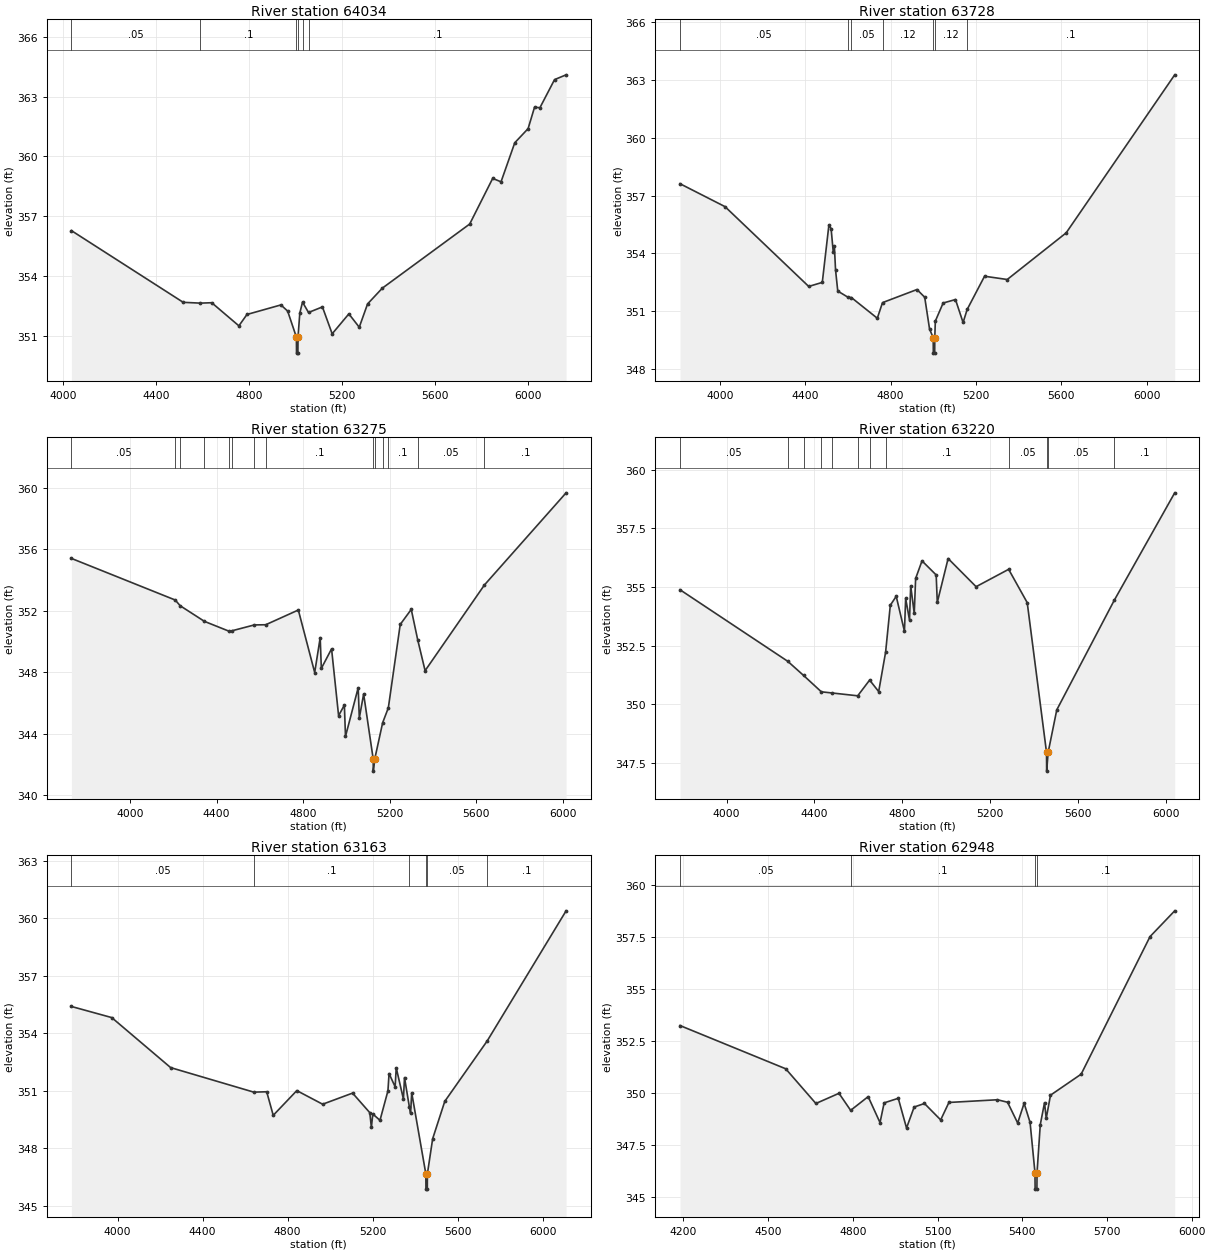
Type RM Length L Ch R = 1,64034,306,306,306
BEGIN DESCRIPTION:
Mapping XS 23389f3b
END DESCRIPTION:
XS GIS Cut Line= 3
      2110469.83     13433625.64      2110068.80     13432703.80
      2109142.90     13432069.19
#Sta/Elev= 30
  4036.6  356.27  4517.5  352.67  4591.1  352.63  4640.2  352.65  4757.0  351.49
  4791.7  352.06  4937.8  352.54  4966.7  352.23  5004.4  350.92  5004.9  350.12
  5010.8  350.12  5011.3  350.92  5019.0  352.13  5030.7  352.68  5056.5  352.16
  5116.3  352.44  5158.2  351.09  5230.0  352.09  5274.7  351.42  5310.5  352.59
  5373.8  353.38  5749.7  356.60  5848.6  358.89  5884.5  358.72  5943.6  360.68
  6001.0  361.39  6028.5  362.46  6051.8  362.44  6114.7  363.85  6164.4  364.09
#Mann=6,-1,0
  4036.6    0.05       0  4591.1     0.1       0  5004.4    0.07       0
  5011.3     0.1       0  5030.7    0.12       0  5056.5     0.1       0
Bank Sta=5004.4,5011.3
Exp/Cntr=0.3,0.1

Type RM Length L Ch R = 1,63728,453,453,453
BEGIN DESCRIPTION:
Mapping XS 0a5c65b3
END DESCRIPTION:
XS GIS Cut Line= 4
      2110766.71     13433578.76      2110547.97     13432761.09
      2110042.76     13432396.51      2109464.64     13431776.73
#Sta/Elev= 30
  3813.7  357.62  4024.6  356.43  4416.5  352.29  4480.1  352.50  4511.2  355.49
  4521.5  355.28  4531.4  354.08  4536.6  354.40  4542.2  353.14  4552.6  352.05
  4598.9  351.74  4616.8  351.71  4737.8  350.64  4762.1  351.45  4923.6  352.13
  4959.8  351.73  4982.5  350.08  4999.6  349.63  5000.2  348.83  5006.5  348.83
  5007.0  349.63  5009.5  350.49  5046.1  351.43  5103.9  351.61  5139.5  350.42
  5158.8  351.10  5240.1  352.82  5346.3  352.65  5622.3  355.07  6130.7  363.27
#Mann=7,-1,0
  3813.7    0.05       0  4598.9     0.1       0  4616.8    0.05       0
  4762.1    0.12       0  4999.6    0.07       0  5007.0    0.12       0
  5158.8     0.1       0
Bank Sta=4999.6,5007
Exp/Cntr=0.3,0.1

Type RM Length L Ch R = 1,63275,55,55,55
BEGIN DESCRIPTION:
Mapping XS 9c6faddc
END DESCRIPTION:
XS GIS Cut Line= 6
      2110939.44     13433340.05      2110435.99     13432454.67
      2110609.60     13432392.17      2110564.46     13432253.28
      2110380.44     13432281.06      2109794.33     13431809.40
#Sta/Elev= 30
  3728.8  355.41  4209.0  352.70  4231.6  352.33  4344.0  351.31  4459.5  350.66
  4471.8  350.70  4575.0  351.08  4627.2  351.09  4778.1  352.05  4853.8  347.98
  4879.2  350.25  4884.5  348.25  4931.8  349.52  4964.3  345.17  4991.0  345.86
  4996.2  343.82  5054.9  346.99  5060.1  345.02  5080.1  346.58  5124.2  342.36
  5124.8  341.56  5131.6  342.36  5168.0  344.71  5194.3  345.68  5249.3  351.11
  5300.3  352.09  5330.1  350.11  5364.3  348.10  5638.6  353.68  6016.3  359.68
#Mann=14,-1,0
  3728.8    0.05       0  4209.0     0.1       0  4231.6    0.05       0
  4344.0     0.1       0  4459.5    0.05       0  4471.8     0.1       0
  4575.0    0.12       0  4627.2     0.1       0  5124.2    0.07       0
  5131.6     0.1       0  5168.0    0.05       0  5194.3     0.1       0
  5330.1    0.05       0  5638.6     0.1       0
Bank Sta=5124.2,5131.6
Exp/Cntr=0.3,0.1

Type RM Length L Ch R = 1,63220,57,57,57
BEGIN DESCRIPTION:
Mapping XS 83352f89
END DESCRIPTION:
XS GIS Cut Line= 6
      2110991.88     13433305.48      2110510.10     13432476.47
      2110653.33     13432389.67      2110570.86     13432172.65
      2110375.55     13432233.42      2109868.83     13431804.66
#Sta/Elev= 30
  3788.2  354.88  4278.5  351.83  4350.1  351.23  4431.2  350.53  4480.5  350.48
  4596.7  350.36  4650.9  351.03  4692.1  350.54  4723.6  352.22  4745.0  354.22
  4771.9  354.60  4809.3  353.11  4814.8  354.51  4832.3  353.59  4837.8  355.05
  4853.9  353.87  4860.2  355.36  4889.2  356.11  4953.7  355.51  4958.7  354.34
  5008.0  356.21  5135.3  355.01  5283.3  355.75  5367.9  354.33  5455.7  347.95
  5456.3  347.15  5463.1  347.95  5502.3  349.76  5763.8  354.43  6038.9  359.01
#Mann=12,-1,0
  3788.2    0.05       0  4278.5     0.1       0  4350.1    0.05       0
  4431.2     0.1       0  4480.5    0.05       0  4596.7     0.1       0
  4650.9    0.12       0  4723.6     0.1       0  5283.3    0.05       0
  5455.7    0.07       0  5463.1    0.05       0  5763.8     0.1       0
Bank Sta=5455.7,5463.1
Exp/Cntr=0.3,0.1

Type RM Length L Ch R = 1,63163,215,215,215
BEGIN DESCRIPTION:
Mapping XS 3e71f0c2
END DESCRIPTION:
XS GIS Cut Line= 6
      2111064.48     13433373.10      2110621.76     13432509.36
      2110730.26     13432413.87      2110665.16     13432205.54
      2110404.74     13432170.82      2109884.20     13431719.68
#Sta/Elev= 30
  3782.4  355.41  3972.3  354.83  4249.6  352.22  4640.9  350.94  4701.7  350.96
  4732.4  349.73  4843.4  351.02  4965.0  350.31  5105.9  350.89  5186.9  349.87
  5194.4  349.10  5201.1  349.80  5234.9  349.47  5272.4  351.01  5277.6  351.91
  5306.2  351.22  5311.4  352.21  5345.2  350.58  5350.4  351.70  5372.9  350.19
  5379.0  349.83  5384.2  350.91  5450.7  346.68  5451.3  345.88  5457.6  345.88
  5458.1  346.68  5482.9  348.51  5539.9  350.46  5739.5  353.61  6111.0  360.40
#Mann=6,-1,0
  3782.4    0.05       0  4640.9     0.1       0  5372.9    0.05       0
  5450.7    0.07       0  5458.1    0.05       0  5739.5     0.1       0
Bank Sta=5450.7,5458.1
Exp/Cntr=0.3,0.1

Type RM Length L Ch R = 1,62948,431,431,431
BEGIN DESCRIPTION:
Mapping XS 6e8eb292
END DESCRIPTION:
XS GIS Cut Line= 4
      2111076.62     13432959.01      2110959.43     13432312.31
      2110720.71     13431991.13      2110140.21     13431609.90
#Sta/Elev= 30
  4188.1  353.24  4562.4  351.16  4669.3  349.49  4751.1  349.98  4792.4  349.16
  4854.4  349.82  4896.4  348.57  4911.0  349.52  4961.0  349.74  4990.3  348.31
  5017.3  349.32  5053.8  349.49  5111.2  348.70  5140.4  349.54  5312.2  349.67
  5348.1  349.55  5383.9  348.55  5406.7  349.50  5427.8  348.58  5445.1  346.17
  5445.7  345.37  5452.0  345.37  5452.5  346.17  5463.9  348.47  5479.0  349.53
  5485.0  348.77  5500.1  349.89  5608.6  350.90  5852.6  357.52  5940.0  358.76
#Mann=4,-1,0
  4188.1    0.05       0  4792.4     0.1       0  5445.1    0.07       0
  5452.5     0.1       0
Bank Sta=5445.1,5452.5
Exp/Cntr=0.3,0.1

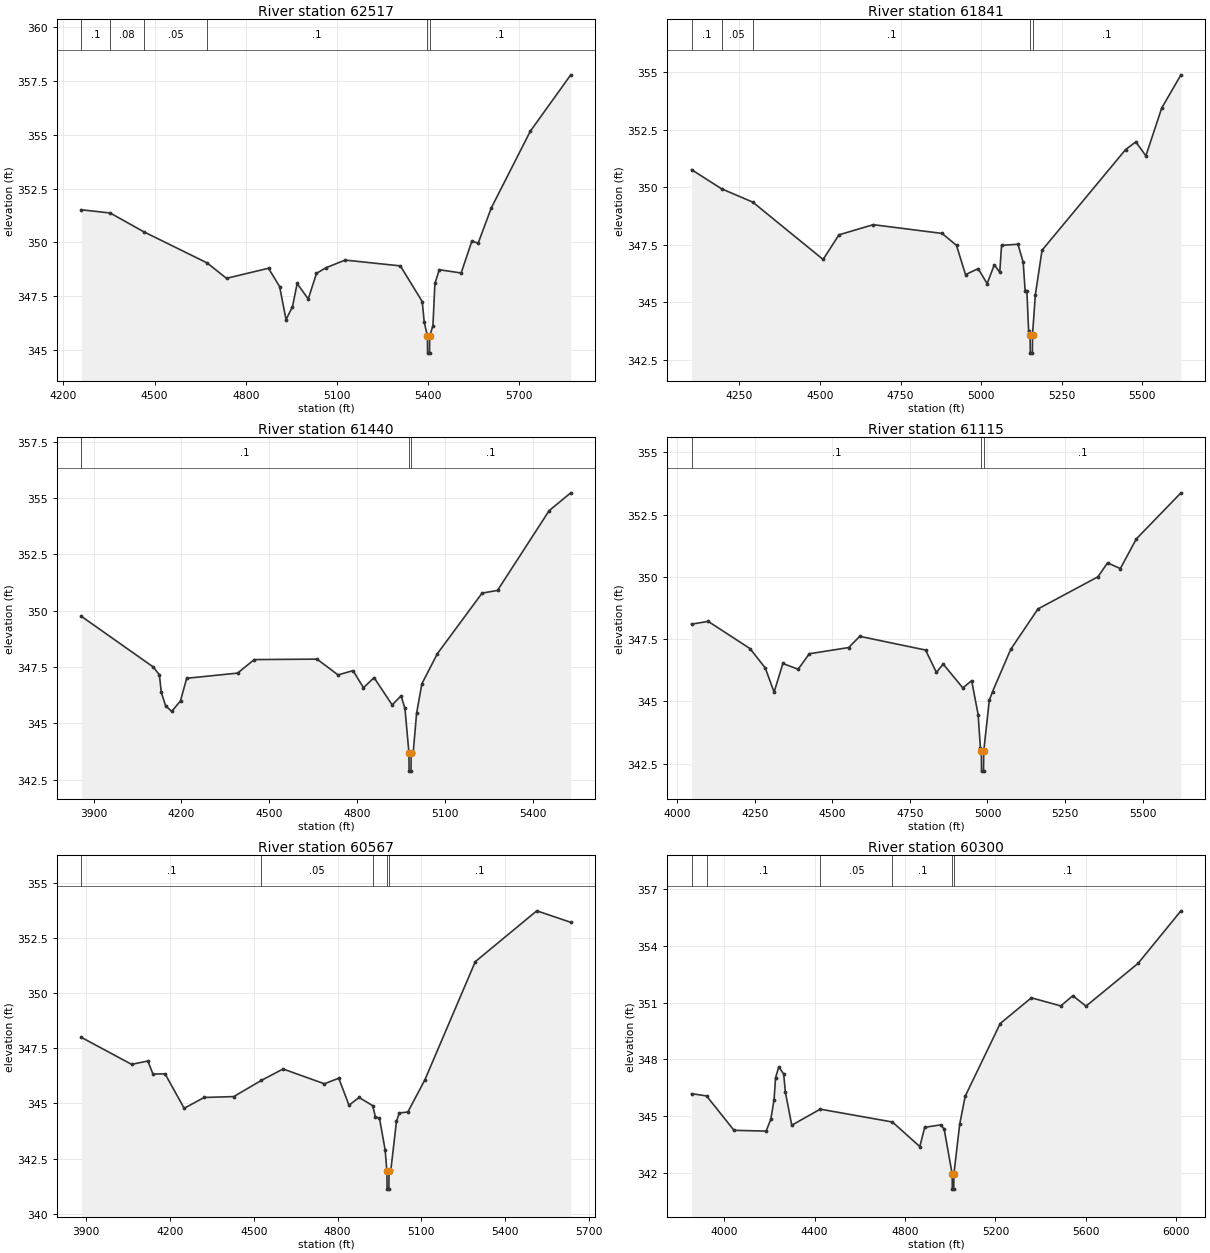
Type RM Length L Ch R = 1,62517,676,676,676
BEGIN DESCRIPTION:
Mapping XS ed6b5707
END DESCRIPTION:
XS GIS Cut Line= 4
      2111441.19     13432520.63      2111241.55     13432082.27
      2110785.82     13431795.82      2110325.73     13431426.88
#Sta/Elev= 30
  4259.5  351.51  4354.4  351.36  4464.3  350.49  4672.8  349.04  4736.9  348.32
  4875.0  348.79  4911.5  347.94  4932.7  346.40  4953.9  347.00  4969.2  348.08
  5005.7  347.36  5032.8  348.55  5063.4  348.81  5127.0  349.17  5308.6  348.90
  5380.7  347.24  5387.1  346.29  5397.7  345.64  5398.3  344.84  5404.6  344.84
  5405.2  345.64  5415.9  346.12  5422.3  348.08  5436.7  348.72  5508.7  348.57
  5543.9  350.05  5564.7  349.96  5607.9  351.60  5735.9  355.16  5869.2  357.79
#Mann=6,-1,0
  4259.5     0.1       0  4354.4    0.08       0  4464.3    0.05       0
  4672.8     0.1       0  5397.7    0.07       0  5405.2     0.1       0
Bank Sta=5397.7,5405.2
Exp/Cntr=0.3,0.1

Type RM Length L Ch R = 1,61841,401,401,401
BEGIN DESCRIPTION:
Mapping XS fbadbed7
END DESCRIPTION:
XS GIS Cut Line= 4
      2111705.98     13432130.05      2111276.27     13431652.59
      2110920.37     13431474.64      2110460.30     13431344.43
#Sta/Elev= 30
  4101.6  350.76  4194.5  349.93  4291.5  349.35  4509.7  346.86  4559.0  347.93
  4665.2  348.37  4878.9  347.99  4923.6  347.47  4951.6  346.20  4990.7  346.46
  5018.7  345.81  5041.0  346.63  5057.8  346.30  5063.4  347.47  5114.3  347.52
  5130.5  346.74  5136.5  345.51  5141.9  345.51  5147.4  343.74  5152.0  343.59
  5152.6  342.79  5159.0  342.79  5159.5  343.59  5168.2  345.32  5189.0  347.26
  5448.1  351.63  5480.0  351.97  5511.2  351.36  5560.4  353.44  5620.0  354.88
#Mann=5,-1,0
  4101.6     0.1       0  4194.5    0.05       0  4291.5     0.1       0
  5152.0    0.07       0  5159.5     0.1       0
Bank Sta=5152,5159.5
Exp/Cntr=0.3,0.1

Type RM Length L Ch R = 1,61440,325,325,325
BEGIN DESCRIPTION:
Mapping XS 2f18f4b5
END DESCRIPTION:
XS GIS Cut Line= 4
      2111760.08     13431929.57      2111354.39     13431331.41
      2110959.43     13431244.60      2110460.30     13431031.93
#Sta/Elev= 30
  3858.6  349.75  4104.0  347.50  4124.9  347.15  4131.0  346.39  4145.9  345.78
  4166.9  345.53  4196.8  346.00  4217.8  347.00  4391.5  347.23  4448.4  347.83
  4662.6  347.85  4734.3  347.15  4785.5  347.34  4821.1  346.58  4857.2  347.03
  4918.9  345.82  4949.3  346.22  4962.6  345.66  4976.3  343.68  4976.8  342.88
  4983.2  342.88  4983.8  343.68  4990.9  343.73  5002.2  345.44  5020.4  346.76
  5073.1  348.09  5225.7  350.78  5278.4  350.90  5454.6  354.44  5528.3  355.23
#Mann=3,-1,0
  3858.6     0.1       0  4976.3    0.07       0  4983.8     0.1       0
Bank Sta=4976.3,4983.8
Exp/Cntr=0.3,0.1

Type RM Length L Ch R = 1,61115,548,548,548
BEGIN DESCRIPTION:
Mapping XS 30362602
END DESCRIPTION:
XS GIS Cut Line= 3
      2111834.36     13431651.37      2111137.38     13431010.23
      2110525.37     13430858.31
#Sta/Elev= 30
  4046.2  348.10  4099.7  348.21  4234.5  347.12  4283.8  346.34  4312.2  345.37
  4340.5  346.52  4389.9  346.29  4425.6  346.91  4552.6  347.16  4588.4  347.61
  4800.5  347.06  4835.6  346.16  4857.2  346.50  4920.7  345.54  4949.1  345.83
  4970.0  344.47  4977.4  343.11  4980.4  343.00  4981.0  342.20  4987.4  342.20
  4988.0  343.00  5006.0  345.04  5016.3  345.39  5075.1  347.09  5162.9  348.71
  5356.3  350.00  5387.2  350.56  5428.4  350.33  5479.9  351.52  5623.8  353.37
#Mann=3,-1,0
  4046.2     0.1       0  4980.4    0.07       0  4988.0     0.1       0
Bank Sta=4980.4,4988
Exp/Cntr=0.3,0.1

Type RM Length L Ch R = 1,60567,267,267,267
BEGIN DESCRIPTION:
Mapping XS 5c6d0b2c
END DESCRIPTION:
XS GIS Cut Line= 5
      2111860.85     13431611.52      2111546.06     13430856.47
      2111445.54     13430697.73      2111159.08     13430649.98
      2110703.35     13430645.64
#Sta/Elev= 30
  3882.9  347.99  4062.5  346.77  4120.9  346.92  4139.2  346.33  4182.5  346.34
  4250.9  344.78  4322.4  345.27  4428.5  345.31  4526.9  346.04  4605.0  346.56
  4752.8  345.89  4804.5  346.14  4841.0  344.92  4877.4  345.27  4925.6  344.90
  4935.4  344.40  4950.2  344.33  4970.5  342.89  4976.8  341.92  4977.4  341.12
  4983.8  341.12  4984.4  341.92  4990.8  341.98  5011.0  344.19  5021.2  344.57
  5051.6  344.61  5112.4  346.06  5293.3  351.42  5513.3  353.72  5635.0  353.20
#Mann=5,-1,0
  3882.9     0.1       0  4526.9    0.05       0  4925.6     0.1       0
  4976.8    0.07       0  4984.4     0.1       0
Bank Sta=4976.8,4984.4
Exp/Cntr=0.3,0.1

Type RM Length L Ch R = 1,60300,619,619,619
BEGIN DESCRIPTION:
Mapping XS 5ea9ac2e
END DESCRIPTION:
XS GIS Cut Line= 4
      2112173.00     13431160.44      2111700.75     13430584.01
      2110957.69     13430285.40      2110348.27     13430174.60
#Sta/Elev= 30
  3855.5  346.18  3921.8  346.06  4043.3  344.24  4185.4  344.20  4206.2  344.83
  4220.6  345.87  4227.1  347.02  4241.4  347.60  4263.3  347.21  4270.1  346.29
  4298.8  344.51  4424.9  345.36  4744.3  344.68  4865.5  343.38  4887.1  344.40
  4958.6  344.53  4973.3  344.30  5008.6  341.93  5009.2  341.13  5015.6  341.13
  5016.2  341.93  5041.9  344.56  5066.1  346.04  5221.2  349.89  5359.1  351.25
  5489.1  350.82  5542.5  351.36  5600.9  350.81  5831.1  353.07  6020.9  355.85
#Mann=6,-1,0
  3855.5    0.05       0  3921.8     0.1       0  4424.9    0.05       0
  4744.3     0.1       0  5008.6    0.07       0  5016.2     0.1       0
Bank Sta=5008.6,5016.2
Exp/Cntr=0.3,0.1