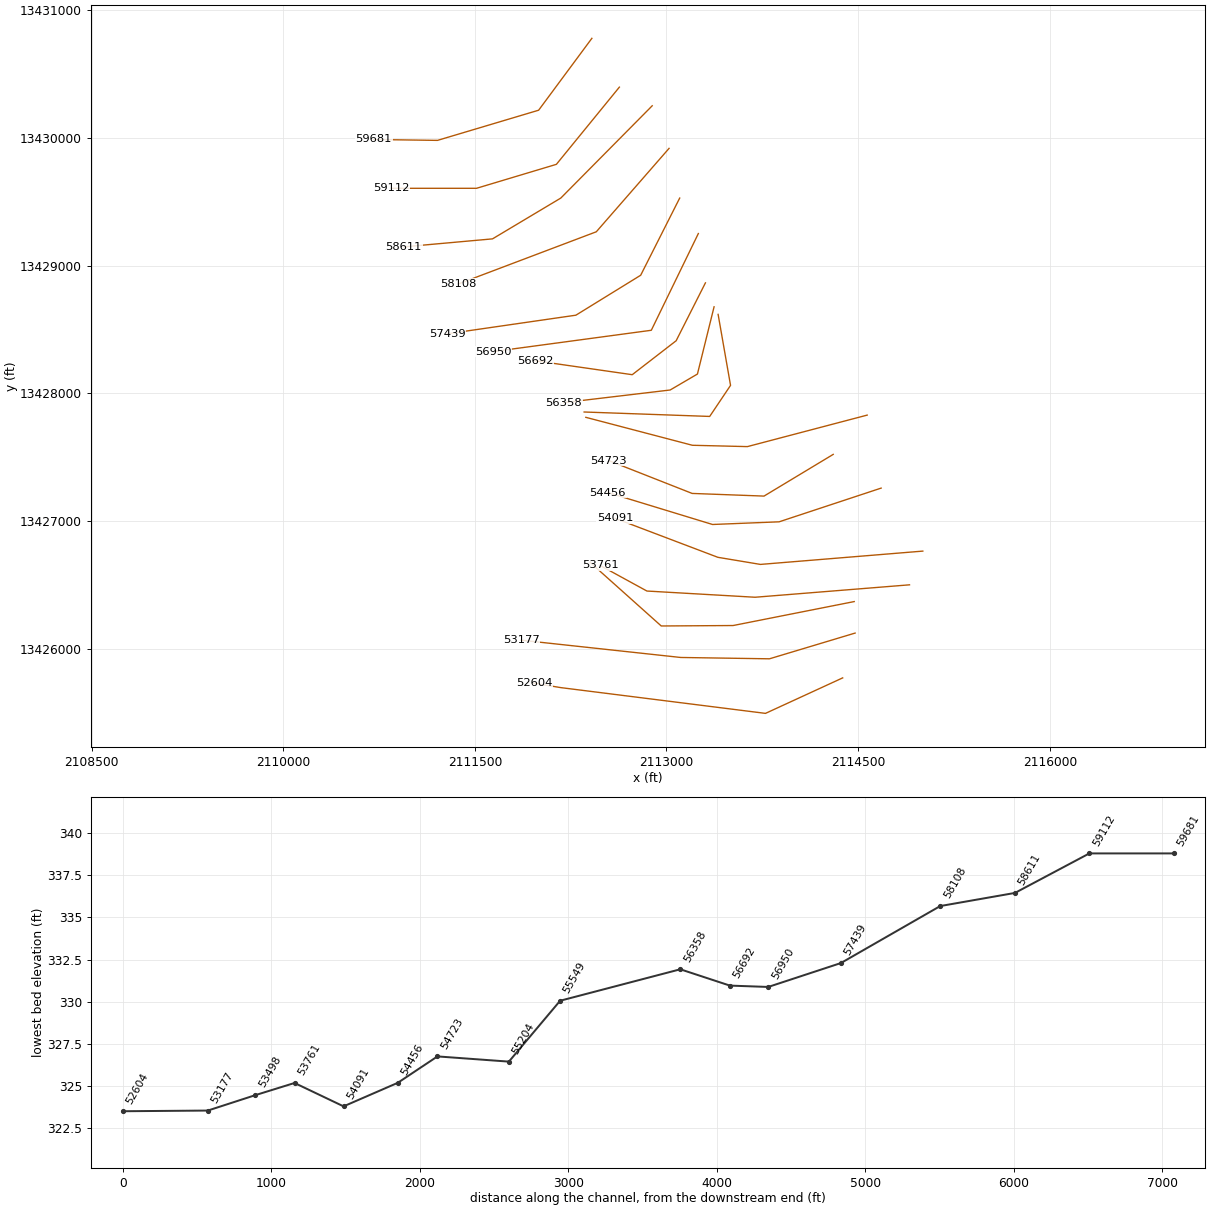
HEC-RAS study La Jarita Creek.prj: La Jarita Creek Base Level Engineering

--- La Jarita Creek.g01 (geometry) --- (continued)

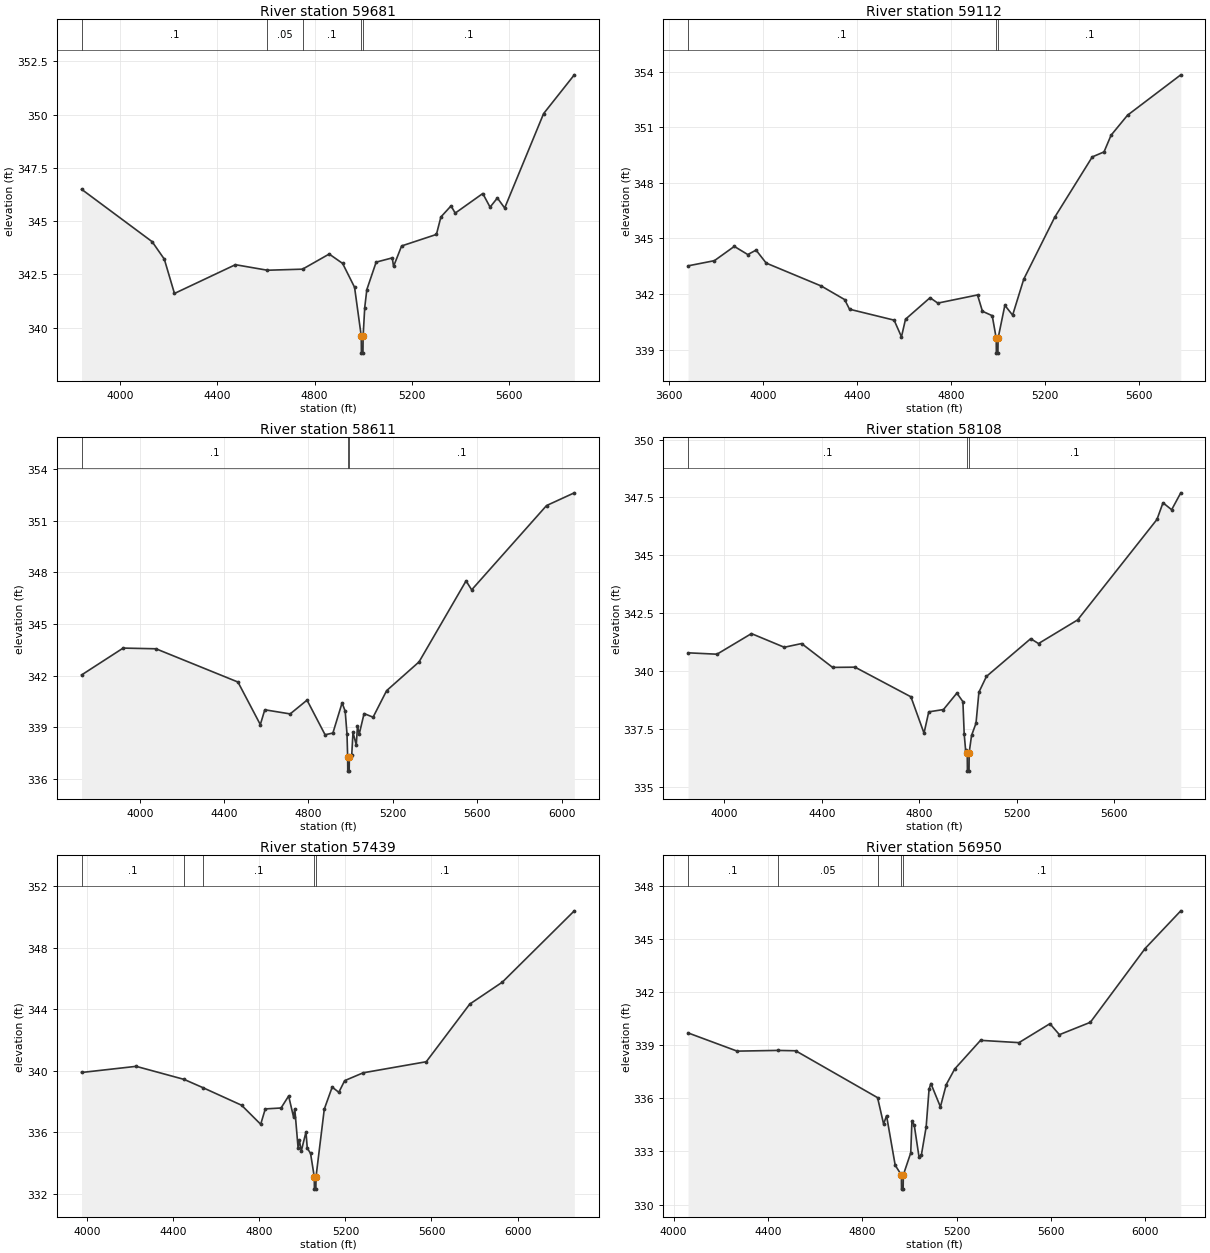
Type RM Length L Ch R = 1,59681,569,569,569
BEGIN DESCRIPTION:
Mapping XS 8a8b97d7
END DESCRIPTION:
XS GIS Cut Line= 4
      2112416.05     13430778.48      2111999.36     13430215.96
      2111207.69     13429979.84      2110708.82     13429986.77
#Sta/Elev= 30
  3842.3  346.50  4132.4  344.04  4182.4  343.22  4224.1  341.61  4474.6  342.96
  4605.9  342.70  4750.5  342.75  4860.0  343.46  4915.2  343.02  4964.3  341.90
  4991.8  339.61  4992.4  338.81  4998.8  338.81  4999.5  339.61  5006.1  340.95
  5014.7  341.79  5053.0  343.08  5119.3  343.28  5124.5  342.88  5157.7  343.84
  5300.7  344.38  5319.1  345.20  5360.8  345.72  5377.9  345.38  5491.2  346.30
  5521.2  345.66  5551.2  346.09  5581.2  345.62  5741.2  350.05  5867.4  351.87
#Mann=5,-1,0
  3842.3     0.1       0  4605.9    0.05       0  4750.5     0.1       0
  4991.8    0.07       0  4999.5     0.1       0
Bank Sta=4991.8,4999.5
Exp/Cntr=0.3,0.1

Type RM Length L Ch R = 1,59112,501,501,501
BEGIN DESCRIPTION:
Mapping XS 40e5565a
END DESCRIPTION:
XS GIS Cut Line= 4
      2112631.33     13430396.55      2112138.25     13429792.34
      2111513.25     13429604.84      2110848.33     13429604.84
#Sta/Elev= 30
  3679.9  343.52  3792.2  343.80  3876.9  344.57  3934.3  344.13  3969.5  344.37
  4012.6  343.67  4247.4  342.43  4346.5  341.70  4367.3  341.18  4557.1  340.59
  4588.4  339.69  4605.6  340.64  4710.0  341.80  4743.1  341.51  4912.1  341.95
  4933.0  341.07  4974.7  340.83  4991.7  339.61  4992.3  338.81  4998.9  338.81
  4999.6  339.61  5028.4  341.39  5061.5  340.86  5108.8  342.80  5240.5  346.14
  5400.5  349.40  5450.5  349.67  5480.5  350.57  5550.5  351.65  5777.2  353.83
#Mann=3,-1,0
  3679.9     0.1       0  4991.7    0.07       0  4999.6     0.1       0
Bank Sta=4991.7,4999.6
Exp/Cntr=0.3,0.1

Type RM Length L Ch R = 1,58611,503,503,503
BEGIN DESCRIPTION:
Mapping XS c346187f
END DESCRIPTION:
XS GIS Cut Line= 4
      2112888.22     13430250.65      2112172.97     13429528.46
      2111638.25     13429209.01      2110943.76     13429146.51
#Sta/Elev= 30
  3723.9  342.04  3921.1  343.60  4076.7  343.56  4465.5  341.63  4571.6  339.16
  4592.8  340.02  4713.1  339.78  4793.1  340.58  4878.7  338.57  4915.7  338.67
  4959.3  340.42  4974.0  339.94  4982.6  338.62  4985.7  337.26  4986.3  336.46
  4992.9  336.46  4993.6  337.26  5005.2  337.42  5011.0  338.71  5026.6  337.98
  5032.4  339.07  5040.8  338.62  5063.6  339.80  5106.3  339.59  5170.5  341.13
  5324.3  342.80  5547.2  347.50  5573.8  346.98  5928.7  351.87  6060.5  352.61
#Mann=3,-1,0
  3723.9     0.1       0  4985.7    0.07       0  4993.6     0.1       0
Bank Sta=4985.7,4993.6
Exp/Cntr=0.3,0.1

Type RM Length L Ch R = 1,58108,669,669,669
BEGIN DESCRIPTION:
Mapping XS 4e75dbfc
END DESCRIPTION:
XS GIS Cut Line= 3
      2113020.18     13429917.33      2112450.75     13429264.57
      2111368.68     13428855.32
#Sta/Elev= 30
  3851.0  340.79  3969.9  340.73  4111.4  341.62  4246.2  341.03  4317.4  341.19
  4444.6  340.16  4536.7  340.17  4766.1  338.89  4819.9  337.32  4839.4  338.24
  4899.8  338.34  4954.8  339.05  4979.6  338.68  4984.9  337.28  4990.7  336.59
  4997.4  336.48  4998.1  335.68  5004.7  335.68  5005.3  336.48  5015.1  337.22
  5033.4  337.75  5045.3  339.09  5076.2  339.77  5257.9  341.40  5290.0  341.19
  5450.4  342.21  5776.3  346.55  5801.1  347.27  5836.6  346.97  5874.1  347.70
#Mann=3,-1,0
  3851.0     0.1       0  4997.4    0.07       0  5005.3     0.1       0
Bank Sta=4997.4,5005.3
Exp/Cntr=0.3,0.1

Type RM Length L Ch R = 1,57439,489,489,489
BEGIN DESCRIPTION:
Mapping XS a21a7649
END DESCRIPTION:
XS GIS Cut Line= 4
      2113103.51     13429528.42      2112797.97     13428924.29
      2112291.03     13428611.79      2111284.06     13428465.95
#Sta/Elev= 30
  3973.9  339.88  4227.6  340.28  4450.6  339.43  4536.8  338.90  4717.6  337.75
  4806.4  336.51  4827.7  337.51  4901.0  337.57  4936.3  338.35  4959.0  336.99
  4964.8  337.52  4980.2  334.98  4986.1  335.46  4995.1  334.77  5016.9  336.01
  5022.8  334.96  5038.2  334.61  5055.4  333.09  5056.1  332.29  5062.9  332.29
  5063.5  333.09  5102.0  337.50  5138.7  338.93  5169.5  338.59  5196.7  339.35
  5282.8  339.86  5575.9  340.58  5777.9  344.33  5929.5  345.76  6263.9  350.40
#Mann=5,-1,0
  3973.9     0.1       0  4450.6    0.05       0  4536.8     0.1       0
  5055.4    0.07       0  5063.5     0.1       0
Bank Sta=5055.4,5063.5
Exp/Cntr=0.3,0.1

Type RM Length L Ch R = 1,56950,258,258,258
BEGIN DESCRIPTION:
Mapping XS 4e686f34
END DESCRIPTION:
XS GIS Cut Line= 3
      2113249.35     13429250.66      2112881.30     13428493.73
      2111645.15     13428327.06
#Sta/Elev= 30
  4060.8  339.70  4269.0  338.67  4440.4  338.71  4517.1  338.69  4864.4  336.04
  4889.9  334.55  4902.5  335.02  4939.1  332.22  4965.3  331.67  4966.0  330.87
  4972.8  330.87  4973.5  331.67  5005.0  332.92  5010.0  334.70  5019.8  334.49
  5040.0  332.70  5050.1  332.80  5070.3  334.38  5082.7  336.52  5090.4  336.84
  5130.8  335.52  5155.5  336.78  5191.4  337.66  5300.9  339.28  5463.8  339.15
  5595.0  340.22  5635.3  339.60  5766.5  340.30  5998.6  344.47  6149.8  346.60
#Mann=5,-1,0
  4060.8     0.1       0  4440.4    0.05       0  4864.4     0.1       0
  4965.3    0.07       0  4973.5     0.1       0
Bank Sta=4965.3,4973.5
Exp/Cntr=0.3,0.1

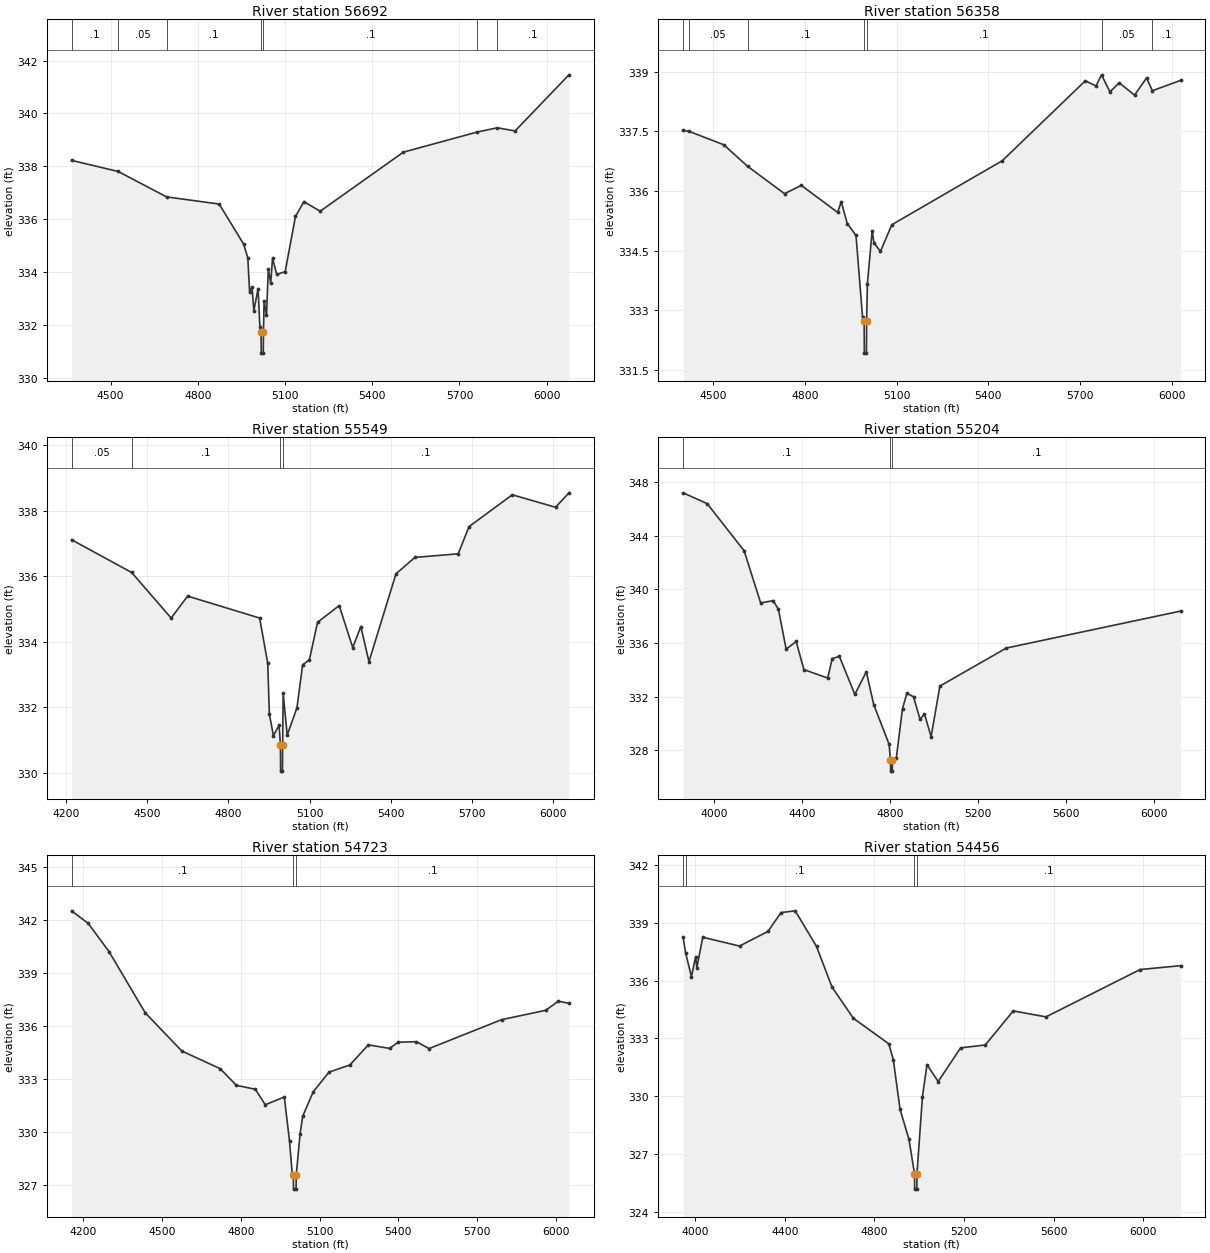
Type RM Length L Ch R = 1,56692,334,334,334
BEGIN DESCRIPTION:
Mapping XS 8bc4e5c7
END DESCRIPTION:
XS GIS Cut Line= 4
      2113304.84     13428864.85      2113075.66     13428411.69
      2112731.91     13428146.07      2111971.47     13428255.45
#Sta/Elev= 30
  4366.0  338.23  4526.4  337.81  4692.9  336.85  4873.8  336.58  4957.6  335.07
  4972.1  334.55  4978.4  333.25  4986.6  333.46  4992.9  332.55  5007.4  333.39
  5013.7  331.93  5017.8  331.75  5018.5  330.95  5025.3  330.95  5026.0  331.75
  5028.2  332.91  5036.4  332.38  5042.7  334.12  5050.9  333.59  5057.2  334.53
  5071.7  333.92  5100.7  334.03  5136.0  336.11  5165.0  336.67  5221.1  336.31
  5507.2  338.54  5761.0  339.30  5830.2  339.46  5891.1  339.34  6076.5  341.46
#Mann=7,-1,0
  4366.0     0.1       0  4526.4    0.05       0  4692.9     0.1       0
  5017.8    0.07       0  5026.0     0.1       0  5761.0    0.05       0
  5830.2     0.1       0
Bank Sta=5017.8,5026
Exp/Cntr=0.3,0.1

Type RM Length L Ch R = 1,56358,809,809,809
BEGIN DESCRIPTION:
Mapping XS bdb6bda3
END DESCRIPTION:
XS GIS Cut Line= 4
      2113372.53     13428677.30      2113242.33     13428151.28
      2113028.79     13428026.28      2112195.47     13427927.32
#Sta/Elev= 30
  4400.9  337.52  4419.9  337.50  4534.2  337.16  4611.8  336.62  4732.9  335.93
  4787.8  336.14  4906.9  335.46  4918.4  335.73  4938.3  335.18  4966.9  334.88
  4988.4  332.82  4993.5  332.72  4994.2  331.92  5001.0  331.92  5001.7  332.72
  5004.1  333.66  5019.8  335.00  5025.6  334.69  5047.0  334.48  5084.2  335.15
  5445.8  336.76  5717.7  338.77  5752.6  338.64  5770.7  338.92  5798.3  338.49
  5828.5  338.72  5878.8  338.41  5918.0  338.84  5937.3  338.52  6029.4  338.78
#Mann=7,-1,0
  4400.9     0.1       0  4419.9    0.05       0  4611.8     0.1       0
  4993.5    0.07       0  5001.7     0.1       0  5770.7    0.05       0
  5937.3     0.1       0
Bank Sta=4993.5,5001.7
Exp/Cntr=0.3,0.1

Type RM Length L Ch R = 1,55549,345,345,345
BEGIN DESCRIPTION:
Mapping XS 3f9a4f04
END DESCRIPTION:
XS GIS Cut Line= 4
      2113404.19     13428617.98      2113501.42     13428062.41
      2113338.22     13427819.36      2112355.61     13427854.08
#Sta/Elev= 30
  4219.6  337.11  4442.0  336.11  4588.1  334.72  4649.0  335.39  4915.4  334.72
  4945.4  333.34  4951.4  331.79  4966.4  331.13  4987.4  331.45  4992.3  330.85
  4993.0  330.05  4999.8  330.05  5000.5  330.85  5002.4  332.42  5017.4  331.15
  5053.4  331.98  5074.4  333.29  5099.6  333.45  5129.6  334.59  5209.7  335.10
  5259.7  333.82  5289.7  334.46  5319.8  333.39  5419.8  336.07  5489.9  336.57
  5650.0  336.68  5690.0  337.51  5850.1  338.48  6010.2  338.10  6059.6  338.54
#Mann=4,-1,0
  4219.6    0.05       0  4442.0     0.1       0  4992.3    0.07       0
  5000.5     0.1       0
Bank Sta=4992.3,5000.5
Exp/Cntr=0.3,0.1

Type RM Length L Ch R = 1,55204,481,481,481
BEGIN DESCRIPTION:
Mapping XS 4f14a5e1
END DESCRIPTION:
XS GIS Cut Line= 4
      2114570.88     13427829.78      2113633.36     13427583.24
      2113202.81     13427593.66      2112368.67     13427812.38
#Sta/Elev= 30
  3858.0  347.21  3967.5  346.40  4135.2  342.89  4210.7  338.99  4267.3  339.16
  4291.4  338.52  4326.6  335.54  4372.1  336.11  4407.3  334.01  4515.5  333.38
  4536.2  334.83  4568.6  335.00  4639.0  332.16  4691.3  333.85  4724.8  331.40
  4794.7  328.44  4801.1  327.23  4801.9  326.43  4809.1  326.43  4810.0  327.23
  4827.4  327.38  4855.8  331.10  4875.8  332.24  4905.8  331.98  4935.8  330.29
  4955.8  330.70  4985.8  329.00  5025.8  332.78  5328.2  335.62  6120.4  338.38
#Mann=3,-1,0
  3858.0     0.1       0  4801.1    0.07       0  4810.0     0.1       0
Bank Sta=4801.1,4810
Exp/Cntr=0.3,0.1

Type RM Length L Ch R = 1,54723,267,267,267
BEGIN DESCRIPTION:
Mapping XS c6772918
END DESCRIPTION:
XS GIS Cut Line= 4
      2114305.02     13427522.36      2113763.38     13427195.98
      2113200.88     13427216.82      2112549.02     13427473.40
#Sta/Elev= 30
  4154.9  342.54  4218.4  341.83  4298.0  340.22  4435.8  336.75  4575.2  334.58
  4721.3  333.58  4783.4  332.63  4855.7  332.41  4893.3  331.53  4965.8  331.97
  4985.8  329.45  4995.8  327.64  5000.3  327.54  5001.0  326.74  5010.6  326.74
  5011.3  327.54  5025.8  329.86  5035.8  330.87  5075.9  332.26  5135.9  333.38
  5215.9  333.79  5286.0  334.93  5367.2  334.73  5399.5  335.08  5468.7  335.11
  5517.5  334.72  5793.7  336.36  5961.6  336.89  6010.4  337.41  6050.7  337.29
#Mann=3,-1,0
  4154.9     0.1       0  5000.3    0.07       0  5011.3     0.1       0
Bank Sta=5000.3,5011.3
Exp/Cntr=0.3,0.1

Type RM Length L Ch R = 1,54456,365,365,365
BEGIN DESCRIPTION:
Mapping XS b78179f9
END DESCRIPTION:
XS GIS Cut Line= 4
      2114680.09     13427258.50      2113881.43     13426994.59
      2113360.60     13426973.76      2112541.16     13427223.76
#Sta/Elev= 30
  3946.5  338.26  3957.5  337.45  3983.5  336.21  4002.4  337.25  4007.6  336.67
  4034.1  338.26  4198.0  337.80  4325.0  338.56  4383.2  339.54  4446.6  339.63
  4541.6  337.78  4610.6  335.67  4705.8  334.05  4864.1  332.72  4884.1  331.90
  4914.2  329.32  4954.2  327.75  4978.7  325.97  4979.4  325.17  4989.0  325.17
  4989.7  325.97  5014.2  329.98  5034.3  331.64  5084.3  330.76  5184.4  332.51
  5294.5  332.66  5419.3  334.43  5565.3  334.12  5985.2  336.58  6165.6  336.78
#Mann=4,-1,0
  3946.5    0.12       0  3957.5     0.1       0  4978.7    0.07       0
  4989.7     0.1       0
Bank Sta=4978.7,4989.7
Exp/Cntr=0.3,0.1

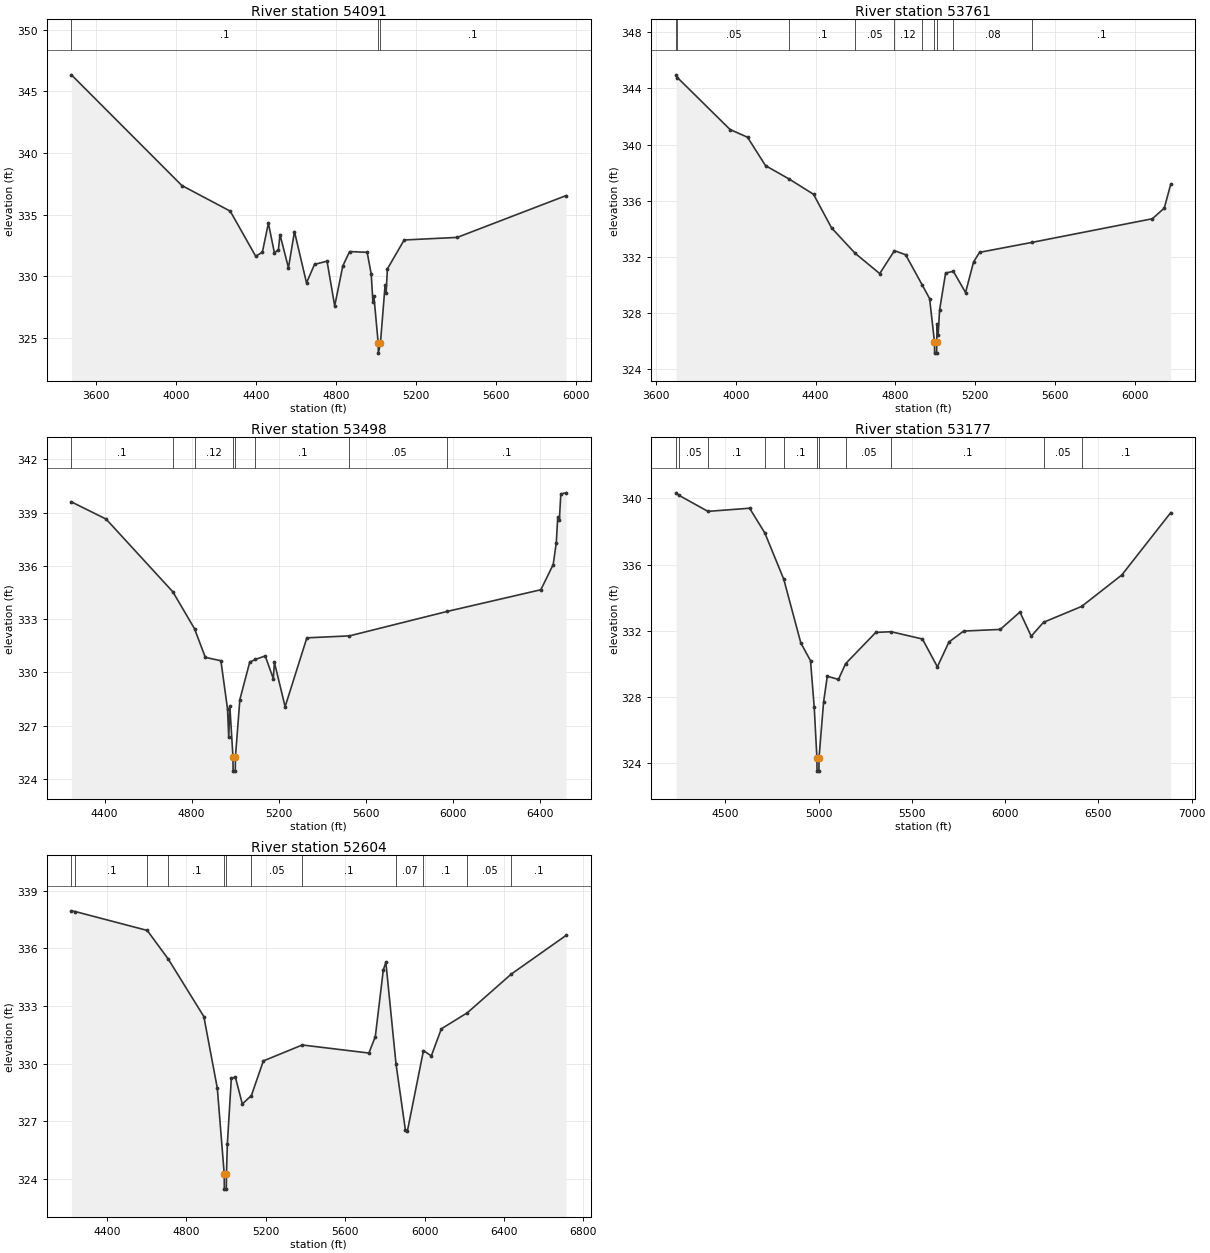
Type RM Length L Ch R = 1,54091,330,330,330
BEGIN DESCRIPTION:
Mapping XS ae50dbe8
END DESCRIPTION:
XS GIS Cut Line= 4
      2115006.46     13426765.43      2113735.60     13426661.26
      2113402.27     13426716.82      2112598.31     13427021.77
#Sta/Elev= 30
  3476.7  346.35  4028.9  337.37  4270.8  335.29  4398.1  331.63  4431.4  331.96
  4461.5  334.31  4491.6  331.91  4511.6  332.15  4519.5  333.39  4561.8  330.69
  4591.9  333.63  4652.1  329.47  4692.2  330.97  4754.7  331.23  4793.0  327.60
  4833.5  330.84  4867.4  332.01  4955.2  331.95  4975.5  330.20  4984.0  327.93
  4989.1  328.38  5010.5  324.57  5011.2  323.77  5021.6  324.57  5044.8  329.26
  5049.9  328.64  5056.6  330.61  5140.3  332.95  5405.6  333.16  5949.6  336.55
#Mann=3,-1,0
  3476.7     0.1       0  5010.5    0.07       0  5021.6     0.1       0
Bank Sta=5010.5,5021.6
Exp/Cntr=0.3,0.1

Type RM Length L Ch R = 1,53761,263,263,263
BEGIN DESCRIPTION:
Mapping XS 811cdbd6
END DESCRIPTION:
XS GIS Cut Line= 4
      2114902.23     13426501.54      2113693.93     13426404.32
      2112846.71     13426452.93      2112479.33     13426653.95
#Sta/Elev= 30
  3700.7  344.96  3708.1  344.76  3971.5  341.07  4059.1  340.52  4149.4  338.50
  4268.7  337.54  4390.1  336.46  4480.4  334.07  4598.8  332.26  4721.8  330.82
  4795.5  332.45  4851.6  332.16  4934.1  330.03  4971.9  329.04  4996.3  325.96
  4997.0  325.16  5007.0  325.16  5007.6  325.96  5009.6  327.23  5014.6  326.46
  5022.0  328.23  5052.1  330.86  5091.0  330.98  5152.2  329.47  5192.3  331.65
  5222.3  332.33  5485.5  333.04  6088.5  334.72  6148.3  335.48  6180.3  337.16
#Mann=10,-1,0
  3700.7     0.1       0  3708.1    0.05       0  4268.7     0.1       0
  4598.8    0.05       0  4795.5    0.12       0  4934.1     0.1       0
  4996.3    0.07       0  5007.6     0.1       0  5091.0    0.08       0
  5485.5     0.1       0
Bank Sta=4996.3,5007.6
Exp/Cntr=0.3,0.1

Type RM Length L Ch R = 1,53498,321,321,321
BEGIN DESCRIPTION:
Mapping XS d0228bec
END DESCRIPTION:
XS GIS Cut Line= 4
      2114469.39     13426370.46      2113521.48     13426182.96
      2112958.98     13426179.49      2112402.91     13426676.66
#Sta/Elev= 30
  4247.1  339.61  4406.8  338.64  4713.8  334.54  4813.4  332.46  4863.0  330.85
  4934.6  330.66  4965.1  327.94  4970.6  326.34  4975.7  328.10  4990.1  325.24
  4990.7  324.44  5000.7  324.44  5001.4  325.24  5021.8  328.47  5067.1  330.58
  5092.3  330.73  5138.4  330.93  5175.6  329.65  5180.7  330.57  5229.9  328.07
  5329.9  331.95  5525.6  332.06  5976.0  333.44  6405.9  334.66  6462.7  336.08
  6476.9  337.31  6483.6  338.75  6491.1  338.61  6497.8  340.06  6521.8  340.12
#Mann=8,-1,0
  4247.1     0.1       0  4713.8    0.08       0  4813.4    0.12       0
  4990.1    0.07       0  5001.4    0.12       0  5092.3     0.1       0
  5525.6    0.05       0  5976.0     0.1       0
Bank Sta=4990.1,5001.4
Exp/Cntr=0.3,0.1

Type RM Length L Ch R = 1,53177,573,573,573
BEGIN DESCRIPTION:
Mapping XS 1e10e0bd
END DESCRIPTION:
XS GIS Cut Line= 4
      2114476.31     13426123.93      2113806.20     13425922.55
      2113111.76     13425932.96      2111861.71     13426068.38
#Sta/Elev= 30
  4235.9  340.33  4251.7  340.18  4406.8  339.21  4630.3  339.40  4711.8  337.91
  4813.5  335.11  4905.0  331.26  4956.8  330.19  4976.8  327.38  4991.2  324.32
  4991.8  323.52  5001.8  323.52  5002.5  324.32  5026.8  327.68  5046.8  329.25
  5106.8  329.06  5144.8  330.01  5306.9  331.90  5389.1  331.94  5556.9  331.50
  5636.9  329.82  5698.9  331.32  5777.8  331.98  5974.0  332.08  6079.5  333.13
  6139.9  331.67  6205.9  332.51  6410.5  333.47  6625.8  335.37  6887.5  339.13
#Mann=11,-1,0
  4235.9     0.1       0  4251.7    0.05       0  4406.8     0.1       0
  4711.8    0.08       0  4813.5     0.1       0  4991.2    0.07       0
  5002.5     0.1       0  5144.8    0.05       0  5389.1     0.1       0
  6205.9    0.05       0  6410.5     0.1       0
Bank Sta=4991.2,5002.5
Exp/Cntr=0.3,0.1

Type RM Length L Ch R = 1,52604,323,323,323
BEGIN DESCRIPTION:
Mapping XS c3d47246
END DESCRIPTION:
XS GIS Cut Line= 4
      2114379.10     13425773.23      2113774.95     13425495.46
      2112174.26     13425696.85      2111962.44     13425731.57
#Sta/Elev= 30
  4220.0  337.96  4240.2  337.92  4602.1  336.94  4708.8  335.44  4887.4  332.46
  4955.4  328.73  4990.1  324.28  4990.8  323.48  5000.8  323.48  5001.5  324.28
  5006.1  325.85  5026.0  329.24  5046.2  329.31  5081.5  327.91  5127.2  328.35
  5187.3  330.15  5383.4  330.98  5719.4  330.56  5751.7  331.42  5792.0  334.89
  5804.8  335.28  5856.1  329.98  5902.9  326.58  5912.9  326.48  5994.3  330.69
  6033.9  330.41  6084.3  331.82  6215.9  332.66  6437.0  334.67  6712.9  336.68
#Mann=12,-1,0
  4220.0    0.05       0  4240.2     0.1       0  4602.1    0.05       0
  4708.8     0.1       0  4990.1    0.07       0  5001.5     0.1       0
  5127.2    0.05       0  5383.4     0.1       0  5856.1    0.07       0
  5994.3     0.1       0  6215.9    0.05       0  6437.0     0.1       0
Bank Sta=4990.1,5001.5
Exp/Cntr=0.3,0.1