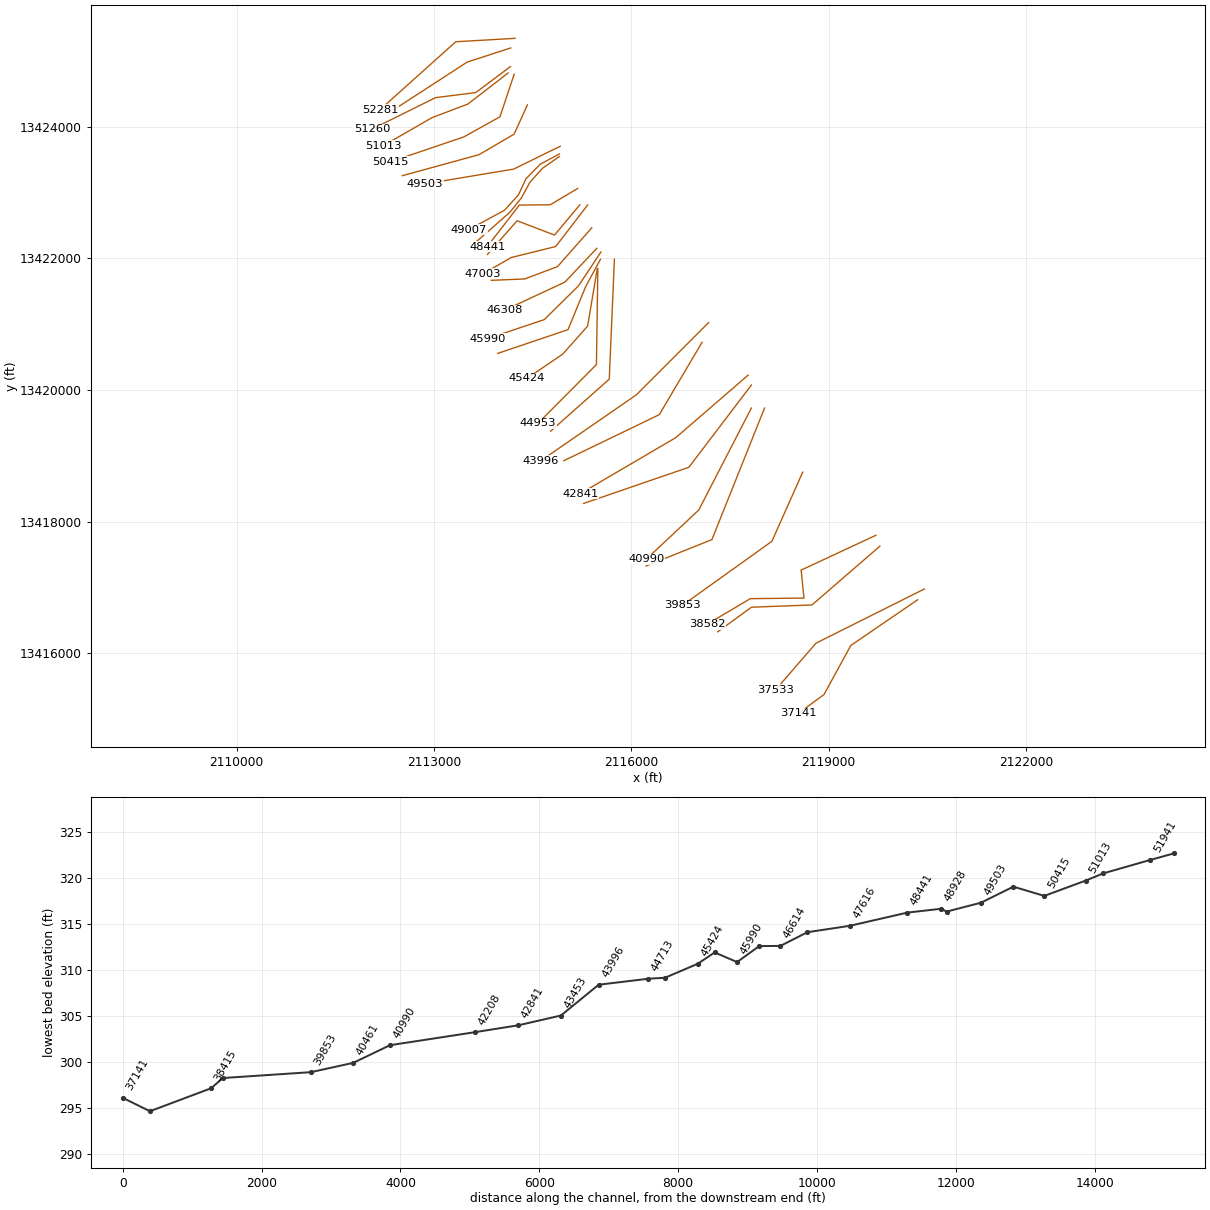
HEC-RAS study La Jarita Creek.prj: La Jarita Creek Base Level Engineering

--- La Jarita Creek.g01 (geometry) --- (continued)

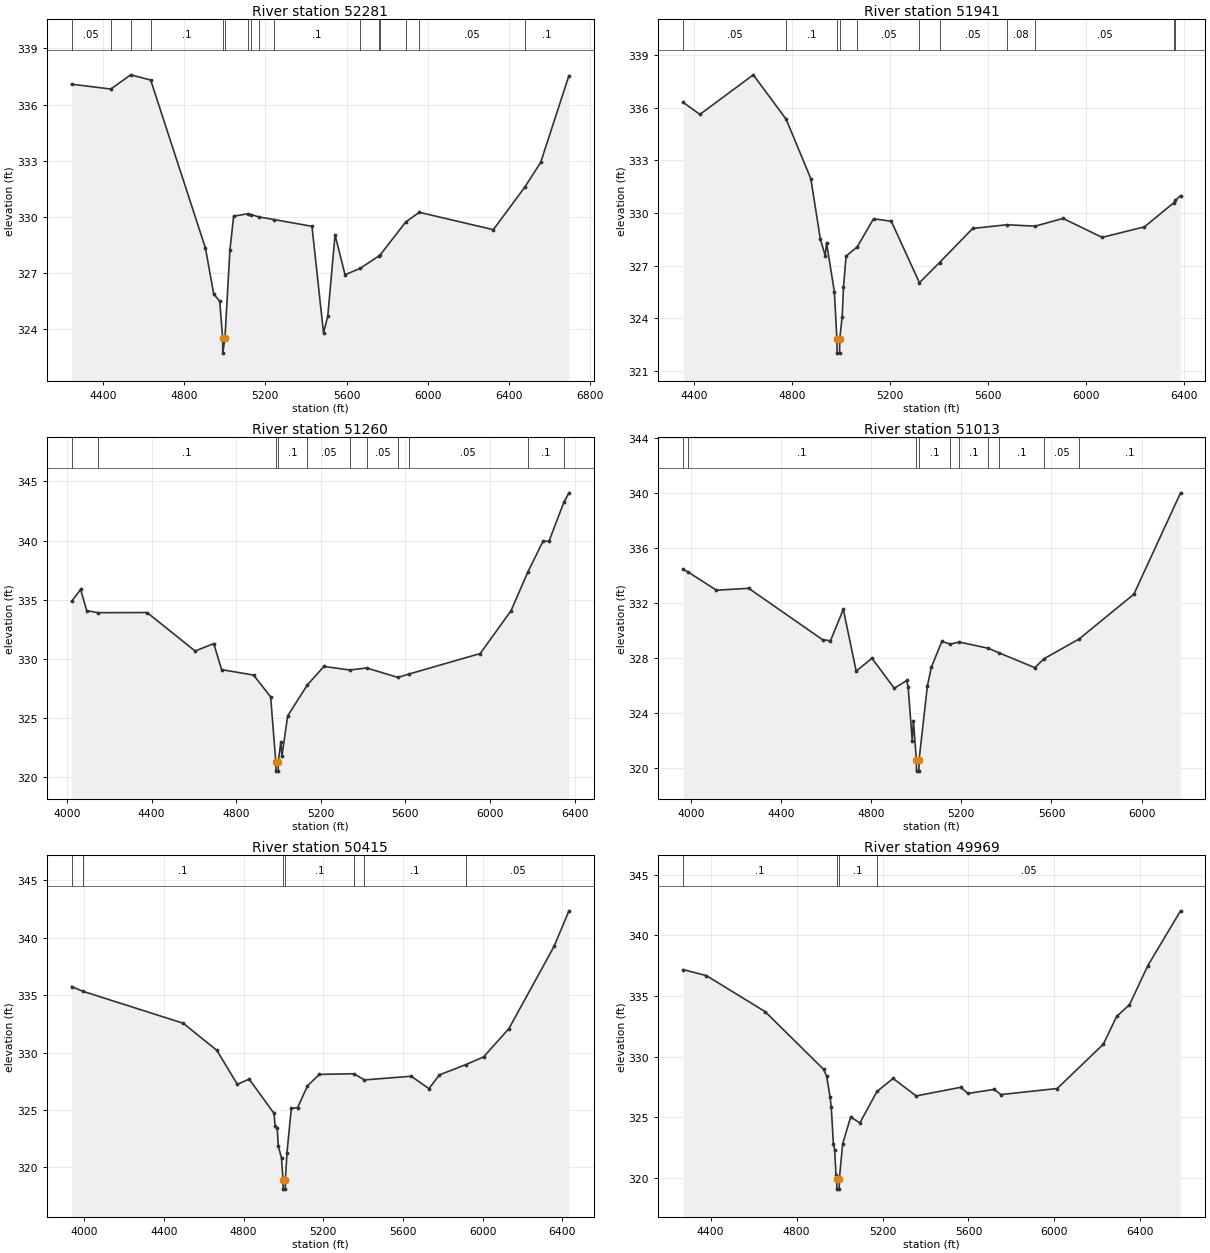
Type RM Length L Ch R = 1,52281,340,340,340
BEGIN DESCRIPTION:
Mapping XS e335065f
END DESCRIPTION:
XS GIS Cut Line= 3
      2114233.25     13425346.15      2113330.51     13425294.07
      2112181.19     13424262.81
#Sta/Elev= 30
  4246.3  337.09  4439.4  336.83  4537.7  337.59  4635.9  337.31  4905.6  328.32
  4945.7  325.89  4975.8  325.48  4990.1  323.51  4990.7  322.71  5001.5  323.51
  5025.8  328.21  5044.3  330.03  5112.5  330.16  5127.9  330.12  5170.4  329.99
  5244.4  329.85  5429.8  329.49  5486.6  323.79  5507.5  324.68  5543.4  329.03
  5592.7  326.90  5666.6  327.24  5761.3  327.92  5765.5  327.96  5891.2  329.72
  5958.0  330.24  6322.3  329.31  6477.7  331.59  6555.6  332.91  6694.7  337.55
#Mann=16,-1,0
  4246.3    0.05       0  4439.4     0.1       0  4537.7    0.05       0
  4635.9     0.1       0  4990.1    0.07       0  5001.5     0.1       0
  5112.5    0.05       0  5127.9     0.1       0  5170.4    0.05       0
  5244.4     0.1       0  5666.6    0.05       0  5761.3     0.1       0
  5765.5    0.08       0  5891.2     0.1       0  5958.0    0.05       0
  6477.7     0.1       0
Bank Sta=4990.1,5001.5
Exp/Cntr=0.3,0.1

Type RM Length L Ch R = 1,51941,681,681,681
BEGIN DESCRIPTION:
Mapping XS 6cd8db94
END DESCRIPTION:
XS GIS Cut Line= 3
      2114167.28     13425200.31      2113504.12     13424985.05
      2112386.60     13424259.70
#Sta/Elev= 30
  4355.3  336.32  4423.6  335.63  4641.6  337.89  4775.8  335.35  4876.3  331.96
  4914.9  328.53  4935.0  327.56  4940.3  328.31  4972.2  325.51  4982.8  322.80
  4983.5  322.00  4993.6  322.00  4994.2  322.80  5004.2  324.08  5009.5  325.76
  5020.1  327.54  5065.8  328.07  5132.1  329.67  5204.6  329.53  5319.4  326.02
  5401.3  327.17  5536.8  329.12  5676.7  329.33  5791.6  329.25  5905.3  329.69
  6064.8  328.61  6237.5  329.21  6356.7  330.58  6364.0  330.73  6384.8  330.99
#Mann=11,-1,0
  4355.3    0.05       0  4775.8     0.1       0  4982.8    0.07       0
  4994.2     0.1       0  5065.8    0.05       0  5319.4     0.1       0
  5401.3    0.05       0  5676.7    0.08       0  5791.6    0.05       0
  6356.7     0.1       0  6364.0    0.05       0
Bank Sta=4982.8,4994.2
Exp/Cntr=0.3,0.1

Type RM Length L Ch R = 1,51260,247,247,247
BEGIN DESCRIPTION:
Mapping XS 602736ff
END DESCRIPTION:
XS GIS Cut Line= 4
      2114162.49     13424917.15      2113634.74     13424521.33
      2113023.63     13424444.94      2112059.18     13423966.19
#Sta/Elev= 30
  4021.1  334.86  4064.0  335.87  4093.0  334.08  4147.2  333.91  4378.6  333.92
  4605.7  330.67  4693.6  331.30  4730.9  329.10  4882.1  328.64  4962.7  326.80
  4987.0  321.33  4987.6  320.53  4998.2  320.53  4998.8  321.33  5011.0  323.01
  5016.1  321.81  5043.3  325.20  5136.4  327.81  5214.7  329.37  5337.3  329.07
  5417.0  329.24  5564.8  328.44  5615.4  328.72  5953.8  330.46  6099.7  334.08
  6179.2  337.35  6251.0  339.95  6279.0  339.94  6349.1  343.22  6373.4  344.03
#Mann=11,-1,0
  4021.1    0.05       0  4147.2     0.1       0  4987.0    0.07       0
  4998.8     0.1       0  5136.4    0.05       0  5337.3    0.08       0
  5417.0    0.05       0  5564.8     0.1       0  5615.4    0.05       0
  6179.2     0.1       0  6349.1    0.05       0
Bank Sta=4987,4998.8
Exp/Cntr=0.3,0.1

Type RM Length L Ch R = 1,51013,598,598,598
BEGIN DESCRIPTION:
Mapping XS e367b0b7
END DESCRIPTION:
XS GIS Cut Line= 4
      2114127.78     13424819.93      2113516.68     13424347.72
      2112968.07     13424139.39      2112231.98     13423715.78
#Sta/Elev= 30
  3964.7  334.46  3986.2  334.26  4112.7  332.93  4255.8  333.07  4583.6  329.33
  4618.9  329.25  4675.9  331.54  4733.0  327.04  4803.0  327.98  4902.1  325.79
  4957.0  326.36  4963.4  325.92  4981.8  321.98  4987.1  323.41  5000.3  320.56
  5000.9  319.76  5011.5  319.76  5012.1  320.56  5049.0  325.95  5066.8  327.33
  5113.2  329.20  5151.1  329.01  5190.4  329.16  5320.2  328.70  5367.4  328.37
  5526.2  327.29  5566.7  327.94  5722.7  329.38  5965.9  332.64  6173.1  340.02
#Mann=10,-1,0
  3964.7    0.05       0  3986.2     0.1       0  5000.3    0.07       0
  5012.1     0.1       0  5151.1    0.05       0  5190.4     0.1       0
  5320.2    0.05       0  5367.4     0.1       0  5566.7    0.05       0
  5722.7     0.1       0
Bank Sta=5000.3,5012.1
Exp/Cntr=0.3,0.1

Type RM Length L Ch R = 1,50415,446,446,446
BEGIN DESCRIPTION:
Mapping XS 310c3995
END DESCRIPTION:
XS GIS Cut Line= 4
      2114218.07     13424799.11      2114002.80     13424153.27
      2113454.18     13423847.72      2112329.56     13423465.90
#Sta/Elev= 30
  3936.4  335.75  3994.5  335.33  4496.8  332.55  4665.6  330.19  4768.5  327.23
  4827.9  327.68  4952.5  324.70  4958.2  323.60  4968.5  323.41  4974.2  321.83
  4990.2  320.80  4997.9  318.89  4998.5  318.09  5009.2  318.09  5009.7  318.89
  5017.7  321.27  5039.4  325.12  5071.4  325.20  5120.6  327.10  5180.0  328.09
  5353.3  328.15  5406.5  327.61  5641.4  327.93  5730.1  326.85  5782.9  328.05
  5916.2  328.95  6004.6  329.62  6131.4  332.08  6358.1  339.25  6432.8  342.35
#Mann=7,-1,0
  3936.4    0.05       0  3994.5     0.1       0  4997.9    0.07       0
  5009.7     0.1       0  5353.3    0.05       0  5406.5     0.1       0
  5916.2    0.05       0
Bank Sta=4997.9,5009.7
Exp/Cntr=0.3,0.1

Type RM Length L Ch R = 1,49969,466,466,466
BEGIN DESCRIPTION:
Mapping XS 1b2b4fc3
END DESCRIPTION:
XS GIS Cut Line= 4
      2114419.45     13424333.81      2114218.07     13423889.39
      2113683.35     13423576.89      2112518.30     13423257.88
#Sta/Elev= 30
  4272.0  337.18  4380.5  336.68  4653.9  333.71  4925.6  328.96  4940.0  328.40
  4955.7  326.70  4961.5  325.84  4971.4  322.79  4977.2  322.35  4983.6  320.22
  4987.0  319.89  4987.6  319.09  4998.3  319.09  4998.8  319.89  5014.4  322.81
  5051.6  325.03  5094.6  324.55  5174.3  327.14  5249.2  328.21  5356.6  326.77
  5564.2  327.48  5597.6  326.97  5719.7  327.31  5751.1  326.88  6013.2  327.38
  6227.7  331.03  6289.9  333.32  6349.5  334.28  6435.1  337.51  6587.2  342.02
#Mann=4,-1,0
  4272.0     0.1       0  4987.0    0.07       0  4998.8     0.1       0
  5174.3    0.05       0
Bank Sta=4987,4998.8
Exp/Cntr=0.3,0.1

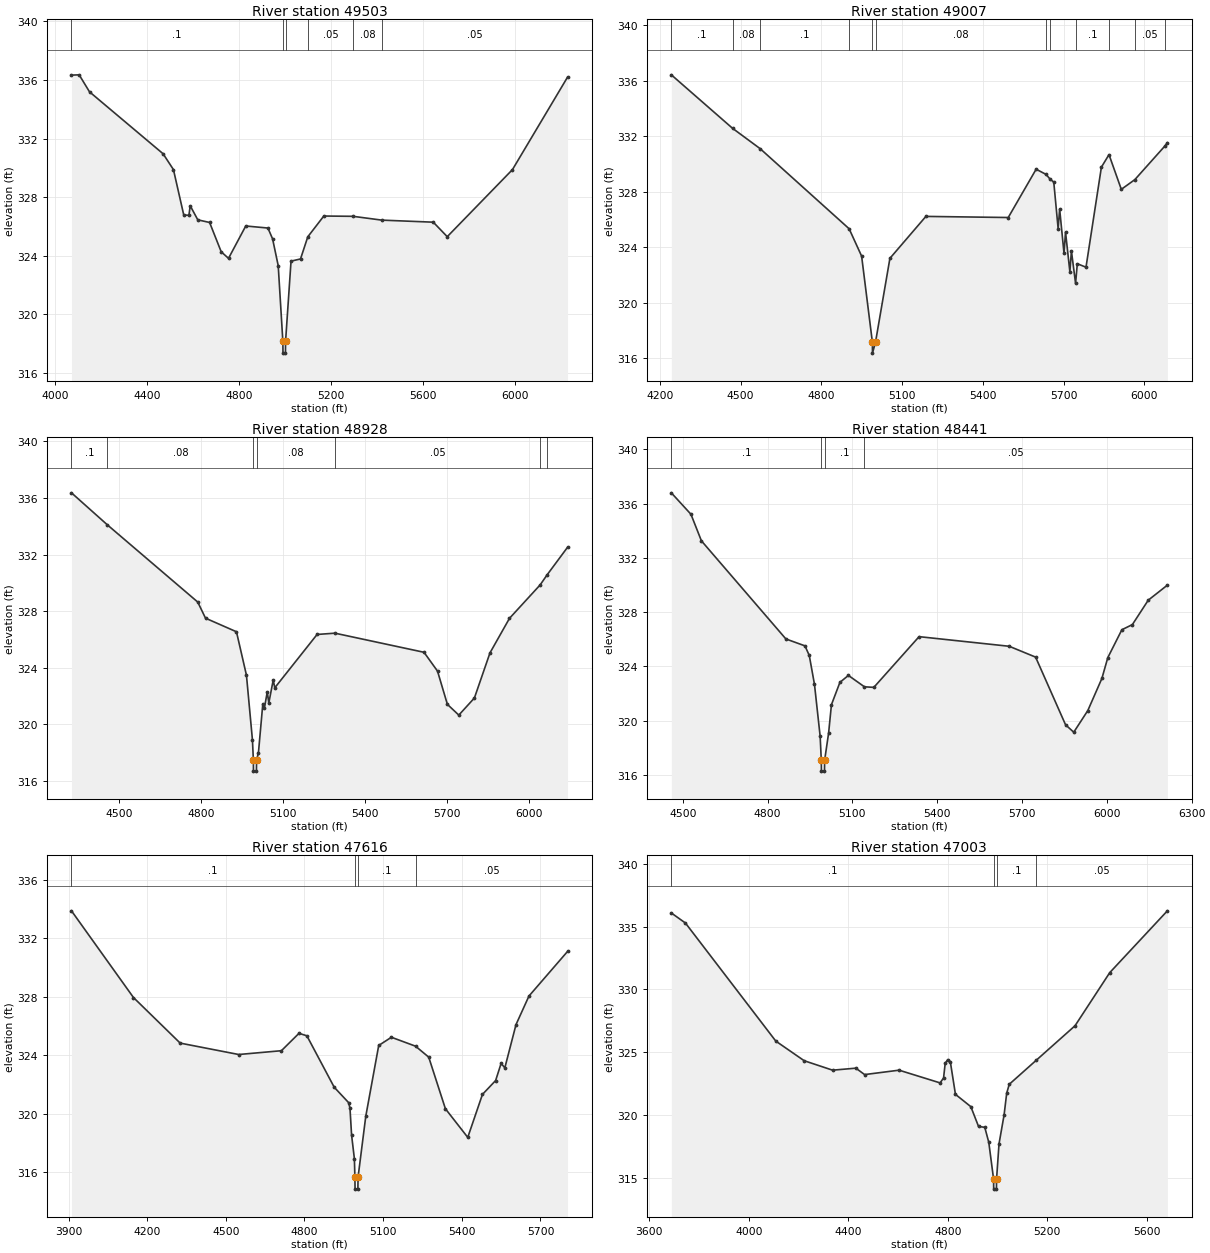
Type RM Length L Ch R = 1,49503,496,496,496
BEGIN DESCRIPTION:
Mapping XS 74c319bb
END DESCRIPTION:
XS GIS Cut Line= 3
      2114918.65     13423705.48      2114211.23     13423358.27
      2112858.52     13423132.82
#Sta/Elev= 30
  4069.6  336.33  4103.1  336.35  4148.1  335.19  4468.5  330.96  4513.5  329.88
  4558.4  326.78  4580.9  326.76  4586.5  327.41  4619.5  326.45  4670.9  326.27
  4721.4  324.27  4753.2  323.82  4828.3  326.03  4924.8  325.89  4945.1  325.15
  4969.6  323.32  4989.8  318.15  4990.4  317.35  5001.1  317.35  5001.6  318.15
  5025.4  323.63  5066.7  323.78  5098.3  325.29  5168.1  326.71  5295.3  326.69
  5420.6  326.43  5644.6  326.29  5705.4  325.30  5989.3  329.88  6229.0  336.19
#Mann=6,-1,0
  4069.6     0.1       0  4989.8    0.07       0  5001.6     0.1       0
  5098.3    0.05       0  5295.3    0.08       0  5420.6    0.05       0
Bank Sta=4989.8,5001.6
Exp/Cntr=0.3,0.1

Type RM Length L Ch R = 1,49007,79,79,79
BEGIN DESCRIPTION:
Mapping XS fb1f65ed
END DESCRIPTION:
XS GIS Cut Line= 6
      2114905.71     13423588.33      2114614.87     13423432.06
      2114397.86     13423210.70      2114285.01     13422967.65
      2114072.34     13422733.27      2113529.82     13422438.15
#Sta/Elev= 30
  4242.8  336.43  4470.0  332.58  4572.7  331.11  4903.1  325.34  4949.5  323.37
  4989.4  317.18  4989.9  316.38  5001.2  317.18  5054.6  323.21  5188.2  326.23
  5494.0  326.15  5597.6  329.63  5634.1  329.26  5649.3  328.92  5663.1  328.70
  5679.3  325.35  5684.9  326.76  5701.1  323.57  5706.8  325.09  5722.9  322.24
  5728.6  323.74  5744.1  321.40  5750.5  322.82  5782.8  322.57  5840.0  329.78
  5868.2  330.68  5913.9  328.18  5964.2  328.88  6074.3  331.27  6085.0  331.54
#Mann=12,-1,0
  4242.8     0.1       0  4470.0    0.08       0  4572.7     0.1       0
  4903.1    0.08       0  4989.4    0.07       0  5001.2    0.08       0
  5634.1    0.07       0  5649.3    0.08       0  5744.1     0.1       0
  5868.2    0.08       0  5964.2    0.05       0  6074.3     0.1       0
Bank Sta=4989.4,5001.2
Exp/Cntr=0.3,0.1

Type RM Length L Ch R = 1,48928,487,487,487
BEGIN DESCRIPTION:
Mapping XS 132c0db5
END DESCRIPTION:
XS GIS Cut Line= 6
      2114905.69     13423549.26      2114649.60     13423371.29
      2114458.62     13423158.62      2114328.41     13422919.91
      2114150.46     13422698.55      2113655.67     13422264.52
#Sta/Elev= 30
  4327.2  336.36  4458.7  334.09  4788.4  328.64  4816.8  327.50  4929.8  326.54
  4966.3  323.47  4988.2  318.89  4991.5  317.49  4992.0  316.69  5002.7  316.69
  5003.3  317.49  5010.0  317.97  5026.1  321.45  5031.8  321.14  5042.3  322.29
  5048.0  321.51  5064.1  323.13  5069.8  322.58  5224.3  326.35  5289.5  326.44
  5614.8  325.09  5664.1  323.76  5700.2  321.41  5741.9  320.65  5798.9  321.86
  5855.8  325.05  5927.0  327.49  6038.9  329.85  6064.3  330.56  6139.0  332.51
#Mann=7,-1,0
  4327.2     0.1       0  4458.7    0.08       0  4991.5    0.07       0
  5003.3    0.08       0  5289.5    0.05       0  6038.9    0.08       0
  6064.3    0.05       0
Bank Sta=4991.5,5003.3
Exp/Cntr=0.3,0.1

Type RM Length L Ch R = 1,48441,825,825,825
BEGIN DESCRIPTION:
Mapping XS 1c067a7a
END DESCRIPTION:
XS GIS Cut Line= 4
      2115183.48     13423063.15      2114766.78     13422815.74
      2114298.03     13422811.40      2113807.58     13422177.71
#Sta/Elev= 30
  4459.4  336.80  4528.8  335.22  4565.8  333.26  4864.7  326.02  4932.2  325.51
  4947.4  324.80  4965.8  322.67  4985.8  318.85  4989.9  317.07  4990.4  316.27
  5001.2  316.27  5001.7  317.07  5015.8  319.08  5025.8  321.17  5055.8  322.82
  5085.8  323.33  5142.5  322.49  5175.8  322.45  5335.8  326.19  5654.7  325.48
  5748.0  324.68  5853.9  319.69  5882.9  319.14  5932.7  320.74  5982.5  323.11
  6003.3  324.64  6053.1  326.70  6090.3  327.08  6146.4  328.88  6214.1  329.99
#Mann=4,-1,0
  4459.4     0.1       0  4989.9    0.07       0  5001.7     0.1       0
  5142.5    0.05       0
Bank Sta=4989.9,5001.7
Exp/Cntr=0.3,0.1

Type RM Length L Ch R = 1,47616,613,613,613
BEGIN DESCRIPTION:
Mapping XS 7d0532e4
END DESCRIPTION:
XS GIS Cut Line= 4
      2115218.14     13422815.70      2114831.89     13422355.67
      2114263.31     13422572.68      2113811.95     13422060.57
#Sta/Elev= 30
  3911.3  333.88  4147.7  327.95  4325.9  324.83  4549.1  324.05  4712.0  324.31
  4779.1  325.50  4809.1  325.33  4913.4  321.81  4968.2  320.76  4973.5  320.38
  4979.6  318.54  4990.3  316.92  4992.3  315.64  4992.9  314.84  5003.7  314.84
  5004.2  315.64  5033.7  319.82  5083.1  324.67  5131.5  325.23  5223.5  324.62
  5273.8  323.87  5337.4  320.34  5422.7  318.38  5478.7  321.32  5529.0  322.27
  5549.9  323.44  5564.1  323.14  5606.8  326.10  5656.1  328.05  5803.2  331.10
#Mann=4,-1,0
  3911.3     0.1       0  4992.3    0.07       0  5004.2     0.1       0
  5223.5    0.05       0
Bank Sta=4992.3,5004.2
Exp/Cntr=0.3,0.1

Type RM Length L Ch R = 1,47003,389,389,389
BEGIN DESCRIPTION:
Mapping XS 536be0f2
END DESCRIPTION:
XS GIS Cut Line= 4
      2115336.16     13422813.03      2114850.02     13422181.05
      2114176.41     13422014.39      2113739.46     13421764.70
#Sta/Elev= 30
  3688.4  336.08  3745.2  335.28  4108.5  325.90  4222.7  324.34  4336.9  323.59
  4430.3  323.75  4465.6  323.24  4604.2  323.59  4769.0  322.58  4783.0  322.97
  4789.6  324.14  4799.9  324.43  4810.2  324.26  4830.8  321.67  4892.7  320.69
  4923.6  319.12  4948.7  319.05  4964.8  317.86  4984.1  314.94  4984.6  314.14
  4995.6  314.14  4996.1  314.94  5006.0  317.74  5026.4  320.04  5036.9  321.77
  5047.2  322.47  5155.2  324.37  5311.6  327.12  5451.2  331.34  5682.9  336.25
#Mann=4,-1,0
  3688.4     0.1       0  4984.1    0.07       0  4996.1     0.1       0
  5155.2    0.05       0
Bank Sta=4984.1,4996.1
Exp/Cntr=0.3,0.1

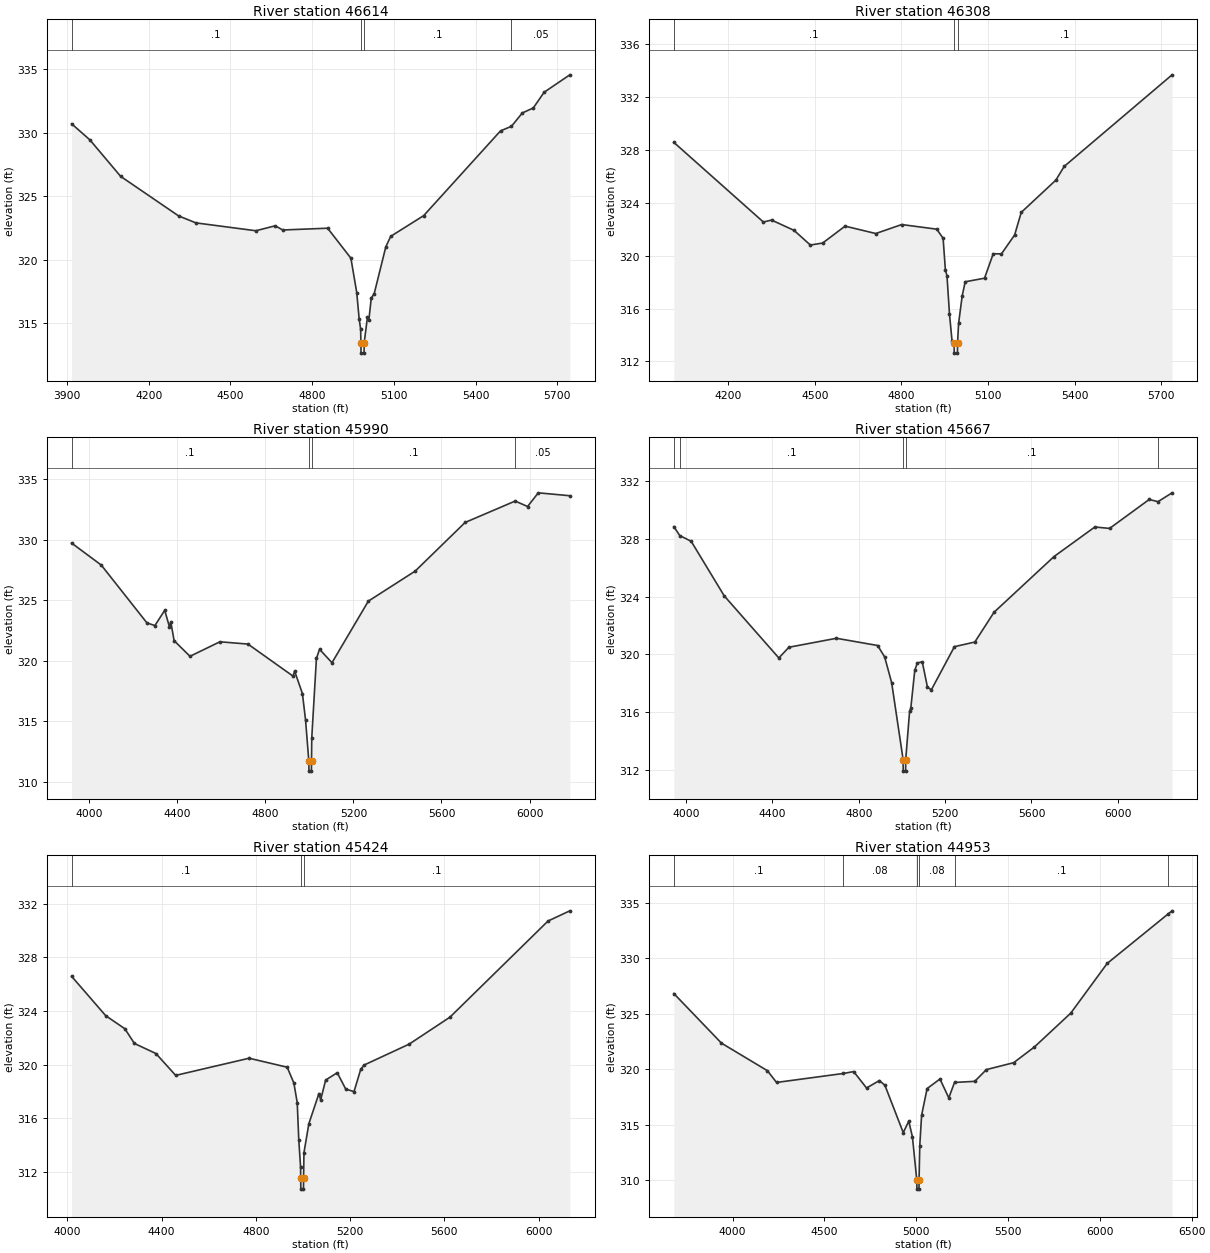
Type RM Length L Ch R = 1,46614,306,306,306
BEGIN DESCRIPTION:
Mapping XS 24b5a684
END DESCRIPTION:
XS GIS Cut Line= 4
      2115398.60     13422465.74      2114877.80     13421875.50
      2114377.80     13421688.00      2113870.89     13421667.17
#Sta/Elev= 30
  3917.0  330.70  3984.2  329.43  4097.1  326.56  4309.6  323.45  4373.2  322.90
  4593.3  322.28  4664.4  322.67  4691.9  322.34  4856.7  322.48  4942.1  320.12
  4963.5  317.42  4972.5  315.32  4977.8  314.54  4978.8  313.45  4979.3  312.65
  4990.3  312.65  4990.8  313.45  5002.7  315.46  5008.1  315.28  5016.9  316.99
  5027.6  317.33  5070.3  321.02  5088.2  321.84  5209.2  323.47  5491.2  330.14
  5531.4  330.50  5571.2  331.55  5611.3  331.94  5651.3  333.18  5745.5  334.55
#Mann=4,-1,0
  3917.0     0.1       0  4978.8    0.07       0  4990.8     0.1       0
  5531.4    0.05       0
Bank Sta=4978.8,4990.8
Exp/Cntr=0.3,0.1

Type RM Length L Ch R = 1,46308,318,318,318
BEGIN DESCRIPTION:
Mapping XS 2bfa785c
END DESCRIPTION:
XS GIS Cut Line= 3
      2115474.99     13422153.25      2114988.91     13421639.39
      2114066.55     13421209.41
#Sta/Elev= 30
  4012.0  328.58  4322.1  322.55  4350.4  322.70  4428.1  321.92  4484.7  320.81
  4527.2  320.96  4604.9  322.24  4711.2  321.68  4800.9  322.36  4922.3  322.01
  4944.3  321.32  4952.2  318.92  4957.7  318.49  4966.4  315.58  4975.1  313.58
  4982.4  313.43  4982.9  312.63  4993.9  312.63  4994.4  313.43  4997.9  314.88
  5010.5  316.98  5020.8  318.03  5087.7  318.30  5117.8  320.15  5146.2  320.14
  5191.9  321.57  5214.8  323.28  5334.6  325.72  5363.6  326.76  5737.0  333.69
#Mann=3,-1,0
  4012.0     0.1       0  4982.4    0.07       0  4994.4     0.1       0
Bank Sta=4982.4,4994.4
Exp/Cntr=0.3,0.1

Type RM Length L Ch R = 1,45990,323,323,323
BEGIN DESCRIPTION:
Mapping XS d251bfc9
END DESCRIPTION:
XS GIS Cut Line= 4
      2115537.51     13422097.70      2115197.24     13421583.83
      2114676.41     13421069.94      2113809.14     13420778.54
#Sta/Elev= 30
  3920.0  329.74  4054.8  327.92  4262.3  323.14  4298.4  322.92  4343.0  324.18
  4364.7  322.80  4370.7  323.22  4385.7  321.67  4457.9  320.38  4593.7  321.58
  4721.0  321.39  4926.0  318.74  4933.0  319.16  4968.4  317.30  4982.6  315.13
  4997.7  311.69  4998.2  310.89  5009.2  310.89  5009.7  311.69  5010.8  313.62
  5032.0  320.20  5046.2  320.96  5102.7  319.85  5267.9  324.94  5480.5  327.42
  5707.3  331.44  5934.7  333.21  5991.0  332.76  6039.6  333.89  6182.9  333.65
#Mann=4,-1,0
  3920.0     0.1       0  4997.7    0.07       0  5009.7     0.1       0
  5934.7    0.05       0
Bank Sta=4997.7,5009.7
Exp/Cntr=0.3,0.1

Type RM Length L Ch R = 1,45667,243,243,243
BEGIN DESCRIPTION:
Mapping XS f106dfd1
END DESCRIPTION:
XS GIS Cut Line= 4
      2115530.56     13421986.58      2115308.35     13421576.89
      2115037.52     13420917.16      2113969.01     13420556.37
#Sta/Elev= 30
  3943.9  328.84  3971.1  328.22  4024.3  327.82  4177.3  324.05  4430.1  319.76
  4476.9  320.50  4696.9  321.12  4887.6  320.62  4920.1  319.83  4952.5  318.05
  5005.6  312.74  5006.1  311.94  5017.1  311.94  5017.6  312.74  5035.6  316.08
  5041.0  316.27  5059.6  318.91  5071.4  319.42  5094.3  319.49  5118.3  317.74
  5136.3  317.56  5243.2  320.54  5337.6  320.86  5426.7  322.92  5704.6  326.77
  5893.4  328.81  5961.6  328.71  6145.0  330.71  6185.9  330.56  6250.9  331.17
#Mann=5,-1,0
  3943.9    0.08       0  3971.1     0.1       0  5005.6    0.07       0
  5017.6     0.1       0  6185.9    0.05       0
Bank Sta=5005.6,5017.6
Exp/Cntr=0.3,0.1

Type RM Length L Ch R = 1,45424,471,471,471
BEGIN DESCRIPTION:
Mapping XS b76e9fac
END DESCRIPTION:
XS GIS Cut Line= 4
      2115482.93     13421847.89      2115335.36     13420971.12
      2114957.76     13420545.77      2114415.19     13420176.83
#Sta/Elev= 30
  4018.0  326.58  4162.9  323.64  4244.0  322.67  4284.6  321.57  4375.9  320.82
  4459.7  319.19  4771.3  320.47  4932.8  319.80  4961.2  318.62  4975.4  317.16
  4982.1  314.35  4989.7  312.34  4990.2  311.51  4990.7  310.71  5001.9  310.71
  5002.4  311.51  5003.9  313.42  5024.8  315.59  5067.4  317.83  5075.0  317.37
  5095.9  318.84  5145.2  319.39  5181.2  318.17  5216.3  317.98  5244.7  319.63
  5258.9  319.96  5450.2  321.52  5623.3  323.53  6039.5  330.70  6132.0  331.46
#Mann=3,-1,0
  4018.0     0.1       0  4990.2    0.07       0  5002.4     0.1       0
Bank Sta=4990.2,5002.4
Exp/Cntr=0.3,0.1

Type RM Length L Ch R = 1,44953,240,240,240
BEGIN DESCRIPTION:
La Jarita Creek 56.0
END DESCRIPTION:
XS GIS Cut Line= 3
      2115490.87     13421844.47      2115469.17     13420386.11
      2114583.72     13419496.33
#Sta/Elev= 30
  3679.5  326.81  3939.0  322.34  4189.0  319.86  4239.0  318.80  4603.6  319.61
  4659.1  319.78  4729.1  318.30  4799.1  318.97  4829.1  318.55  4929.1  314.28
  4959.1  315.31  4979.1  313.90  5003.0  309.99  5003.5  309.19  5014.7  309.19
  5015.2  309.99  5019.1  313.11  5029.1  315.85  5059.1  318.25  5129.1  319.11
  5177.1  317.41  5208.4  318.80  5318.5  318.90  5382.2  319.96  5530.7  320.58
  5643.8  322.00  5841.8  325.05  6039.8  329.52  6373.4  334.00  6393.3  334.26
#Mann=6,-1,0
  3679.5     0.1       0  4603.6    0.08       0  5003.0    0.07       0
  5015.2    0.08       0  5208.4     0.1       0  6373.4    0.08       0
Bank Sta=5003,5015.2
Exp/Cntr=0.3,0.1

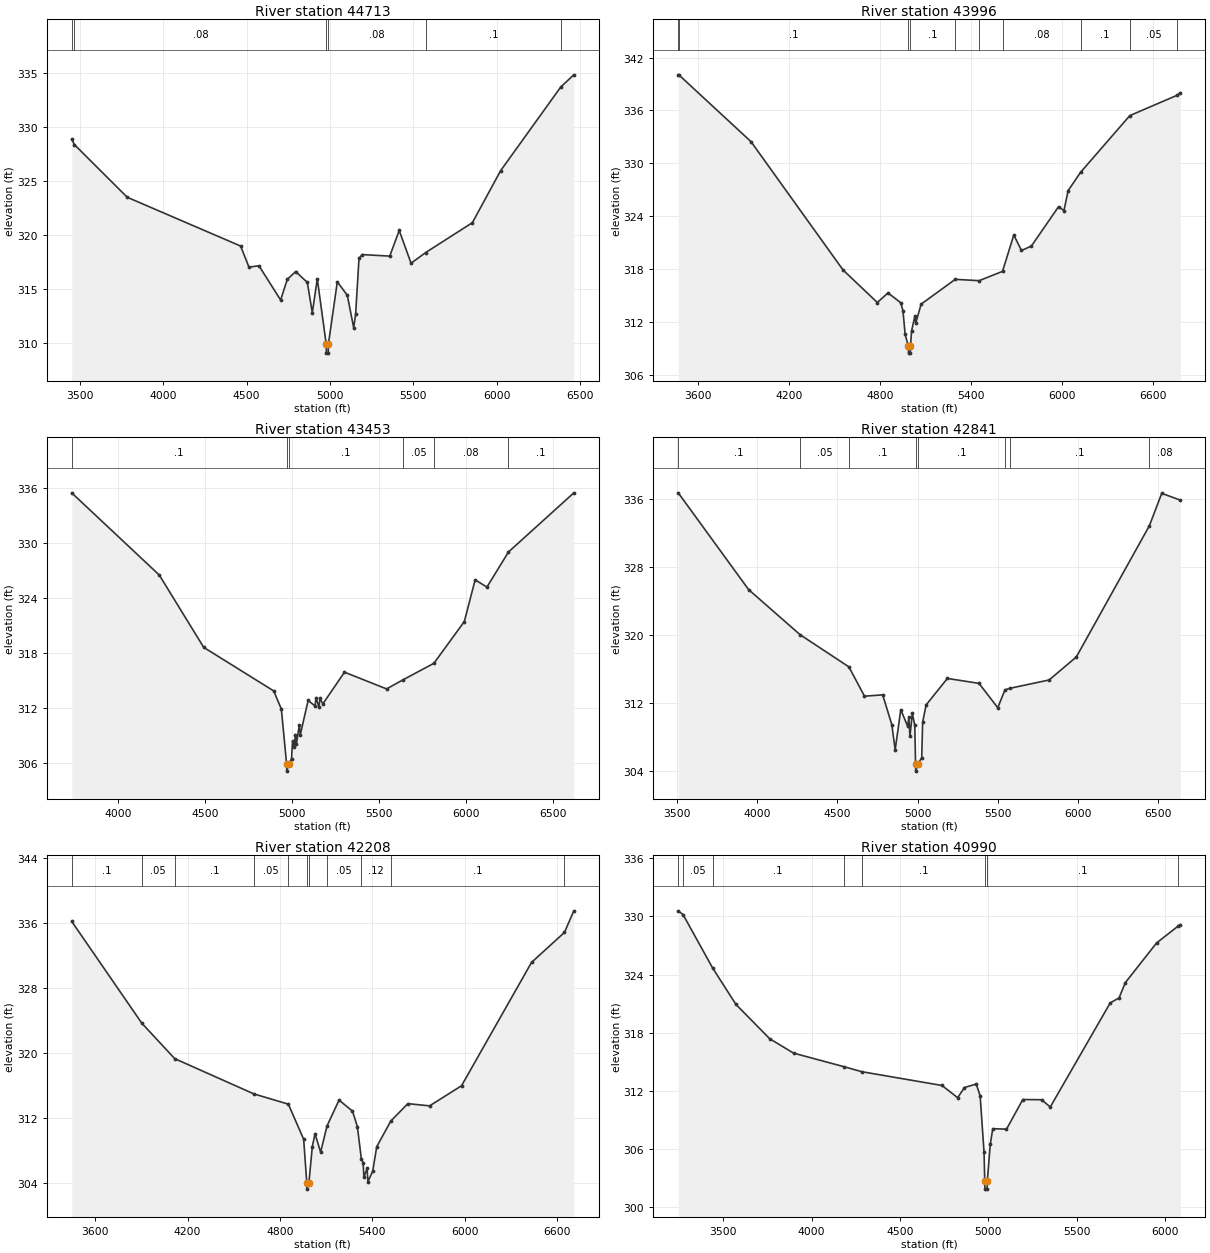
Type RM Length L Ch R = 1,44713,717,717,717
BEGIN DESCRIPTION:
La Jarita Creek 55.0
END DESCRIPTION:
XS GIS Cut Line= 3
      2115742.60     13421987.68      2115664.48     13420164.75
      2114774.99     13419374.99
#Sta/Elev= 30
  3450.0  328.85  3466.3  328.35  3783.0  323.49  4463.6  318.98  4513.7  317.03
  4573.7  317.16  4703.8  313.99  4743.9  315.90  4793.9  316.62  4864.0  315.62
  4894.0  312.81  4924.0  315.95  4977.8  309.88  4978.3  309.08  4989.8  309.08
  4990.3  309.88  5044.1  315.67  5104.2  314.43  5142.4  311.43  5154.2  312.71
  5174.3  317.84  5194.3  318.19  5358.9  318.05  5415.8  320.42  5486.9  317.39
  5574.7  318.38  5854.9  321.14  6024.6  325.95  6386.3  333.70  6464.1  334.81
#Mann=6,-1,0
  3450.0     0.1       0  3466.3    0.08       0  4977.8    0.07       0
  4990.3    0.08       0  5574.7     0.1       0  6386.3    0.08       0
Bank Sta=4977.8,4990.3
Exp/Cntr=0.3,0.1

Type RM Length L Ch R = 1,43996,543,543,543
BEGIN DESCRIPTION:
La Jarita Creek 54.0
END DESCRIPTION:
XS GIS Cut Line= 3
      2117175.01     13421025.01      2116075.00     13419925.00
      2114625.03     13418925.02
#Sta/Elev= 30
  3466.7  340.04  3471.1  340.03  3947.5  332.45  4555.7  317.87  4781.9  314.18
  4852.6  315.27  4937.5  314.14  4951.6  313.22  4965.8  310.55  4987.1  309.23
  4988.0  308.43  5000.2  308.43  5001.1  309.23  5008.2  310.94  5029.8  312.62
  5035.9  311.86  5071.7  314.00  5297.0  316.81  5454.7  316.66  5609.2  317.72
  5683.6  321.85  5734.3  320.09  5799.8  320.59  5979.1  325.06  6014.9  324.62
  6042.7  326.89  6124.3  328.96  6450.2  335.41  6762.9  337.72  6783.7  338.02
#Mann=10,-1,0
  3466.7    0.05       0  3471.1     0.1       0  4987.1    0.07       0
  5001.1     0.1       0  5297.0    0.05       0  5454.7     0.1       0
  5609.2    0.08       0  6124.3     0.1       0  6450.2    0.05       0
  6762.9     0.1       0
Bank Sta=4987.1,5001.1
Exp/Cntr=0.3,0.1

Type RM Length L Ch R = 1,43453,612,612,612
BEGIN DESCRIPTION:
La Jarita Creek 53.0
END DESCRIPTION:
XS GIS Cut Line= 3
      2117075.00     13420725.00      2116425.00     13419625.00
      2114975.02     13418925.01
#Sta/Elev= 30
  3733.7  335.47  4237.0  326.50  4492.5  318.60  4895.2  313.84  4939.2  311.86
  4969.3  305.88  4970.2  305.08  4983.3  305.88  4997.8  306.45  5003.6  308.40
  5014.2  307.75  5019.9  309.07  5025.5  308.01  5042.5  310.11  5048.1  309.06
  5093.3  312.80  5133.0  312.20  5138.5  313.11  5155.6  312.05  5161.1  313.03
  5178.0  312.43  5302.3  315.89  5544.4  314.06  5637.6  315.04  5816.6  316.86
  5991.6  321.42  6053.8  325.98  6121.6  325.18  6245.5  329.02  6621.5  335.48
#Mann=6,-1,0
  3733.7     0.1       0  4969.3    0.07       0  4983.3     0.1       0
  5637.6    0.05       0  5816.6    0.08       0  6245.5     0.1       0
Bank Sta=4969.3,4983.3
Exp/Cntr=0.3,0.1

Type RM Length L Ch R = 1,42841,633,633,633
BEGIN DESCRIPTION:
La Jarita Creek 52.0
END DESCRIPTION:
XS GIS Cut Line= 3
      2117775.00     13420225.00      2116675.00     13419275.00
      2115225.01     13418425.01
#Sta/Elev= 30
  3506.1  336.78  3945.4  325.39  4266.2  320.09  4571.6  316.29  4668.8  312.84
  4782.4  313.00  4839.4  309.49  4860.3  306.53  4895.4  311.26  4938.2  309.30
  4945.8  310.38  4952.4  308.10  4967.4  310.81  4982.7  309.42  4987.7  304.82
  4988.6  304.02  5001.7  304.82  5026.0  305.60  5031.8  309.76  5053.3  311.81
  5186.3  314.93  5383.7  314.35  5500.9  311.48  5545.6  313.59  5577.0  313.77
  5821.4  314.75  5991.2  317.46  6447.0  332.90  6524.4  336.72  6640.3  335.92
#Mann=8,-1,0
  3506.1     0.1       0  4266.2    0.05       0  4571.6     0.1       0
  4987.7    0.07       0  5001.7     0.1       0  5545.6    0.05       0
  5577.0     0.1       0  6447.0    0.08       0
Bank Sta=4987.7,5001.7
Exp/Cntr=0.3,0.1

Type RM Length L Ch R = 1,42208,1218,1218,1218
BEGIN DESCRIPTION:
La Jarita Creek 51.0
END DESCRIPTION:
XS GIS Cut Line= 3
      2117825.03     13420075.04      2116875.00     13418825.00
      2115274.98     13418274.99
#Sta/Elev= 30
  3448.0  336.14  3903.3  323.64  4116.9  319.29  4631.0  314.96  4855.1  313.70
  4954.6  309.39  4974.7  304.06  4975.6  303.26  4988.8  304.06  5010.8  308.49
  5028.4  310.05  5064.9  307.80  5106.3  311.02  5184.6  314.20  5271.9  312.84
  5303.6  310.94  5329.2  307.01  5340.8  306.52  5346.1  304.74  5366.8  305.80
  5372.1  304.18  5403.3  305.48  5429.3  308.47  5520.5  311.62  5631.4  313.76
  5772.9  313.49  5980.3  315.96  6435.0  331.11  6649.1  334.80  6710.0  337.45
#Mann=11,-1,0
  3448.0     0.1       0  3903.3    0.05       0  4116.9     0.1       0
  4631.0    0.05       0  4855.1     0.1       0  4974.7    0.07       0
  4988.8     0.1       0  5106.3    0.05       0  5329.2    0.12       0
  5520.5     0.1       0  6649.1    0.08       0
Bank Sta=4974.7,4988.8
Exp/Cntr=0.3,0.1

Type RM Length L Ch R = 1,40990,529,529,529
BEGIN DESCRIPTION:
La Jarita Creek 50.0
END DESCRIPTION:
XS GIS Cut Line= 3
      2117825.02     13419725.04      2117025.00     13418175.00
      2116225.01     13417425.01
#Sta/Elev= 30
  3245.3  330.58  3272.6  330.19  3439.9  324.68  3571.7  320.92  3763.2  317.37
  3898.0  315.89  4180.8  314.50  4284.6  313.97  4737.7  312.55  4826.3  311.29
  4865.0  312.34  4931.4  312.70  4953.6  311.49  4975.7  305.65  4979.6  302.65
  4980.7  301.85  4993.0  301.85  4994.0  302.65  5010.9  306.48  5025.0  308.09
  5102.7  308.04  5195.0  311.10  5301.0  311.08  5350.4  310.33  5689.8  321.08
  5739.6  321.59  5774.8  323.16  5951.7  327.26  6072.9  328.99  6086.2  329.15
#Mann=8,-1,0
  3245.3     0.1       0  3272.6    0.05       0  3439.9     0.1       0
  4180.8    0.05       0  4284.6     0.1       0  4979.6    0.07       0
  4994.0     0.1       0  6072.9    0.05       0
Bank Sta=4979.6,4994
Exp/Cntr=0.3,0.1

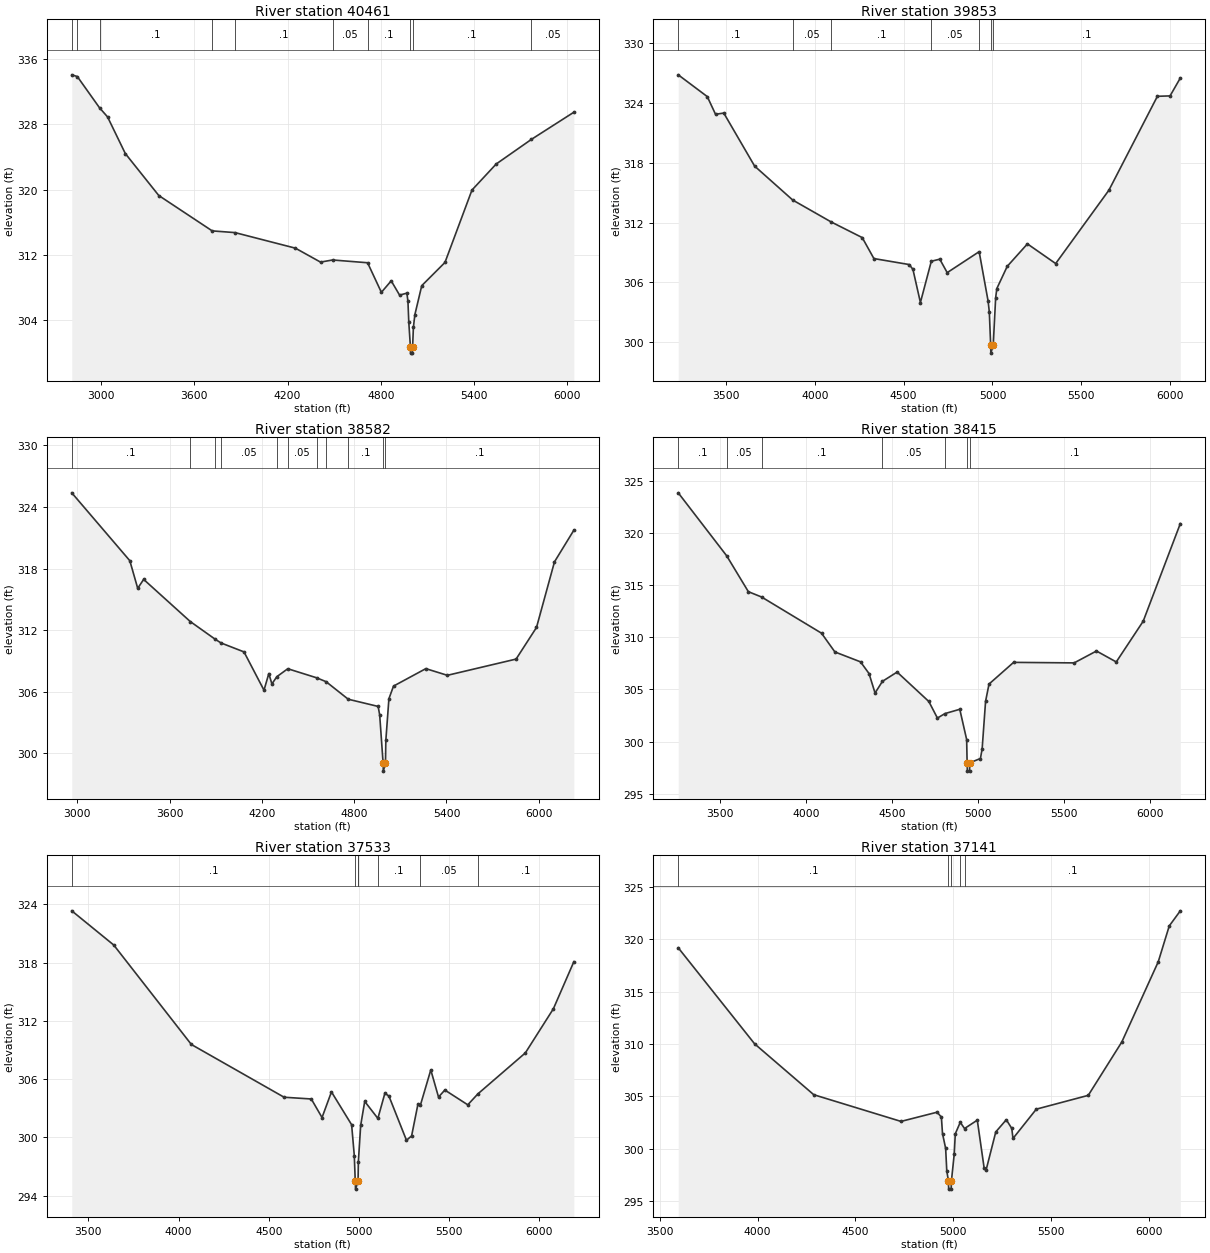
Type RM Length L Ch R = 1,40461,608,608,608
BEGIN DESCRIPTION:
La Jarita Creek 49.0
END DESCRIPTION:
XS GIS Cut Line= 3
      2118024.99     13419724.98      2117225.00     13417725.00
      2116224.97     13417324.99
#Sta/Elev= 30
  2811.6  334.08  2847.3  333.87  2990.4  330.03  3041.8  328.92  3156.2  324.42
  3371.6  319.27  3715.4  314.93  3862.1  314.72  4250.8  312.81  4412.3  311.10
  4490.6  311.36  4715.3  311.02  4804.1  307.39  4867.4  308.80  4921.2  307.05
  4968.3  307.29  4975.1  306.27  4980.4  303.75  4990.8  300.73  4991.8  299.93
  5004.1  299.93  5005.2  300.73  5010.1  303.09  5019.5  304.64  5063.9  308.21
  5213.4  311.06  5387.0  319.94  5543.2  323.14  5769.7  326.16  6042.7  329.49
#Mann=10,-1,0
  2811.6     0.1       0  2847.3    0.05       0  2990.4     0.1       0
  3715.4    0.05       0  3862.1     0.1       0  4490.6    0.05       0
  4715.3     0.1       0  4990.8    0.07       0  5005.2     0.1       0
  5769.7    0.05       0
Bank Sta=4990.8,5005.2
Exp/Cntr=0.3,0.1

Type RM Length L Ch R = 1,39853,1271,1271,1271
BEGIN DESCRIPTION:
La Jarita Creek 48.0
END DESCRIPTION:
XS GIS Cut Line= 3
      2118605.76     13418751.07      2118137.01     13417698.99
      2116775.01     13416725.01
#Sta/Elev= 30
  3231.3  326.79  3394.8  324.61  3441.2  322.84  3487.7  322.96  3661.3  317.65
  3875.8  314.25  4092.9  312.05  4267.0  310.49  4332.7  308.39  4531.5  307.79
  4552.4  307.31  4594.5  303.99  4655.9  308.12  4703.5  308.33  4745.3  306.98
  4925.2  309.08  4975.7  304.12  4982.4  303.04  4990.0  299.72  4991.0  298.92
  5004.4  299.72  5018.1  304.48  5024.8  305.39  5083.2  307.61  5196.9  309.86
  5355.9  307.89  5655.7  315.24  5928.5  324.64  5999.8  324.68  6057.5  326.47
#Mann=7,-1,0
  3231.3     0.1       0  3875.8    0.05       0  4092.9     0.1       0
  4655.9    0.05       0  4925.2     0.1       0  4990.0    0.07       0
  5004.4     0.1       0
Bank Sta=4990,5004.4
Exp/Cntr=0.3,0.1

Type RM Length L Ch R = 1,38582,167,167,167
BEGIN DESCRIPTION:
Mapping XS f40ba179
END DESCRIPTION:
XS GIS Cut Line= 5
      2119718.58     13417790.99      2118581.45     13417261.49
      2118624.86     13416836.14      2117808.88     13416827.46
      2117149.62     13416437.11
#Sta/Elev= 30
  2964.0  325.38  3341.4  318.77  3392.7  316.08  3431.3  316.95  3734.1  312.85
  3896.7  311.12  3934.5  310.76  4083.7  309.89  4213.7  306.16  4245.0  307.78
  4265.1  306.77  4297.5  307.48  4368.4  308.25  4555.7  307.37  4617.3  306.99
  4761.5  305.28  4955.8  304.58  4965.8  303.75  4988.0  299.08  4989.5  298.28
  5003.5  299.08  5005.8  301.27  5025.8  305.33  5055.8  306.56  5265.8  308.26
  5405.8  307.61  5852.6  309.19  5985.3  312.27  6102.2  318.66  6228.1  321.74
#Mann=11,-1,0
  2964.0     0.1       0  3734.1    0.05       0  3896.7    0.08       0
  3934.5    0.05       0  4297.5     0.1       0  4368.4    0.05       0
  4555.7     0.1       0  4617.3    0.05       0  4761.5     0.1       0
  4988.0    0.07       0  5003.5     0.1       0
Bank Sta=4988,5003.5
Exp/Cntr=0.3,0.1

Type RM Length L Ch R = 1,38415,882,882,882
BEGIN DESCRIPTION:
Mapping XS bb09901d
END DESCRIPTION:
XS GIS Cut Line= 4
      2119779.38     13417626.08      2118746.38     13416731.97
      2117826.24     13416697.25      2117314.12     13416324.01
#Sta/Elev= 30
  3254.8  323.86  3536.6  317.82  3662.7  314.38  3739.6  313.87  4088.2  310.40
  4166.1  308.60  4315.2  307.65  4364.6  306.53  4399.7  304.66  4442.6  305.78
  4528.0  306.67  4712.5  303.85  4762.5  302.26  4806.5  302.69  4892.6  303.10
  4932.6  300.20  4935.3  297.97  4936.8  297.17  4949.3  297.17  4950.8  297.97
  5012.7  298.38  5022.7  299.30  5042.7  303.87  5062.7  305.52  5205.7  307.60
  5558.0  307.55  5687.8  308.69  5802.9  307.64  5959.7  311.55  6175.5  320.91
#Mann=7,-1,0
  3254.8     0.1       0  3536.6    0.05       0  3739.6     0.1       0
  4442.6    0.05       0  4806.5     0.1       0  4935.3    0.07       0
  4950.8     0.1       0
Bank Sta=4935.3,4950.8
Exp/Cntr=0.3,0.1

Type RM Length L Ch R = 1,37533,392,392,392
BEGIN DESCRIPTION:
Mapping XS dd9d110a
END DESCRIPTION:
XS GIS Cut Line= 3
      2120456.46     13416975.03      2118807.15     13416150.37
      2118191.44     13415439.28
#Sta/Elev= 30
  3407.8  323.32  3640.6  319.80  4071.1  309.56  4585.4  304.13  4736.3  303.95
  4795.8  302.04  4848.1  304.68  4959.9  301.30  4974.7  298.13  4980.1  295.47
  4981.6  294.67  4995.6  295.47  4997.3  297.49  5010.2  301.24  5032.6  303.70
  5105.5  301.95  5144.4  304.54  5166.8  304.25  5264.1  299.70  5292.6  300.15
  5327.7  303.41  5341.0  303.29  5399.0  306.94  5441.8  304.15  5476.9  304.87
  5604.1  303.35  5660.5  304.48  5923.3  308.69  6079.0  313.24  6192.4  318.08
#Mann=7,-1,0
  3407.8     0.1       0  4980.1    0.07       0  4995.6     0.1       0
  4997.3    0.12       0  5105.5     0.1       0  5341.0    0.05       0
  5660.5     0.1       0
Bank Sta=4980.1,4995.6
Exp/Cntr=0.3,0.1

Type RM Length L Ch R = 1,37141,1110,1110,1110
BEGIN DESCRIPTION:
Mapping XS 874e5834
END DESCRIPTION:
XS GIS Cut Line= 4
      2120352.31     13416810.11      2119336.66     13416115.65
      2118928.68     13415369.12      2118539.03     13415083.39
#Sta/Elev= 30
  3595.0  319.19  3985.2  310.01  4287.2  305.15  4732.8  302.60  4917.1  303.48
  4939.0  303.01  4944.7  301.44  4960.8  300.02  4966.5  297.89  4974.8  296.93
  4976.3  296.13  4988.8  296.13  4990.4  296.93  5004.4  299.44  5010.1  301.42
  5035.3  302.51  5057.3  301.92  5122.4  302.72  5157.2  298.17  5167.6  297.97
  5216.9  301.60  5270.6  302.76  5298.5  301.93  5304.7  300.97  5423.8  303.77
  5689.2  305.09  5860.6  310.19  6046.6  317.85  6102.9  321.28  6159.3  322.72
#Mann=5,-1,0
  3595.0     0.1       0  4974.8    0.07       0  4990.4     0.1       0
  5035.3    0.12       0  5057.3     0.1       0
Bank Sta=4974.8,4990.4
Exp/Cntr=0.3,0.1