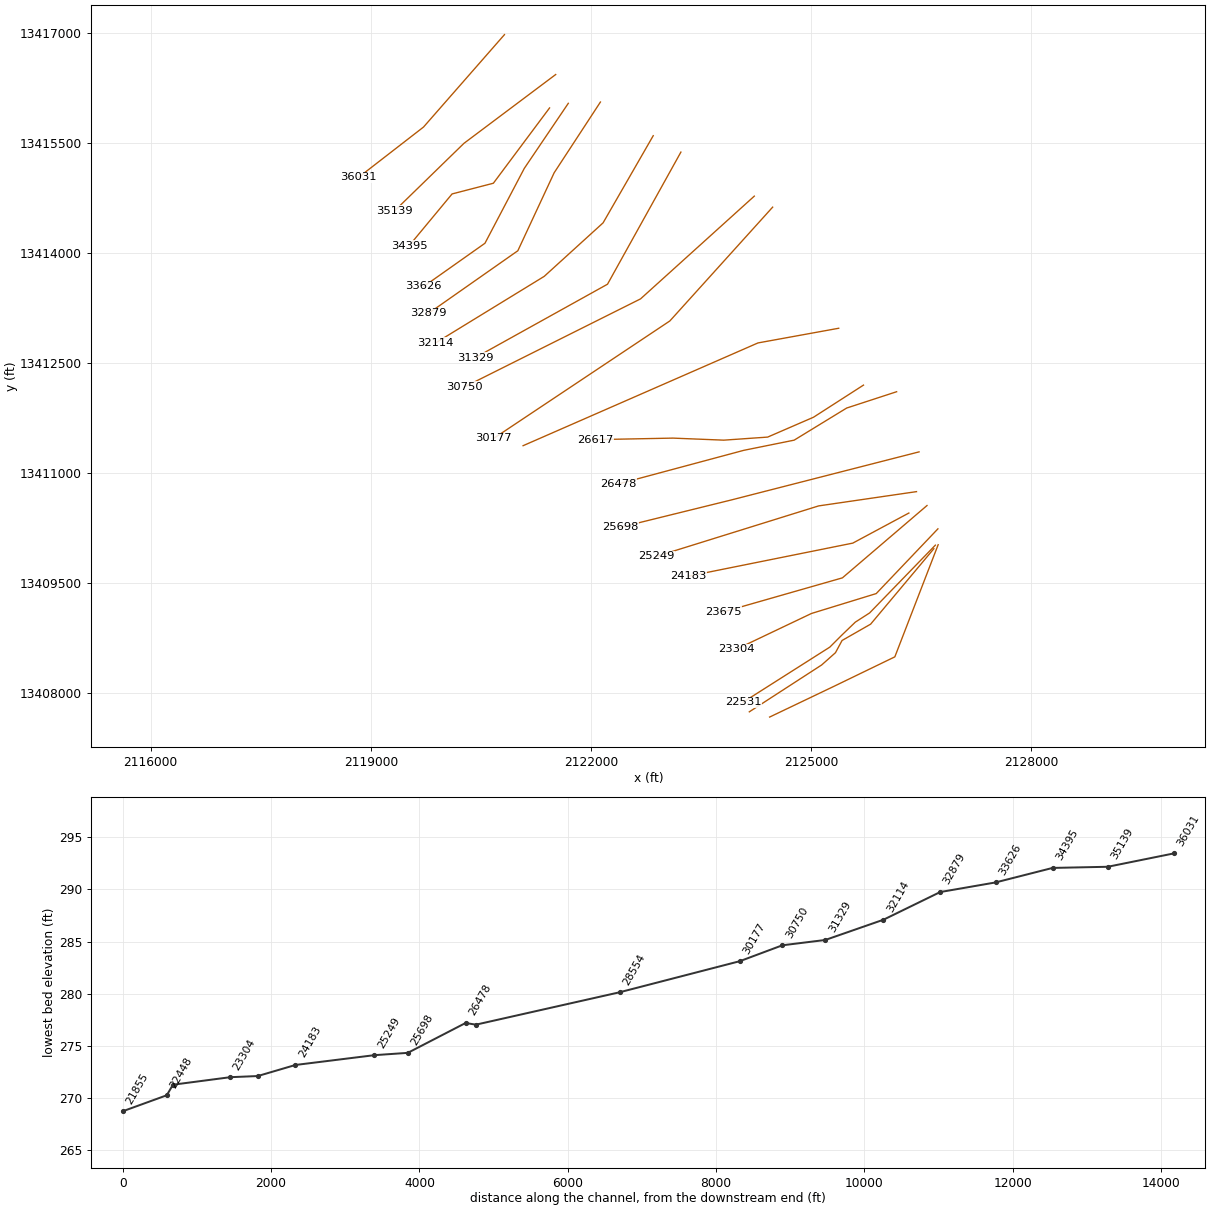
HEC-RAS study La Jarita Creek.prj: La Jarita Creek Base Level Engineering

--- La Jarita Creek.g01 (geometry) --- (continued)

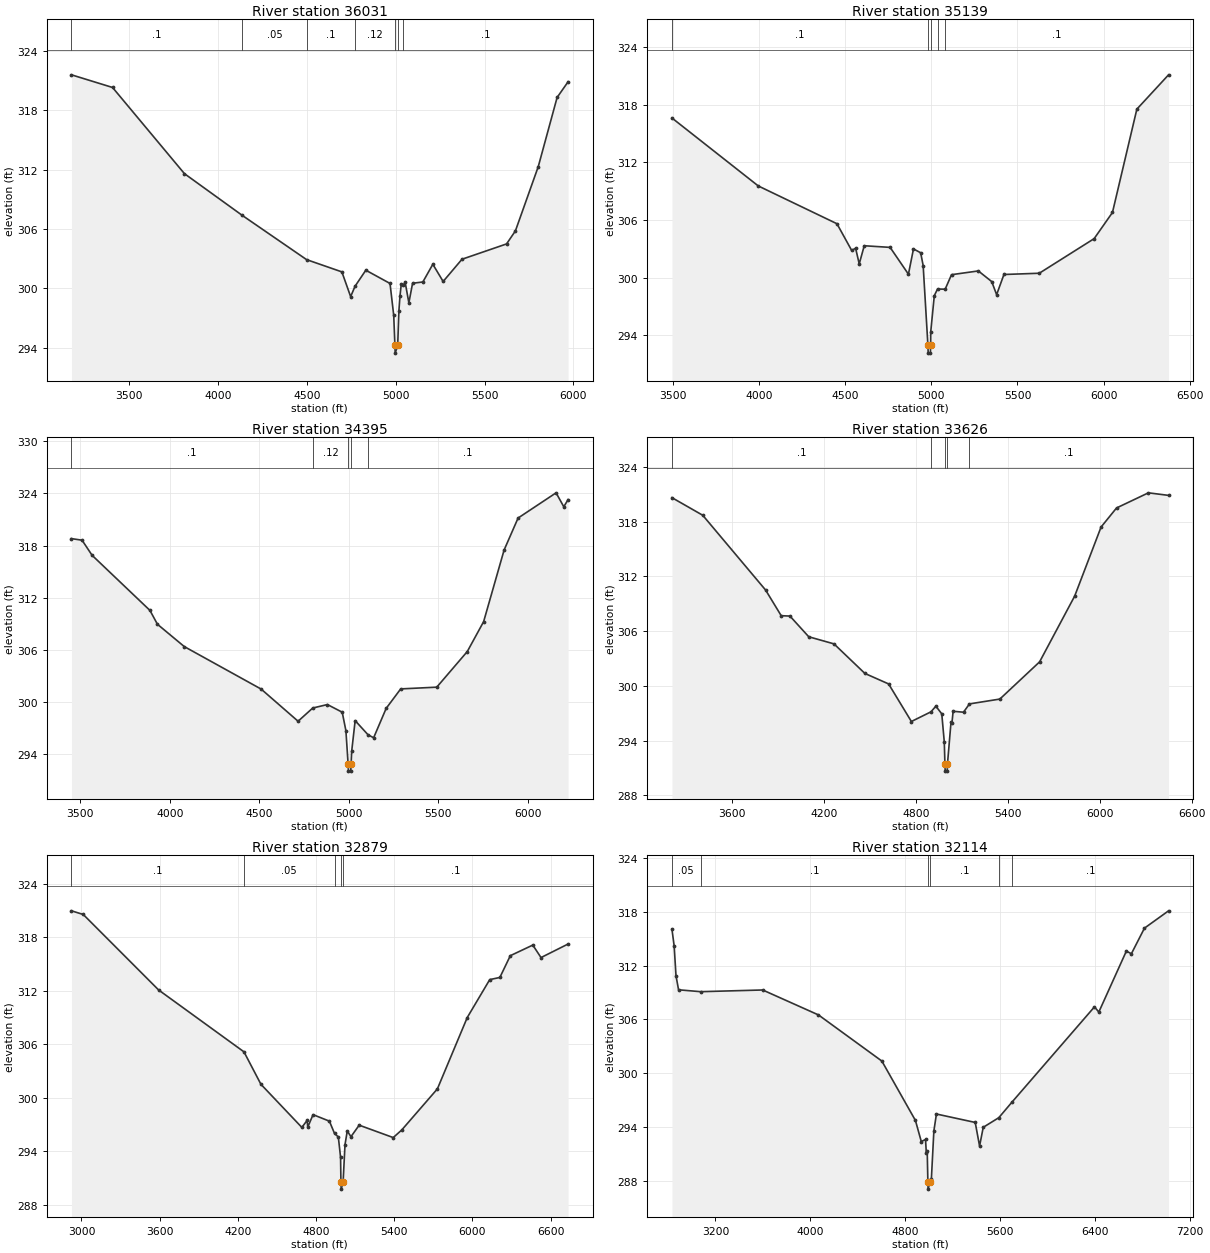
Type RM Length L Ch R = 1,36031,892,892,892
BEGIN DESCRIPTION:
Mapping XS ac710576
END DESCRIPTION:
XS GIS Cut Line= 3
      2120821.01     13416974.99      2119718.61     13415716.35
      2118833.18     13415030.58
#Sta/Elev= 30
  3176.9  321.60  3407.8  320.32  3812.1  311.60  4137.1  307.38  4499.2  302.90
  4697.6  301.66  4746.9  299.16  4772.1  300.22  4832.3  301.83  4968.4  300.49
  4989.3  297.25  4995.9  294.24  4997.5  293.44  5011.6  294.24  5018.2  297.68
  5024.6  299.26  5031.7  300.42  5043.7  300.33  5053.5  300.61  5074.4  298.53
  5095.2  300.51  5153.1  300.64  5209.2  302.43  5267.2  300.69  5373.2  302.94
  5623.9  304.49  5673.7  305.81  5802.3  312.32  5908.2  319.31  5970.0  320.90
#Mann=7,-1,0
  3176.9     0.1       0  4137.1    0.05       0  4499.2     0.1       0
  4772.1    0.12       0  4995.9    0.07       0  5011.6    0.12       0
  5043.7     0.1       0
Bank Sta=4995.9,5011.6
Exp/Cntr=0.3,0.1

Type RM Length L Ch R = 1,35139,744,744,744
BEGIN DESCRIPTION:
La Jarita Creek 41.0
END DESCRIPTION:
XS GIS Cut Line= 3
      2121518.92     13416431.60      2120268.95     13415494.12
      2119324.98     13414574.98
#Sta/Elev= 30
  3496.3  316.62  3997.0  309.55  4453.2  305.62  4538.7  302.84  4561.5  303.07
  4582.4  301.44  4611.5  303.33  4761.5  303.16  4867.8  300.37  4897.0  303.00
  4938.7  302.60  4953.2  301.27  4980.8  292.96  4982.4  292.16  4995.0  292.16
  4996.6  292.96  4997.0  294.36  5017.8  298.14  5036.6  298.83  5080.8  298.81
  5117.6  300.32  5273.2  300.71  5350.9  299.60  5379.2  298.24  5421.6  300.34
  5626.6  300.47  5944.8  304.07  6051.0  306.79  6192.5  317.54  6376.3  321.11
#Mann=5,-1,0
  3496.3     0.1       0  4980.8    0.07       0  4996.6     0.1       0
  5036.6    0.12       0  5080.8     0.1       0
Bank Sta=4980.8,4996.6
Exp/Cntr=0.3,0.1

Type RM Length L Ch R = 1,34395,769,769,769
BEGIN DESCRIPTION:
Mapping XS bc0ad676
END DESCRIPTION:
XS GIS Cut Line= 4
      2121435.62     13415976.77      2120669.99     13414950.72
      2120107.49     13414804.89      2119524.17     13414101.77
#Sta/Elev= 30
  3450.6  318.80  3509.6  318.62  3565.8  316.88  3889.0  310.54  3930.7  308.95
  4080.8  306.38  4510.3  301.49  4716.7  297.79  4798.6  299.31  4880.6  299.71
  4963.3  298.83  4983.9  296.71  4996.3  292.85  4998.2  292.05  5010.9  292.05
  5012.9  292.85  5016.3  294.35  5035.6  297.86  5107.7  296.23  5138.9  295.89
  5208.9  299.27  5290.1  301.51  5491.6  301.71  5662.2  305.81  5753.5  309.25
  5867.9  317.49  5946.0  321.17  6158.3  324.07  6201.3  322.47  6225.5  323.29
#Mann=5,-1,0
  3450.6     0.1       0  4798.6    0.12       0  4996.3    0.07       0
  5012.9    0.12       0  5107.7     0.1       0
Bank Sta=4996.3,5012.9
Exp/Cntr=0.3,0.1

Type RM Length L Ch R = 1,33626,747,747,747
BEGIN DESCRIPTION:
Mapping XS 1cb0fa17
END DESCRIPTION:
XS GIS Cut Line= 4
      2121690.84     13416039.28      2121091.87     13415153.85
      2120555.41     13414133.01      2119722.09     13413544.48
#Sta/Elev= 30
  3206.7  320.64  3407.8  318.71  3818.3  310.51  3920.1  307.70  3977.1  307.66
  4099.9  305.39  4264.7  304.61  4466.4  301.37  4621.3  300.22  4770.0  296.10
  4897.8  297.16  4929.9  297.78  4968.4  296.94  4984.8  293.87  4989.0  291.46
  4991.0  290.66  5003.7  290.66  5005.7  291.46  5028.9  296.05  5034.5  295.89
  5042.6  297.22  5110.3  297.12  5149.2  298.03  5347.6  298.56  5607.2  302.64
  5836.2  309.85  6008.5  317.42  6109.5  319.51  6317.6  321.17  6449.1  320.89
#Mann=5,-1,0
  3206.7     0.1       0  4897.8    0.12       0  4989.0    0.07       0
  5005.7    0.12       0  5149.2     0.1       0
Bank Sta=4989,5005.7
Exp/Cntr=0.3,0.1

Type RM Length L Ch R = 1,32879,765,765,765
BEGIN DESCRIPTION:
Mapping XS 280b2305
END DESCRIPTION:
XS GIS Cut Line= 4
      2122128.48     13416056.95      2121498.29     13415093.43
      2121003.50     13414030.93      2119784.78     13413176.78
#Sta/Elev= 30
  2923.3  320.94  3013.6  320.53  3592.6  312.06  4247.1  305.13  4377.4  301.49
  4691.3  296.66  4731.5  297.44  4737.0  296.70  4777.3  298.09  4902.7  297.36
  4942.2  295.98  4971.3  295.59  4988.5  293.31  4991.3  290.54  4993.3  289.74
  5008.0  290.54  5022.6  294.73  5039.9  296.26  5068.3  295.62  5131.4  296.91
  5392.6  295.52  5458.0  296.37  5731.7  300.98  5960.9  308.98  6133.5  313.23
  6211.1  313.47  6291.3  315.91  6463.9  317.10  6527.0  315.70  6734.9  317.22
#Mann=5,-1,0
  2923.3     0.1       0  4247.1    0.05       0  4942.2     0.1       0
  4991.3    0.07       0  5008.0     0.1       0
Bank Sta=4991.3,5008
Exp/Cntr=0.3,0.1

Type RM Length L Ch R = 1,32114,785,785,785
BEGIN DESCRIPTION:
Mapping XS 2b850d4f
END DESCRIPTION:
XS GIS Cut Line= 4
      2122847.94     13415598.28      2122164.96     13414411.14
      2121362.88     13413681.97      2119883.69     13412775.71
#Sta/Elev= 30
  2832.7  316.05  2851.2  314.21  2867.0  310.85  2888.6  309.30  3074.9  309.09
  3597.9  309.28  4068.5  306.50  4603.1  301.36  4886.3  294.74  4935.6  292.39
  4971.4  292.62  4978.2  291.07  4985.6  291.30  4991.2  287.89  4993.2  287.09
  5008.0  287.89  5020.7  288.22  5041.7  293.57  5063.3  295.46  5390.5  294.52
  5427.2  291.89  5458.1  293.98  5589.4  295.05  5703.5  296.83  6396.2  307.40
  6432.9  306.82  6665.0  313.61  6707.6  313.32  6817.8  316.17  7021.0  318.10
#Mann=6,-1,0
  2832.7    0.05       0  3074.9     0.1       0  4991.2    0.07       0
  5008.0     0.1       0  5589.4    0.05       0  5703.5     0.1       0
Bank Sta=4991.2,5008
Exp/Cntr=0.3,0.1

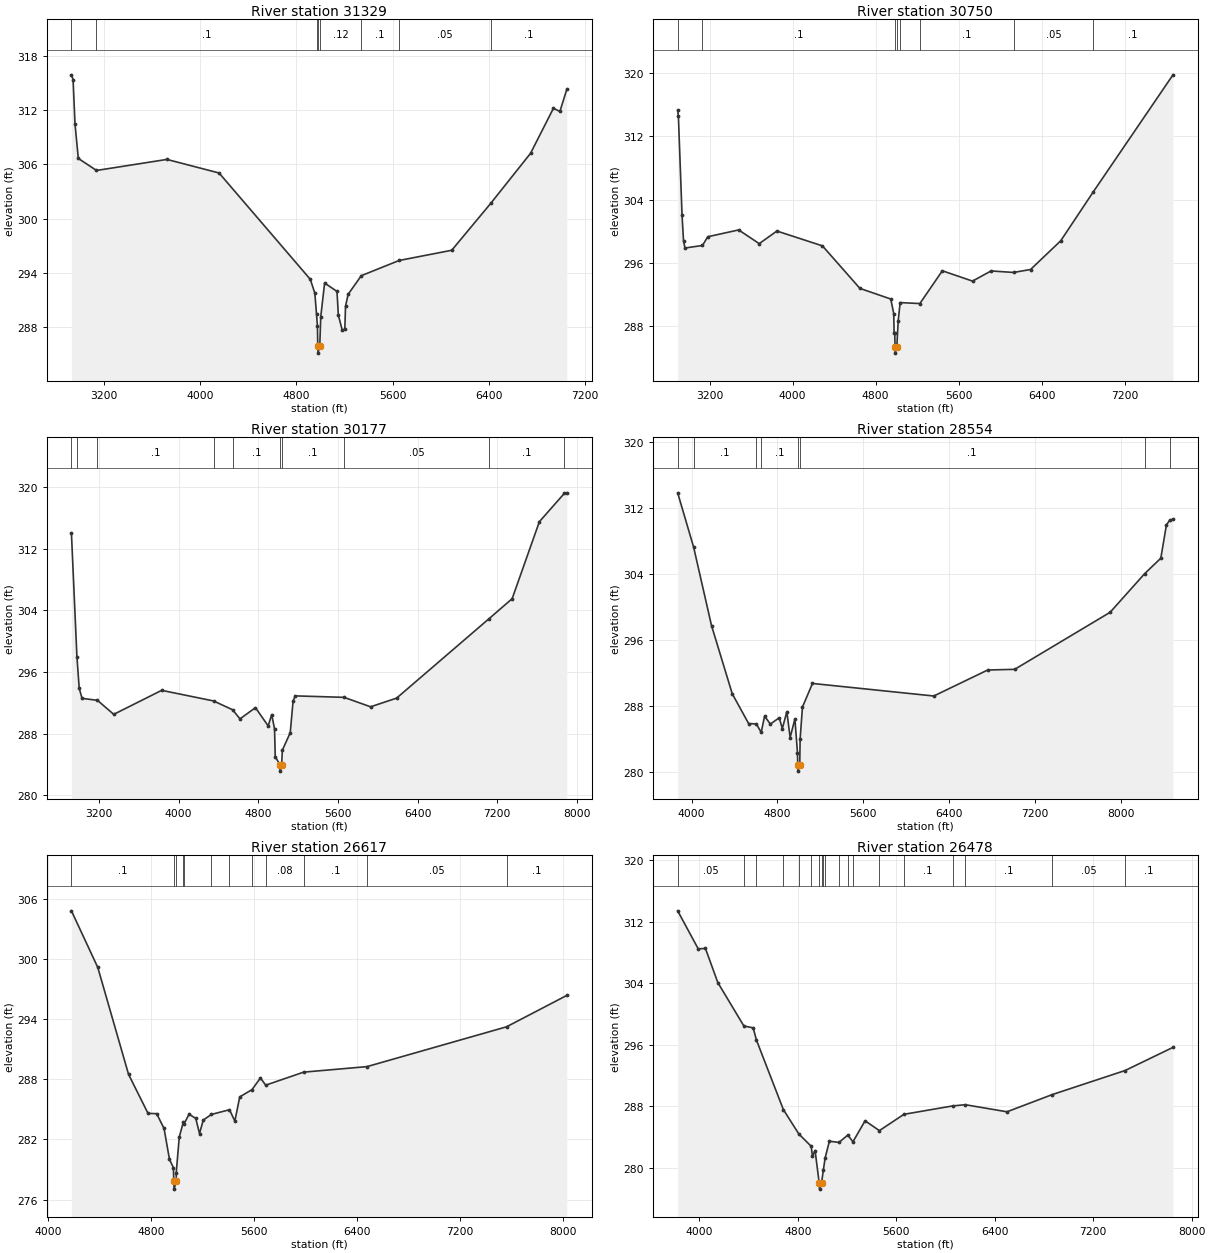
Type RM Length L Ch R = 1,31329,579,579,579
BEGIN DESCRIPTION:
La Jarita Creek 35.0
END DESCRIPTION:
XS GIS Cut Line= 3
      2123225.00     13415374.99      2122225.00     13413575.00
      2120425.04     13412575.02
#Sta/Elev= 30
  2930.1  315.91  2943.8  315.38  2959.8  310.48  2987.3  306.67  3138.5  305.34
  3724.0  306.56  4157.6  305.06  4916.0  293.31  4953.8  291.78  4967.7  289.46
  4975.5  288.15  4978.0  285.95  4980.0  285.15  4994.8  285.95  5002.9  289.16
  5035.0  292.90  5137.9  291.97  5149.4  289.35  5181.4  287.70  5203.1  287.80
  5208.9  290.33  5230.6  291.65  5340.1  293.71  5654.5  295.39  6092.0  296.52
  6415.3  301.69  6747.5  307.24  6937.4  312.21  6991.1  311.86  7048.3  314.29
#Mann=8,-1,0
  2930.1    0.05       0  3138.5     0.1       0  4967.7    0.12       0
  4978.0    0.07       0  4994.8    0.12       0  5340.1     0.1       0
  5654.5    0.05       0  6415.3     0.1       0
Bank Sta=4978,4994.8
Exp/Cntr=0.3,0.1

Type RM Length L Ch R = 1,30750,573,573,573
BEGIN DESCRIPTION:
La Jarita Creek 34.0
END DESCRIPTION:
XS GIS Cut Line= 3
      2124224.97     13414774.97      2122675.00     13413375.00
      2120275.00     13412175.00
#Sta/Elev= 30
  2893.0  315.23  2900.1  314.49  2935.2  302.05  2949.4  298.81  2963.6  297.89
  3131.8  298.21  3183.3  299.31  3480.7  300.17  3678.7  298.44  3849.1  300.03
  4287.8  298.16  4648.7  292.80  4946.1  291.46  4974.5  289.63  4978.2  287.17
  4984.4  287.17  4987.1  285.44  4989.2  284.64  5004.1  285.44  5018.0  288.75
  5036.3  291.01  5226.4  290.89  5442.8  295.02  5733.5  293.72  5912.4  295.00
  6128.6  294.81  6292.5  295.18  6583.2  298.80  6898.6  305.00  7664.9  319.72
#Mann=8,-1,0
  2893.0    0.05       0  3131.8     0.1       0  4987.1    0.07       0
  5004.1     0.1       0  5036.3    0.12       0  5226.4     0.1       0
  6128.6    0.05       0  6898.6     0.1       0
Bank Sta=4987.1,5004.1
Exp/Cntr=0.3,0.1

Type RM Length L Ch R = 1,30177,1623,1623,1623
BEGIN DESCRIPTION:
La Jarita Creek 33.0
END DESCRIPTION:
XS GIS Cut Line= 3
      2124474.99     13414624.99      2123075.00     13413075.00
      2120674.99     13411475.00
#Sta/Elev= 30
  2924.2  314.03  2979.4  297.98  3002.3  293.88  3030.7  292.58  3185.4  292.32
  3349.0  290.50  3830.3  293.62  4351.3  292.24  4543.0  291.09  4616.4  289.91
  4771.9  291.37  4899.6  288.99  4934.8  290.47  4963.2  288.63  4970.6  285.02
  5017.9  283.92  5020.0  283.12  5034.9  283.92  5041.4  285.83  5121.0  288.11
  5149.6  292.22  5170.6  292.90  5661.0  292.71  5927.8  291.48  6189.2  292.61
  7113.2  302.89  7348.9  305.53  7622.4  315.54  7874.4  319.24  7897.3  319.29
#Mann=10,-1,0
  2924.2     0.1       0  2979.4    0.05       0  3185.4     0.1       0
  4351.3    0.05       0  4543.0     0.1       0  5017.9    0.07       0
  5034.9     0.1       0  5661.0    0.05       0  7113.2     0.1       0
  7874.4    0.08       0
Bank Sta=5017.9,5034.9
Exp/Cntr=0.3,0.1

Type RM Length L Ch R = 1,28554,1937,1937,1937
BEGIN DESCRIPTION:
La Jarita Creek 32.0
END DESCRIPTION:
XS GIS Cut Line= 3
      2125375.03     13412975.01      2124275.00     13412775.00
      2121075.01     13411375.01
#Sta/Elev= 30
  3870.8  313.85  4019.6  307.26  4185.9  297.77  4379.0  289.51  4531.5  285.90
  4603.2  285.86  4648.3  284.84  4680.1  286.80  4733.5  285.84  4816.1  286.60
  4845.3  285.30  4887.2  287.34  4917.7  284.21  4962.2  286.46  4986.3  282.33
  4988.4  280.94  4990.9  280.14  5007.3  280.94  5010.7  284.02  5032.5  287.90
  5125.7  290.76  6255.0  289.24  6757.1  292.39  7008.2  292.47  7896.6  299.38
  8217.4  304.05  8368.3  305.93  8420.5  309.96  8452.4  310.56  8481.7  310.63
#Mann=8,-1,0
  3870.8    0.05       0  4019.6     0.1       0  4603.2    0.05       0
  4648.3     0.1       0  4988.4    0.07       0  5007.3     0.1       0
  8217.4    0.08       0  8452.4     0.1       0
Bank Sta=4988.4,5007.3
Exp/Cntr=0.3,0.1

Type RM Length L Ch R = 1,26617,139,139,139
BEGIN DESCRIPTION:
Mapping XS f4d4dc52
END DESCRIPTION:
XS GIS Cut Line= 6
      2125712.57     13412200.49      2125031.98     13411762.96
      2124406.98     13411492.13      2123809.75     13411450.46
      2123115.31     13411478.24      2122052.84     13411457.41
#Sta/Elev= 30
  4183.6  304.80  4388.3  299.15  4627.4  288.48  4778.7  284.59  4845.4  284.57
  4902.8  283.09  4945.1  280.01  4975.5  279.18  4978.5  277.84  4981.0  277.04
  4997.4  277.84  4997.5  278.69  5021.0  282.24  5051.9  283.69  5059.3  283.58
  5096.8  284.51  5149.2  284.10  5178.2  282.58  5207.4  283.93  5270.7  284.49
  5410.9  284.96  5452.7  283.83  5490.7  286.24  5586.1  286.97  5651.4  288.13
  5692.1  287.41  5987.0  288.71  6478.9  289.26  7562.3  293.23  8030.2  296.36
#Mann=12,-1,0
  4183.6     0.1       0  4978.5    0.07       0  4997.4     0.1       0
  5051.9    0.08       0  5059.3     0.1       0  5270.7    0.05       0
  5410.9     0.1       0  5586.1    0.05       0  5692.1    0.08       0
  5987.0     0.1       0  6478.9    0.05       0  7562.3     0.1       0
Bank Sta=4978.5,4997.4
Exp/Cntr=0.3,0.1

Type RM Length L Ch R = 1,26478,780,780,780
BEGIN DESCRIPTION:
Mapping XS 163a5a5f
END DESCRIPTION:
XS GIS Cut Line= 5
      2126163.93     13412110.19      2125483.37     13411887.96
      2124768.09     13411450.46      2124080.59     13411311.57
      2122372.28     13410853.25
#Sta/Elev= 30
  3823.9  313.40  3991.1  308.45  4049.5  308.51  4150.4  304.06  4362.0  298.42
  4437.4  298.18  4464.4  296.57  4682.6  287.55  4808.2  284.38  4908.8  282.77
  4919.0  281.51  4940.4  282.22  4973.9  278.00  4976.4  277.20  4992.8  278.00
  5007.3  279.64  5021.9  281.25  5056.5  283.43  5134.9  283.28  5206.4  284.23
  5248.0  283.36  5346.7  286.09  5462.8  284.81  5662.1  286.93  6057.0  288.02
  6161.3  288.18  6499.6  287.26  6867.7  289.50  7459.4  292.63  7848.4  295.64
#Mann=19,-1,0
  3823.9    0.05       0  4362.0     0.1       0  4464.4    0.05       0
  4682.6    0.08       0  4808.2    0.05       0  4908.8    0.08       0
  4973.9    0.07       0  4992.8    0.08       0  5007.3    0.05       0
  5021.9     0.1       0  5134.9    0.08       0  5206.4    0.05       0
  5248.0    0.08       0  5462.8    0.05       0  5662.1     0.1       0
  6057.0    0.05       0  6161.3     0.1       0  6867.7    0.05       0
  7459.4     0.1       0
Bank Sta=4973.9,4992.8
Exp/Cntr=0.3,0.1

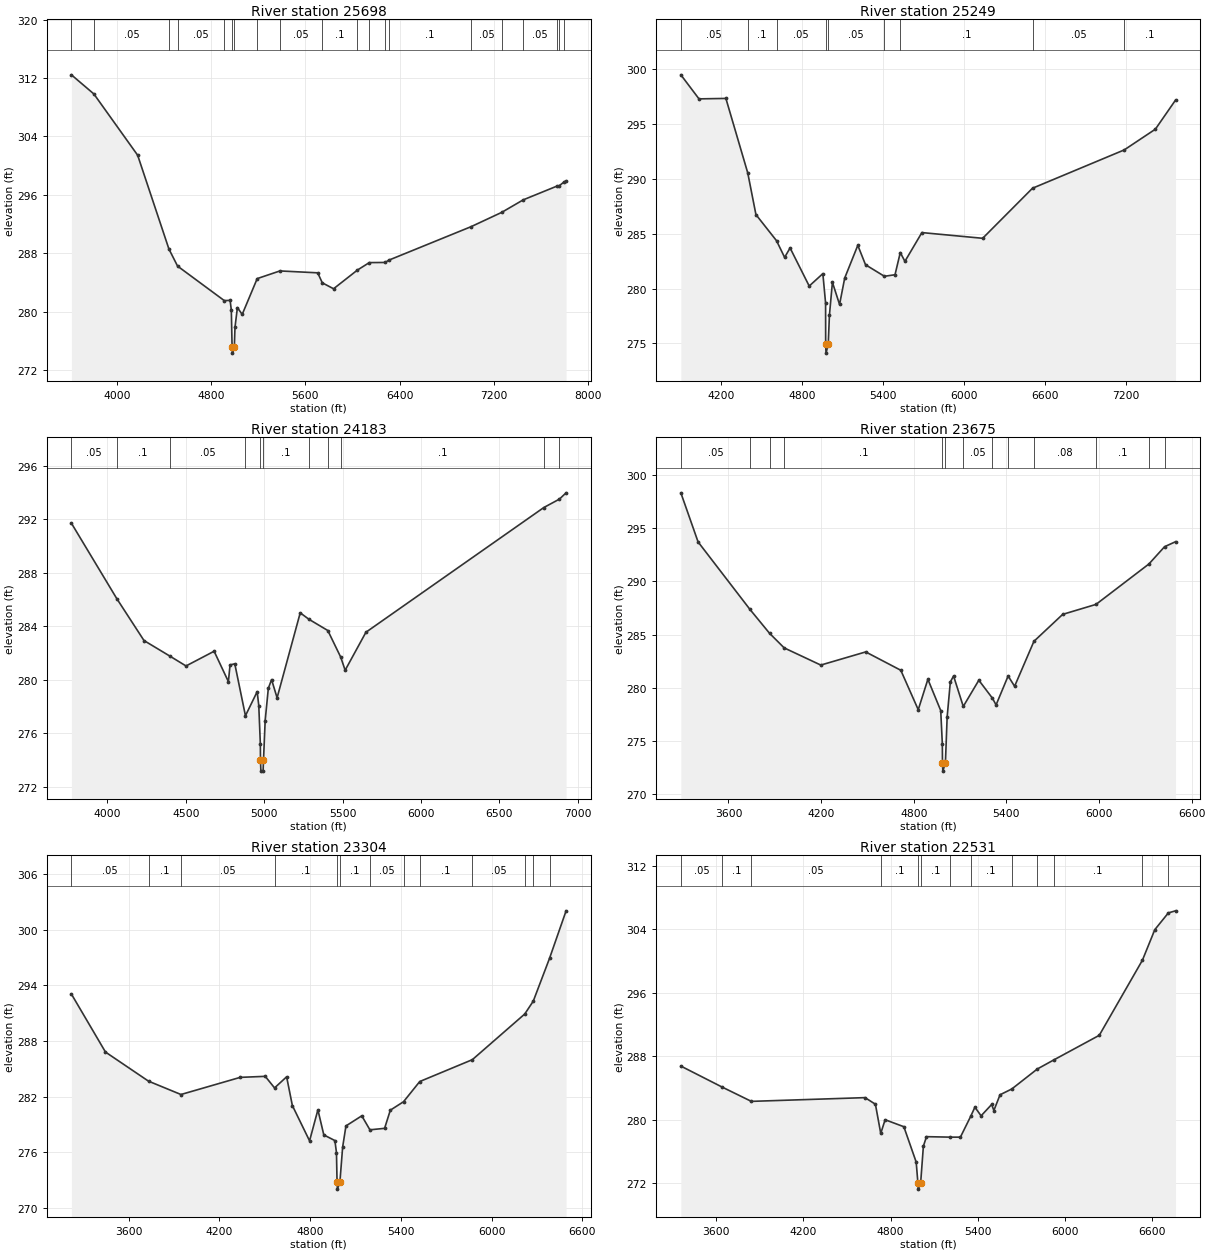
Type RM Length L Ch R = 1,25698,449,449,449
BEGIN DESCRIPTION:
Mapping XS 665c02e5
END DESCRIPTION:
XS GIS Cut Line= 3
      2126469.45     13411290.73      2123920.87     13410637.96
      2122400.07     13410262.97
#Sta/Elev= 30
  3615.4  312.43  3806.2  309.81  4177.4  301.43  4442.8  288.59  4516.2  286.25
  4912.4  281.53  4962.0  281.56  4972.3  280.22  4978.8  275.14  4981.3  274.34
  4997.7  275.14  5003.3  277.86  5023.8  280.57  5064.6  279.64  5191.9  284.54
  5384.8  285.59  5705.2  285.33  5744.2  283.96  5839.8  283.15  6042.3  285.71
  6143.0  286.73  6279.1  286.75  6306.4  287.05  7006.9  291.65  7265.8  293.60
  7449.1  295.32  7736.6  297.21  7751.3  297.21  7794.3  297.75  7812.6  297.90
#Mann=20,-1,0
  3615.4     0.1       0  3806.2    0.05       0  4442.8     0.1       0
  4516.2    0.05       0  4912.4     0.1       0  4978.8    0.07       0
  4997.7     0.1       0  5191.9    0.08       0  5384.8    0.05       0
  5744.2     0.1       0  6042.3    0.05       0  6143.0     0.1       0
  6279.1    0.05       0  6306.4     0.1       0  7006.9    0.05       0
  7265.8     0.1       0  7449.1    0.05       0  7736.6     0.1       0
  7751.3    0.05       0  7794.3     0.1       0
Bank Sta=4978.8,4997.7
Exp/Cntr=0.3,0.1

Type RM Length L Ch R = 1,25249,1066,1066,1066
BEGIN DESCRIPTION:
Mapping XS 1a37cd5e
END DESCRIPTION:
XS GIS Cut Line= 3
      2126434.73     13410749.07      2125101.42     13410554.63
      2122893.08     13409867.13
#Sta/Elev= 30
  3904.6  299.47  4038.8  297.28  4237.8  297.32  4399.7  290.53  4460.1  286.74
  4612.5  284.36  4672.4  282.84  4712.8  283.70  4854.3  280.23  4955.3  281.36
  4975.5  278.68  4976.2  274.92  4978.7  274.12  4995.1  274.92  5003.9  277.57
  5026.1  280.57  5078.9  278.55  5117.0  280.96  5213.9  283.94  5271.0  282.17
  5410.6  281.12  5489.2  281.26  5528.2  283.28  5562.5  282.48  5688.1  285.10
  6137.8  284.58  6506.5  289.14  7185.2  292.63  7415.8  294.52  7564.9  297.17
#Mann=9,-1,0
  3904.6    0.05       0  4399.7     0.1       0  4612.5    0.05       0
  4976.2    0.07       0  4995.1    0.05       0  5410.6    0.08       0
  5528.2     0.1       0  6506.5    0.05       0  7185.2     0.1       0
Bank Sta=4976.2,4995.1
Exp/Cntr=0.3,0.1

Type RM Length L Ch R = 1,24183,508,508,508
BEGIN DESCRIPTION:
Mapping XS 789518c5
END DESCRIPTION:
XS GIS Cut Line= 3
      2126330.62     13410457.42      2125566.70     13410047.69
      2123323.63     13409596.29
#Sta/Elev= 30
  3770.1  291.71  4059.1  286.08  4233.1  282.94  4396.2  281.79  4501.1  281.04
  4680.3  282.14  4771.3  279.87  4782.0  281.12  4812.1  281.20  4880.1  277.32
  4954.9  279.12  4965.1  278.08  4975.1  275.21  4976.0  273.98  4978.5  273.18
  4992.6  273.18  4995.1  273.98  5005.9  276.96  5026.0  279.37  5046.7  280.02
  5081.9  278.66  5229.4  285.01  5284.9  284.53  5405.3  283.69  5487.7  281.70
  5515.9  280.72  5648.5  283.56  6782.8  292.88  6882.4  293.51  6925.0  293.98
#Mann=11,-1,0
  3770.1    0.05       0  4059.1     0.1       0  4396.2    0.05       0
  4880.1     0.1       0  4976.0    0.07       0  4995.1     0.1       0
  5284.9    0.08       0  5405.3    0.05       0  5487.7     0.1       0
  6782.8    0.08       0  6882.4     0.1       0
Bank Sta=4976,4995.1
Exp/Cntr=0.3,0.1

Type RM Length L Ch R = 1,23675,371,371,371
BEGIN DESCRIPTION:
Mapping XS 03964f7b
END DESCRIPTION:
XS GIS Cut Line= 3
      2126577.97     13410559.83      2125425.33     13409574.39
      2123802.79     13409110.18
#Sta/Elev= 30
  3291.6  298.36  3403.2  293.73  3738.5  287.38  3865.8  285.12  3960.8  283.74
  4198.0  282.12  4488.9  283.36  4716.2  281.63  4829.2  277.91  4891.6  280.78
  4974.8  277.83  4985.2  274.68  4986.1  272.92  4988.6  272.12  5005.2  272.92
  5016.4  277.23  5037.1  280.53  5058.0  281.09  5120.8  278.22  5221.6  280.69
  5310.0  278.99  5333.3  278.36  5411.3  281.09  5453.3  280.12  5578.5  284.36
  5764.7  286.90  5980.4  287.84  6323.2  291.65  6424.6  293.28  6495.7  293.75
#Mann=13,-1,0
  3291.6    0.05       0  3738.5     0.1       0  3865.8    0.05       0
  3960.8     0.1       0  4986.1    0.07       0  5005.2     0.1       0
  5120.8    0.05       0  5310.0    0.08       0  5411.3     0.1       0
  5578.5    0.08       0  5980.4     0.1       0  6323.2    0.05       0
  6424.6     0.1       0
Bank Sta=4986.1,5005.2
Exp/Cntr=0.3,0.1

Type RM Length L Ch R = 1,23304,773,773,773
BEGIN DESCRIPTION:
Mapping XS 1a1d2500
END DESCRIPTION:
XS GIS Cut Line= 4
      2126726.44     13410242.15      2125886.14     13409360.19
      2125004.20     13409089.35      2123983.40     13408603.26
#Sta/Elev= 30
  3220.8  293.06  3446.2  286.80  3730.7  283.66  3945.3  282.22  4337.2  284.07
  4502.7  284.18  4564.3  282.93  4644.1  284.13  4682.0  281.03  4795.8  277.22
  4850.9  280.57  4890.0  277.86  4963.2  277.25  4973.7  275.96  4977.5  272.81
  4980.0  272.01  4996.6  272.81  5014.5  276.54  5036.4  278.83  5141.1  279.92
  5194.8  278.41  5292.0  278.57  5329.9  280.53  5417.1  281.44  5524.4  283.62
  5872.4  285.98  6219.0  290.91  6275.3  292.30  6382.6  296.91  6492.2  302.04
#Mann=13,-1,0
  3220.8    0.05       0  3730.7     0.1       0  3945.3    0.05       0
  4564.3     0.1       0  4977.5    0.07       0  4996.6     0.1       0
  5194.8    0.05       0  5417.1    0.08       0  5524.4     0.1       0
  5872.4    0.05       0  6219.0     0.1       0  6275.3    0.05       0
  6382.6     0.1       0
Bank Sta=4977.5,4996.6
Exp/Cntr=0.3,0.1

Type RM Length L Ch R = 1,22531,83,83,83
BEGIN DESCRIPTION:
Mapping XS 6e60bc44
END DESCRIPTION:
XS GIS Cut Line= 6
      2126691.70     13410019.91      2125795.87     13409096.30
      2125601.42     13408971.30      2125420.87     13408797.69
      2125254.20     13408631.02      2124073.62     13407881.01
#Sta/Elev= 30
  3356.7  286.77  3639.4  284.14  3841.7  282.33  4623.7  282.80  4695.0  281.97
  4731.7  278.30  4761.7  280.02  4890.6  279.14  4975.5  274.69  4987.1  272.09
  4989.6  271.29  5006.2  272.09  5024.9  276.69  5046.3  277.89  5208.3  277.83
  5279.6  277.83  5349.9  280.43  5379.4  281.60  5421.8  280.51  5494.6  281.94
  5509.8  281.18  5552.2  283.16  5633.2  283.89  5808.4  286.40  5922.6  287.55
  6234.8  290.64  6531.6  300.09  6616.8  303.93  6709.9  306.04  6759.4  306.30
#Mann=13,-1,0
  3356.7    0.05       0  3639.4     0.1       0  3841.7    0.05       0
  4731.7     0.1       0  4987.1    0.07       0  5006.2     0.1       0
  5208.3    0.05       0  5349.9     0.1       0  5633.2    0.08       0
  5808.4    0.05       0  5922.6     0.1       0  6531.6    0.05       0
  6709.9     0.1       0
Bank Sta=4987.1,5006.2
Exp/Cntr=0.3,0.1

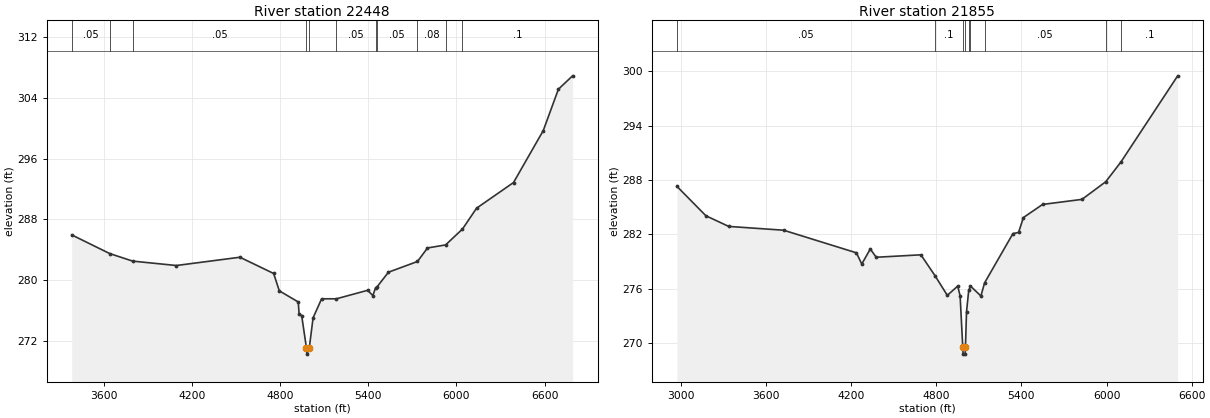
Type RM Length L Ch R = 1,22448,593,593,593
BEGIN DESCRIPTION:
Mapping XS 1b70e450
END DESCRIPTION:
XS GIS Cut Line= 6
      2126670.89     13409971.32      2125809.75     13408943.52
      2125420.87     13408721.30      2125330.59     13408554.63
      2125143.09     13408387.96      2124156.99     13407749.08
#Sta/Elev= 30
  3383.2  285.97  3641.9  283.51  3797.7  282.52  4095.1  281.94  4527.1  283.03
  4756.8  280.89  4795.1  278.61  4924.1  277.14  4929.6  275.58  4947.3  275.35
  4979.8  271.08  4982.3  270.28  4998.9  271.08  5024.9  275.06  5082.9  277.56
  5183.5  277.56  5396.1  278.68  5431.2  277.98  5449.9  279.01  5457.8  279.08
  5537.4  281.06  5734.8  282.47  5803.0  284.25  5926.2  284.65  6041.0  286.74
  6136.6  289.48  6388.1  292.86  6590.5  299.70  6693.3  305.14  6789.6  306.90
#Mann=11,-1,0
  3383.2    0.05       0  3641.9     0.1       0  3797.7    0.05       0
  4979.8    0.07       0  4998.9    0.05       0  5183.5    0.05       0
  5449.9     0.1       0  5457.8    0.05       0  5734.8    0.08       0
  5926.2    0.05       0  6041.0     0.1       0
Bank Sta=4979.8,4998.9
Exp/Cntr=0.3,0.1

Type RM Length L Ch R = 1,21855,340,340,340
BEGIN DESCRIPTION:
Mapping XS 87e444d6
END DESCRIPTION:
XS GIS Cut Line= 4
      2126729.90     13410026.01      2126139.62     13408498.21
      2125314.96     13408098.90      2124433.89     13407677.90
#Sta/Elev= 30
  2971.0  287.31  3175.8  284.05  3336.7  282.87  3723.9  282.45  4237.1  279.95
  4274.7  278.71  4334.6  280.37  4376.5  279.46  4691.4  279.73  4791.1  277.42
  4877.6  275.25  4950.9  276.27  4967.9  275.19  4986.5  269.55  4989.0  268.75
  5003.1  268.75  5005.6  269.55  5013.1  273.43  5028.5  275.79  5041.0  276.27
  5114.6  275.18  5140.4  276.63  5340.4  282.08  5380.0  282.20  5414.0  283.85
  5549.3  285.30  5827.0  285.86  5994.5  287.81  6101.8  290.00  6501.6  299.52
#Mann=9,-1,0
  2971.0    0.05       0  4791.1     0.1       0  4986.5    0.07       0
  5005.6     0.1       0  5028.5    0.12       0  5041.0     0.1       0
  5140.4    0.05       0  5994.5    0.08       0  6101.8     0.1       0
Bank Sta=4986.5,5005.6
Exp/Cntr=0.3,0.1