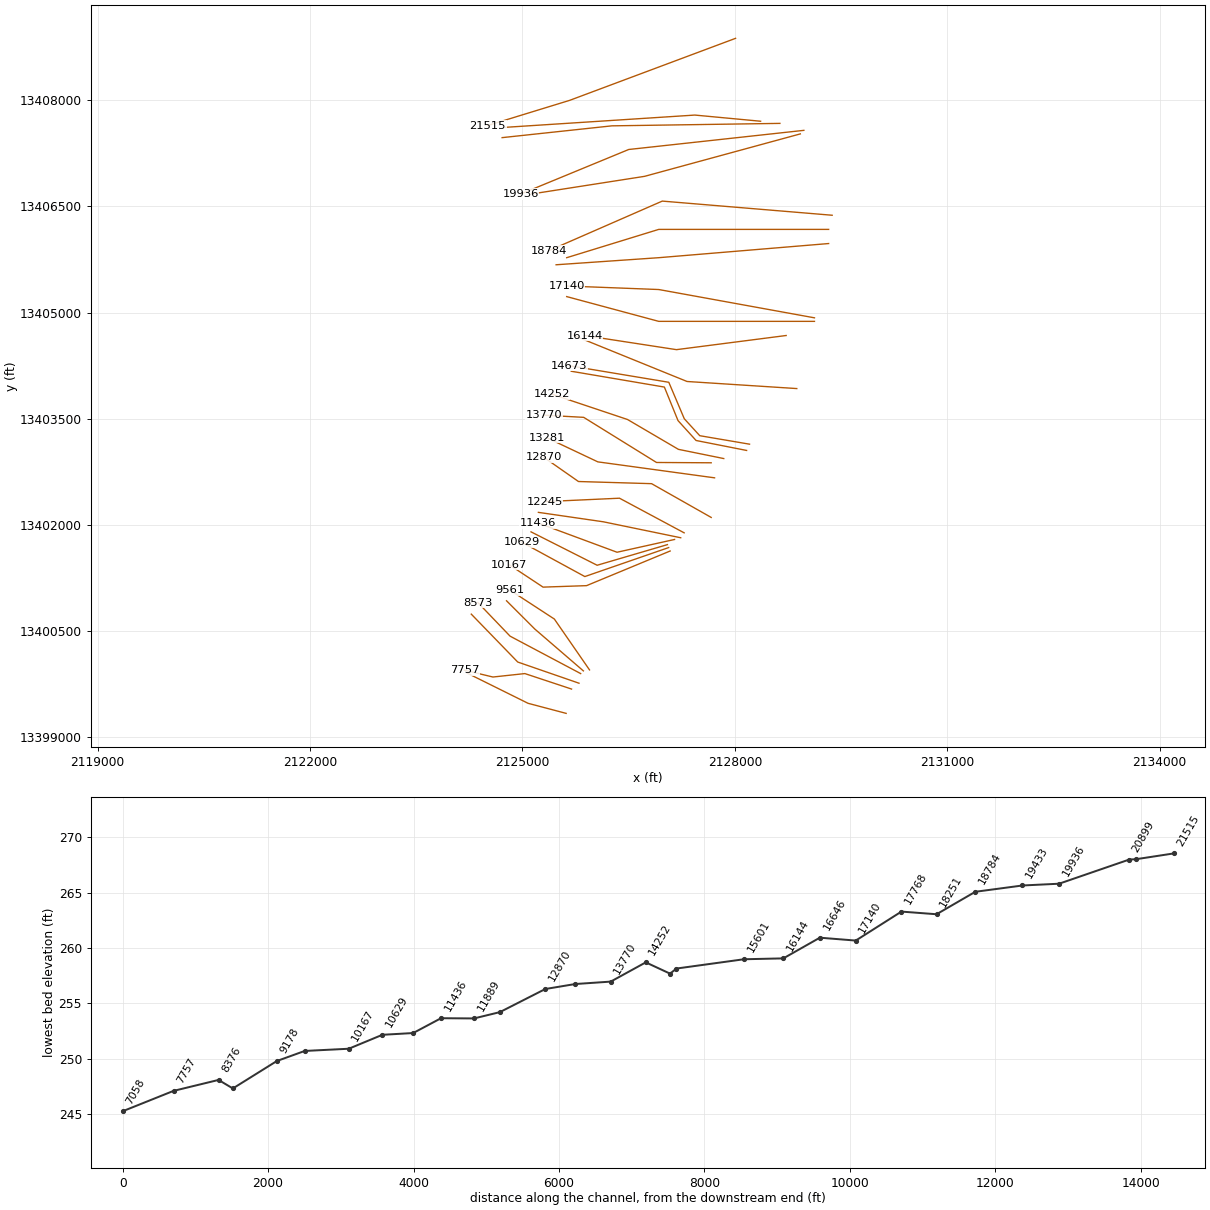
HEC-RAS study La Jarita Creek.prj: La Jarita Creek Base Level Engineering

--- La Jarita Creek.g01 (geometry) --- (continued)

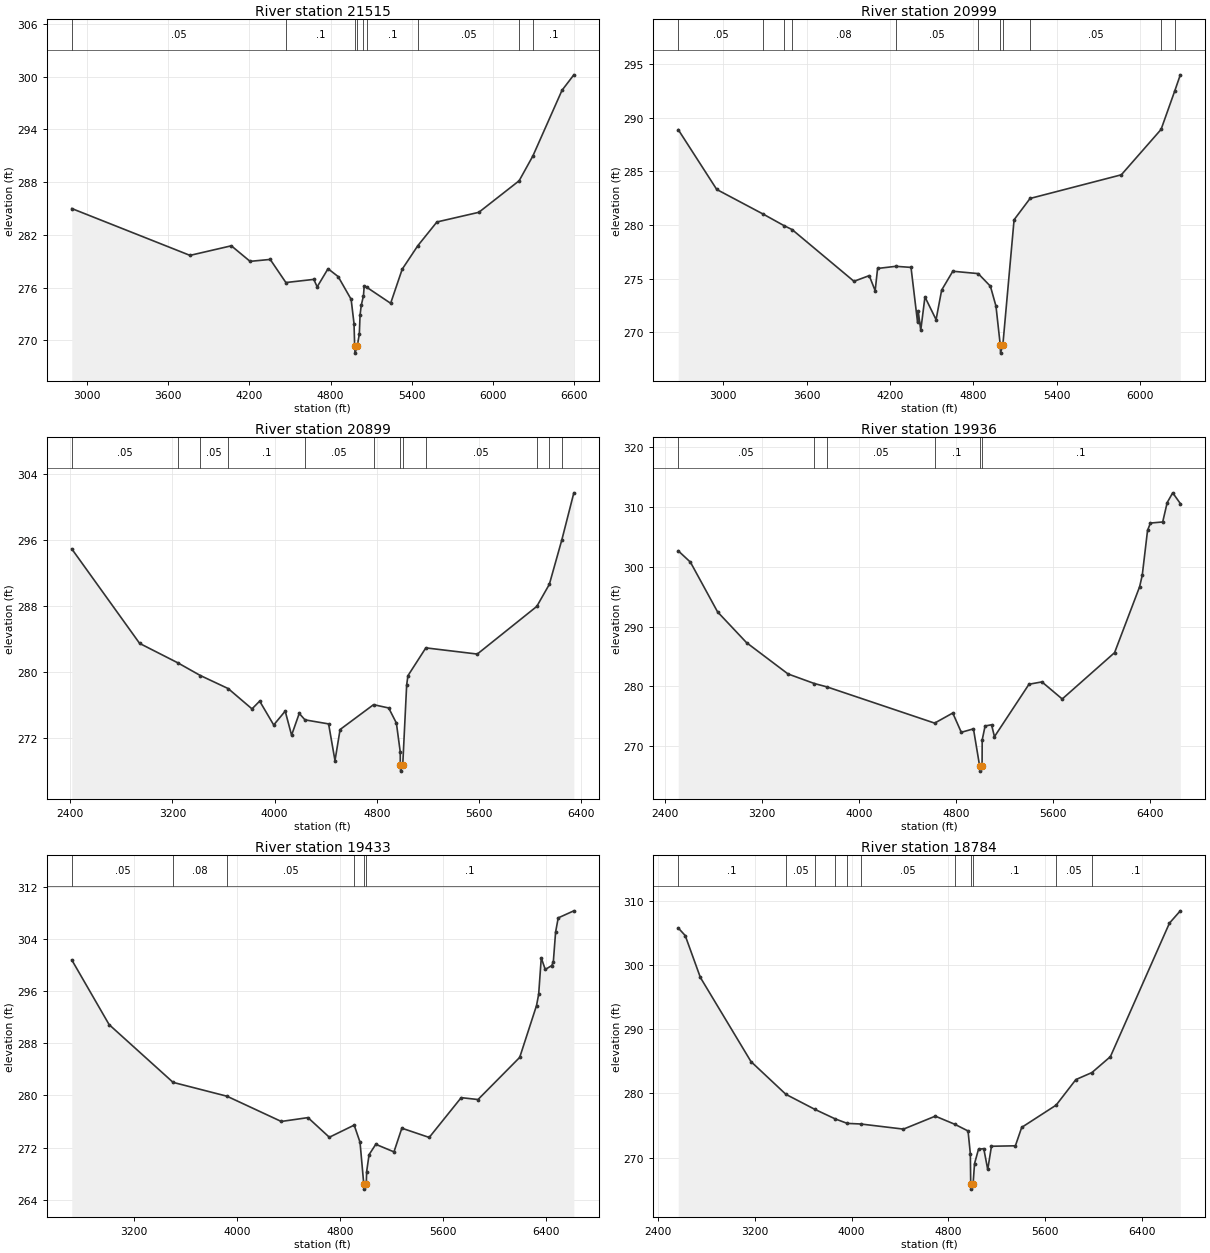
Type RM Length L Ch R = 1,21515,516,516,516
BEGIN DESCRIPTION:
Mapping XS b2d7994c
END DESCRIPTION:
XS GIS Cut Line= 3
      2128010.31     13408875.82      2125666.52     13407999.07
      2124508.80     13407643.52
#Sta/Elev= 30
  2885.9  285.00  3760.3  279.67  4066.0  280.76  4204.8  278.99  4353.6  279.21
  4469.5  276.58  4676.0  276.94  4701.0  276.09  4781.2  278.15  4856.1  277.26
  4952.2  274.67  4973.5  271.91  4978.3  269.35  4980.8  268.55  4997.4  269.35
  5012.8  270.72  5018.1  272.86  5026.9  273.98  5043.5  275.09  5048.4  276.13
  5068.7  276.03  5244.4  274.22  5329.9  278.10  5445.3  280.77  5586.5  283.47
  5896.7  284.57  6194.8  288.16  6296.7  290.99  6511.8  298.45  6599.4  300.21
#Mann=9,-1,0
  2885.9    0.05       0  4469.5     0.1       0  4978.3    0.07       0
  4997.4     0.1       0  5043.5    0.12       0  5068.7     0.1       0
  5445.3    0.05       0  6194.8    0.08       0  6296.7     0.1       0
Bank Sta=4978.3,4997.4
Exp/Cntr=0.3,0.1

Type RM Length L Ch R = 1,20999,100,100,100
BEGIN DESCRIPTION:
Mapping XS d7fef3cb
END DESCRIPTION:
XS GIS Cut Line= 3
      2128364.04     13407703.93      2127435.16     13407791.11
      2124761.62     13407618.00
#Sta/Elev= 30
  2676.5  288.91  2953.6  283.32  3288.9  281.01  3436.2  279.95  3496.0  279.57
  3940.8  274.74  4050.5  275.27  4093.3  273.86  4110.7  275.94  4241.9  276.14
  4351.2  276.04  4398.4  270.90  4403.4  271.92  4421.3  270.17  4451.4  273.28
  4531.5  271.16  4571.6  273.92  4651.8  275.68  4834.6  275.46  4922.4  274.28
  4962.4  272.42  4992.9  268.83  4995.4  268.03  5012.1  268.83  5092.7  280.49
  5207.7  282.48  5864.3  284.69  6150.2  288.93  6248.5  292.52  6288.6  294.03
#Mann=11,-1,0
  2676.5    0.05       0  3288.9    0.08       0  3436.2    0.05       0
  3496.0    0.08       0  4241.9    0.05       0  4834.6     0.1       0
  4992.9    0.07       0  5012.1     0.1       0  5207.7    0.05       0
  6150.2    0.08       0  6248.5     0.1       0
Bank Sta=4992.9,5012.1
Exp/Cntr=0.3,0.1

Type RM Length L Ch R = 1,20899,963,963,963
BEGIN DESCRIPTION:
Mapping XS dc6ab202
END DESCRIPTION:
XS GIS Cut Line= 3
      2128636.61     13407673.55      2126263.31     13407638.83
      2124712.99     13407472.17
#Sta/Elev= 30
  2411.4  294.91  2943.1  283.46  3240.6  281.12  3418.7  279.57  3636.6  277.99
  3823.2  275.53  3883.2  276.47  3993.2  273.58  4083.2  275.26  4133.2  272.34
  4193.2  274.98  4238.2  274.20  4423.2  273.71  4473.2  269.26  4513.2  273.03
  4775.2  276.04  4893.9  275.64  4954.2  273.81  4984.4  270.31  4984.9  268.79
  4987.4  267.99  5004.1  268.79  5034.7  278.43  5044.7  279.55  5184.9  282.92
  5587.9  282.17  6053.8  287.94  6152.3  290.62  6250.8  296.04  6344.2  301.70
#Mann=12,-1,0
  2411.4    0.05       0  3240.6    0.08       0  3418.7    0.05       0
  3636.6     0.1       0  4238.2    0.05       0  4775.2     0.1       0
  4984.9    0.07       0  5004.1     0.1       0  5184.9    0.05       0
  6053.8     0.1       0  6152.3    0.08       0  6250.8     0.1       0
Bank Sta=4984.9,5004.1
Exp/Cntr=0.3,0.1

Type RM Length L Ch R = 1,19936,503,503,503
BEGIN DESCRIPTION:
La Jarita Creek 22.0
END DESCRIPTION:
XS GIS Cut Line= 3
      2128974.96     13407575.00      2126500.80     13407304.54
      2124974.97     13406674.99
#Sta/Elev= 30
  2511.1  302.70  2611.7  300.80  2835.6  292.47  3074.4  287.32  3416.4  282.08
  3633.0  280.48  3738.3  279.91  4625.0  273.85  4774.5  275.54  4844.9  272.31
  4945.1  272.89  4996.5  266.61  4999.0  265.81  5016.1  266.61  5017.2  271.03
  5041.1  273.37  5094.4  273.57  5118.3  271.58  5403.1  280.36  5509.7  280.75
  5677.0  277.89  6108.7  285.65  6315.2  296.69  6336.9  298.62  6380.4  306.12
  6404.3  307.35  6505.4  307.53  6542.4  310.78  6588.0  312.41  6650.6  310.62
#Mann=6,-1,0
  2511.1    0.05       0  3633.0    0.08       0  3738.3    0.05       0
  4625.0     0.1       0  4996.5    0.07       0  5016.1     0.1       0
Bank Sta=4996.5,5016.1
Exp/Cntr=0.3,0.1

Type RM Length L Ch R = 1,19433,649,649,649
BEGIN DESCRIPTION:
La Jarita Creek 21.0
END DESCRIPTION:
XS GIS Cut Line= 3
      2128924.97     13407524.99      2126725.00     13406925.00
      2125125.03     13406675.00
#Sta/Elev= 30
  2715.6  300.78  3005.8  290.86  3502.6  282.01  3920.9  279.89  4342.9  276.02
  4550.2  276.61  4716.1  273.60  4909.2  275.46  4954.5  272.84  4983.5  266.45
  4986.0  265.65  5003.1  266.45  5006.0  268.34  5024.8  270.93  5076.9  272.52
  5218.1  271.36  5279.3  274.99  5491.9  273.57  5740.3  279.67  5870.9  279.38
  6194.8  285.84  6325.4  293.78  6342.1  295.51  6362.3  301.09  6393.2  299.31
  6443.3  299.91  6455.9  300.46  6473.6  305.05  6493.9  307.22  6615.3  308.30
#Mann=6,-1,0
  2715.6    0.05       0  3502.6    0.08       0  3920.9    0.05       0
  4909.2     0.1       0  4983.5    0.07       0  5003.1     0.1       0
Bank Sta=4983.5,5003.1
Exp/Cntr=0.3,0.1

Type RM Length L Ch R = 1,18784,533,533,533
BEGIN DESCRIPTION:
La Jarita Creek 20.0
END DESCRIPTION:
XS GIS Cut Line= 3
      2129374.96     13406375.00      2126975.00     13406575.00
      2125375.00     13405875.00
#Sta/Elev= 30
  2565.4  305.77  2623.1  304.59  2748.5  298.06  3167.4  284.95  3456.3  279.85
  3695.8  277.51  3865.8  276.01  3964.7  275.32  4074.7  275.23  4429.3  274.43
  4692.7  276.45  4854.4  275.18  4963.6  274.14  4982.6  270.58  4985.7  265.88
  4988.2  265.08  5005.3  265.88  5017.3  269.06  5050.1  271.29  5093.7  271.39
  5126.5  268.14  5157.3  271.76  5355.3  271.83  5407.6  274.70  5692.7  278.17
  5855.9  282.15  5988.6  283.24  6141.6  285.72  6630.1  306.52  6720.1  308.44
#Mann=11,-1,0
  2565.4     0.1       0  3456.3    0.05       0  3695.8     0.1       0
  3865.8    0.05       0  3964.7     0.1       0  4074.7    0.05       0
  4854.4     0.1       0  4985.7    0.07       0  5005.3     0.1       0
  5692.7    0.05       0  5988.6     0.1       0
Bank Sta=4985.7,5005.3
Exp/Cntr=0.3,0.1

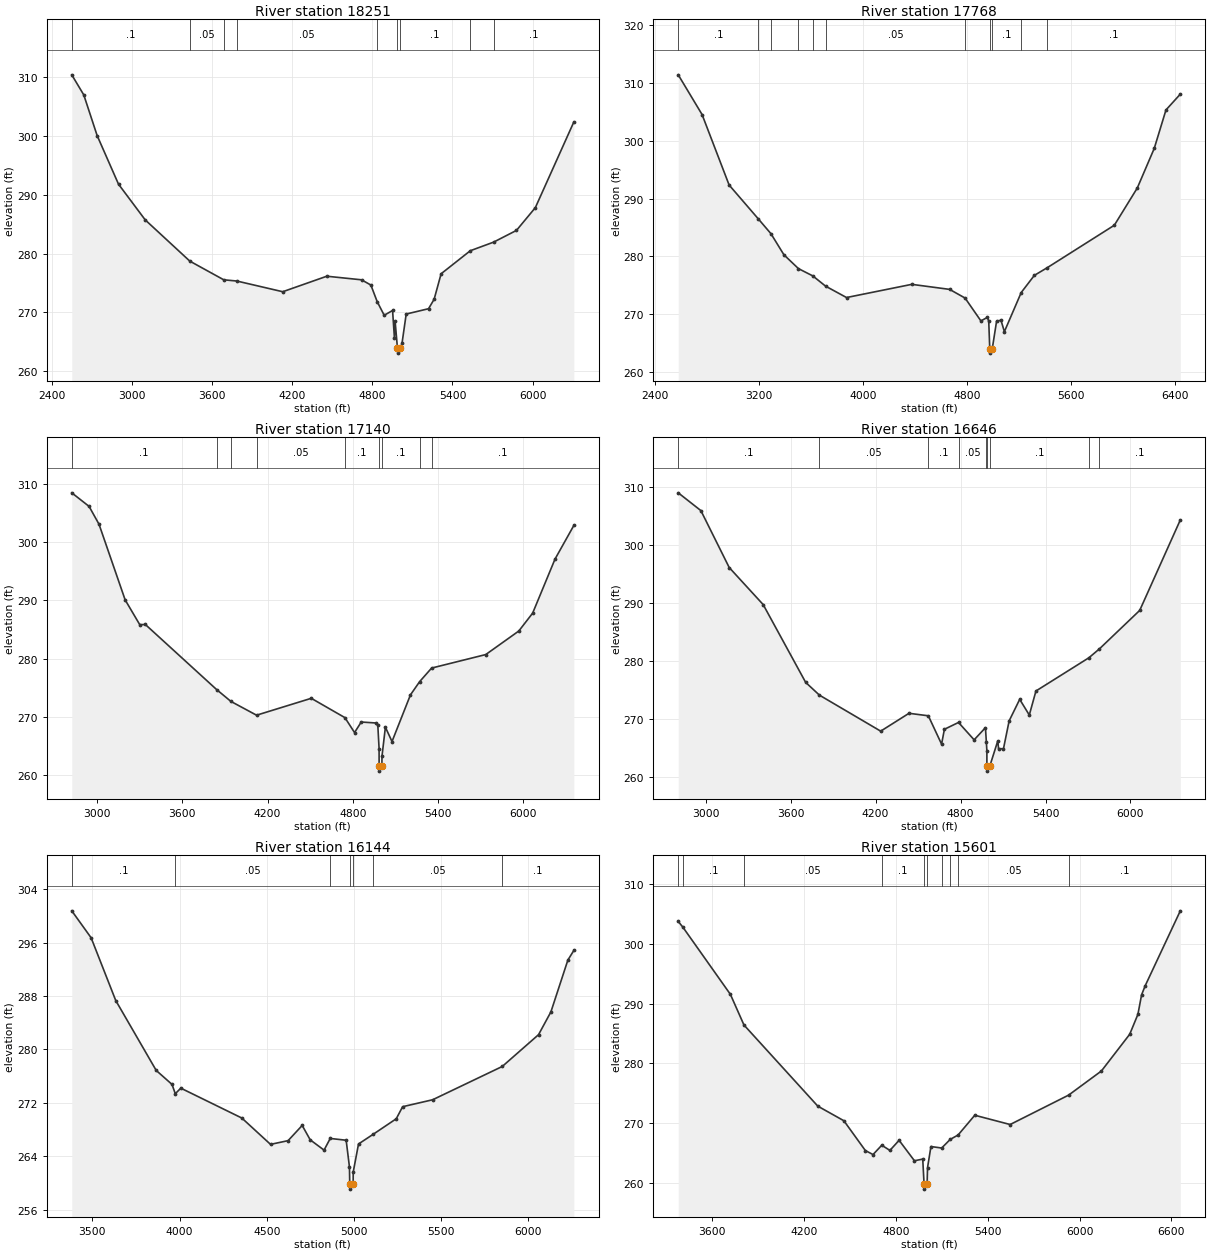
Type RM Length L Ch R = 1,18251,483,483,483
BEGIN DESCRIPTION:
La Jarita Creek 19.0
END DESCRIPTION:
XS GIS Cut Line= 3
      2129325.01     13406175.00      2126925.00     13406175.00
      2125624.96     13405774.99
#Sta/Elev= 30
  2549.0  310.42  2639.0  307.00  2739.0  300.08  2899.0  291.81  3099.0  285.73
  3433.1  278.71  3687.3  275.53  3785.6  275.32  4129.0  273.50  4459.0  276.14
  4719.0  275.53  4789.0  274.64  4836.4  271.81  4889.0  269.49  4951.6  270.31
  4965.4  265.66  4970.6  268.48  4988.3  263.85  4990.8  263.05  5007.9  263.85
  5022.2  264.70  5053.6  269.70  5221.0  270.61  5262.9  272.22  5315.2  276.56
  5533.8  280.48  5708.0  281.94  5879.5  283.94  6020.8  287.81  6309.2  302.40
#Mann=9,-1,0
  2549.0     0.1       0  3433.1    0.05       0  3687.3    0.08       0
  3785.6    0.05       0  4836.4     0.1       0  4988.3    0.07       0
  5007.9     0.1       0  5533.8    0.05       0  5708.0     0.1       0
Bank Sta=4988.3,5007.9
Exp/Cntr=0.3,0.1

Type RM Length L Ch R = 1,17768,628,628,628
BEGIN DESCRIPTION:
La Jarita Creek 18.0
END DESCRIPTION:
XS GIS Cut Line= 3
      2129325.05     13405975.00      2126925.00     13405775.00
      2125475.01     13405675.00
#Sta/Elev= 30
  2577.4  311.40  2760.6  304.54  2968.8  292.35  3194.7  286.46  3290.4  283.94
  3390.3  280.29  3502.0  277.90  3612.4  276.64  3710.7  274.87  3871.9  272.90
  4373.7  275.18  4664.7  274.31  4783.7  272.81  4905.5  268.86  4955.7  269.48
  4965.7  268.79  4973.5  264.09  4976.0  263.29  4993.1  264.09  5025.9  268.79
  5059.7  268.98  5086.0  267.00  5215.6  273.77  5316.5  276.73  5417.3  278.08
  5931.8  285.40  6108.4  291.84  6238.7  298.68  6328.9  305.33  6439.2  308.06
#Mann=11,-1,0
  2577.4     0.1       0  3194.7    0.05       0  3290.4     0.1       0
  3502.0    0.05       0  3612.4    0.08       0  3710.7    0.05       0
  4783.7     0.1       0  4973.5    0.07       0  4993.1     0.1       0
  5215.6    0.05       0  5417.3     0.1       0
Bank Sta=4973.5,4993.1
Exp/Cntr=0.3,0.1

Type RM Length L Ch R = 1,17140,494,494,494
BEGIN DESCRIPTION:
La Jarita Creek 17.0
END DESCRIPTION:
XS GIS Cut Line= 3
      2129125.04     13404924.99      2126925.00     13405325.00
      2125624.97     13405375.00
#Sta/Elev= 30
  2820.6  308.44  2942.6  306.11  3012.5  303.05  3196.7  290.06  3299.6  285.81
  3339.0  285.84  3841.1  274.67  3941.6  272.64  4122.4  270.27  4507.9  273.17
  4745.0  269.85  4812.8  267.29  4859.8  269.10  4965.2  268.93  4976.7  268.52
  4985.6  264.55  4985.9  261.47  4988.4  260.67  5005.5  261.47  5005.9  263.19
  5030.0  268.21  5076.7  265.75  5206.8  273.77  5271.4  276.03  5355.6  278.36
  5737.2  280.68  5969.9  284.72  6067.5  287.79  6225.1  297.07  6357.7  302.84
#Mann=9,-1,0
  2820.6     0.1       0  3841.1    0.08       0  3941.6     0.1       0
  4122.4    0.05       0  4745.0     0.1       0  4985.9    0.07       0
  5005.5     0.1       0  5271.4    0.05       0  5355.6     0.1       0
Bank Sta=4985.9,5005.5
Exp/Cntr=0.3,0.1

Type RM Length L Ch R = 1,16646,502,502,502
BEGIN DESCRIPTION:
La Jarita Creek 16.0
END DESCRIPTION:
XS GIS Cut Line= 3
      2129125.00     13404875.00      2126925.00     13404875.00
      2125624.99     13405225.00
#Sta/Elev= 30
  2805.8  308.96  2965.8  305.89  3165.8  296.07  3405.8  289.67  3705.8  276.25
  3802.7  274.05  4235.8  267.83  4435.8  270.91  4572.3  270.48  4665.8  265.59
  4685.8  268.15  4785.4  269.33  4895.8  266.33  4975.8  268.43  4981.9  266.01
  4985.8  264.47  4986.0  261.73  4988.5  260.93  5005.6  261.73  5063.1  266.17
  5068.3  264.79  5103.1  264.80  5143.0  269.60  5217.7  273.32  5285.4  270.61
  5332.4  274.76  5706.2  280.49  5780.8  282.03  6065.4  288.67  6352.1  304.28
#Mann=9,-1,0
  2805.8     0.1       0  3802.7    0.05       0  4572.3     0.1       0
  4785.4    0.05       0  4981.9     0.1       0  4986.0    0.07       0
  5005.6     0.1       0  5706.2    0.05       0  5780.8     0.1       0
Bank Sta=4986,5005.6
Exp/Cntr=0.3,0.1

Type RM Length L Ch R = 1,16144,543,543,543
BEGIN DESCRIPTION:
La Jarita Creek 15.0
END DESCRIPTION:
XS GIS Cut Line= 3
      2128725.01     13404675.00      2127175.00     13404475.00
      2125874.96     13404675.01
#Sta/Elev= 30
  3382.3  300.79  3493.2  296.75  3634.4  287.34  3866.3  276.86  3957.0  274.76
  3975.7  273.37  4007.5  274.20  4357.2  269.72  4521.7  265.77  4622.5  266.33
  4703.2  268.61  4749.2  266.45  4828.6  264.91  4863.9  266.66  4955.3  266.39
  4974.2  262.37  4975.8  259.86  4978.3  259.06  4995.4  259.86  4995.7  261.62
  5026.1  265.83  5111.7  267.31  5242.4  269.61  5279.0  271.42  5451.0  272.46
  5850.0  277.45  6058.1  282.22  6128.9  285.63  6226.3  293.41  6260.5  294.85
#Mann=7,-1,0
  3382.3     0.1       0  3975.7    0.05       0  4863.9     0.1       0
  4975.8    0.07       0  4995.4     0.1       0  5111.7    0.05       0
  5850.0     0.1       0
Bank Sta=4975.8,4995.4
Exp/Cntr=0.3,0.1

Type RM Length L Ch R = 1,15601,928,928,928
BEGIN DESCRIPTION:
La Jarita Creek 14.0
END DESCRIPTION:
XS GIS Cut Line= 3
      2128874.98     13403925.00      2127325.00     13404025.00
      2125724.99     13404675.00
#Sta/Elev= 30
  3377.5  303.73  3407.7  302.77  3718.2  291.54  3806.8  286.42  4289.4  272.85
  4459.7  270.41  4600.0  265.43  4650.1  264.76  4707.3  266.32  4760.3  265.45
  4820.5  267.14  4920.7  263.72  4974.9  264.00  4983.7  259.78  4986.2  258.98
  5003.4  259.78  5006.3  262.58  5028.5  266.10  5098.6  265.85  5154.4  267.29
  5206.0  268.03  5314.9  271.33  5545.9  269.78  5927.7  274.69  6142.3  278.73
  6327.0  284.86  6380.6  288.19  6404.7  291.46  6428.7  293.00  6657.7  305.50
#Mann=10,-1,0
  3377.5    0.05       0  3407.7     0.1       0  3806.8    0.05       0
  4707.3     0.1       0  4983.7    0.07       0  5003.4     0.1       0
  5098.6    0.05       0  5154.4     0.1       0  5206.0    0.05       0
  5927.7     0.1       0
Bank Sta=4983.7,5003.4
Exp/Cntr=0.3,0.1

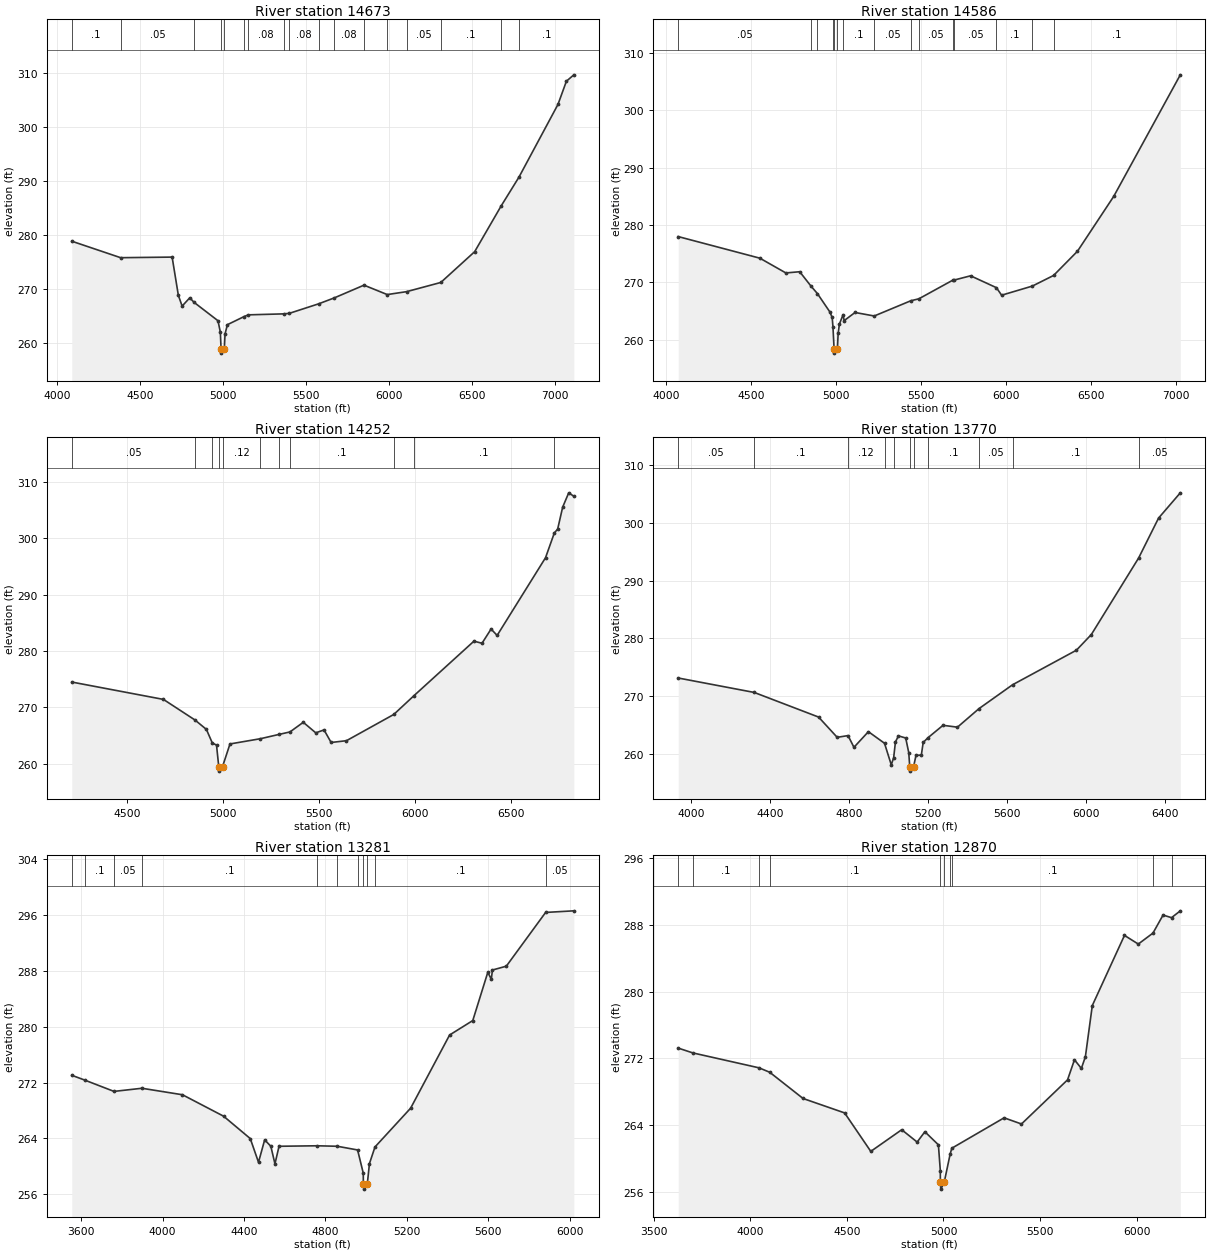
Type RM Length L Ch R = 1,14673,87,87,87
BEGIN DESCRIPTION:
Mapping XS a150b799
END DESCRIPTION:
XS GIS Cut Line= 5
      2128207.78     13403138.83      2127504.63     13403258.62
      2127285.88     13403498.21      2127067.13     13404013.83
      2125660.85     13404248.21
#Sta/Elev= 30
  4088.7  278.84  4383.0  275.79  4693.1  275.90  4730.6  268.82  4753.3  266.84
  4799.3  268.37  4825.2  267.53  4969.2  264.13  4983.4  262.02  4987.7  258.94
  4990.2  258.14  5007.4  258.94  5011.7  261.69  5025.9  263.40  5127.0  264.91
  5152.3  265.22  5363.9  265.40  5398.1  265.49  5575.5  267.26  5669.2  268.35
  5848.4  270.71  5988.4  268.97  6105.2  269.51  6311.1  271.21  6514.9  276.90
  6675.0  285.39  6781.5  290.68  7016.7  304.14  7067.4  308.43  7112.2  309.61
#Mann=17,-1,0
  4088.7     0.1       0  4383.0    0.05       0  4825.2    0.08       0
  4987.7    0.07       0  5007.4    0.08       0  5127.0     0.1       0
  5152.3    0.08       0  5363.9     0.1       0  5398.1    0.08       0
  5575.5    0.05       0  5669.2    0.08       0  5848.4    0.05       0
  5988.4     0.1       0  6105.2    0.05       0  6311.1     0.1       0
  6675.0    0.05       0  6781.5     0.1       0
Bank Sta=4987.7,5007.4
Exp/Cntr=0.3,0.1

Type RM Length L Ch R = 1,14586,334,334,334
BEGIN DESCRIPTION:
Mapping XS 1a50e2f5
END DESCRIPTION:
XS GIS Cut Line= 5
      2128166.10     13403050.29      2127452.55     13403190.91
      2127197.34     13403472.16      2127004.63     13403946.12
      2125688.69     13404169.78
#Sta/Elev= 30
  4070.7  277.98  4550.9  274.22  4703.7  271.65  4785.3  271.86  4851.2  269.37
  4889.2  268.06  4962.1  264.88  4976.3  263.89  4980.8  262.30  4987.4  258.48
  4989.9  257.68  5007.1  258.48  5011.4  261.12  5018.9  262.76  5040.5  264.38
  5046.6  263.34  5110.8  264.76  5223.7  264.15  5438.7  266.80  5486.0  267.14
  5687.1  270.41  5695.3  270.42  5790.5  271.15  5942.5  269.08  5973.0  267.77
  6153.8  269.36  6278.7  271.21  6419.3  275.43  6632.4  284.98  7024.2  306.16
#Mann=15,-1,0
  4070.7    0.05       0  4851.2    0.08       0  4889.2     0.1       0
  4980.8    0.08       0  4987.4    0.07       0  5007.1    0.08       0
  5040.5     0.1       0  5223.7    0.05       0  5438.7    0.08       0
  5486.0    0.05       0  5687.1    0.08       0  5695.3    0.05       0
  5942.5     0.1       0  6153.8    0.05       0  6278.7     0.1       0
Bank Sta=4987.4,5007.1
Exp/Cntr=0.3,0.1

Type RM Length L Ch R = 1,14252,482,482,482
BEGIN DESCRIPTION:
Mapping XS e195cb24
END DESCRIPTION:
XS GIS Cut Line= 4
      2127843.19     13402935.70      2127202.55     13403065.91
      2126483.80     13403487.79      2125410.84     13403847.18
#Sta/Elev= 30
  4210.7  274.50  4688.8  271.42  4853.7  267.76  4912.9  266.10  4943.9  263.68
  4965.7  263.32  4977.3  259.50  4979.8  258.70  4997.0  259.50  5035.9  263.52
  5194.9  264.45  5290.3  265.20  5348.7  265.65  5418.2  267.36  5483.4  265.49
  5526.4  266.01  5563.5  263.78  5643.6  264.10  5890.1  268.75  5994.8  272.06
  6308.3  281.75  6350.4  281.38  6397.7  283.90  6429.3  282.77  6681.7  296.55
  6727.7  300.95  6744.9  301.62  6771.2  305.53  6802.7  308.06  6829.4  307.45
#Mann=11,-1,0
  4210.7    0.05       0  4853.7     0.1       0  4943.9    0.12       0
  4977.3    0.07       0  4997.0    0.12       0  5194.9     0.1       0
  5290.3    0.05       0  5348.7     0.1       0  5890.1    0.05       0
  5994.8     0.1       0  6727.7    0.05       0
Bank Sta=4977.3,4997
Exp/Cntr=0.3,0.1

Type RM Length L Ch R = 1,13770,489,489,489
BEGIN DESCRIPTION:
Mapping XS 3614dbe3
END DESCRIPTION:
XS GIS Cut Line= 4
      2127666.11     13402875.81      2126893.52     13402880.15
      2125864.88     13403518.17      2125304.95     13403548.56
#Sta/Elev= 30
  3934.5  273.10  4319.4  270.60  4645.6  266.33  4739.8  262.82  4794.8  263.12
  4824.8  261.09  4898.0  263.80  4979.6  261.79  5013.8  258.06  5025.9  259.27
  5035.0  262.03  5050.4  263.07  5087.0  262.70  5102.4  260.17  5107.4  257.76
  5109.9  256.96  5127.1  257.76  5139.0  259.67  5166.2  259.75  5175.6  261.93
  5199.5  262.74  5276.0  264.90  5349.3  264.58  5458.5  267.80  5628.4  271.93
  5951.9  277.92  6027.6  280.64  6267.2  293.91  6368.1  300.82  6478.3  305.20
#Mann=11,-1,0
  3934.5    0.05       0  4319.4     0.1       0  4794.8    0.12       0
  4979.6     0.1       0  5025.9    0.12       0  5107.4    0.07       0
  5127.1    0.12       0  5199.5     0.1       0  5458.5    0.05       0
  5628.4     0.1       0  6267.2    0.05       0
Bank Sta=5107.4,5127.1
Exp/Cntr=0.3,0.1

Type RM Length L Ch R = 1,13281,411,411,411
BEGIN DESCRIPTION:
Mapping XS 80ed2c76
END DESCRIPTION:
XS GIS Cut Line= 3
      2127713.84     13402663.14      2126064.53     13402888.83
      2125339.81     13403231.66
#Sta/Elev= 30
  3553.6  273.05  3616.5  272.37  3761.0  270.74  3898.2  271.19  4097.5  270.26
  4299.3  267.19  4430.5  263.98  4470.9  260.59  4501.2  263.80  4531.5  262.88
  4551.7  260.36  4571.8  262.88  4758.5  262.95  4858.1  262.88  4957.7  262.35
  4985.7  259.01  4985.9  257.54  4988.4  256.74  5005.6  257.54  5015.9  260.40
  5043.1  262.78  5218.3  268.34  5409.7  278.82  5523.5  280.89  5597.3  287.80
  5614.5  286.81  5620.1  288.13  5688.3  288.68  5881.3  296.38  6020.0  296.61
#Mann=11,-1,0
  3553.6    0.05       0  3616.5     0.1       0  3761.0    0.05       0
  3898.2     0.1       0  4758.5    0.12       0  4858.1     0.1       0
  4957.7    0.12       0  4985.9    0.07       0  5005.6    0.12       0
  5043.1     0.1       0  5881.3    0.05       0
Bank Sta=4985.9,5005.6
Exp/Cntr=0.3,0.1

Type RM Length L Ch R = 1,12870,625,625,625
BEGIN DESCRIPTION:
Mapping XS c17c175a
END DESCRIPTION:
XS GIS Cut Line= 4
      2127666.13     13402103.22      2126824.08     13402580.67
      2125791.09     13402611.05      2125300.60     13402953.96
#Sta/Elev= 30
  3626.6  273.22  3702.6  272.64  4045.3  270.85  4100.4  270.32  4273.1  267.17
  4488.1  265.44  4623.7  260.82  4783.8  263.42  4863.8  261.94  4903.8  263.18
  4973.8  261.61  4983.8  258.49  4983.9  257.09  4986.4  256.29  5003.7  257.09
  5035.0  260.53  5043.3  261.20  5314.0  264.85  5404.0  264.11  5642.6  269.41
  5678.4  271.82  5714.1  270.78  5735.0  272.19  5770.8  278.33  5937.4  286.75
  6008.9  285.71  6085.0  287.03  6137.1  289.19  6181.1  288.88  6226.5  289.70
#Mann=10,-1,0
  3626.6    0.05       0  3702.6     0.1       0  4045.3    0.05       0
  4100.4     0.1       0  4983.9    0.07       0  5003.7     0.1       0
  5035.0    0.12       0  5043.3     0.1       0  6085.0    0.05       0
  6181.1     0.1       0
Bank Sta=4983.9,5003.7
Exp/Cntr=0.3,0.1

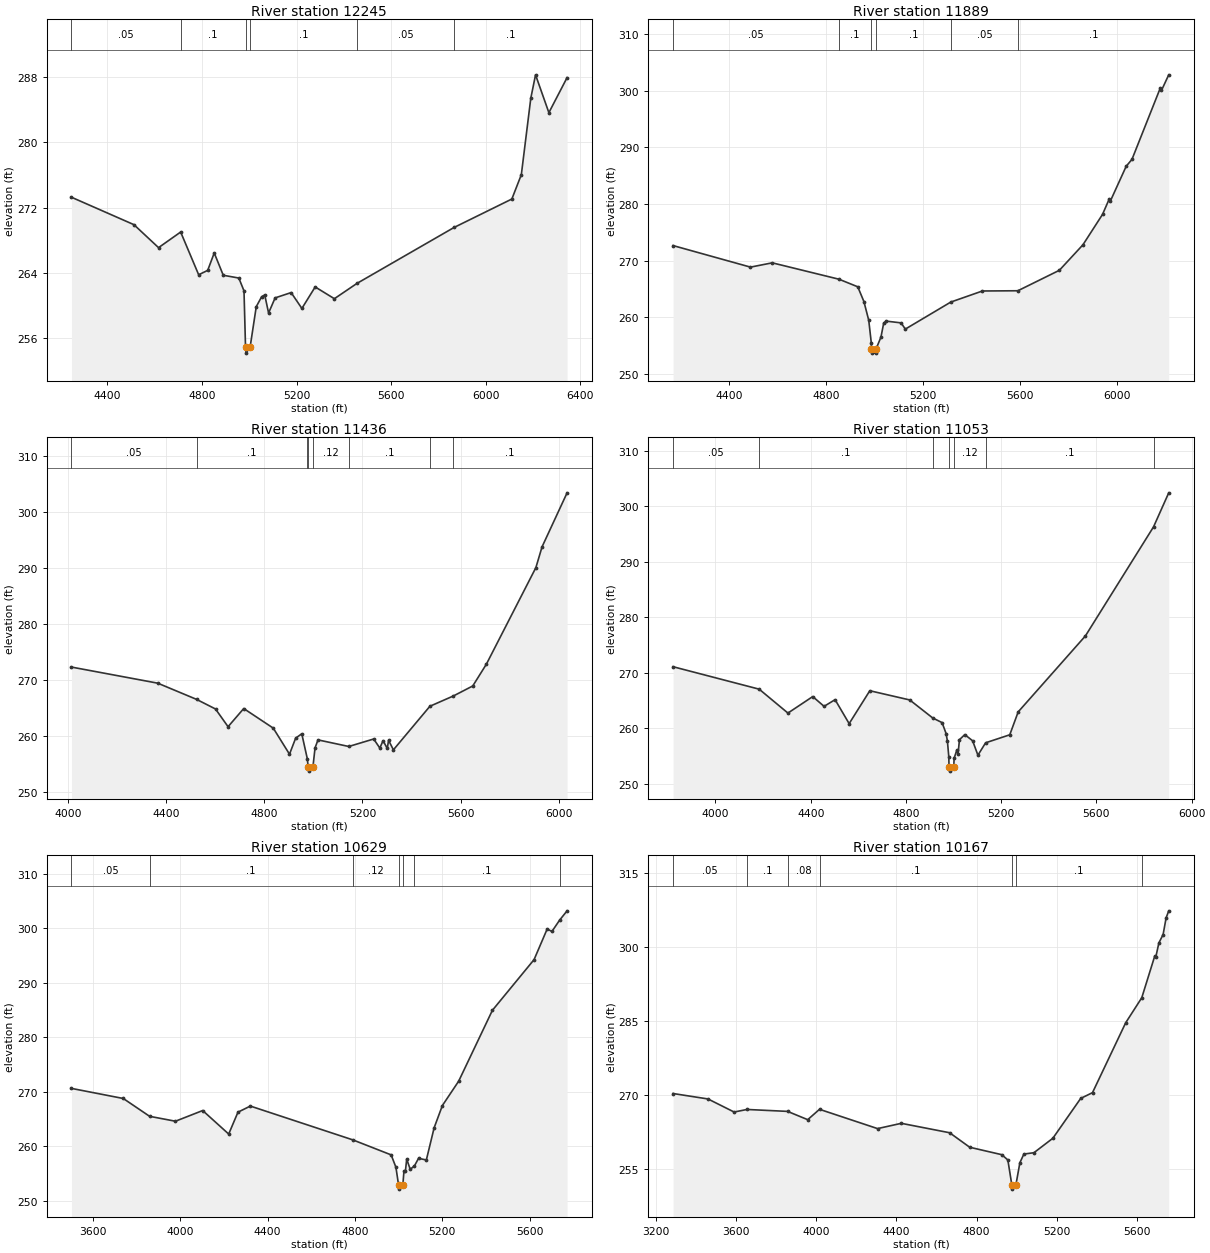
Type RM Length L Ch R = 1,12245,356,356,356
BEGIN DESCRIPTION:
La Jarita Creek 11.0
END DESCRIPTION:
XS GIS Cut Line= 3
      2127283.91     13401885.54      2126370.68     13402375.15
      2125311.69     13402326.54
#Sta/Elev= 30
  4247.6  273.28  4512.0  269.92  4616.0  267.11  4709.5  269.02  4785.7  263.79
  4823.9  264.33  4851.5  266.46  4889.7  263.73  4955.5  263.39  4977.4  261.82
  4983.8  255.00  4986.3  254.20  5003.6  255.00  5029.3  259.89  5052.0  261.10
  5065.1  261.32  5081.4  259.11  5109.0  260.96  5176.8  261.61  5222.2  259.67
  5278.5  262.30  5359.6  260.86  5455.0  262.73  5865.9  269.58  6110.3  273.06
  6150.4  276.04  6190.4  285.39  6210.5  288.26  6266.9  283.63  6343.9  287.92
#Mann=6,-1,0
  4247.6    0.05       0  4709.5     0.1       0  4983.8    0.07       0
  5003.6     0.1       0  5455.0    0.05       0  5865.9     0.1       0
Bank Sta=4983.8,5003.6
Exp/Cntr=0.3,0.1

Type RM Length L Ch R = 1,11889,453,453,453
BEGIN DESCRIPTION:
La Jarita Creek 10.0
END DESCRIPTION:
XS GIS Cut Line= 3
      2127235.28     13401816.11      2126141.51     13402041.81
      2125225.05     13402174.99
#Sta/Elev= 30
  4170.8  272.65  4489.8  268.84  4579.5  269.60  4854.7  266.70  4932.0  265.36
  4957.3  262.75  4977.2  259.44  4987.9  255.38  4988.2  254.43  4990.7  253.63
  5005.5  253.63  5008.0  254.43  5027.5  256.46  5039.0  258.96  5049.2  259.29
  5110.5  258.98  5128.0  257.88  5315.4  262.66  5445.8  264.62  5591.8  264.66
  5762.9  268.28  5860.1  272.79  5940.9  278.17  5968.3  280.88  5973.3  280.54
  6038.4  286.68  6062.2  287.90  6178.7  300.49  6183.7  300.08  6213.7  302.85
#Mann=6,-1,0
  4170.8    0.05       0  4854.7     0.1       0  4988.2    0.07       0
  5008.0     0.1       0  5315.4    0.05       0  5591.8     0.1       0
Bank Sta=4988.2,5008
Exp/Cntr=0.3,0.1

Type RM Length L Ch R = 1,11436,383,383,383
BEGIN DESCRIPTION:
Mapping XS 063f65a6
END DESCRIPTION:
XS GIS Cut Line= 3
      2127148.44     13401791.81      2126335.96     13401611.26
      2125221.38     13402024.45
#Sta/Elev= 30
  4013.3  272.27  4365.1  269.39  4523.4  266.49  4600.7  264.77  4651.9  261.60
  4715.8  264.85  4836.3  261.34  4902.4  256.68  4927.5  259.55  4952.5  260.33
  4975.2  255.84  4978.3  254.45  4980.8  253.65  4998.1  254.45  5006.6  257.81
  5018.6  259.24  5144.2  258.06  5245.7  259.40  5270.7  257.78  5283.9  259.10
  5301.1  257.71  5306.4  259.17  5326.1  257.46  5475.0  265.26  5570.7  267.10
  5649.7  268.89  5705.1  272.78  5907.1  290.07  5932.2  293.78  6034.3  303.45
#Mann=8,-1,0
  4013.3    0.05       0  4523.4     0.1       0  4975.2    0.12       0
  4978.3    0.07       0  4998.1    0.12       0  5144.2     0.1       0
  5475.0    0.05       0  5570.7     0.1       0
Bank Sta=4978.3,4998.1
Exp/Cntr=0.3,0.1

Type RM Length L Ch R = 1,11053,424,424,424
BEGIN DESCRIPTION:
Mapping XS 7cb460b4
END DESCRIPTION:
XS GIS Cut Line= 3
      2127047.74     13401718.89      2126054.71     13401427.23
      2125120.67     13401899.45
#Sta/Elev= 30
  3822.1  271.10  4183.7  267.06  4304.4  262.76  4408.6  265.73  4456.2  263.97
  4502.4  265.17  4561.5  260.86  4648.3  266.78  4816.0  265.12  4912.4  261.88
  4951.9  261.04  4968.6  259.08  4974.2  257.72  4980.0  254.90  4981.0  253.11
  4983.5  252.31  5000.8  253.11  5002.4  254.63  5013.2  256.03  5018.8  255.36
  5024.8  257.97  5047.2  258.88  5080.1  257.77  5102.3  255.18  5134.7  257.41
  5236.1  258.85  5271.4  262.97  5553.7  276.64  5840.1  296.29  5903.7  302.40
#Mann=7,-1,0
  3822.1    0.05       0  4183.7     0.1       0  4912.4    0.12       0
  4981.0    0.07       0  5000.8    0.12       0  5134.7     0.1       0
  5840.1    0.05       0
Bank Sta=4981,5000.8
Exp/Cntr=0.3,0.1

Type RM Length L Ch R = 1,10629,462,462,462
BEGIN DESCRIPTION:
La Jarita Creek 9.0
END DESCRIPTION:
XS GIS Cut Line= 3
      2127065.16     13401677.24      2125881.10     13401267.51
      2124989.38     13401753.27
#Sta/Elev= 30
  3502.4  270.62  3739.6  268.77  3860.1  265.50  3978.4  264.60  4103.0  266.56
  4222.1  262.25  4264.5  266.26  4321.1  267.38  4790.3  261.18  4965.6  258.43
  4987.4  256.16  4999.4  252.95  5001.9  252.15  5019.2  252.95  5024.2  255.44
  5031.1  255.55  5036.8  257.65  5053.0  255.78  5072.3  256.42  5090.9  257.79
  5126.7  257.50  5162.2  263.38  5200.1  267.48  5274.7  271.95  5429.0  284.94
  5619.8  294.24  5679.7  299.85  5701.5  299.40  5736.9  301.49  5770.8  303.18
#Mann=7,-1,0
  3502.4    0.05       0  3860.1     0.1       0  4790.3    0.12       0
  4999.4    0.07       0  5019.2    0.12       0  5072.3     0.1       0
  5736.9    0.05       0
Bank Sta=4999.4,5019.2
Exp/Cntr=0.3,0.1

Type RM Length L Ch R = 1,10167,606,606,606
BEGIN DESCRIPTION:
La Jarita Creek 8.0
END DESCRIPTION:
XS GIS Cut Line= 4
      2127085.96     13401628.62      2125905.40     13401139.03
      2125290.82     13401118.20      2124809.07     13401437.06
#Sta/Elev= 30
  3287.1  270.27  3461.1  269.17  3591.3  266.52  3655.6  267.04  3857.9  266.65
  3958.1  264.97  4017.0  267.07  4306.4  263.16  4424.8  264.23  4665.6  262.32
  4765.7  259.38  4925.8  257.87  4955.8  256.80  4975.9  251.69  4978.4  250.89
  4995.7  251.69  5015.8  256.25  5035.8  258.00  5085.8  258.27  5180.1  261.20
  5319.0  269.28  5377.8  270.45  5543.3  284.62  5623.4  289.69  5687.7  298.09
  5693.7  298.01  5708.7  300.80  5729.8  302.51  5744.8  305.89  5757.8  307.31
#Mann=7,-1,0
  3287.1    0.05       0  3655.6     0.1       0  3857.9    0.08       0
  4017.0     0.1       0  4975.9    0.07       0  4995.7     0.1       0
  5623.4    0.05       0
Bank Sta=4975.9,4995.7
Exp/Cntr=0.3,0.1

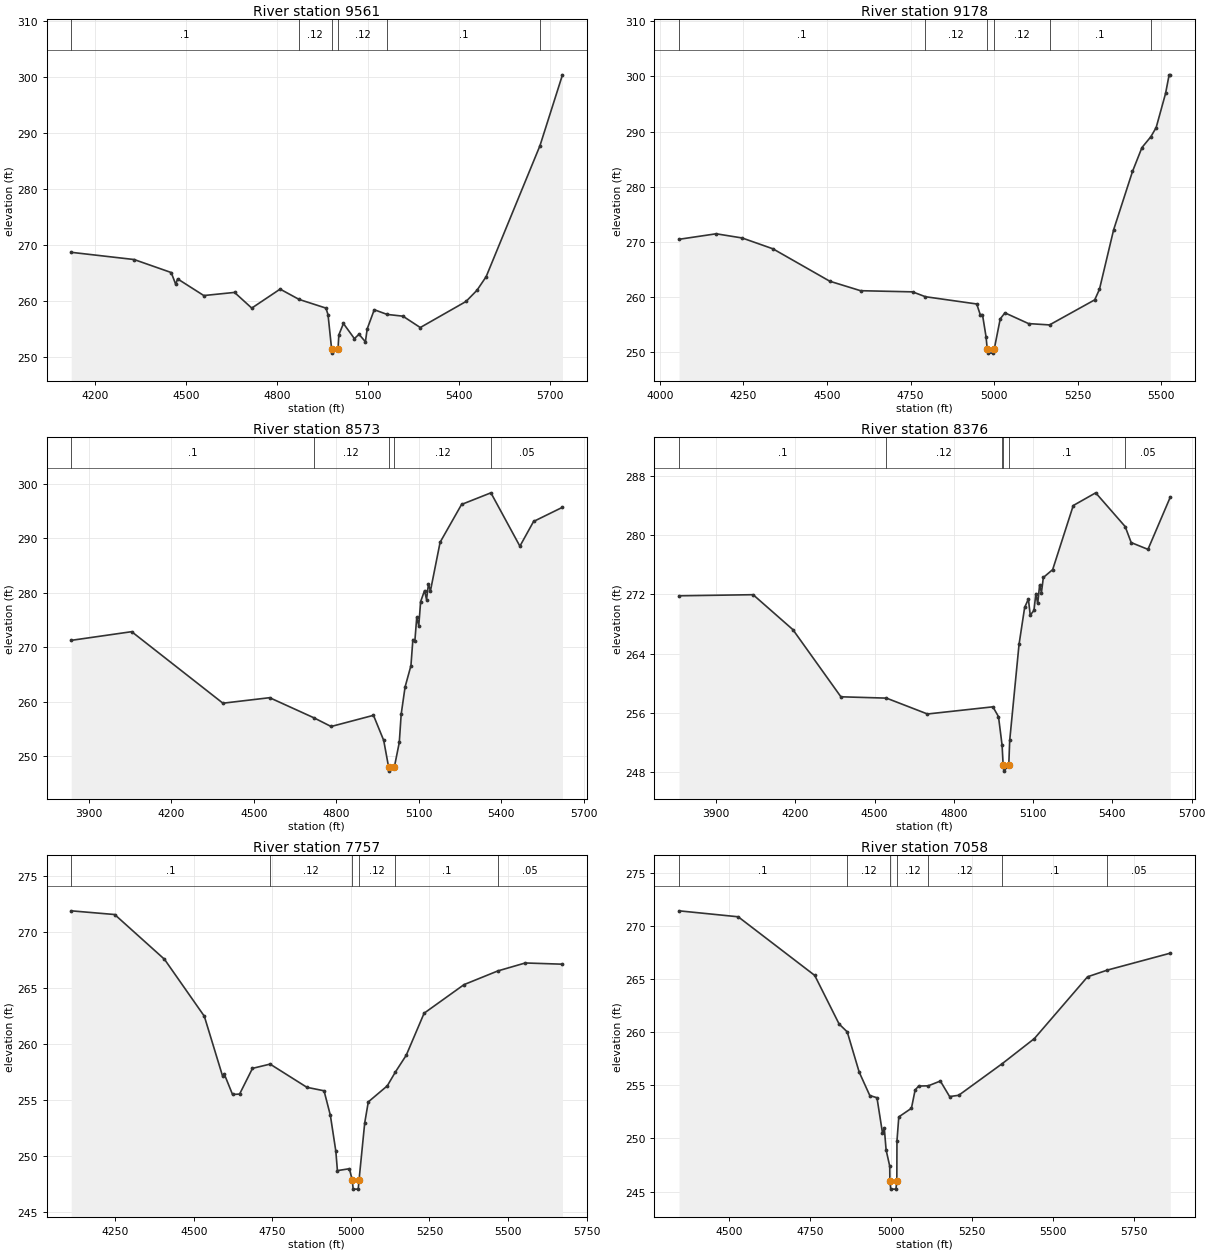
Type RM Length L Ch R = 1,9561,383,383,383
BEGIN DESCRIPTION:
La Jarita Creek 7.0
END DESCRIPTION:
XS GIS Cut Line= 3
      2125947.08     13399948.04      2125450.54     13400666.81
      2124825.04     13401074.98
#Sta/Elev= 30
  4121.0  268.69  4328.5  267.40  4450.8  265.08  4465.7  262.97  4471.8  263.95
  4558.3  260.97  4659.7  261.53  4716.5  258.73  4810.1  262.12  4872.6  260.28
  4961.2  258.73  4968.1  257.55  4979.8  251.49  4982.4  250.69  5001.1  251.49
  5003.8  253.95  5018.9  255.98  5055.1  253.28  5070.3  254.06  5091.4  252.71
  5097.3  255.01  5120.6  258.44  5163.0  257.60  5215.1  257.29  5272.4  255.26
  5423.2  259.91  5459.4  261.91  5489.7  264.34  5667.3  287.74  5741.5  300.38
#Mann=6,-1,0
  4121.0     0.1       0  4872.6    0.12       0  4979.8    0.07       0
  5001.1    0.12       0  5163.0     0.1       0  5667.3    0.05       0
Bank Sta=4979.8,5001.1
Exp/Cntr=0.3,0.1

Type RM Length L Ch R = 1,9178,605,605,605
BEGIN DESCRIPTION:
La Jarita Creek 6.0
END DESCRIPTION:
XS GIS Cut Line= 3
      2125860.26     13399934.17      2125175.00     13400525.00
      2124774.99     13400925.01
#Sta/Elev= 30
  4057.2  270.44  4168.3  271.44  4246.1  270.68  4338.3  268.71  4508.4  262.83
  4600.5  261.11  4756.3  260.90  4794.5  260.02  4948.3  258.70  4958.7  256.76
  4965.5  256.76  4976.1  252.77  4979.6  250.58  4982.2  249.78  4998.3  249.78
  5000.9  250.58  5018.6  256.00  5032.7  257.09  5103.4  255.14  5166.1  254.90
  5301.4  259.45  5315.6  261.36  5358.0  272.16  5414.5  282.75  5442.8  287.09
  5469.5  289.06  5485.3  290.71  5513.5  296.91  5524.2  300.29  5527.7  300.29
#Mann=6,-1,0
  4057.2     0.1       0  4794.5    0.12       0  4979.6    0.07       0
  5000.9    0.12       0  5166.1     0.1       0  5469.5    0.05       0
Bank Sta=4979.6,5000.9
Exp/Cntr=0.3,0.1

Type RM Length L Ch R = 1,8573,197,197,197
BEGIN DESCRIPTION:
La Jarita Creek 5.0
END DESCRIPTION:
XS GIS Cut Line= 3
      2125822.06     13399895.98      2124825.00     13400425.00
      2124370.68     13400899.45
#Sta/Elev= 30
  3836.3  271.27  4056.0  272.86  4387.7  259.75  4557.5  260.76  4718.1  257.08
  4780.9  255.48  4934.9  257.53  4972.1  252.93  4989.7  248.10  4992.3  247.30
  5011.0  248.10  5028.7  252.55  5035.6  257.73  5049.8  262.73  5071.1  266.64
  5078.1  271.41  5085.3  271.13  5092.2  275.50  5099.5  273.96  5106.4  278.38
  5120.5  280.39  5127.8  278.75  5134.7  281.59  5141.9  280.32  5177.1  289.25
  5255.1  296.18  5361.7  298.31  5467.1  288.53  5516.8  293.06  5621.9  295.66
#Mann=5,-1,0
  3836.3     0.1       0  4718.1    0.12       0  4989.7    0.07       0
  5011.0    0.12       0  5361.7    0.05       0
Bank Sta=4989.7,5011
Exp/Cntr=0.3,0.1

Type RM Length L Ch R = 1,8376,619,619,619
BEGIN DESCRIPTION:
Mapping XS e99a36ac
END DESCRIPTION:
XS GIS Cut Line= 3
      2125798.75     13399759.79      2124933.18     13400059.17
      2124276.94     13400736.25
#Sta/Elev= 30
  3760.4  271.82  4040.6  271.97  4191.1  267.24  4372.8  258.14  4545.1  257.96
  4700.3  255.81  4947.9  256.78  4969.1  255.45  4982.7  251.58  4986.7  248.87
  4989.3  248.07  5008.0  248.87  5011.5  252.22  5046.8  265.23  5068.1  270.25
  5082.2  271.38  5089.2  269.20  5103.3  269.84  5110.5  272.12  5117.5  270.78
  5124.7  273.28  5131.6  272.26  5138.8  274.30  5174.1  275.37  5252.0  284.05
  5336.9  285.77  5448.4  281.20  5471.2  279.03  5534.7  278.11  5619.2  285.20
#Mann=6,-1,0
  3760.4     0.1       0  4545.1    0.12       0  4982.7     0.1       0
  4986.7    0.07       0  5008.0     0.1       0  5448.4    0.05       0
Bank Sta=4986.7,5008
Exp/Cntr=0.3,0.1

Type RM Length L Ch R = 1,7757,699,699,699
BEGIN DESCRIPTION:
Mapping XS 7db22360
END DESCRIPTION:
XS GIS Cut Line= 4
      2125693.57     13399677.24      2125033.88     13399895.98
      2124582.49     13399847.37      2124179.87     13399944.55
#Sta/Elev= 30
  4110.2  271.90  4248.5  271.57  4406.9  267.58  4533.7  262.50  4591.8  257.16
  4597.1  257.35  4623.5  255.52  4646.0  255.56  4686.9  257.85  4743.0  258.23
  4860.2  256.16  4914.7  255.85  4934.8  253.66  4952.2  250.46  4957.2  248.73
  4995.2  248.90  5004.6  247.88  5007.3  247.08  5023.4  247.08  5026.0  247.88
  5044.1  252.99  5055.5  254.86  5115.9  256.29  5141.6  257.52  5176.2  259.02
  5233.1  262.77  5360.2  265.32  5467.7  266.54  5555.0  267.25  5673.4  267.14
#Mann=6,-1,0
  4110.2     0.1       0  4743.0    0.12       0  5004.6    0.07       0
  5026.0    0.12       0  5141.6     0.1       0  5467.7    0.05       0
Bank Sta=5004.6,5026
Exp/Cntr=0.3,0.1

Type RM Length L Ch R = 1,7058,389,389,389
BEGIN DESCRIPTION:
Mapping XS 14db5731
END DESCRIPTION:
XS GIS Cut Line= 3
      2125617.23     13399333.47      2125079.01     13399475.84
      2124218.92     13399902.42
#Sta/Elev= 30
  4344.8  271.40  4527.4  270.84  4763.7  265.33  4839.0  260.76  4864.1  260.02
  4901.0  256.24  4933.7  254.04  4955.9  253.83  4972.9  250.52  4978.5  250.97
  4984.1  248.92  4995.3  247.40  4995.8  246.04  4998.4  245.24  5014.5  245.24
  5017.2  246.04  5017.6  249.76  5023.3  252.03  5062.3  252.84  5073.7  254.56
  5084.6  254.93  5114.2  254.95  5151.6  255.40  5180.2  253.94  5208.2  254.06
  5342.9  257.04  5441.8  259.39  5606.1  265.20  5667.4  265.83  5861.6  267.42
#Mann=7,-1,0
  4344.8     0.1       0  4864.1    0.12       0  4995.8    0.07       0
  5017.2    0.12       0  5114.2    0.12       0  5342.9     0.1       0
  5667.4    0.05       0
Bank Sta=4995.8,5017.2
Exp/Cntr=0.3,0.1