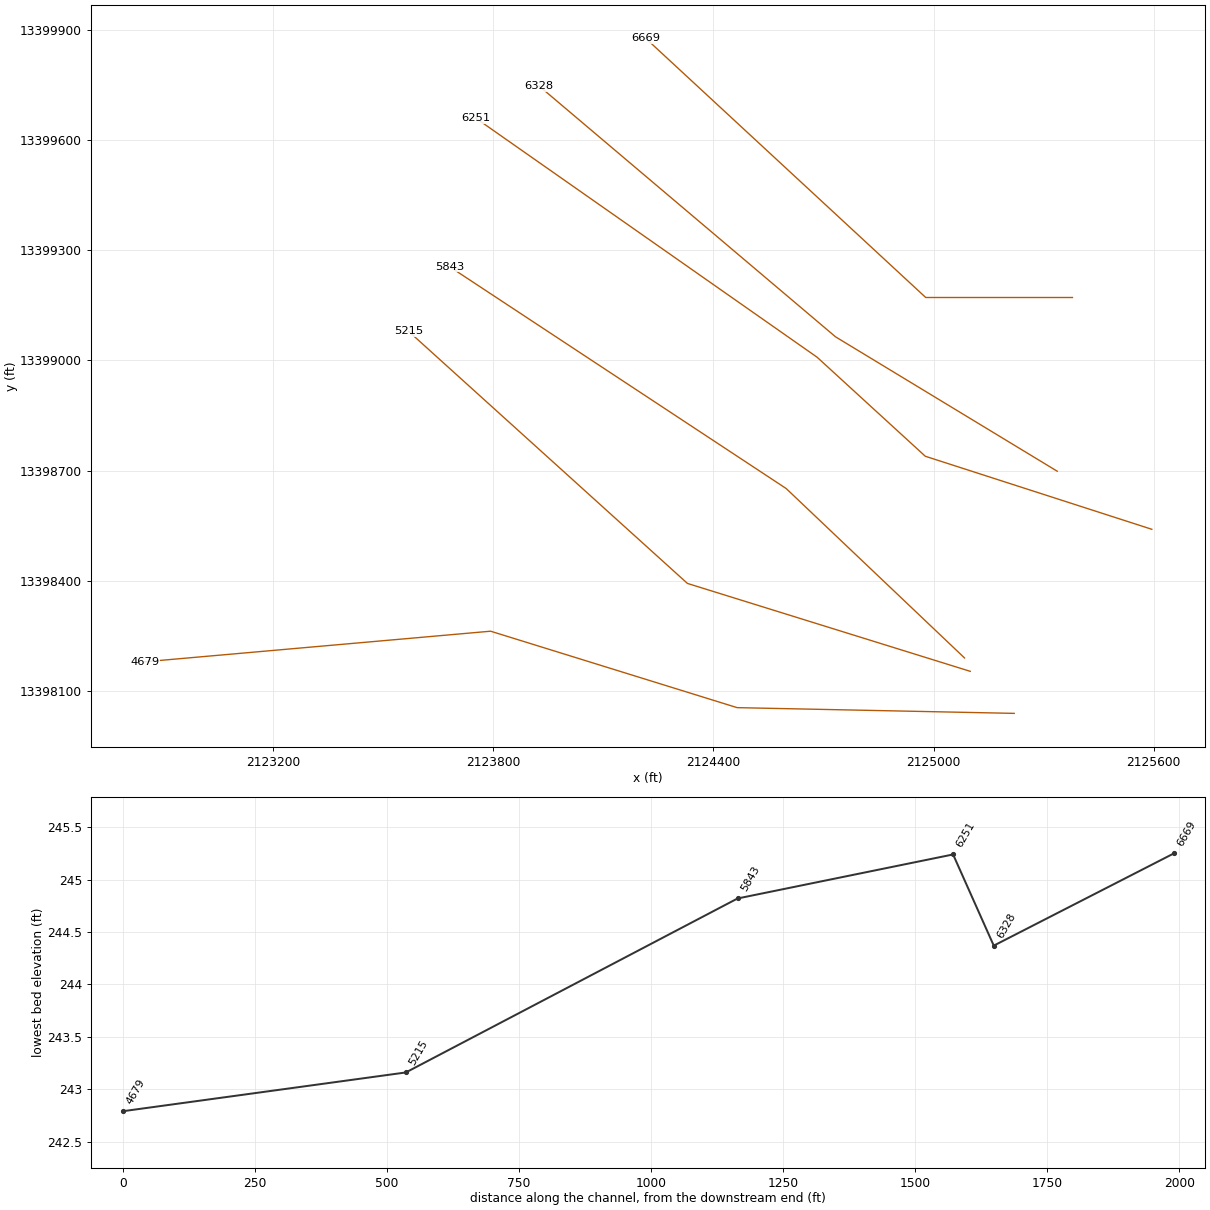
HEC-RAS study La Jarita Creek.prj: La Jarita Creek Base Level Engineering

--- La Jarita Creek.g01 (geometry) --- (continued)

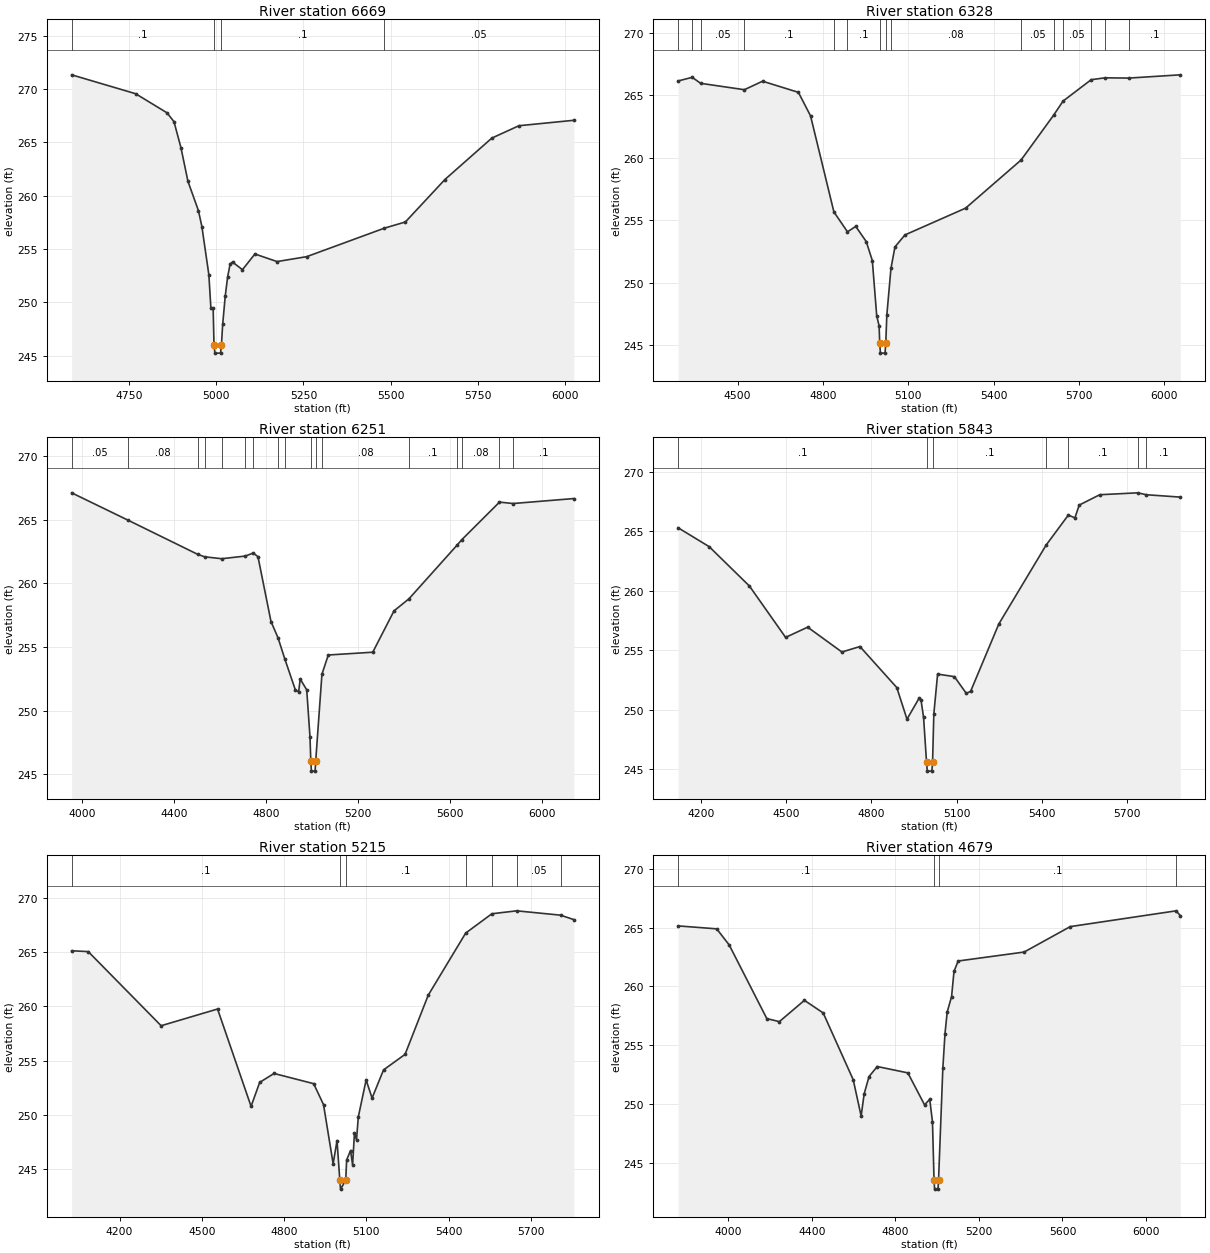
Type RM Length L Ch R = 1,6669,341,341,341
BEGIN DESCRIPTION:
La Jarita Creek 4.0
END DESCRIPTION:
XS GIS Cut Line= 3
      2125378.44     13399171.53      2124978.47     13399171.53
      2124215.36     13399877.87
#Sta/Elev= 30
  4585.4  271.33  4768.8  269.56  4858.8  267.77  4878.8  266.94  4898.8  264.50
  4918.8  261.35  4948.8  258.61  4958.8  257.11  4978.8  252.59  4984.6  249.45
  4991.1  249.45  4993.5  246.05  4996.1  245.25  5012.2  245.25  5014.9  246.05
  5018.4  247.94  5025.7  250.58  5032.5  252.37  5039.9  253.62  5046.7  253.78
  5075.1  253.07  5110.8  254.54  5174.3  253.83  5259.3  254.29  5481.9  256.96
  5542.2  257.54  5655.6  261.52  5790.0  265.40  5867.7  266.56  6025.2  267.07
#Mann=4,-1,0
  4585.4     0.1       0  4993.5    0.07       0  5014.9     0.1       0
  5481.9    0.05       0
Bank Sta=4993.5,5014.9
Exp/Cntr=0.3,0.1

Type RM Length L Ch R = 1,6328,77,77,77
BEGIN DESCRIPTION:
Mapping XS 59cbcd61
END DESCRIPTION:
XS GIS Cut Line= 3
      2125336.92     13398697.99      2124732.74     13399064.32
      2123924.46     13399748.15
#Sta/Elev= 30
  4290.9  266.13  4340.4  266.42  4370.2  265.94  4523.9  265.43  4587.7  266.11
  4713.7  265.22  4756.4  263.34  4838.5  255.66  4886.2  254.07  4915.4  254.50
  4952.2  253.29  4973.6  251.77  4989.0  247.36  4997.5  246.54  4999.5  245.17
  5002.1  244.37  5018.2  244.37  5020.9  245.17  5024.5  247.40  5039.1  251.14
  5053.1  252.86  5088.2  253.82  5301.4  255.96  5496.5  259.81  5610.8  263.39
  5644.0  264.52  5742.9  266.23  5791.4  266.38  5875.1  266.36  6056.2  266.62
#Mann=15,-1,0
  4290.9    0.05       0  4340.4     0.1       0  4370.2    0.05       0
  4523.9     0.1       0  4838.5    0.08       0  4886.2     0.1       0
  4999.5    0.07       0  5020.9     0.1       0  5039.1    0.08       0
  5496.5    0.05       0  5610.8    0.08       0  5644.0    0.05       0
  5742.9    0.08       0  5791.4    0.05       0  5875.1     0.1       0
Bank Sta=4999.5,5020.9
Exp/Cntr=0.3,0.1

Type RM Length L Ch R = 1,6251,408,408,408
BEGIN DESCRIPTION:
Mapping XS 25271676
END DESCRIPTION:
XS GIS Cut Line= 4
      2125594.68     13398539.77      2124977.32     13398738.83
      2124682.39     13399008.77      2123751.87     13399660.63
#Sta/Elev= 30
  3953.4  267.12  4197.5  264.98  4501.0  262.29  4531.7  262.09  4606.3  261.94
  4709.6  262.15  4743.3  262.39  4763.9  262.10  4820.6  257.00  4851.0  255.73
  4880.3  254.08  4926.7  251.62  4940.9  251.48  4947.7  252.48  4976.0  251.63
  4990.2  247.93  4993.7  246.04  4996.4  245.24  5012.5  245.24  5015.1  246.04
  5042.2  252.86  5069.8  254.37  5263.3  254.59  5355.7  257.84  5420.9  258.79
  5628.7  262.98  5649.8  263.42  5814.6  266.39  5873.8  266.28  6138.0  266.67
#Mann=17,-1,0
  3953.4    0.05       0  4197.5    0.08       0  4501.0    0.05       0
  4531.7    0.08       0  4606.3    0.05       0  4709.6    0.08       0
  4743.3     0.1       0  4851.0    0.08       0  4880.3     0.1       0
  4993.7    0.07       0  5015.1     0.1       0  5042.2    0.08       0
  5420.9     0.1       0  5628.7    0.05       0  5649.8    0.08       0
  5814.6    0.05       0  5873.8     0.1       0
Bank Sta=4993.7,5015.1
Exp/Cntr=0.3,0.1

Type RM Length L Ch R = 1,5843,628,628,628
BEGIN DESCRIPTION:
Mapping XS 49a424d1
END DESCRIPTION:
XS GIS Cut Line= 3
      2125084.20     13398189.11      2124598.11     13398650.90
      2123681.47     13399255.05
#Sta/Elev= 30
  4119.5  265.29  4229.0  263.70  4370.6  260.39  4498.0  256.07  4575.7  256.93
  4696.2  254.84  4759.7  255.30  4889.5  251.85  4925.4  249.19  4968.7  250.98
  4974.7  250.82  4983.8  249.34  4994.1  245.62  4996.8  244.82  5012.9  244.82
  5015.5  245.62  5019.9  249.63  5033.2  252.98  5092.2  252.77  5134.3  251.36
  5149.4  251.53  5248.8  257.20  5415.5  263.84  5493.6  266.36  5516.7  266.12
  5531.8  267.20  5604.1  268.07  5737.9  268.23  5768.0  268.07  5887.8  267.87
#Mann=7,-1,0
  4119.5     0.1       0  4994.1    0.07       0  5015.5     0.1       0
  5415.5    0.05       0  5493.6     0.1       0  5737.9    0.05       0
  5768.0     0.1       0
Bank Sta=4994.1,5015.5
Exp/Cntr=0.3,0.1

Type RM Length L Ch R = 1,5215,536,536,536
BEGIN DESCRIPTION:
Mapping XS 3a07f40b
END DESCRIPTION:
XS GIS Cut Line= 3
      2125099.86     13398152.63      2124329.01     13398392.22
      2123569.30     13399079.08
#Sta/Elev= 30
  4025.3  265.13  4085.9  265.05  4351.6  258.22  4557.4  259.76  4679.6  250.79
  4711.1  253.00  4763.4  253.82  4907.9  252.88  4943.8  250.95  4978.9  245.50
  4993.1  247.63  5003.3  243.96  5006.0  243.16  5024.8  243.96  5028.2  245.85
  5042.4  246.72  5049.9  245.39  5056.6  248.31  5064.1  247.71  5070.8  249.83
  5099.2  253.22  5120.9  251.55  5162.7  254.15  5241.2  255.58  5325.6  261.03
  5462.3  266.76  5557.9  268.54  5648.5  268.81  5808.2  268.41  5856.7  268.00
#Mann=7,-1,0
  4025.3     0.1       0  5003.3    0.07       0  5024.8     0.1       0
  5462.3    0.05       0  5557.9     0.1       0  5648.5    0.05       0
  5808.2     0.1       0
Bank Sta=5003.3,5024.8
Exp/Cntr=0.3,0.1

Type RM Length L Ch R = 1,4679,0,0,0
BEGIN DESCRIPTION:
Mapping XS 598e2ca0
END DESCRIPTION:
XS GIS Cut Line= 4
      2125219.66     13398038.05      2124464.43     13398053.68
      2123792.56     13398262.01      2122849.96     13398178.68
#Sta/Elev= 30
  3759.2  265.14  3943.9  264.89  4003.9  263.52  4184.0  257.27  4244.0  257.01
  4364.0  258.82  4454.0  257.75  4597.8  252.08  4635.8  248.99  4650.1  250.87
  4673.6  252.35  4712.9  253.20  4859.5  252.66  4939.6  249.94  4964.2  250.42
  4977.4  248.51  4984.8  243.59  4987.5  242.79  5003.7  242.79  5006.5  243.59
  5027.0  253.04  5037.3  255.99  5047.9  257.83  5068.9  259.14  5080.4  261.27
  5100.3  262.16  5416.4  262.92  5637.2  265.08  6144.4  266.42  6164.3  266.01
#Mann=4,-1,0
  3759.2     0.1       0  4984.8    0.07       0  5006.5     0.1       0
  6144.4    0.05       0
Bank Sta=4984.8,5006.5
Exp/Cntr=0.3,0.1

Chan Stop Cuts=-1