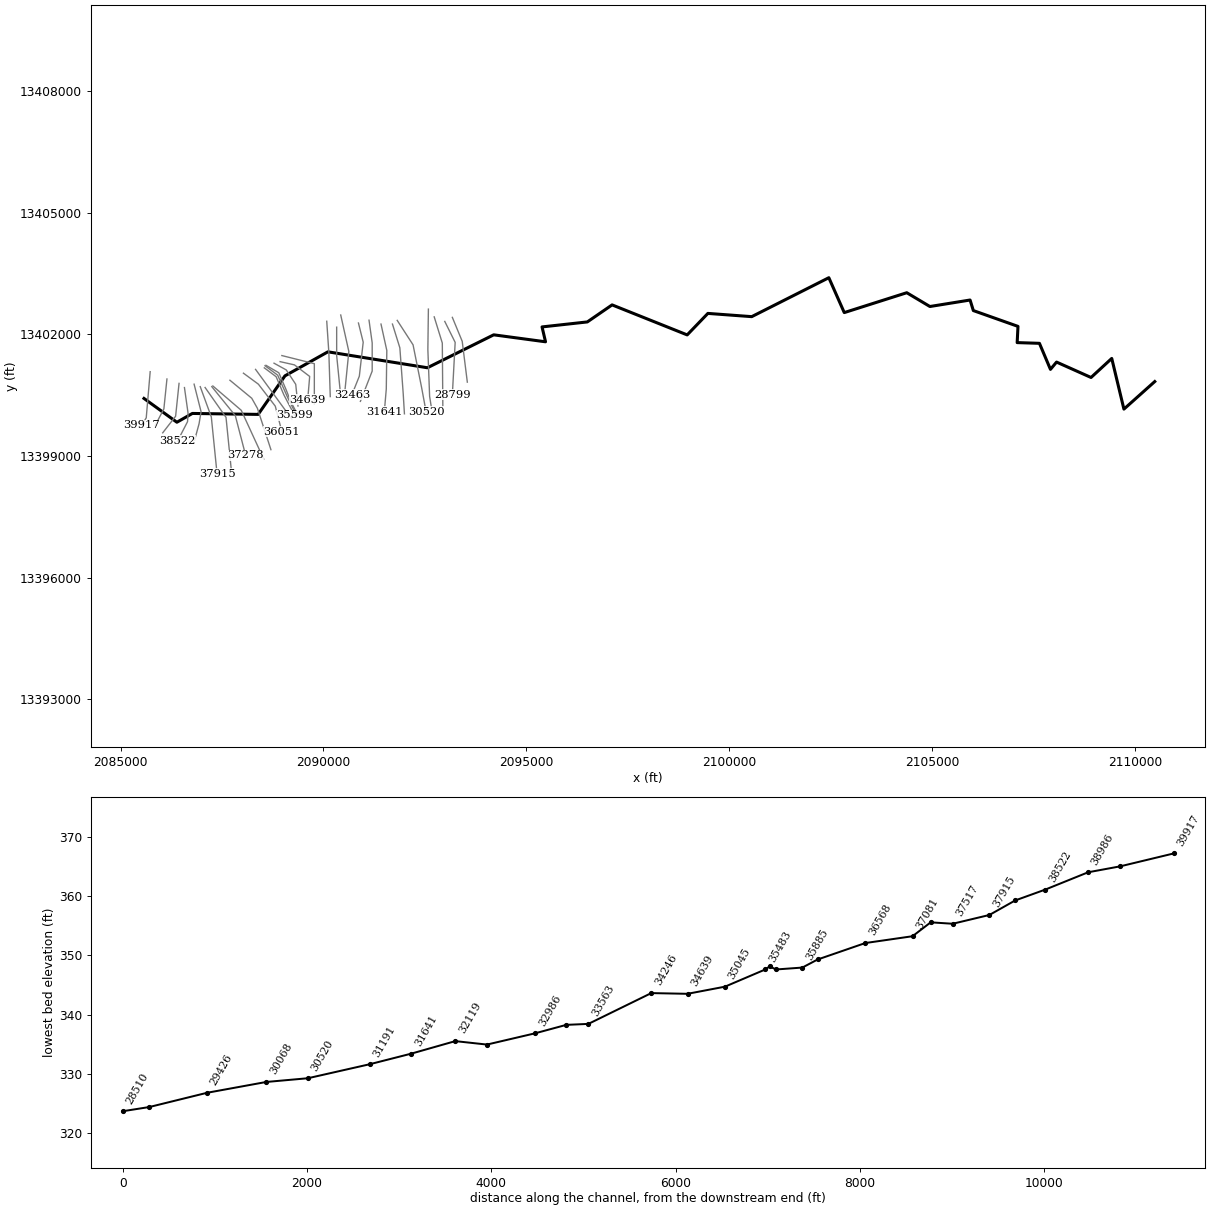
--- Live Oak Creek.prj (project) ---

Proj Title=Live Oak Creek Base Level Engineering
Current Plan=p01
Default Exp/Contr=0.3,0.1
English Units
Geom File=g01
Flow File=f01
Plan File=p01
Y Axis Title=Elevation
X Axis Title(PF)=Main Channel Distance
X Axis Title(XS)=Station
BEGIN DESCRIPTION:
Live Oak Creek
END DESCRIPTION:
DSS Export Rating Curves= 0
DSS Export Rating Curve Sorted= 0
DSS Export Volume Flow Curves= 0
DXF OffsetX= 0
DXF OffsetY= 0
DXF ScaleX= 1
DXF ScaleY= 10

--- Live Oak Creek.p01 (plan) ---

Plan Title=Multiple Run
Short Identifier=Multiple
Geom File=g01
Flow File=f01
Subcritical Flow
K Sum by GR= 0
Std Step Tol= 0.01
Critical Tol= 0.01
Num of Std Step Trials= 20
Max Error Tol= 0.3
Flow Tol Ratio= 0.001
Split Flow NTrial= 30
Split Flow Tol= 0.02
Split Flow Ratio= 0.02
Log Output Level= 0
Friction Slope Method= 1
Unsteady Friction Slope Method= 2
Unsteady Bridges Friction Slope Method= 1
Parabolic Critical Depth
Global Vel Dist=  1 , 1 , 1
Global Log Level= 0
CheckData=True
Encroach Param= -1, 0, 0, 0
BEGIN DESCRIPTION:
Multiple Run
END DESCRIPTION:

--- Live Oak Creek.f01 (steady flow) ---

Flow Title=Multiple
Program Version=5.05
Number of Profiles= 7
Profile Names=10-year,25-year,50-year,1pct_min,100-year,1pct_plu,500-year
River Rch & RM=Live Oak Creek,Reach-1         ,39917
     174     237     289     175     350     698     522
River Rch & RM=Live Oak Creek,Reach-1         ,36568
     185     253     308     188     374     747     560
River Rch & RM=Live Oak Creek,Reach-1         ,33563
     386     548     685     426     849    1695    1329
River Rch & RM=Live Oak Creek,Reach-1         ,26309
     439     627     786     491     980    1955    1546
River Rch & RM=Live Oak Creek,Reach-1         ,24966
     507     728     918     575    1147    2290    1824
River Rch & RM=Live Oak Creek,Reach-1         ,23576
     555     798    1006     631    1258    2510    2000
River Rch & RM=Live Oak Creek,Reach-1         ,18322
     602     867    1094     686    1369    2732    2180
River Rch & RM=Live Oak Creek,Reach-1         ,10563
     617     888    1120     702    1400    2793    2224
Boundary for River Rch & Prof#=Live Oak Creek,Reach-1         , 1
Up Type= 0
Dn Type= 3
Dn Slope=0.005
Boundary for River Rch & Prof#=Live Oak Creek,Reach-1         , 2
Up Type= 0
Dn Type= 3
Dn Slope=0.005
Boundary for River Rch & Prof#=Live Oak Creek,Reach-1         , 3
Up Type= 0
Dn Type= 3
Dn Slope=0.005
Boundary for River Rch & Prof#=Live Oak Creek,Reach-1         , 4
Up Type= 0
Dn Type= 3
Dn Slope=0.005
Boundary for River Rch & Prof#=Live Oak Creek,Reach-1         , 5
Up Type= 0
Dn Type= 3
Dn Slope=0.005
Boundary for River Rch & Prof#=Live Oak Creek,Reach-1         , 6
Up Type= 0
Dn Type= 3
Dn Slope=0.005
Boundary for River Rch & Prof#=Live Oak Creek,Reach-1         , 7
Up Type= 0
Dn Type= 3
Dn Slope=0.005
DSS Import GetInterval= 0
DSS Import GetPeak= 0
DSS Import FillOption= 0

--- Live Oak Creek.g01 (geometry) ---

Geom Title=Existing Conditions
Program Version=5.05

River Reach=Live Oak Creek  ,Reach-1
Reach XY= 30
      2085578.02     13400418.02      2086388.49     13399831.38
      2086770.36     13400048.01       2088390.8     13400024.54
       2089050.8     13400974.54      2090109.32     13401567.31
       2092560.8     13401174.54      2094194.21     13401986.41
       2095470.8     13401814.54      2095385.03     13402181.38
       2096500.8     13402304.54       2097110.8     13402724.54
       2098960.8     13401984.54       2099470.8     13402514.54
       2100550.8     13402434.54       2102450.8     13403394.54
       2102830.8     13402534.54       2104370.8     13403024.54
       2104940.8     13402684.54       2105930.8     13402844.54
       2106010.8     13402584.54       2107110.8     13402194.54
       2107090.8     13401794.54      2107639.32     13401776.99
       2107910.8     13401134.54       2108060.8     13401314.54
       2108910.8     13400934.54       2109420.8     13401404.54
       2109720.8     13400154.54       2110480.8     13400834.54

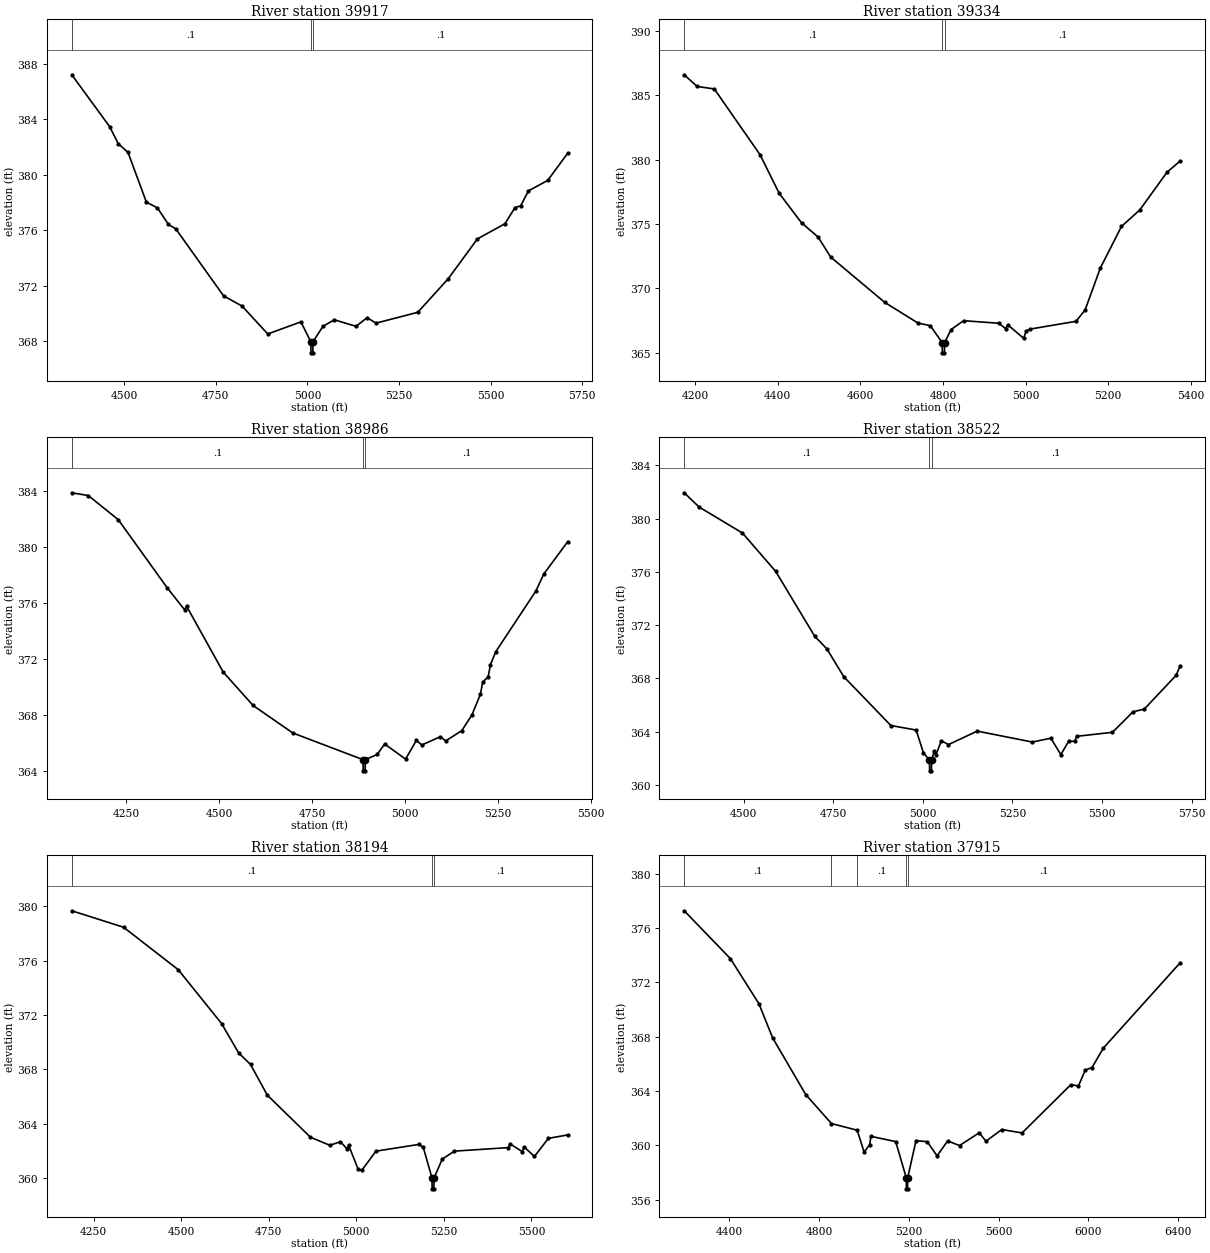
Type RM Length L Ch R = 1 ,39917   ,583,583,583
BEGIN DESCRIPTION:
Mapping XS 26f1d7fd
END DESCRIPTION:
XS GIS Cut Line= 3
      2085730.68     13401077.81      2085633.42      13399940.7
      2085524.46     13399759.38
#Sta/Elev= 30
    4357  387.19  4460.2  383.46  4483.8  382.23  4510.4   381.6  4560.5  378.02
  4590.7   377.6  4620.8  376.41  4640.8  376.09  4771.3  371.26  4821.5  370.53
  4891.8  368.52  4982.1  369.39  5009.2  367.96  5009.7  367.16  5014.7  367.16
  5015.2  367.96  5042.3  369.07  5073.2  369.54  5132.6  369.07  5162.7  369.69
  5187.1   369.3    5301  370.08  5383.5  372.48  5463.8  375.37  5538.9  376.46
  5566.1  377.62  5581.7  377.75    5603  378.83  5655.5  379.58  5709.8  381.53
#Mann= 3 ,-1 , 0
    4357      .1       0  5009.2     .07       0  5015.2      .1       0
Bank Sta=5009.2,5015.2
XS Rating Curve= 0 ,0
Exp/Cntr=0.3,0.1

Type RM Length L Ch R = 1 ,39334   ,348,348,348
BEGIN DESCRIPTION:
Mapping XS f35b7bae
END DESCRIPTION:
XS GIS Cut Line= 3
      2086143.57     13400897.42        2086068.     13400160.09
      2085853.92     13399754.51
#Sta/Elev= 30
    4174   386.6  4205.3  385.69  4246.8   385.5  4357.4  380.39  4403.9  377.38
  4457.9  375.09  4498.1  373.98  4528.3  372.43  4658.9  368.91  4739.4   367.3
  4769.5  367.09  4798.1  365.78  4798.6  364.98  4803.6  364.98  4804.1  365.78
  4819.8  366.79  4849.9  367.48  4935.1  367.28  4951.5  366.87  4957.1  367.15
  4995.5  366.11  5001.2  366.67  5011.4  366.83    5122  367.43    5144  368.31
    5181  371.58  5232.1  374.81  5276.1  376.08  5342.2  379.02  5373.8  379.89
#Mann= 3 ,-1 , 0
    4174      .1       0  4798.1     .07       0  4804.1      .1       0
Bank Sta=4798.1,4804.1
XS Rating Curve= 0 ,0
Exp/Cntr=0.3,0.1

Type RM Length L Ch R = 1 ,38986   ,464,464,464
BEGIN DESCRIPTION:
Mapping XS a949f6d2
END DESCRIPTION:
XS GIS Cut Line= 3
       2086441.7      13400789.4       2086357.2     13399979.32
       2086039.6     13399570.58
#Sta/Elev= 30
  4104.6  383.88  4149.2  383.68  4229.7  381.95  4360.4   377.1  4407.9   375.5
  4412.9  375.77  4511.4  371.05  4591.6  368.66  4698.3  366.69  4887.1  364.78
  4887.6  363.98  4892.6  363.98  4893.1  364.78  4924.9  365.15  4945.3   365.9
  5001.4  364.82  5030.4  366.16  5044.9  365.83  5094.6  366.42  5109.1  366.12
  5152.5  366.86  5179.7  367.98  5202.3  369.45  5208.7  370.34  5223.2   370.7
  5229.5  371.59    5244  372.52  5351.7  376.86  5372.5  378.06  5436.7  380.37
#Mann= 3 ,-1 , 0
  4104.6      .1       0  4887.1     .07       0  4893.1      .1       0
Bank Sta=4887.1,4893.1
XS Rating Curve= 0 ,0
Exp/Cntr=0.3,0.1

Type RM Length L Ch R = 1 ,38522   ,328,328,328
BEGIN DESCRIPTION:
Mapping XS 892a9735
END DESCRIPTION:
XS GIS Cut Line= 4
      2086574.89     13400685.97      2086663.93     13400052.95
      2086650.84     13399845.27      2086405.71     13399368.43
#Sta/Elev= 30
  4334.2  381.93  4375.8  380.86  4496.8  378.91  4589.5  376.03  4698.7  371.15
    4732  370.23  4779.5  368.13  4910.8  364.47  4981.4  364.13  5001.5  362.43
  5018.5  361.87    5019  361.07    5024  361.07  5024.5  361.87  5031.2  362.53
  5036.2  362.23  5051.6  363.33  5071.6  363.04  5151.8  364.05  5305.5  363.23
  5357.2  363.52    5385  362.29  5407.2   363.3  5423.8  363.28  5429.4  363.66
  5529.1  363.96  5586.6   365.5  5617.8   365.7  5706.5  368.23  5717.7  368.93
#Mann= 3 ,-1 , 0
  4334.2      .1       0  5018.5     .07       0  5024.5      .1       0
Bank Sta=5018.5,5024.5
XS Rating Curve= 0 ,0
Exp/Cntr=0.3,0.1

Type RM Length L Ch R = 1 ,38194   ,279,279,279
BEGIN DESCRIPTION:
Mapping XS d1107203
END DESCRIPTION:
XS GIS Cut Line= 4
      2086812.85     13400769.78      2086984.52      13400090.3
      2086935.05     13399794.26      2086826.36     13399394.24
#Sta/Elev= 30
  4187.9  379.66  4335.8  378.45  4491.9  375.33  4615.7  371.37  4664.1  369.22
  4698.2  368.37  4746.2  366.11  4869.4  363.02  4924.5  362.43  4954.9  362.69
  4973.5  362.17  4978.5  362.42  5005.6  360.66  5015.8  360.59  5056.3     362
    5178  362.49  5191.1   362.3  5216.2  360.03  5216.7  359.23  5221.7  359.23
  5222.2  360.03  5245.7  361.42  5280.3     362  5434.3  362.26  5439.5  362.53
  5474.1  361.96  5479.3  362.31  5508.7  361.61  5548.5  362.94  5603.4  363.19
#Mann= 3 ,-1 , 0
  4187.9      .1       0  5216.2     .07       0  5222.2      .1       0
Bank Sta=5216.2,5222.2
XS Rating Curve= 0 ,0
Exp/Cntr=0.3,0.1

Type RM Length L Ch R = 1 ,37915   ,398,398,398
BEGIN DESCRIPTION:
Mapping XS 0439d53e
END DESCRIPTION:
XS GIS Cut Line= 3
      2086964.24     13400707.96      2087236.91     13399961.32
      2087378.81     13398555.03
#Sta/Elev= 30
  4199.9  377.28  4405.3  373.76  4532.6  370.43  4593.6  367.92    4741  363.74
  4855.7   361.6  4970.2  361.11  5001.1   359.5  5025.9  360.05  5031.3  360.66
  5141.8  360.27  5189.1  357.59  5189.6  356.79  5194.6  356.79  5195.1  357.59
  5232.3  360.35  5282.5  360.26  5326.1  359.22    5373  360.32  5426.1  359.98
  5513.7  360.92  5543.9   360.3  5614.2  361.16  5704.7  360.91  5921.4  364.46
  5955.9  364.38  5986.1  365.54  6016.2  365.73  6066.5  367.16  6408.2  373.44
#Mann= 5 ,-1 , 0
  4199.9      .1       0  4855.7     .05       0  4970.2      .1       0
  5189.1     .07       0  5195.1      .1       0
Bank Sta=5189.1,5195.1
XS Rating Curve= 0 ,0
Exp/Cntr=0.3,0.1

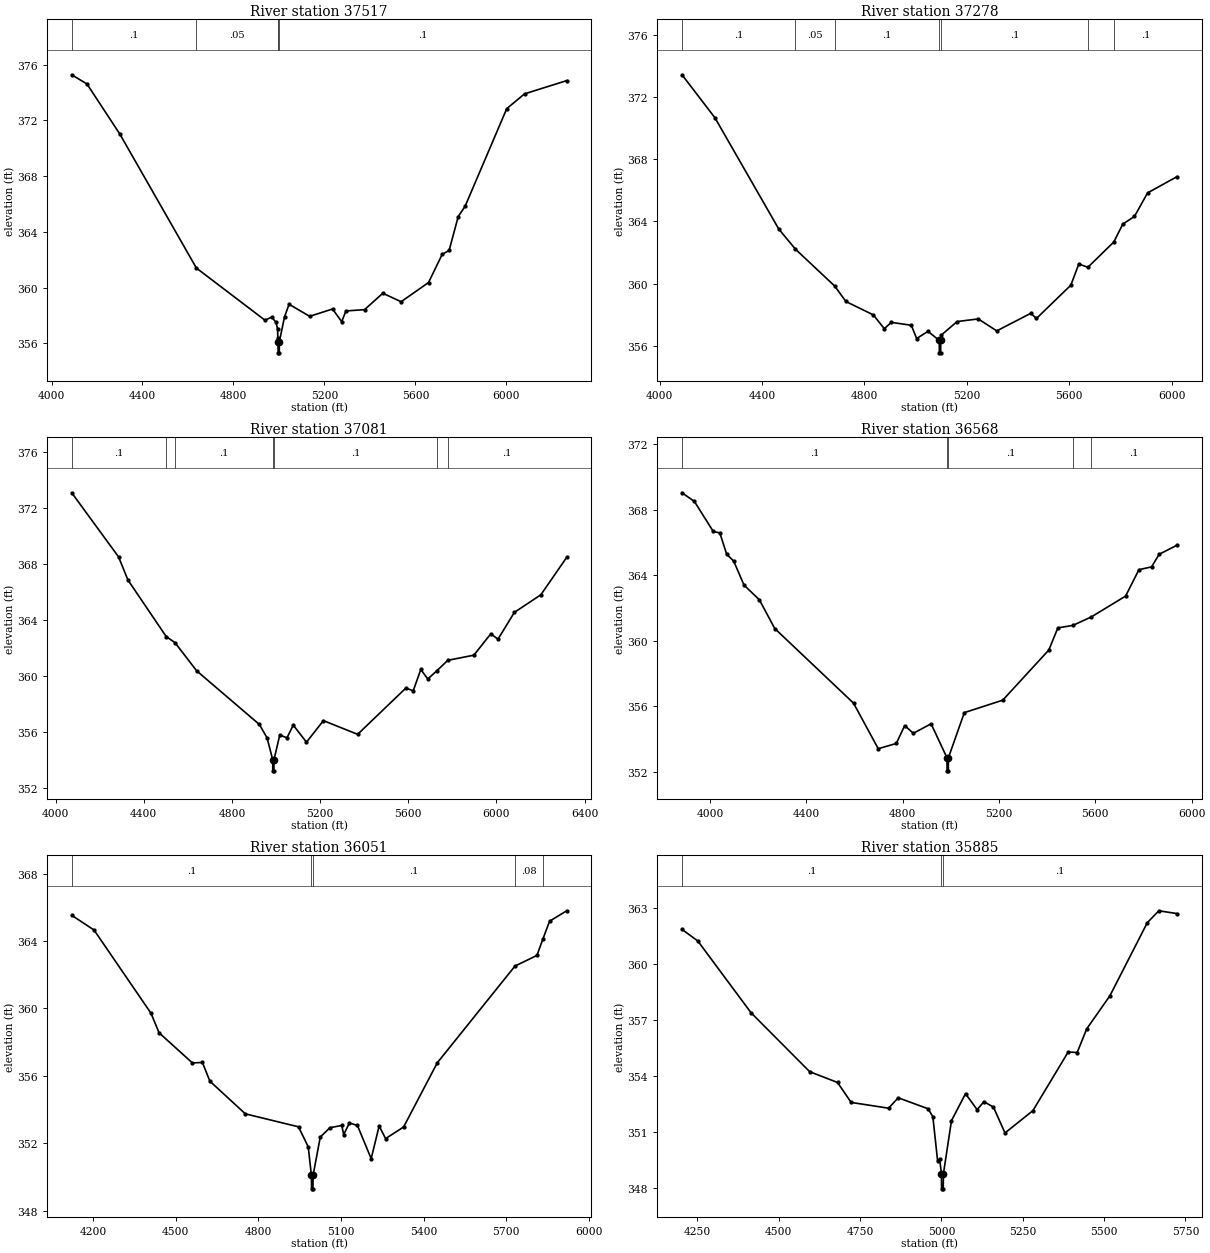
Type RM Length L Ch R = 1 ,37517   ,239,239,239
BEGIN DESCRIPTION:
Mapping XS a9a3d713
END DESCRIPTION:
XS GIS Cut Line= 3
      2087083.41     13400687.59      2087598.88     13399952.09
      2087726.61     13398680.74
#Sta/Elev= 30
  4088.9  375.28  4155.9  374.62  4299.7  371.04  4636.9   361.4  4938.7  357.65
  4968.4  357.88    4987  357.49  4993.7  357.04  4995.1  356.39  4995.7  356.11
  4996.2  355.31  5001.2  355.31  5001.7  356.11  5024.3  357.89  5044.4   358.8
  5134.9  357.93  5235.4  358.46  5275.6  357.55  5294.5  358.32  5376.1  358.41
  5456.5  359.59  5536.9  358.98  5657.5  360.36  5717.8  362.39  5747.9  362.66
  5788.1   365.1  5818.3  365.84  6001.4  372.85  6079.6  373.91  6264.8  374.86
#Mann= 5 ,-1 , 0
  4088.9      .1       0  4636.9     .05       0  4995.1      .1       0
  4995.7     .07       0  5001.7      .1       0
Bank Sta=4995.7,5001.7
XS Rating Curve= 0 ,0
Exp/Cntr=0.3,0.1

Type RM Length L Ch R = 1 ,37278   ,197,197,197
BEGIN DESCRIPTION:
Mapping XS a89997f9
END DESCRIPTION:
XS GIS Cut Line= 3
       2087248.3     13400708.83      2087827.82     13399994.34
      2088082.93     13399014.06
#Sta/Elev= 30
  4087.4  373.42  4215.9  370.66  4465.2  363.51  4530.5  362.21  4683.9  359.84
  4727.4  358.85  4834.4  357.99  4877.6   357.1  4904.8  357.51  4983.1  357.32
  5003.7  356.47    5048  356.93    5092  356.35  5092.5  355.55  5097.5  355.55
    5098  356.35  5100.1  356.69  5161.7  357.56  5244.3  357.73  5316.7  356.96
  5449.3  358.09  5471.7  357.76    5606   359.9    5637  361.26  5672.5  361.05
  5773.6  362.67  5808.8  363.82  5854.5  364.32  5905.7  365.83  6020.3  366.87
#Mann= 7 ,-1 , 0
  4087.4      .1       0  4530.5     .05       0  4683.9      .1       0
    5092     .07       0    5098      .1       0  5672.5     .05       0
  5773.6      .1       0
Bank Sta=5092,5098
XS Rating Curve= 0 ,0
Exp/Cntr=0.3,0.1

Type RM Length L Ch R = 1 ,37081   ,513,513,513
BEGIN DESCRIPTION:
Live Oak Creek 58.0
END DESCRIPTION:
XS GIS Cut Line= 3
      2087274.98     13400725.02        2087975.       13400125.
      2088528.25     13398922.33
#Sta/Elev= 30
  4073.3  373.09  4285.7  368.51  4328.5  366.85    4502  362.81  4541.6  362.38
  4640.2  360.36  4924.5  356.53  4959.6  355.57  4985.1  354.01  4985.6  353.21
  4990.6  353.21  4991.1  354.01  5017.3  355.77    5050  355.57  5078.4  356.48
  5138.4  355.26  5215.4   356.8  5370.6  355.82  5589.7  359.13  5622.7  358.93
  5657.3  360.46  5688.7  359.78  5729.3  360.35  5779.5  361.11    5898  361.48
  5974.9  363.01  6007.3  362.62  6081.8  364.54  6202.1   365.8  6319.1  368.47
#Mann= 7 ,-1 , 0
  4073.3      .1       0    4502     .05       0  4541.6      .1       0
  4985.1     .07       0  4991.1      .1       0  5729.3     .05       0
  5779.5      .1       0
Bank Sta=4985.1,4991.1
XS Rating Curve= 0 ,0
Exp/Cntr=0.3,0.1

Type RM Length L Ch R = 1 ,36568   ,517,517,517
BEGIN DESCRIPTION:
Mapping XS 123dc8a7
END DESCRIPTION:
XS GIS Cut Line= 4
      2087694.93     13400866.78      2088233.09     13400422.36
      2088371.98     13400175.83      2088705.32     13399154.98
#Sta/Elev= 30
  3884.2  369.02  3935.8  368.49    4014  366.66  4041.3  366.57    4070  365.26
  4098.6  364.86  4141.6  363.39  4205.5  362.49  4269.3  360.74  4596.3  356.19
  4698.9  353.41    4774  353.73  4808.7  354.82  4844.8  354.35  4918.2  354.93
  4984.2  352.86  4984.7  352.06  4989.8  352.06  4990.3  352.86  5056.3  355.61
  5215.7  356.37  5407.1  359.43  5444.6  360.78  5506.8  360.93  5583.8  361.45
  5725.9  362.72  5781.2  364.33  5833.8   364.5  5865.3  365.27    5939  365.82
#Mann= 5 ,-1 , 0
  3884.2      .1       0  4984.2     .07       0  4990.3      .1       0
  5506.8     .05       0  5583.8      .1       0
Bank Sta=4984.2,4990.3
XS Rating Curve= 0 ,0
Exp/Cntr=0.3,0.1

Type RM Length L Ch R = 1 ,36051   ,166,166,166
BEGIN DESCRIPTION:
Mapping XS 40b43fb5
END DESCRIPTION:
XS GIS Cut Line= 4
      2088028.21     13401040.43      2088396.29     13400769.58
      2088812.96     13400227.92      2088976.15     13399592.51
#Sta/Elev= 30
  4122.6  365.52  4203.5  364.65  4410.3  359.71  4439.6  358.55  4560.7  356.76
  4596.9  356.79    4624  355.68  4752.7  353.74  4945.7  352.97    4981  351.78
  4992.5  350.09    4993  349.29  4998.1  349.29  4998.6  350.09  5024.6  352.36
  5059.9  352.92  5102.6  353.05  5109.7  352.51  5130.6   353.2  5159.6  353.05
  5209.4  351.08  5238.4  353.02  5261.7  352.27  5327.1  352.96  5449.4  356.77
  5731.4  362.51    5811  363.14  5832.4   364.1  5856.9  365.17    5919  365.79
#Mann= 5 ,-1 , 0
  4122.6      .1       0  4992.5     .07       0  4998.6      .1       0
  5731.4     .08       0  5832.4      .1       0
Bank Sta=4992.5,4998.6
XS Rating Curve= 0 ,0
Exp/Cntr=0.3,0.1

Type RM Length L Ch R = 1 ,35885   ,286,286,286
BEGIN DESCRIPTION:
Mapping XS 437e9a0a
END DESCRIPTION:
XS GIS Cut Line= 2
      2088326.81     13401134.21      2089222.66     13399905.02
#Sta/Elev= 30
  4202.9  361.86  4251.4  361.24  4415.3  357.38  4595.3  354.22    4681  353.64
  4722.7  352.57  4837.8  352.26  4867.2  352.82  4959.1  352.23  4973.8   351.8
  4988.5  349.42  4994.7  349.55  5000.1  348.73  5000.6  347.93  5005.7  347.93
  5006.2  348.73    5031  351.59  5074.2  353.04  5109.8  352.18  5130.6  352.61
    5160  352.32  5195.5  350.93  5281.3  352.13  5389.8  355.28  5417.3  355.25
  5446.6  356.52  5517.7  358.29  5632.8  362.22  5668.3  362.86  5723.9  362.71
#Mann= 3 ,-1 , 0
  4202.9      .1       0  5000.1     .07       0  5006.2      .1       0
Bank Sta=5000.1,5006.2
XS Rating Curve= 0 ,0
Exp/Cntr=0.3,0.1

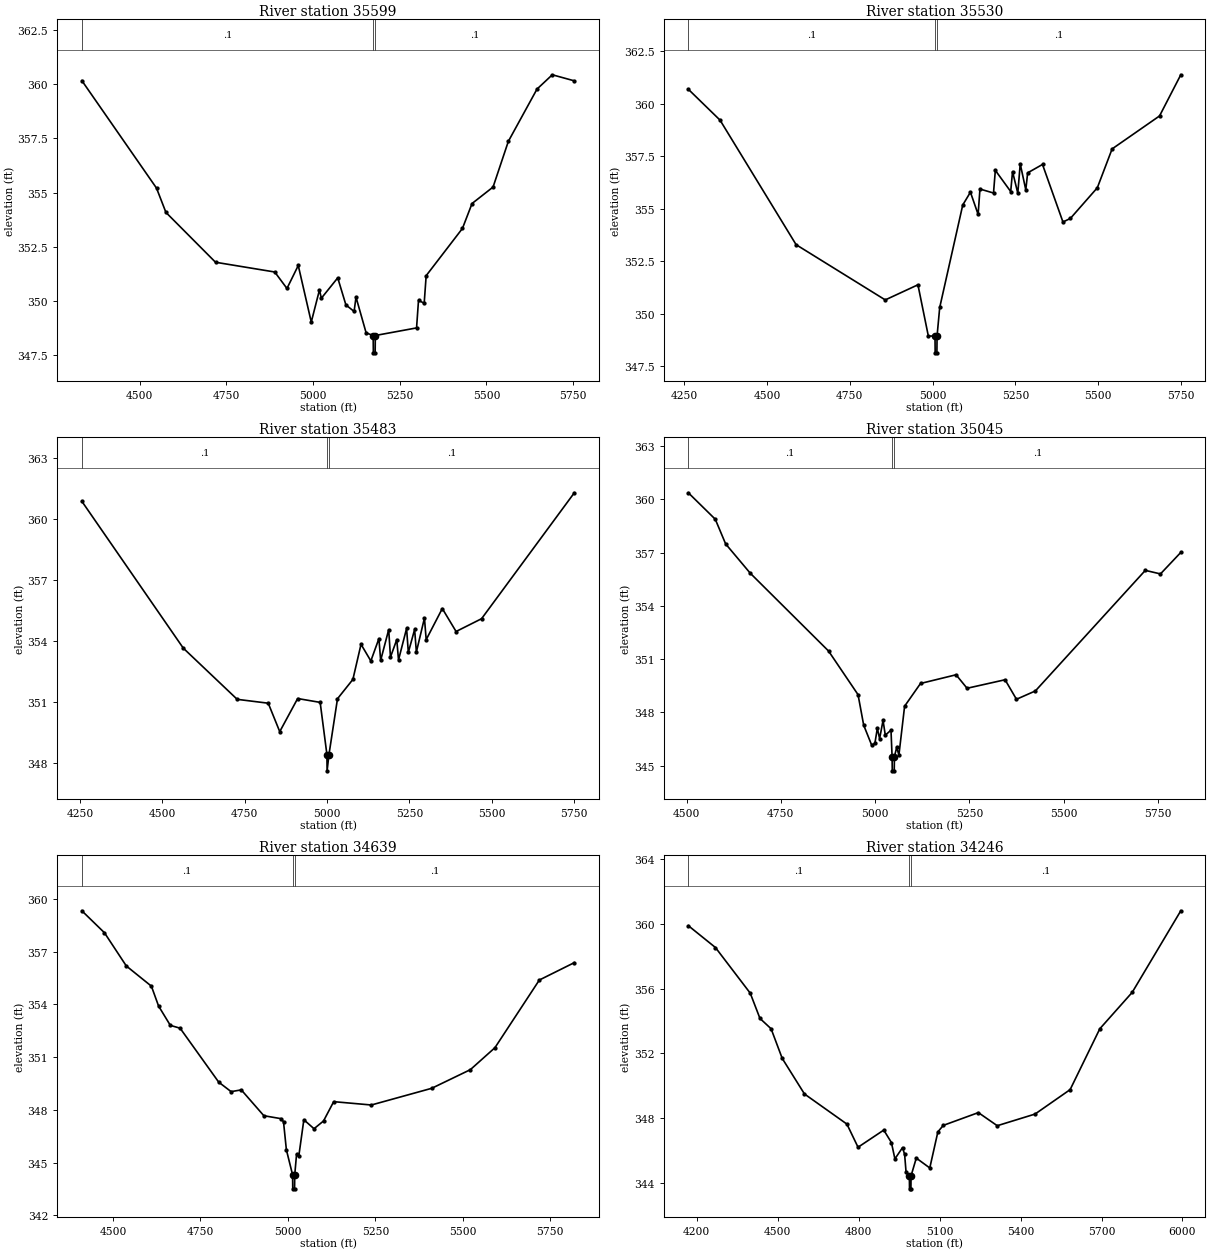
Type RM Length L Ch R = 1 ,35599   ,69,69,69
BEGIN DESCRIPTION:
Mapping XS 25a17667
END DESCRIPTION:
XS GIS Cut Line= 4
      2088542.09     13401172.39      2088833.79     13400953.61
      2089024.76     13400505.69      2089288.65     13400002.21
#Sta/Elev= 30
  4333.5  360.17  4548.8  355.21  4575.9  354.09  4718.9  351.79  4889.7  351.34
  4924.9  350.58  4957.5  351.64    4995  349.03  5018.6  350.51  5024.1  350.13
  5071.3  351.07  5094.9  349.82  5118.5  349.52    5124  350.18  5153.2  348.53
  5173.5  348.41    5174  347.61  5179.2  347.61  5179.7  348.41  5298.6  348.76
  5304.2  350.03  5320.6   349.9  5326.3  351.17  5430.9  353.35  5458.6   354.5
  5519.2  355.26  5563.3  357.37  5645.9  359.78    5690  360.44  5753.5  360.16
#Mann= 3 ,-1 , 0
  4333.5      .1       0  5173.5     .07       0  5179.7      .1       0
Bank Sta=5173.5,5179.7
XS Rating Curve= 0 ,0
Exp/Cntr=0.3,0.1

Type RM Length L Ch R = 1 ,35530   ,47,47,47
BEGIN DESCRIPTION:
Mapping XS 55c93c34
END DESCRIPTION:
XS GIS Cut Line= 4
      2088559.52     13401224.42      2088871.98      13400991.8
      2089118.51     13400439.72      2089336.94     13399999.39
#Sta/Elev= 30
    4263  360.68  4358.7  359.21  4588.2  353.28  4857.1  350.65  4955.7  351.37
  4987.1  348.93  5007.2  348.93  5007.7  348.13  5012.9  348.13  5013.4  348.93
  5021.4  350.29  5090.9  355.17  5114.1  355.78  5137.3  354.72  5142.8  355.93
  5183.7  355.74  5189.2  356.82  5235.6  355.81  5241.1  356.76    5257  355.73
  5264.3  357.13  5281.1  355.89  5286.7   356.7  5331.5   357.1  5393.2  354.36
  5415.6  354.53  5496.9  355.99  5541.5  357.84  5684.6  359.41  5748.7  361.37
#Mann= 3 ,-1 , 0
    4263      .1       0  5007.2     .07       0  5013.4      .1       0
Bank Sta=5007.2,5013.4
XS Rating Curve= 0 ,0
Exp/Cntr=0.3,0.1

Type RM Length L Ch R = 1 ,35483   ,438,438,438
BEGIN DESCRIPTION:
Mapping XS f0c9a534
END DESCRIPTION:
XS GIS Cut Line= 5
      2088583.76     13401234.88      2088899.76     13401050.83
      2089080.32     13400630.69       2089194.9     13400339.03
      2089360.66     13400021.32
#Sta/Elev= 30
  4255.7  360.88  4563.6  353.65  4727.2  351.13  4821.4  350.94  4856.3  349.54
  4910.7  351.17    4979  350.98  4999.5  348.41    5000  347.61  5005.7  348.41
  5031.6  351.16  5078.3  352.11    5103  353.84  5132.8  353.02  5157.3  354.12
  5162.6  353.05    5187  354.56  5192.4  353.21  5211.5  354.07  5216.8  353.07
  5241.3  354.62  5246.6  353.44  5265.7  354.57    5271  353.46  5295.5  355.13
  5300.8  354.07  5349.7   355.6  5391.5  354.47  5468.9   355.1  5750.4   361.3
#Mann= 3 ,-1 , 0
  4255.7      .1       0  4999.5     .07       0  5005.7      .1       0
Bank Sta=4999.5,5005.7
XS Rating Curve= 0 ,0
Exp/Cntr=0.3,0.1

Type RM Length L Ch R = 1 ,35045   ,406,406,406
BEGIN DESCRIPTION:
Mapping XS 2ae9a7e1
END DESCRIPTION:
XS GIS Cut Line= 4
      2088781.75     13401286.92      2089083.79     13401120.28
      2089316.43     13400766.11      2089371.98     13400231.39
#Sta/Elev= 30
  4504.6  360.37  4576.1  358.88  4603.6  357.49  4668.9  355.84  4876.5  351.46
  4954.8     349  4969.8  347.28  4990.9  346.16  4999.4  346.25    5006  347.11
    5012  346.52  5021.1  347.55  5027.1  346.72  5042.2     347  5045.1  345.51
  5045.6  344.71  5050.8  344.71  5051.3  345.51  5057.3  346.03  5063.2   345.6
  5078.3  348.35  5120.5  349.63  5214.8  350.12    5244  349.36  5344.8  349.84
    5375  348.74  5425.2  349.21  5716.8     356    5757   355.8  5810.9  357.01
#Mann= 3 ,-1 , 0
  4504.6      .1       0  5045.1     .07       0  5051.3      .1       0
Bank Sta=5045.1,5051.3
XS Rating Curve= 0 ,0
Exp/Cntr=0.3,0.1

Type RM Length L Ch R = 1 ,34639   ,393,393,393
BEGIN DESCRIPTION:
Mapping XS 0dba3142
END DESCRIPTION:
XS GIS Cut Line= 4
      2088931.05     13401325.13      2089285.18     13401245.28
      2089660.18     13400960.55      2089611.67     13400388.86
#Sta/Elev= 30
  4411.2  359.33  4475.8  358.08  4538.3  356.19    4610  355.04  4630.5  353.91
  4664.1  352.81    4692  352.65  4802.4  349.58  4837.8  349.04  4866.9  349.14
  4931.4  347.67  4981.3   347.5  4987.6  347.32  4995.8  345.73  5013.5  344.31
    5014  343.51  5019.2  343.51  5019.7  344.31  5024.9  345.48  5031.2  345.36
  5045.7  347.44  5074.8  346.93  5101.9  347.37    5131  348.47  5238.6  348.28
  5411.2  349.23  5521.6  350.29  5591.9  351.54  5718.8  355.39  5818.8  356.38
#Mann= 3 ,-1 , 0
  4411.2      .1       0  5013.5     .07       0  5019.7      .1       0
Bank Sta=5013.5,5019.7
XS Rating Curve= 0 ,0
Exp/Cntr=0.3,0.1

Type RM Length L Ch R = 1 ,34246   ,683,683,683
BEGIN DESCRIPTION:
Live Oak Creek 52.0
END DESCRIPTION:
XS GIS Cut Line= 3
      2088974.98       13401475.        2089775.       13401275.
        2089775.     13400275.04
#Sta/Elev= 30
  4169.1  359.89  4269.6  358.54  4398.5  355.72  4434.5  354.16  4475.8  353.52
    4517  351.69  4599.5  349.49  4756.7  347.63  4797.9   346.2  4893.2  347.26
  4921.6  346.49  4934.5  345.48  4962.8  346.18  4970.5  345.76  4975.7  344.69
  4988.1  344.43  4988.6  343.63  4993.8  343.63  4994.3  344.43  5013.7  345.53
  5063.7  344.92  5093.7  347.15  5113.7  347.55  5243.7  348.34  5313.7  347.53
  5453.7  348.25  5583.7  349.76  5693.7  353.52  5813.7  355.77  5993.7  360.81
#Mann= 3 ,-1 , 0
  4169.1      .1       0  4988.1     .07       0  4994.3      .1       0
Bank Sta=4988.1,4994.3
XS Rating Curve= 0 ,0
Exp/Cntr=0.3,0.1

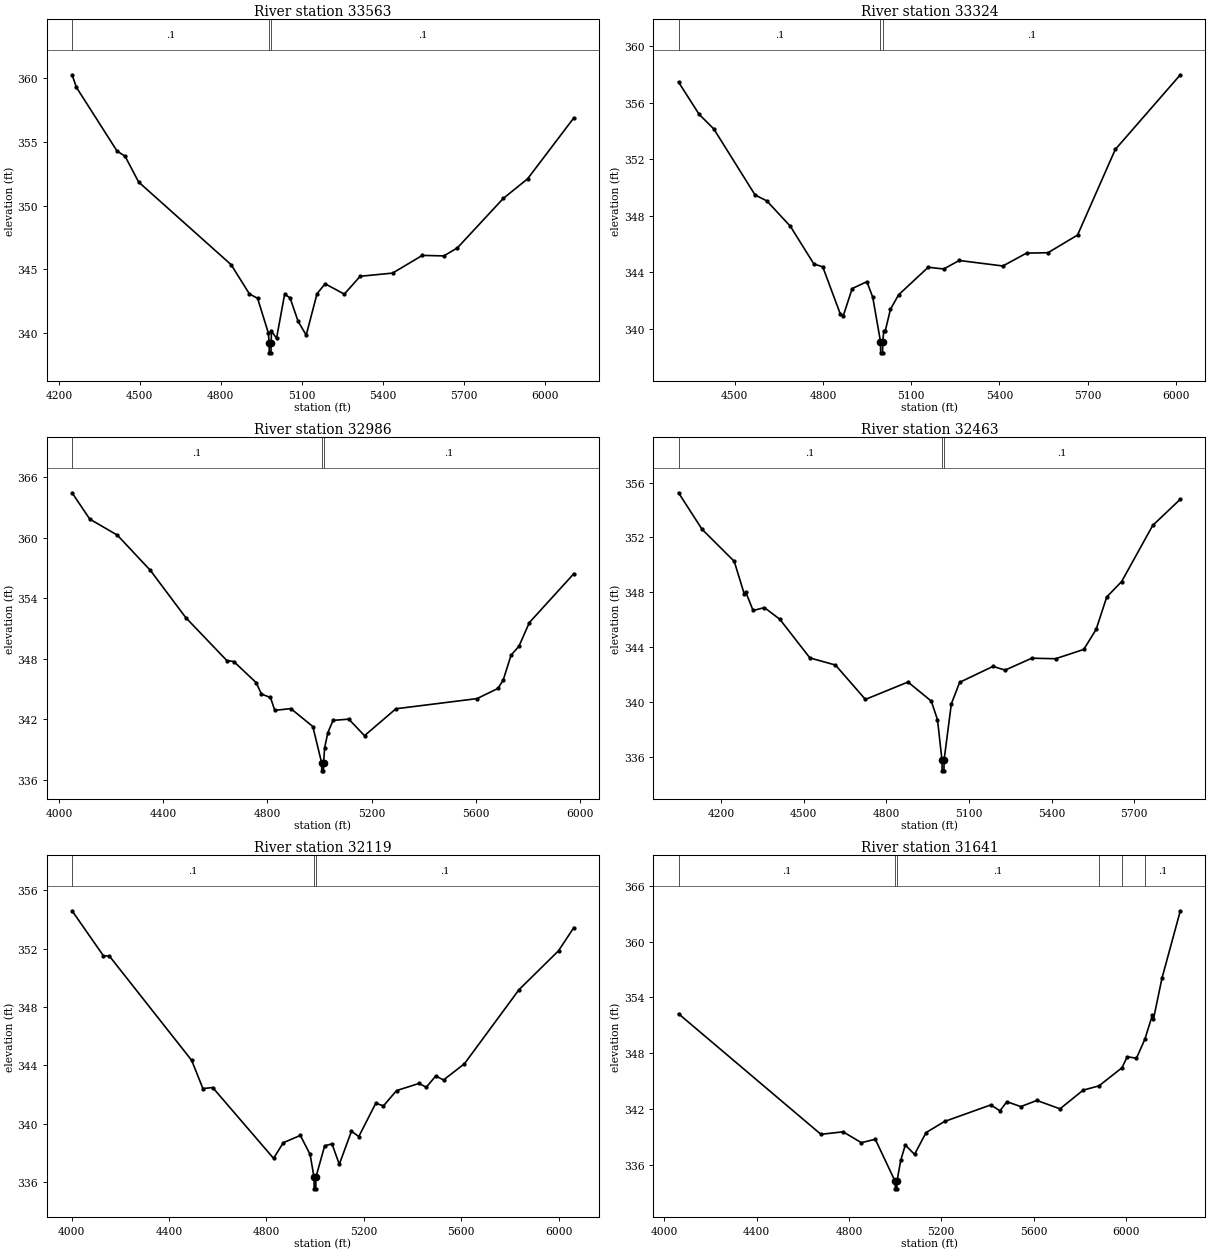
Type RM Length L Ch R = 1 ,33563   ,239,239,239
BEGIN DESCRIPTION:
Live Oak Creek 51.0
END DESCRIPTION:
XS GIS Cut Line= 3
      2090080.53     13402321.14      2090132.62     13401548.55
      2090167.34     13400463.45
#Sta/Elev= 30
  4248.8  360.27    4265  359.28  4415.3  354.29  4445.4  353.87  4495.5  351.85
  4838.4  345.36  4906.4  343.06  4936.5  342.72  4976.6  339.98  4979.1  339.24
  4979.7  338.44  4986.1  338.44  4986.8  339.24  4987.9  340.16  5006.7  339.57
  5036.7  343.04  5056.7  342.76  5086.7  340.91  5116.7  339.83  5156.8  343.08
  5186.8  343.86  5257.9  343.05  5316.8  344.45  5436.9   344.7    5547  346.09
    5627  346.05    5677  346.68  5847.1  350.56  5937.2   352.1  6108.8  356.89
#Mann= 3 ,-1 , 0
  4248.8      .1       0  4979.1     .07       0  4986.8      .1       0
Bank Sta=4979.1,4986.8
XS Rating Curve= 0 ,0
Exp/Cntr=0.3,0.1

Type RM Length L Ch R = 1 ,33324   ,338,338,338
BEGIN DESCRIPTION:
Live Oak Creek 50.0
END DESCRIPTION:
XS GIS Cut Line= 3
        2090325.     13402175.04        2090325.       13401475.
        2090425.     13400475.03
#Sta/Elev= 30
  4309.5  357.45  4379.5  355.17  4429.5  354.13  4569.5  349.46  4609.5  349.04
  4689.5  347.24  4769.5  344.57  4799.5  344.37  4859.5  341.01  4869.5  340.92
  4899.5  342.83  4949.5  343.32  4969.5  342.21  4995.7  339.08  4996.3  338.28
  5002.8  338.28  5003.4  339.08    5007  339.85  5012.1  339.85  5029.6  341.37
  5057.3  342.39  5157.8  344.34  5210.5  344.22  5263.3  344.82  5411.5  344.43
  5491.9  345.34  5564.8  345.37  5665.3  346.62  5793.4  352.68  6014.5  357.97
#Mann= 3 ,-1 , 0
  4309.5      .1       0  4995.7     .07       0  5003.4      .1       0
Bank Sta=4995.7,5003.4
XS Rating Curve= 0 ,0
Exp/Cntr=0.3,0.1

Type RM Length L Ch R = 1 ,32986   ,523,523,523
BEGIN DESCRIPTION:
Live Oak Creek 49.0
END DESCRIPTION:
XS GIS Cut Line= 3
        2090425.       13402475.        2090625.       13401575.
        2090525.     13400575.04
#Sta/Elev= 30
  4049.6  364.46  4117.5  361.85  4223.7  360.25  4350.5  356.75  4486.2  352.07
  4643.7  347.81  4670.6  347.71  4756.4  345.62  4776.9  344.48  4811.5  344.14
  4828.1  342.86  4889.6  343.04  4974.1  341.26  5007.9  337.66  5008.5  336.86
    5015  336.86  5015.6  337.66  5019.3  339.13  5031.9  340.66    5052  341.87
  5112.3  341.99  5172.6  340.35  5293.1  343.02  5604.7  344.03  5685.1  345.04
  5705.2  345.87  5735.3  348.34  5765.5  349.22  5805.7  351.58  5976.5  356.43
#Mann= 3 ,-1 , 0
  4049.6      .1       0  5007.9     .07       0  5015.6      .1       0
Bank Sta=5007.9,5015.6
XS Rating Curve= 0 ,0
Exp/Cntr=0.3,0.1

Type RM Length L Ch R = 1 ,32463   ,344,344,344
BEGIN DESCRIPTION:
Mapping XS 290adef5
END DESCRIPTION:
XS GIS Cut Line= 4
      2090861.79      13402277.7      2090978.97     13401804.63
      2090883.48     13400966.96      2090701.19     13400511.23
#Sta/Elev= 30
  4045.6  355.25  4130.8  352.59  4247.7  350.25  4283.9  347.88  4289.1  348.03
  4316.2  346.66  4357.4  346.87  4413.3  346.02  4522.3   343.2  4615.2  342.68
  4723.8  340.17  4878.4  341.44  4962.9  340.05  4985.5  338.69  5001.7  335.76
  5002.4  334.96  5008.9  334.96  5009.5  335.76  5035.8  339.85    5066  341.42
  5186.8  342.58  5231.2  342.31  5327.7  343.18  5414.1  343.14  5516.4  343.82
  5561.3  345.28  5599.9  347.65  5653.8  348.77  5766.8  352.87  5866.9  354.78
#Mann= 3 ,-1 , 0
  4045.6      .1       0  5001.7     .07       0  5009.5      .1       0
Bank Sta=5001.7,5009.5
XS Rating Curve= 0 ,0
Exp/Cntr=0.3,0.1

Type RM Length L Ch R = 1 ,32119   ,478,478,478
BEGIN DESCRIPTION:
Mapping XS 778de929
END DESCRIPTION:
XS GIS Cut Line= 4
      2091122.19     13402347.21      2091200.32     13401787.27
      2091200.32     13401092.82      2090909.52     13400346.28
#Sta/Elev= 30
  4001.9  354.59  4130.5  351.51  4155.6  351.48  4493.2  344.34  4539.3  342.41
  4579.5  342.48  4829.5  337.63  4869.5   338.7  4939.5   339.2  4979.5   337.9
  4995.6  336.34  4996.3  335.54  5002.8  335.54  5003.4  336.34  5039.5  338.49
  5069.5  338.62  5099.5  337.22  5149.5  339.49  5179.5  339.12  5249.5  341.41
  5280.8  341.22  5334.5  342.27  5426.8  342.76  5456.7   342.5  5495.5  343.27
  5527.7     343  5613.5  344.11  5837.4  349.18  5999.9  351.85  6062.9  353.44
#Mann= 3 ,-1 , 0
  4001.9      .1       0  4995.6     .07       0  5003.4      .1       0
Bank Sta=4995.6,5003.4
XS Rating Curve= 0 ,0
Exp/Cntr=0.3,0.1

Type RM Length L Ch R = 1 ,31641   ,450,450,450
BEGIN DESCRIPTION:
Mapping XS 8171faec
END DESCRIPTION:
XS GIS Cut Line= 4
      2091417.33     13402251.72      2091560.57     13401600.64
      2091547.55     13400650.12       2091499.9     13400095.72
#Sta/Elev= 30
    4062  352.25  4678.8  339.29  4774.7  339.56  4854.3  338.39  4914.3  338.76
  5000.4  334.23    5001  333.43  5007.6  333.43  5008.3  334.23  5024.3  336.48
  5044.3  338.14  5084.3  337.13  5134.3  339.48  5214.3  340.67  5414.4  342.45
  5454.4  341.82  5484.4   342.8  5544.4  342.27  5614.4  342.93  5714.5  342.03
  5814.9  344.04  5883.4   344.5  5982.7  346.44  6005.8  347.63  6045.7  347.47
    6082  349.51  6114.4  352.08  6119.4  351.69  6156.1  356.06  6235.7  363.32
#Mann= 6 ,-1 , 0
    4062      .1       0  5000.4     .07       0  5008.3      .1       0
  5883.4     .08       0  5982.7     .05       0    6082      .1       0
Bank Sta=5000.4,5008.3
XS Rating Curve= 0 ,0
Exp/Cntr=0.3,0.1

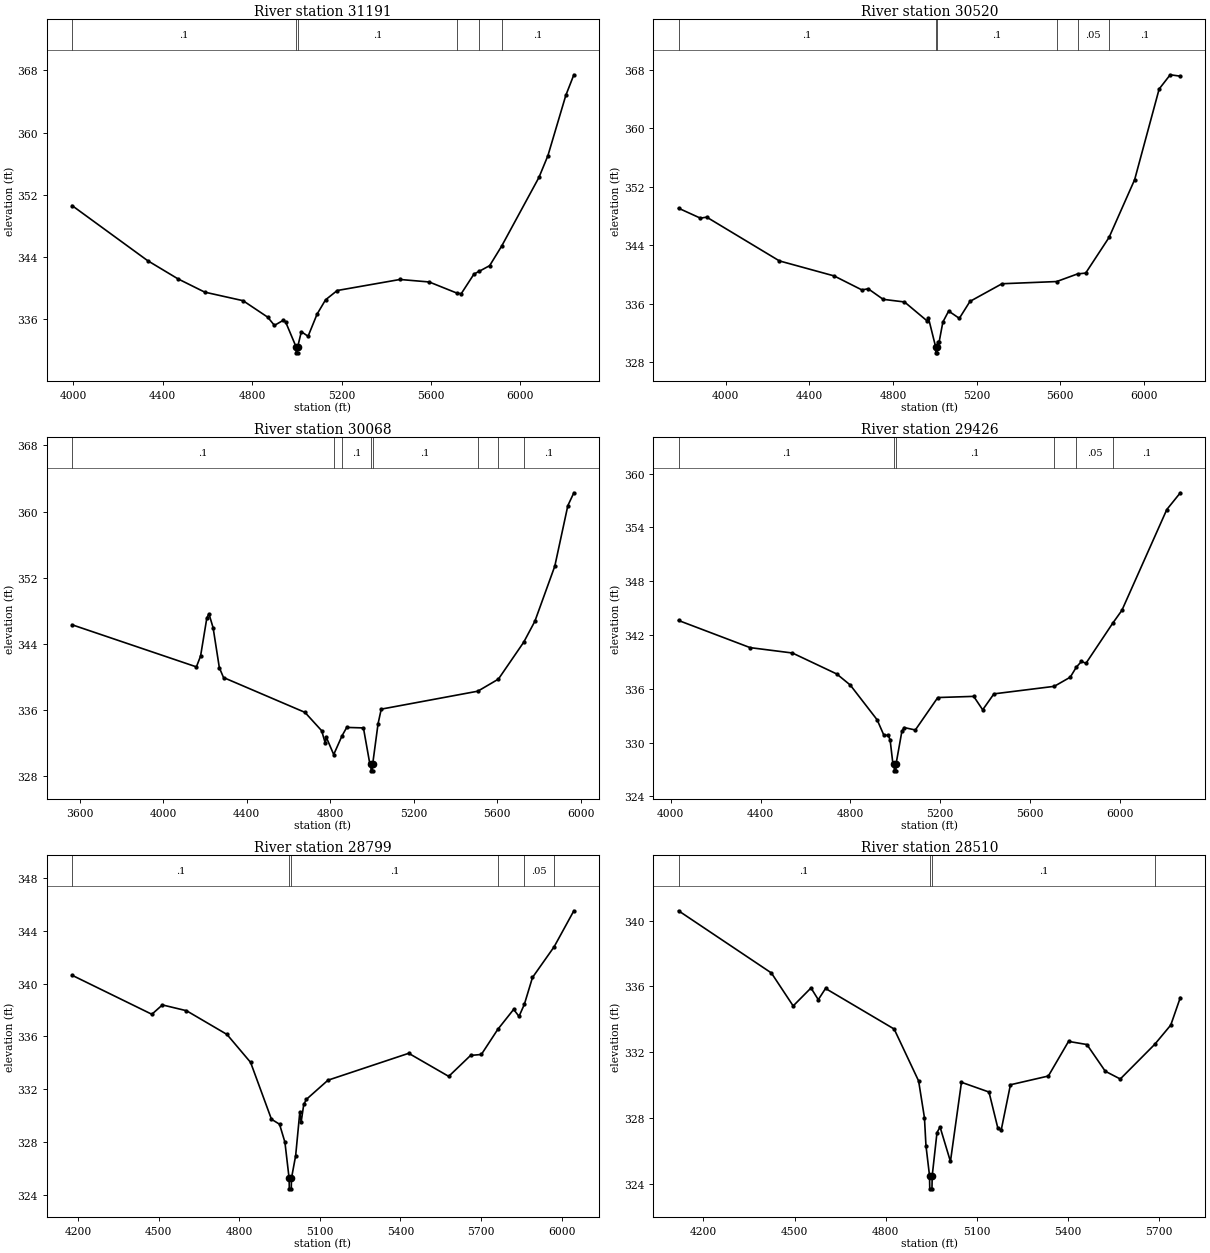
Type RM Length L Ch R = 1 ,31191   ,671,671,671
BEGIN DESCRIPTION:
Mapping XS fc242821
END DESCRIPTION:
XS GIS Cut Line= 4
      2091699.47     13402251.63      2091881.75     13401665.74
      2091964.21     13400541.61      2091994.54     13400039.07
#Sta/Elev= 30
    3995   350.6  4332.6  343.52    4468  341.18  4588.4  339.46  4759.7  338.36
    4870  336.24  4900.1  335.18  4940.2  335.85  4950.2  335.62  4996.4  332.45
  4997.1  331.65  5003.7  331.65  5004.3  332.45  5020.4  334.37  5050.5  333.78
  5090.6  336.62  5128.6  338.47  5180.9  339.67  5461.6  341.09    5592  340.77
  5718.5  339.31  5735.7  339.27  5792.5  341.79  5817.1  342.16  5862.6  342.87
  5915.8  345.36    6083  354.22  6123.1  357.02  6203.2  364.78  6239.2  367.43
#Mann= 6 ,-1 , 0
    3995      .1       0  4996.4     .07       0  5004.3      .1       0
  5718.5     .08       0  5817.1     .05       0  5915.8      .1       0
Bank Sta=4996.4,5004.3
XS Rating Curve= 0 ,0
Exp/Cntr=0.3,0.1

Type RM Length L Ch R = 1 ,30520   ,452,452,452
BEGIN DESCRIPTION:
Mapping XS 40d7ed35
END DESCRIPTION:
XS GIS Cut Line= 4
      2091816.65     13402342.82      2092207.27     13401739.53
       2092415.6     13400697.86      2092528.44     13400090.25
#Sta/Elev= 30
  3775.2  349.05  3879.8  347.69  3909.9  347.83  4257.4  341.85  4518.9   339.8
  4651.5  337.89  4682.1  338.04  4753.5   336.6  4855.5  336.24  4964.6  333.63
  4969.7  334.09  5004.5  330.09  5005.1  329.29  5011.7  329.29  5012.4  330.09
  5015.6  330.76  5020.7  330.72    5039   333.5  5066.6     335  5117.6     334
  5168.6  336.32  5321.6  338.73  5582.9  339.03  5682.6  340.07  5721.8  340.19
  5833.5  345.06  5955.8  352.95    6073  365.34  6125.8  367.28  6174.2  367.09
#Mann= 6 ,-1 , 0
  3775.2      .1       0  5004.5     .07       0  5012.4      .1       0
  5582.9     .08       0  5682.6     .05       0  5833.5      .1       0
Bank Sta=5004.5,5012.4
XS Rating Curve= 0 ,0
Exp/Cntr=0.3,0.1

Type RM Length L Ch R = 1 ,30068   ,642,642,642
BEGIN DESCRIPTION:
Mapping XS 65307d2f
END DESCRIPTION:
XS GIS Cut Line= 4
      2092584.87     13402620.64      2092571.85     13401622.34
      2092615.26     13400467.82      2092654.32     13400220.41
#Sta/Elev= 30
  3563.5  346.32  4159.2  341.23  4179.2  342.54  4209.2  347.14  4219.2  347.65
  4239.2  345.97  4269.2  341.12  4289.2  339.94  4679.3  335.73  4759.4  333.51
  4776.6  332.01  4781.6  332.72  4817.1  330.63    4857   332.9  4879.5  333.91
  4959.5  333.85  4989.5   329.6  4995.3  329.46  4996.1  328.66    5003  328.66
  5003.7  329.46  5029.6  334.36  5044.8  336.12  5507.5  338.29  5606.1  339.75
  5727.6  344.22  5780.8  346.74  5876.4  353.41  5938.9  360.73  5967.7  362.28
#Mann= 8 ,-1 , 0
  3563.5      .1       0  4817.1     .05       0    4857      .1       0
  4995.3     .07       0  5003.7      .1       0  5507.5     .08       0
  5606.1     .05       0  5727.6      .1       0
Bank Sta=4995.3,5003.7
XS Rating Curve= 0 ,0
Exp/Cntr=0.3,0.1

Type RM Length L Ch R = 1 ,29426   ,627,627,627
BEGIN DESCRIPTION:
Mapping XS 11ffca62
END DESCRIPTION:
XS GIS Cut Line= 3
      2092728.12     13402429.58      2092927.76     13401782.93
      2092940.78     13400224.75
#Sta/Elev= 30
  4034.2  343.62    4353  340.59  4541.4  339.99  4738.9  337.65  4798.9  336.42
  4918.9  332.53  4948.9  330.81  4968.9   330.8  4976.8  330.25  4988.9  327.65
  4994.5  327.64  4995.3  326.84  5002.5  326.84  5003.3  327.64  5028.9  331.24
  5038.9  331.67  5088.9   331.4  5188.9  335.02  5348.9  335.15  5388.9  333.65
  5438.9  335.43  5707.7  336.27  5778.9  337.29  5806.3  338.42  5828.9  339.05
  5848.9  338.84  5967.4  343.29  6008.9  344.75    6209     356  6269.2  357.87
#Mann= 6 ,-1 , 0
  4034.2      .1       0  4994.5     .07       0  5003.3      .1       0
  5707.7     .08       0  5806.3     .05       0  5967.4      .1       0
Bank Sta=4994.5,5003.3
XS Rating Curve= 0 ,0
Exp/Cntr=0.3,0.1

Type RM Length L Ch R = 1 ,28799   ,289,289,289
BEGIN DESCRIPTION:
Mapping XS a11f4dfd
END DESCRIPTION:
XS GIS Cut Line= 3
      2092988.52     13402316.78       2093244.6     13401800.29
      2093175.15     13400511.24
#Sta/Elev= 30
    4178  340.64  4474.9  337.68  4514.1  338.39  4603.8  337.95  4754.5  336.15
  4842.4  334.03    4920  329.72  4950.1  329.34  4970.1  327.98  4985.7  325.24
  4986.5  324.44  4993.7  324.44  4994.5  325.24  5010.1  326.96  5025.5  330.25
  5030.5   329.5  5040.2  330.84  5050.2  331.23  5130.3  332.68  5430.8  334.72
  5579.7  332.97  5661.1  334.56  5701.1  334.63  5762.1  336.53  5821.3  338.05
  5841.3  337.52  5861.1  338.43  5891.4  340.47    5972   342.8  6045.4  345.53
#Mann= 6 ,-1 , 0
    4178      .1       0  4985.7     .07       0  4994.5      .1       0
  5762.1     .08       0  5861.1     .05       0    5972      .1       0
Bank Sta=4985.7,4994.5
XS Rating Curve= 0 ,0
Exp/Cntr=0.3,0.1

Type RM Length L Ch R = 1 ,28510   ,385,385,385
BEGIN DESCRIPTION:
Mapping XS 6d34ce60
END DESCRIPTION:
XS GIS Cut Line= 3
      2093175.16     13402416.58      2093418.21     13401826.33
      2093544.04     13400819.69
#Sta/Elev= 30
    4118  340.59  4423.8  336.82  4495.6  334.82  4554.3  335.91  4578.3   335.2
  4602.2  335.88  4828.2  333.42  4908.8  330.27    4928  328.04    4933  326.34
  4944.7  324.53  4945.5  323.73  4952.7  323.73  4953.6  324.53  4969.3  327.14
  4979.4  327.48  5013.6  325.39  5049.9  330.19  5140.6   329.6  5169.9   327.4
  5180.9   327.3  5211.2  330.04  5336.1  330.57  5402.6  332.67  5463.1  332.48
  5523.6  330.86    5573  330.39  5686.4  332.49  5739.3  333.66  5770.8  335.33
#Mann= 4 ,-1 , 0
    4118      .1       0  4944.7     .07       0  4953.6      .1       0
  5686.4     .08       0
Bank Sta=4944.7,4953.6
XS Rating Curve= 0 ,0
Exp/Cntr=0.3,0.1