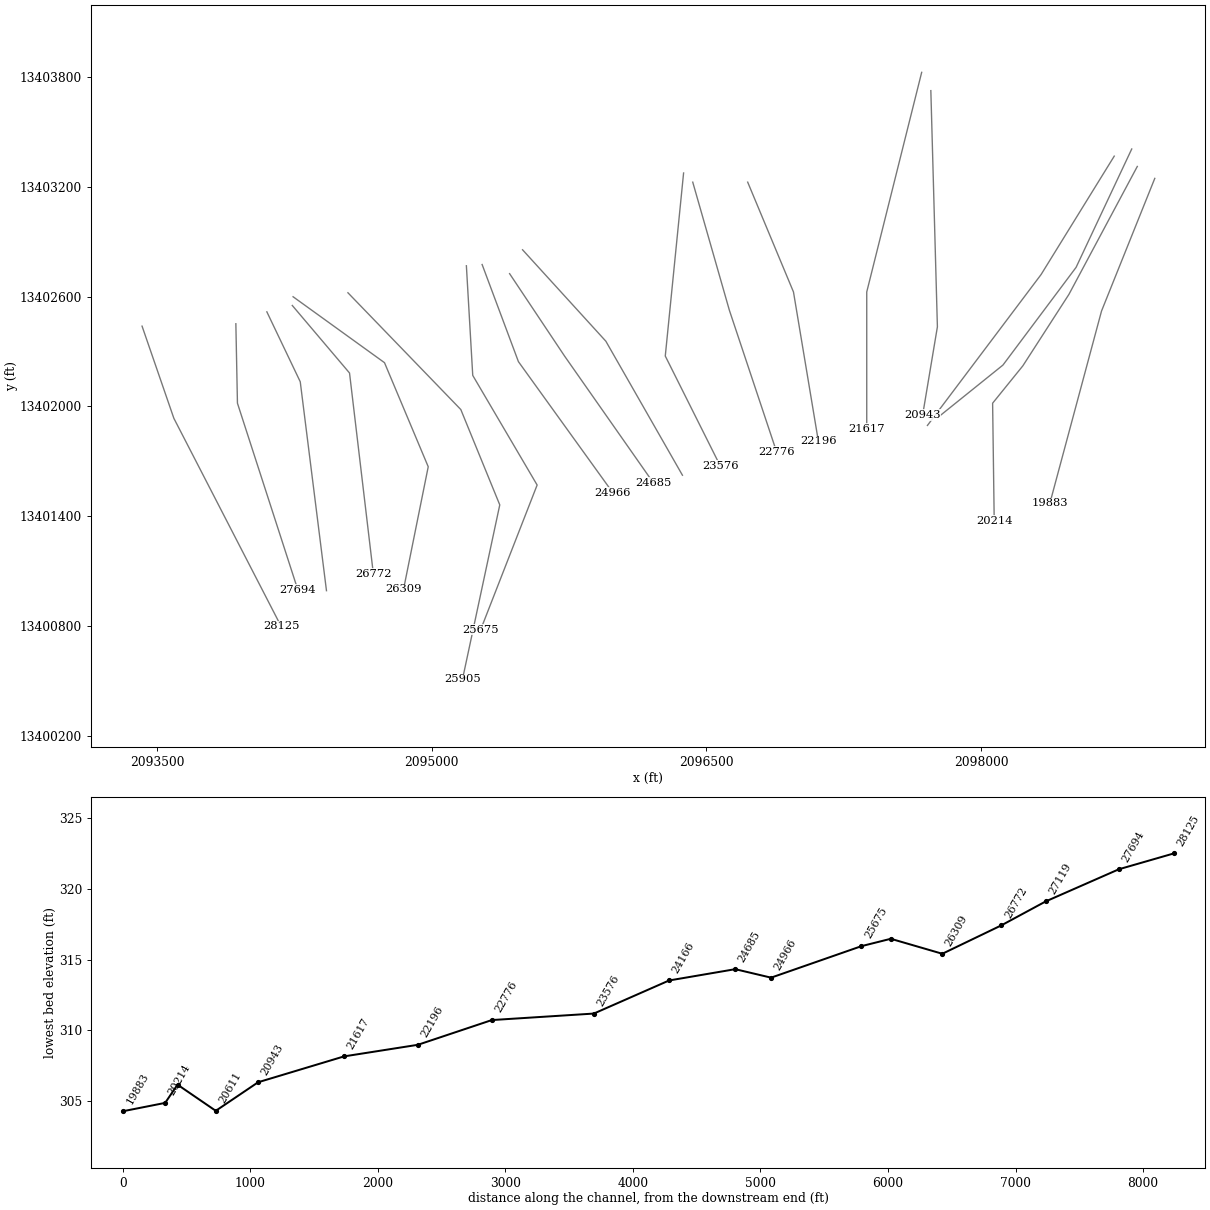
HEC-RAS study Live Oak Creek.prj: Live Oak Creek Base Level Engineering

--- Live Oak Creek.g01 (geometry) --- (continued)

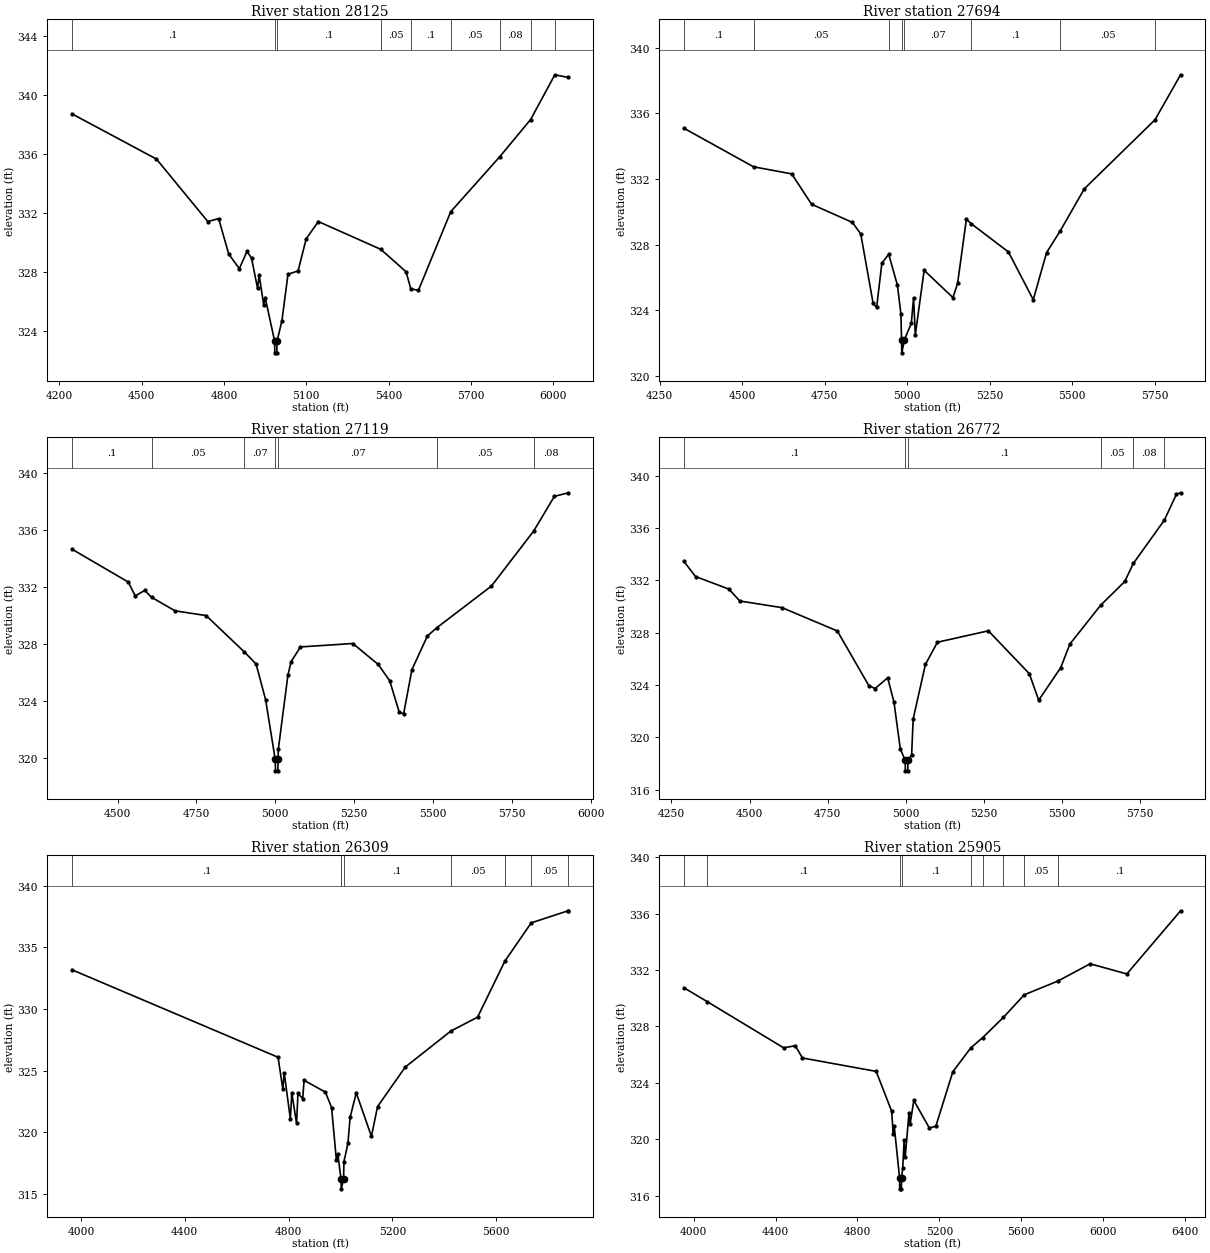
Type RM Length L Ch R = 1 ,28125   ,431,431,431
BEGIN DESCRIPTION:
Mapping XS 3c7dbc91
END DESCRIPTION:
XS GIS Cut Line= 3
      2093418.19     13402438.35      2093591.82     13401934.84
      2094177.14     13400798.88
#Sta/Elev= 30
  4245.2  338.71  4553.9  335.64  4741.1  331.41  4780.5  331.61  4817.3  329.21
    4856  328.22  4883.8  329.39  4900.3  328.94  4922.5  326.88  4928.1  327.79
  4944.6  325.78  4950.2  326.26  4984.5  323.32  4985.3  322.52  4992.6  322.52
  4993.4  323.32  5011.1  324.68  5033.3  327.84  5070.1  328.07  5099.8  330.25
  5144.1  331.41  5371.6  329.53  5463.8  328.01  5480.9  326.86  5508.8  326.75
  5626.7  332.08  5805.4   335.8  5917.9  338.32  6006.2  341.35  6055.7  341.17
#Mann= 9 ,-1 , 0
  4245.2      .1       0  4984.5     .07       0  4993.4      .1       0
  5371.6     .05       0  5480.9      .1       0  5626.7     .05       0
  5805.4     .08       0  5917.9     .05       0  6006.2     .08       0
Bank Sta=4984.5,4993.4
XS Rating Curve= 0 ,0
Exp/Cntr=0.3,0.1

Type RM Length L Ch R = 1 ,27694   ,575,575,575
BEGIN DESCRIPTION:
Mapping XS 4873995a
END DESCRIPTION:
XS GIS Cut Line= 3
      2093930.36     13402451.38      2093939.04      13402017.3
      2094268.46     13400998.71
#Sta/Elev= 30
    4324  335.09  4534.8  332.74  4650.4  332.31  4710.5  330.46  4834.2  329.35
  4859.6  328.65  4897.2  324.41  4907.7  324.17  4923.6  326.86  4944.3  327.41
  4970.8  325.52  4981.3  323.76  4983.2   322.2    4984   321.4  4992.1   322.2
  5012.8   323.2  5019.7  324.76  5024.9  322.49  5051.7  326.43  5138.9  324.77
    5153  325.63  5179.7  329.54  5194.5  329.27  5307.1  327.55  5382.3  324.64
  5422.7  327.51  5463.9  328.83  5537.1   331.4  5751.3  335.61  5828.7  338.35
#Mann= 8 ,-1 , 0
    4324      .1       0  4534.8     .05       0  4944.3     .07       0
  4983.2     .07       0  4992.1     .07       0  5194.5      .1       0
  5463.9     .05       0  5751.3     .08       0
Bank Sta=4983.2,4992.1
XS Rating Curve= 0 ,0
Exp/Cntr=0.3,0.1

Type RM Length L Ch R = 1 ,27119   ,347,347,347
BEGIN DESCRIPTION:
Mapping XS cc024adc
END DESCRIPTION:
XS GIS Cut Line= 3
      2094099.63     13402516.44      2094281.92     13402134.49
      2094425.16     13400992.96
#Sta/Elev= 30
  4355.1  334.67    4534  332.36  4556.1  331.39    4586  331.77  4607.9  331.29
  4682.3  330.34  4780.6  330.01  4901.3  327.47  4939.1  326.61  4969.3   324.1
  4999.7  319.92  5000.5  319.12  5007.9  319.12  5008.7  319.92  5009.6  320.64
  5039.8  325.82  5049.9  326.77  5079.6  327.81  5245.6  328.05  5326.1  326.58
  5362.4  325.44  5392.6  323.24  5406.6  323.12  5432.9  326.22    5482  328.58
    5512  329.16  5684.9  332.08  5818.8  335.94  5884.4  338.37  5928.8  338.62
#Mann= 7 ,-1 , 0
  4355.1      .1       0  4607.9     .05       0  4901.3     .07       0
  4999.7     .07       0  5008.7     .07       0    5512     .05       0
  5818.8     .08       0
Bank Sta=4999.7,5008.7
XS Rating Curve= 0 ,0
Exp/Cntr=0.3,0.1

Type RM Length L Ch R = 1 ,26772   ,463,463,463
BEGIN DESCRIPTION:
Mapping XS f228a31c
END DESCRIPTION:
XS GIS Cut Line= 3
      2094238.54     13402551.14      2094551.02     13402182.23
      2094681.22     13401084.19
#Sta/Elev= 30
  4290.3  333.43  4327.3  332.28  4433.9  331.32    4469  330.41  4604.2   329.9
    4781  328.12  4881.7  323.95  4901.9  323.72  4942.2  324.54  4962.3  322.69
  4982.4  319.13  4998.1  318.23  4998.9  317.43  5006.3  317.43  5007.1  318.23
  5018.8  318.65  5023.8   321.4    5063  325.57  5101.5  327.26  5264.4  328.13
  5395.3  324.86  5425.5  322.83    5496  325.32  5525.3  327.12  5623.9  330.09
  5700.9   331.9  5728.3  333.28  5827.3  336.58  5866.3  338.57  5879.5  338.68
#Mann= 6 ,-1 , 0
  4290.3      .1       0  4998.1     .07       0  5007.1      .1       0
  5623.9     .05       0  5728.3     .08       0  5827.3     .05       0
Bank Sta=4998.1,5007.1
XS Rating Curve= 0 ,0
Exp/Cntr=0.3,0.1

Type RM Length L Ch R = 1 ,26309   ,404,404,404
BEGIN DESCRIPTION:
Mapping XS df53f6eb
END DESCRIPTION:
XS GIS Cut Line= 4
      2094242.84     13402598.91      2094741.99     13402238.66
      2094980.71     13401670.08      2094846.17     13401001.72
#Sta/Elev= 30
  3964.7  333.19  4759.6  326.09  4777.9  323.52  4783.3  324.83  4807.1  321.09
  4812.5   323.2  4830.9  320.74  4836.3  323.16  4854.6  322.74    4860  324.22
  4942.2  323.26  4965.9  322.01  4984.3  317.76  4989.7  318.27  5002.3  316.22
  5003.2  315.42  5012.2  316.22  5013.5  317.63  5028.9   319.1  5037.2  321.21
    5061   323.2  5119.4  319.68  5143.1  322.09  5249.6  325.29  5425.7  328.22
  5528.5  329.34  5634.1   333.9  5735.4  336.99  5877.3  337.97  5878.7  337.97
#Mann= 7 ,-1 , 0
  3964.7      .1       0  5002.3     .07       0  5012.2      .1       0
  5425.7     .05       0  5634.1     .08       0  5735.4     .05       0
  5877.3      .1       0
Bank Sta=5002.3,5012.2
XS Rating Curve= 0 ,0
Exp/Cntr=0.3,0.1

Type RM Length L Ch R = 1 ,25905   ,230,230,230
BEGIN DESCRIPTION:
Mapping XS 4149a5bb
END DESCRIPTION:
XS GIS Cut Line= 4
      2094542.34     13402620.61      2095158.66     13401982.58
      2095371.33     13401461.75      2095167.67     13400508.43
#Sta/Elev= 30
    3953  330.74    4066  329.76  4439.7  326.48  4496.3  326.63  4531.6  325.76
  4891.3  324.81  4967.1  321.98  4974.2   320.4  4979.6  320.91  5005.4  317.28
  5006.3  316.48  5014.3  316.48  5015.3  317.28  5021.1  317.96  5027.7  319.93
  5033.1  318.72  5051.7  321.89  5057.1  321.08  5075.1  322.75  5150.7   320.8
  5182.6  320.92  5265.5  324.78  5352.7  326.47    5411   327.2  5512.6  328.64
  5614.2  330.24  5780.6  331.23  5935.9  332.44  6115.1  331.72  6377.5   336.2
#Mann= 9 ,-1 , 0
    3953     .05       0    4066      .1       0  5005.4     .07       0
  5015.3      .1       0  5352.7     .05       0    5411      .1       0
  5512.6     .08       0  5614.2     .05       0  5780.6      .1       0
Bank Sta=5005.4,5015.3
XS Rating Curve= 0 ,0
Exp/Cntr=0.3,0.1

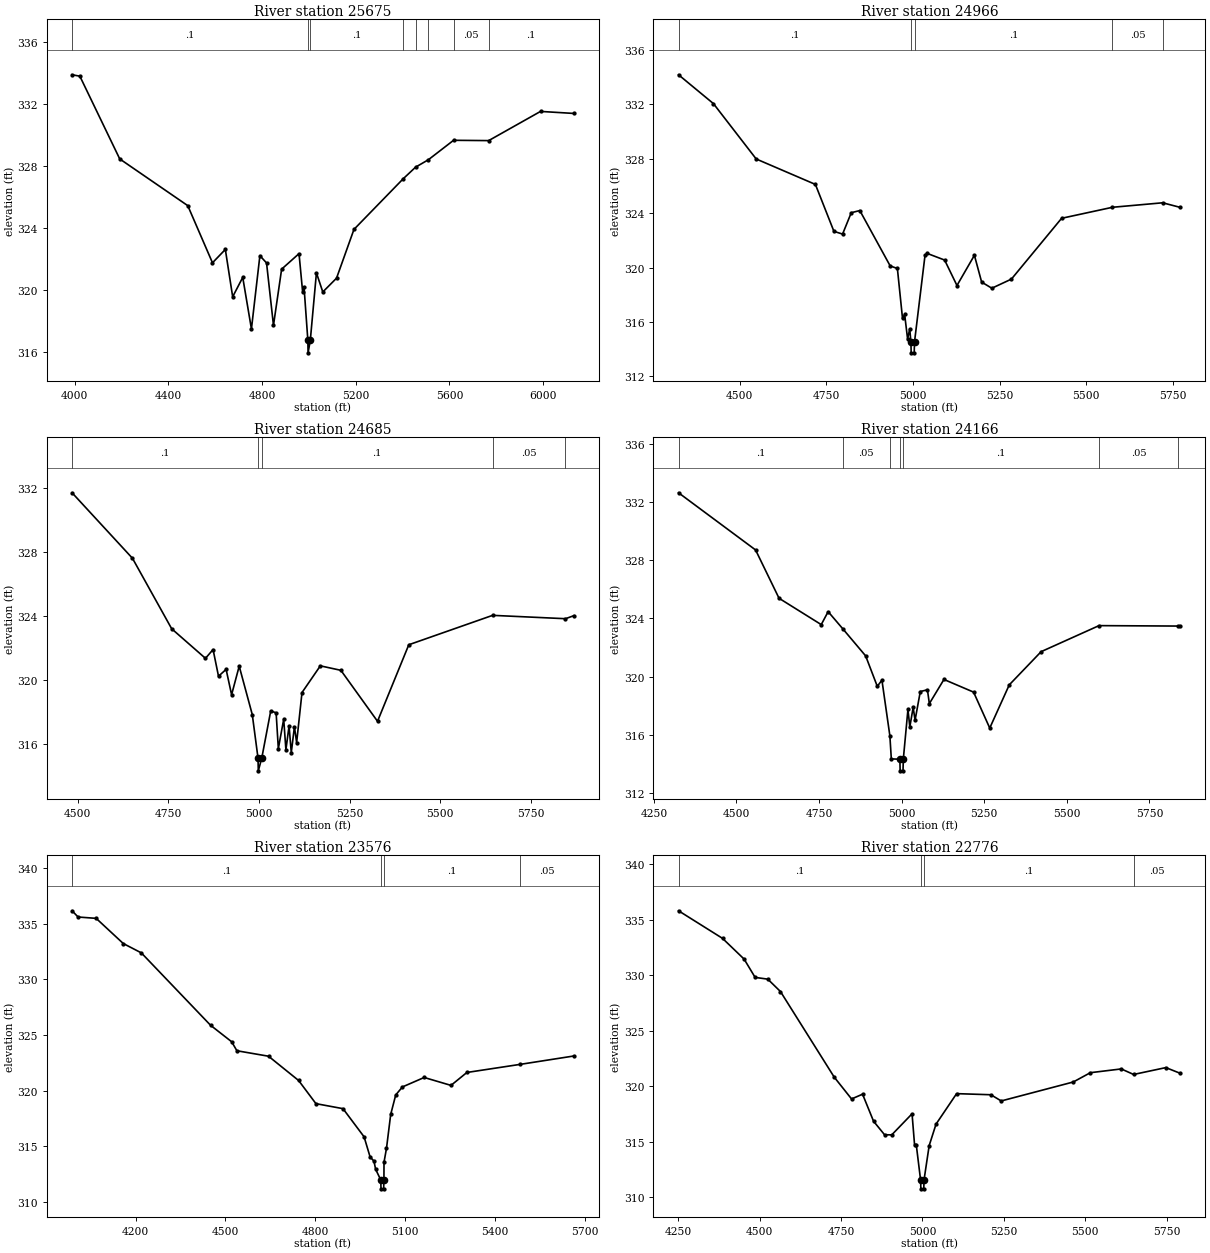
Type RM Length L Ch R = 1 ,25675   ,709,709,709
BEGIN DESCRIPTION:
Mapping XS 04839a39
END DESCRIPTION:
XS GIS Cut Line= 4
      2095189.04     13402768.15      2095223.76     13402169.21
      2095575.32     13401570.26      2095267.15     13400780.29
#Sta/Elev= 30
  3988.8  333.87    4022  333.78  4192.3  328.45  4482.8  325.44  4588.3  321.76
  4643.2  322.62  4674.5  319.57  4717.5  320.82  4754.6   317.5  4790.7  322.22
  4819.1  321.75  4848.7  317.73  4883.5  321.35  4957.8  322.35  4973.4  319.85
  4979.2   320.2  4995.5  316.76  4996.4  315.96  5005.9  316.76  5032.1  321.11
  5059.3  319.88    5118  320.77  5192.3  323.91  5403.1  327.18  5455.5  327.92
  5510.3   328.4  5617.6  329.65  5767.5  329.63  5988.9  331.51  6131.2  331.38
#Mann= 8 ,-1 , 0
  3988.8      .1       0  4995.5     .07       0  5005.9      .1       0
  5403.1     .08       0  5455.5      .1       0  5510.3     .08       0
  5617.6     .05       0  5767.5      .1       0
Bank Sta=4995.5,5005.9
XS Rating Curve= 0 ,0
Exp/Cntr=0.3,0.1

Type RM Length L Ch R = 1 ,24966   ,281,281,281
BEGIN DESCRIPTION:
Live Oak Creek 33.0
END DESCRIPTION:
XS GIS Cut Line= 3
      2095275.01     13402774.97      2095473.19     13402244.27
      2095988.06     13401529.13
#Sta/Elev= 30
  4323.4  334.17  4424.1  332.05  4547.5  327.98  4718.3  326.11  4771.7  322.66
  4796.7  322.46  4821.7  324.03  4846.4  324.19    4934  320.12  4954.8  319.93
  4969.6  316.26  4975.7  316.56  4984.3  314.74  4990.4   315.5  4993.8  314.53
  4994.6  313.73  5003.3  313.73  5004.2  314.53  5034.6  320.91  5040.7  321.04
  5091.1  320.55  5126.7  318.68    5177   320.9  5197.9  318.93  5227.3  318.48
  5283.8  319.15  5428.6  323.62  5575.4  324.43  5720.2  324.76  5771.1  324.42
#Mann= 5 ,-1 , 0
  4323.4      .1       0  4993.8     .07       0  5004.2      .1       0
  5575.4     .05       0  5720.2      .1       0
Bank Sta=4993.8,5004.2
XS Rating Curve= 0 ,0
Exp/Cntr=0.3,0.1

Type RM Length L Ch R = 1 ,24685   ,519,519,519
BEGIN DESCRIPTION:
Live Oak Creek 32.0
END DESCRIPTION:
XS GIS Cut Line= 3
      2095425.01     13402724.99        2095725.       13402275.
      2096208.93     13401583.67
#Sta/Elev= 30
  4484.2  331.73  4650.9  327.63  4759.1  323.22  4852.3  321.37  4873.3  321.92
  4888.3  320.25  4909.3  320.68  4924.4  319.09  4945.4  320.88  4981.5  317.85
  4997.3  315.13  4998.1  314.33  5007.7  315.13  5032.4  318.08  5047.3  317.96
  5053.4  315.72  5068.2  317.56  5074.3  315.65    5083  317.14  5089.1  315.47
  5097.8  317.09  5103.9   316.1  5118.7  319.23  5169.3   320.9    5226  320.62
  5327.1  317.43  5413.4  322.22  5644.7  324.06  5845.8  323.85  5868.9  324.04
#Mann= 5 ,-1 , 0
  4484.2      .1       0  4997.3     .07       0  5007.7      .1       0
  5644.7     .05       0  5845.8     .08       0
Bank Sta=4997.3,5007.7
XS Rating Curve= 0 ,0
Exp/Cntr=0.3,0.1

Type RM Length L Ch R = 1 ,24166   ,590,590,590
BEGIN DESCRIPTION:
Live Oak Creek 31.0
END DESCRIPTION:
XS GIS Cut Line= 3
      2095495.76     13402855.49       2095950.5     13402356.04
      2096368.73     13401623.82
#Sta/Elev= 30
  4324.7  332.64  4557.9  328.71  4628.9  325.39  4756.6  323.58  4777.5  324.47
  4821.9  323.29    4891  321.43  4926.2  319.34  4940.3  319.76  4964.3  315.94
  4968.7  314.35  4994.6  314.33  4995.4  313.53  5004.1  313.53    5005  314.33
    5019  317.75  5024.7  316.55  5034.8  317.89  5040.6  317.01  5056.4  318.98
    5078   319.1  5083.8  318.15    5128  319.81  5217.7  318.94  5266.6  316.47
  5325.7  319.44  5422.1  321.72  5597.3  323.51  5837.1  323.48  5843.4  323.48
#Mann= 7 ,-1 , 0
  4324.7      .1       0  4821.9     .05       0  4964.3      .1       0
  4994.6     .07       0    5005      .1       0  5597.3     .05       0
  5837.1     .08       0
Bank Sta=4994.6,5005
XS Rating Curve= 0 ,0
Exp/Cntr=0.3,0.1

Type RM Length L Ch R = 1 ,23576   ,800,800,800
BEGIN DESCRIPTION:
Live Oak Creek 30.0
END DESCRIPTION:
XS GIS Cut Line= 3
        2096375.     13403275.03        2096275.       13402275.
      2096574.72     13401675.57
#Sta/Elev= 30
    3988  336.16  4008.1   335.6  4068.4  335.48  4158.9  333.22  4219.2  332.38
  4450.3  325.88  4520.7   324.4  4538.3  323.59  4643.8   323.1  4744.3  320.92
  4802.1  318.84  4892.5  318.39  4962.9  315.86    4983  314.05  4995.8  313.68
  5001.4  312.95  5018.5  311.99  5019.4  311.19  5028.2  311.19  5029.1  311.99
  5029.4  313.58  5037.7  314.83  5051.7  317.87  5068.5  319.62  5090.8  320.34
  5163.5  321.19    5253  320.48  5306.1  321.64  5484.6  322.37  5663.2  323.12
#Mann= 4 ,-1 , 0
    3988      .1       0  5018.5     .07       0  5029.1      .1       0
  5484.6     .05       0
Bank Sta=5018.5,5029.1
XS Rating Curve= 0 ,0
Exp/Cntr=0.3,0.1

Type RM Length L Ch R = 1 ,22776   ,580,580,580
BEGIN DESCRIPTION:
Live Oak Creek 29.0
END DESCRIPTION:
XS GIS Cut Line= 3
      2096424.99     13403225.02        2096625.       13402525.
       2096882.4      13401752.8
#Sta/Elev= 30
  4250.4  335.82  4385.6  333.33  4451.9  331.46  4485.7  329.81  4524.7  329.65
  4563.7  328.53  4728.8  320.81  4782.1  318.84  4815.9  319.27  4849.7  316.83
  4883.5  315.61  4905.6   315.6    4968   317.5  4975.8  314.67  4981.1  314.67
  4994.2  311.53  4995.1  310.73    5004  310.73  5004.8  311.53  5020.6  314.63
  5041.7  316.57  5104.9  319.32  5210.3  319.22    5242  318.66  5463.3  320.37
    5516  321.21  5610.9  321.55  5648.8  321.05  5747.9  321.67  5792.4  321.15
#Mann= 4 ,-1 , 0
  4250.4      .1       0  4994.2     .07       0  5004.8      .1       0
  5648.8     .05       0
Bank Sta=4994.2,5004.8
XS Rating Curve= 0 ,0
Exp/Cntr=0.3,0.1

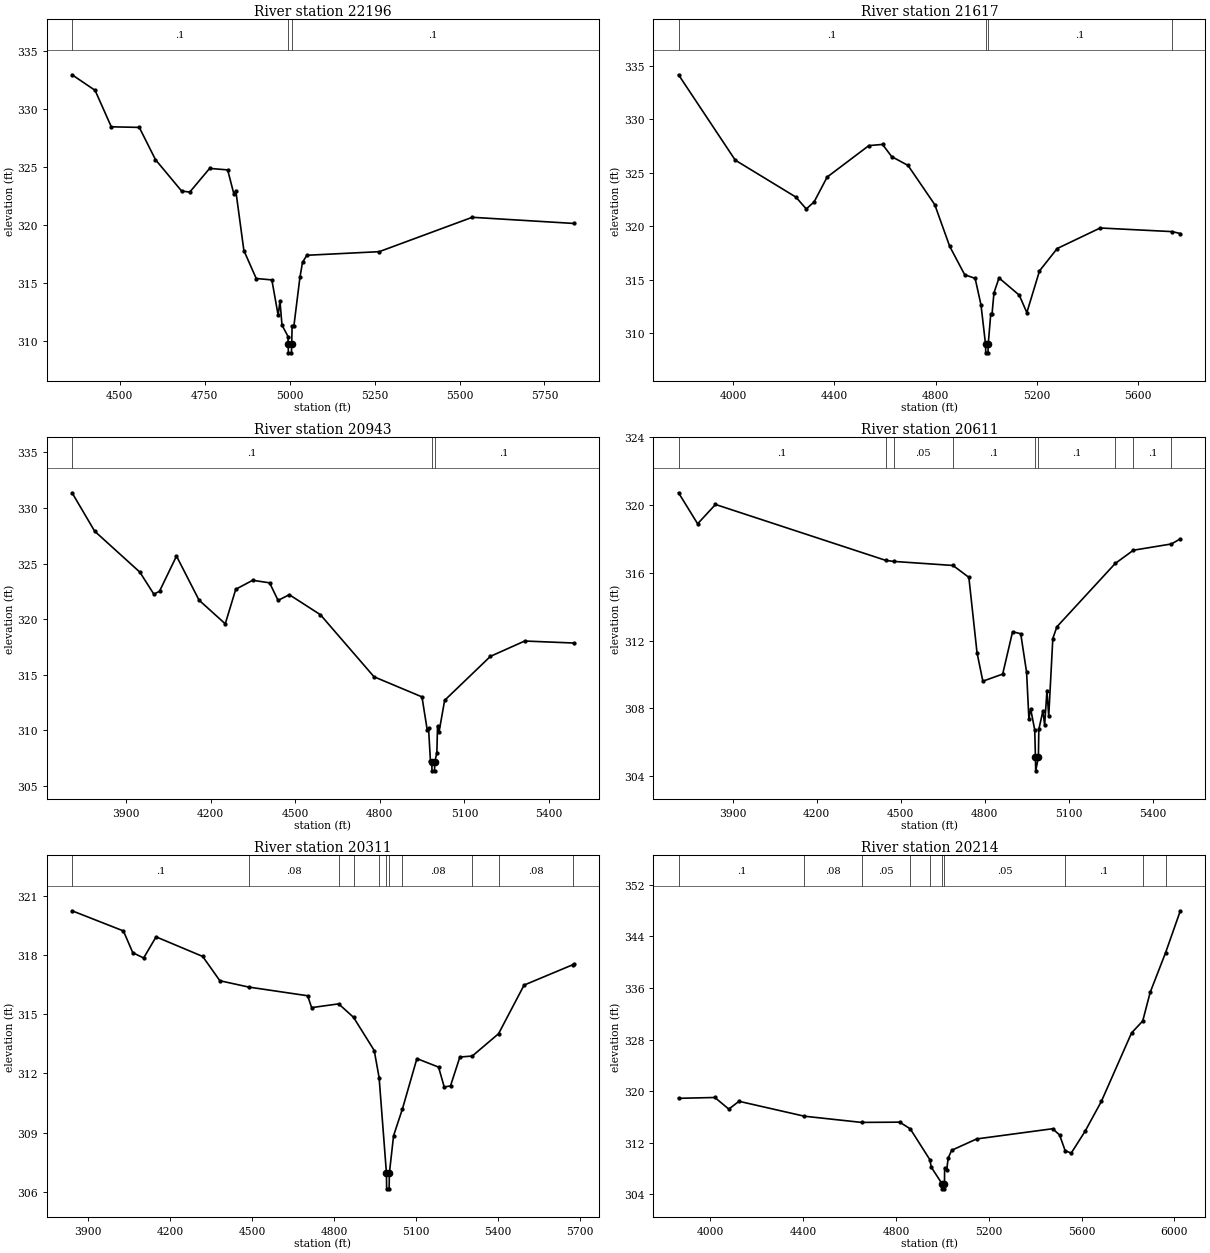
Type RM Length L Ch R = 1 ,22196   ,579,579,579
BEGIN DESCRIPTION:
Live Oak Creek 28.0
END DESCRIPTION:
XS GIS Cut Line= 3
      2096724.99     13403225.03        2096975.       13402625.
       2097110.8     13401810.17
#Sta/Elev= 30
  4360.3  332.92    4428  331.58  4475.7  328.44    4558  328.39  4605.7  325.61
  4682.6  322.91  4706.5  322.82    4765  324.86    4818  324.73  4836.5  322.63
  4841.9  322.95  4865.7  317.79    4902  315.38    4948  315.26  4966.5  312.22
  4971.9  313.43  4977.8  311.37  4995.7  310.38  4995.8  309.78  4996.7  308.98
  5005.6  308.98  5006.4  309.78  5007.6  311.31  5012.9  311.31  5030.6  315.48
  5038.2  316.77  5050.9  317.38  5263.8  317.69  5537.5  320.65  5836.4  320.12
#Mann= 3 ,-1 , 0
  4360.3      .1       0  4995.8     .07       0  5006.4      .1       0
Bank Sta=4995.8,5006.4
XS Rating Curve= 0 ,0
Exp/Cntr=0.3,0.1

Type RM Length L Ch R = 1 ,21617   ,674,674,674
BEGIN DESCRIPTION:
Live Oak Creek 27.0
END DESCRIPTION:
XS GIS Cut Line= 3
      2097674.99     13403824.96        2097375.       13402625.
        2097375.     13401878.29
#Sta/Elev= 30
    3784  334.15  4008.2  326.17  4247.8  322.72    4289  321.61    4320  322.27
  4371.5  324.59  4536.4  327.53  4590.5  327.64  4626.6   326.5    4691  325.68
  4796.7  322.02    4856  318.11  4915.2  315.46  4956.5  315.12  4979.7  312.63
  4997.6  308.96  4998.4  308.16  5007.3  308.16  5008.2  308.96  5018.3  311.81
  5023.4  311.81  5030.9  313.77  5050.9  315.16  5130.9  313.55  5160.9  311.92
  5210.9  315.82  5280.9  317.91  5450.9  319.83  5735.7  319.49  5767.6  319.31
#Mann= 4 ,-1 , 0
    3784      .1       0  4997.6     .07       0  5008.2      .1       0
  5735.7     .08       0
Bank Sta=4997.6,5008.2
XS Rating Curve= 0 ,0
Exp/Cntr=0.3,0.1

Type RM Length L Ch R = 1 ,20943   ,332,332,332
BEGIN DESCRIPTION:
Live Oak Creek 26.0
END DESCRIPTION:
XS GIS Cut Line= 3
        2097725.     13403725.04       2097760.8     13402434.54
      2097680.33     13401953.22
#Sta/Elev= 30
    3709  331.37  3789.1  327.91  3949.1  324.23  3999.2  322.23  4019.2  322.51
  4079.2  325.67  4159.2   321.7  4252.1  319.57  4289.3  322.68  4349.3  323.49
  4409.3  323.26  4439.3  321.68  4479.3  322.19  4589.4  320.39  4779.5   314.8
  4949.5  312.99  4967.9  310.05  4972.9  310.15  4979.5  307.24  4984.2  307.13
  4985.1  306.33    4994  306.33  4994.8  307.13  5002.3  307.95  5004.7  310.36
  5009.8   309.8  5029.9  312.68  5192.2  316.64  5313.8  318.02    5488  317.84
#Mann= 3 ,-1 , 0
    3709      .1       0  4984.2     .07       0  4994.8      .1       0
Bank Sta=4984.2,4994.8
XS Rating Curve= 0 ,0
Exp/Cntr=0.3,0.1

Type RM Length L Ch R = 1 ,20611   ,300,300,300
BEGIN DESCRIPTION:
Mapping XS cfb937e4
END DESCRIPTION:
XS GIS Cut Line= 3
      2098726.38     13403367.15      2098327.06     13402720.43
      2097706.39     13401895.76
#Sta/Elev= 30
  3706.9  320.72  3775.1  318.89  3838.9  320.03  4447.2  316.73  4474.9  316.67
  4687.2  316.43  4743.8  315.73    4773  311.28  4793.8   309.6  4864.6  310.02
    4900  312.52  4929.1   312.4    4950  310.13  4958.3  307.37  4964.5  307.97
  4979.1  306.72  4981.6  305.11  4982.5  304.31  4992.2  305.11  4993.7  306.76
  5008.3  307.84  5014.5  307.01  5022.8  309.05  5029.1  307.53  5043.7  312.12
  5058.2  312.81  5266.7  316.55  5331.5  317.33  5467.5   317.7  5499.1     318
#Mann= 9 ,-1 , 0
  3706.9      .1       0  4447.2     .08       0  4474.9     .05       0
  4687.2      .1       0  4981.6     .07       0  4992.2      .1       0
  5266.7     .08       0  5331.5      .1       0  5467.5     .08       0
Bank Sta=4981.6,4992.2
XS Rating Curve= 0 ,0
Exp/Cntr=0.3,0.1

Type RM Length L Ch R = 1 ,20311   ,97,97,97
BEGIN DESCRIPTION:
Mapping XS 6605f498
END DESCRIPTION:
XS GIS Cut Line= 4
      2098821.85     13403406.18      2098518.03     13402759.49
      2098118.73     13402225.64      2097763.31     13401939.57
#Sta/Elev= 30
    3841  320.23    4029  319.21  4063.3  318.11    4103  317.84  4148.6  318.91
  4319.3  317.92  4382.2  316.69  4487.7  316.37  4703.6  315.93  4718.2  315.33
  4817.1  315.52  4871.6  314.84  4947.4  313.16  4965.3  311.79  4992.1  306.96
  4992.9  306.16    5002  306.16  5002.9  306.96  5018.3  308.85  5050.8  310.21
  5103.7  312.75    5183  312.32  5203.8  311.31  5226.7  311.37    5261  312.83
  5306.5  312.88  5402.7  314.01  5496.2  316.47  5674.5   317.5  5678.4  317.53
#Mann= 11 ,-1 , 0
    3841      .1       0  4487.7     .08       0  4817.1     .05       0
  4871.6     .08       0  4965.3     .05       0  4992.1    .035       0
  5002.9     .05       0  5050.8     .08       0  5306.5      .1       0
  5402.7     .08       0  5674.5      .1       0
Bank Sta=4992.1,5002.9
XS Rating Curve= 0 ,0
Exp/Cntr=0.3,0.1

Type RM Length L Ch R = 1 ,20214   ,331,331,331
BEGIN DESCRIPTION:
Mapping XS acee8896
END DESCRIPTION:
XS GIS Cut Line= 5
      2098852.25     13403310.73      2098478.97     13402611.92
      2098227.23      13402221.3       2098062.3      13402017.3
      2098070.98     13401374.96
#Sta/Elev= 30
  3863.7  318.89  4020.2  319.02  4080.3  317.22  4124.2  318.43  4405.7  316.12
    4652  315.16  4816.6   315.2    4862  314.16  4946.3  309.39  4952.5  308.22
  4998.6  305.67  4999.5  304.87  5008.6  304.87  5009.4  305.67    5010  308.08
  5019.2  307.83  5025.2  309.63  5040.3  310.84  5148.1   312.6  5475.3  314.18
  5505.3  313.21  5529.1  310.79  5555.3   310.4  5615.3   313.8  5685.3  318.42
  5815.3  329.02  5863.4  330.87  5895.4  335.29    5962  341.46  6025.4  347.94
#Mann= 10 ,-1 , 0
  3863.7      .1       0  4405.7     .08       0    4652     .05       0
    4862      .1       0  4946.3     .05       0  4998.6    .035       0
  5009.4     .05       0  5529.1      .1       0  5863.4     .08       0
    5962      .1       0
Bank Sta=4998.6,5009.4
XS Rating Curve= 0 ,0
Exp/Cntr=0.3,0.1

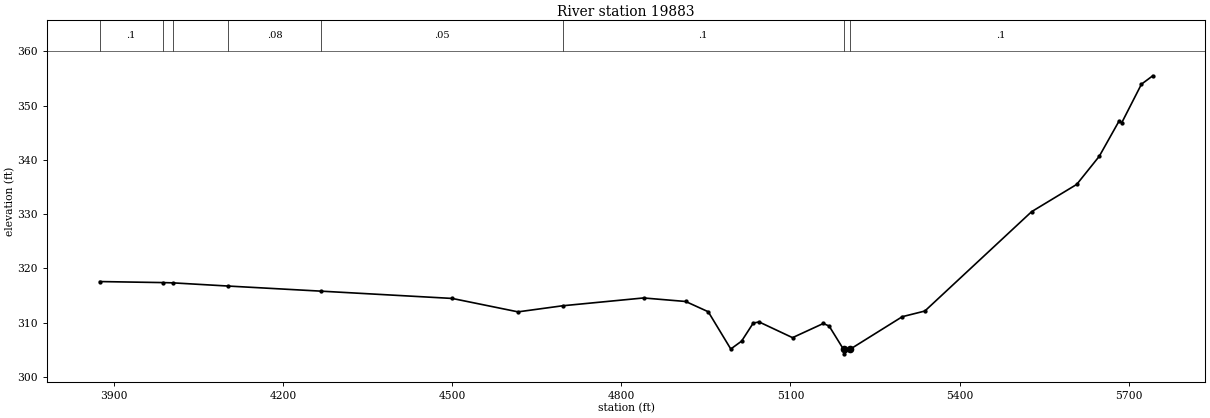
Type RM Length L Ch R = 1 ,19883   ,552,552,552
BEGIN DESCRIPTION:
Mapping XS 7a39aef5
END DESCRIPTION:
XS GIS Cut Line= 3
      2098947.71     13403245.58      2098656.92     13402520.78
      2098374.81     13401470.47
#Sta/Elev= 30
  3874.3  317.59  3986.4   317.4  4004.3  317.35  4102.7  316.76  4267.5  315.82
  4499.9  314.48  4616.6  312.01  4695.7  313.13  4839.3  314.57  4914.1  313.92
  4954.1  312.03  4994.1  305.17  5013.3  306.62    5034  309.95  5044.4  310.15
  5103.7  307.26  5158.3  309.87  5168.6   309.4  5194.3  305.08  5195.1  304.28
  5205.1  305.08  5298.4  311.12  5338.4  312.16  5527.9  330.46  5607.9  335.48
  5647.9  340.66  5682.7  347.09  5687.9  346.86  5722.7  353.93  5742.8  355.48
#Mann= 8 ,-1 , 0
  3874.3      .1       0  3986.4     .08       0  4004.3      .1       0
  4102.7     .08       0  4267.5     .05       0  4695.7      .1       0
  5194.3     .07       0  5205.1      .1       0
Bank Sta=5194.3,5205.1
XS Rating Curve= 0 ,0
Exp/Cntr=0.3,0.1