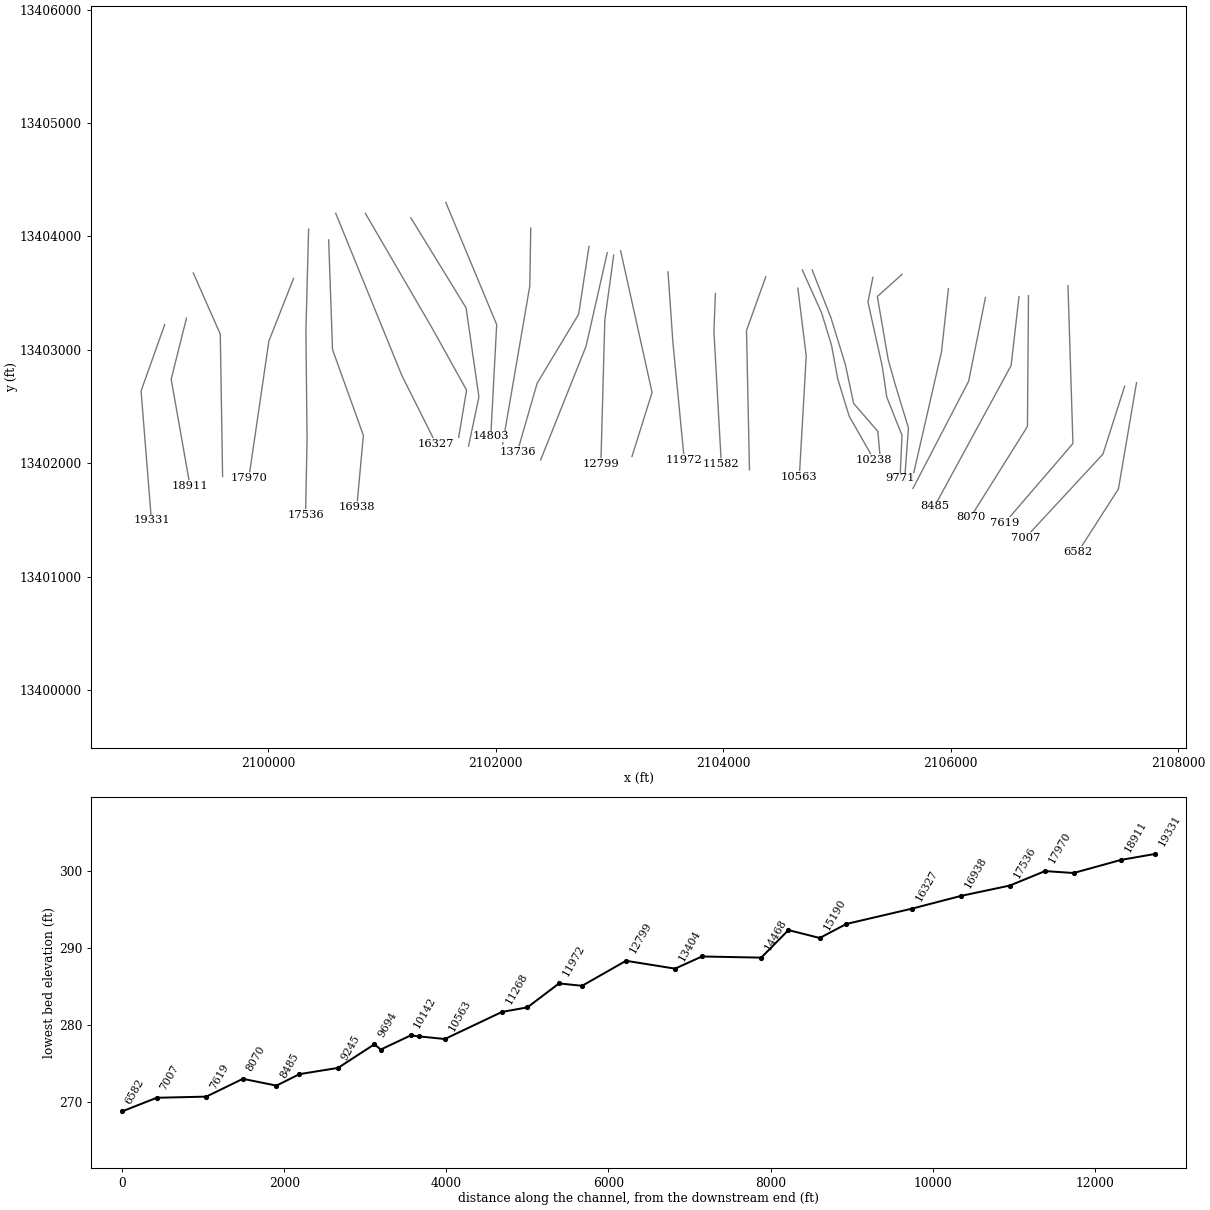
HEC-RAS study Live Oak Creek.prj: Live Oak Creek Base Level Engineering

--- Live Oak Creek.g01 (geometry) --- (continued)

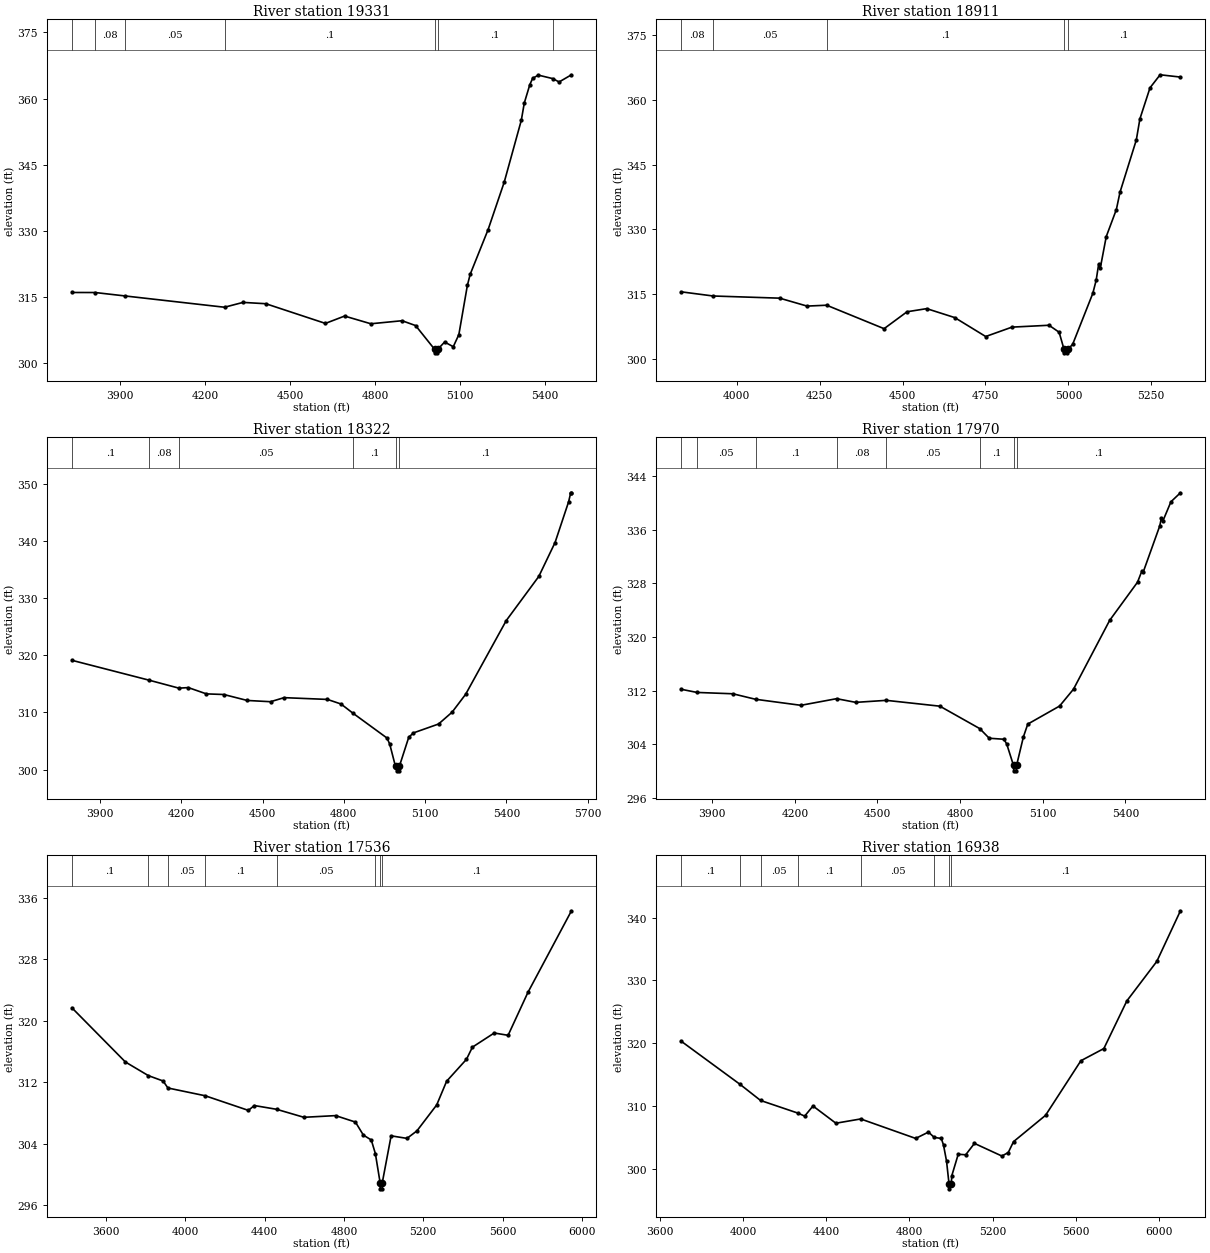
Type RM Length L Ch R = 1 ,19331   ,420,420,420
BEGIN DESCRIPTION:
Mapping XS 3c0e45d9
END DESCRIPTION:
XS GIS Cut Line= 3
      2099090.94     13403223.87      2098882.62     13402637.96
      2098973.62     13401498.23
#Sta/Elev= 30
  3729.2  315.97  3811.4  315.96  3917.3  315.18  4268.3  312.62  4333.6  313.72
  4414.2  313.42  4624.9  308.95  4692.6  310.62  4785.4  308.87  4895.7  309.56
  4943.6  308.46  5010.7  303.07  5011.4  302.27  5020.8  302.27  5021.6  303.07
  5046.2  304.72  5076.7  303.66  5096.4  306.41  5126.5  317.58  5136.5  320.11
  5199.7  330.23  5256.9  341.05  5317.1  355.06  5327.7  358.99  5347.2  363.15
  5357.2  364.59  5377.3  365.31  5427.7  364.53  5450.7  363.76  5494.4  365.39
#Mann= 7 ,-1 , 0
  3729.2      .1       0  3811.4     .08       0  3917.3     .05       0
  4268.3      .1       0  5010.7     .07       0  5021.6      .1       0
  5427.7     .08       0
Bank Sta=5010.7,5021.6
XS Rating Curve= 0 ,0
Exp/Cntr=0.3,0.1

Type RM Length L Ch R = 1 ,18911   ,589,589,589
BEGIN DESCRIPTION:
Mapping XS 6b996b22
END DESCRIPTION:
XS GIS Cut Line= 3
      2099281.92     13403280.34      2099147.37     13402742.13
      2099312.31      13401804.6
#Sta/Elev= 30
  3831.3   315.6  3928.5  314.63  4129.2  314.13  4211.7   312.3  4270.9   312.5
  4444.1  307.08  4513.4  310.99  4572.7  311.71  4657.3  309.64  4750.6  305.27
  4829.9  307.44  4941.6  307.87  4972.1  306.26  4986.9   302.3  4987.7   301.5
  4997.1   301.5  4997.8   302.3  5012.7  303.43  5073.6  315.22  5083.8  318.26
  5091.3  321.99  5096.4  321.14  5114.2  328.35  5144.7   334.6  5155.7   338.6
  5204.9  350.67  5215.7  355.54  5246.2  362.72  5276.7  365.73    5338   365.2
#Mann= 5 ,-1 , 0
  3831.3     .08       0  3928.5     .05       0  4270.9      .1       0
  4986.9     .07       0  4997.8      .1       0
Bank Sta=4986.9,4997.8
XS Rating Curve= 0 ,0
Exp/Cntr=0.3,0.1

Type RM Length L Ch R = 1 ,18322   ,352,352,352
BEGIN DESCRIPTION:
Mapping XS 6c60a868
END DESCRIPTION:
XS GIS Cut Line= 3
      2099341.75     13403678.03      2099579.09     13403138.93
      2099599.43     13401884.42
#Sta/Elev= 30
  3796.5  319.12  4081.6  315.64  4191.4  314.25  4225.9  314.35  4292.7  313.25
    4357  313.14  4443.2   312.1  4529.5  311.88  4579.5  312.59  4739.5  312.28
  4789.5  311.48  4832.5  309.91  4959.5  305.52  4969.5  304.45  4989.5  300.76
    4994  300.59  4994.8  299.79  5004.3  299.79    5005  300.59  5039.5  305.65
  5056.6  306.42  5149.6  307.98  5199.6  310.05  5249.6  313.18  5399.6  326.08
  5519.6  333.79  5579.6  339.72  5629.6  346.84  5637.4  348.42  5640.2  348.42
#Mann= 6 ,-1 , 0
  3796.5      .1       0  4081.6     .08       0  4191.4     .05       0
  4832.5      .1       0    4994     .07       0    5005      .1       0
Bank Sta=4994,5005
XS Rating Curve= 0 ,0
Exp/Cntr=0.3,0.1

Type RM Length L Ch R = 1 ,17970   ,434,434,434
BEGIN DESCRIPTION:
Mapping XS b87e6d53
END DESCRIPTION:
XS GIS Cut Line= 3
      2100223.29     13403630.56       2100006.3      13403077.9
      2099829.99     13401870.84
#Sta/Elev= 30
  3786.4  312.21  3844.7  311.73    3975  311.53  4057.3  310.71  4222.1  309.81
  4351.6   310.8  4421.1  310.25  4532.1  310.55  4726.7  309.68  4871.2  306.34
  4905.8   304.9  4959.1  304.75  4969.2  304.05    4994  300.84  4994.7  300.04
  5004.3  300.04    5005  300.84  5029.9  305.11  5045.7  307.01  5161.2   309.7
  5211.8  312.22  5343.1  322.48  5444.2  328.17  5460.5  329.89  5465.5  329.75
  5525.1  336.58  5530.4  337.67  5535.5  337.22  5565.5  340.16    5600   341.5
#Mann= 8 ,-1 , 0
  3786.4     .08       0  3844.7     .05       0  4057.3      .1       0
  4351.6     .08       0  4532.1     .05       0  4871.2      .1       0
    4994     .07       0    5005      .1       0
Bank Sta=4994,5005
XS Rating Curve= 0 ,0
Exp/Cntr=0.3,0.1

Type RM Length L Ch R = 1 ,17536   ,598,598,598
BEGIN DESCRIPTION:
Mapping XS d9d4542f
END DESCRIPTION:
XS GIS Cut Line= 4
      2100355.53     13404064.56       2100331.8     13403169.45
      2100341.97     13402209.91      2100328.41     13401545.36
#Sta/Elev= 30
  3427.8  321.69  3697.5  314.65  3813.1  312.88  3887.5  312.18  3911.9  311.27
    4100  310.26  4317.7  308.36  4347.7  308.99  4460.2   308.5  4597.7  307.46
  4757.7  307.68  4857.7  306.84  4897.7  305.15  4937.7  304.51  4958.4  302.73
  4982.2  298.96  4982.9  298.16  4992.5  298.16  4993.2  298.96  5037.7  305.05
  5117.7  304.72  5167.7  305.69  5267.7  309.07  5317.7  312.15  5417.8     315
  5447.8  316.58  5557.8  318.42  5627.8  318.12  5727.8   323.7  5947.5  334.31
#Mann= 8 ,-1 , 0
  3427.8      .1       0  3813.1     .08       0  3911.9     .05       0
    4100      .1       0  4460.2     .05       0  4958.4      .1       0
  4982.2     .07       0  4993.2      .1       0
Bank Sta=4982.2,4993.2
XS Rating Curve= 0 ,0
Exp/Cntr=0.3,0.1

Type RM Length L Ch R = 1 ,16938   ,611,611,611
BEGIN DESCRIPTION:
Mapping XS 53cc7b34
END DESCRIPTION:
XS GIS Cut Line= 4
      2100531.84     13403969.63      2100565.75     13403003.31
        2100837.     13402247.21      2100779.52     13401618.33
#Sta/Elev= 30
  3701.7  320.35  3986.1  313.45  4084.7  310.89  4264.9  308.87  4296.7   308.4
  4336.7  310.01  4446.8  307.27  4566.1  307.95  4830.4  304.85  4891.9  305.86
  4919.4  305.02  4953.7  304.84  4964.3  303.79  4978.8  301.24  4990.7  297.63
  4991.4  296.83  5001.7  297.63  5004.2  298.93    5035  302.33    5071  302.25
    5113  304.06  5244.9  302.05  5275.6  302.61    5301  304.34  5454.7  308.52
  5624.7  317.21  5735.2  319.15  5845.7  326.73  5989.7  333.01  6103.4  341.07
#Mann= 8 ,-1 , 0
  3701.7      .1       0  3986.1     .08       0  4084.7     .05       0
  4264.9      .1       0  4566.1     .05       0  4919.4      .1       0
  4990.7     .07       0  5001.7      .1       0
Bank Sta=4990.7,5001.7
XS Rating Curve= 0 ,0
Exp/Cntr=0.3,0.1

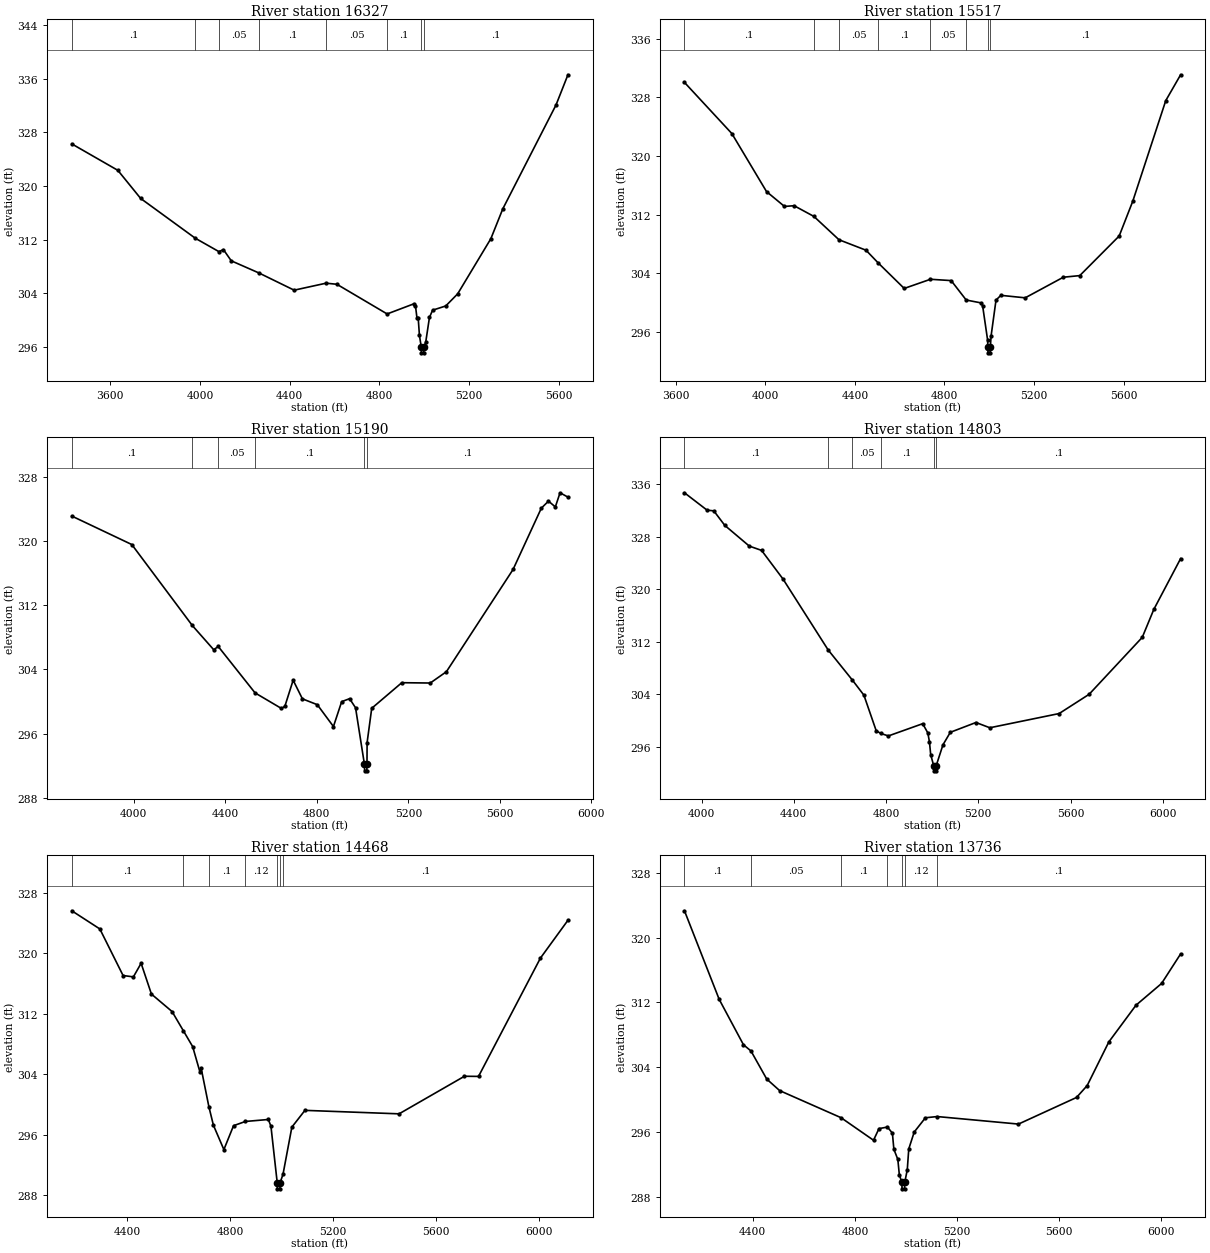
Type RM Length L Ch R = 1 ,16327   ,810,810,810
BEGIN DESCRIPTION:
Live Oak Creek 17.0
END DESCRIPTION:
XS GIS Cut Line= 3
      2100594.08     13404204.08        2101175.       13402775.
      2101475.02     13402174.97
#Sta/Elev= 30
    3428  326.27  3633.6  322.33  3735.2  318.15  3979.2  312.22  4084.4  310.23
  4104.6  310.53  4139.5  308.86  4263.1  307.05  4420.1  304.49  4562.4  305.53
  4610.6  305.37  4834.9  300.95  4955.9  302.48  4961.3  302.17  4967.9  300.37
  4973.4  300.37    4979  297.75  4987.5  295.96  4988.2  295.16  4997.9  295.16
  4998.6  295.96    5007  296.74  5023.7  300.43  5037.7  301.51  5096.4  302.14
  5149.5  303.94  5297.7  312.16  5350.8  316.59  5588.4  332.07  5641.5  336.56
#Mann= 8 ,-1 , 0
    3428      .1       0  3979.2     .08       0  4084.4     .05       0
  4263.1      .1       0  4562.4     .05       0  4834.9      .1       0
  4987.5     .07       0  4998.6      .1       0
Bank Sta=4987.5,4998.6
XS Rating Curve= 0 ,0
Exp/Cntr=0.3,0.1

Type RM Length L Ch R = 1 ,15517   ,327,327,327
BEGIN DESCRIPTION:
Mapping XS 47d9fc96
END DESCRIPTION:
XS GIS Cut Line= 4
      2100854.47     13404204.15      2101436.08     13403201.52
      2101744.24     13402645.96      2101674.85     13402229.62
#Sta/Elev= 30
  3638.5  330.04  3850.1  323.07    4005  315.16  4085.3  313.13  4128.3  313.23
  4216.7  311.77  4328.7  308.59  4449.6  307.16  4503.9  305.43  4620.2  301.95
  4737.5   303.2    4830  303.02  4897.2  300.37    4965  299.97  4970.8  299.53
  4992.5  294.97  4993.9  293.97  4994.6  293.17  5004.3  293.17    5005  293.97
  5008.5  295.51  5030.3  300.36    5052  301.01  5160.7  300.67  5331.1  303.48
  5404.5   303.7  5580.6   309.1  5641.5  313.86  5788.7  327.56    5855  331.08
#Mann= 8 ,-1 , 0
  3638.5      .1       0  4216.7     .08       0  4328.7     .05       0
  4503.9      .1       0  4737.5     .05       0  4897.2      .1       0
  4993.9     .07       0    5005      .1       0
Bank Sta=4993.9,5005
XS Rating Curve= 0 ,0
Exp/Cntr=0.3,0.1

Type RM Length L Ch R = 1 ,15190   ,387,387,387
BEGIN DESCRIPTION:
Mapping XS 12c33419
END DESCRIPTION:
XS GIS Cut Line= 4
       2101253.8     13404165.04       2101739.9     13403370.79
      2101852.75      13402585.2      2101761.61     13402151.22
#Sta/Elev= 30
  3729.1  323.09  3991.5  319.54  4255.7  309.46  4349.3  306.44  4369.2  306.84
  4530.1  301.06  4645.4  299.12  4660.3  299.39  4696.5  302.64  4736.9  300.32
  4802.1  299.59  4872.6  296.87  4908.6  299.97  4943.1  300.34  4969.2  299.21
  5008.1  292.15  5008.8  291.35  5018.5  291.35  5019.2  292.15  5019.7  294.86
  5039.9  299.14  5171.3  302.33  5295.8  302.29  5366.3   303.7  5657.7  316.44
  5781.1  324.07  5812.4  324.95  5842.4  324.23  5862.9  325.99  5897.4  325.45
#Mann= 6 ,-1 , 0
  3729.1      .1       0  4255.7     .08       0  4369.2     .05       0
  4530.1      .1       0  5008.1     .07       0  5019.2      .1       0
Bank Sta=5008.1,5019.2
XS Rating Curve= 0 ,0
Exp/Cntr=0.3,0.1

Type RM Length L Ch R = 1 ,14803   ,335,335,335
BEGIN DESCRIPTION:
Live Oak Creek 16.0
END DESCRIPTION:
XS GIS Cut Line= 3
      2101562.03     13404299.43        2102009.     13403223.22
      2101956.97     13402239.03
#Sta/Elev= 30
  3926.1  334.66    4024  332.02  4053.3  331.91    4101   329.7  4207.3  326.55
  4260.4   325.9  4353.2  321.55  4548.9  310.77  4654.3  306.17    4704  303.89
  4757.2  298.49  4777.3  298.06  4810.3  297.69  4958.9  299.55  4981.2  298.14
  4988.2  296.78  4993.6  294.83  5006.5  293.18  5007.2  292.38  5016.9  292.38
  5017.6  293.18  5046.8  296.34  5078.7  298.24  5189.8  299.73  5249.9  298.93
  5550.3  301.09  5680.5  304.02  5910.8  312.68  5960.9  316.93    6077  324.65
#Mann= 6 ,-1 , 0
  3926.1      .1       0  4548.9     .08       0  4654.3     .05       0
  4777.3      .1       0  5006.5     .07       0  5017.6      .1       0
Bank Sta=5006.5,5017.6
XS Rating Curve= 0 ,0
Exp/Cntr=0.3,0.1

Type RM Length L Ch R = 1 ,14468   ,732,732,732
BEGIN DESCRIPTION:
Mapping XS 11b85fe5
END DESCRIPTION:
XS GIS Cut Line= 3
      2102308.48     13404073.93       2102299.8     13403561.76
      2102061.21      13402169.3
#Sta/Elev= 30
  4186.2  325.65  4295.1  323.24  4385.2  317.07  4425.2  316.89  4455.2  318.69
  4495.2  314.61  4575.2   312.3  4619.1  309.75  4655.2  307.65  4683.3   304.3
  4688.3  304.76  4718.2  299.67  4735.7  297.23  4776.3     294  4813.8  297.17
  4859.9  297.73  4948.8  297.99  4958.9   297.1  4983.3   289.6    4984   288.8
  4993.7   288.8  4994.4   289.6  5005.8  290.74  5040.1  296.98  5090.8   299.2
  5456.1  298.74  5709.7  303.72  5764.3   303.7  6004.5  319.38  6111.2  324.39
#Mann= 7 ,-1 , 0
  4186.2      .1       0  4619.1     .08       0  4718.2      .1       0
  4859.9     .12       0  4983.3     .07       0  4994.4     .12       0
  5005.8      .1       0
Bank Sta=4983.3,4994.4
XS Rating Curve= 0 ,0
Exp/Cntr=0.3,0.1

Type RM Length L Ch R = 1 ,13736   ,332,332,332
BEGIN DESCRIPTION:
Mapping XS ce447a5c
END DESCRIPTION:
XS GIS Cut Line= 4
      2102820.64     13403913.36      2102729.48     13403314.37
       2102364.9     13402706.73      2102191.29     13402103.42
#Sta/Elev= 30
  4132.8  323.34  4268.8  312.38  4363.8  306.77  4393.2     306  4454.8  302.53
  4505.4   301.1  4745.7  297.75  4872.9  294.96  4894.3   296.4  4927.4  296.59
  4946.8  295.84  4952.6  293.84  4968.1  292.59    4974  290.68  4983.9  289.75
  4984.5  288.95  4994.5  288.95  4995.2  289.75  5005.1  291.32  5010.9  293.89
  5032.3  295.98  5076.1  297.74  5122.3  297.89  5440.4  296.96  5667.6  300.25
  5709.3  301.72  5794.1  307.12  5900.4  311.66  6000.6  314.35  6075.1     318
#Mann= 7 ,-1 , 0
  4132.8      .1       0  4393.2     .05       0  4745.7      .1       0
  4927.4     .12       0  4983.9     .07       0  4995.2     .12       0
  5122.3      .1       0
Bank Sta=4983.9,4995.2
XS Rating Curve= 0 ,0
Exp/Cntr=0.3,0.1

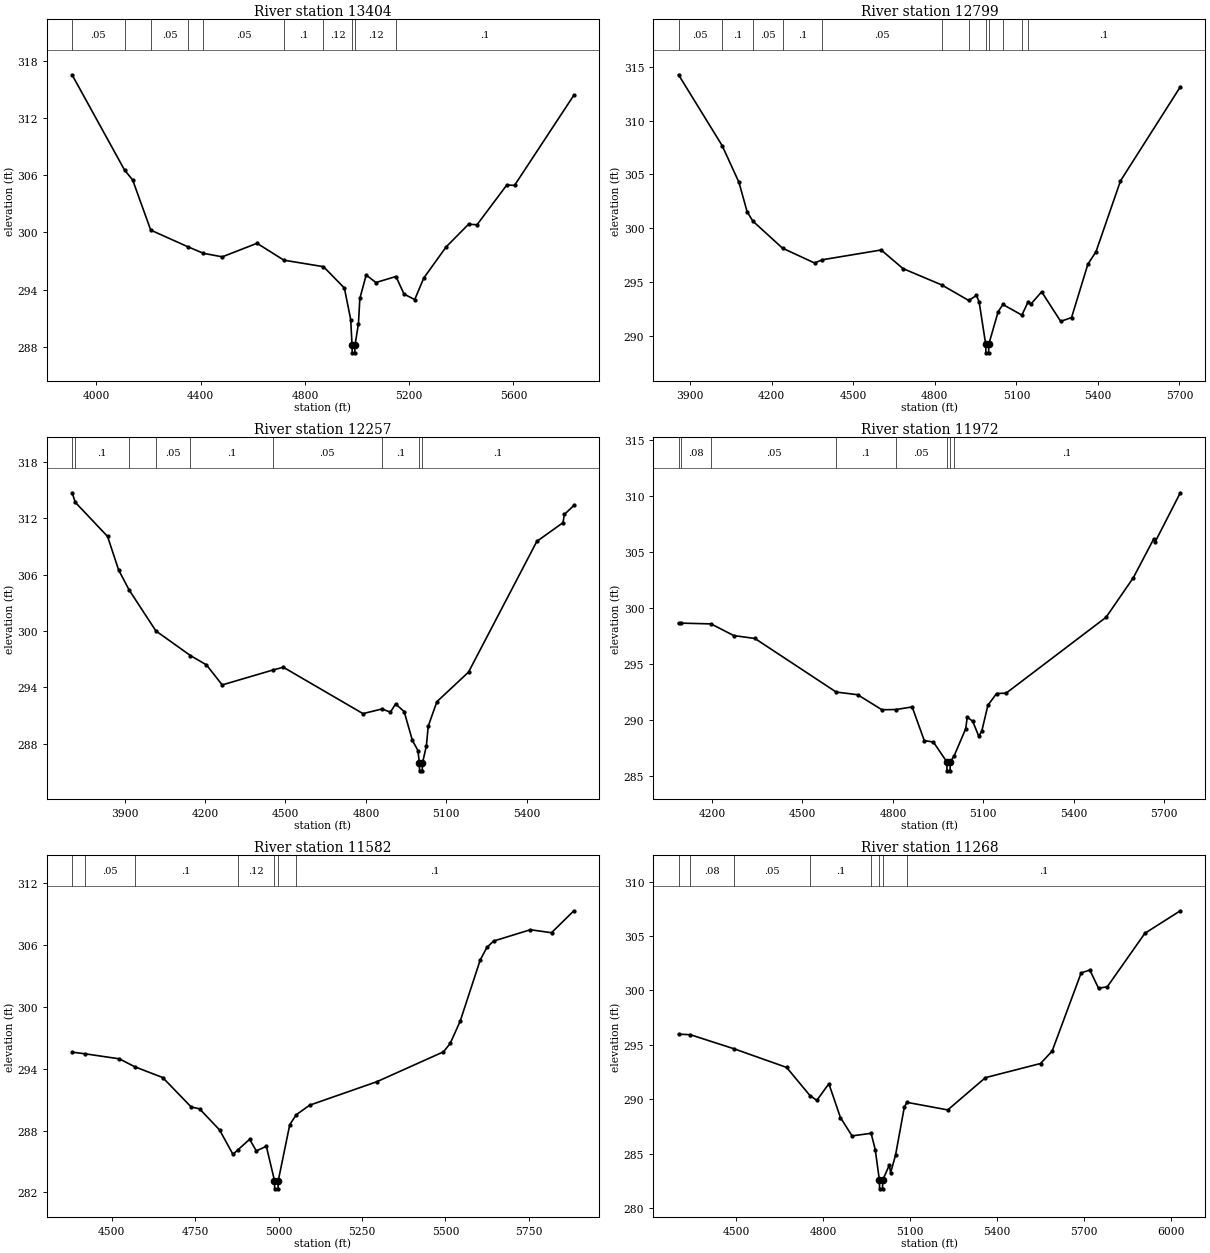
Type RM Length L Ch R = 1 ,13404   ,605,605,605
BEGIN DESCRIPTION:
Mapping XS adc0f76e
END DESCRIPTION:
XS GIS Cut Line= 3
      2102981.22      13403856.9      2102794.59     13403032.25
      2102395.36     13402029.83
#Sta/Elev= 30
    3907  316.51  4108.2  306.53  4139.3  305.49  4208.7  300.23  4351.7  298.48
  4410.9   297.8  4483.1  297.43  4616.4  298.85  4719.4  297.08  4871.3   296.4
  4951.4  294.16  4975.6  290.86  4980.8  288.17  4981.4  287.37  4991.4  287.37
  4992.1  288.17  5005.3  290.41  5010.7  293.07    5035  295.52  5072.5  294.74
  5149.2  295.37  5180.1  293.53  5221.1  292.95  5256.1  295.22  5341.6  298.47
  5427.7  300.85    5460  300.79  5574.3  304.96    5604  304.92  5831.5  314.37
#Mann= 10 ,-1 , 0
    3907     .05       0  4108.2      .1       0  4208.7     .05       0
  4351.7      .1       0  4410.9     .05       0  4719.4      .1       0
  4871.3     .12       0  4980.8     .07       0  4992.1     .12       0
  5149.2      .1       0
Bank Sta=4980.8,4992.1
XS Rating Curve= 0 ,0
Exp/Cntr=0.3,0.1

Type RM Length L Ch R = 1 ,12799   ,542,542,542
BEGIN DESCRIPTION:
Mapping XS 58d2f7f6
END DESCRIPTION:
XS GIS Cut Line= 3
      2103037.64     13403835.18      2102959.52     13403262.28
       2102924.8     13401994.96
#Sta/Elev= 30
  3857.1  314.26  4017.3  307.68  4079.3  304.26  4109.6   301.5  4130.8  300.64
  4239.6  298.13  4357.3  296.75  4386.4  297.05  4602.6  297.96  4682.7  296.23
    4826   294.7  4924.8  293.26  4952.8  293.73  4962.8  293.15  4987.1  289.19
  4987.8  288.39  4997.8  288.39  4998.5  289.19  5032.8  292.21  5050.3  292.89
  5120.3   291.9  5143.6  293.16  5152.9  292.91  5192.9  294.07  5262.9  291.32
  5302.9  291.67  5362.9  296.63  5392.9   297.8    5483  304.39  5703.1  313.14
#Mann= 12 ,-1 , 0
  3857.1     .05       0  4017.3      .1       0  4130.8     .05       0
  4239.6      .1       0  4386.4     .05       0    4826      .1       0
  4924.8     .12       0  4987.1     .07       0  4998.5     .12       0
  5050.3      .1       0  5120.3     .12       0  5143.6      .1       0
Bank Sta=4987.1,4998.5
XS Rating Curve= 0 ,0
Exp/Cntr=0.3,0.1

Type RM Length L Ch R = 1 ,12257   ,285,285,285
BEGIN DESCRIPTION:
Live Oak Creek 15.0
END DESCRIPTION:
XS GIS Cut Line= 3
       2103098.4     13403874.31        2103375.       13402625.
      2103198.25     13402060.07
#Sta/Elev= 30
  3704.2  314.69  3716.4  313.67  3836.6  310.05  3877.6   306.5  3916.4  304.39
  4016.8  300.01  4145.7  297.39  4205.4   296.4  4264.2  294.27  4452.6  295.85
  4492.1  296.15  4789.2  291.22  4859.4  291.71  4891.6  291.38  4910.7  292.25
  4942.8  291.44  4973.5  288.37  4994.2   287.3  4999.5  285.94  5000.2  285.14
  5010.2  285.14  5010.9  285.94  5025.7   287.8  5032.5  289.88  5064.9  292.49
  5182.8  295.63  5437.7  309.53  5535.1  311.51  5540.3  312.39  5575.7  313.34
#Mann= 9 ,-1 , 0
  3704.2     .05       0  3716.4      .1       0  3916.4     .08       0
  4016.8     .05       0  4145.7      .1       0  4452.6     .05       0
  4859.4      .1       0  4999.5     .07       0  5010.9      .1       0
Bank Sta=4999.5,5010.9
XS Rating Curve= 0 ,0
Exp/Cntr=0.3,0.1

Type RM Length L Ch R = 1 ,11972   ,390,390,390
BEGIN DESCRIPTION:
Mapping XS d5ee8486
END DESCRIPTION:
XS GIS Cut Line= 3
      2103515.07     13403687.65      2103558.48     13403062.63
      2103658.28     13402029.86
#Sta/Elev= 30
  4089.1  298.61  4098.2  298.63  4196.9  298.56  4272.2  297.52  4342.4  297.26
  4611.9  292.48  4683.2  292.24  4763.5   290.9  4809.8  290.92  4863.9  291.15
  4904.1  288.15  4934.3  288.02  4978.8  286.25  4979.4  285.45  4989.5  285.45
  4990.2  286.25  5002.5  286.75  5041.5  289.21  5046.6  290.25  5064.9  289.86
    5085  288.52    5095  289.02  5115.1   291.3  5143.8  292.35  5175.4  292.38
  5506.9  299.15  5597.3  302.68  5664.9  306.14  5669.9  305.89  5753.2  310.26
#Mann= 8 ,-1 , 0
  4089.1     .05       0  4098.2     .08       0  4196.9     .05       0
  4611.9      .1       0  4809.8     .05       0  4978.8     .03       0
  4990.2     .05       0  5002.5      .1       0
Bank Sta=4978.8,4990.2
XS Rating Curve= 0 ,0
Exp/Cntr=0.3,0.1

Type RM Length L Ch R = 1 ,11582   ,314,314,314
BEGIN DESCRIPTION:
Mapping XS 07ffd6ce
END DESCRIPTION:
XS GIS Cut Line= 3
      2103931.74     13403496.61      2103918.72     13403162.46
      2103983.83     13401994.88
#Sta/Elev= 30
    4381  295.61  4419.5  295.45  4522.7  294.96  4568.9  294.19  4652.8  293.14
  4738.1  290.28  4762.9  290.11    4823  288.06  4863.1  285.69  4877.5  286.11
  4913.1  287.15  4933.2  286.02  4963.2  286.47  4987.6  283.14  4988.2  282.34
  4998.3  282.34    4999  283.14  5033.4  288.57  5052.8  289.53    5093  290.46
  5293.8  292.73  5494.1  295.64  5514.1  296.45  5544.1  298.61  5604.2  304.56
  5624.3  305.78  5644.3  306.39  5754.5  307.49  5817.8   307.2  5884.8  309.33
#Mann= 7 ,-1 , 0
    4381     .08       0  4419.5     .05       0  4568.9      .1       0
  4877.5     .12       0  4987.6     .07       0    4999     .12       0
  5052.8      .1       0
Bank Sta=4987.6,4999
XS Rating Curve= 0 ,0
Exp/Cntr=0.3,0.1

Type RM Length L Ch R = 1 ,11268   ,705,705,705
BEGIN DESCRIPTION:
Mapping XS e5ccb9d8
END DESCRIPTION:
XS GIS Cut Line= 3
      2104374.45     13403644.22      2104205.18     13403171.14
      2104231.22     13401942.87
#Sta/Elev= 30
  4300.9  295.98  4341.5  295.93  4492.7  294.63  4673.7  292.92  4754.3  290.33
    4778  289.89  4819.5  291.42  4859.5   288.3  4899.5  286.62  4965.3  286.86
  4979.5  285.35  4993.8  282.55  4994.5  281.75  5004.6  281.75  5005.2  282.55
  5027.7  283.92  5032.7  283.24  5049.5  284.85  5079.6  289.24  5088.4  289.71
  5229.6  289.01  5359.6  291.98  5549.7  293.28  5589.7  294.42  5689.7  301.61
  5719.7  301.88  5749.7  300.21  5779.7  300.33  5909.7  305.26  6031.9  307.33
#Mann= 8 ,-1 , 0
  4300.9     .05       0  4341.5     .08       0  4492.7     .05       0
  4754.3      .1       0  4965.3     .12       0  4993.8     .07       0
  5005.2     .12       0  5088.4      .1       0
Bank Sta=4993.8,5005.2
XS Rating Curve= 0 ,0
Exp/Cntr=0.3,0.1

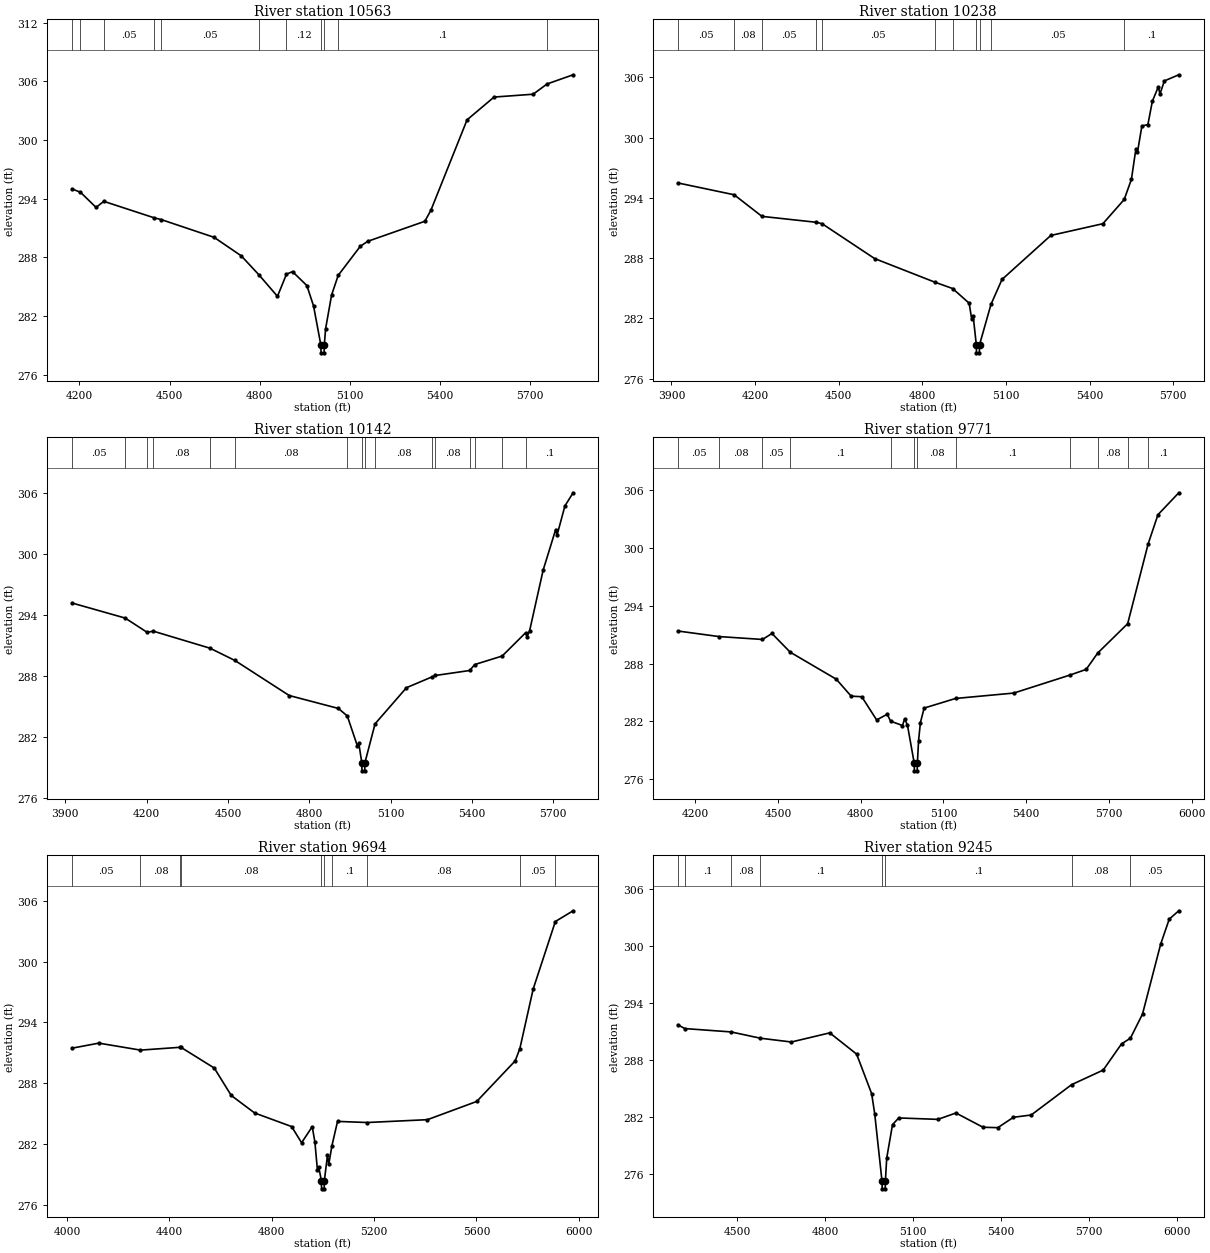
Type RM Length L Ch R = 1 ,10563   ,325,325,325
BEGIN DESCRIPTION:
Mapping XS c74fbaf8
END DESCRIPTION:
XS GIS Cut Line= 3
      2104656.56     13403544.45      2104730.35     13402945.44
      2104669.59     13401882.11
#Sta/Elev= 30
  4175.2     295  4203.3  294.66  4255.2  293.11  4281.1  293.73  4447.2  292.06
  4472.6  291.86  4648.2  290.05  4738.9  288.15  4797.6  286.21  4859.3  284.01
  4889.3  286.28  4909.4  286.54  4957.3  285.11  4979.5  283.02  5003.8  279.03
  5004.5  278.23  5014.7  278.23  5015.3  279.03  5019.6   280.7  5039.6  284.15
  5061.6  286.16  5135.1  289.13  5159.8  289.64  5350.1  291.69  5370.1  292.81
  5490.7  302.07  5580.5   304.4  5710.7  304.69  5757.1  305.74  5843.8  306.68
#Mann= 11 ,-1 , 0
  4175.2     .05       0  4203.3     .08       0  4281.1     .05       0
  4447.2      .1       0  4472.6     .05       0  4797.6      .1       0
  4889.3     .12       0  5003.8     .07       0  5015.3     .12       0
  5061.6      .1       0  5757.1     .05       0
Bank Sta=5003.8,5015.3
XS Rating Curve= 0 ,0
Exp/Cntr=0.3,0.1

Type RM Length L Ch R = 1 ,10238   ,96,96,96
BEGIN DESCRIPTION:
Mapping XS d24af12b
END DESCRIPTION:
XS GIS Cut Line= 6
      2104695.64     13403704.97       2104864.9     13403327.39
      2104951.71     13403045.27      2105008.13     13402741.45
      2105107.96     13402415.93      2105324.95     13402034.02
#Sta/Elev= 30
  3922.5  295.49    4125  294.31  4224.7  292.16  4420.1  291.57  4440.5  291.43
    4629  287.96  4844.3  285.62  4908.8  284.98  4968.1  283.52  4977.2  281.94
  4982.4  282.28  4993.8  279.38  4994.4  278.58  5004.6  278.58  5005.3  279.38
  5046.4   283.4  5085.9  285.88    5261  290.26  5447.9  291.43  5524.4  293.84
  5550.3  295.85  5566.1  298.84  5571.9  298.53  5587.8  301.15  5609.4   301.3
  5625.3  303.61  5646.9  305.06  5652.6  304.33  5668.5  305.64  5720.2  306.25
#Mann= 11 ,-1 , 0
  3922.5     .05       0    4125     .08       0  4224.7     .05       0
  4420.1     .08       0  4440.5     .05       0  4844.3      .1       0
  4908.8     .08       0  4993.8     .07       0  5005.3     .08       0
  5046.4     .05       0  5524.4      .1       0
Bank Sta=4993.8,5005.3
XS Rating Curve= 0 ,0
Exp/Cntr=0.3,0.1

Type RM Length L Ch R = 1 ,10142   ,371,371,371
BEGIN DESCRIPTION:
Mapping XS e91def8f
END DESCRIPTION:
XS GIS Cut Line= 6
      2104782.42     13403705.03      2104947.37     13403283.98
      2105073.23       13402876.      2105147.02     13402528.78
      2105359.69     13402281.38      2105385.73     13401994.94
#Sta/Elev= 30
  3925.1  295.19  4121.1  293.71    4202  292.31  4225.1  292.42  4433.9  290.75
  4525.4  289.55  4726.1   286.1  4907.5  284.83  4940.3  284.09  4977.6  281.14
  4982.7   281.4  4993.8   279.5  4994.4   278.7  5004.6   278.7  5005.3   279.5
  5042.7  283.32  5158.6  286.87  5253.6  287.94  5265.3  288.07  5392.1  288.56
  5409.9  289.14  5511.5  289.98    5598  292.27  5603.3  291.89  5612.4  292.43
  5662.6  298.42  5708.8  302.41  5713.8  301.85  5742.9  304.73  5773.1  306.02
#Mann= 16 ,-1 , 0
  3925.1     .05       0  4121.1     .08       0    4202     .05       0
  4225.1     .08       0  4433.9     .05       0  4525.4     .08       0
  4940.3      .1       0  4993.8     .07       0  5005.3      .1       0
  5042.7     .08       0  5253.6      .1       0  5265.3     .08       0
  5392.1     .05       0  5409.9     .08       0  5511.5     .05       0
    5598      .1       0
Bank Sta=4993.8,5005.3
XS Rating Curve= 0 ,0
Exp/Cntr=0.3,0.1

Type RM Length L Ch R = 1 ,9771    ,77,77,77
BEGIN DESCRIPTION:
Mapping XS dce89d8b
END DESCRIPTION:
XS GIS Cut Line= 6
      2105316.28     13403639.85      2105272.89     13403422.87
      2105398.76      13402854.3      2105437.82      13402585.2
      2105572.37     13402246.66      2105555.03     13401869.49
#Sta/Elev= 30
    4136  291.39  4286.1  290.81  4443.5  290.51  4477.8  291.13  4543.9  289.19
  4711.2  286.38  4765.1  284.62  4803.6  284.56  4857.5  282.15    4896  282.74
  4908.1  282.02  4951.2  281.57  4959.1  282.26  4969.2  281.62  4993.8  277.66
  4994.4  276.86  5004.6  276.86  5005.3  277.66  5009.6  280.01  5016.3  281.88
  5029.8  283.38  5143.8  284.38  5354.9  284.94  5559.6  286.82  5617.5   287.4
  5659.4   289.1    5768  292.15  5842.3  300.44  5877.8  303.47  5953.4  305.75
#Mann= 12 ,-1 , 0
    4136     .05       0  4286.1     .08       0  4443.5     .05       0
  4543.9      .1       0  4908.1     .08       0  4993.8     .07       0
  5005.3     .08       0  5143.8      .1       0  5559.6     .05       0
  5659.4     .08       0    5768     .05       0  5842.3      .1       0
Bank Sta=4993.8,5005.3
XS Rating Curve= 0 ,0
Exp/Cntr=0.3,0.1

Type RM Length L Ch R = 1 ,9694    ,449,449,449
BEGIN DESCRIPTION:
Mapping XS ccd8554c
END DESCRIPTION:
XS GIS Cut Line= 6
      2105572.35     13403665.91      2105355.35     13403470.62
      2105450.84     13402915.06       2105511.6     13402698.05
      2105628.79     13402311.76      2105594.11      13401839.3
#Sta/Elev= 30
  4019.2  291.44  4123.9  291.94  4286.7  291.25  4442.3  291.53  4445.2  291.52
  4575.1  289.48  4641.5  286.77  4732.9  285.04  4877.5   283.7  4916.4   282.1
    4958  283.69  4968.4  282.17  4978.3   279.4  4983.5  279.69  4993.8  278.35
  4994.4  277.55  5004.6  277.55  5005.3  278.35  5017.6  280.86  5022.8     280
    5035  281.81  5056.9  284.21  5172.8   284.1  5408.2  284.38  5600.9  286.18
  5751.3  290.19  5769.5   291.4  5821.5  297.28  5908.2  303.95  5977.6  305.01
#Mann= 10 ,-1 , 0
  4019.2     .05       0  4286.7     .08       0  4442.3     .05       0
  4445.2     .08       0  4993.8     .07       0  5005.3     .08       0
    5035      .1       0  5172.8     .08       0  5769.5     .05       0
  5908.2      .1       0
Bank Sta=4993.8,5005.3
XS Rating Curve= 0 ,0
Exp/Cntr=0.3,0.1

Type RM Length L Ch R = 1 ,9245    ,476,476,476
BEGIN DESCRIPTION:
Mapping XS 89bee35d
END DESCRIPTION:
XS GIS Cut Line= 3
      2105980.35     13403540.01      2105919.59      13402984.5
      2105663.52     13401864.73
#Sta/Elev= 30
  4297.6  291.72  4322.3  291.32  4479.4  290.97    4579  290.31  4684.9  289.91
  4815.7  290.87  4907.2  288.64  4958.5  284.48  4968.8  282.39  4993.8  275.28
  4994.4  274.48  5004.6  274.48  5005.3  275.28  5009.8  277.71  5029.6  281.23
  5050.8  281.93  5184.2  281.78  5245.7  282.45    5338  280.95  5388.5  280.91
  5441.7     282  5502.2  282.24    5640  285.43  5747.5  286.96  5809.9  289.71
  5840.3  290.31  5881.5  292.85  5943.3  300.19  5972.5  302.82  6005.1   303.7
#Mann= 8 ,-1 , 0
  4297.6     .05       0  4322.3      .1       0  4479.4     .08       0
    4579      .1       0  4993.8     .07       0  5005.3      .1       0
    5640     .08       0  5840.3     .05       0
Bank Sta=4993.8,5005.3
XS Rating Curve= 0 ,0
Exp/Cntr=0.3,0.1

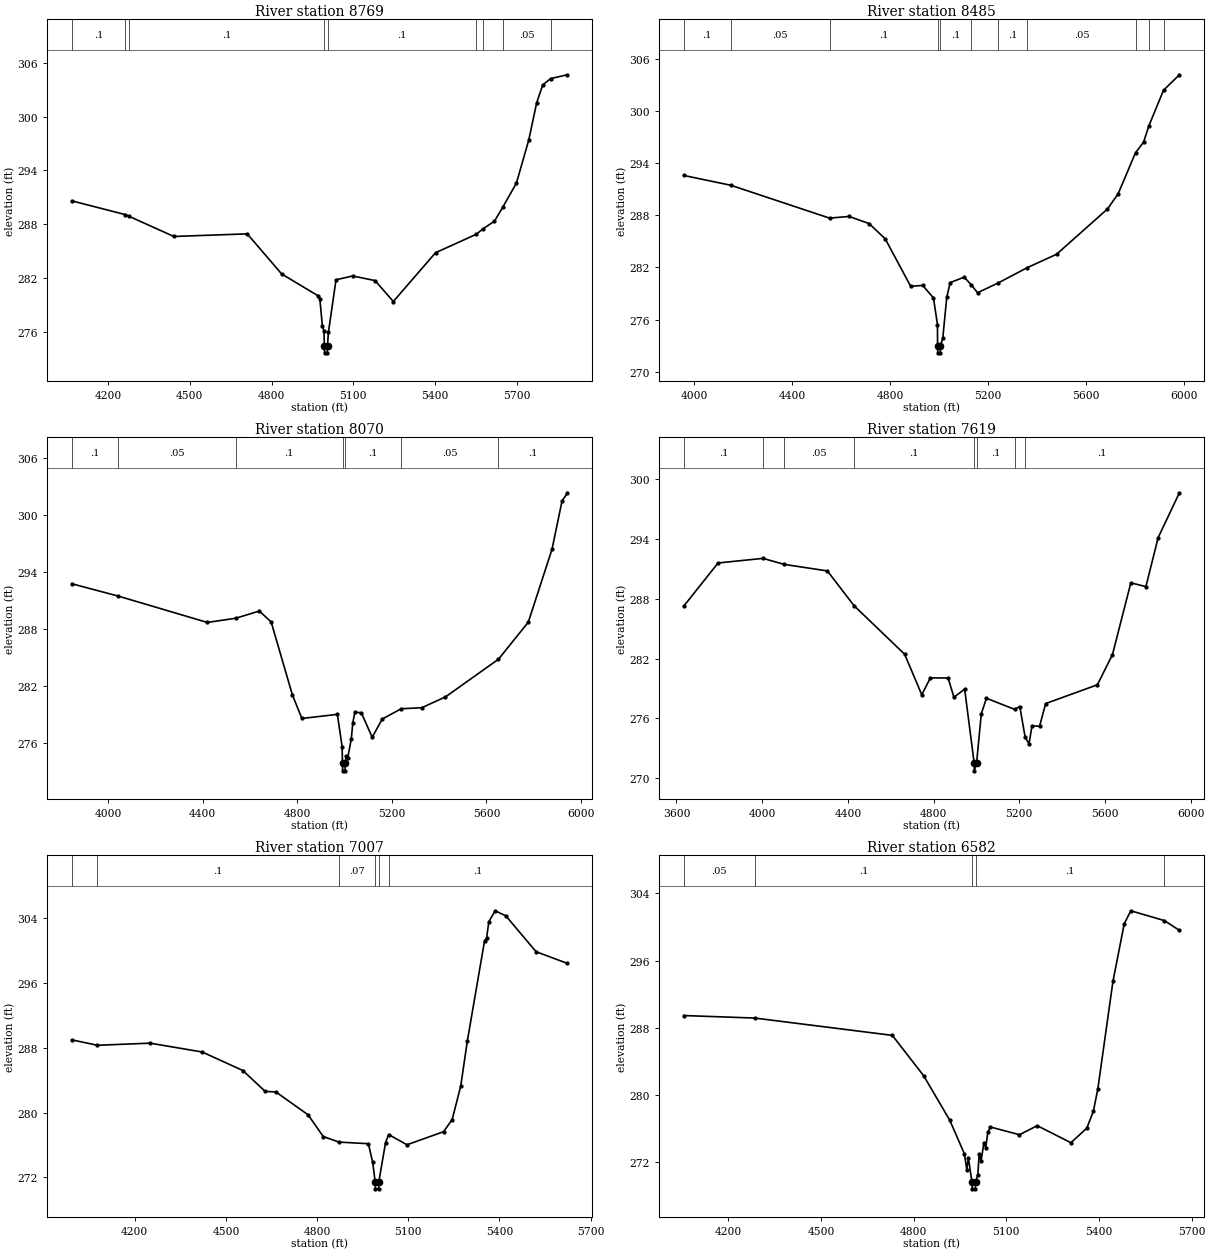
Type RM Length L Ch R = 1 ,8769    ,284,284,284
BEGIN DESCRIPTION:
Mapping XS 6e9b178e
END DESCRIPTION:
XS GIS Cut Line= 3
      2106305.88     13403461.96       2106158.3     13402724.09
      2105668.42       13401779.
#Sta/Elev= 30
  4067.8  290.61  4263.4  289.08  4276.7   288.9    4442  286.64    4711  286.93
  4837.2  282.46    4970  280.04    4977  279.72  4986.5  276.62  4992.1  276.14
  4993.7  274.47  4994.4  273.67  5004.6  273.67  5005.2  274.47  5008.6  275.98
  5036.4  281.81  5097.2  282.24  5179.7  281.72  5246.4  279.39  5401.3  284.83
    5551  286.89  5576.1  287.51    5617  288.34  5647.5  289.89  5697.8   292.6
  5742.9  297.39  5771.9  301.54    5794  303.52  5823.2  304.24  5884.8  304.66
#Mann= 9 ,-1 , 0
  4067.8      .1       0  4263.4     .05       0  4276.7      .1       0
  4993.7     .07       0  5005.2      .1       0    5551     .05       0
  5576.1     .08       0  5647.5     .05       0  5823.2      .1       0
Bank Sta=4993.7,5005.2
XS Rating Curve= 0 ,0
Exp/Cntr=0.3,0.1

Type RM Length L Ch R = 1 ,8485    ,415,415,415
BEGIN DESCRIPTION:
Mapping XS 1e2a2d3a
END DESCRIPTION:
XS GIS Cut Line= 3
      2106601.01     13403470.58      2106531.57     13402862.98
      2105859.42     13401622.76
#Sta/Elev= 30
    3958  292.59  4150.1  291.46  4553.1  287.68  4632.8  287.87  4714.6  287.05
  4780.2  285.29  4883.9  279.84  4933.3  279.93    4977  278.49  4993.2  275.43
  4993.7  272.98  4994.3  272.18  5004.6  272.18  5005.2  272.98  5015.1  273.91
  5031.2  278.58    5045  280.26  5102.5  280.89  5131.5  279.99  5156.8  279.09
  5241.7  280.23  5359.5  281.98  5479.1  283.52  5686.4  288.72  5730.1  290.46
  5801.2  295.21  5833.8   296.4  5856.1  298.33  5915.4  302.39  5980.2  304.17
#Mann= 11 ,-1 , 0
    3958      .1       0  4150.1     .05       0  4553.1      .1       0
  4993.7     .07       0  5005.2      .1       0  5131.5     .07       0
  5241.7      .1       0  5359.5     .05       0  5801.2     .08       0
  5856.1     .05       0  5915.4      .1       0
Bank Sta=4993.7,5005.2
XS Rating Curve= 0 ,0
Exp/Cntr=0.3,0.1

Type RM Length L Ch R = 1 ,8070    ,451,451,451
BEGIN DESCRIPTION:
Live Oak Creek 9.0
END DESCRIPTION:
XS GIS Cut Line= 3
       2106684.2     13403478.52        2106675.       13402325.
      2106174.98     13401524.96
#Sta/Elev= 30
  3845.9  292.74  4041.5  291.45  4419.4  288.67  4539.3  289.11  4639.4  289.87
  4689.4  288.72  4779.4  281.03  4819.4  278.57  4969.5     279  4989.5  275.62
  4991.2  273.86  4991.8  273.06  5002.1  273.06  5002.7  273.86  5007.1   274.6
    5013  274.41  5028.3  276.39  5034.8  278.12  5043.7  279.23  5070.8  279.17
  5116.8  276.59  5159.2  278.51  5239.6  279.59  5326.7   279.7  5426.9  280.84
    5651   284.8  5777.2   288.7  5877.4  296.36  5919.9  301.44  5942.9  302.31
#Mann= 7 ,-1 , 0
  3845.9      .1       0  4041.5     .05       0  4539.3      .1       0
  4991.2     .07       0  5002.7      .1       0  5239.6     .05       0
    5651      .1       0
Bank Sta=4991.2,5002.7
XS Rating Curve= 0 ,0
Exp/Cntr=0.3,0.1

Type RM Length L Ch R = 1 ,7619    ,612,612,612
BEGIN DESCRIPTION:
Live Oak Creek 8.0
END DESCRIPTION:
XS GIS Cut Line= 3
      2107031.42      13403565.3        2107075.       13402175.
      2106475.03     13401475.03
#Sta/Elev= 30
  3634.1  287.24  3794.5  291.57  4004.2  292.03  4102.8  291.43  4304.7  290.77
    4429  287.29  4664.9  282.43    4745  278.37    4785  280.06  4867.8  280.05
    4895  278.12    4945  278.93  4989.3  271.55  4989.9  270.75  5000.8  271.55
  5022.6  276.45  5046.5  278.02  5177.9  276.91  5202.3  277.19  5227.2  274.12
  5245.1  273.45  5259.4  275.26  5294.5  275.21  5323.1  277.49  5564.5  279.37
  5634.8   282.4  5720.4  289.58  5790.6   289.2  5847.7   294.1    5947   298.6
#Mann= 8 ,-1 , 0
  3634.1      .1       0  4004.2     .08       0  4102.8     .05       0
    4429      .1       0  4989.3     .07       0  5000.8      .1       0
  5177.9     .07       0  5227.2      .1       0
Bank Sta=4989.3,5000.8
XS Rating Curve= 0 ,0
Exp/Cntr=0.3,0.1

Type RM Length L Ch R = 1 ,7007    ,425,425,425
BEGIN DESCRIPTION:
Mapping XS d16adecc
END DESCRIPTION:
XS GIS Cut Line= 3
      2107529.82     13402680.64      2107338.86     13402081.73
      2106658.72     13401345.27
#Sta/Elev= 30
  3992.6  288.99  4077.1  288.32  4250.3  288.58  4421.8  287.49  4555.8   285.2
  4628.9  282.63  4664.1  282.56  4770.1  279.74    4820  277.06  4871.7  276.37
  4968.6  276.17  4982.8  273.88  4991.2   271.4  4991.8   270.6  5002.1   270.6
  5002.7   271.4  5025.1  276.31  5035.3   277.3  5095.6  276.04  5215.8  277.65
  5244.2  279.14  5272.5  283.29  5294.1  288.82  5350.8   301.2  5357.6  301.55
  5364.9  303.57  5385.9  304.92  5421.1  304.29  5520.3  299.87  5623.7  298.42
#Mann= 6 ,-1 , 0
  3992.6     .05       0  4077.1      .1       0  4871.7     .07       0
  4991.2     .07       0  5002.7     .07       0  5035.3      .1       0
Bank Sta=4991.2,5002.7
XS Rating Curve= 0 ,0
Exp/Cntr=0.3,0.1

Type RM Length L Ch R = 1 ,6582    ,320,320,320
BEGIN DESCRIPTION:
Live Oak Creek 7.0
END DESCRIPTION:
XS GIS Cut Line= 3
        2107634.     13402711.06        2107475.       13401775.
      2107121.86     13401222.37
#Sta/Elev= 30
  4055.1  289.47  4285.3  289.17  4730.7  287.11  4832.1  282.31  4916.7  277.01
    4964  273.02  4971.9  271.13    4977  272.52  4988.6  269.64  4989.3  268.84
  4999.6  268.84  5000.2  269.64  5007.5  270.51  5012.2  273.02  5018.1  272.16
  5027.4  274.34  5033.3  273.75  5040.2  275.62  5048.6   276.2  5142.4  275.28
    5200  276.36  5309.1  274.33  5360.6  276.07  5381.8  278.07  5396.2  280.73
  5445.3  293.56  5481.7  300.39    5503  301.94  5611.8  300.77  5660.4  299.61
#Mann= 5 ,-1 , 0
  4055.1     .05       0  4285.3      .1       0  4988.6     .07       0
  5000.2      .1       0  5611.8     .05       0
Bank Sta=4988.6,5000.2
XS Rating Curve= 0 ,0
Exp/Cntr=0.3,0.1