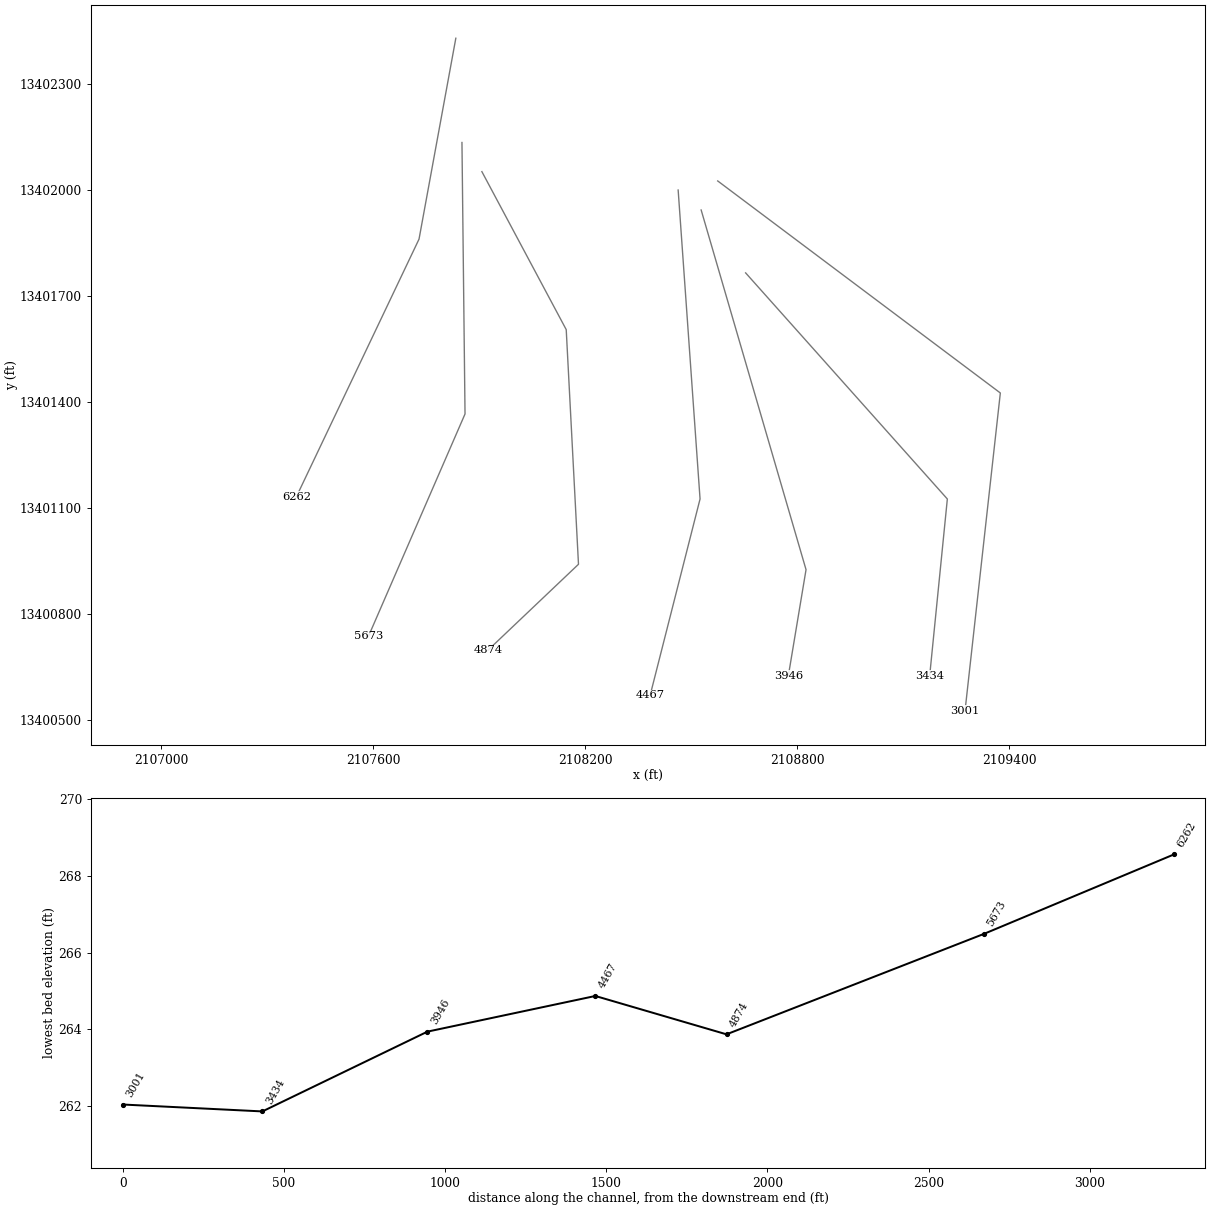
HEC-RAS study Live Oak Creek.prj: Live Oak Creek Base Level Engineering

--- Live Oak Creek.g01 (geometry) --- (continued)

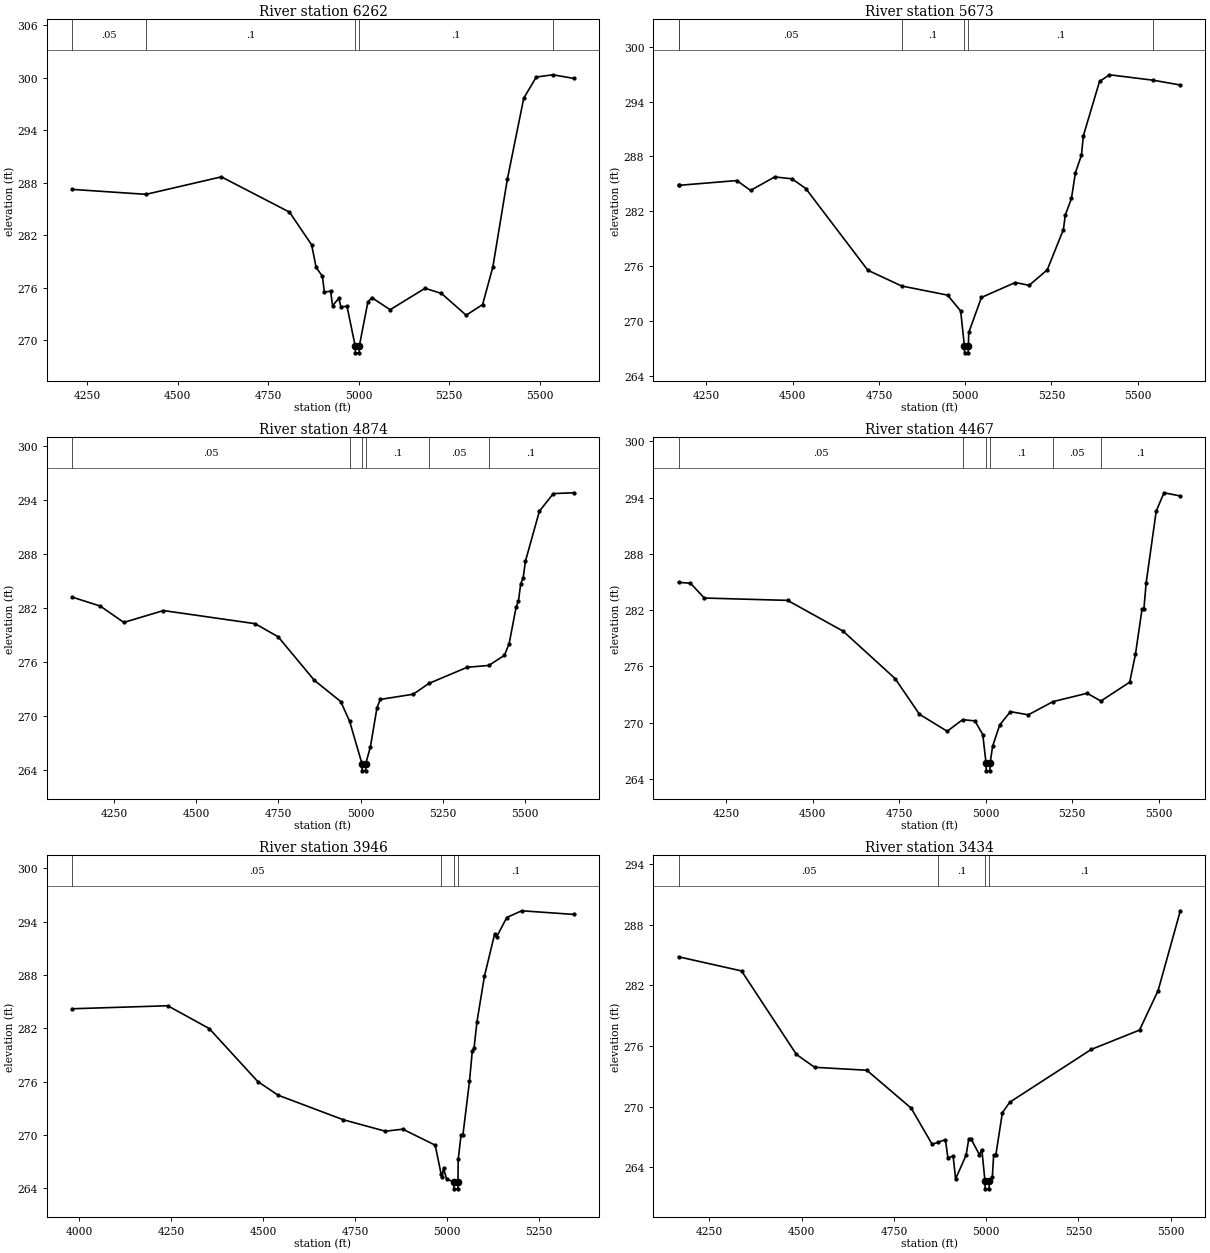
Type RM Length L Ch R = 1 ,6262    ,589,589,589
BEGIN DESCRIPTION:
Mapping XS b7e11313
END DESCRIPTION:
XS GIS Cut Line= 3
      2107833.65     13402428.93      2107729.48     13401860.37
      2107382.28     13401131.24
#Sta/Elev= 30
  4208.5  287.25  4412.6  286.68  4620.7  288.68  4808.8  284.65    4870  280.91
  4882.5  278.32  4899.7  277.32  4905.2  275.51  4922.4  275.61  4927.9  273.95
  4945.1  274.79  4950.6  273.84  4967.8  273.86  4990.2  269.36  4990.9  268.56
  5001.2  268.56  5001.8  269.36  5025.1  274.33  5035.9  274.88  5086.8  273.49
  5183.2  275.94  5228.6  275.35  5296.7  272.86  5342.1  274.08  5370.4  278.37
  5410.3  288.38  5455.7  297.67  5490.3  300.09  5536.3  300.35  5594.1  299.93
#Mann= 5 ,-1 , 0
  4208.5     .05       0  4412.6      .1       0  4990.2     .07       0
  5001.8      .1       0  5536.3     .05       0
Bank Sta=4990.2,5001.8
XS Rating Curve= 0 ,0
Exp/Cntr=0.3,0.1

Type RM Length L Ch R = 1 ,5673    ,799,799,799
BEGIN DESCRIPTION:
Live Oak Creek 6.0
END DESCRIPTION:
XS GIS Cut Line= 3
      2107851.01     13402133.81      2107859.69     13401365.58
      2107586.24      13400736.2
#Sta/Elev= 30
  4169.2  284.84  4171.1  284.83    4338  285.35    4378  284.27    4448  285.75
    4498  285.54    4538  284.48    4718  275.53  4815.7  273.81    4949  272.81
    4987  271.07  4997.7  267.29  4998.3  266.49  5008.7  266.49  5009.3  267.29
  5010.5  268.72  5047.1  272.55  5145.3  274.19  5185.5  273.88  5237.9  275.57
  5284.8  279.99  5290.2  281.56  5308.2  283.41  5319.7  286.23  5337.1  288.12
  5342.6  290.25  5389.5   296.2  5418.4  296.93  5545.9  296.33  5623.7  295.81
#Mann= 6 ,-1 , 0
  4169.2      .1       0  4171.1     .05       0  4815.7      .1       0
  4997.7     .07       0  5009.3      .1       0  5545.9     .05       0
Bank Sta=4997.7,5009.3
XS Rating Curve= 0 ,0
Exp/Cntr=0.3,0.1

Type RM Length L Ch R = 1 ,4874    ,407,407,407
BEGIN DESCRIPTION:
Mapping XS 2500123f
END DESCRIPTION:
XS GIS Cut Line= 4
      2107907.42     13402051.38      2108146.15      13401604.3
      2108180.87     13400940.23      2107924.77     13400697.15
#Sta/Elev= 30
  4122.9  283.21  4208.6  282.21  4280.1  280.39  4400.5  281.71  4679.1  280.25
  4749.2  278.79  4859.3  273.94  4939.5  271.58  4966.5  269.37  5003.8  264.67
  5004.4  263.87  5014.8  263.87  5015.4  264.67  5029.6  266.56  5049.6  270.91
  5059.6  271.82  5159.8   272.4  5207.3   273.6  5323.8   275.4  5389.2   275.6
    5437  276.73  5451.2  278.04  5472.3  282.09  5479.5  282.79  5486.4  284.71
  5493.7  285.35  5500.6  287.19    5543  292.77  5585.5  294.73  5647.8  294.82
#Mann= 6 ,-1 , 0
  4122.9     .05       0  4966.5      .1       0  5003.8     .07       0
  5015.4      .1       0  5207.3     .05       0  5389.2      .1       0
Bank Sta=5003.8,5015.4
XS Rating Curve= 0 ,0
Exp/Cntr=0.3,0.1

Type RM Length L Ch R = 1 ,4467    ,521,521,521
BEGIN DESCRIPTION:
Live Oak Creek 5.0
END DESCRIPTION:
XS GIS Cut Line= 3
      2108462.99     13401999.31        2108525.       13401125.
      2108383.63      13400569.3
#Sta/Elev= 30
  4112.7  284.96  4147.1  284.87  4187.2  283.29  4427.8  283.04  4588.2  279.76
  4738.6   274.7  4808.8   270.9    4889  269.09  4933.7  270.33  4969.2  270.19
  4991.8  268.73  5001.3  265.67  5001.9  264.87  5012.3  264.87  5012.9  265.67
  5020.2  267.49  5040.8  269.77  5071.8  271.18  5123.3  270.84  5194.8  272.25
  5293.5  273.14    5333  272.31  5416.3  274.32  5432.9  277.28    5452  282.13
  5457.2  282.08  5463.9  284.92  5492.9  292.55  5515.4  294.51  5562.6  294.17
#Mann= 6 ,-1 , 0
  4112.7     .05       0  4933.7      .1       0  5001.3     .07       0
  5012.9      .1       0  5194.8     .05       0    5333      .1       0
Bank Sta=5001.3,5012.9
XS Rating Curve= 0 ,0
Exp/Cntr=0.3,0.1

Type RM Length L Ch R = 1 ,3946    ,512,512,512
BEGIN DESCRIPTION:
Live Oak Creek 4.0
END DESCRIPTION:
XS GIS Cut Line= 3
      2108528.09     13401942.86        2108825.       13400925.
        2108775.     13400625.02
#Sta/Elev= 30
  3980.9  284.19    4241  284.53  4353.7  281.97  4485.8  276.01  4541.2  274.47
  4718.3  271.71  4832.9  270.42  4880.1  270.65  4968.3  268.85  4984.3  265.61
  4985.8  265.23    4991  266.24  4999.5  265.02  5018.6  264.74  5019.2  263.94
  5029.6  263.94  5030.2  264.74  5030.8  267.24  5038.6  270.01  5043.7  270.01
  5061.5  276.04  5069.1  279.42  5074.1  279.82  5081.7  282.69    5102  287.82
  5129.9   292.6    5135  292.25  5162.8  294.45  5203.4  295.21  5345.3   294.8
#Mann= 4 ,-1 , 0
  3980.9     .05       0  4984.3      .1       0  5018.6     .07       0
  5030.2      .1       0
Bank Sta=5018.6,5030.2
XS Rating Curve= 0 ,0
Exp/Cntr=0.3,0.1

Type RM Length L Ch R = 1 ,3434    ,433,433,433
BEGIN DESCRIPTION:
Live Oak Creek 3.0
END DESCRIPTION:
XS GIS Cut Line= 3
      2108653.99     13401764.86        2109225.       13401125.
        2109175.     13400624.99
#Sta/Elev= 30
  4166.3  284.81  4337.1  283.41  4485.9  275.15  4535.2  273.88  4676.5  273.59
  4796.9  269.84  4853.8  266.26  4870.3  266.48  4889.7  266.72  4896.4  264.93
  4910.6   265.1  4917.3  262.84  4945.7  265.19  4953.2  266.83  4959.9  266.75
  4981.7  265.24  4988.4  265.74  4996.8  262.66  4997.4  261.86  5007.8  261.86
  5008.4  262.66  5016.8  263.01  5020.5  265.22  5026.4  265.22    5044  269.38
  5064.1  270.43  5285.2  275.65  5415.8  277.56  5466.1  281.46  5526.4  289.36
#Mann= 4 ,-1 , 0
  4166.3     .05       0  4870.3      .1       0  4996.8     .07       0
  5008.4      .1       0
Bank Sta=4996.8,5008.4
XS Rating Curve= 0 ,0
Exp/Cntr=0.3,0.1

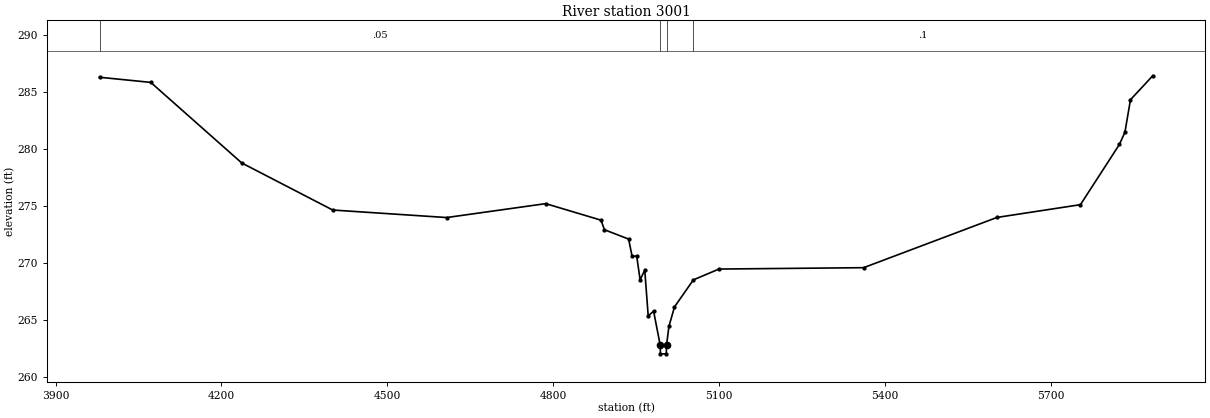
Type RM Length L Ch R = 1 ,3001    ,0,0,0
BEGIN DESCRIPTION:
Live Oak Creek 2.0
END DESCRIPTION:
XS GIS Cut Line= 3
      2108574.99     13402025.01        2109375.       13401425.
      2109274.99     13400524.95
#Sta/Elev= 30
  3979.4  286.31  4072.1  285.86  4236.7  278.79  4401.3  274.66  4607.5     274
  4786.7  275.22  4886.7  273.77    4893  272.93  4936.7  272.11    4943  270.59
  4951.3  270.63  4957.5  268.53  4965.9  269.39  4972.1  265.38  4981.9  265.78
  4993.7  262.84  4994.3  262.04  5004.8  262.04  5005.4  262.84  5009.6  264.44
  5019.7  266.16  5053.8  268.53  5100.2  269.48  5361.8   269.6  5603.2  274.01
  5754.2  275.13  5824.6  280.41  5834.6  281.48  5844.7  284.34    5885  286.44
#Mann= 4 ,-1 , 0
  3979.4     .05       0  4993.7     .03       0  5005.4     .05       0
  5053.8      .1       0
Bank Sta=4993.7,5005.4
XS Rating Curve= 0 ,0
Exp/Cntr=0.3,0.1
LCMann Table=0

Chan Stop Cuts=-1
Use User Specified Reach Order=0
Composite Channel Slope=5