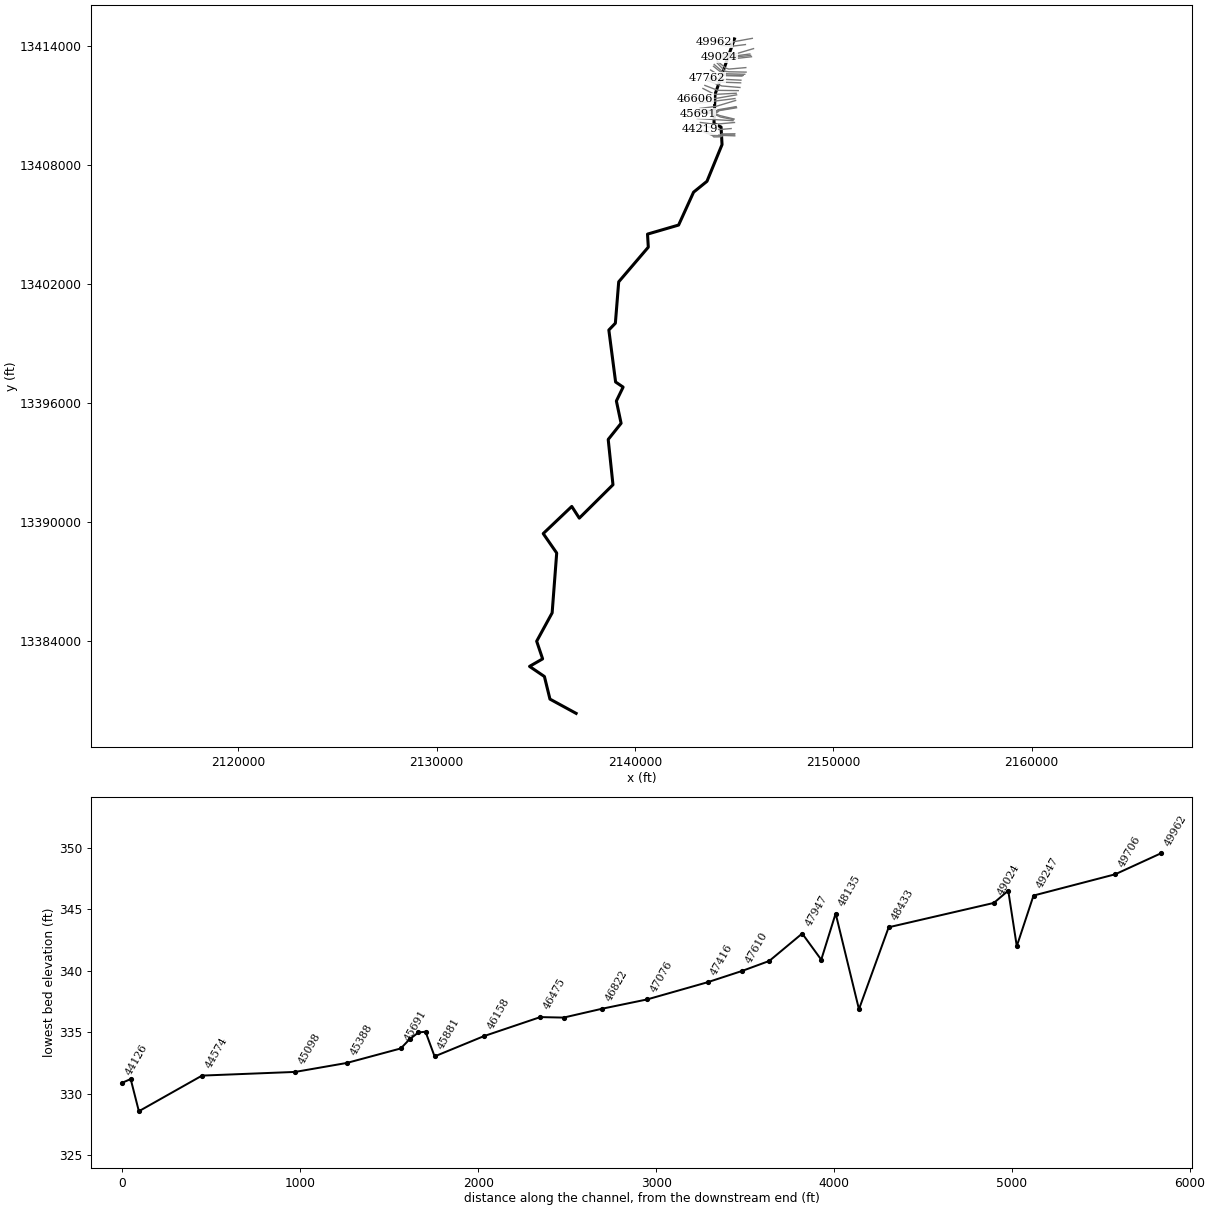
--- Mustang Branch.prj (project) ---

Proj Title=Mustang Branch Base Level Engineering
Current Plan=p01
Default Exp/Contr=0.3,0.1
English Units
Geom File=g01
Flow File=f01
Plan File=p01
Y Axis Title=Elevation
X Axis Title(PF)=Main Channel Distance
X Axis Title(XS)=Station
BEGIN DESCRIPTION:
Mustang Branch
END DESCRIPTION:
DSS Export Rating Curves= 0
DSS Export Rating Curve Sorted= 0
DSS Export Volume Flow Curves= 0
DXF OffsetX= 0
DXF OffsetY= 0
DXF ScaleX= 1
DXF ScaleY= 10

--- Mustang Branch.p01 (plan) ---

Plan Title=Multiple Run
Short Identifier=Multiple
Geom File=g01
Flow File=f01
Subcritical Flow
K Sum by GR= 0
Std Step Tol= 0.01
Critical Tol= 0.01
Num of Std Step Trials= 20
Max Error Tol= 0.3
Flow Tol Ratio= 0.001
Split Flow NTrial= 30
Split Flow Tol= 0.02
Split Flow Ratio= 0.02
Log Output Level= 0
Friction Slope Method= 1
Unsteady Friction Slope Method= 2
Unsteady Bridges Friction Slope Method= 1
Parabolic Critical Depth
Global Vel Dist=  1 , 1 , 1
Global Log Level= 0
CheckData=True
Encroach Param= -1, 0, 0, 0
BEGIN DESCRIPTION:
Multiple Run
END DESCRIPTION:

--- Mustang Branch.f01 (steady flow) ---

Flow Title=Multiple
Program Version=5.05
Number of Profiles= 7
Profile Names=10-year,25-year,50-year,1pct_min,100-year,1pct_plu,500-year
River Rch & RM=Mustang Branch,Reach-1         ,49962
     156     210     253     152     304     607     444
River Rch & RM=Mustang Branch,Reach-1         ,46158
     229     314     383     233     464     926     694
River Rch & RM=Mustang Branch,Reach-1         ,40414
     301     418     514     315     629    1254     955
River Rch & RM=Mustang Branch,Reach-1         ,35063
     372     522     647     399     795    1587    1223
River Rch & RM=Mustang Branch,Reach-1         ,32808
     423     596     740     457     913    1821    1410
River Rch & RM=Mustang Branch,Reach-1         ,27063
     447     630     784     485     967    1930    1496
River Rch & RM=Mustang Branch,Reach-1         ,21973
     470     665     828     512    1022    2039    1583
River Rch & RM=Mustang Branch,Reach-1         ,19781
     493     698     871     540    1077    2148    1672
River Rch & RM=Mustang Branch,Reach-1         ,15722
     526     747     933     579    1155    2305    1799
River Rch & RM=Mustang Branch,Reach-1         ,6309
     682     979    1232     770    1536    3065    2428
Boundary for River Rch & Prof#=Mustang Branch,Reach-1         , 1
Up Type= 0
Dn Type= 3
Dn Slope=0.00718
Boundary for River Rch & Prof#=Mustang Branch,Reach-1         , 2
Up Type= 0
Dn Type= 3
Dn Slope=0.00718
Boundary for River Rch & Prof#=Mustang Branch,Reach-1         , 3
Up Type= 0
Dn Type= 3
Dn Slope=0.00718
Boundary for River Rch & Prof#=Mustang Branch,Reach-1         , 4
Up Type= 0
Dn Type= 3
Dn Slope=0.00718
Boundary for River Rch & Prof#=Mustang Branch,Reach-1         , 5
Up Type= 0
Dn Type= 3
Dn Slope=0.00718
Boundary for River Rch & Prof#=Mustang Branch,Reach-1         , 6
Up Type= 0
Dn Type= 3
Dn Slope=0.00718
Boundary for River Rch & Prof#=Mustang Branch,Reach-1         , 7
Up Type= 0
Dn Type= 3
Dn Slope=0.00718
DSS Import GetInterval= 0
DSS Import GetPeak= 0
DSS Import FillOption= 0

--- Mustang Branch.g01 (geometry) ---

Geom Title=Existing Conditions
Program Version=5.05

River Reach=Mustang Branch  ,Reach-1
Reach XY= 30
      2145014.27      13414380.7      2144037.35     13411585.11
      2143982.28     13410111.16       2144340.8     13409934.54
      2144389.94     13409048.95      2143630.39     13407197.67
      2142954.48     13406649.27      2142199.27     13404990.41
      2140631.57     13404533.38       2140670.8     13403874.54
      2139178.39     13402126.42      2139009.73     13400037.92
       2138680.8     13399694.54      2139021.77     13397072.52
       2139400.8     13396814.54       2139060.8     13396114.54
       2139298.9     13394988.74      2138648.73     13394173.63
        2138889.       13391889.       2137190.8     13390204.54
       2136810.8     13390794.54       2135370.8     13389424.54
       2136050.8     13388444.54       2135820.8     13385424.54
       2135040.8     13383994.54       2135340.8     13383104.54
       2134680.8     13382724.54       2135430.8     13382214.54
       2135710.8     13381074.54       2137030.8     13380354.54

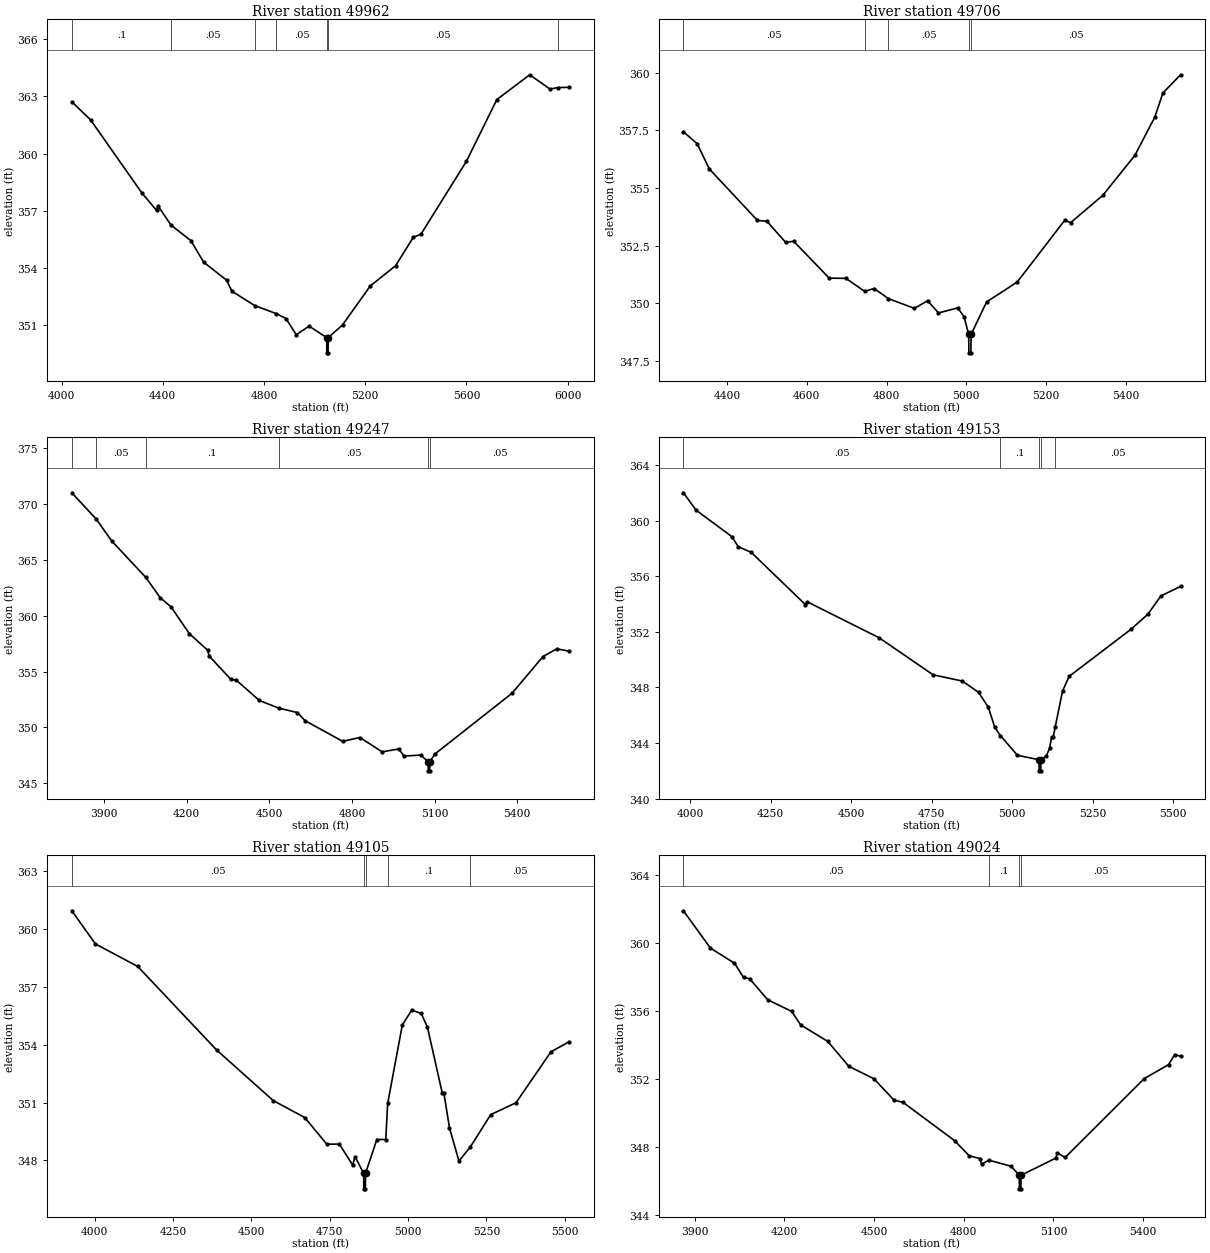
Type RM Length L Ch R = 1 ,49962   ,256,256,256
BEGIN DESCRIPTION:
Mapping XS b8367963
END DESCRIPTION:
XS GIS Cut Line= 3
      2145917.74     13414410.31      2144871.58     13414219.88
       2143969.9     13414208.67
#Sta/Elev= 30
  4040.4  362.71  4114.3  361.77  4316.9  357.94  4375.3  357.02  4380.4  357.27
  4432.8  356.24  4510.7  355.44  4561.6   354.3  4652.2  353.36  4673.4  352.78
  4762.9  352.03  4847.9  351.61  4886.8  351.35  4927.5   350.5  4978.3  350.95
  5047.9  350.35  5048.4  349.55  5053.4  349.55  5053.9  350.35  5110.3  351.01
  5220.3  353.06  5320.3  354.12  5390.3  355.61  5420.4  355.77  5600.4   359.6
  5720.4  362.83  5850.4  364.13  5930.4  363.38  5961.2  363.46  6005.5  363.47
#Mann= 7 ,-1 , 0
  4040.4      .1       0  4432.8     .05       0  4762.9      .1       0
  4847.9     .05       0  5047.9     .03       0  5053.9     .05       0
  5961.2      .1       0
Bank Sta=5047.9,5053.9
XS Rating Curve= 0 ,0
Exp/Cntr=0.3,0.1

Type RM Length L Ch R = 1 ,49706   ,459,459,459
BEGIN DESCRIPTION:
Mapping XS cefe5ad7
END DESCRIPTION:
XS GIS Cut Line= 3
       2145569.2     13414095.76      2144871.57     13414008.46
      2144330.83     13414054.93
#Sta/Elev= 30
    4291  357.44  4325.5  356.92  4355.7  355.83  4476.6  353.59  4500.1  353.56
  4547.2  352.64  4567.3  352.69  4656.3  351.09  4698.4  351.08  4744.8  350.52
  4768.9  350.64  4804.9   350.2  4869.7  349.78    4903  350.11  4930.1  349.58
  4978.6   349.8  4994.1  349.42  5005.9  348.65  5006.4  347.85  5011.4  347.85
  5011.9  348.65  5050.8  350.06  5127.5  350.92  5246.1  353.59  5261.6   353.5
  5341.9  354.68  5422.2  356.41  5472.4  358.08  5492.5  359.12  5536.8  359.91
#Mann= 5 ,-1 , 0
    4291     .05       0  4744.8      .1       0  4804.9     .05       0
  5005.9     .03       0  5011.9     .05       0
Bank Sta=5005.9,5011.9
XS Rating Curve= 0 ,0
Exp/Cntr=0.3,0.1

Type RM Length L Ch R = 1 ,49247   ,94,94,94
BEGIN DESCRIPTION:
Mapping XS 0c953111
END DESCRIPTION:
XS GIS Cut Line= 4
      2145977.79     13413891.14      2144966.19     13413592.32
      2144685.21      13413573.5      2144221.58     13413637.84
#Sta/Elev= 30
  3783.3  370.98  3872.7   368.6  3927.7  366.68  4051.6  363.42  4104.6  361.58
  4143.1  360.79  4209.7  358.39  4276.3   356.9  4281.5  356.39  4359.7  354.32
  4380.6  354.22    4464  352.41    4534  351.73    4602  351.33  4630.1   350.6
  4766.4  348.76  4828.9   349.1  4909.5  347.82  4969.6  348.07  4989.6  347.44
  5049.8  347.53  5076.8  346.92  5077.3  346.12  5082.3  346.12  5082.8  346.92
  5099.9   347.6  5381.3  353.06  5493.5  356.34    5544  357.03  5587.8  356.82
#Mann= 6 ,-1 , 0
  3783.3      .1       0  3872.7     .05       0  4051.6      .1       0
    4534     .05       0  5076.8     .03       0  5082.8     .05       0
Bank Sta=5076.8,5082.8
XS Rating Curve= 0 ,0
Exp/Cntr=0.3,0.1

Type RM Length L Ch R = 1 ,49153   ,48,48,48
BEGIN DESCRIPTION:
Mapping XS 022a3e76
END DESCRIPTION:
XS GIS Cut Line= 4
      2145793.83     13413620.73       2144821.5     13413490.12
      2144657.79     13413492.85      2144265.22     13413568.02
#Sta/Elev= 30
    3979  362.01  4018.2  360.76  4129.2  358.86  4149.4  358.13  4189.7  357.72
  4358.1  353.96  4363.2  354.17  4586.8  351.58  4754.7  348.91  4845.5  348.46
    4896  347.65  4926.3  346.57  4946.4  345.13  4963.8  344.54  5016.6  343.12
  5083.6   342.8  5084.1     342  5089.1     342  5089.6   342.8  5106.6  343.07
  5116.6  343.63  5122.7  344.41  5127.8  344.41    5134  345.15  5156.9  347.75
  5177.5   348.8  5370.2   352.2  5421.9  353.27  5462.6  354.59  5523.5  355.27
#Mann= 5 ,-1 , 0
    3979     .05       0  4963.8      .1       0  5083.6     .07       0
  5089.6      .1       0    5134     .05       0
Bank Sta=5083.6,5089.6
XS Rating Curve= 0 ,0
Exp/Cntr=0.3,0.1

Type RM Length L Ch R = 1 ,49105   ,81,81,81
BEGIN DESCRIPTION:
Mapping XS 266f4841
END DESCRIPTION:
XS GIS Cut Line= 5
       2145834.3      13413547.4      2144861.83      13413451.8
      2144750.68     13413444.28      2144654.95     13413440.33
      2144258.16     13413501.18
#Sta/Elev= 30
  3927.3  360.95  4002.5  359.23  4137.6  358.06  4388.8  353.73  4569.7   351.1
  4670.2  350.22  4740.5  348.84  4780.7  348.84  4823.3  347.75  4830.9  348.19
  4858.1  347.32  4858.6  346.52  4863.6  346.52  4864.1  347.32  4900.3  349.08
  4928.7  349.08  4934.8  350.95  4981.5  355.02  5011.2  355.79  5041.6  355.63
  5061.6  354.91  5109.1  351.48  5114.2  351.48  5131.9  349.69  5162.2  347.96
  5198.7   348.7  5263.4  350.37  5344.3  350.99  5455.6  353.63  5513.1  354.15
#Mann= 5 ,-1 , 0
  3927.3     .05       0  4858.1     .07       0  4864.1     .05       0
  4934.8      .1       0  5198.7     .05       0
Bank Sta=4858.1,4864.1
XS Rating Curve= 0 ,0
Exp/Cntr=0.3,0.1

Type RM Length L Ch R = 1 ,49024   ,591,591,591
BEGIN DESCRIPTION:
Mapping XS 1fce2de9
END DESCRIPTION:
XS GIS Cut Line= 4
      2145874.74     13413481.08      2144868.41     13413367.82
      2144649.12     13413366.79      2144225.61     13413445.32
#Sta/Elev= 30
  3862.4  361.91  3952.7  359.71  4033.2  358.82  4063.4  357.98  4083.5  357.91
  4144.6  356.66  4224.4  355.98  4254.6  355.18  4345.2  354.21  4415.6  352.74
  4499.5  352.01  4566.6  350.75  4596.7  350.62  4769.5  348.36  4818.1  347.47
  4854.5   347.3  4859.5  346.97    4884  347.21  4958.5  346.85  4985.5  346.32
    4986  345.52    4991  345.52  4991.5  346.32  5107.8  347.33  5112.9  347.64
  5139.2  347.37  5403.7  352.02    5485  352.84  5505.4  353.43  5525.1  353.34
#Mann= 4 ,-1 , 0
  3862.4     .05       0    4884      .1       0  4985.5     .03       0
  4991.5     .05       0
Bank Sta=4985.5,4991.5
XS Rating Curve= 0 ,0
Exp/Cntr=0.3,0.1

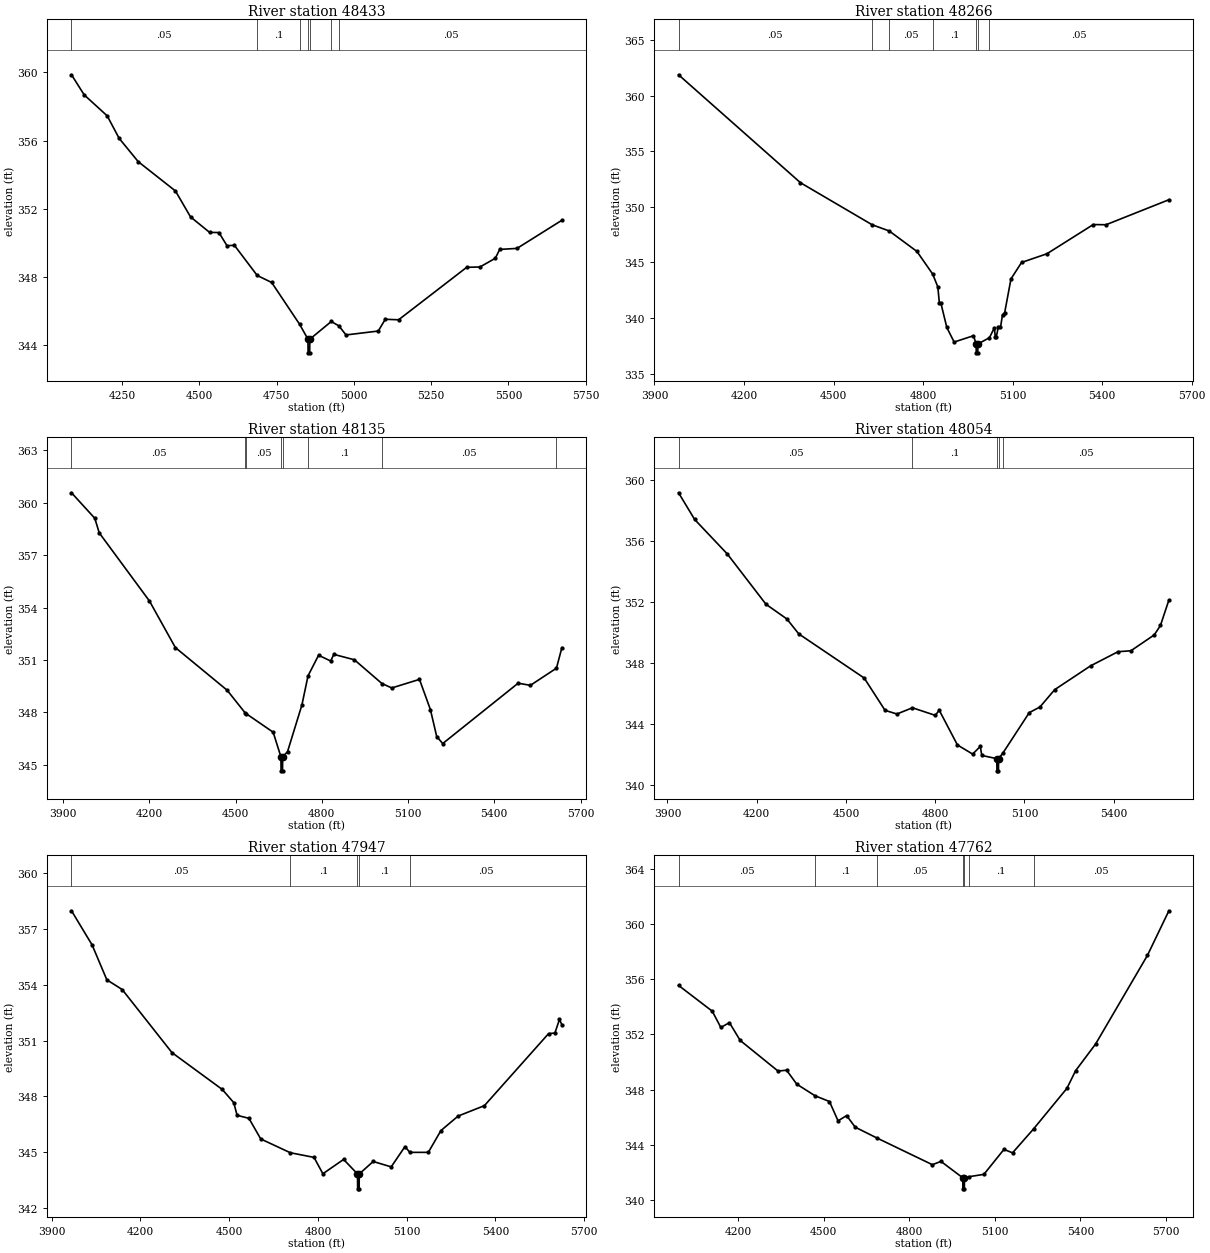
Type RM Length L Ch R = 1 ,48433   ,167,167,167
BEGIN DESCRIPTION:
Mapping XS ca285f55
END DESCRIPTION:
XS GIS Cut Line= 4
      2145590.07     13412933.63      2144737.98     13412859.61
      2144577.15     13412907.86      2144143.08     13413266.38
#Sta/Elev= 30
  4086.4  359.86  4127.5  358.68  4201.9  357.45  4240.5  356.13  4302.3  354.76
  4422.7  353.04  4471.4  351.52  4533.1  350.61  4563.3   350.6  4589.4  349.83
  4613.4  349.85  4687.2  348.08  4733.9  347.67  4824.5  345.21  4851.3  344.34
  4851.8  343.54  4856.8  343.54  4857.3  344.34  4926.8  345.38  4951.5  345.12
  4974.4  344.59  5078.8  344.82  5101.4  345.51  5144.6  345.48  5364.8  348.56
  5407.8  348.58  5457.3  349.09  5471.6  349.61  5527.6  349.67  5672.6  351.32
#Mann= 7 ,-1 , 0
  4086.4     .05       0  4687.2      .1       0  4824.5     .05       0
  4851.3     .03       0  4857.3     .05       0  4926.8      .1       0
  4951.5     .05       0
Bank Sta=4851.3,4857.3
XS Rating Curve= 0 ,0
Exp/Cntr=0.3,0.1

Type RM Length L Ch R = 1 ,48266   ,131,131,131
BEGIN DESCRIPTION:
Mapping XS aedf8a34
END DESCRIPTION:
XS GIS Cut Line= 4
      2145603.52     13412706.15      2144729.36     13412723.04
      2144543.91     13412750.18       2144140.4      13413168.4
#Sta/Elev= 30
  3980.8  361.88  4389.4  352.17  4629.4  348.39  4686.8  347.83  4779.5  345.99
  4832.4  343.95  4849.5   342.8  4854.8  341.32  4859.9  341.32  4879.7  339.15
  4904.1  337.84    4969  338.41  4977.8  337.67  4978.3  336.87  4983.3  336.87
  4983.8  337.67  5022.5  338.23  5038.9  339.12  5041.9  338.32  5045.4  338.32
  5052.2  339.17  5059.4  339.15  5066.3   340.3  5073.5  340.48  5094.6  343.52
  5130.1     345    5215  345.78  5370.4  348.41  5412.9  348.39  5623.7  350.64
#Mann= 7 ,-1 , 0
  3980.8     .05       0  4629.4      .1       0  4686.8     .05       0
  4832.4      .1       0  4977.8     .07       0  4983.8      .1       0
  5022.5     .05       0
Bank Sta=4977.8,4983.8
XS Rating Curve= 0 ,0
Exp/Cntr=0.3,0.1

Type RM Length L Ch R = 1 ,48135   ,81,81,81
BEGIN DESCRIPTION:
Mapping XS 6ed9cfce
END DESCRIPTION:
XS GIS Cut Line= 6
      2145536.08     13412597.31      2144674.24     13412621.26
      2144507.29     13412655.49      2144442.25     13412693.69
      2144370.87     13412766.87      2143995.99     13413090.36
#Sta/Elev= 30
  3929.5  360.56  4010.6   359.1  4025.9  358.27  4200.7  354.37  4290.7  351.71
  4470.8  349.27  4534.1  347.96  4537.8  347.92  4630.8  346.87  4657.9  345.46
  4658.4  344.66  4663.4  344.66  4663.9  345.46  4680.9  345.76  4730.9  348.43
  4752.1  350.09  4788.8  351.27  4830.9  350.94  4841.9  351.32  4913.4  351.01
  5009.3  349.65  5043.5   349.4  5139.7  349.89  5177.8  348.16  5199.7  346.62
  5220.6  346.22  5482.8  349.67  5525.6  349.55  5616.2  350.53  5634.9   351.7
#Mann= 8 ,-1 , 0
  3929.5     .05       0  4534.1      .1       0  4537.8     .05       0
  4657.9     .07       0  4663.9     .05       0  4752.1      .1       0
  5009.3     .05       0  5616.2      .1       0
Bank Sta=4657.9,4663.9
XS Rating Curve= 0 ,0
Exp/Cntr=0.3,0.1

Type RM Length L Ch R = 1 ,48054   ,107,107,107
BEGIN DESCRIPTION:
Mapping XS 2f304d9f
END DESCRIPTION:
XS GIS Cut Line= 5
      2145459.11     13412540.94      2144686.92     13412551.31
       2144436.5     13412602.64      2144293.82      13412731.5
      2143959.46     13412999.11
#Sta/Elev= 30
  3937.3  359.15  3991.4   357.4  4101.4  355.13  4231.4  351.83  4301.4  350.87
  4341.4  349.89  4561.5  346.99  4631.5  344.87  4671.5  344.63  4723.6  345.04
  4800.5  344.54  4813.6  344.88  4874.8   342.6  4925.9     342  4951.7   342.5
  4956.8  341.91  5007.2   341.7  5007.7   340.9  5012.7   340.9  5013.2   341.7
  5028.5  342.09  5116.3  344.72  5152.2  345.09  5201.9  346.23  5322.4  347.79
  5414.8  348.72    5458  348.78  5536.4  349.82  5557.3  350.44  5585.7  352.11
#Mann= 5 ,-1 , 0
  3937.3     .05       0  4723.6      .1       0  5007.2     .07       0
  5013.2      .1       0  5028.5     .05       0
Bank Sta=5007.2,5013.2
XS Rating Curve= 0 ,0
Exp/Cntr=0.3,0.1

Type RM Length L Ch R = 1 ,47947   ,185,185,185
BEGIN DESCRIPTION:
Mapping XS 2fc2bc81
END DESCRIPTION:
XS GIS Cut Line= 4
      2145394.49     13412505.63      2144368.88     13412532.31
      2144232.87     13412556.18      2143811.57     13412813.28
#Sta/Elev= 30
  3966.8  357.97  4036.3  356.14  4086.3  354.26  4138.1  353.74  4306.4  350.35
  4476.5  348.37  4515.4  347.66  4526.5  346.98  4566.5  346.82  4606.5  345.71
  4706.4  344.97  4786.6  344.72  4816.6  343.84  4886.6  344.61  4933.6  343.83
  4934.1  343.03  4939.1  343.03  4939.6  343.83  4986.6   344.5  5047.5  344.21
  5094.1   345.3  5110.5  344.99    5173  344.99  5215.6  346.16  5273.7  346.94
  5362.6   347.5  5579.5  351.37  5600.9   351.4  5616.3  352.13  5624.4  351.85
#Mann= 5 ,-1 , 0
  3966.8     .05       0  4706.4      .1       0  4933.6     .07       0
  4939.6      .1       0  5110.5     .05       0
Bank Sta=4933.6,4939.6
XS Rating Curve= 0 ,0
Exp/Cntr=0.3,0.1

Type RM Length L Ch R = 1 ,47762   ,152,152,152
BEGIN DESCRIPTION:
Mapping XS 8a74d486
END DESCRIPTION:
XS GIS Cut Line= 3
      2145342.95     13412298.84      2144338.85     13412350.14
      2143629.08     13412406.25
#Sta/Elev= 30
  3992.2  355.55  4110.3  353.68  4140.3   352.5  4170.4  352.85  4208.1  351.56
  4340.6  349.34  4370.6   349.4  4406.3  348.39  4470.1  347.55  4520.8  347.13
  4550.9  345.73  4580.9  346.11    4611  345.27  4685.7   344.5  4881.3  342.55
  4911.3  342.79  4987.7   341.6  4988.2   340.8  4993.2   340.8  4993.7   341.6
  5009.6  341.68  5061.7  341.85  5131.9  343.66    5162  343.41  5235.5  345.14
  5352.6  348.09  5382.7  349.36  5452.9   351.3  5634.3  357.72  5709.6  360.96
#Mann= 7 ,-1 , 0
  3992.2     .05       0  4470.1      .1       0  4685.7     .05       0
  4987.7    .035       0  4993.7     .05       0  5009.6      .1       0
  5235.5     .05       0
Bank Sta=4987.7,4993.7
XS Rating Curve= 0 ,0
Exp/Cntr=0.3,0.1

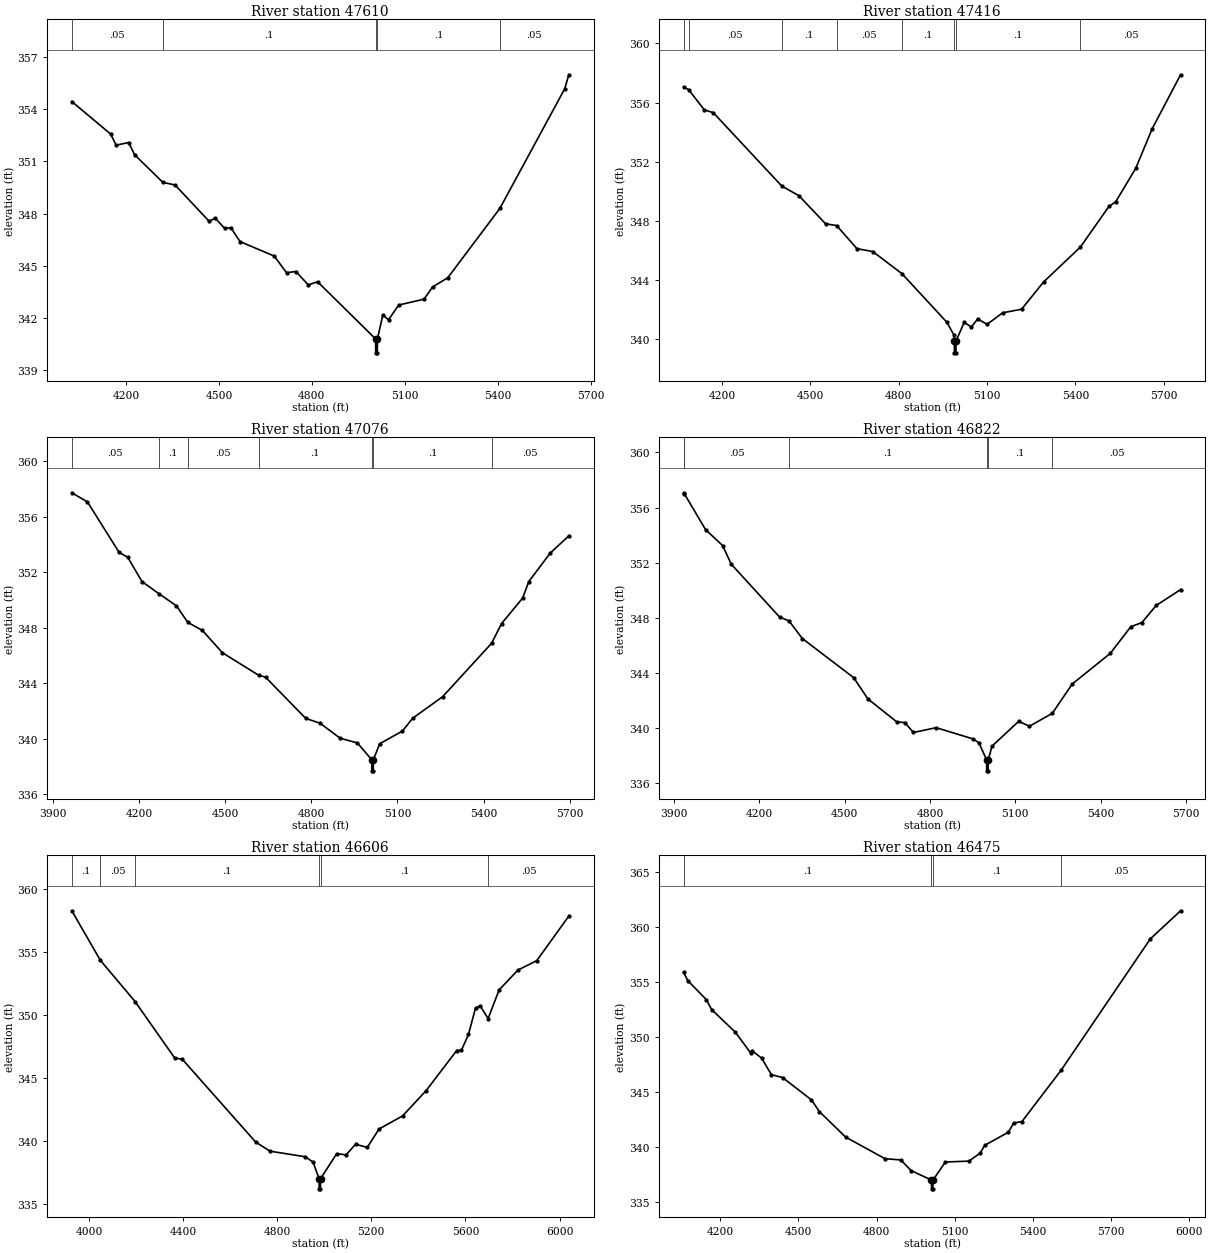
Type RM Length L Ch R = 1 ,47610   ,194,194,194
BEGIN DESCRIPTION:
Mapping XS caae3733
END DESCRIPTION:
XS GIS Cut Line= 3
      2145328.12     13412165.75      2144351.91     13412199.67
      2143738.31     13412332.95
#Sta/Elev= 30
    4025  354.45  4150.3  352.58  4168.2  351.94  4208.2  352.09  4228.2  351.38
  4318.8   349.8  4358.3  349.65  4468.4  347.56  4488.4  347.74  4518.4  347.15
  4538.4  347.19  4568.4  346.39  4678.5  345.56  4718.4   344.6  4748.6  344.67
  4788.6   343.9  4818.6  344.08  5005.9  340.79  5006.4  339.99  5011.4  339.99
  5011.9  340.79  5029.3  342.17  5047.6  341.89  5080.5  342.74  5162.4  343.08
  5189.9  343.78    5239  344.31  5407.2   348.3  5616.8  355.19  5629.7  355.99
#Mann= 5 ,-1 , 0
    4025     .05       0  4318.8      .1       0  5005.9     .07       0
  5011.9      .1       0  5407.2     .05       0
Bank Sta=5005.9,5011.9
XS Rating Curve= 0 ,0
Exp/Cntr=0.3,0.1

Type RM Length L Ch R = 1 ,47416   ,340,340,340
BEGIN DESCRIPTION:
Mapping XS 1f12f2ad
END DESCRIPTION:
XS GIS Cut Line= 3
      2145295.19     13411931.05      2144380.61     13412007.27
      2143658.32      13412272.8
#Sta/Elev= 30
    4070  357.05  4086.8  356.88  4140.4   355.5  4170.5  355.32  4403.4  350.35
  4461.5   349.7  4551.9   347.8  4589.5  347.68  4658.3  346.12  4712.4  345.92
  4811.1  344.43  4963.3  341.15  4987.8  340.28    4989  339.87  4989.5  339.07
  4994.5  339.07    4995  339.87  5022.5  341.13    5047  340.82  5068.3  341.36
  5100.3     341  5153.5  341.78  5217.5  342.02    5292  343.86  5417.3  346.23
  5513.9  348.97  5537.1  349.29  5605.3  351.56  5660.9  354.23  5757.3  357.88
#Mann= 8 ,-1 , 0
    4070      .1       0  4086.8     .05       0  4403.4      .1       0
  4589.5     .05       0  4811.1      .1       0    4989     .07       0
    4995      .1       0  5417.3     .05       0
Bank Sta=4989,4995
XS Rating Curve= 0 ,0
Exp/Cntr=0.3,0.1

Type RM Length L Ch R = 1 ,47076   ,254,254,254
BEGIN DESCRIPTION:
Mapping XS f0539da5
END DESCRIPTION:
XS GIS Cut Line= 3
      2145209.52     13411773.12      2144177.79     13411785.78
      2143524.87     13412034.78
#Sta/Elev= 30
    3966  357.71  4020.5  357.05  4130.5  353.42  4160.5  353.06  4210.5  351.31
  4268.3  350.45  4330.5  349.56  4369.8  348.37  4420.6  347.79  4490.6  346.18
  4616.5  344.56  4640.6  344.42  4780.6  341.45  4830.6   341.1  4900.6  340.02
  4960.6  339.68  5010.3  338.47  5010.8  337.67  5015.8  337.67  5016.3  338.47
    5038  339.62  5117.5  340.54    5153  341.46  5257.3  343.01  5427.7  346.86
  5462.5  348.28  5535.9  350.12  5557.3  351.31  5632.3  353.37  5696.6   354.6
#Mann= 7 ,-1 , 0
    3966     .05       0  4268.3      .1       0  4369.8     .05       0
  4616.5      .1       0  5010.3     .07       0  5016.3      .1       0
  5427.7     .05       0
Bank Sta=5010.3,5016.3
XS Rating Curve= 0 ,0
Exp/Cntr=0.3,0.1

Type RM Length L Ch R = 1 ,46822   ,216,216,216
BEGIN DESCRIPTION:
Mapping XS 362594c0
END DESCRIPTION:
XS GIS Cut Line= 3
      2145102.03     13411639.59      2144018.13     13411581.99
      2143426.74     13411880.31
#Sta/Elev= 30
  3933.6  357.07  3935.8  357.01  4010.7   354.4  4070.8  353.24  4100.9   351.9
  4271.1  348.06  4304.4  347.78  4351.2   346.5  4531.5  343.67  4581.5  342.13
  4683.2  340.46  4711.7  340.41  4741.8  339.69  4821.9  340.04  4952.1  339.22
  4972.1  338.94  4999.1  337.71  4999.6  336.91  5004.6  336.91  5005.1  337.71
  5018.1   338.7  5112.1   340.5  5149.6  340.14  5230.3  341.08  5300.1   343.2
  5433.9  345.42  5506.4  347.36  5545.4  347.66  5595.6   348.9  5681.4  350.05
#Mann= 6 ,-1 , 0
  3933.6      .1       0  3935.8     .05       0  4304.4      .1       0
  4999.1     .07       0  5005.1      .1       0  5230.3     .05       0
Bank Sta=4999.1,5005.1
XS Rating Curve= 0 ,0
Exp/Cntr=0.3,0.1

Type RM Length L Ch R = 1 ,46606   ,131,131,131
BEGIN DESCRIPTION:
Mustang Branch 83.0
END DESCRIPTION:
XS GIS Cut Line= 3
      2145124.99     13411560.15      2144086.75     13411379.58
      2143028.86     13411365.71
#Sta/Elev= 30
  3927.4  358.27  4048.6  354.34  4196.3  351.06  4363.8   346.6  4397.3  346.47
  4708.9   339.9  4769.8  339.18  4918.7  338.74  4952.5  338.32  4978.2  336.99
  4978.7  336.19  4983.7  336.19  4984.2  336.99    5053  338.98    5093  338.89
    5133  339.73    5183  339.48    5233  340.94    5333  341.98    5433  343.99
    5563  347.17    5583  347.19    5613  348.45    5643  350.55    5663  350.71
  5696.5  349.71    5743  351.98    5823  353.56  5903.1  354.31  6039.2  357.84
#Mann= 6 ,-1 , 0
  3927.4      .1       0  4048.6     .05       0  4196.3      .1       0
  4978.2     .07       0  4984.2      .1       0  5696.5     .05       0
Bank Sta=4978.2,4984.2
XS Rating Curve= 0 ,0
Exp/Cntr=0.3,0.1

Type RM Length L Ch R = 1 ,46475   ,317,317,317
BEGIN DESCRIPTION:
Mapping XS 7c997b90
END DESCRIPTION:
XS GIS Cut Line= 2
      2145041.59     13411372.64      2143149.59      13411133.1
#Sta/Elev= 30
  4059.5   355.9  4075.8  355.15  4146.8  353.43  4166.9  352.53  4257.7  350.48
  4316.2   348.6  4321.3   348.8  4358.5  348.12  4396.4  346.61  4439.1  346.35
    4550  344.32  4580.2  343.26    4681  340.94  4832.2  338.97  4892.7  338.86
    4933  337.88  5010.6  337.03  5011.1  336.23  5016.1  336.23  5016.6  337.03
    5064  338.67  5154.8  338.75  5197.6  339.49  5215.2  340.19    5306  341.38
  5326.1  342.21  5357.9  342.35  5508.7  347.03  5850.3  358.95  5966.6  361.51
#Mann= 4 ,-1 , 0
  4059.5      .1       0  5010.6     .07       0  5016.6      .1       0
  5508.7     .05       0
Bank Sta=5010.6,5016.6
XS Rating Curve= 0 ,0
Exp/Cntr=0.3,0.1

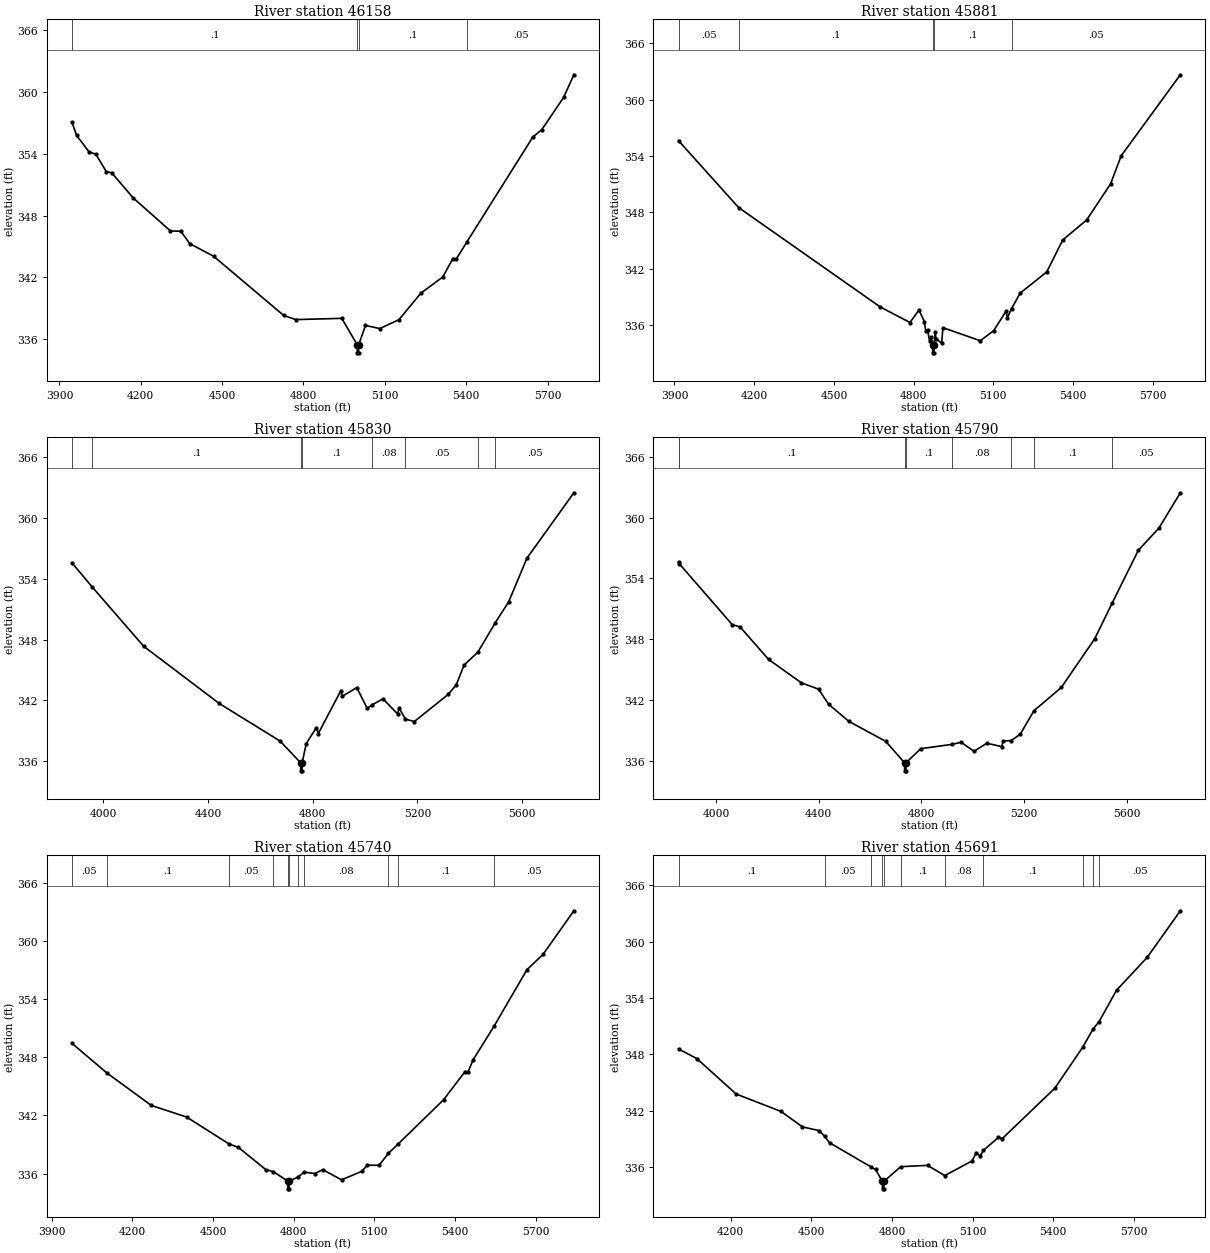
Type RM Length L Ch R = 1 ,46158   ,277,277,277
BEGIN DESCRIPTION:
Mustang Branch 82.0
END DESCRIPTION:
XS GIS Cut Line= 3
      2145074.97     13411274.99        2144075.       13410975.
      2143275.02       13410875.
#Sta/Elev= 30
  3946.7  357.07  3963.2  355.81  4009.3   354.2  4034.5  353.97  4072.8  352.29
  4092.8  352.17    4172  349.73  4309.5  346.52  4347.7  346.49  4380.8  345.29
  4468.7  344.06  4727.1  338.31  4771.5  337.91  4941.1  338.03  4997.8  335.48
  4998.3  334.68  5003.3  334.68  5003.8  335.48  5028.5  337.34  5081.4  337.04
  5151.9   337.9  5232.6  340.47  5313.2  342.04    5351  343.84  5363.6  343.81
  5402.6  345.46  5645.8  355.65  5678.5  356.35  5759.1  359.49  5796.9  361.69
#Mann= 4 ,-1 , 0
  3946.7      .1       0  4997.8     .07       0  5003.8      .1       0
  5402.6     .05       0
Bank Sta=4997.8,5003.8
XS Rating Curve= 0 ,0
Exp/Cntr=0.3,0.1

Type RM Length L Ch R = 1 ,45881   ,51,51,51
BEGIN DESCRIPTION:
Mapping XS e4b0d3e5
END DESCRIPTION:
XS GIS Cut Line= 5
      2145093.73     13410962.92      2144183.97     13410806.67
      2144149.25     13410775.42      2144097.16     13410761.53
      2143232.56     13410796.25
#Sta/Elev= 30
  3915.2  355.63  4141.2  348.51  4674.9  337.91  4786.5  336.26  4820.3  337.59
  4840.9  336.35  4845.9  335.34  4852.7  335.45  4860.1   334.3  4866.9  334.73
  4871.3  333.83  4871.8  333.03  4876.8  333.03  4877.3  333.83  4881.1  335.23
  4884.5  334.55  4905.5  334.06  4910.6  335.71  5051.1  334.32  5101.2  335.38
  5148.1  337.46  5153.1  336.77  5168.8  337.74  5201.3  339.39  5301.4  341.65
  5361.4  345.05  5451.5  347.18  5541.5  351.02  5581.6  354.02  5804.2  362.65
#Mann= 5 ,-1 , 0
  3915.2     .05       0  4141.2      .1       0  4871.3     .07       0
  4877.3      .1       0  5168.8     .05       0
Bank Sta=4871.3,4877.3
XS Rating Curve= 0 ,0
Exp/Cntr=0.3,0.1

Type RM Length L Ch R = 1 ,45830   ,40,40,40
BEGIN DESCRIPTION:
Mapping XS 60dee859
END DESCRIPTION:
XS GIS Cut Line= 6
      2145107.55     13410938.61      2144197.86     13410775.42
       2144142.3     13410723.33      2144076.33     13410716.39
      2143902.72     13410719.86      2143225.69     13410737.22
#Sta/Elev= 30
  3880.1  355.56  3956.4  353.21  4153.6  347.34  4442.5  341.69  4675.1  337.98
  4753.4  335.84  4753.9  335.04  4758.9  335.04  4759.4  335.84    4775  337.73
  4813.7   339.3    4821  338.72  4907.6  342.97  4912.6   342.4  4968.1  343.26
  5008.1   341.2  5025.7  341.54  5068.2  342.15  5124.5  340.65  5129.5  341.26
  5154.2  340.14  5188.2  339.91  5318.2   342.6  5348.2  343.53  5378.2  345.48
  5430.7  346.75    5498  349.68  5548.3  351.71  5618.3  356.03  5797.7  362.49
#Mann= 8 ,-1 , 0
  3880.1     .05       0  3956.4      .1       0  4753.4     .07       0
  4759.4      .1       0  5025.7     .08       0  5154.2     .05       0
  5430.7      .1       0    5498     .05       0
Bank Sta=4753.4,4759.4
XS Rating Curve= 0 ,0
Exp/Cntr=0.3,0.1

Type RM Length L Ch R = 1 ,45790   ,50,50,50
BEGIN DESCRIPTION:
Mapping XS ea6ed841
END DESCRIPTION:
XS GIS Cut Line= 5
       2145121.5     13410907.37      2144249.94       13410765.
       2144204.8     13410719.86      2144138.83     13410674.72
      2143211.75     13410695.56
#Sta/Elev= 30
  3854.5  355.63  3858.1  355.42  4063.7  349.42  4094.1   349.2  4205.4  345.98
  4333.3  343.67  4399.8  343.05  4438.6  341.57  4517.6  339.87  4661.6  337.89
  4734.6  335.78  4735.1  334.98  4740.1  334.98  4740.6  335.78  4797.7  337.17
  4918.4  337.59  4955.2   337.8  5005.2  336.91  5055.3  337.71  5113.3  337.37
  5118.3  337.93  5150.1  337.97  5185.3   338.6  5238.4  340.91  5345.3  343.22
  5475.4  348.03  5543.6  351.57  5645.4  356.78  5725.4  358.96  5808.7  362.45
#Mann= 8 ,-1 , 0
  3854.5     .05       0  3858.1      .1       0  4734.6     .07       0
  4740.6      .1       0  4918.4     .08       0  5150.1     .05       0
  5238.4      .1       0  5543.6     .05       0
Bank Sta=4734.6,4740.6
XS Rating Curve= 0 ,0
Exp/Cntr=0.3,0.1

Type RM Length L Ch R = 1 ,45740   ,49,49,49
BEGIN DESCRIPTION:
Mapping XS 69de15f8
END DESCRIPTION:
XS GIS Cut Line= 4
      2144996.42      13410341.4      2144270.78       13410515.
      2143947.86     13410657.36       2143180.5     13410660.83
#Sta/Elev= 30
  3976.1  349.43  4104.2  346.41  4270.8  343.03  4402.1  341.83  4560.1  339.05
  4594.5   338.7  4696.5  336.41    4725  336.19    4778  335.22  4778.5  334.42
  4783.5  334.42    4784  335.22    4815  335.62  4839.8  336.14  4879.7     336
  4908.5   336.4  4978.5  335.35  5053.9  336.23    5074  336.86    5118  336.85
  5152.1  338.07  5187.2     339    5358  343.62    5438  346.53    5448  346.43
    5468  347.75  5545.3  351.19    5668  357.04    5728  358.62  5842.5  363.12
#Mann= 11 ,-1 , 0
  3976.1     .05       0  4104.2      .1       0  4560.1     .05       0
    4725     .08       0    4778     .07       0    4784     .08       0
    4815      .1       0  4839.8     .08       0  5152.1     .05       0
  5187.2      .1       0  5545.3     .05       0
Bank Sta=4778,4784
XS Rating Curve= 0 ,0
Exp/Cntr=0.3,0.1

Type RM Length L Ch R = 1 ,45691   ,303,303,303
BEGIN DESCRIPTION:
Mapping XS e4aee0b3
END DESCRIPTION:
XS GIS Cut Line= 4
      2144968.66     13410306.67      2144308.97     13410442.08
      2143902.72     13410633.06      2143158.08     13410605.35
#Sta/Elev= 30
  4005.7  348.57  4073.9  347.55  4219.9  343.78  4387.2  341.92  4466.8  340.28
  4530.1  339.87  4549.6  339.26  4567.6  338.59  4722.3  336.01  4738.8  335.74
  4764.3  334.48  4764.8  333.68  4769.8  333.68  4770.3  334.48  4832.5  336.04
  4932.5  336.18  4996.4  335.09  5097.6  336.65  5114.5  337.54    5128  337.17
  5140.2  337.77  5195.8  339.15  5210.5  339.03    5406  344.39  5509.9  348.76
  5548.6  350.71  5569.8  351.44  5636.1  354.84  5749.7  358.32  5873.2  363.29
#Mann= 11 ,-1 , 0
  4005.7      .1       0  4549.6     .05       0  4722.3     .08       0
  4764.3     .07       0  4770.3     .08       0  4832.5      .1       0
  4996.4     .08       0  5140.2      .1       0  5509.9     .05       0
  5548.6      .1       0  5569.8     .05       0
Bank Sta=4764.3,4770.3
XS Rating Curve= 0 ,0
Exp/Cntr=0.3,0.1

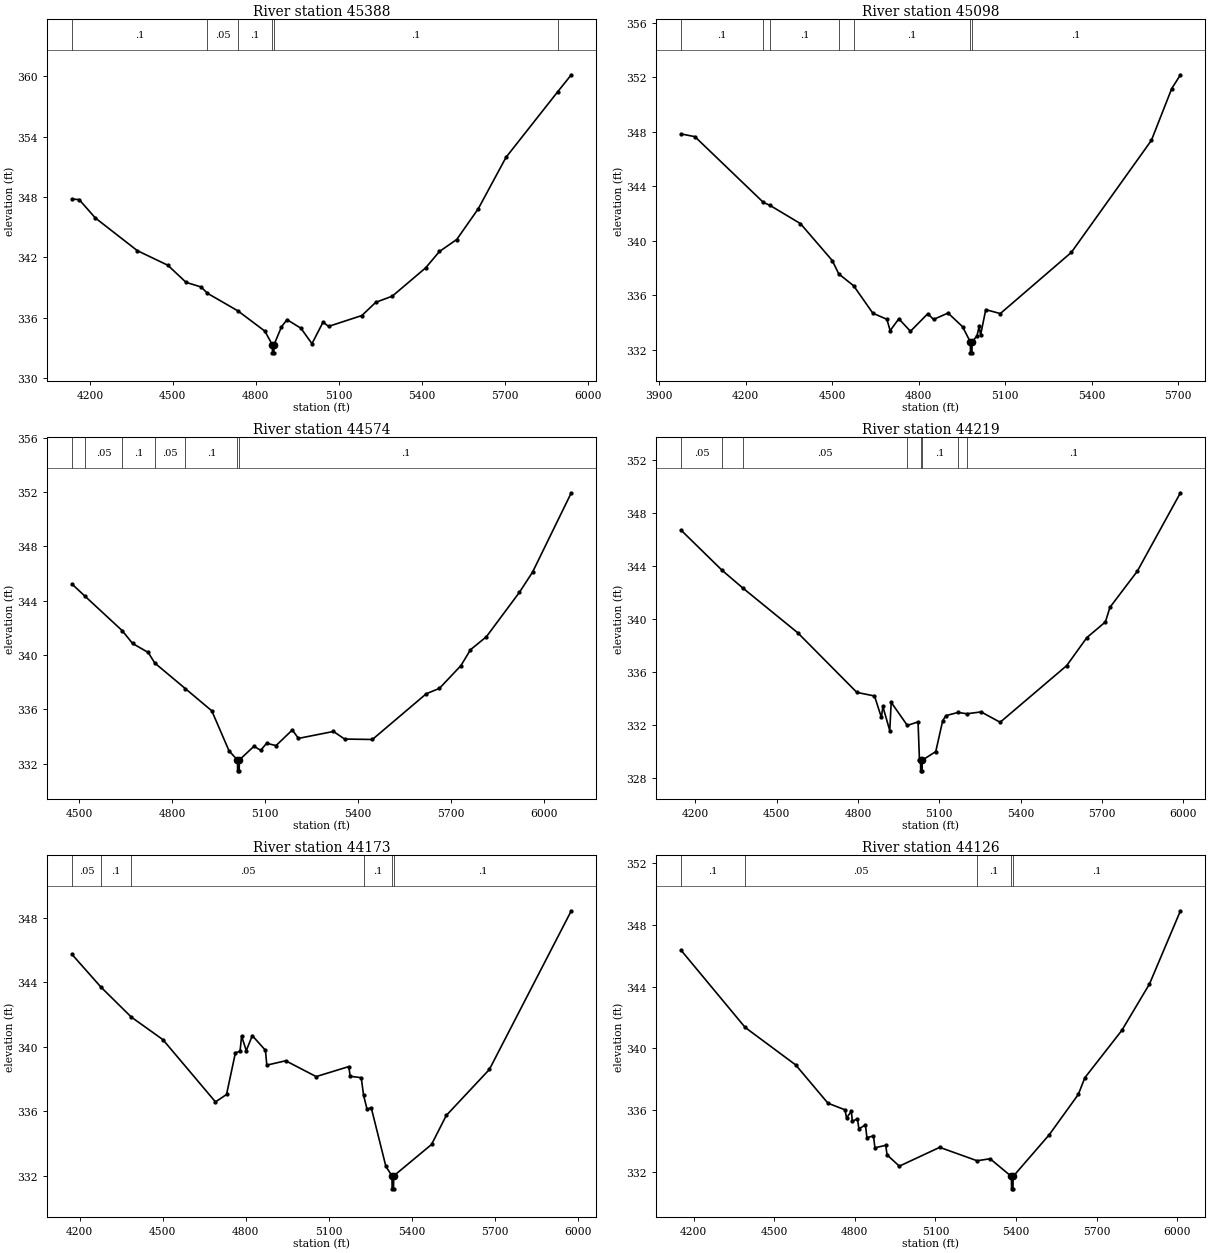
Type RM Length L Ch R = 1 ,45388   ,290,290,290
BEGIN DESCRIPTION:
Mapping XS b01cd2d2
END DESCRIPTION:
XS GIS Cut Line= 2
      2144940.93     13410254.58      2143139.45     13410365.66
#Sta/Elev= 30
  4135.2  347.79  4161.2  347.74  4219.8  345.91  4371.6  342.66  4481.8  341.21
  4547.6  339.51    4602  339.05  4625.1  338.42  4735.2  336.67  4832.5  334.66
  4859.5   333.3    4860   332.5  4865.1   332.5  4865.6   333.3  4892.6  335.09
  4912.6   335.8  4962.7  334.95  5002.8  333.41  5042.8  335.55  5062.9  335.13
  5183.1  336.21  5233.2  337.52  5293.3  338.14  5413.6  340.95  5463.6  342.58
    5526  343.77  5603.9  346.83  5704.1  351.94  5890.9  358.46  5940.1  360.15
#Mann= 6 ,-1 , 0
  4135.2      .1       0  4625.1     .05       0  4735.2      .1       0
  4859.5     .07       0  4865.6      .1       0  5890.9     .05       0
Bank Sta=4859.5,4865.6
XS Rating Curve= 0 ,0
Exp/Cntr=0.3,0.1

Type RM Length L Ch R = 1 ,45098   ,524,524,524
BEGIN DESCRIPTION:
Mustang Branch 79.0
END DESCRIPTION:
XS GIS Cut Line= 3
      2145017.29     13410164.31        2144025.       13410075.
      2143295.07     13410167.78
#Sta/Elev= 30
  3976.3  347.83  4024.1  347.63  4261.6  342.81  4284.5  342.59  4390.3  341.25
  4500.7  338.54  4523.2  337.56  4574.9  336.69  4641.3  334.68  4690.1  334.23
  4701.5   333.4  4731.6  334.27  4771.8  333.35    4832  334.64  4852.1  334.22
  4902.3  334.69  4952.5  333.69  4979.6  332.57  4980.1  331.77  4985.2  331.77
  4985.7  332.57  5002.8  333.02  5010.1  333.71  5015.1  333.07  5033.1  334.94
  5083.5  334.65    5330  339.14  5607.7  347.36  5678.2  351.16  5708.4  352.17
#Mann= 7 ,-1 , 0
  3976.3      .1       0  4261.6     .05       0  4284.5      .1       0
  4523.2     .05       0  4574.9      .1       0  4979.6     .07       0
  4985.7      .1       0
Bank Sta=4979.6,4985.7
XS Rating Curve= 0 ,0
Exp/Cntr=0.3,0.1

Type RM Length L Ch R = 1 ,44574   ,355,355,355
BEGIN DESCRIPTION:
Mustang Branch 78.0
END DESCRIPTION:
XS GIS Cut Line= 3
      2144849.95     13409858.75      2144246.47     13409806.67
      2143268.61       13410039.
#Sta/Elev= 30
  4476.5  345.23  4517.8  344.35  4638.4   341.8  4672.2  340.85  4722.4  340.19
  4743.7  339.41  4842.1  337.53  4927.6  335.89  4983.3  332.94  5010.4  332.27
  5010.9  331.47    5016  331.47  5016.5  332.27  5063.6  333.28  5085.5  332.98
  5104.3   333.5  5134.9  333.33  5187.4  334.48  5207.1  333.86  5320.1  334.37
  5356.2  333.81  5445.7  333.78  5619.6  337.15  5661.7  337.54  5731.3  339.22
  5762.1  340.39  5813.5  341.35    5920  344.62  5962.2   346.1  6087.3  351.95
#Mann= 7 ,-1 , 0
  4476.5      .1       0  4517.8     .05       0  4638.4      .1       0
  4743.7     .05       0  4842.1      .1       0  5010.4     .07       0
  5016.5      .1       0
Bank Sta=5010.4,5016.5
XS Rating Curve= 0 ,0
Exp/Cntr=0.3,0.1

Type RM Length L Ch R = 1 ,44219   ,46,46,46
BEGIN DESCRIPTION:
Mapping XS e6c61817
END DESCRIPTION:
XS GIS Cut Line= 6
      2145034.71     13409594.86      2144399.25     13409587.92
      2144256.89     13409521.95      2144114.53     13409535.83
      2143986.05      13409553.2      2143260.38     13409824.02
#Sta/Elev= 30
    4148   346.7  4299.6  343.67  4375.8  342.34  4577.7  338.98  4796.1  334.48
  4861.1  334.21  4886.6  332.59  4891.9  333.42  4917.4   331.6  4922.7  333.73
  4982.2  331.99  5021.7  332.26  5026.8  329.41  5030.9  329.37  5031.4  328.57
  5036.6  328.57  5037.1  329.37    5087  330.02  5112.6  332.35  5124.6  332.73
  5169.3  332.97  5201.7  332.87  5254.2  333.01  5324.4  332.23  5569.9   336.5
  5644.1  338.61  5712.6  339.79  5729.2  340.89  5830.1  343.61  5989.2  349.52
#Mann= 8 ,-1 , 0
    4148     .05       0  4299.6      .1       0  4375.8     .05       0
  4982.2      .1       0  5030.9     .07       0  5037.1      .1       0
  5169.3     .05       0  5201.7      .1       0
Bank Sta=5030.9,5037.1
XS Rating Curve= 0 ,0
Exp/Cntr=0.3,0.1

Type RM Length L Ch R = 1 ,44173   ,47,47,47
BEGIN DESCRIPTION:
Mapping XS 914a333c
END DESCRIPTION:
XS GIS Cut Line= 6
      2145013.81     13409539.31      2144444.39     13409546.25
      2144336.75      13409490.7      2144013.83      13409490.7
      2143947.86     13409535.83      2143281.18     13409782.37
#Sta/Elev= 30
  4172.1  345.73  4277.4  343.69  4386.6  341.84  4500.9  340.44  4690.9  336.58
  4730.9  337.04    4763  339.63  4779.7  339.71  4785.3  340.66  4802.3  339.76
    4824  340.69  4871.5  339.78  4876.5  338.86  4944.7  339.13  5054.9  338.15
  5172.8  338.77  5177.8  338.17  5217.9  338.08  5226.2  336.99  5238.9  336.12
  5253.8  336.23  5306.9  332.58  5328.9  331.99  5329.4  331.19  5334.6  331.19
  5335.1  331.99  5471.9  333.94  5525.2  335.74  5680.9  338.59  5977.1  348.43
#Mann= 6 ,-1 , 0
  4172.1     .05       0  4277.4      .1       0  4386.6     .05       0
  5226.2      .1       0  5328.9    .035       0  5335.1      .1       0
Bank Sta=5328.9,5335.1
XS Rating Curve= 0 ,0
Exp/Cntr=0.3,0.1

Type RM Length L Ch R = 1 ,44126   ,540,540,540
BEGIN DESCRIPTION:
Mapping XS f5a6660a
END DESCRIPTION:
XS GIS Cut Line= 6
      2145031.18      13409490.7      2144461.75     13409511.53
      2144308.97     13409442.08      2143975.64     13409435.14
      2143906.19     13409508.06      2143268.69     13409760.98
#Sta/Elev= 30
  4153.6  346.35    4392  341.35  4580.1  338.92  4700.1  336.44  4763.6  336.01
  4769.3  335.49  4787.1  335.91  4790.9  335.28  4809.9  335.42  4815.3  334.78
  4839.7  335.03  4845.1  334.21  4869.5  334.32  4874.9  333.55  4915.1  333.71
  4920.1  333.09  4965.8  332.36    5116  333.58  5255.1  332.71  5303.6  332.84
  5382.9  331.69  5383.4  330.89  5388.6  330.89  5389.1  331.69  5523.8   334.4
  5631.8  337.01  5656.1  338.09  5793.8  341.16  5896.5  344.16  6011.9  348.91
#Mann= 5 ,-1 , 0
  4153.6      .1       0    4392     .05       0  5255.1      .1       0
  5382.9    .035       0  5389.1      .1       0
Bank Sta=5382.9,5389.1
XS Rating Curve= 0 ,0
Exp/Cntr=0.3,0.1