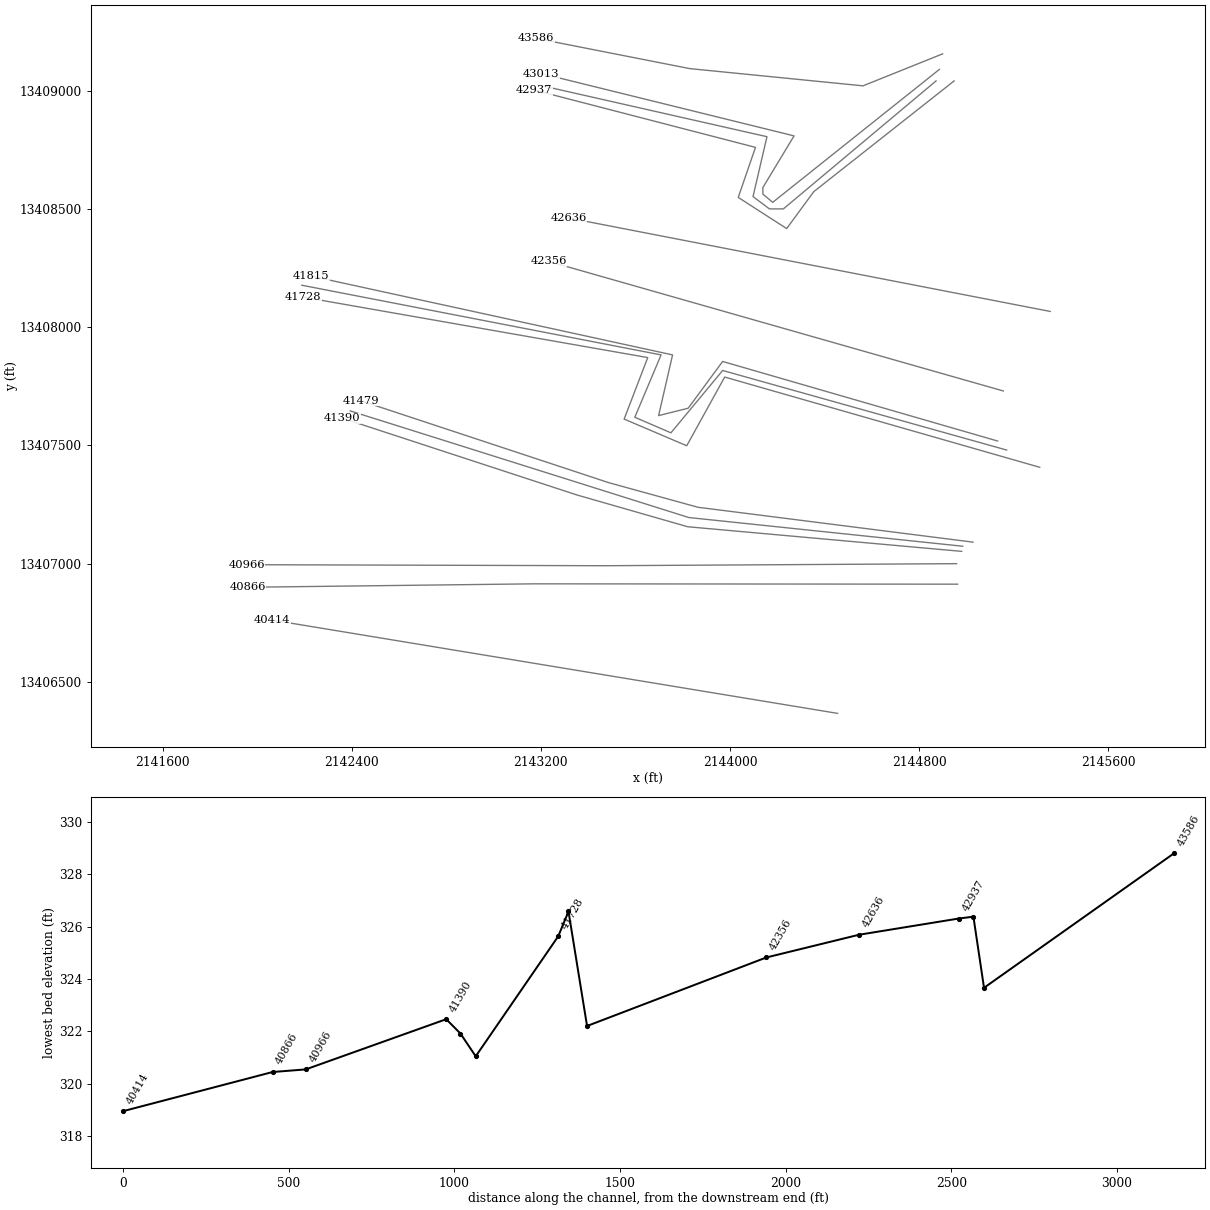
HEC-RAS study Mustang Branch.prj: Mustang Branch Base Level Engineering

--- Mustang Branch.g01 (geometry) --- (continued)

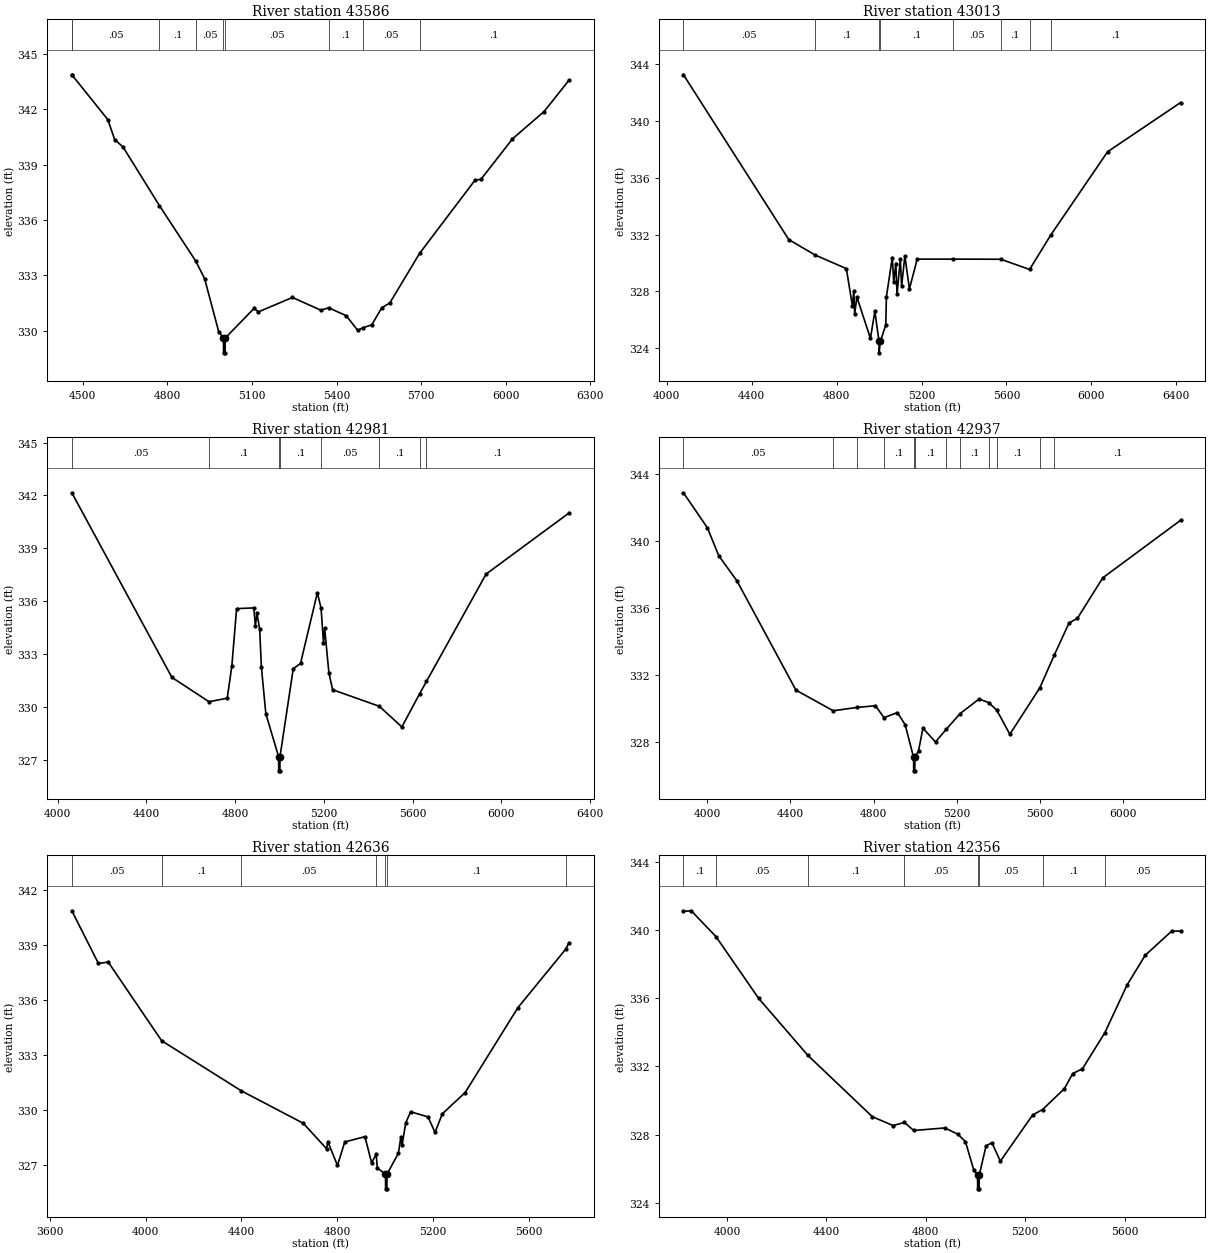
Type RM Length L Ch R = 1 ,43586   ,573,573,573
BEGIN DESCRIPTION:
Mapping XS 6b135dc9
END DESCRIPTION:
XS GIS Cut Line= 4
      2144899.21     13409157.35      2144562.44     13409021.95
       2143829.8     13409094.86      2143178.52     13409223.04
#Sta/Elev= 30
    4461  343.86  4461.1  343.86  4588.7  341.43  4612.9  340.35  4642.5  339.95
  4771.4  336.78  4899.6  333.79  4931.9  332.82  4982.2  329.93  4998.7   329.6
  4999.2   328.8  5004.4   328.8  5004.9   329.6  5107.5  331.21  5122.9  331.02
  5243.5   331.8    5344  331.11  5371.9  331.24  5434.4  330.81  5474.6  330.02
  5492.4  330.15  5524.9  330.32  5560.1  331.24  5588.7   331.5  5694.5  334.19
  5891.3  338.16  5911.6  338.19  6023.8  340.39  6135.9  341.87    6224  343.56
#Mann= 9 ,-1 , 0
    4461      .1       0  4461.1     .05       0  4771.4      .1       0
  4899.6     .05       0  4998.7    .035       0  5004.9     .05       0
  5371.9      .1       0  5492.4     .05       0  5694.5      .1       0
Bank Sta=4998.7,5004.9
XS Rating Curve= 0 ,0
Exp/Cntr=0.3,0.1

Type RM Length L Ch R = 1 ,43013   ,32,32,32
BEGIN DESCRIPTION:
Mapping XS 75ac1b04
END DESCRIPTION:
XS GIS Cut Line= 6
      2144885.33     13409091.36       2144180.5     13408528.89
      2144138.83     13408563.61      2144138.83     13408591.39
      2144270.78     13408810.14      2143201.33     13409074.03
#Sta/Elev= 30
  4078.6  343.27  4574.5  331.65  4698.4  330.56  4845.8   329.6  4874.4  326.96
  4880.9  328.05    4885  326.39  4895.3   327.6  4959.2  324.68    4980  326.59
  4999.7  324.46  5000.2  323.66  5005.9  324.46  5031.5  325.63  5034.3   327.6
  5062.1  330.38    5069  328.64  5078.7  329.96  5084.5  327.78    5100  330.28
  5105.9  328.36  5121.4   330.5  5142.7  328.17  5179.6  330.27  5347.1  330.27
  5573.1  330.26  5708.9  329.54  5808.1  331.96  6076.1  337.84  6419.8  341.31
#Mann= 8 ,-1 , 0
  4078.6     .05       0  4698.4      .1       0  4999.7     .07       0
  5005.9      .1       0  5347.1     .05       0  5573.1      .1       0
  5708.9     .05       0  5808.1      .1       0
Bank Sta=4999.7,5005.9
XS Rating Curve= 0 ,0
Exp/Cntr=0.3,0.1

Type RM Length L Ch R = 1 ,42981   ,44,44,44
BEGIN DESCRIPTION:
Mapping XS da4d7858
END DESCRIPTION:
XS GIS Cut Line= 6
      2144871.44     13409042.76      2144225.64     13408501.11
      2144166.61     13408501.11      2144097.16      13408553.2
      2144156.19     13408806.67      2143190.87     13409025.43
#Sta/Elev= 30
  4063.7  342.15  4514.8  331.68  4682.2   330.3  4764.4   330.5  4785.2  332.34
  4806.6  335.58  4884.3  335.62  4891.1   334.6  4898.5  335.31  4910.5  334.41
  4918.4  332.25  4938.4  329.62    4996  327.18  4996.5  326.38  5001.7  326.38
  5002.2  327.18    5062  332.17  5094.7  332.47  5170.7  336.48  5187.4  335.61
  5198.3  333.62  5203.5  334.46  5222.8  331.93  5239.4  330.98  5450.2  330.04
  5551.7  328.87  5631.7  330.75  5662.5  331.45  5931.5  337.54  6304.9     341
#Mann= 8 ,-1 , 0
  4063.7     .05       0  4682.2      .1       0    4996     .07       0
  5002.2      .1       0  5187.4     .05       0  5450.2      .1       0
  5631.7     .05       0  5662.5      .1       0
Bank Sta=4996,5002.2
XS Rating Curve= 0 ,0
Exp/Cntr=0.3,0.1

Type RM Length L Ch R = 1 ,42937   ,301,301,301
BEGIN DESCRIPTION:
Mapping XS 109e6f2c
END DESCRIPTION:
XS GIS Cut Line= 6
      2144947.85     13409042.77      2144354.11     13408574.03
      2144239.53     13408417.78      2144034.66     13408549.72
      2144107.58     13408761.53      2143170.13     13409004.57
#Sta/Elev= 30
  3885.5  342.88  4000.2   340.8  4056.2  339.11  4142.9  337.63  4426.6  331.12
  4605.9  329.89  4722.1  330.09  4809.1  330.19  4850.1  329.48  4914.7  329.78
  4951.9  329.06  4992.6  327.11  4993.1  326.31  4998.3  326.31  4998.8  327.11
  5016.6  327.52  5037.4  328.85    5098  328.03  5149.1  328.78  5216.3  329.72
  5307.5  330.59    5353  330.38  5392.5  329.93  5455.6  328.49  5599.9  331.26
  5669.8  333.22  5740.2  335.12  5780.7   335.4  5902.5  337.81  6276.8  341.24
#Mann= 12 ,-1 , 0
  3885.5     .05       0  4605.9      .1       0  4722.1     .05       0
  4850.1      .1       0  4992.6     .07       0  4998.8      .1       0
  5149.1     .05       0  5216.3      .1       0    5353     .05       0
  5392.5      .1       0  5599.9     .05       0  5669.8      .1       0
Bank Sta=4992.6,4998.8
XS Rating Curve= 0 ,0
Exp/Cntr=0.3,0.1

Type RM Length L Ch R = 1 ,42636   ,280,280,280
BEGIN DESCRIPTION:
Mapping XS a5e44ac1
END DESCRIPTION:
XS GIS Cut Line= 2
      2145354.13     13408067.08      2143315.92     13408462.92
#Sta/Elev= 30
  3691.5  340.88  3802.7     338  3843.4  338.08  4066.7  333.78    4400  331.04
  4658.4  329.27  4755.5  327.88  4760.6  328.27    4801  326.97  4831.5  328.25
  4915.7  328.54  4943.6  327.11  4962.8  327.58  4967.4  326.83  5001.6  326.49
  5002.1  325.69  5007.4  325.69  5007.9  326.49  5055.7  327.64  5065.7  328.51
  5070.8  328.07  5086.2   329.3  5106.6   329.9  5179.3  329.62  5208.5  328.77
    5239  329.79  5334.3  330.95  5554.8  335.59  5754.2  338.78  5767.8  339.13
#Mann= 7 ,-1 , 0
  3691.5     .05       0  4066.7      .1       0    4400     .05       0
  4962.8      .1       0  5001.6     .07       0  5007.9      .1       0
  5754.2     .05       0
Bank Sta=5001.6,5007.9
XS Rating Curve= 0 ,0
Exp/Cntr=0.3,0.1

Type RM Length L Ch R = 1 ,42356   ,541,541,541
BEGIN DESCRIPTION:
Mapping XS b347a61a
END DESCRIPTION:
XS GIS Cut Line= 2
       2145156.2     13407730.28       2143232.6     13408278.88
#Sta/Elev= 30
  3825.1  341.09  3856.4  341.12  3955.7  339.61  4127.9  335.98  4325.4  332.65
    4585  329.05  4668.6  328.53  4714.1  328.71  4751.8  328.24  4876.4  328.39
  4928.6  328.03  4959.8  327.59  4993.5  325.91  5008.4  325.62  5008.9  324.82
  5014.7  324.82  5015.2  325.62    5043  327.35  5066.4  327.52  5100.2  326.44
  5230.2  329.15  5270.2  329.47  5357.8  330.69  5391.6  331.58  5430.7  331.86
  5520.7  333.97  5610.2  336.77  5683.1  338.51  5789.8  339.93  5825.4  339.93
#Mann= 8 ,-1 , 0
  3825.1      .1       0  3955.7     .05       0  4325.4      .1       0
  4714.1     .05       0  5008.4     .03       0  5015.2     .05       0
  5270.2      .1       0  5520.7     .05       0
Bank Sta=5008.4,5015.2
XS Rating Curve= 0 ,0
Exp/Cntr=0.3,0.1

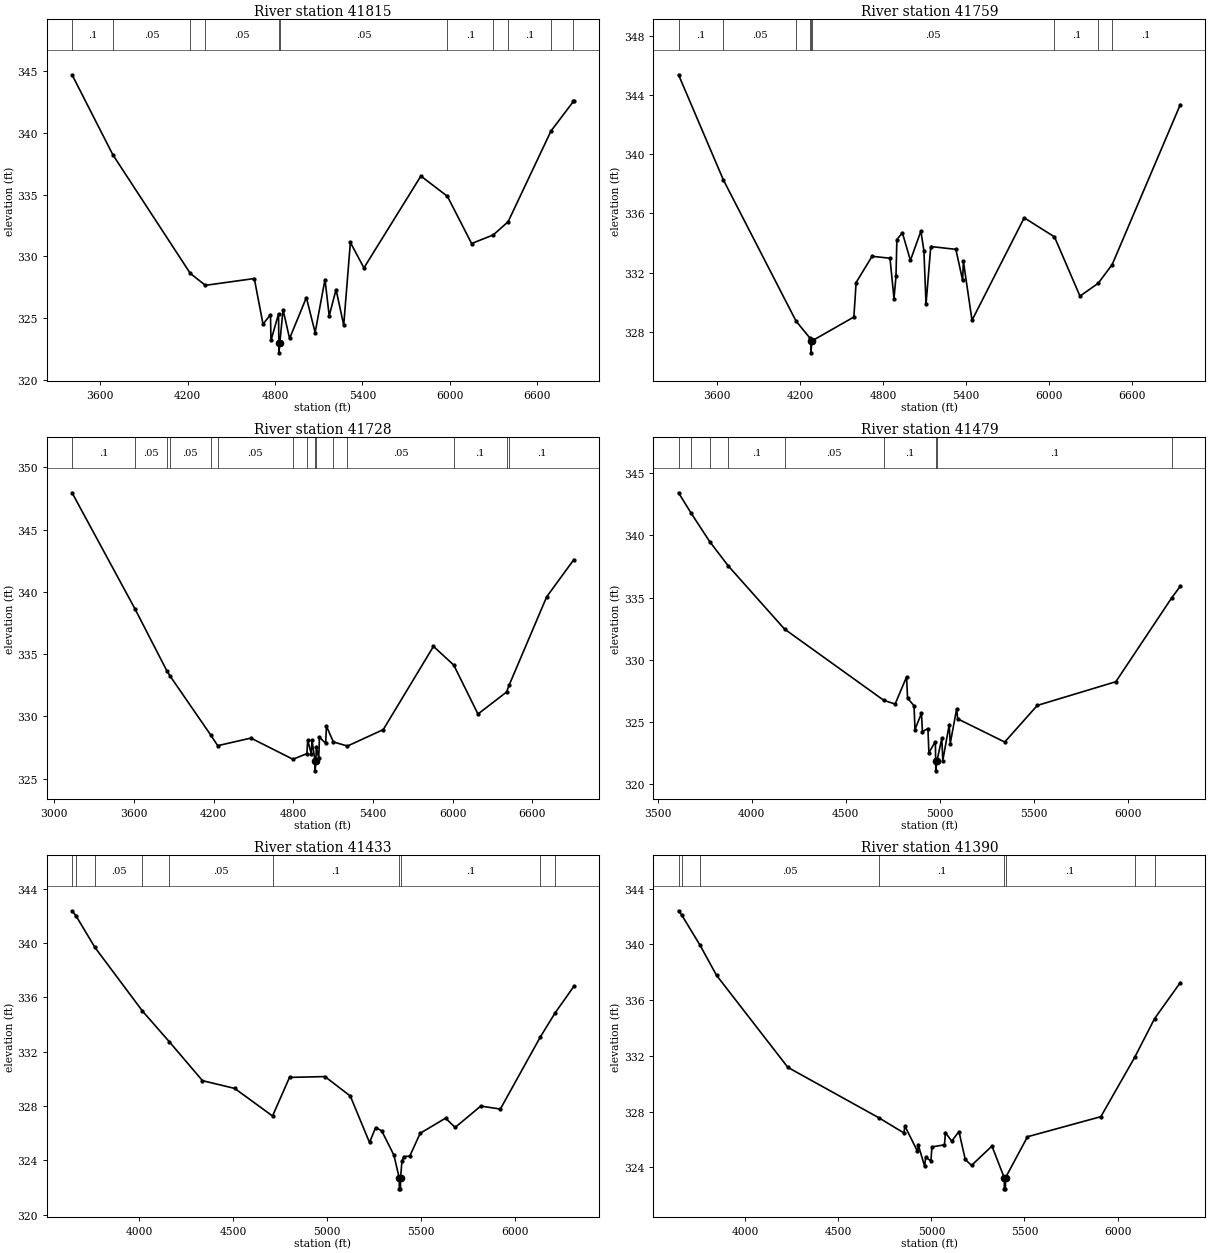
Type RM Length L Ch R = 1 ,41815   ,56,56,56
BEGIN DESCRIPTION:
Mapping XS e606c06d
END DESCRIPTION:
XS GIS Cut Line= 6
      2145131.88     13407518.48      2143968.69     13407855.28
      2143822.86     13407657.36      2143697.86     13407626.11
      2143756.89     13407883.06      2142229.58     13408216.29
#Sta/Elev= 30
  3407.7  344.69  3687.5  338.22  4219.1  328.62  4322.3  327.66  4657.9  328.21
  4717.7  324.52    4769  325.29  4772.3   323.2  4824.3  325.35  4826.2     323
  4826.7   322.2    4833     323  4855.1  325.69    4900  323.36  5015.2  326.67
  5075.3  323.84  5142.9  328.13  5171.8  325.19  5218.8  327.32  5271.3  324.44
  5317.1  331.13  5410.1  329.07  5800.8   336.5  5982.8  334.86  6148.8  331.04
  6297.7  331.74    6399   332.8  6693.3  340.14  6846.9  342.53  6850.3  342.56
#Mann= 11 ,-1 , 0
  3407.7      .1       0  3687.5     .05       0  4219.1      .1       0
  4322.3     .05       0  4826.2    .035       0    4833     .05       0
  5982.8      .1       0  6297.7     .05       0    6399      .1       0
  6693.3     .05       0  6846.9      .1       0
Bank Sta=4826.2,4833
XS Rating Curve= 0 ,0
Exp/Cntr=0.3,0.1

Type RM Length L Ch R = 1 ,41759   ,31,31,31
BEGIN DESCRIPTION:
Mapping XS e69a7015
END DESCRIPTION:
XS GIS Cut Line= 6
      2145170.04     13407480.29      2143968.69     13407817.08
      2143749.94      13407553.2      2143597.16     13407619.17
      2143708.28     13407883.06      2142188.68     13408177.95
#Sta/Elev= 30
  3323.7  345.36  3646.9  338.27  4171.7  328.73  4274.6  327.55  4279.1  327.38
  4279.6  326.58  4285.9  327.38  4589.5     329  4605.8  331.33  4720.8   333.1
  4850.2  332.97  4879.1  330.25  4893.5  331.74  4899.9  334.23  4939.7  334.69
  4997.7  332.82  5073.2   334.8    5095  333.48  5110.3  329.87  5144.6  333.76
  5325.8  333.57  5374.6  331.48    5380  332.77  5442.3  328.78  5819.2   335.7
  6037.8  334.41  6221.8  330.41  6353.5  331.28  6454.2  332.54  6946.2  343.35
#Mann= 9 ,-1 , 0
  3323.7      .1       0  3646.9     .05       0  4171.7      .1       0
  4274.6     .05       0  4279.1    .035       0  4285.9     .05       0
  6037.8      .1       0  6353.5     .05       0  6454.2      .1       0
Bank Sta=4279.1,4285.9
XS Rating Curve= 0 ,0
Exp/Cntr=0.3,0.1

Type RM Length L Ch R = 1 ,41728   ,249,249,249
BEGIN DESCRIPTION:
Mapping XS c8ecaba4
END DESCRIPTION:
XS GIS Cut Line= 6
      2145309.85     13407407.36      2143977.37     13407789.31
      2143816.78     13407498.51      2143552.03     13407611.36
      2143651.85     13407871.77      2142193.51     13408127.85
#Sta/Elev= 30
  3134.3  347.95  3608.1  338.63  3847.2  333.68  3871.3  333.26  4177.6  328.52
  4231.4  327.65  4481.3  328.26  4797.6  326.56  4903.3  327.01  4908.9   328.1
  4936.5  326.98  4941.7  328.09  4964.1  326.43  4964.6  325.63  4970.9  326.43
  4974.2  327.54  4992.3  326.65  4997.7  328.34  5044.6  327.83  5050.1  329.22
  5102.4  327.95  5208.7  327.62  5478.3  328.94  5856.5  335.62  6009.3  334.12
  6191.5  330.19  6406.6  331.95  6427.2  332.53  6709.3   339.6  6913.9  342.59
#Mann= 15 ,-1 , 0
  3134.3      .1       0  3608.1     .05       0  3847.2      .1       0
  3871.3     .05       0  4177.6      .1       0  4231.4     .05       0
  4797.6      .1       0  4903.3     .05       0  4964.1    .035       0
  4970.9     .05       0  5102.4      .1       0  5208.7     .05       0
  6009.3      .1       0  6406.6     .05       0  6427.2      .1       0
Bank Sta=4964.1,4970.9
XS Rating Curve= 0 ,0
Exp/Cntr=0.3,0.1

Type RM Length L Ch R = 1 ,41479   ,46,46,46
BEGIN DESCRIPTION:
Mapping XS 38f205b7
END DESCRIPTION:
XS GIS Cut Line= 4
      2145027.73     13407090.52      2143864.53     13407238.09
      2143486.92     13407342.26      2142438.27     13407688.92
#Sta/Elev= 30
  3610.9  343.44  3677.5  341.81  3776.9   339.5  3876.4  337.53  4174.7  332.46
  4702.5  326.72  4762.8  326.42  4823.7  328.61  4828.9   326.9  4863.3  326.28
  4868.5  324.37  4902.8  325.68    4908   324.2  4937.2  324.45  4942.4   322.5
  4976.7  323.39  4978.5  321.84    4979  321.04  4985.4  321.84  5011.1  323.65
  5016.3  321.87  5050.6  324.77  5055.8  323.23  5090.2  326.04  5095.4  325.23
  5345.7  323.36  5518.9  326.31  5936.7  328.22  6234.3  334.99  6279.6  335.91
#Mann= 9 ,-1 , 0
  3610.9     .05       0  3677.5      .1       0  3776.9     .05       0
  3876.4      .1       0  4174.7     .05       0  4702.5      .1       0
  4978.5     .07       0  4985.4      .1       0  6234.3     .05       0
Bank Sta=4978.5,4985.4
XS Rating Curve= 0 ,0
Exp/Cntr=0.3,0.1

Type RM Length L Ch R = 1 ,41433   ,43,43,43
BEGIN DESCRIPTION:
Mapping XS fa8d0559
END DESCRIPTION:
XS GIS Cut Line= 3
      2144984.35     13407073.16      2143825.46     13407194.69
      2142393.15     13407646.08
#Sta/Elev= 30
  3644.9  342.37    3667  341.97  3766.1  339.68  4019.1  334.99  4162.6  332.72
    4338  329.87    4509   329.3  4710.4  327.27  4800.6  330.11  4988.9  330.17
  5123.6  328.74  5225.9  325.32  5258.3  326.42  5290.6  326.18  5355.4  324.39
  5383.8  322.71  5384.3  321.91  5390.2  321.91  5390.7  322.71  5398.2  323.95
  5408.3  324.28  5439.7  324.32  5495.3     326    5630  327.11  5680.9  326.43
  5817.2     328  5921.2  327.78  6133.5  333.08    6211  334.83  6311.9  336.81
#Mann= 10 ,-1 , 0
  3644.9     .05       0    3667      .1       0  3766.1     .05       0
  4019.1      .1       0  4162.6     .05       0  4710.4      .1       0
  5383.8     .07       0  5390.7      .1       0  6133.5     .05       0
    6211      .1       0
Bank Sta=5383.8,5390.7
XS Rating Curve= 0 ,0
Exp/Cntr=0.3,0.1

Type RM Length L Ch R = 1 ,41390   ,424,424,424
BEGIN DESCRIPTION:
Mapping XS a4fc8d60
END DESCRIPTION:
XS GIS Cut Line= 4
        2144980.     13407051.46      2143821.12     13407155.63
      2143352.37     13407290.17      2142359.21     13407615.45
#Sta/Elev= 30
  3641.2  342.42  3658.2  342.12  3757.1  339.94  3845.2  337.79  4228.6  331.18
  4717.7  327.56  4852.2  326.47  4857.4  326.97  4924.9  325.16  4930.1  325.58
  4963.8  324.07    4969  324.73  4997.5  324.46  5002.7  325.47  5070.2  325.62
  5075.4   326.5  5109.1  325.88    5148  326.57  5181.8  324.57  5215.5  324.14
  5325.2  325.53  5391.4  323.26  5391.9  322.46  5397.8  322.46  5398.3  323.26
  5516.3   326.2  5910.5  327.64  6092.3   331.9  6199.2  334.68  6337.5  337.27
#Mann= 8 ,-1 , 0
  3641.2     .05       0  3658.2      .1       0  3757.1     .05       0
  4717.7      .1       0  5391.4     .07       0  5398.3      .1       0
  6092.3     .05       0  6199.2      .1       0
Bank Sta=5391.4,5398.3
XS Rating Curve= 0 ,0
Exp/Cntr=0.3,0.1

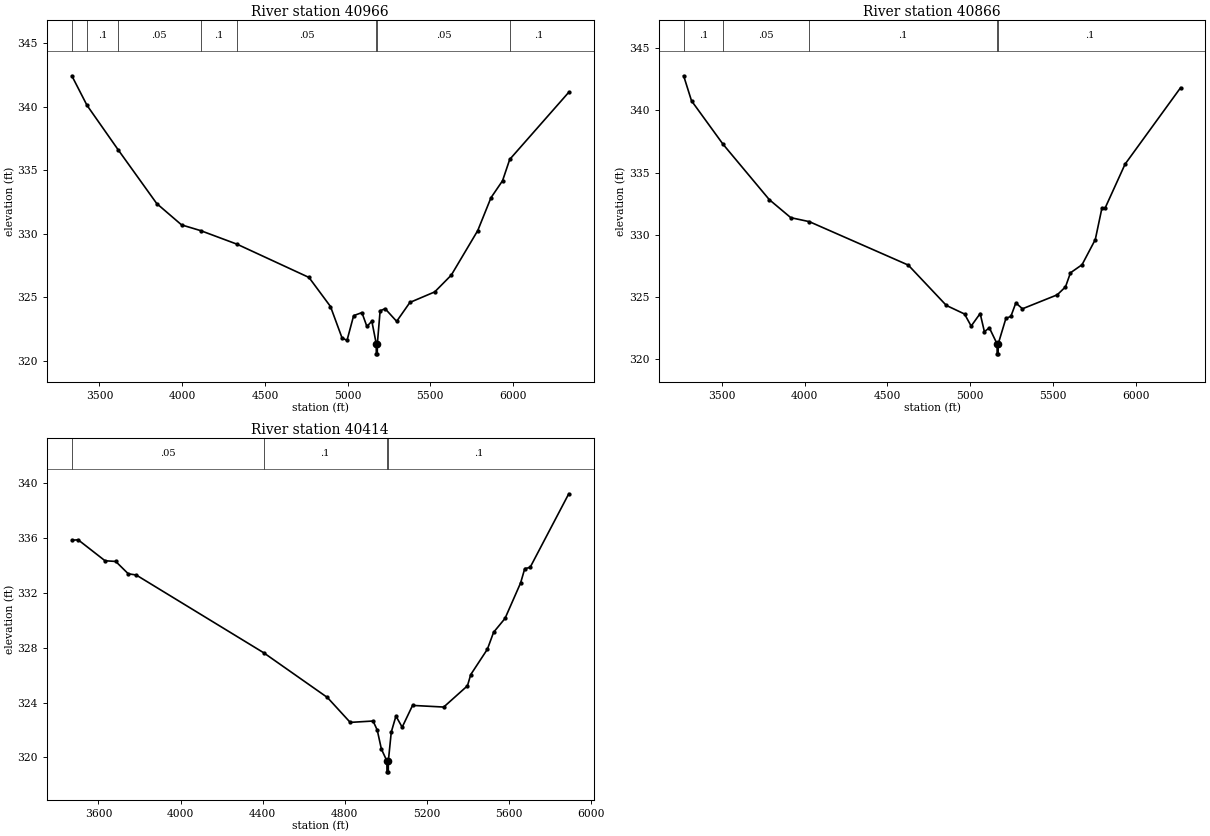
Type RM Length L Ch R = 1 ,40966   ,100,100,100
BEGIN DESCRIPTION:
Mustang Branch 71.0
END DESCRIPTION:
XS GIS Cut Line= 3
      2144958.25     13406999.38      2143469.56      13406990.7
      2141954.78     13406995.04
#Sta/Elev= 30
    3333  342.45  3424.8  340.12  3612.4  336.63  3846.3  332.38  3996.3   330.7
  4111.2  330.25  4331.4  329.18  4766.3  326.56  4896.3  324.27  4966.3  321.79
  4996.3   321.6  5036.3  323.55  5086.3  323.79  5116.3   322.7  5146.3  323.11
  5172.8  321.34  5173.3  320.54  5179.2  320.54  5179.7  321.34  5196.3  323.93
  5226.3   324.1  5296.3   323.1  5376.3  324.59  5526.3  325.42  5626.3  326.74
  5786.3  330.25  5866.3  332.84  5936.3  334.18  5979.6  335.86  6336.5  341.15
#Mann= 8 ,-1 , 0
    3333     .05       0  3424.8      .1       0  3612.4     .05       0
  4111.2      .1       0  4331.4     .05       0  5172.8     .04       0
  5179.7     .05       0  5979.6      .1       0
Bank Sta=5172.8,5179.7
XS Rating Curve= 0 ,0
Exp/Cntr=0.3,0.1

Type RM Length L Ch R = 1 ,40866   ,452,452,452
BEGIN DESCRIPTION:
Mustang Branch 70.0
END DESCRIPTION:
XS GIS Cut Line= 3
      2144962.62     13406912.57      2143170.66     13406914.06
       2141959.6     13406899.56
#Sta/Elev= 30
  3268.9  342.78  3316.5  340.77    3507  337.28  3786.5  332.83  3916.5  331.38
  4028.5  331.06  4626.5  327.57  4856.5  324.33  4966.5  323.64  5006.5  322.67
  5060.9  323.68  5086.5  322.22  5116.5  322.53  5163.1  321.24  5163.6  320.44
  5169.5  320.44    5170  321.24  5216.5  323.29  5246.5  323.45  5276.5  324.53
  5316.5  324.06  5526.5  325.18  5576.6  325.82  5606.6  326.95  5676.6   327.6
  5756.6  329.62  5796.6  332.14  5816.6  332.17  5936.6  335.68    6272  341.82
#Mann= 5 ,-1 , 0
  3268.9      .1       0    3507     .05       0  4028.5      .1       0
  5163.1     .07       0    5170      .1       0
Bank Sta=5163.1,5170
XS Rating Curve= 0 ,0
Exp/Cntr=0.3,0.1

Type RM Length L Ch R = 1 ,40414   ,474,474,474
BEGIN DESCRIPTION:
Mapping XS be5b8f2c
END DESCRIPTION:
XS GIS Cut Line= 2
      2144454.79      13406365.7      2142063.29     13406760.66
#Sta/Elev= 30
  3469.9  335.85  3500.7  335.88  3631.9  334.35    3684   334.3  3745.1   333.4
  3783.9  333.31    4405  327.64  4716.4  324.37  4827.8  322.55  4939.3  322.65
  4959.6  321.99  4979.9   320.6  5006.6  319.74  5007.2  318.94  5013.4  318.94
  5013.9  319.74    5028  321.84  5050.8  323.01  5081.2   322.2  5131.9  323.79
  5283.9  323.67  5399.6  325.22  5415.7  326.04  5496.8  327.89  5527.2  329.13
  5582.9  330.14  5658.9  332.73  5679.2  333.78  5705.1  333.86  5893.8  339.24
#Mann= 4 ,-1 , 0
  3469.9     .05       0    4405      .1       0  5006.6     .07       0
  5013.9      .1       0
Bank Sta=5006.6,5013.9
XS Rating Curve= 0 ,0
Exp/Cntr=0.3,0.1