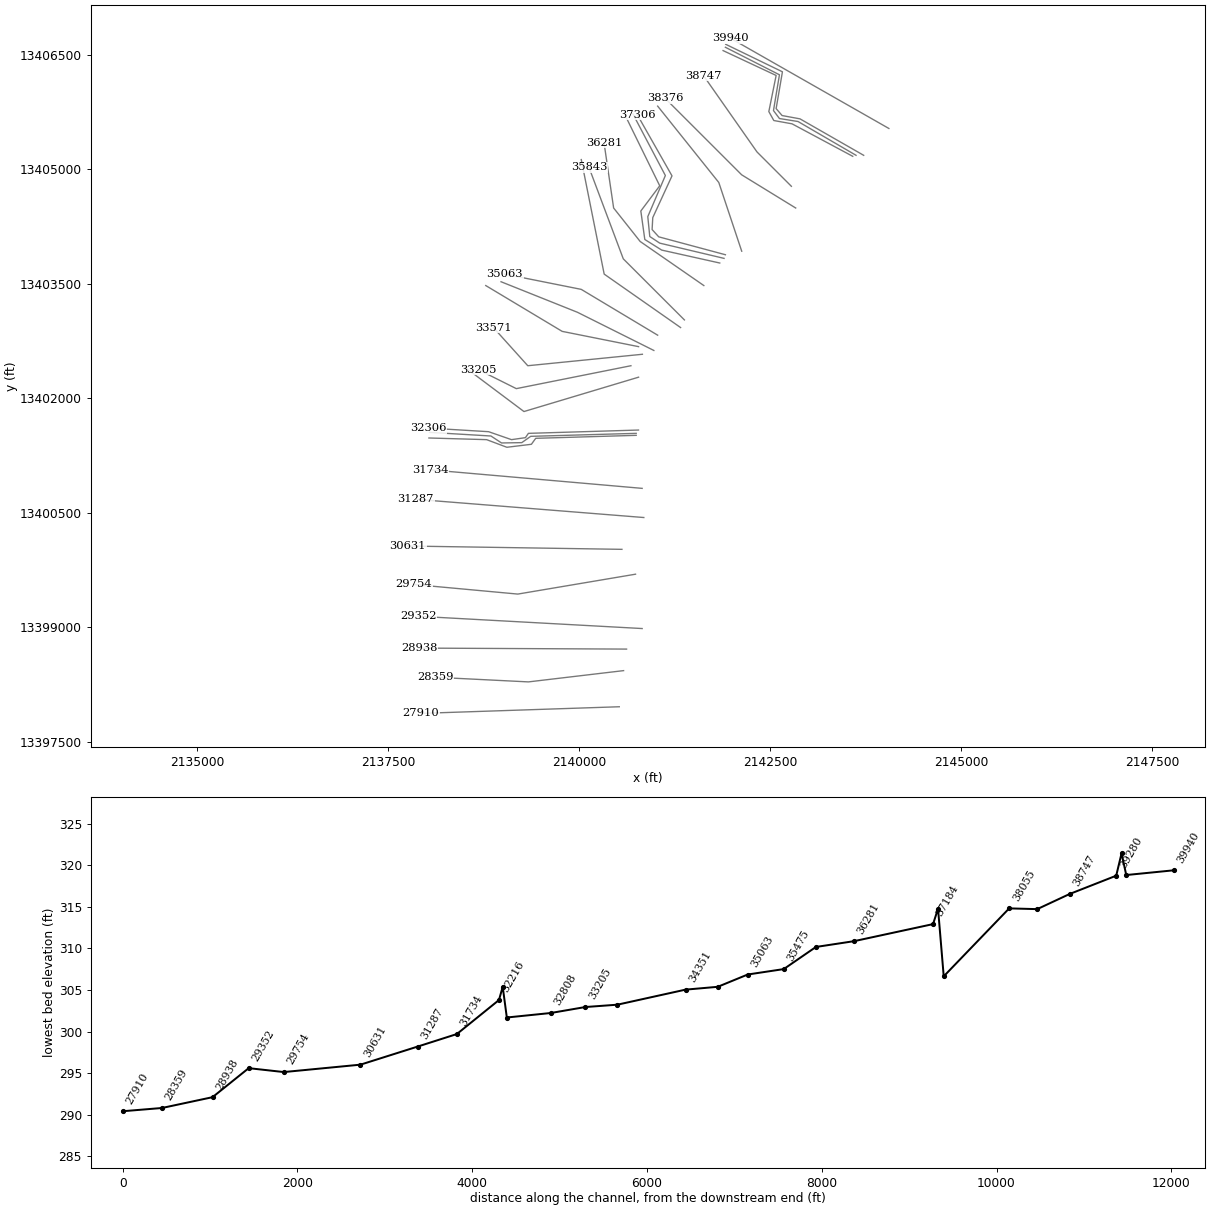
HEC-RAS study Mustang Branch.prj: Mustang Branch Base Level Engineering

--- Mustang Branch.g01 (geometry) --- (continued)

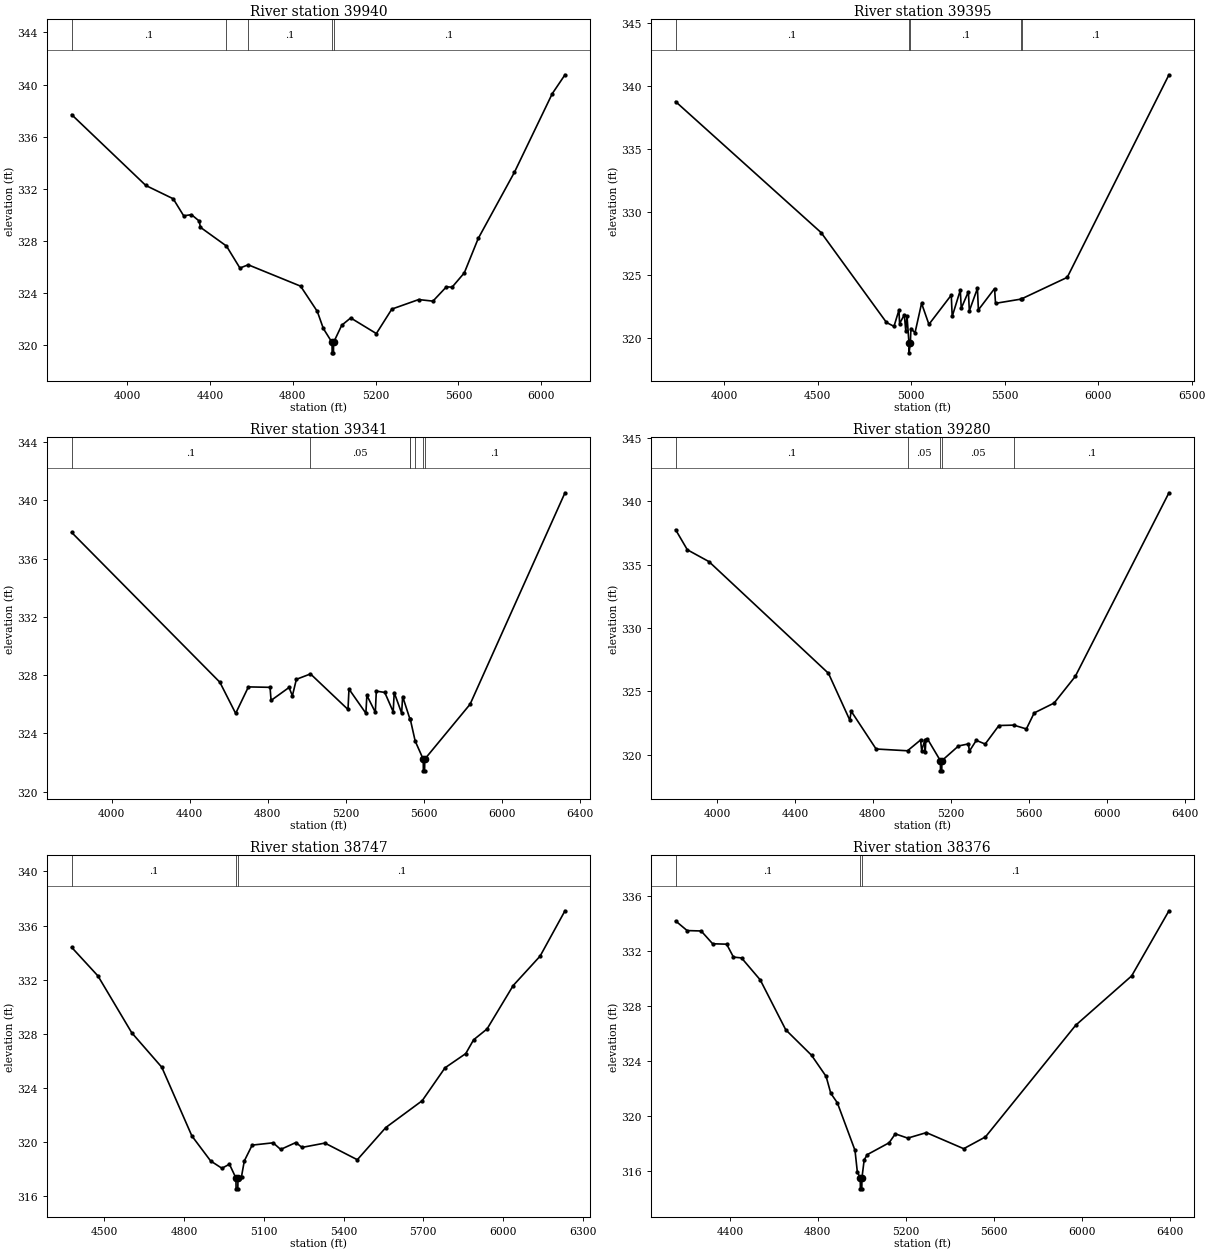
Type RM Length L Ch R = 1 ,39940   ,545,545,545
BEGIN DESCRIPTION:
Mapping XS 306037e7
END DESCRIPTION:
XS GIS Cut Line= 2
      2144051.15     13405532.37      2141980.89     13406712.89
#Sta/Elev= 30
  3731.7  337.69  4090.1  332.25  4222.3  331.23    4273  329.92  4310.5  330.01
  4347.9  329.52  4353.7  329.04  4479.6   327.6  4544.6  325.91  4584.6  326.16
  4837.7  324.52  4918.4  322.58  4947.5  321.27  4989.5   320.2  4990.1   319.4
  4996.5   319.4    4997   320.2  5036.5  321.52  5079.7  322.08  5203.6  320.88
  5278.5  322.76  5408.1  323.49    5477  323.37  5542.1  324.47  5569.4  324.44
  5628.5  325.54  5695.7  328.18  5870.5  333.26  6053.4   339.3  6114.9  340.75
#Mann= 5 ,-1 , 0
  3731.7      .1       0  4479.6     .05       0  4584.6      .1       0
  4989.5     .07       0    4997      .1       0
Bank Sta=4989.5,4997
XS Rating Curve= 0 ,0
Exp/Cntr=0.3,0.1

Type RM Length L Ch R = 1 ,39395   ,54,54,54
BEGIN DESCRIPTION:
Mapping XS acca8d33
END DESCRIPTION:
XS GIS Cut Line= 6
      2143721.32     13405180.79      2142887.96     13405658.23
      2142653.59     13405701.63      2142575.46     13405792.78
      2142657.93     13406274.55      2141915.71     13406634.81
#Sta/Elev= 30
  3740.8  338.77  4519.1  328.37  4868.2  321.24  4908.4  320.93  4934.9  322.22
  4938.3  321.15  4963.7  321.85  4971.4  320.57    4978  321.75  4988.4  319.63
    4989  318.83  4996.1  319.63  4998.8  320.76  5020.8  320.42  5055.9  322.76
  5095.2  321.09  5214.6  323.41  5219.7  321.72  5262.9   323.8  5268.1  322.37
  5306.2  323.68  5311.3  322.16  5354.6  323.95  5359.7  322.24  5446.2  323.93
  5451.3  322.76  5589.6   323.1  5594.3  323.14  5834.7  324.82  6378.6   340.9
#Mann= 5 ,-1 , 0
  3740.8      .1       0  4988.4     .07       0  4996.1      .1       0
  5589.6     .05       0  5594.3      .1       0
Bank Sta=4988.4,4996.1
XS Rating Curve= 0 ,0
Exp/Cntr=0.3,0.1

Type RM Length L Ch R = 1 ,39341   ,61,61,61
BEGIN DESCRIPTION:
Mapping XS af2b0fa9
END DESCRIPTION:
XS GIS Cut Line= 6
      2143621.43     13405180.82      2142861.92     13405623.51
      2142618.87     13405662.57      2142540.74     13405766.74
      2142618.87     13406235.49      2141911.44     13406595.71
#Sta/Elev= 30
  3794.7  337.79  4554.5  327.51  4635.5  325.37  4700.8  327.19  4811.8  327.16
    4817  326.26  4909.1  327.15  4926.3  326.58  4946.7  327.71  5019.1  328.08
  5211.3  325.64  5216.4  327.04    5303  325.38  5308.1  326.61  5351.4  325.45
  5356.5   326.9  5399.8  326.81  5443.1  325.48  5448.2   326.8  5486.3  325.39
  5491.5  326.53  5528.2  325.01    5530  325.01  5555.8  323.47    5597  322.23
  5597.7  321.43  5604.1  321.43  5604.7  322.23  5837.2     326  6323.7  340.51
#Mann= 7 ,-1 , 0
  3794.7      .1       0  5019.1     .05       0  5528.2      .1       0
    5530     .05       0  5555.8      .1       0    5597     .07       0
  5604.7      .1       0
Bank Sta=5597,5604.7
XS Rating Curve= 0 ,0
Exp/Cntr=0.3,0.1

Type RM Length L Ch R = 1 ,39280   ,533,533,533
BEGIN DESCRIPTION:
Mapping XS f763fe32
END DESCRIPTION:
XS GIS Cut Line= 6
      2143578.04     13405167.79       2142783.8     13405593.13
      2142545.08     13405636.53      2142479.98     13405753.72
      2142575.46     13406226.81      2141881.04     13406552.32
#Sta/Elev= 30
  3787.7  337.74  3847.9  336.16  3958.7  335.23  4572.2  326.43  4681.8  322.74
  4688.7  323.45  4816.6  320.47  4977.8  320.33  5044.8  321.18  5050.5  320.35
  5066.5  321.16  5068.7  320.24    5072  321.16    5080  321.27  5146.5  319.55
  5147.1  318.75  5153.6  318.75  5154.2  319.55  5239.5  320.71  5290.3  320.87
  5295.5   320.3  5330.8  321.15  5376.4  320.86    5447  322.32  5523.3  322.35
  5587.8  322.05  5627.9  323.31  5730.3  324.09  5838.9  326.19  6319.6  340.65
#Mann= 5 ,-1 , 0
  3787.7      .1       0  4977.8     .05       0  5146.5    .035       0
  5154.2     .05       0  5523.3      .1       0
Bank Sta=5146.5,5154.2
XS Rating Curve= 0 ,0
Exp/Cntr=0.3,0.1

Type RM Length L Ch R = 1 ,38747   ,371,371,371
BEGIN DESCRIPTION:
Mustang Branch 64.0
END DESCRIPTION:
XS GIS Cut Line= 3
      2142774.97     13404775.03        2142325.       13405225.
        2141625.       13406225.
#Sta/Elev= 30
  4376.4  334.39  4475.3  332.28  4602.6  328.08  4715.8  325.53  4828.9  320.46
  4899.6  318.61    4942  318.07  4970.3  318.37  4994.8  317.35  4995.4  316.55
  5001.9  316.55  5002.5  317.35  5015.8  317.46  5026.3  318.61  5055.9  319.78
  5134.8  319.95  5163.2  319.46  5220.3  319.97  5243.4  319.61  5329.7  319.93
  5451.7   318.7    5559  321.08  5695.9  323.06  5781.8  325.49  5859.8  326.54
  5889.4  327.56    5940  328.36  6038.5  331.57  6139.7  333.74  6233.4  337.09
#Mann= 3 ,-1 , 0
  4376.4      .1       0  4994.8     .07       0  5002.5      .1       0
Bank Sta=4994.8,5002.5
XS Rating Curve= 0 ,0
Exp/Cntr=0.3,0.1

Type RM Length L Ch R = 1 ,38376   ,321,321,321
BEGIN DESCRIPTION:
Mustang Branch 63.0
END DESCRIPTION:
XS GIS Cut Line= 3
      2142831.55     13404490.69        2142125.       13404925.
      2141124.99     13405925.01
#Sta/Elev= 30
  4153.3  334.22  4205.7  333.52  4269.5  333.49  4321.7  332.56  4385.5  332.53
  4416.3  331.59  4453.1  331.53  4538.2  329.93  4654.2   326.3  4771.4  324.45
  4837.7  322.91    4859  321.68  4888.8  320.99  4969.1  317.53  4979.7  315.96
  4992.9  315.53  4993.6  314.73  5000.1  314.73  5000.7  315.53  5010.9  316.84
  5025.1  317.22  5124.1  318.08  5152.4  318.73  5208.9  318.42  5293.8  318.82
  5463.5  317.65  5562.5  318.51  5972.6  326.63  6227.2  330.22  6396.9  334.96
#Mann= 3 ,-1 , 0
  4153.3      .1       0  4992.9     .07       0  5000.7      .1       0
Bank Sta=4992.9,5000.7
XS Rating Curve= 0 ,0
Exp/Cntr=0.3,0.1

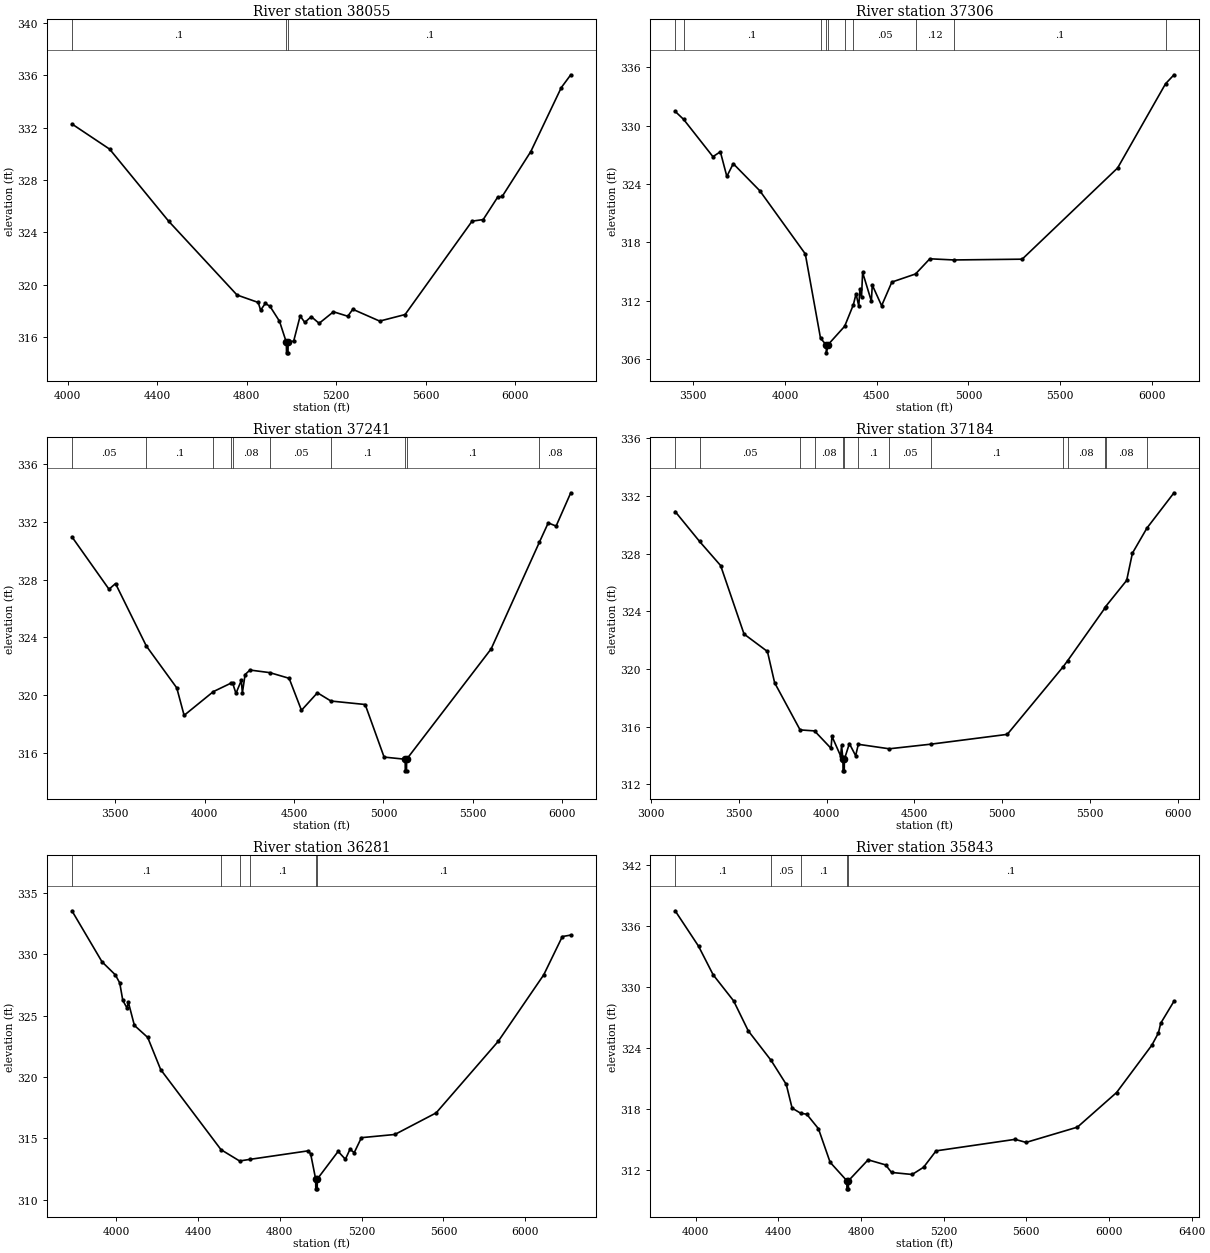
Type RM Length L Ch R = 1 ,38055   ,749,749,749
BEGIN DESCRIPTION:
Mustang Branch 62.0
END DESCRIPTION:
XS GIS Cut Line= 3
      2142124.99     13403925.04        2141825.       13404825.
      2141024.98     13405825.02
#Sta/Elev= 30
  4019.4  332.27    4188  330.35  4451.5  324.86  4757.2  319.23  4852.1  318.66
  4862.6  318.07  4883.7  318.59  4904.8  318.36    4947  317.23  4977.7  315.62
  4978.4  314.82    4985  314.82  4985.6  315.62  5010.5  315.72  5039.3  317.63
  5060.1  317.14  5088.9  317.58  5124.1  317.07  5188.2  317.95  5252.2  317.61
  5274.6  318.14  5394.7  317.24  5508.3  317.74  5807.7  324.86  5857.3  324.98
  5921.3  326.67  5942.1  326.74  6070.2  330.17  6206.2  335.04  6248.7  336.02
#Mann= 3 ,-1 , 0
  4019.4      .1       0  4977.7     .07       0  4985.6      .1       0
Bank Sta=4977.7,4985.6
XS Rating Curve= 0 ,0
Exp/Cntr=0.3,0.1

Type RM Length L Ch R = 1 ,37306   ,65,65,65
BEGIN DESCRIPTION:
Mapping XS d2951806
END DESCRIPTION:
XS GIS Cut Line= 6
      2141911.43     13403878.71      2141039.01     13404113.09
       2140952.2     13404208.58      2140960.88     13404364.83
      2141212.62      13404911.7       2140756.9     13405714.63
#Sta/Elev= 30
  3401.8  331.45  3447.9  330.63  3607.7   326.8  3648.2   327.3  3683.5  324.77
  3718.4  326.08  3863.1   323.3  4111.1  316.81    4194  308.16  4225.4  307.45
    4226  306.65  4233.4  307.45  4325.7  309.38  4373.1  311.59  4387.7  312.71
  4402.6  311.45  4408.7   313.2  4417.5  312.37  4423.5  314.91  4471.2  311.96
  4476.2  313.61  4527.1  311.49  4582.9  313.92  4711.9  314.75  4789.8  316.31
  4920.2  316.19  5293.1  316.27  5813.4  325.64  6074.6  334.29  6120.6  335.21
#Mann= 10 ,-1 , 0
  3401.8     .05       0  3447.9      .1       0    4194     .12       0
  4225.4     .07       0  4233.4     .12       0  4325.7     .08       0
  4373.1     .05       0  4711.9     .12       0  4920.2      .1       0
  6074.6     .08       0
Bank Sta=4225.4,4233.4
XS Rating Curve= 0 ,0
Exp/Cntr=0.3,0.1

Type RM Length L Ch R = 1 ,37241   ,57,57,57
BEGIN DESCRIPTION:
Mapping XS d467104e
END DESCRIPTION:
XS GIS Cut Line= 6
      2141894.01     13403830.98      2141052.03     13404030.63
      2140921.82     13404117.43      2140895.78     13404377.85
      2141125.81     13404916.04      2140701.34     13405721.66
#Sta/Elev= 30
  3258.4  330.95  3465.7  327.33  3502.1  327.72  3674.4  323.41  3844.5  320.52
  3885.7  318.62  4049.1  320.26  4145.2  320.83    4157  320.84  4175.6  320.14
  4205.5  321.03  4211.4  320.17  4226.7  321.44  4253.9  321.75  4365.1  321.57
  4472.8  321.18  4541.8  318.97    4631  320.18  4706.7  319.61    4898  319.37
  5003.8  315.74  5121.6  315.59  5122.3  314.79  5129.1  314.79  5129.8  315.59
  5602.3  323.21  5872.5  330.59  5921.5  331.91  5965.5  331.69  6047.5  333.99
#Mann= 10 ,-1 , 0
  3258.4     .05       0  3674.4      .1       0  4049.1     .08       0
  4145.2     .12       0    4157     .08       0  4365.1     .05       0
  4706.7      .1       0  5121.6     .07       0  5129.8      .1       0
  5872.5     .08       0
Bank Sta=5121.6,5129.8
XS Rating Curve= 0 ,0
Exp/Cntr=0.3,0.1

Type RM Length L Ch R = 1 ,37184   ,903,903,903
BEGIN DESCRIPTION:
Mapping XS a25eb785
END DESCRIPTION:
XS GIS Cut Line= 6
      2141837.59     13403770.22      2141078.07     13403939.48
      2140856.71     13404078.37      2140804.63     13404451.63
      2141052.03     13404781.49        2140618.     13405666.91
#Sta/Elev= 30
    3138  330.92  3276.6  328.85  3396.8  327.17    3530  322.42  3663.2  321.21
  3704.1  319.04    3849  315.77  3931.2   315.7  4025.1  314.49  4030.5  315.32
  4079.8  313.96  4085.1  314.69  4092.8  313.73  4093.5  312.93  4100.3  312.93
    4101  313.73  4129.4  314.82  4165.1  313.98  4180.4  314.77  4356.4  314.46
  4593.3  314.78    5028  315.46  5346.7  320.16  5371.5  320.57  5584.7  324.24
    5588  324.33  5707.4  326.14  5740.1  328.03  5822.7  329.77  5976.8  332.22
#Mann= 14 ,-1 , 0
    3138      .1       0  3276.6     .05       0    3849      .1       0
  3931.2     .08       0  4092.8     .07       0    4101     .08       0
  4180.4      .1       0  4356.4     .05       0  4593.3      .1       0
  5346.7     .05       0  5371.5     .08       0  5584.7      .1       0
    5588     .08       0  5822.7      .1       0
Bank Sta=4092.8,4101
XS Rating Curve= 0 ,0
Exp/Cntr=0.3,0.1

Type RM Length L Ch R = 1 ,36281   ,438,438,438
BEGIN DESCRIPTION:
Mapping XS 7c749c9a
END DESCRIPTION:
XS GIS Cut Line= 4
      2141629.28     13403475.07      2140795.95     13404052.33
      2140448.73      13404490.7      2140322.86     13405345.72
#Sta/Elev= 30
  3784.7  333.54  3931.8  329.38  3996.7  328.32  4018.3  327.66  4033.2  326.24
  4054.1  325.61  4060.2   326.1  4089.9   324.2  4154.9  323.22  4218.3   320.6
  4513.2  314.07  4603.9  313.15  4653.4  313.28  4936.3  313.97  4950.8  313.75
  4975.5  311.68  4976.2  310.88    4983  310.88  4983.7  311.68  5085.3  313.93
  5120.8  313.29  5143.1   314.1  5163.9  313.83  5199.1  315.05  5362.4  315.31
  5564.2  317.07  5867.4   322.9  6089.8  328.32  6180.7  331.44  6221.9  331.56
#Mann= 6 ,-1 , 0
  3784.7      .1       0  4513.2     .05       0  4603.9     .08       0
  4653.4      .1       0  4975.5     .07       0  4983.7      .1       0
Bank Sta=4975.5,4983.7
XS Rating Curve= 0 ,0
Exp/Cntr=0.3,0.1

Type RM Length L Ch R = 1 ,35843   ,368,368,368
BEGIN DESCRIPTION:
Mustang Branch 57.0
END DESCRIPTION:
XS GIS Cut Line= 3
      2141375.03     13403024.97        2140575.       13403825.
        2140125.     13405024.99
#Sta/Elev= 30
  3901.3  337.49  4014.5  334.01  4085.2   331.2  4184.2  328.64  4254.9   325.7
  4365.6  322.79  4438.7  320.44    4467  318.11  4508.9   317.6  4537.7  317.51
  4594.3  316.09  4650.9  312.79  4731.6  310.98  4732.3  310.18  4739.1  310.18
  4739.8  310.98  4834.7  313.03  4919.6  312.53  4947.9  311.79  5047.8  311.59
    5103   312.3  5163.5  313.91  5545.4  315.04  5598.8  314.74  5847.1  316.24
  6036.6  319.64  6207.5   324.3  6238.7  325.48  6250.2  326.45  6314.3  328.61
#Mann= 5 ,-1 , 0
  3901.3      .1       0  4365.6     .05       0  4508.9      .1       0
  4731.6     .07       0  4739.8      .1       0
Bank Sta=4731.6,4739.8
XS Rating Curve= 0 ,0
Exp/Cntr=0.3,0.1

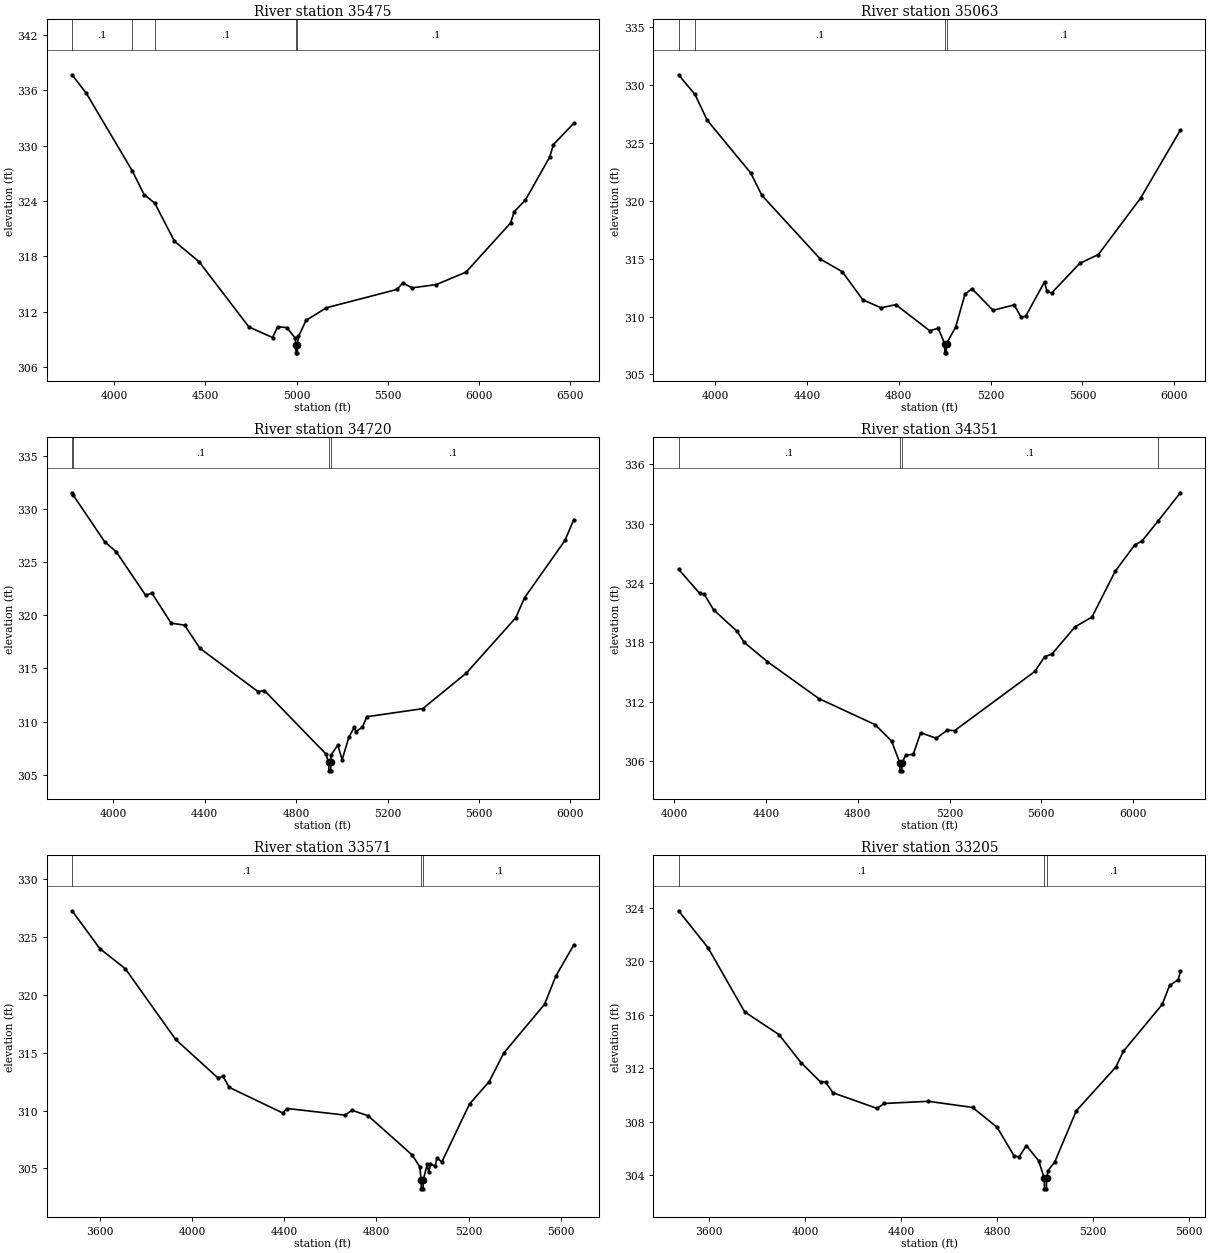
Type RM Length L Ch R = 1 ,35475   ,412,412,412
BEGIN DESCRIPTION:
Mustang Branch 56.0
END DESCRIPTION:
XS GIS Cut Line= 3
      2141325.01     13402924.99        2140325.       13403625.
        2140025.     13405125.02
#Sta/Elev= 30
  3769.6  337.68  3848.5  335.65  4100.4  327.23  4164.2  324.69    4223  323.75
  4330.7  319.63  4465.4  317.41  4738.7  310.33  4868.2  309.18  4896.5  310.35
  4947.1  310.26  4992.8  309.11  4996.3  308.32    4997  307.52  5003.9  307.52
  5004.6  308.32  5010.7   309.3  5051.5  311.03  5163.6  312.41  5551.2   314.4
  5581.8  315.11  5632.7  314.57  5765.3  314.92  5928.5  316.27  6173.2  321.61
  6193.6  322.84  6254.8  324.11  6387.4  328.75  6407.8  330.11    6520  332.43
#Mann= 5 ,-1 , 0
  3769.6      .1       0  4100.4     .05       0    4223      .1       0
  4996.3     .07       0  5004.6      .1       0
Bank Sta=4996.3,5004.6
XS Rating Curve= 0 ,0
Exp/Cntr=0.3,0.1

Type RM Length L Ch R = 1 ,35063   ,343,343,343
BEGIN DESCRIPTION:
Mustang Branch 55.0
END DESCRIPTION:
XS GIS Cut Line= 3
      2141024.98     13402825.01        2140025.       13403425.
      2139024.97     13403625.01
#Sta/Elev= 30
  3840.6  330.88  3912.4  329.18    3965  326.97  4155.4  322.39    4204  320.46
  4458.7  314.96  4553.9  313.88  4643.3  311.45    4723  310.76  4787.1  311.03
  4934.8  308.78  4971.8  308.99  4999.7  307.67  5000.4  306.87  5007.3  306.87
    5008  307.67  5047.6  309.08  5088.3  311.92  5118.9  312.41  5210.7  310.54
  5302.5  311.01  5333.1  309.95  5353.5  310.05  5435.1     313  5445.3   312.2
  5465.7  312.03  5588.1  314.59  5669.6  315.36  5853.2  320.22  6026.6   326.1
#Mann= 4 ,-1 , 0
  3840.6     .05       0  3912.4      .1       0  4999.7     .07       0
    5008      .1       0
Bank Sta=4999.7,5008
XS Rating Curve= 0 ,0
Exp/Cntr=0.3,0.1

Type RM Length L Ch R = 1 ,34720   ,369,369,369
BEGIN DESCRIPTION:
Mustang Branch 54.0
END DESCRIPTION:
XS GIS Cut Line= 3
      2140975.04     13402624.98        2139975.       13403125.
      2138975.01       13403525.
#Sta/Elev= 30
  3819.7   331.5  3824.7  331.28  3962.3   326.9  4012.6  325.97  4141.2  321.88
  4169.1  322.07    4253  319.26  4311.7  319.07  4378.8   316.9  4633.1  312.83
  4661.1  312.93  4929.4  306.99  4942.5  306.19  4943.4  305.39  4951.1  305.39
    4952  306.19  4952.6  306.89  4982.2   307.8  5001.1  306.44  5030.7  308.55
  5054.9  309.52  5060.3  309.07  5089.9  309.48  5108.8  310.47  5353.8  311.23
    5545  314.58  5760.4  319.76  5799.4  321.65  5975.8  327.02  6014.8  328.99
#Mann= 4 ,-1 , 0
  3819.7     .08       0  3824.7      .1       0  4942.5     .07       0
    4952      .1       0
Bank Sta=4942.5,4952
XS Rating Curve= 0 ,0
Exp/Cntr=0.3,0.1

Type RM Length L Ch R = 1 ,34351   ,780,780,780
BEGIN DESCRIPTION:
Mustang Branch 53.0
END DESCRIPTION:
XS GIS Cut Line= 3
      2140775.01       13402675.        2139775.       13402875.
        2138775.       13403475.
#Sta/Elev= 30
  4019.5  325.39  4111.3  322.96  4131.7  322.85  4172.5  321.29  4274.5  319.13
  4305.1  318.02    4407  316.06  4631.4  312.33  4876.1  309.71  4947.5  308.06
  4983.5  305.85  4984.5  305.05  4992.2  305.05  4993.1  305.85  5008.7   306.6
  5042.2  306.73  5074.3  308.89  5142.3  308.34  5190.9  309.16    5222   309.1
  5571.9  315.08  5614.6  316.57  5645.7  316.82  5746.8  319.57  5820.7  320.57
  5921.7  325.18  6007.3  327.85  6038.4  328.23  6109.7  330.28  6205.5   333.1
#Mann= 4 ,-1 , 0
  4019.5      .1       0  4983.5     .07       0  4993.1      .1       0
  6109.7     .05       0
Bank Sta=4983.5,4993.1
XS Rating Curve= 0 ,0
Exp/Cntr=0.3,0.1

Type RM Length L Ch R = 1 ,33571   ,366,366,366
BEGIN DESCRIPTION:
Mustang Branch 52.0
END DESCRIPTION:
XS GIS Cut Line= 3
      2140825.03       13402575.        2139325.       13402425.
      2138874.99     13402925.01
#Sta/Elev= 30
  3477.4  327.26    3598  323.99  3708.6  322.26  3927.2  316.15  4110.6  312.83
  4133.2  312.95  4160.8     312    4392   309.8  4412.1  310.18  4663.3  309.61
  4693.5  310.03  4763.8  309.55  4954.8  306.17  4988.3  305.14  4993.9  304.04
  4994.8  303.24  5002.6  303.24  5003.5  304.04  5020.4  305.35  5027.1  304.69
  5034.6  305.36  5055.5  305.24    5063  305.92  5083.9  305.56  5204.3  310.57
  5289.5   312.5    5353  314.97  5530.2  319.18  5579.5  321.63  5657.6  324.32
#Mann= 3 ,-1 , 0
  3477.4      .1       0  4993.9     .07       0  5003.5      .1       0
Bank Sta=4993.9,5003.5
XS Rating Curve= 0 ,0
Exp/Cntr=0.3,0.1

Type RM Length L Ch R = 1 ,33205   ,397,397,397
BEGIN DESCRIPTION:
Mustang Branch 51.0
END DESCRIPTION:
XS GIS Cut Line= 3
      2140675.02       13402425.        2139175.       13402125.
      2138675.04     13402374.98
#Sta/Elev= 30
  3473.7   323.8  3596.1  321.04  3749.1  316.22  3891.8  314.52  3983.6  312.42
  4065.2  310.96  4085.6  310.98  4116.2  310.16  4299.8  308.99  4330.4  309.36
  4513.9  309.52  4697.5  309.06  4799.5  307.58  4870.8  305.42  4891.2  305.36
  4921.8   306.2  4972.8  305.06    4996  303.76  4996.9  302.96  5004.8  302.96
  5005.8  303.76  5011.8  304.33  5039.8  304.98  5129.2   308.8  5294.1  312.09
  5324.9  313.26    5487  316.78  5517.7   318.2  5554.1  318.64  5562.4  319.26
#Mann= 3 ,-1 , 0
  3473.7      .1       0    4996     .07       0  5005.8      .1       0
Bank Sta=4996,5005.8
XS Rating Curve= 0 ,0
Exp/Cntr=0.3,0.1

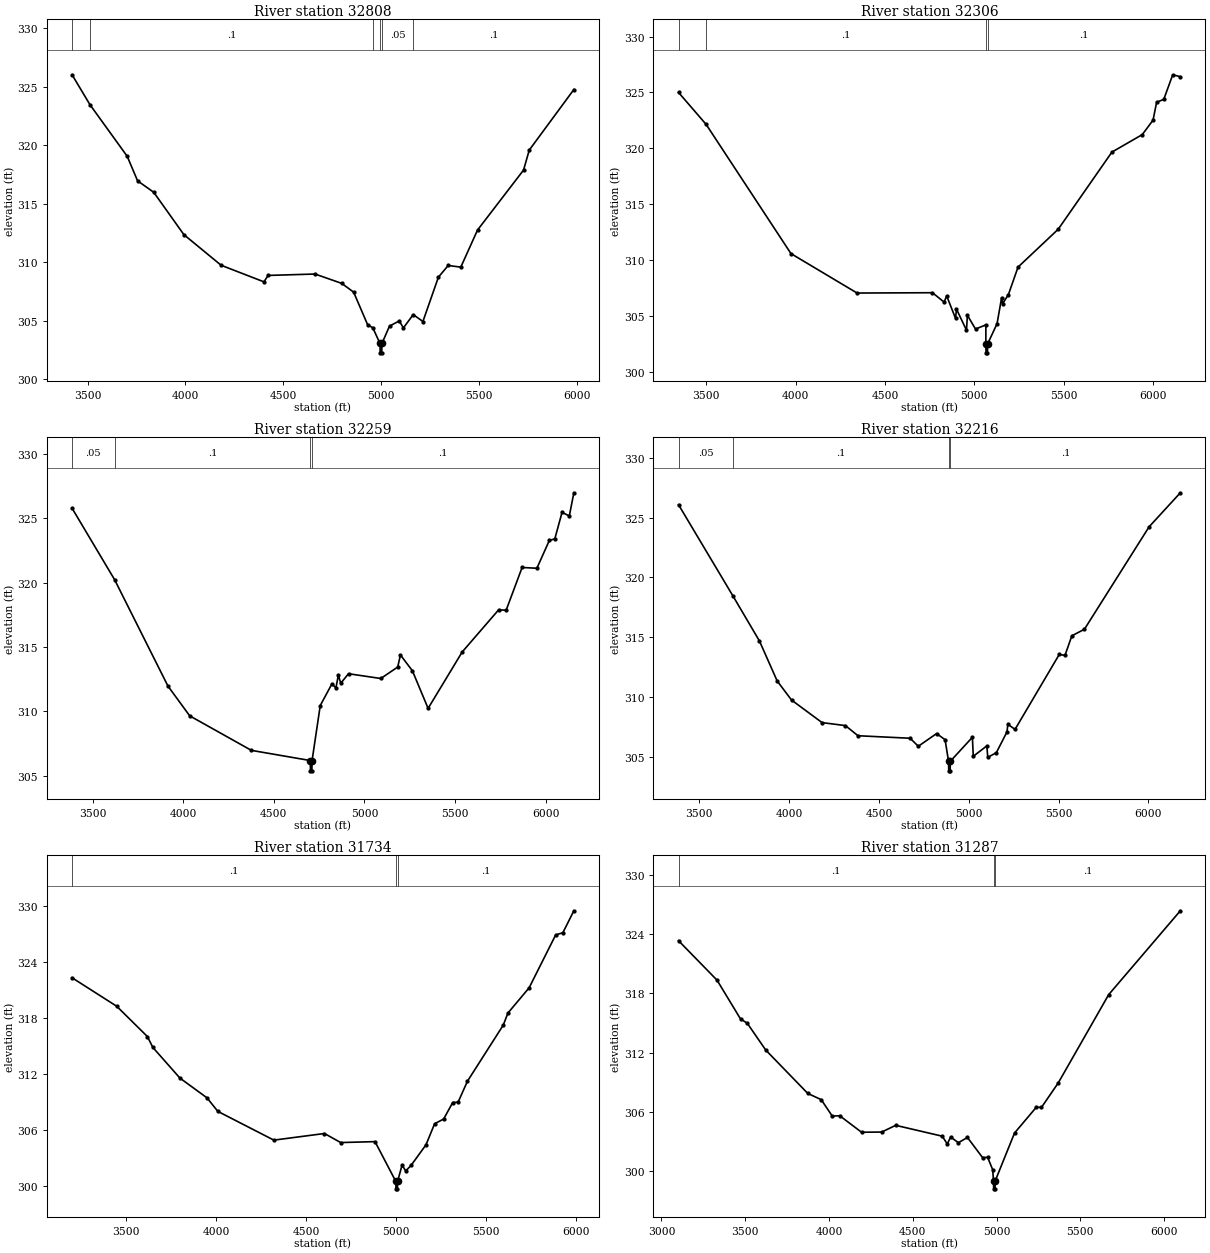
Type RM Length L Ch R = 1 ,32808   ,502,502,502
BEGIN DESCRIPTION:
Mustang Branch 50.0
END DESCRIPTION:
XS GIS Cut Line= 3
      2140775.04     13402275.01        2139275.       13401825.
      2138474.99     13402425.01
#Sta/Elev= 30
    3420  326.02  3511.6  323.46  3701.9  319.05    3755  316.95  3837.7  315.97
  3991.7  312.35  4182.2  309.73  4401.4  308.31  4422.3  308.86  4662.4  308.98
    4799  308.18  4859.9  307.43  4931.3  304.65    4958  304.38  4994.7  303.04
  4995.7  302.24  5003.6  302.24  5004.6  303.04  5043.4  304.53  5093.4  304.97
  5114.2  304.37  5164.7  305.51  5214.2  304.92  5293.4  308.71  5343.4  309.71
    5408  309.57  5493.4  312.74  5728.8  317.87    5758  319.58  5986.1  324.76
#Mann= 6 ,-1 , 0
    3420     .05       0  3511.6      .1       0    4958     .05       0
  4994.7    .033       0  5004.6     .05       0  5164.7      .1       0
Bank Sta=4994.7,5004.6
XS Rating Curve= 0 ,0
Exp/Cntr=0.3,0.1

Type RM Length L Ch R = 1 ,32306   ,47,47,47
BEGIN DESCRIPTION:
Mapping XS 1a054081
END DESCRIPTION:
XS GIS Cut Line= 6
      2140774.24     13401582.71      2139333.28     13401539.31
      2139294.21     13401482.88      2139111.92     13401456.84
      2138812.44     13401561.01      2138022.51     13401608.75
#Sta/Elev= 30
  3344.2     325  3498.7  322.14  3973.7  310.58  4343.9  307.05  4765.9  307.08
  4831.2  306.24  4845.6  306.79  4895.4  304.78  4900.6  305.61  4956.6  303.72
  4961.6  305.06  5007.1  303.83    5065   304.2  5065.1   302.5  5066.1   301.7
    5074   301.7    5075   302.5  5127.7  304.31  5153.3  306.64  5158.8  306.09
  5191.5  306.92  5245.1  309.37  5470.2  312.76  5770.7  319.66    5941  321.23
  6001.1  322.52  6021.2  324.12  6061.2  324.38  6111.3  326.58  6153.9  326.41
#Mann= 4 ,-1 , 0
  3344.2     .05       0  3498.7      .1       0  5065.1     .07       0
    5075      .1       0
Bank Sta=5065.1,5075
XS Rating Curve= 0 ,0
Exp/Cntr=0.3,0.1

Type RM Length L Ch R = 1 ,32259   ,43,43,43
BEGIN DESCRIPTION:
Mapping XS 71241e58
END DESCRIPTION:
XS GIS Cut Line= 6
      2140743.87     13401539.31      2139363.66     13401500.24
      2139246.47     13401417.78      2138981.71     13401413.44
      2138842.82     13401504.58      2138039.94     13401552.32
#Sta/Elev= 30
  3386.8  325.78  3621.6  320.23  3915.9  311.97  4035.9  309.66  4376.1  306.98
  4701.2  306.19  4702.2  305.39  4710.1  305.39  4711.1  306.19  4756.2  310.46
  4820.9  312.15  4842.6  311.82  4856.2  312.82  4869.3  312.19  4912.1  312.93
  5090.4  312.56  5183.7  313.45  5198.6  314.39  5264.6  313.16  5351.3  310.24
  5539.5  314.62  5739.8  317.88  5782.2  317.87    5870  321.18  5951.6  321.12
  6020.3  323.28  6050.4   323.4  6090.4  325.46  6130.5  325.18  6155.6  326.98
#Mann= 4 ,-1 , 0
  3386.8     .05       0  3621.6      .1       0  4701.2     .07       0
  4711.1      .1       0
Bank Sta=4701.2,4711.1
XS Rating Curve= 0 ,0
Exp/Cntr=0.3,0.1

Type RM Length L Ch R = 1 ,32216   ,482,482,482
BEGIN DESCRIPTION:
Mapping XS b1e68141
END DESCRIPTION:
XS GIS Cut Line= 6
      2140743.91     13401513.27      2139428.76      13401474.2
      2139372.34     13401396.08      2139051.16     13401357.01
       2138786.4     13401456.84      2138031.19     13401478.54
#Sta/Elev= 30
  3384.1  326.09  3688.2  318.42  3834.6  314.68  3933.3  311.33  4013.3  309.73
  4183.4  307.84  4313.4  307.59  4383.5  306.74  4673.6  306.53  4719.4  305.86
    4821  306.92  4868.4  306.41  4887.7   304.6  4888.7   303.8  4896.6   303.8
  4897.6   304.6  5020.4  306.61  5025.5  305.02    5101  305.89  5106.1  304.93
  5153.8  305.32    5213  307.06    5218   307.7  5257.9  307.27  5504.3  313.55
  5536.1  313.47  5574.3  315.11  5644.4  315.66  6004.5  324.24  6178.4  327.09
#Mann= 4 ,-1 , 0
  3384.1     .05       0  3688.2      .1       0  4887.7     .07       0
  4897.6      .1       0
Bank Sta=4887.7,4897.6
XS Rating Curve= 0 ,0
Exp/Cntr=0.3,0.1

Type RM Length L Ch R = 1 ,31734   ,447,447,447
BEGIN DESCRIPTION:
Mapping XS 0887c84d
END DESCRIPTION:
XS GIS Cut Line= 2
      2140822.03     13400818.82      2138044.25     13401061.87
#Sta/Elev= 30
  3200.3  322.33  3448.3  319.28  3618.9  316.03    3649  314.87  3799.6  311.58
  3950.2  309.46  4010.4  308.01  4321.6  304.93  4602.7  305.64    4693  304.67
  4883.7  304.77  4999.2  300.51  5000.2  299.71  5008.2  299.71  5009.1  300.51
  5034.3  302.26  5054.4  301.63  5084.5  302.23    5167  304.43    5215  306.69
  5265.2  307.19  5315.4  308.96  5345.5     309  5397.2  311.24  5596.5  317.26
  5622.3  318.55  5739.9  321.25  5887.6  326.92  5927.7  327.16  5988.7  329.51
#Mann= 3 ,-1 , 0
  3200.3      .1       0  4999.2     .07       0  5009.1      .1       0
Bank Sta=4999.2,5009.1
XS Rating Curve= 0 ,0
Exp/Cntr=0.3,0.1

Type RM Length L Ch R = 1 ,31287   ,656,656,656
BEGIN DESCRIPTION:
Mapping XS d61507a5
END DESCRIPTION:
XS GIS Cut Line= 2
      2140843.73     13400436.87      2137858.75      13400675.5
#Sta/Elev= 30
  3102.2  323.33  3331.7  319.34  3472.1  315.41  3512.2  314.98  3622.6  312.26
  3873.4  307.87  3953.6  307.24  4019.4  305.58    4064  305.61  4194.4  303.94
  4314.8  303.96  4398.2  304.64  4675.9  303.54    4706  302.75  4726.1  303.46
    4772  302.88  4826.4  303.41  4916.7  301.37  4946.8   301.4  4976.9  300.15
  4981.9  299.01  4982.9  298.21  4990.9  298.21  4991.9  299.01  5107.3  303.86
  5237.7  306.48  5267.8  306.45  5368.1  308.93  5669.1  317.87  6096.7  326.36
#Mann= 3 ,-1 , 0
  3102.2      .1       0  4981.9     .07       0  4991.9      .1       0
Bank Sta=4981.9,4991.9
XS Rating Curve= 0 ,0
Exp/Cntr=0.3,0.1

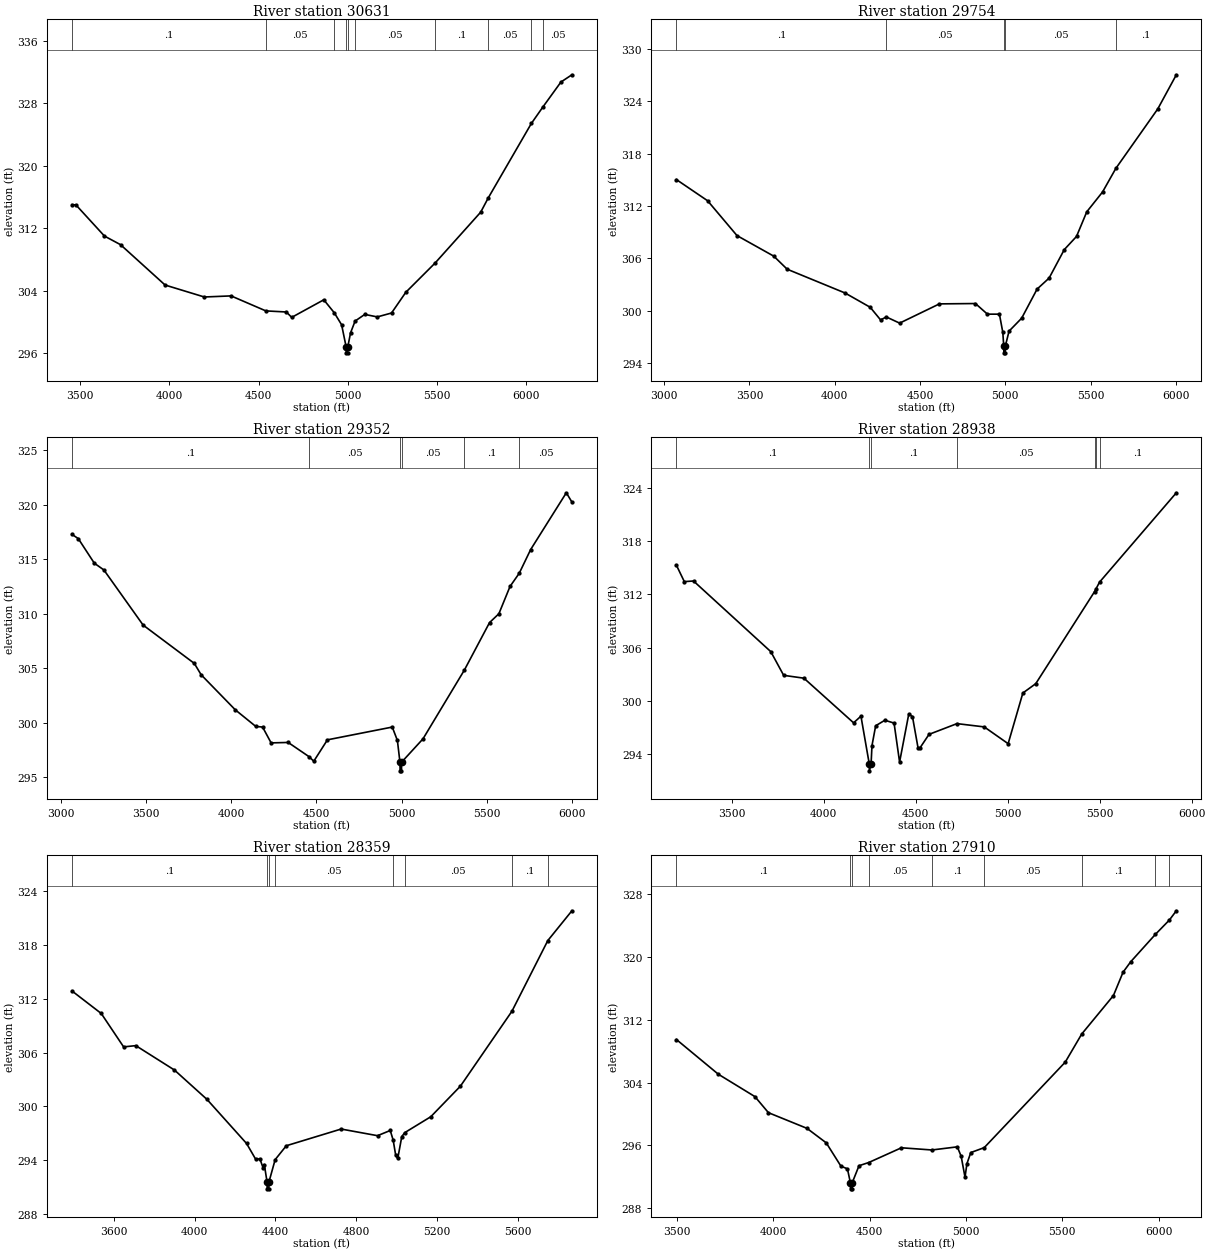
Type RM Length L Ch R = 1 ,30631   ,877,877,877
BEGIN DESCRIPTION:
Mapping XS 52bed4bc
END DESCRIPTION:
XS GIS Cut Line= 2
      2140557.21     13400020.21      2137753.45     13400063.61
#Sta/Elev= 30
  3453.6  314.99  3475.8  314.97  3635.8  310.98  3725.8  309.88  3975.9  304.71
  4195.9  303.18  4345.9  303.32    4541   301.4    4656  301.26    4686  300.57
    4866  302.82  4924.8  301.16    4966  299.62    4991  296.83    4992  296.03
    5000  296.03    5001  296.83    5016  298.58  5041.6   300.1    5096  300.95
    5166  300.63    5246  301.13    5326  303.78    5490  307.52  5746.1  314.04
  5788.3  315.86  6030.3   325.4  6094.7   327.5  6196.1   330.7  6257.7  331.63
#Mann= 10 ,-1 , 0
  3453.6      .1       0    4541     .05       0  4924.8      .1       0
    4991     .07       0    5001      .1       0  5041.6     .05       0
    5490      .1       0  5788.3     .05       0  6030.3      .1       0
  6094.7     .05       0
Bank Sta=4991,5001
XS Rating Curve= 0 ,0
Exp/Cntr=0.3,0.1

Type RM Length L Ch R = 1 ,29754   ,402,402,402
BEGIN DESCRIPTION:
Mapping XS f223b154
END DESCRIPTION:
XS GIS Cut Line= 3
       2140735.2     13399694.69      2139194.39     13399434.27
      2137832.25     13399560.07
#Sta/Elev= 30
  3072.2  315.03    3255   312.6  3427.4   308.6  3642.9  306.24  3721.5  304.74
  4060.8  302.01  4208.3  300.37  4269.1  298.92  4302.7  299.26  4380.7  298.55
    4614  300.76  4825.1   300.8  4895.4  299.58  4965.7  299.58  4985.7  297.48
  4990.8  295.94  4991.7  295.14  4999.8  295.14  5000.8  295.94  5022.1  297.63
  5096.2  299.12  5186.6  302.46  5256.9  303.72  5345.9  306.99  5417.6   308.5
  5477.8  311.33  5570.1   313.6  5648.1  316.31  5893.9  323.14  6002.8  327.06
#Mann= 5 ,-1 , 0
  3072.2      .1       0  4302.7     .05       0  4990.8    .035       0
  5000.8     .05       0  5648.1      .1       0
Bank Sta=4990.8,5000.8
XS Rating Curve= 0 ,0
Exp/Cntr=0.3,0.1

Type RM Length L Ch R = 1 ,29352   ,414,414,414
BEGIN DESCRIPTION:
Mapping XS 514e7d56
END DESCRIPTION:
XS GIS Cut Line= 2
        2140822.     13398982.88       2137892.3     13399143.47
#Sta/Elev= 30
  3065.9  317.27    3103  316.88    3197  314.63  3253.2  314.01  3483.5  308.96
    3784  305.45    3824  304.41  4024.3   301.2  4144.5  299.68  4184.6  299.62
  4234.7  298.17  4334.8  298.21  4457.9   296.9    4485  296.49  4565.1  298.45
  4945.7  299.62  4975.8  298.39  4990.7  296.41  4991.7  295.61  4999.8  295.61
  5000.8  296.41    5126  298.54  5368.5  304.83  5516.6  309.19  5571.4     310
  5636.8   312.5  5690.9  313.71  5757.9  315.88  5967.2  321.08    6000  320.23
#Mann= 6 ,-1 , 0
  3065.9      .1       0  4457.9     .05       0  4990.7     .03       0
  5000.8     .05       0  5368.5      .1       0  5690.9     .05       0
Bank Sta=4990.7,5000.8
XS Rating Curve= 0 ,0
Exp/Cntr=0.3,0.1

Type RM Length L Ch R = 1 ,28938   ,579,579,579
BEGIN DESCRIPTION:
Mapping XS 83329405
END DESCRIPTION:
XS GIS Cut Line= 2
      2140618.02     13398713.79      2137900.95     13398726.81
#Sta/Elev= 30
  3199.7  315.29  3242.7  313.44  3292.7  313.51  3712.7  305.55  3782.7  302.88
  3892.7  302.56  4162.7  297.53  4202.7  298.28  4247.7  292.92  4248.7  292.12
  4257.8  292.92  4262.7  294.97  4282.7   297.2  4332.7  297.82  4382.7   297.5
  4412.7  293.11  4462.7  298.53  4482.7  298.23  4512.7  294.74  4522.7  294.68
  4572.7  296.23  4724.7  297.44  4872.7  297.07  5002.7  295.18  5082.7  300.89
  5152.7  301.94  5472.3  312.31  5479.8  312.61  5499.4  313.38  5916.8  323.45
#Mann= 7 ,-1 , 0
  3199.7      .1       0  4247.7     .03       0  4257.8      .1       0
  4724.7     .05       0  5472.3      .1       0  5479.8     .05       0
  5499.4      .1       0
Bank Sta=4247.7,4257.8
XS Rating Curve= 0 ,0
Exp/Cntr=0.3,0.1

Type RM Length L Ch R = 1 ,28359   ,449,449,449
BEGIN DESCRIPTION:
Mapping XS 95e7094c
END DESCRIPTION:
XS GIS Cut Line= 3
      2140578.96     13398431.67      2139333.28      13398284.1
      2138113.68     13398344.86
#Sta/Elev= 30
    3393  312.86    3538  310.35  3648.7  306.63  3709.2  306.77  3900.5  304.05
  4061.6  300.78  4257.6  295.87  4303.3  294.09  4323.4  294.17  4340.4  293.09
  4345.4  293.53  4358.7  291.62  4359.7  290.82  4367.8  290.82  4368.8  291.62
    4399  294.07  4454.3  295.62  4725.8  297.48    4906  296.74    4969  297.32
  4983.5  296.24  4996.1  294.54  5006.1   294.2  5026.1  296.64  5040.8  297.08
  5169.6  298.85  5316.5  302.26  5571.5   310.6  5749.1  318.47  5868.5  321.79
#Mann= 8 ,-1 , 0
    3393      .1       0  4358.7     .07       0  4368.8      .1       0
    4399     .05       0  4983.5      .1       0  5040.8     .05       0
  5571.5      .1       0  5749.1     .05       0
Bank Sta=4358.7,4368.8
XS Rating Curve= 0 ,0
Exp/Cntr=0.3,0.1

Type RM Length L Ch R = 1 ,27910   ,459,459,459
BEGIN DESCRIPTION:
Mapping XS 9e22971a
END DESCRIPTION:
XS GIS Cut Line= 2
       2140522.5     13397958.58      2137928.56     13397871.82
#Sta/Elev= 30
  3497.1  309.49  3714.7  305.06  3904.8   302.2  3974.9  300.15    4175  298.15
    4275   296.3  4351.1  293.33  4385.1  292.98  4400.1  291.23  4401.1  290.43
  4409.2  290.43  4410.2  291.23  4445.1  293.38  4495.6  293.79  4665.3  295.67
  4823.6  295.39  4955.4  295.79  4975.4  294.59  4995.4  291.92  5005.4  293.65
  5025.5  295.06  5095.2  295.69  5515.7   306.6  5601.3  310.19  5765.9   315.1
  5815.9  318.08  5855.9  319.42  5983.8  322.91  6056.1  324.73  6092.5  325.92
#Mann= 9 ,-1 , 0
  3497.1      .1       0  4400.1     .07       0  4410.2      .1       0
  4495.6     .05       0  4823.6      .1       0  5095.2     .05       0
  5601.3      .1       0  5983.8     .05       0  6056.1      .1       0
Bank Sta=4400.1,4410.2
XS Rating Curve= 0 ,0
Exp/Cntr=0.3,0.1