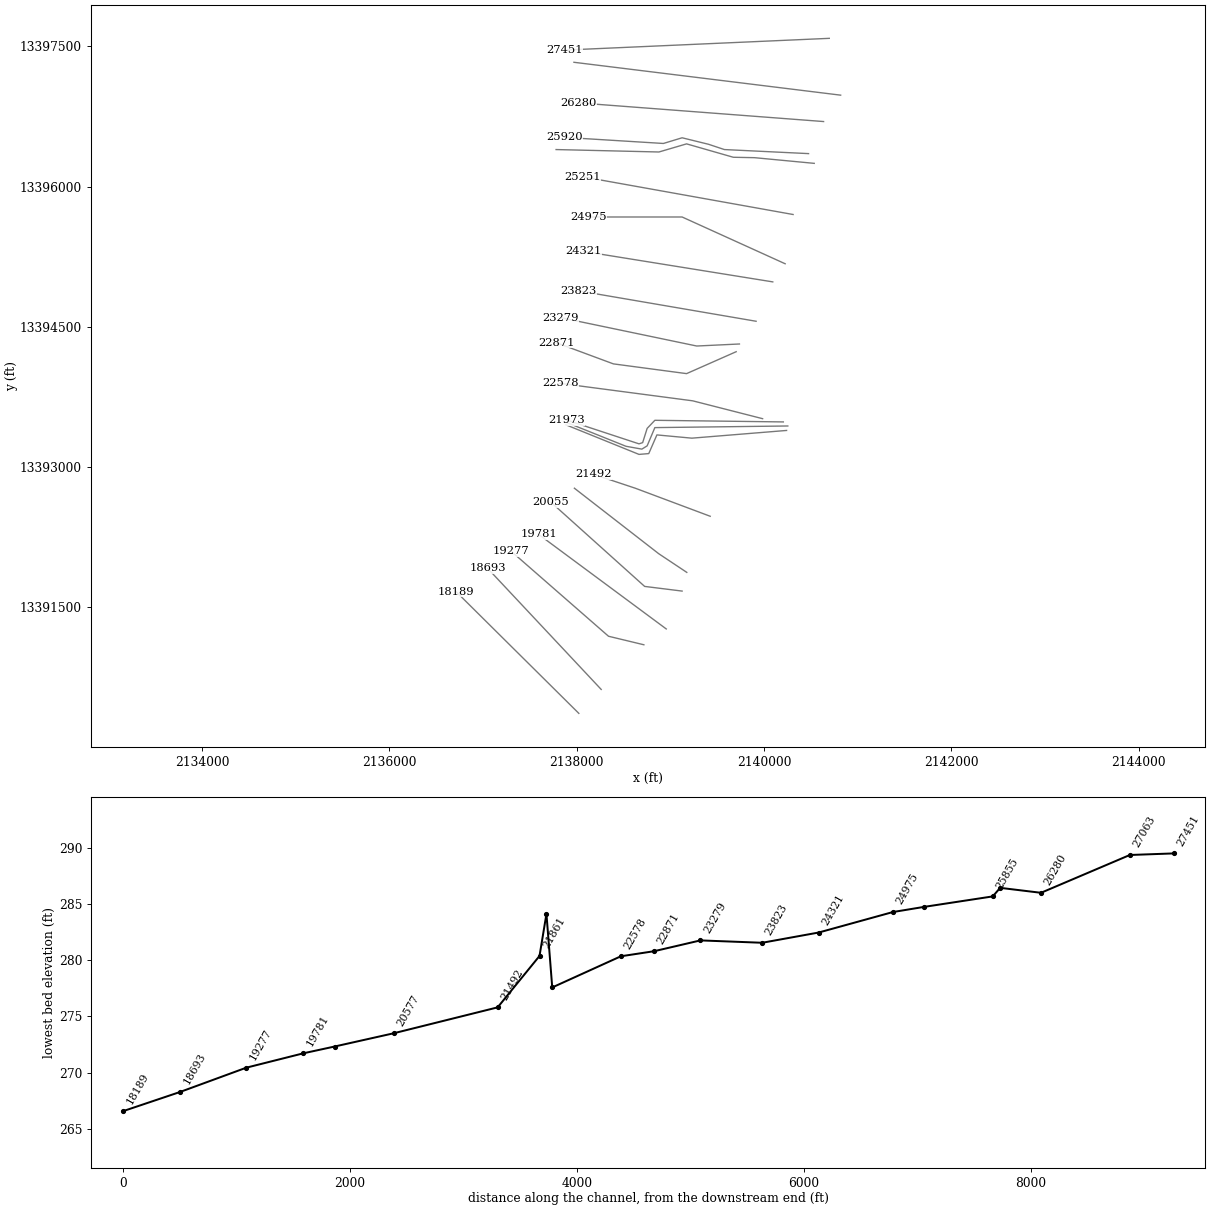
HEC-RAS study Mustang Branch.prj: Mustang Branch Base Level Engineering

--- Mustang Branch.g01 (geometry) --- (continued)

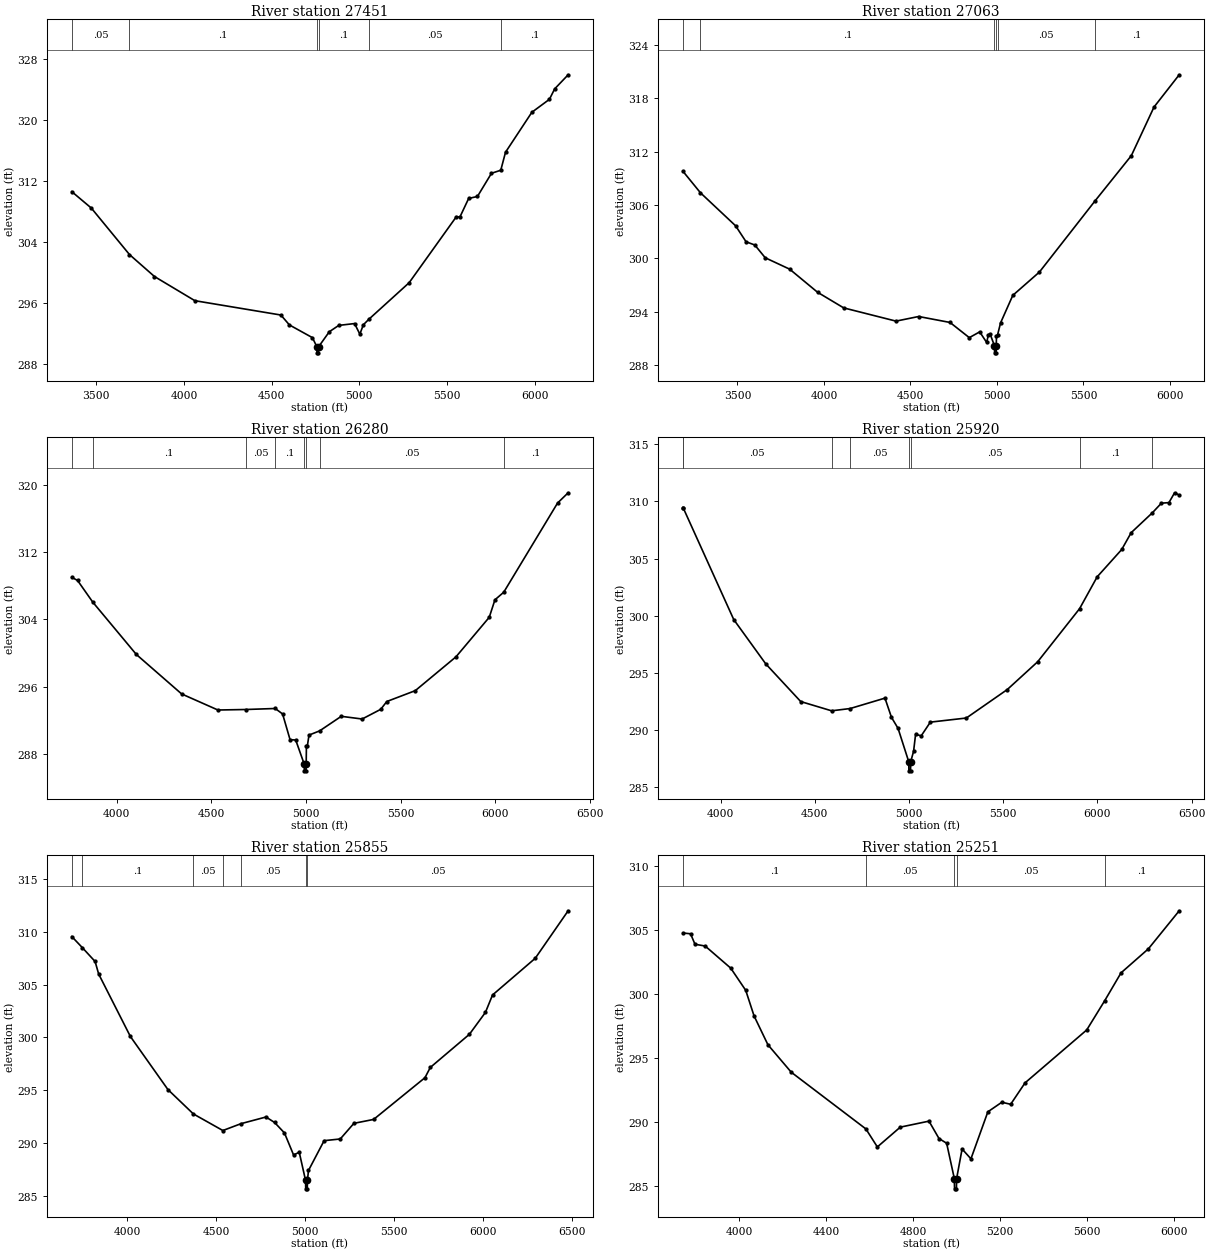
Type RM Length L Ch R = 1 ,27451   ,388,388,388
BEGIN DESCRIPTION:
Mapping XS aa694355
END DESCRIPTION:
XS GIS Cut Line= 2
      2140696.08     13397585.31      2137868.17     13397459.53
#Sta/Elev= 30
  3360.6  310.63  3471.8  308.48  3689.6  302.38  3832.1   299.5  4062.4  296.33
  4552.9  294.45  4601.6  293.15    4733  291.48    4758  290.29    4759  289.49
  4767.2  289.49  4768.1  290.29  4829.3  292.26  4883.2  293.09  4973.3  293.33
  5003.3  291.94  5023.3  293.17    5054  293.88  5284.6  298.69  5553.8  307.35
  5573.9   307.3  5623.9  309.74    5674     310    5754  313.04    5807  313.44
  5834.1   315.8  5984.3  321.04  6084.4  322.74  6114.4  324.11  6191.3  325.96
#Mann= 6 ,-1 , 0
  3360.6     .05       0  3689.6      .1       0    4758     .07       0
  4768.1      .1       0    5054     .05       0    5807      .1       0
Bank Sta=4758,4768.1
XS Rating Curve= 0 ,0
Exp/Cntr=0.3,0.1

Type RM Length L Ch R = 1 ,27063   ,783,783,783
BEGIN DESCRIPTION:
Mapping XS e1d42826
END DESCRIPTION:
XS GIS Cut Line= 2
      2140817.63     13396977.68      2137970.45     13397329.23
#Sta/Elev= 30
  3184.5   309.8  3286.5  307.36  3489.4  303.65  3549.9  301.85  3600.3  301.49
  3660.7  300.05  3801.8  298.77    3963  296.17  4114.1  294.41  4416.4  292.92
  4547.4  293.44  4728.8  292.77  4840.1  291.06  4900.1  291.71  4940.4  290.52
  4950.4  291.38  4960.5  291.46  4985.5  290.15  4986.4  289.35    4995  289.35
  4995.9  290.15  4997.2  291.25  5003.2  291.35    5021  292.73  5091.5  295.82
  5245.6  298.45  5566.7  306.45  5776.7  311.55  5907.7  317.02  6053.3  320.65
#Mann= 6 ,-1 , 0
  3184.5     .05       0  3286.5      .1       0  4985.5     .07       0
  4995.9      .1       0  5003.2     .05       0  5566.7      .1       0
Bank Sta=4985.5,4995.9
XS Rating Curve= 0 ,0
Exp/Cntr=0.3,0.1

Type RM Length L Ch R = 1 ,26280   ,360,360,360
BEGIN DESCRIPTION:
Mapping XS f3b2de92
END DESCRIPTION:
XS GIS Cut Line= 2
      2140635.31     13396695.56      2138019.11     13396895.14
#Sta/Elev= 30
  3761.9  308.99  3792.3  308.62  3873.2  306.03  4103.2  299.82  4342.5  295.13
  4534.4  293.22  4680.8  293.28  4837.2   293.4  4876.2  292.75  4915.6   289.7
  4945.6  289.65  4990.5  286.79  4991.4  285.99  5000.1  285.99    5001  286.79
  5002.1  288.98  5007.2  288.97  5015.8  290.24    5072  290.74  5186.3  292.47
  5296.7  292.15  5394.9   293.3    5427  294.23  5577.5  295.52  5792.7  299.54
  5968.6  304.24  5998.7  306.32  6045.2  307.22  6329.7  317.82  6385.7  319.04
#Mann= 8 ,-1 , 0
  3761.9     .05       0  3873.2      .1       0  4680.8     .05       0
  4837.2      .1       0  4990.5     .07       0    5001      .1       0
    5072     .05       0  6045.2      .1       0
Bank Sta=4990.5,5001
XS Rating Curve= 0 ,0
Exp/Cntr=0.3,0.1

Type RM Length L Ch R = 1 ,25920   ,65,65,65
BEGIN DESCRIPTION:
Mapping XS 64f8f14b
END DESCRIPTION:
XS GIS Cut Line= 6
      2140474.82     13396352.67      2139576.33     13396396.08
      2139407.06      13396452.5      2139124.94     13396521.95
      2138925.29     13396461.18      2137870.56     13396526.29
#Sta/Elev= 30
  3800.1  309.45  3801.4  309.45  4070.2  299.66  4240.3  295.78  4425.6  292.49
  4589.4  291.68    4688  291.88  4872.6  292.79  4907.2  291.11  4942.2  290.14
  4998.8  287.23  4999.7  286.43  5008.4  286.43  5009.3  287.23  5024.5  288.14
  5035.1  289.61  5065.3   289.5  5113.5  290.69  5304.5  291.05  5521.7  293.54
    5683  295.97  5905.3  300.61  5998.8   303.4  6129.1  305.79  6179.2  307.26
  6292.3  309.01  6339.5  309.84  6379.6  309.89  6409.6  310.75  6434.1  310.55
#Mann= 8 ,-1 , 0
  3800.1      .1       0  3801.4     .05       0  4589.4      .1       0
    4688     .05       0  4998.8     .04       0  5009.3     .05       0
  5905.3      .1       0  6292.3     .05       0
Bank Sta=4998.8,5009.3
XS Rating Curve= 0 ,0
Exp/Cntr=0.3,0.1

Type RM Length L Ch R = 1 ,25855   ,604,604,604
BEGIN DESCRIPTION:
Mapping XS 8c489e19
END DESCRIPTION:
XS GIS Cut Line= 6
      2140535.55     13396248.51      2139897.51     13396309.27
      2139671.82     13396313.61      2139172.69     13396456.84
      2138877.55     13396370.04      2137779.77     13396396.07
#Sta/Elev= 30
  3687.2  309.55  3746.5   308.5  3818.3  307.19  3838.4     306  4016.8  300.09
  4227.8  295.07  4371.1  292.76    4537  291.19  4639.3  291.84  4779.5  292.47
  4828.1  291.95  4883.5  290.96  4934.7  288.88  4966.7  289.13  5002.2  286.47
  5003.1  285.67  5011.8  285.67  5012.7  286.47  5018.7  287.41  5106.6  290.23
  5197.4  290.39  5274.2  291.87  5385.1  292.24  5673.9  296.19  5703.9  297.16
    5924   300.3    6014  302.37    6054  304.02  6294.1  307.49  6479.4  311.99
#Mann= 7 ,-1 , 0
  3687.2     .05       0  3746.5      .1       0  4371.1     .05       0
    4537      .1       0  4639.3     .05       0  5002.2     .04       0
  5012.7     .05       0
Bank Sta=5002.2,5012.7
XS Rating Curve= 0 ,0
Exp/Cntr=0.3,0.1

Type RM Length L Ch R = 1 ,25251   ,276,276,276
BEGIN DESCRIPTION:
Mapping XS c225eceb
END DESCRIPTION:
XS GIS Cut Line= 2
      2140309.89     13395701.62      2138061.54     13396105.29
#Sta/Elev= 30
  3741.1  304.77  3776.5  304.71  3796.9  303.89  3843.8  303.75  3961.4  302.02
  4030.5  300.28  4068.8  298.28  4132.6  296.02    4240  293.87  4583.5  289.43
  4636.2  288.02  4741.7  289.57  4873.8  290.04  4919.9  288.68  4955.1  288.31
  4990.5  285.54  4991.4  284.74  5000.1  284.74    5001  285.54  5026.2  287.86
  5066.9  287.09  5144.8  290.77  5209.1  291.52  5249.7  291.36  5316.1  293.04
  5599.8  297.18  5682.9  299.48  5757.7  301.65  5883.5  303.53  6025.4  306.51
#Mann= 5 ,-1 , 0
  3741.1      .1       0  4583.5     .05       0  4990.5     .03       0
    5001     .05       0  5682.9      .1       0
Bank Sta=4990.5,5001
XS Rating Curve= 0 ,0
Exp/Cntr=0.3,0.1

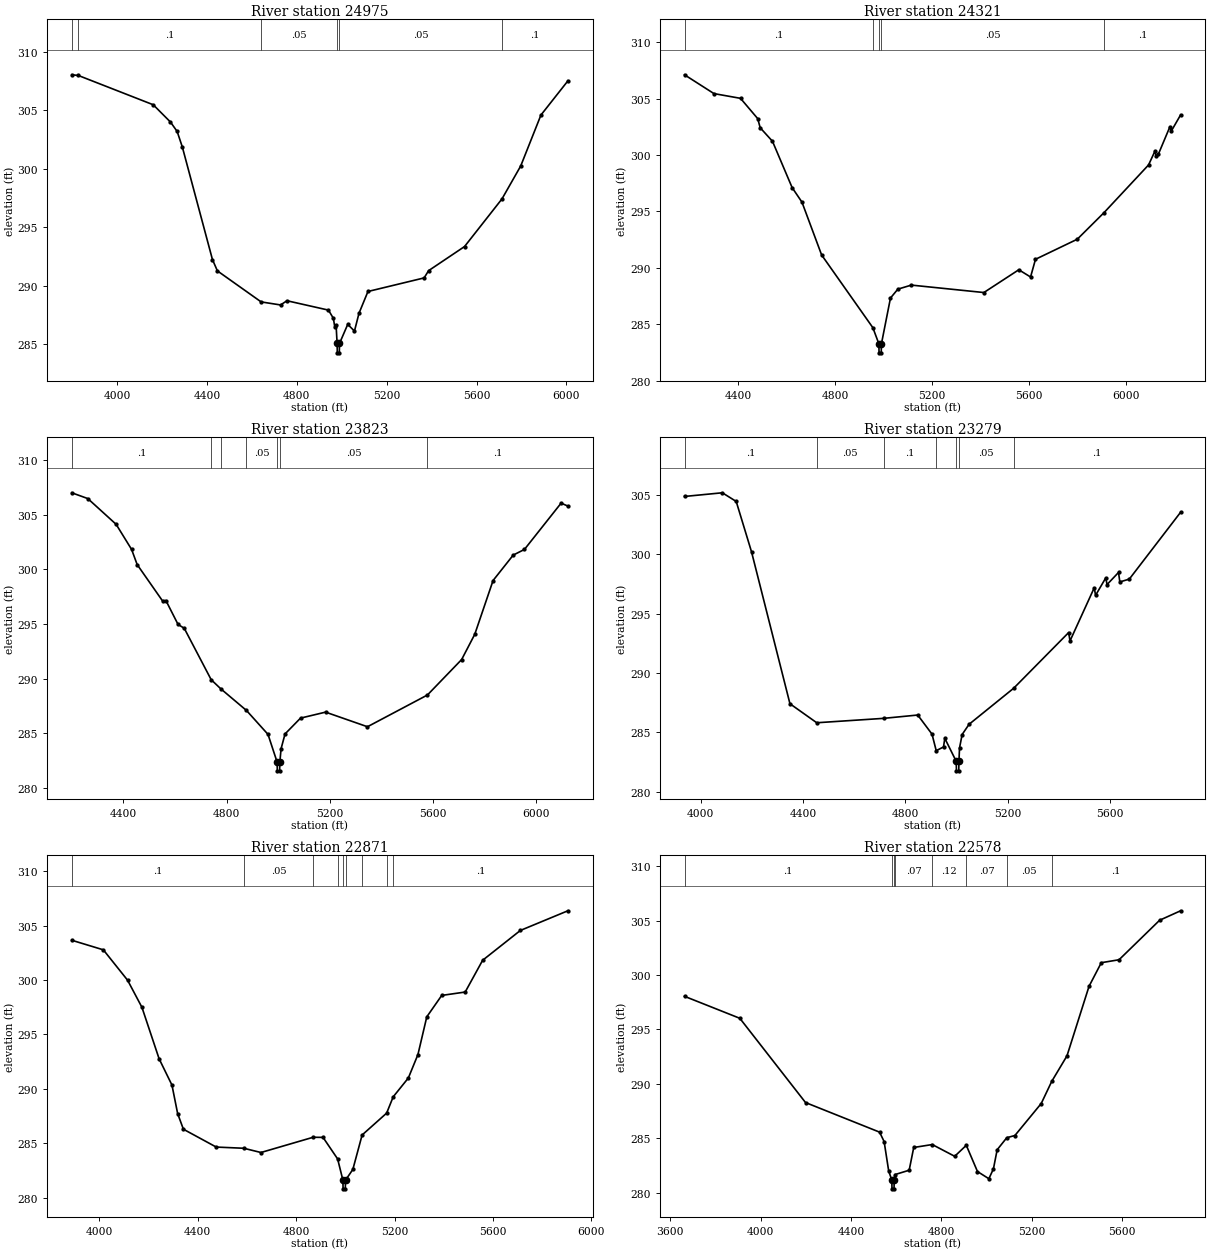
Type RM Length L Ch R = 1 ,24975   ,654,654,654
BEGIN DESCRIPTION:
Mustang Branch 33.0
END DESCRIPTION:
XS GIS Cut Line= 3
      2140224.99     13395175.01        2139125.       13395675.
      2138124.99       13395675.
#Sta/Elev= 30
  3798.1  308.03  3827.3  307.97  4160.6  305.47  4237.5  303.99  4267.1  303.19
  4290.2  301.86  4424.2  292.25  4446.2  291.28    4641  288.63  4727.4  288.37
  4755.9  288.73  4940.5  287.93  4962.5  287.23    4969  286.45  4974.5  286.68
  4979.1  285.08    4980  284.28  4988.9  284.28  4989.7  285.08  5026.4  286.71
  5056.4  286.14  5076.4  287.65  5116.4  289.52  5366.4  290.68  5386.4   291.3
  5546.4  293.36  5713.1  297.43  5796.4  300.24  5886.4  304.59  6006.4  307.51
#Mann= 6 ,-1 , 0
  3798.1     .05       0  3827.3      .1       0    4641     .05       0
  4979.1     .03       0  4989.7     .05       0  5713.1      .1       0
Bank Sta=4979.1,4989.7
XS Rating Curve= 0 ,0
Exp/Cntr=0.3,0.1

Type RM Length L Ch R = 1 ,24321   ,498,498,498
BEGIN DESCRIPTION:
Mapping XS 9ccb622b
END DESCRIPTION:
XS GIS Cut Line= 2
      2140092.84     13394981.14      2138074.63     13395306.66
#Sta/Elev= 30
  4179.3  307.13  4300.7  305.46  4410.1  305.04    4481  303.24  4491.2  302.43
  4541.8  301.23  4622.8  297.12  4663.3  295.83  4744.4  291.14  4955.5  284.69
  4980.2  283.26    4981  282.46  4989.9  282.46  4990.8  283.26    5028  287.32
  5058.4  288.11  5114.1  288.47  5412.9  287.81  5556.8  289.83  5605.3  289.19
  5625.6  290.76  5797.8  292.54  5908.1   294.9  6091.5  299.13  6117.9  300.36
    6123  299.88  6132.1  300.09  6179.7  302.53  6184.8  302.12  6223.6  303.57
#Mann= 5 ,-1 , 0
  4179.3      .1       0  4955.5     .05       0  4980.2     .03       0
  4990.8     .05       0  5908.1      .1       0
Bank Sta=4980.2,4990.8
XS Rating Curve= 0 ,0
Exp/Cntr=0.3,0.1

Type RM Length L Ch R = 1 ,23823   ,544,544,544
BEGIN DESCRIPTION:
Mapping XS 62a9c671
END DESCRIPTION:
XS GIS Cut Line= 2
      2139914.85     13394560.14      2138019.06     13394885.51
#Sta/Elev= 30
  4199.7  307.03  4261.7   306.5  4371.6  304.14  4431.6  301.84  4453.2  300.45
  4551.6  297.12  4564.8  297.15  4611.6  294.97  4635.8  294.61  4740.2   289.9
  4776.8  289.08  4877.1  287.08  4960.5  284.89  4995.8  282.35  4996.6  281.55
  5005.5  281.55  5006.4  282.35  5011.2  283.58  5026.5  284.93  5086.5  286.38
  5183.7  286.93  5346.1  285.59  5578.6   288.5  5711.3  291.75  5762.1  294.06
  5833.1  298.99  5911.2  301.32  5954.8  301.84  6096.9  306.08  6123.2  305.81
#Mann= 7 ,-1 , 0
  4199.7      .1       0  4740.2     .05       0  4776.8      .1       0
  4877.1     .05       0  4995.8    .035       0  5006.4     .05       0
  5578.6      .1       0
Bank Sta=4995.8,5006.4
XS Rating Curve= 0 ,0
Exp/Cntr=0.3,0.1

Type RM Length L Ch R = 1 ,23279   ,408,408,408
BEGIN DESCRIPTION:
Mapping XS 829534a7
END DESCRIPTION:
XS GIS Cut Line= 3
      2139736.94     13394317.09      2139281.19     13394295.38
      2137828.63      13394598.9
#Sta/Elev= 30
  3936.6  304.87  4084.6  305.18  4138.8  304.45  4198.8   300.2    4349  287.41
  4453.8  285.81    4715  286.18  4848.7  286.46  4904.6  284.85    4921  283.46
  4949.5  283.77  4954.6   284.5  4999.3  282.56  5000.1  281.76  5009.1  281.76
  5009.9  282.56  5012.2  283.69  5022.4  284.82  5049.5  285.68  5224.1  288.72
  5439.1  293.41  5444.2   292.7  5539.1  297.18  5544.2  296.54    5584  298.01
  5589.1  297.45    5634  298.47  5639.1  297.67  5676.2  297.91  5876.8  303.54
#Mann= 7 ,-1 , 0
  3936.6      .1       0  4453.8     .05       0    4715      .1       0
    4921     .05       0  4999.3    .035       0  5009.9     .05       0
  5224.1      .1       0
Bank Sta=4999.3,5009.9
XS Rating Curve= 0 ,0
Exp/Cntr=0.3,0.1

Type RM Length L Ch R = 1 ,22871   ,293,293,293
BEGIN DESCRIPTION:
Mapping XS 9ce6635e
END DESCRIPTION:
XS GIS Cut Line= 4
      2139702.19     13394234.61      2139172.69     13394000.24
      2138391.44     13394104.41       2137783.9     13394330.07
#Sta/Elev= 30
    3889  303.65  4017.2  302.77  4115.6  299.98  4173.9  297.49  4243.8  292.75
  4295.9  290.34  4319.1  287.71  4342.4  286.28  4475.8  284.64  4587.6  284.53
  4657.4  284.14  4869.4  285.54  4909.6  285.53  4968.9  283.55  4990.3   281.6
  4991.1   280.8  5000.1   280.8    5001   281.6  5030.7  282.58  5068.4  285.75
    5168  287.76  5194.7  289.26  5256.2  290.99  5295.1  293.14  5331.1  296.61
  5391.8  298.58  5487.1  298.89    5558  301.81  5711.1  304.55  5904.3  306.36
#Mann= 9 ,-1 , 0
    3889      .1       0  4587.6     .05       0  4869.4     .07       0
  4968.9     .05       0  4990.3    .035       0    5001     .05       0
  5068.4     .12       0    5168     .05       0  5194.7      .1       0
Bank Sta=4990.3,5001
XS Rating Curve= 0 ,0
Exp/Cntr=0.3,0.1

Type RM Length L Ch R = 1 ,22578   ,605,605,605
BEGIN DESCRIPTION:
Mapping XS 522f920d
END DESCRIPTION:
XS GIS Cut Line= 3
      2139984.33     13393518.47      2139237.79     13393709.45
      2137822.83     13393896.08
#Sta/Elev= 30
  3662.6  298.04  3907.7  296.02  4198.7  288.28  4526.8  285.56    4547  284.69
  4567.1     282    4581  281.15  4581.8  280.35  4590.8  280.35  4591.7  281.15
  4594.9  281.66  4657.9  282.06  4678.1  284.15  4760.2  284.42  4859.6  283.34
    4911  284.35  4960.5  281.94  5010.9  281.28  5031.1  282.18  5047.7  283.94
  5090.4  285.05  5126.3  285.25  5242.9  288.19  5289.4  290.22    5357  292.57
  5454.7  298.96  5509.1  301.13  5587.7   301.4  5767.4  305.03  5860.4   305.9
#Mann= 8 ,-1 , 0
  3662.6      .1       0    4581     .07       0  4591.7      .1       0
  4594.9     .07       0  4760.2     .12       0    4911     .07       0
  5090.4     .05       0  5289.4      .1       0
Bank Sta=4581,4591.7
XS Rating Curve= 0 ,0
Exp/Cntr=0.3,0.1

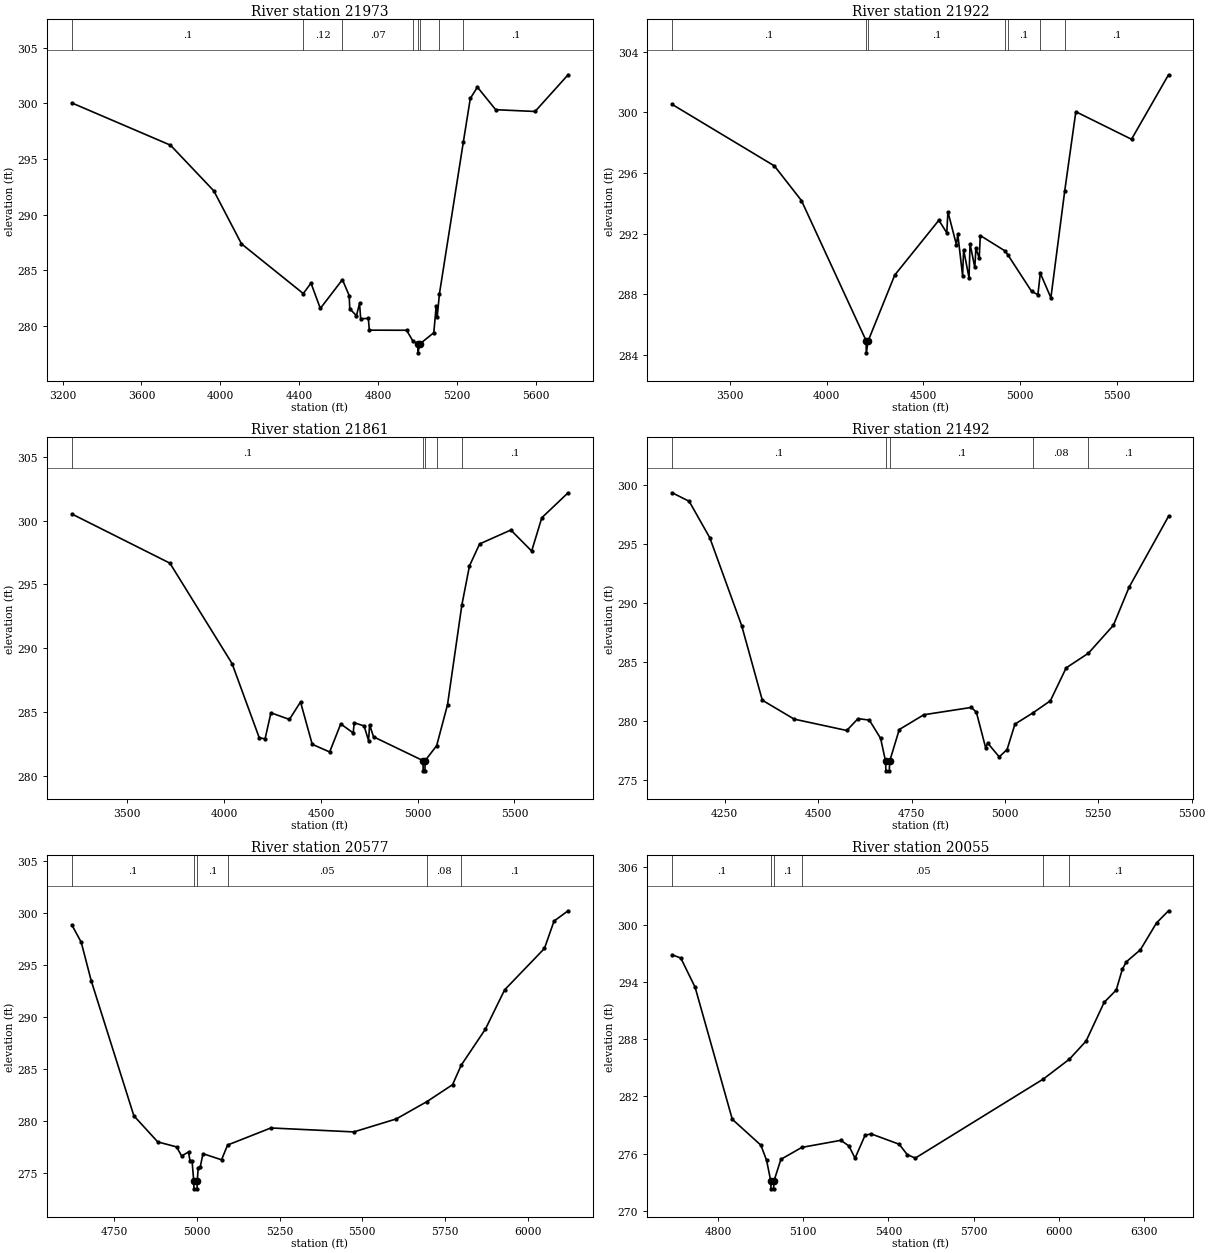
Type RM Length L Ch R = 1 ,21973   ,51,51,51
BEGIN DESCRIPTION:
Mapping XS a1f0a121
END DESCRIPTION:
XS GIS Cut Line= 6
      2140205.64     13393483.75      2138834.14     13393501.11
      2138751.68     13393414.31      2138703.94      13393262.4
      2138664.87     13393249.38      2137888.97     13393505.09
#Sta/Elev= 30
  3246.6  300.05  3747.3  296.25  3967.3  292.14  4107.4  287.38    4421  282.91
  4460.1  283.85  4507.5  281.57  4619.5  284.16  4653.9  282.73  4656.9  281.54
  4690.7  280.92  4706.4  282.02  4712.2  280.65    4751  280.67  4756.1  279.62
  4945.1  279.61  4977.8  278.62  5001.7  278.38  5002.6  277.58  5012.5  278.38
  5083.2  279.39  5095.2  281.79  5100.5  280.82  5111.8   282.9  5233.3  296.57
  5268.3  300.45  5304.4  301.47  5397.1  299.44  5596.8  299.28  5764.4  302.58
#Mann= 8 ,-1 , 0
  3246.6      .1       0    4421     .12       0  4619.5     .07       0
  4977.8      .1       0  5001.7     .07       0  5012.5      .1       0
  5111.8     .08       0  5233.3      .1       0
Bank Sta=5001.7,5012.5
XS Rating Curve= 0 ,0
Exp/Cntr=0.3,0.1

Type RM Length L Ch R = 1 ,21922   ,61,61,61
BEGIN DESCRIPTION:
Mapping XS 1c8dcce6
END DESCRIPTION:
XS GIS Cut Line= 6
      2140253.45     13393440.35      2138834.14     13393422.99
      2138751.68     13393227.67      2138695.26     13393192.95
      2138525.98     13393223.33      2137889.01       13393479.
#Sta/Elev= 30
  3200.4  300.53  3728.9  296.47  3868.9  294.18  4203.5  284.92  4204.3  284.12
  4214.3  284.92  4351.6  289.26  4579.7  292.88  4620.6  292.05  4626.6  293.44
  4670.3  291.27  4677.7  291.95  4702.5  289.21  4707.7  290.94  4735.8  289.07
    4741  291.32  4765.7  289.76  4771.2  291.03  4788.5  290.37    4794  291.87
  4922.2  290.85  4937.3  290.58  5059.4  288.18  5091.9  287.96  5104.5  289.38
  5159.2  287.76    5231  294.84  5288.2  300.05  5576.2  298.23  5767.6  302.49
#Mann= 7 ,-1 , 0
  3200.4      .1       0  4203.5     .07       0  4214.3      .1       0
  4922.2     .07       0  4937.3      .1       0  5104.5     .08       0
    5231      .1       0
Bank Sta=4203.5,4214.3
XS Rating Curve= 0 ,0
Exp/Cntr=0.3,0.1

Type RM Length L Ch R = 1 ,21861   ,369,369,369
BEGIN DESCRIPTION:
Mapping XS f79548a5
END DESCRIPTION:
XS GIS Cut Line= 6
      2140240.36      13393392.6      2139229.11     13393310.14
      2138855.85     13393344.86      2138769.04     13393145.21
      2138664.87     13393136.53      2137883.65     13393453.36
#Sta/Elev= 30
  3212.9  300.52  3719.9  296.66    4041  288.79  4181.5  282.97  4211.6  282.89
  4241.8  284.93  4337.4  284.41  4394.7  285.78  4455.2  282.46  4545.3  281.86
  4602.5  284.06  4666.9  283.35    4672  284.15  4723.3   283.9  4746.3  282.75
  4751.6  283.99  4771.8  283.05  5027.6  281.18  5028.5  280.38  5037.6  280.38
  5038.4  281.18  5098.1  282.35  5154.3  285.57  5228.3  293.38  5267.7  296.45
  5320.1  298.17  5481.4  299.26    5589  297.61  5641.3  300.22  5777.2  302.18
#Mann= 5 ,-1 , 0
  3212.9      .1       0  5027.6     .07       0  5038.4      .1       0
  5098.1     .08       0  5228.3      .1       0
Bank Sta=5027.6,5038.4
XS Rating Curve= 0 ,0
Exp/Cntr=0.3,0.1

Type RM Length L Ch R = 1 ,21492   ,915,915,915
BEGIN DESCRIPTION:
Mustang Branch 26.0
END DESCRIPTION:
XS GIS Cut Line= 3
      2139425.01       13392475.        2138625.       13392775.
      2138174.95     13392925.02
#Sta/Elev= 30
  4109.2  299.31  4154.6  298.59  4209.8  295.51  4295.2  288.08  4350.4  281.78
  4435.8  280.18  4576.5  279.22  4606.7  280.22    4637   280.1  4667.2  278.55
  4680.5  276.61  4681.3  275.81  4690.5  275.81  4691.3  276.61  4717.1   279.3
  4782.9  280.55  4910.2  281.17  4923.6  280.76  4948.5  277.75  4953.8  278.16
  4984.7  276.99  5005.8  277.61  5026.9  279.76  5076.5  280.74  5121.7  281.73
  5163.9  284.51  5223.5  285.75  5290.4  288.11  5332.5  291.33    5438  297.32
#Mann= 5 ,-1 , 0
  4109.2      .1       0  4680.5     .07       0  4691.3      .1       0
  5076.5     .08       0  5223.5      .1       0
Bank Sta=4680.5,4691.3
XS Rating Curve= 0 ,0
Exp/Cntr=0.3,0.1

Type RM Length L Ch R = 1 ,20577   ,522,522,522
BEGIN DESCRIPTION:
Mustang Branch 25.0
END DESCRIPTION:
XS GIS Cut Line= 3
      2139174.96     13391875.03        2138875.       13392075.
      2137974.99     13392775.01
#Sta/Elev= 30
  4621.5  298.88    4650  297.21    4680  293.53  4809.2  280.53  4881.4  278.02
  4938.4  277.54  4953.5  276.67  4974.5  277.05    4979  276.19  4985.2  276.19
  4990.1  274.31  4990.9  273.51  5000.2  273.51    5001  274.31  5003.7   275.5
  5010.1  275.64  5018.2  276.89  5074.3   276.3  5092.6  277.72  5223.6  279.36
  5474.3  278.98  5602.8  280.23  5695.7   281.9  5772.9  283.52  5798.8  285.38
  5872.4  288.87  5930.3  292.63  6050.7  296.61  6079.7  299.24  6122.2  300.23
#Mann= 6 ,-1 , 0
  4621.5      .1       0  4990.1     .07       0    5001      .1       0
  5092.6     .05       0  5695.7     .08       0  5798.8      .1       0
Bank Sta=4990.1,5001
XS Rating Curve= 0 ,0
Exp/Cntr=0.3,0.1

Type RM Length L Ch R = 1 ,20055   ,274,274,274
BEGIN DESCRIPTION:
Mustang Branch 24.0
END DESCRIPTION:
XS GIS Cut Line= 3
      2139125.03       13391675.        2138725.       13391725.
        2137725.       13392625.
#Sta/Elev= 30
  4638.3  296.83  4668.6  296.49    4719  293.43    4850  279.61  4950.7   276.9
  4970.9   275.3  4985.6  273.13  4986.4  272.33  4995.7  272.33  4996.5  273.13
  5021.3  275.42    5095  276.67  5232.4  277.41  5260.8  276.82  5282.5  275.54
  5317.6  277.93  5338.5  278.09  5437.9     277  5466.4  275.91  5494.8  275.55
    5946  283.83  6037.9  285.91  6096.4   287.8    6160  291.85  6202.6  293.14
  6224.2  295.33  6238.4   296.1  6287.8  297.36  6344.6  300.17  6386.8  301.44
#Mann= 6 ,-1 , 0
  4638.3      .1       0  4985.6     .07       0  4996.5      .1       0
    5095     .05       0    5946     .08       0  6037.9      .1       0
Bank Sta=4985.6,4996.5
XS Rating Curve= 0 ,0
Exp/Cntr=0.3,0.1

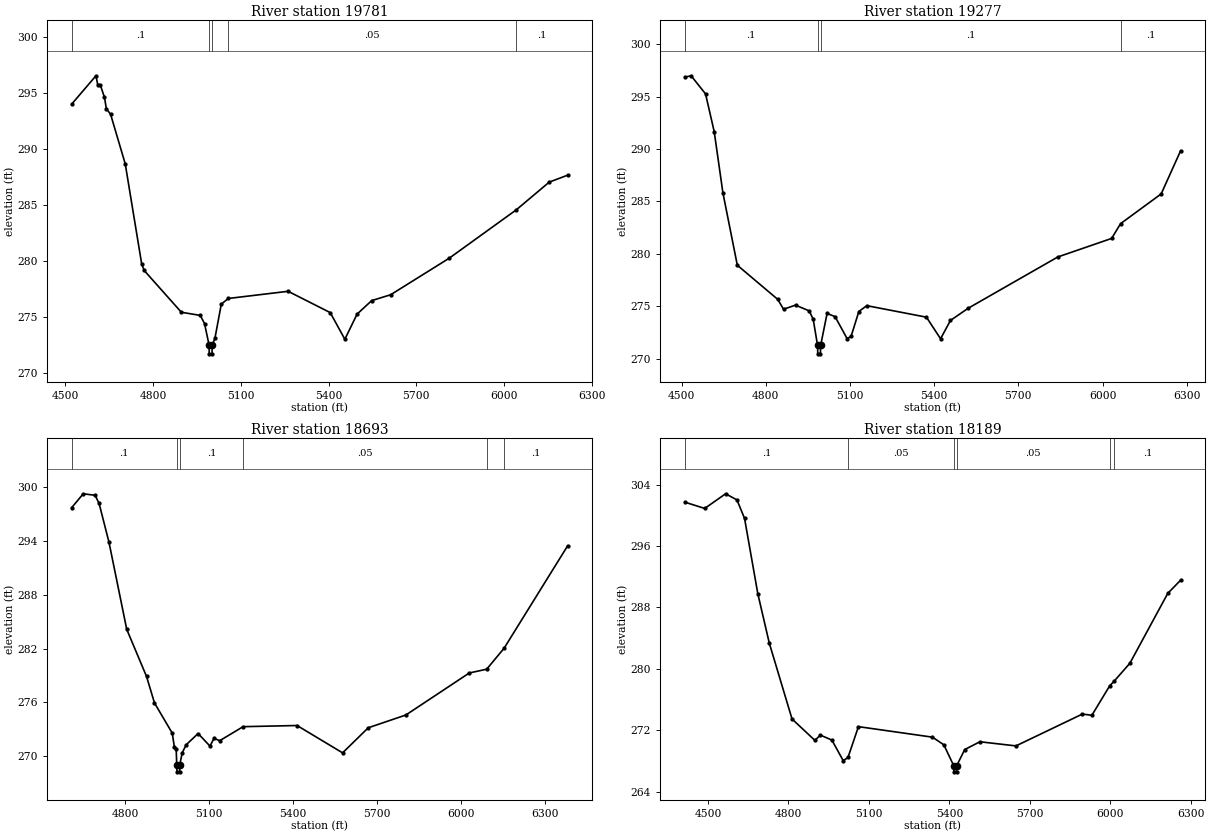
Type RM Length L Ch R = 1 ,19781   ,504,504,504
BEGIN DESCRIPTION:
Mapping XS 8a49fc61
END DESCRIPTION:
XS GIS Cut Line= 2
      2138955.71     13391270.18       2137593.8     13392280.77
#Sta/Elev= 30
  4521.6  294.02  4604.3  296.54  4610.5  295.73  4618.9  295.74  4633.5  294.61
  4639.8  293.61  4654.4   293.1  4704.5  288.68  4760.8  279.74  4769.2  279.17
  4896.4  275.44  4961.1  275.16  4975.7  274.43  4991.1  272.53  4991.8  271.73
  5001.2  271.73    5002  272.53  5011.1   273.1    5033  276.16  5056.8  276.67
  5261.5  277.31  5405.5  275.41  5455.6  273.03  5497.3  275.27  5547.4  276.48
  5612.1     277  5812.4  280.26    6042  284.58  6154.5  287.05  6217.5  287.67
#Mann= 5 ,-1 , 0
  4521.6      .1       0  4991.1     .07       0    5002      .1       0
  5056.8     .05       0    6042      .1       0
Bank Sta=4991.1,5002
XS Rating Curve= 0 ,0
Exp/Cntr=0.3,0.1

Type RM Length L Ch R = 1 ,19277   ,584,584,584
BEGIN DESCRIPTION:
Mapping XS 0cd1829b
END DESCRIPTION:
XS GIS Cut Line= 3
      2138716.98     13391100.93      2138339.35     13391192.08
      2137302.01     13392099.22
#Sta/Elev= 30
  4511.6  296.87  4534.2     297  4585.6  295.27  4616.5  291.66  4647.4  285.83
  4698.8  278.91  4842.8  275.65  4863.4  274.71  4906.1   275.1    4955  274.55
  4969.2  273.74  4984.7  271.25  4985.4  270.45  4994.8  270.45  4995.6  271.25
  5018.6  274.31  5047.1     274  5089.8  271.91    5104  272.11  5131.7  274.49
    5160  275.05  5372.6  273.95  5422.9  271.89  5458.1  273.64  5521.7  274.81
  5840.6   279.7  6032.3  281.47  6064.2  282.88  6208.8  285.72  6278.1  289.84
#Mann= 4 ,-1 , 0
  4511.6      .1       0  4984.7    .035       0  4995.6      .1       0
  6064.2      .1       0
Bank Sta=4984.7,4995.6
XS Rating Curve= 0 ,0
Exp/Cntr=0.3,0.1

Type RM Length L Ch R = 1 ,18693   ,504,504,504
BEGIN DESCRIPTION:
Mapping XS a7843169
END DESCRIPTION:
XS GIS Cut Line= 2
      2138261.26     13390623.47      2137050.32     13391916.88
#Sta/Elev= 30
  4609.8  297.67  4650.8   299.2  4693.3  299.03  4707.5  298.12  4742.7  293.82
  4806.2  284.13    4877  278.89  4905.3  275.95  4968.9  272.59  4976.2  271.09
    4983  270.78  4984.8  269.09  4985.6  268.29  4995.1  268.29  4995.8  269.09
  5004.5  270.41  5018.7   271.3  5061.2  272.55  5103.7  271.15  5117.8     272
  5138.8  271.76    5222  273.31  5414.8  273.44  5577.5   270.4  5669.3  273.19
  5803.7  274.61  6030.3  279.28  6092.4   279.7  6154.6  282.03  6381.6  293.41
#Mann= 6 ,-1 , 0
  4609.8      .1       0  4984.8     .07       0  4995.8      .1       0
    5222     .05       0  6092.4     .08       0  6154.6      .1       0
Bank Sta=4984.8,4995.8
XS Rating Curve= 0 ,0
Exp/Cntr=0.3,0.1

Type RM Length L Ch R = 1 ,18189   ,490,490,490
BEGIN DESCRIPTION:
Mapping XS 6fbd01ed
END DESCRIPTION:
XS GIS Cut Line= 2
      2138022.54     13390367.41      2136711.75     13391669.51
#Sta/Elev= 30
  4413.9  301.73  4488.2  300.91    4566  302.82  4608.4  302.02  4636.7   299.6
  4686.2  289.77  4728.7  283.37  4813.5  273.47  4898.4  270.69  4919.6  271.36
    4962  270.72  5004.4  268.03    5022  268.45    5061  272.47  5336.8   271.1
  5379.2   270.1  5416.1  267.38  5416.9  266.58  5426.4  266.58  5427.1  267.38
    5457  269.48  5513.5   270.5  5647.9  269.96  5895.4  274.11  5930.8  273.95
    5997  277.78  6013.6  278.39  6072.2  280.72  6213.6  289.84  6261.5  291.56
#Mann= 6 ,-1 , 0
  4413.9      .1       0    5022     .05       0  5416.1     .07       0
  5427.1     .05       0    5997     .08       0  6013.6      .1       0
Bank Sta=5416.1,5427.1
XS Rating Curve= 0 ,0
Exp/Cntr=0.3,0.1