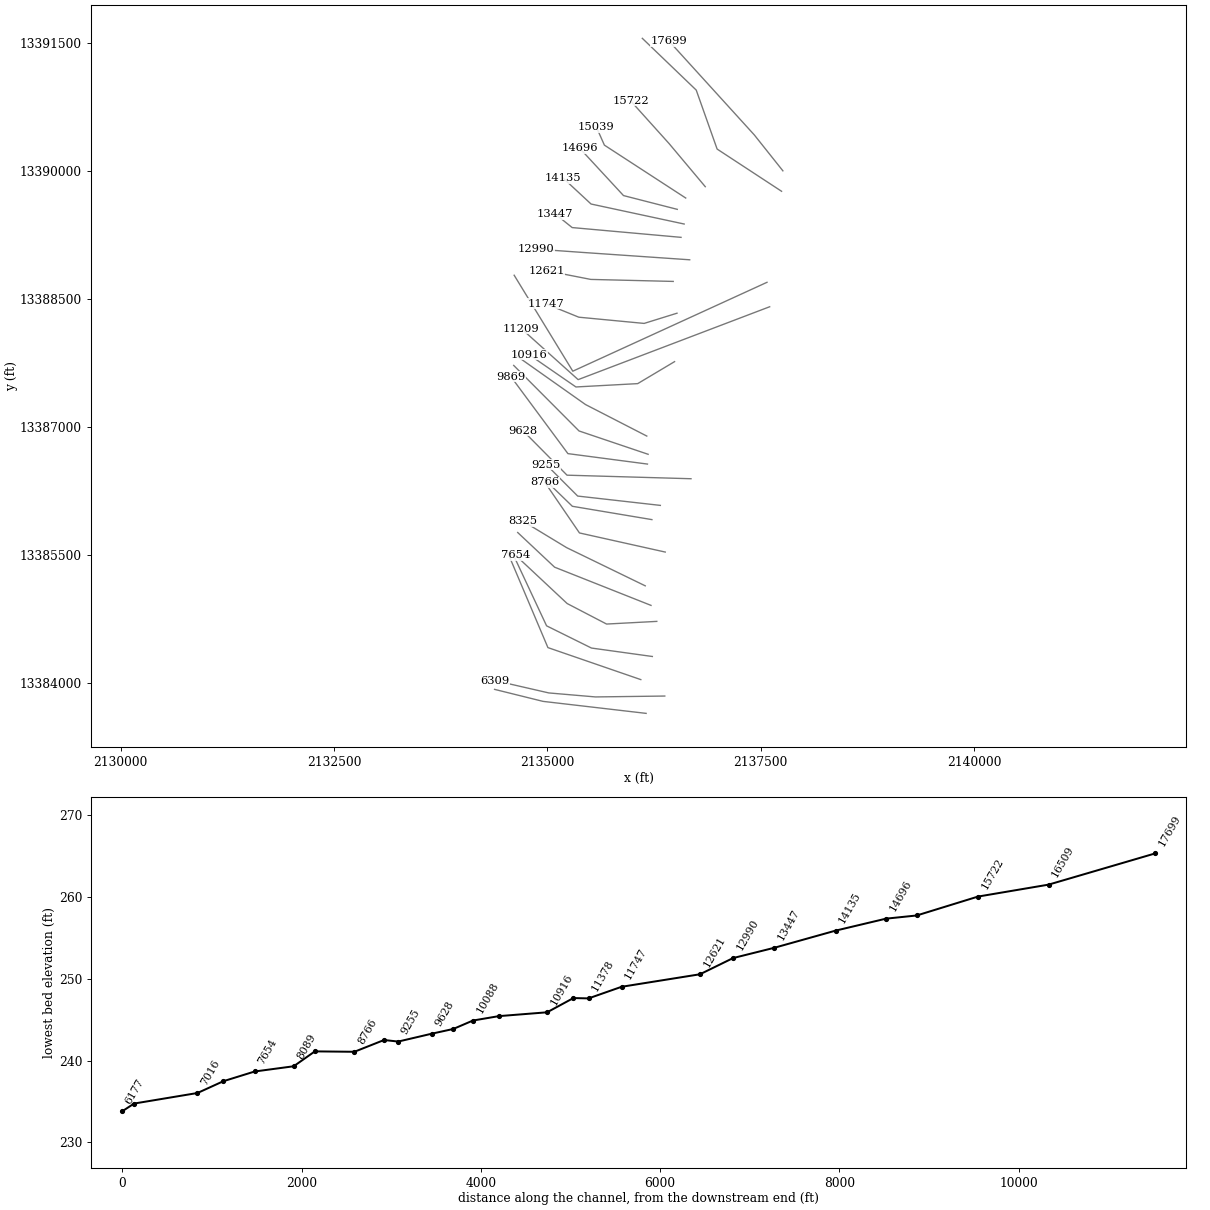
HEC-RAS study Mustang Branch.prj: Mustang Branch Base Level Engineering

--- Mustang Branch.g01 (geometry) --- (continued)

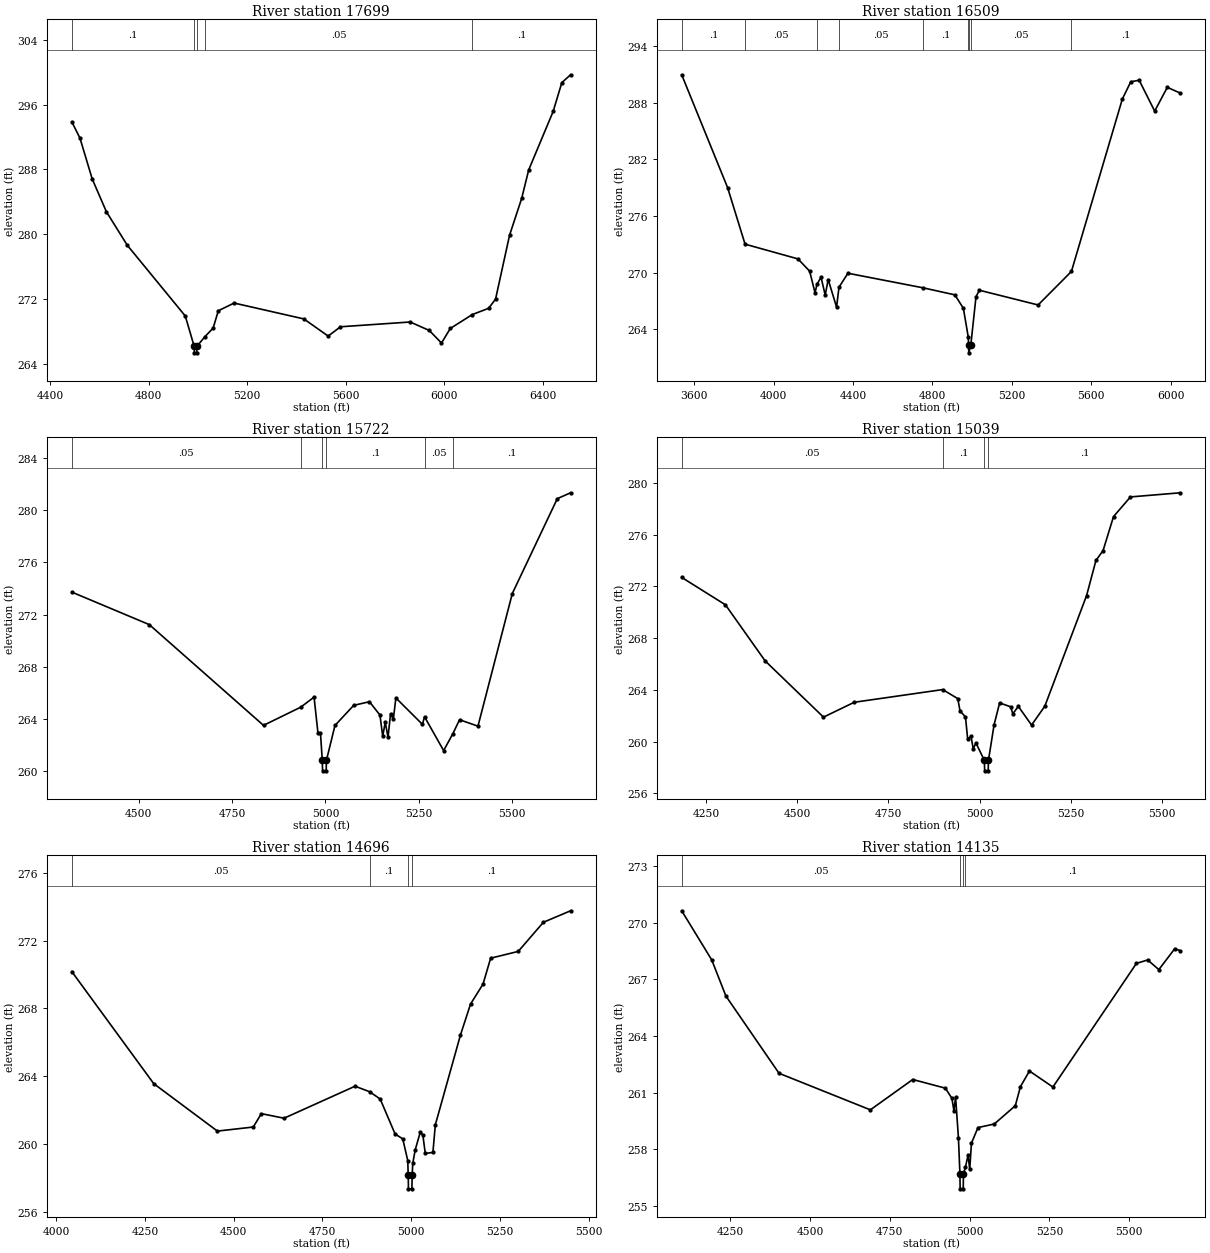
Type RM Length L Ch R = 1 ,17699   ,1190,1190,1190
BEGIN DESCRIPTION:
Mustang Branch 19.0
END DESCRIPTION:
XS GIS Cut Line= 3
      2137760.35     13390003.73        2137425.       13390425.
      2136424.97     13391525.03
#Sta/Elev= 30
  4487.7  293.87  4520.8  291.86  4570.5  286.82  4628.2  282.76    4713  278.62
  4948.5  269.88  4984.6  266.13  4985.4  265.33  4994.9  265.33  4995.6  266.13
  5027.1  267.29  5061.6  268.39  5082.6  270.53  5146.8  271.48  5429.9  269.52
  5528.6   267.4  5578.6  268.55  5861.7  269.14  5939.4  268.09  5988.7  266.54
  6024.5  268.34  6113.9  270.06    6180  270.83  6208.3  271.97  6265.1  279.86
  6314.4  284.42  6342.8  287.93  6442.1  295.15  6477.3  298.71  6512.8  299.68
#Mann= 5 ,-1 , 0
  4487.7      .1       0  4984.6     .07       0  4995.6      .1       0
  5027.1     .05       0  6113.9      .1       0
Bank Sta=4984.6,4995.6
XS Rating Curve= 0 ,0
Exp/Cntr=0.3,0.1

Type RM Length L Ch R = 1 ,16509   ,787,787,787
BEGIN DESCRIPTION:
Mapping XS f81a363b
END DESCRIPTION:
XS GIS Cut Line= 4
      2137744.77     13389764.11      2136989.53     13390258.92
      2136744.73      13390949.9      2136112.82     13391556.64
#Sta/Elev= 30
  3537.5  290.96  3768.8     279  3856.6  273.02    4123  271.46  4181.9  270.16
  4208.9  267.88  4218.9  268.76  4239.1  269.53  4260.2  267.63  4275.3  269.27
  4317.5  266.35  4329.7  268.46  4374.7  269.94  4754.6  268.39  4913.2  267.65
  4956.1  266.23  4980.5  263.21  4982.4  262.31  4983.2  261.51  4993.4  262.31
  5019.7  267.45  5036.8  268.14  5332.5  266.58  5500.3  270.13  5756.7  288.39
  5799.2  290.22  5841.6  290.38  5919.6  287.11  5983.1  289.63  6049.5  289.01
#Mann= 9 ,-1 , 0
  3537.5      .1       0  3856.6     .05       0  4218.9      .1       0
  4329.7     .05       0  4754.6      .1       0  4980.5     .05       0
  4982.4     .03       0  4993.4     .05       0  5500.3      .1       0
Bank Sta=4982.4,4993.4
XS Rating Curve= 0 ,0
Exp/Cntr=0.3,0.1

Type RM Length L Ch R = 1 ,15722   ,683,683,683
BEGIN DESCRIPTION:
Mustang Branch 18.0
END DESCRIPTION:
XS GIS Cut Line= 3
      2136850.62     13389817.97        2136425.       13390325.
      2135974.98     13390825.02
#Sta/Elev= 30
  4321.2  273.73  4528.6  271.24  4834.2  263.53  4933.7  264.92  4969.5  265.69
  4979.9  262.96  4986.6  262.96  4991.5  260.85  4992.2  260.05  5001.9  260.05
  5002.6  260.85  5025.4  263.52  5075.5  265.06  5117.7  265.34  5145.8  264.32
  5153.2   262.7    5160  263.77  5167.4  262.62  5174.2  264.42  5181.6  263.99
  5188.4  265.63  5259.4  263.61  5265.1  264.19  5316.2   261.6  5340.9  262.89
  5358.8  263.96  5408.1  263.47    5500  273.62  5620.4  280.88  5655.9  281.33
#Mann= 6 ,-1 , 0
  4321.2     .05       0  4933.7      .1       0  4991.5     .07       0
  5002.6      .1       0  5265.1     .05       0  5340.9      .1       0
Bank Sta=4991.5,5002.6
XS Rating Curve= 0 ,0
Exp/Cntr=0.3,0.1

Type RM Length L Ch R = 1 ,15039   ,343,343,343
BEGIN DESCRIPTION:
Mapping XS 702956de
END DESCRIPTION:
XS GIS Cut Line= 3
      2136621.45     13389685.15      2135668.35     13390304.93
      2135574.61     13390515.84
#Sta/Elev= 30
  4183.2  272.69  4303.2  270.57  4411.9  266.24    4572  261.89  4656.4  263.04
  4898.9  264.02  4940.3  263.32  4946.3  262.38  4961.4   261.9  4967.4  260.18
  4976.5  260.42  4982.5  259.45  4990.1  259.89  5013.2  258.54  5013.9  257.74
  5023.6  257.74  5024.3  258.54  5039.8   261.3    5055  262.99  5085.2  262.69
  5091.2  262.15  5106.3  262.72  5142.6  261.28  5178.8  262.73  5293.5  271.29
  5319.1     274  5338.6  274.76  5367.3  277.39  5413.8  278.91  5550.9  279.23
#Mann= 4 ,-1 , 0
  4183.2     .05       0  4898.9      .1       0  5013.2     .07       0
  5024.3      .1       0
Bank Sta=5013.2,5024.3
XS Rating Curve= 0 ,0
Exp/Cntr=0.3,0.1

Type RM Length L Ch R = 1 ,14696   ,561,561,561
BEGIN DESCRIPTION:
Mapping XS 99ed8910
END DESCRIPTION:
XS GIS Cut Line= 3
      2136522.47     13389552.34       2135892.3     13389713.79
      2135379.67     13390268.05
#Sta/Elev= 30
  4043.6  270.18  4274.6  263.56  4453.9  260.76    4555     261  4577.8  261.79
  4641.7  261.52  4841.8  263.41  4883.4  263.08  4912.7  262.65  4954.6  260.59
  4976.2   260.3  4990.3  259.02  4991.6  258.15  4992.3  257.35    5002  257.35
  5002.7  258.15  5004.5  258.86  5011.3  259.65  5025.5  260.69  5032.9  260.52
  5039.7  259.44  5061.2   259.5    5068  261.13  5138.9  266.44  5167.2  268.26
  5202.4  269.44  5223.9  270.97  5301.6  271.37  5372.5  273.09  5449.1  273.77
#Mann= 4 ,-1 , 0
  4043.6     .05       0  4883.4      .1       0  4991.6     .07       0
  5002.7      .1       0
Bank Sta=4991.6,5002.7
XS Rating Curve= 0 ,0
Exp/Cntr=0.3,0.1

Type RM Length L Ch R = 1 ,14135   ,688,688,688
BEGIN DESCRIPTION:
Mapping XS 30ef8fe3
END DESCRIPTION:
XS GIS Cut Line= 3
      2136603.27     13389380.45       2135512.1     13389614.83
        2135184.     13389919.49
#Sta/Elev= 30
  4097.4  270.64  4191.7  268.03  4235.9  266.12  4402.5  262.02  4688.9  260.08
  4821.8  261.69  4924.1  261.23  4944.6  260.69    4951  260.02  4956.1  260.76
    4965   258.6  4969.7  256.69  4970.4  255.89  4980.1  255.89  4980.8  256.69
  4987.1  257.04  4995.3  257.69  5000.4  256.92  5005.9  258.32  5026.4  259.14
  5077.5  259.33  5143.4   260.3  5159.4  261.31  5187.7  262.14  5261.2  261.29
  5523.1  267.85  5558.3  268.03  5593.4  267.52  5643.3  268.63  5661.2  268.52
#Mann= 4 ,-1 , 0
  4097.4     .05       0  4969.7     .07       0  4980.8     .05       0
  4987.1      .1       0
Bank Sta=4969.7,4980.8
XS Rating Curve= 0 ,0
Exp/Cntr=0.3,0.1

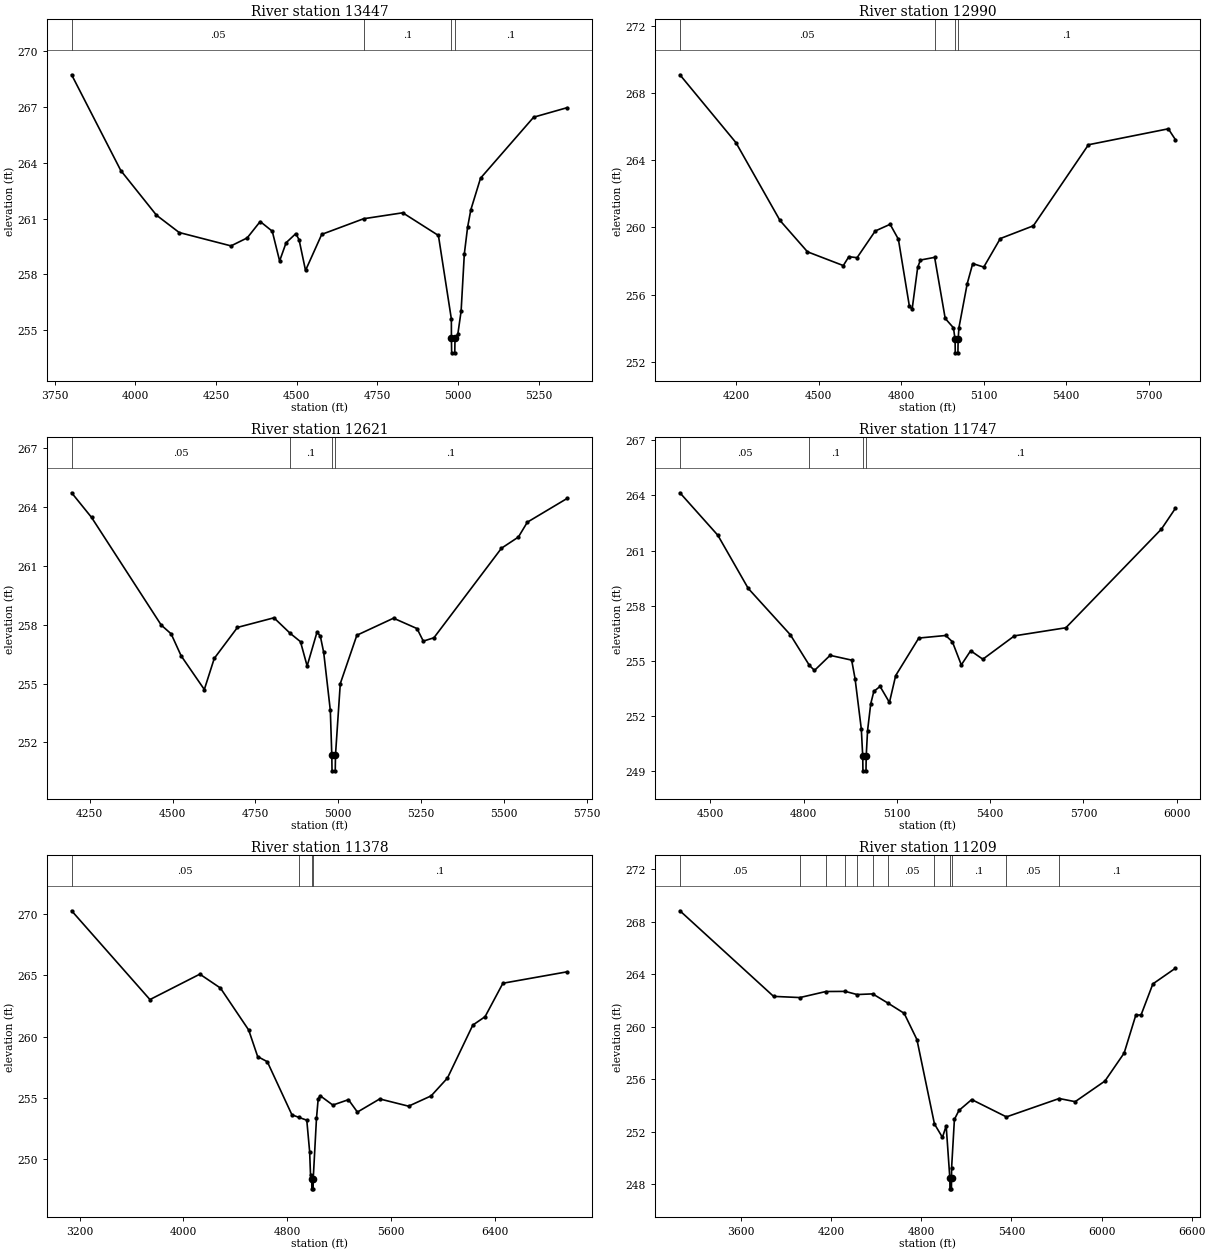
Type RM Length L Ch R = 1 ,13447   ,457,457,457
BEGIN DESCRIPTION:
Mapping XS 9e333a5b
END DESCRIPTION:
XS GIS Cut Line= 3
      2136566.83      13389224.2      2135290.74     13389338.79
      2135092.83     13389497.64
#Sta/Elev= 30
  3802.4  268.73  3954.8  263.58  4065.3  261.18  4135.6  260.25  4296.2  259.53
  4346.4  259.96  4386.6  260.84    4424  260.32  4446.8  258.72  4466.9   259.7
    4497  260.19  4507.1  259.86  4527.1  258.21  4577.3  260.15  4707.1  260.99
  4828.3  261.31  4938.8  260.09  4978.9   255.6  4979.1  254.58  4979.8  253.78
  4989.5  253.78  4990.2  254.58    4999  254.79  5009.1  256.02  5019.1   259.1
  5029.1  260.52  5039.2  261.47  5069.3  263.17  5233.9  266.45  5337.4  266.96
#Mann= 4 ,-1 , 0
  3802.4     .05       0  4707.1      .1       0  4979.1     .07       0
  4990.2      .1       0
Bank Sta=4979.1,4990.2
XS Rating Curve= 0 ,0
Exp/Cntr=0.3,0.1

Type RM Length L Ch R = 1 ,12990   ,369,369,369
BEGIN DESCRIPTION:
Mapping XS f7189c47
END DESCRIPTION:
XS GIS Cut Line= 3
      2136668.32     13388961.18      2135418.35     13389047.12
      2134869.46     13389086.14
#Sta/Elev= 30
  3994.5   269.1  4198.3  265.06  4358.7  260.42  4458.9  258.55  4589.2  257.73
  4609.3  258.26  4639.3   258.2  4705.4  259.79  4759.6  260.19  4789.7   259.3
  4829.8   255.3  4839.8  255.14  4859.9  257.62  4869.9  258.06  4921.6  258.22
  4960.1  254.58  4990.2  254.02    4996  253.33  4996.7  252.53  5006.4  252.53
  5007.1  253.33  5010.2  254.04  5040.3  256.66  5060.3  257.85  5100.4  257.64
  5160.6  259.34  5280.9   260.1  5481.4  264.93  5772.1  265.88  5797.7  265.24
#Mann= 4 ,-1 , 0
  3994.5     .05       0  4921.6      .1       0    4996     .07       0
  5007.1      .1       0
Bank Sta=4996,5007.1
XS Rating Curve= 0 ,0
Exp/Cntr=0.3,0.1

Type RM Length L Ch R = 1 ,12621   ,874,874,874
BEGIN DESCRIPTION:
Mapping XS 70bf3f99
END DESCRIPTION:
XS GIS Cut Line= 3
      2136475.16     13388707.71      2135509.06     13388731.15
       2134990.8     13388832.71
#Sta/Elev= 30
  4195.4  264.74  4255.6  263.48  4465.6  257.99  4495.6  257.54  4525.7  256.42
  4595.7   254.7  4625.7  256.29  4695.7  257.87  4805.7  258.36  4854.5  257.57
  4885.8  257.14  4905.8   255.9  4935.8  257.64  4945.8  257.41  4955.8  256.59
  4975.8  253.63  4980.2  251.35  4980.9  250.55  4990.6  250.55  4991.3  251.35
  5005.8     255  5055.8  257.47  5166.4  258.34  5237.3  257.81  5256.2  257.17
  5288.2  257.34    5492  261.91    5543  262.48  5570.1  263.24  5689.9  264.45
#Mann= 4 ,-1 , 0
  4195.4     .05       0  4854.5      .1       0  4980.2     .07       0
  4991.3      .1       0
Bank Sta=4980.2,4991.3
XS Rating Curve= 0 ,0
Exp/Cntr=0.3,0.1

Type RM Length L Ch R = 1 ,11747   ,369,369,369
BEGIN DESCRIPTION:
Mapping XS a6a66035
END DESCRIPTION:
XS GIS Cut Line= 4
      2136519.44      13388335.3      2136134.06     13388215.52
      2135368.43     13388288.44      2134978.87     13388446.86
#Sta/Elev= 30
  4402.3  264.14  4524.3  261.83    4622  258.94  4757.4  256.42  4818.5  254.76
  4835.1  254.48  4885.3   255.3  4954.6  255.04  4965.6  254.03  4985.7  251.29
  4990.2  249.82  4990.9  249.02  5000.7  249.02  5001.4  249.82  5005.8  251.21
  5015.9  252.66  5025.9  253.34    5046  253.61  5076.1  252.74  5096.2   254.2
  5170.5  256.24    5257  256.38  5278.5  256.04  5307.2  254.78  5337.3  255.55
  5376.5  255.09    5478  256.36  5643.4   256.8  5950.9  262.17  5995.5  263.29
#Mann= 4 ,-1 , 0
  4402.3     .05       0  4818.5      .1       0  4990.2     .07       0
  5001.4      .1       0
Bank Sta=4990.2,5001.4
XS Rating Curve= 0 ,0
Exp/Cntr=0.3,0.1

Type RM Length L Ch R = 1 ,11378   ,169,169,169
BEGIN DESCRIPTION:
Mustang Branch 15.0
END DESCRIPTION:
XS GIS Cut Line= 3
      2137574.18      13388697.3      2135298.12     13387655.63
       2134610.8     13388780.33
#Sta/Elev= 30
  3137.7  270.24  3741.7  263.01  4126.6  265.08  4285.3  263.95  4503.4  260.53
  4572.5  258.37    4647  257.95  4836.6  253.63    4890  253.42  4951.4  253.19
  4973.4  250.63  4980.2  248.73  4989.8   248.4  4990.5   247.6  5000.3   247.6
    5001   248.4  5026.2  253.34  5039.4  254.93  5054.7  255.18  5152.3  254.42
  5272.8  254.86  5341.9  253.85    5514  254.92  5736.4  254.33  5910.6  255.17
  6036.3  256.62  6231.8  260.93  6326.6  261.62  6464.1  264.34  6958.9  265.27
#Mann= 4 ,-1 , 0
  3137.7     .05       0    4890      .1       0  4989.8     .07       0
    5001      .1       0
Bank Sta=4989.8,5001
XS Rating Curve= 0 ,0
Exp/Cntr=0.3,0.1

Type RM Length L Ch R = 1 ,11209   ,293,293,293
BEGIN DESCRIPTION:
Mustang Branch 14.0
END DESCRIPTION:
XS GIS Cut Line= 3
      2137605.37     13388410.82      2135360.62     13387556.67
      2134693.94     13388155.64
#Sta/Elev= 30
  3193.5  268.82  3817.1   262.3  3992.3  262.21  4165.2  262.67  4294.1  262.68
    4373  262.44  4476.9  262.49  4580.9  261.77  4686.3  261.01  4771.3  259.01
    4888  252.58  4941.2  251.56    4966  252.44  4990.5  248.44  4991.2  247.64
    5001  247.64  5001.7  248.44  5002.1  249.23  5020.8  252.93  5050.9  253.61
  5135.9  254.44  5367.1  253.12  5718.2  254.52  5824.7  254.28  6022.7  255.85
  6150.6  257.98  6228.3  260.87  6263.4  260.89  6341.9  263.25  6491.5  264.44
#Mann= 12 ,-1 , 0
  3193.5     .05       0  3992.3      .1       0  4165.2     .08       0
  4294.1      .1       0    4373     .05       0  4476.9     .08       0
  4580.9     .05       0    4888      .1       0  4990.5     .07       0
  5001.7      .1       0  5367.1     .05       0  5718.2      .1       0
Bank Sta=4990.5,5001.7
XS Rating Curve= 0 ,0
Exp/Cntr=0.3,0.1

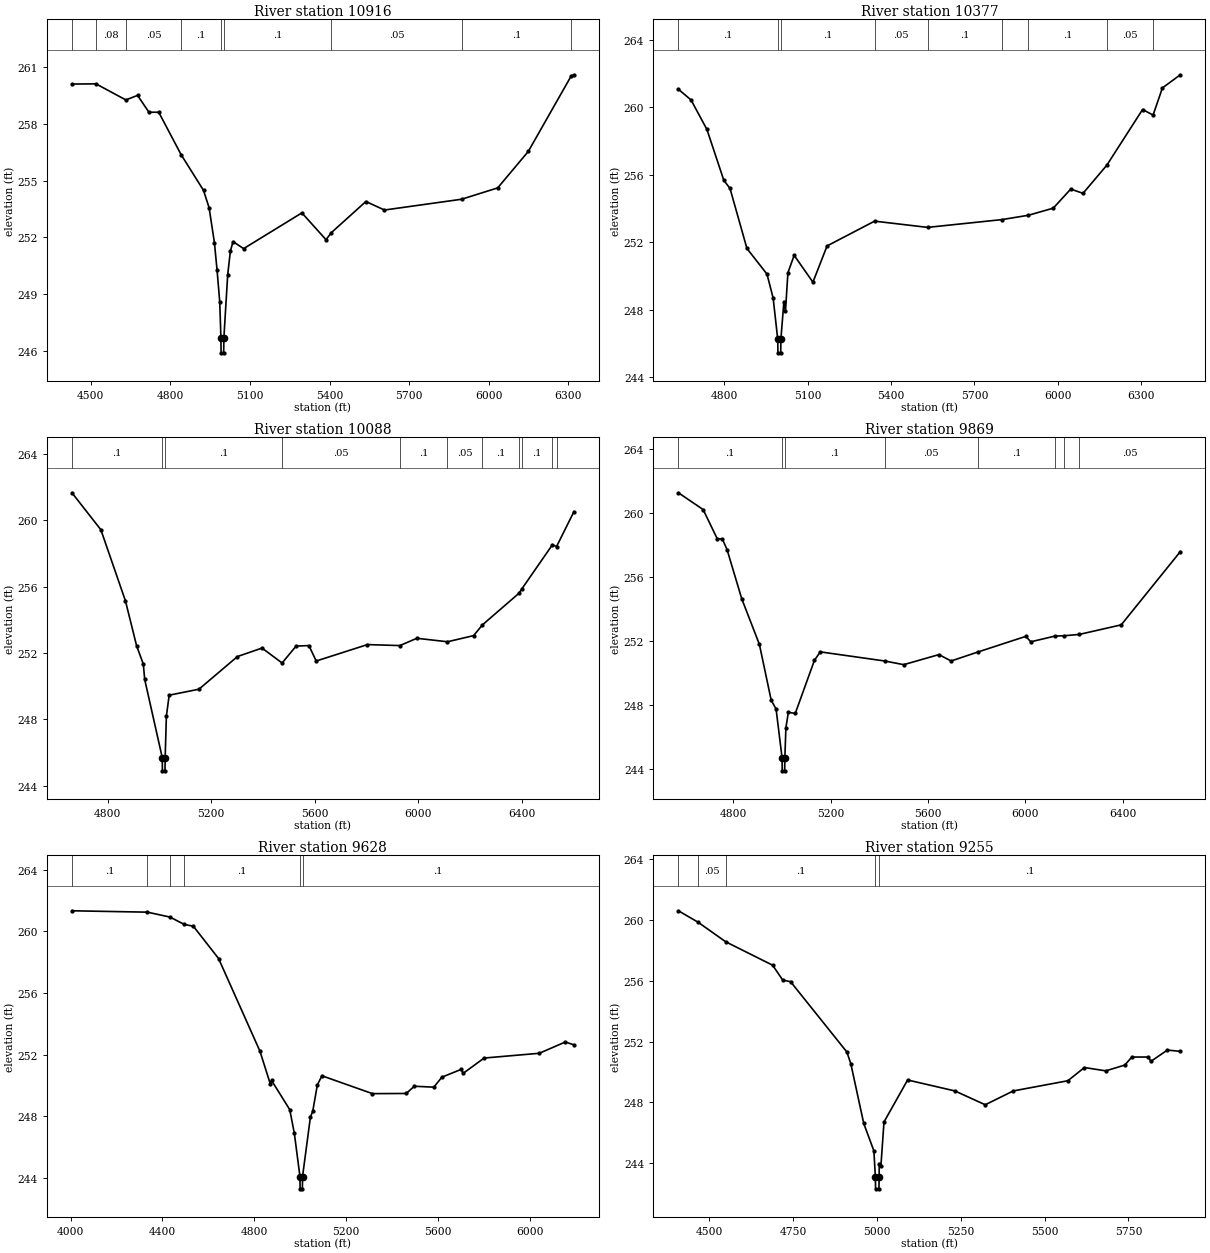
Type RM Length L Ch R = 1 ,10916   ,539,539,539
BEGIN DESCRIPTION:
Mapping XS 08fe4208
END DESCRIPTION:
XS GIS Cut Line= 4
      2136490.85     13387767.62      2136058.54     13387509.79
      2135334.58     13387470.73      2134788.81     13387847.57
#Sta/Elev= 30
  4428.8  260.11  4519.5  260.12  4631.9  259.27  4676.1  259.51  4718.9  258.62
  4755.9  258.62  4840.1  256.38  4924.6  254.49  4945.7  253.57  4965.7  251.73
  4975.8  250.26  4985.8  248.59  4990.2   246.7  4990.9   245.9  5000.7   245.9
  5001.4   246.7  5015.8  250.03  5025.8  251.27  5035.9  251.78  5075.9  251.41
  5295.4   253.3  5386.4  251.88  5406.1  252.25  5536.6   253.9  5606.7  253.45
  5897.2  254.02  6033.4  254.62  6148.8  256.55  6310.5  260.54  6320.4   260.6
#Mann= 9 ,-1 , 0
  4428.8      .1       0  4519.5     .08       0  4631.9     .05       0
  4840.1      .1       0  4990.2     .07       0  5001.4      .1       0
  5406.1     .05       0  5897.2      .1       0  6310.5     .05       0
Bank Sta=4990.2,5001.4
XS Rating Curve= 0 ,0
Exp/Cntr=0.3,0.1

Type RM Length L Ch R = 1 ,10377   ,289,289,289
BEGIN DESCRIPTION:
Mapping XS 283c28b9
END DESCRIPTION:
XS GIS Cut Line= 3
      2136165.27     13386895.23      2135446.56       13387265.
      2134631.83     13387840.25
#Sta/Elev= 30
  4635.1  261.06  4680.4  260.43  4737.6  258.68  4798.5  255.66  4820.7  255.18
  4881.6  251.62  4953.7   250.1  4975.9  248.68  4992.4  246.23  4993.1  245.43
  5003.1  245.43  5003.7  246.23  5014.6  248.47  5020.3  247.91    5029  250.18
  5051.5  251.21    5119  249.62  5169.9  251.77  5340.8  253.24  5531.6  252.87
  5798.3  253.33  5894.5  253.59  5983.6  254.01  6046.4  255.14  6090.7  254.89
  6176.4  256.56  6304.9  259.86  6342.7  259.53  6376.3  261.14  6440.7  261.92
#Mann= 9 ,-1 , 0
  4635.1      .1       0  4992.4     .07       0  5003.7      .1       0
  5340.8     .05       0  5531.6      .1       0  5798.3     .05       0
  5894.5      .1       0  6176.4     .05       0  6342.7      .1       0
Bank Sta=4992.4,5003.7
XS Rating Curve= 0 ,0
Exp/Cntr=0.3,0.1

Type RM Length L Ch R = 1 ,10088   ,219,219,219
BEGIN DESCRIPTION:
Mapping XS f52a22ce
END DESCRIPTION:
XS GIS Cut Line= 3
      2136180.94     13386681.66      2135371.04     13386955.11
      2134605.43     13387723.32
#Sta/Elev= 30
  4662.1  261.65  4773.9  259.42  4868.9  255.13  4911.7  252.44  4937.9  251.32
  4943.2   250.4    5011  245.69  5011.7  244.89  5021.7  244.89  5022.3  245.69
    5027  248.19  5037.8  249.45  5152.8  249.81  5301.6  251.78  5396.6  252.29
  5474.1  251.39  5528.2  252.41  5577.7  252.44    5606  251.51    5804   252.5
  5929.3  252.44  5994.9  252.88  6113.2  252.67  6214.1  253.04  6248.4  253.69
  6389.9   255.6  6401.1  255.87  6518.8  258.52  6534.7  258.41  6601.5   260.5
#Mann= 11 ,-1 , 0
  4662.1      .1       0    5011     .07       0  5022.3      .1       0
  5474.1     .05       0  5929.3      .1       0  6113.2     .05       0
  6248.4      .1       0  6389.9     .05       0  6401.1      .1       0
  6518.8     .05       0  6534.7      .1       0
Bank Sta=5011,5022.3
XS Rating Curve= 0 ,0
Exp/Cntr=0.3,0.1

Type RM Length L Ch R = 1 ,9869    ,241,241,241
BEGIN DESCRIPTION:
Mapping XS b430c7d6
END DESCRIPTION:
XS GIS Cut Line= 3
      2136173.07     13386567.09      2135240.83     13386689.48
      2134572.72     13387591.56
#Sta/Elev= 30
  4574.1  261.25  4675.7   260.2  4733.5  258.38  4754.4  258.36  4773.9   257.7
  4834.4  254.62  4906.9  251.77  4955.4  248.28  4975.6  247.72  5000.2  244.66
  5000.8  243.86  5010.8  243.86  5011.5  244.66  5015.9  246.56    5026  247.52
  5054.3  247.45  5133.1  250.77  5157.1   251.3    5422  250.73  5500.1   250.5
  5644.8  251.13  5694.9  250.73  5804.5  251.29  6001.7  252.27  6022.5  251.93
  6122.2  252.29  6160.1  252.31  6221.1  252.39    6394  252.99  6636.9  257.57
#Mann= 8 ,-1 , 0
  4574.1      .1       0  5000.2     .07       0  5011.5      .1       0
    5422     .05       0  5804.5      .1       0  6122.2     .05       0
  6160.1      .1       0  6221.1     .05       0
Bank Sta=5000.2,5011.5
XS Rating Curve= 0 ,0
Exp/Cntr=0.3,0.1

Type RM Length L Ch R = 1 ,9628    ,373,373,373
BEGIN DESCRIPTION:
Mapping XS f1d7a41f
END DESCRIPTION:
XS GIS Cut Line= 3
      2136683.55     13386395.21      2135230.41     13386436.88
      2134714.81     13386957.69
#Sta/Elev= 30
    4006  261.33  4334.9  261.24  4433.3  260.92  4495.9  260.44  4534.8  260.33
  4644.8  258.23  4824.9  252.22  4870.4  250.08  4875.4  250.32  4954.9  248.42
  4974.9  246.88  4999.3  244.08    5000  243.28    5010  243.28  5010.6  244.08
    5045  247.95    5055  248.31    5075  250.02    5095  250.62  5315.1  249.46
  5462.2  249.47  5497.6  249.94  5582.5  249.88  5617.8  250.53  5702.7  251.04
  5709.8  250.77  5801.7  251.77  6042.1  252.08  6155.2  252.81  6192.6  252.63
#Mann= 6 ,-1 , 0
    4006      .1       0  4334.9     .08       0  4433.3     .05       0
  4495.9      .1       0  4999.3     .07       0  5010.6      .1       0
Bank Sta=4999.3,5010.6
XS Rating Curve= 0 ,0
Exp/Cntr=0.3,0.1

Type RM Length L Ch R = 1 ,9255    ,158,158,158
BEGIN DESCRIPTION:
Mapping XS 4662fb75
END DESCRIPTION:
XS GIS Cut Line= 3
      2136324.11     13386082.71      2135355.41     13386192.08
      2134986.55     13386560.94
#Sta/Elev= 30
  4408.2  260.61  4466.6  259.86  4549.3  258.57  4689.1  257.03  4719.3  256.05
  4742.5  255.95  4910.5  251.32  4922.2  250.55  4960.8  246.62    4991  244.82
  4995.4  243.12  4996.1  242.32  5006.1  242.32  5006.7  243.12    5007  243.97
    5012  243.85  5021.2  246.72  5091.6  249.48  5232.5  248.76  5323.1  247.85
  5406.6  248.76  5569.3  249.43  5618.8   250.3  5682.4  250.08    5739  250.46
  5760.2  250.99  5809.7  250.99  5816.7   250.7  5866.2  251.45  5904.7  251.36
#Mann= 5 ,-1 , 0
  4408.2     .08       0  4466.6     .05       0  4549.3      .1       0
  4995.4     .07       0  5006.7      .1       0
Bank Sta=4995.4,5006.7
XS Rating Curve= 0 ,0
Exp/Cntr=0.3,0.1

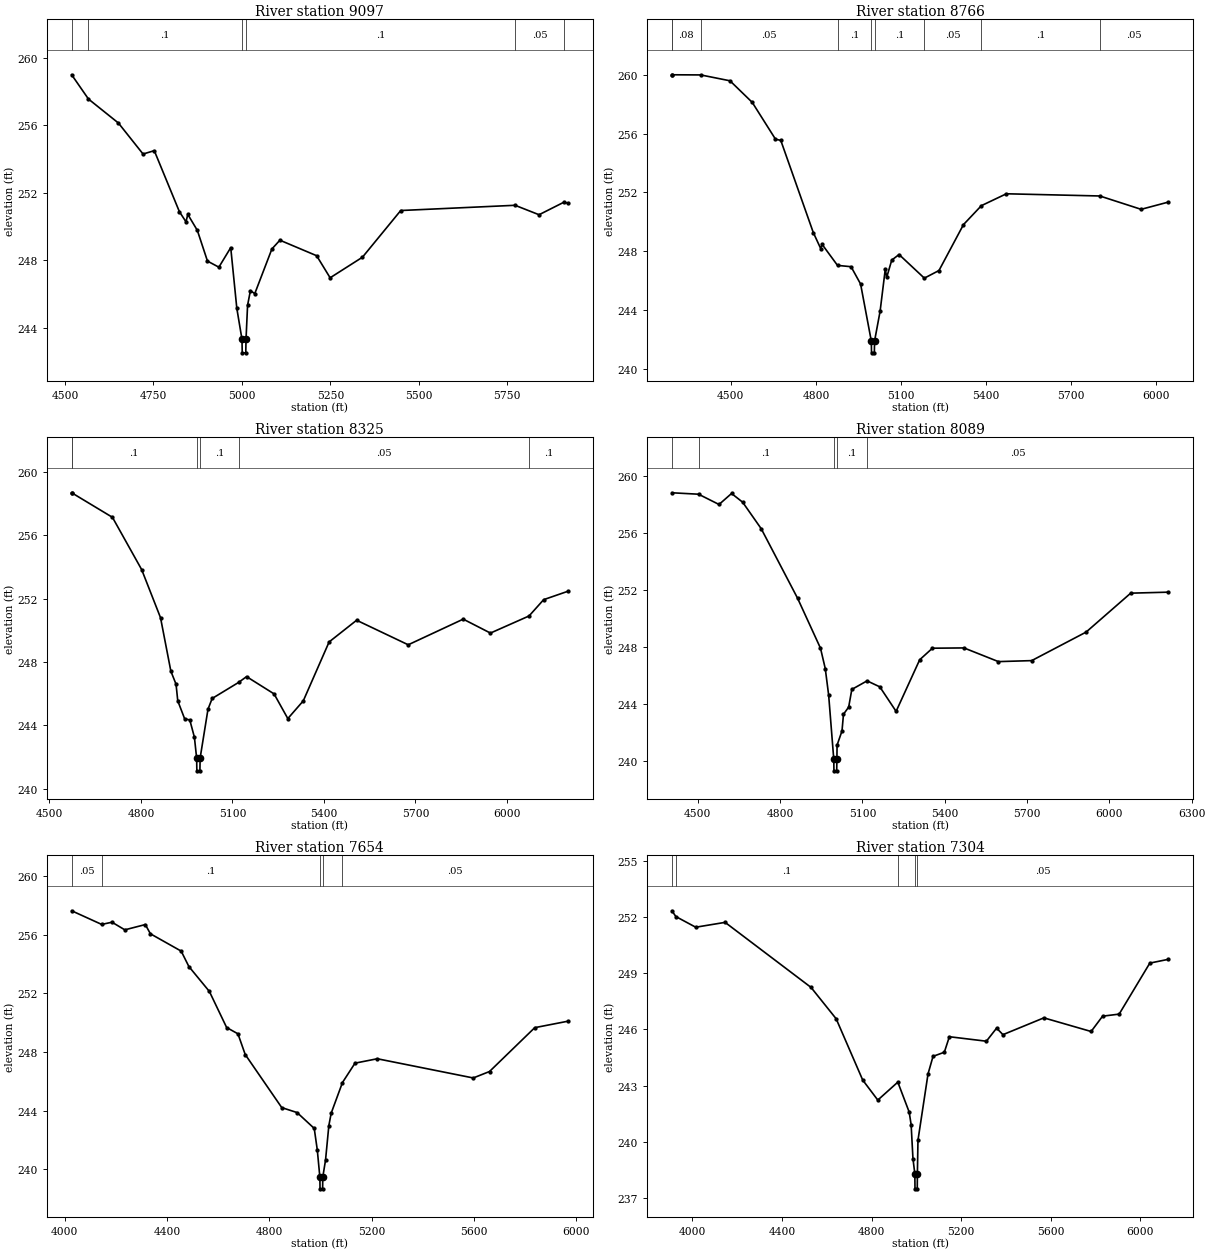
Type RM Length L Ch R = 1 ,9097    ,331,331,331
BEGIN DESCRIPTION:
Mapping XS 2d24dac9
END DESCRIPTION:
XS GIS Cut Line= 3
      2136225.18     13385916.05      2135292.91     13386072.29
      2134964.79       13386390.
#Sta/Elev= 30
    4519     259  4566.5  257.56    4651  256.14  4720.7   254.3  4752.4   254.5
  4823.4  250.88    4842  250.28  4847.1  250.72  4874.1  249.77  4902.7  247.95
  4934.9  247.59  4968.4  248.75  4985.6  245.15  5000.2  243.31  5000.9  242.51
  5010.9  242.51  5011.6  243.31    5016  245.33    5024   246.2  5036.3  246.02
  5084.7  248.67  5107.3  249.19  5211.1  248.27  5249.2  246.96  5340.5  248.18
  5448.7  250.95  5771.7  251.26  5839.5   250.7  5910.4  251.45    5921  251.38
#Mann= 6 ,-1 , 0
    4519     .05       0  4566.5      .1       0  5000.2     .07       0
  5011.6      .1       0  5771.7     .05       0  5910.4      .1       0
Bank Sta=5000.2,5011.6
XS Rating Curve= 0 ,0
Exp/Cntr=0.3,0.1

Type RM Length L Ch R = 1 ,8766    ,441,441,441
BEGIN DESCRIPTION:
Mapping XS fb4fcd85
END DESCRIPTION:
XS GIS Cut Line= 3
      2136381.46     13385535.83      2135376.24     13385759.79
      2134969.99     13386353.55
#Sta/Elev= 30
  4292.4  260.02  4292.7  260.02    4394  260.01  4497.2  259.61  4575.6  258.14
  4657.6  255.63  4676.2  255.55  4790.8  249.27  4816.9  248.18    4822  248.46
  4876.2  247.03    4924  246.94  4957.6  245.76  4995.4  241.87  4996.1  241.07
  5006.1  241.07  5006.8  241.87  5026.4  243.91  5044.6  246.77  5049.7  246.22
  5067.4  247.39  5093.2  247.77  5182.3  246.16  5233.9  246.68  5320.3  249.81
  5383.4   251.1  5471.5  251.91  5800.8  251.76  5946.5  250.85  6041.7  251.34
#Mann= 9 ,-1 , 0
  4292.4      .1       0  4292.7     .08       0    4394     .05       0
  4876.2      .1       0  4995.4     .07       0  5006.8      .1       0
  5182.3     .05       0  5383.4      .1       0  5800.8     .05       0
Bank Sta=4995.4,5006.8
XS Rating Curve= 0 ,0
Exp/Cntr=0.3,0.1

Type RM Length L Ch R = 1 ,8325    ,236,236,236
BEGIN DESCRIPTION:
Mapping XS 2607a43a
END DESCRIPTION:
XS GIS Cut Line= 3
      2136147.07       13385140.       2135225.2     13385587.92
      2134710.14     13385900.08
#Sta/Elev= 30
  4572.9  258.68    4573  258.68  4706.6  257.13  4802.4  253.83  4864.3  250.79
  4898.2  247.41  4915.2  246.59  4920.8  245.54  4943.3  244.41  4960.3  244.33
  4975.4  243.24  4982.7  241.92  4983.4  241.12  4993.4  241.12  4994.1  241.92
  5019.9  245.01  5033.6  245.69    5120   246.7  5146.4  247.07  5236.6  245.98
  5281.7  244.42  5332.4  245.54  5417.1  249.26  5507.3  250.63  5676.5  249.08
  5856.9   250.7  5946.1  249.82  6072.7   250.9  6120.6  251.93  6200.1  252.46
#Mann= 6 ,-1 , 0
  4572.9     .05       0    4573      .1       0  4982.7     .07       0
  4994.1      .1       0    5120     .05       0  6072.7      .1       0
Bank Sta=4982.7,4994.1
XS Rating Curve= 0 ,0
Exp/Cntr=0.3,0.1

Type RM Length L Ch R = 1 ,8089    ,435,435,435
BEGIN DESCRIPTION:
Mapping XS 3e27272e
END DESCRIPTION:
XS GIS Cut Line= 3
      2136214.76     13384910.85      2135084.58     13385358.75
       2134652.3     13385764.98
#Sta/Elev= 30
  4405.3   258.8  4502.4   258.7  4577.1  257.98  4622.8  258.75  4663.2  258.14
  4730.9  256.28  4863.3  251.41    4947   247.9  4964.4  246.47  4976.8   244.6
  4995.4   240.1    4996   239.3  5006.1   239.3  5006.8   240.1  5007.4   241.1
  5025.4   242.1  5030.8  243.27  5049.7  243.77  5061.2  245.01  5116.8  245.61
  5163.2  245.19  5222.6  243.47  5308.6  247.09    5355   247.9    5470  247.92
  5595.5  246.96  5716.9  247.03  5915.2  249.03  6077.8  251.76  6214.2  251.83
#Mann= 5 ,-1 , 0
  4405.3     .05       0  4502.4      .1       0  4995.4     .07       0
  5006.8      .1       0  5116.8     .05       0
Bank Sta=4995.4,5006.8
XS Rating Curve= 0 ,0
Exp/Cntr=0.3,0.1

Type RM Length L Ch R = 1 ,7654    ,350,350,350
BEGIN DESCRIPTION:
Mustang Branch 10.0
END DESCRIPTION:
XS GIS Cut Line= 4
       2136282.5     13384723.33      2135693.95     13384692.08
       2135231.7     13384932.66      2134626.24     13385499.38
#Sta/Elev= 30
  4027.2  257.62  4144.5  256.69  4184.9  256.84    4235  256.32  4315.1  256.68
  4335.1  256.05  4455.3  254.87  4485.3  253.82  4565.5  252.12    4633  249.66
  4677.2  249.23  4705.6  247.82  4848.4   244.2  4908.5  243.86  4975.4  242.78
  4987.4  241.31  4997.4  239.46  4998.1  238.66  5008.2  238.66  5008.8  239.46
  5019.6  240.62  5032.5  242.97  5041.7  243.82  5085.8  245.91  5134.8  247.23
  5221.9  247.53    5597  246.22  5660.6  246.66  5837.4  249.65    5967  250.09
#Mann= 5 ,-1 , 0
  4027.2     .05       0  4144.5      .1       0  4997.4     .07       0
  5008.8      .1       0  5085.8     .05       0
Bank Sta=4997.4,5008.8
XS Rating Curve= 0 ,0
Exp/Cntr=0.3,0.1

Type RM Length L Ch R = 1 ,7304    ,288,288,288
BEGIN DESCRIPTION:
Mapping XS 83591543
END DESCRIPTION:
XS GIS Cut Line= 4
      2136230.37     13384311.88      2135516.87     13384410.83
      2134990.83     13384671.25      2134605.41     13385494.17
#Sta/Elev= 30
  3908.5  252.35  3926.3  252.04  4014.9  251.47  4146.1  251.73  4529.8  248.25
  4642.1  246.57  4760.7  243.29    4828  242.22  4917.4  243.18  4968.1  241.58
  4976.8  240.91    4985  239.09  4993.4  238.27  4994.1  237.47  5004.2  237.47
  5004.8  238.27  5007.4  240.07  5052.3  243.62  5074.7  244.56  5125.1  244.78
  5147.6  245.61  5312.9  245.37  5358.6  246.07  5386.9  245.72  5569.6  246.62
  5780.6  245.89  5831.8  246.71  5905.8  246.82  6042.8  249.55  6124.5  249.75
#Mann= 5 ,-1 , 0
  3908.5     .05       0  3926.3      .1       0  4917.4     .05       0
  4993.4     .03       0  5004.8     .05       0
Bank Sta=4993.4,5004.8
XS Rating Curve= 0 ,0
Exp/Cntr=0.3,0.1

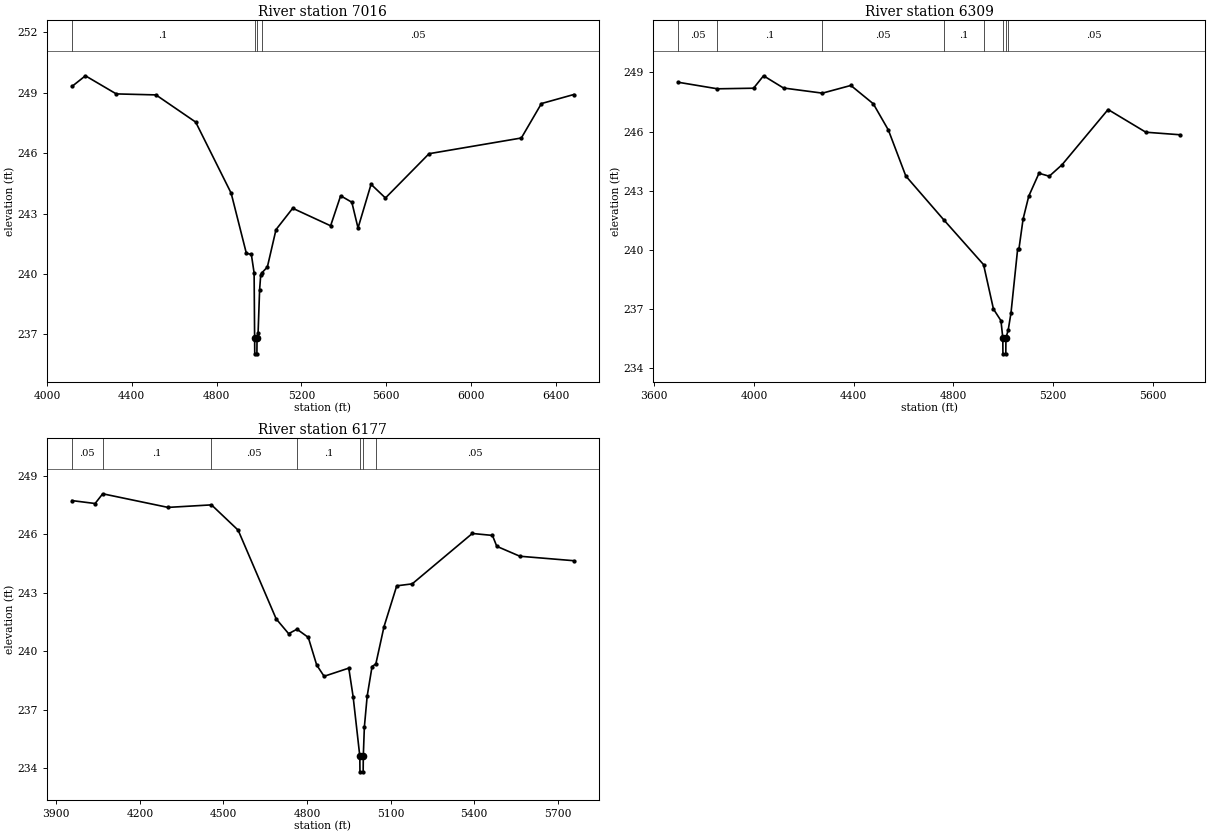
Type RM Length L Ch R = 1 ,7016    ,707,707,707
BEGIN DESCRIPTION:
Mapping XS 5cba5814
END DESCRIPTION:
XS GIS Cut Line= 3
      2136094.99     13384041.05      2135006.45     13384416.04
      2134532.49     13385535.85
#Sta/Elev= 30
  4117.7  249.31  4181.2  249.84  4326.7  248.94    4514  248.89  4701.3  247.54
  4868.6  244.01  4940.4  241.02  4963.8  240.97  4976.9  240.05  4979.3  236.83
  4979.9  236.03    4990  236.03  4990.7  236.83  4995.6  237.05  5002.8  239.21
  5008.1  239.95  5014.1  240.06  5039.3  240.34  5080.2   242.2  5158.9  243.26
  5337.7  242.39    5385  243.88  5437.8  243.56    5467  242.28  5528.5  244.45
  5596.3  243.77    5802  245.97  6237.3  246.75    6332  248.46    6485  248.91
#Mann= 4 ,-1 , 0
  4117.7      .1       0  4979.3     .07       0  4990.7      .1       0
  5014.1     .05       0
Bank Sta=4979.3,4990.7
XS Rating Curve= 0 ,0
Exp/Cntr=0.3,0.1

Type RM Length L Ch R = 1 ,6309    ,132,132,132
BEGIN DESCRIPTION:
Mapping XS 8dfae60a
END DESCRIPTION:
XS GIS Cut Line= 4
      2136376.22     13383848.33      2135563.74     13383837.92
      2135016.87     13383884.79      2134382.78     13384030.32
#Sta/Elev= 30
  3697.5   248.5    3854  248.17  3998.7   248.2  4038.7  248.83  4118.8  248.21
  4274.8  247.95  4388.8  248.34  4478.8  247.41  4539.2  246.08  4609.1  243.75
  4760.6  241.54  4920.8  239.26  4960.4  237.01  4990.5  236.42  4997.9  235.54
  4998.4  234.74  5009.9  234.74  5010.4  235.54  5019.6  235.95  5030.7  236.81
  5057.3  240.04  5062.4  240.04  5079.2  241.57  5101.9  242.73  5142.9  243.89
    5184  243.74  5235.3  244.32  5419.9  247.12  5571.3  245.97  5709.5  245.84
#Mann= 8 ,-1 , 0
  3697.5     .05       0    3854      .1       0  4274.8     .05       0
  4760.6      .1       0  4920.8     .16       0  4997.9     .07       0
  5010.4     .16       0  5019.6     .05       0
Bank Sta=4997.9,5010.4
XS Rating Curve= 0 ,0
Exp/Cntr=0.3,0.1

Type RM Length L Ch R = 1 ,6177    ,0,0,0
BEGIN DESCRIPTION:
Mustang Branch 9.0
END DESCRIPTION:
XS GIS Cut Line= 3
       2136157.5     13383645.21      2134949.16     13383785.83
      2134381.42     13383926.47
#Sta/Elev= 30
  3956.3  247.74  4039.4  247.59  4066.7  248.09  4301.1  247.39  4457.1  247.52
  4552.8  246.22  4689.3  241.66    4734   240.9    4764  241.13  4804.5  240.71
  4834.7  239.29  4861.3  238.71  4949.9  239.13  4965.6  237.65  4989.5   234.6
    4990   233.8  5001.5   233.8    5002   234.6  5005.8   236.1  5015.9  237.69
  5033.4  239.21  5047.1  239.35  5076.3  241.26    5122  243.36  5177.5  243.46
  5393.2  246.05  5465.5  245.95  5481.1  245.39  5563.9  244.88  5757.7  244.65
#Mann= 7 ,-1 , 0
  3956.3     .05       0  4066.7      .1       0  4457.1     .05       0
    4764      .1       0  4989.5     .07       0    5002      .1       0
  5047.1     .05       0
Bank Sta=4989.5,5002
XS Rating Curve= 0 ,0
Exp/Cntr=0.3,0.1
LCMann Table=0

Chan Stop Cuts=-1
Use User Specified Reach Order=0
Composite Channel Slope=5