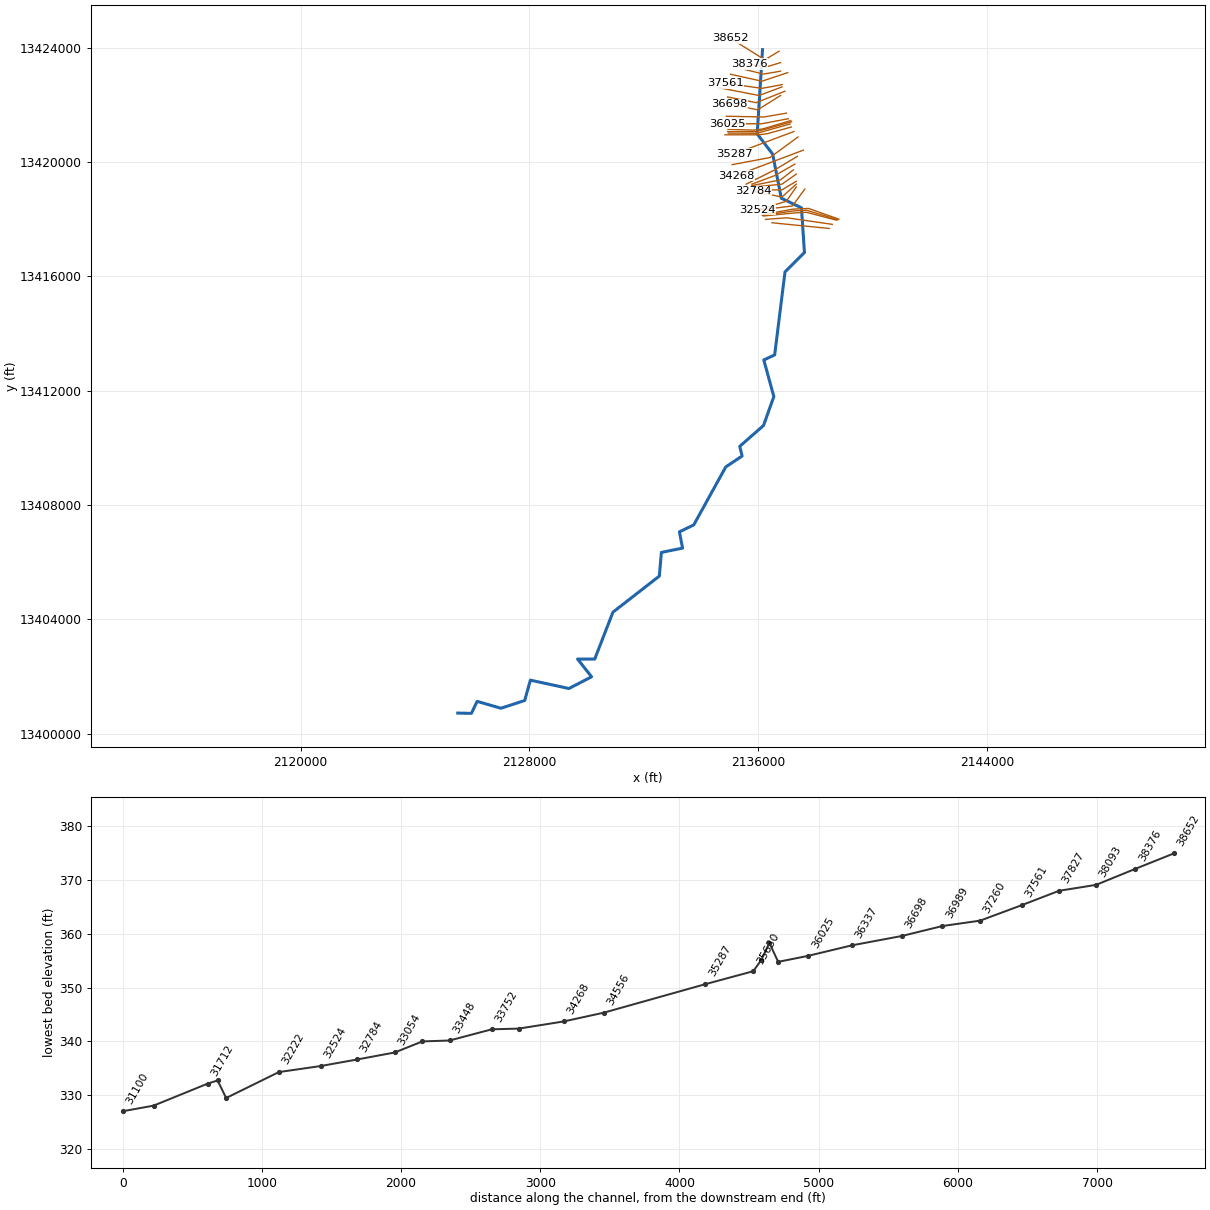
--- Salt Branch.prj (project) ---

Proj Title=Salt Branch Base Level Engineering
Current Plan=p01
Default Exp/Contr=0.3,0.1
English Units
Geom File=g01
Flow File=f01
Plan File=p01
BEGIN DESCRIPTION:
Salt Branch
END DESCRIPTION:

--- Salt Branch.p01 (plan) ---

Plan Title=Multiple Run
Short Identifier=Multiple
Geom File=g01
Flow File=f01
Subcritical Flow
K Sum by GR= 0
Std Step Tol= 0.01
Critical Tol= 0.01
Num of Std Step Trials= 20
Max Error Tol= 0.3
Flow Tol Ratio= 0.001
Split Flow NTrial= 30
Split Flow Tol= 0.02
Split Flow Ratio= 0.02
Log Output Level= 0
Friction Slope Method= 1
Unsteady Friction Slope Method= 2
Unsteady Bridges Friction Slope Method= 1
Parabolic Critical Depth
Global Vel Dist=  1 , 1 , 1
Global Log Level= 0
CheckData=True
Encroach Param= -1, 0, 0, 0
BEGIN DESCRIPTION:
Multiple Run
END DESCRIPTION:

--- Salt Branch.f01 (steady flow) ---

Flow Title=Multiple
Number of Profiles=7
Profile Names=10-year,25-year,50-year,1pct_min,100-year,1pct_plu,500-year
River Rch & RM= Salt Branch,Reach-1,38652
     120     159     190     113     226     450     324
River Rch & RM= Salt Branch,Reach-1,31712
     225     309     377     230     459     915     689
River Rch & RM= Salt Branch,Reach-1,30053
     294     409     503     309     616    1229     938
River Rch & RM= Salt Branch,Reach-1,24460
     367     515     640     396     789    1575    1219
River Rch & RM= Salt Branch,Reach-1,23455
     418     591     736     456     910    1815    1412
River Rch & RM= Salt Branch,Reach-1,20617
     468     664     829     514    1026    2047    1598
River Rch & RM= Salt Branch,Reach-1,15376
     496     703     878     544    1086    2167    1689
River Rch & RM= Salt Branch,Reach-1,7101
     545     776     970     603    1203    2401    1881
Boundary for River Rch & Prof#=Salt Branch,Reach-1,1
Up Type=0
Dn Type=3
Dn Slope=0.005
Boundary for River Rch & Prof#=Salt Branch,Reach-1,2
Up Type=0
Dn Type=3
Dn Slope=0.005
Boundary for River Rch & Prof#=Salt Branch,Reach-1,3
Up Type=0
Dn Type=3
Dn Slope=0.005
Boundary for River Rch & Prof#=Salt Branch,Reach-1,4
Up Type=0
Dn Type=3
Dn Slope=0.005
Boundary for River Rch & Prof#=Salt Branch,Reach-1,5
Up Type=0
Dn Type=3
Dn Slope=0.005
Boundary for River Rch & Prof#=Salt Branch,Reach-1,6
Up Type=0
Dn Type=3
Dn Slope=0.005
Boundary for River Rch & Prof#=Salt Branch,Reach-1,7
Up Type=0
Dn Type=3
Dn Slope=0.005

--- Salt Branch.g01 (geometry) ---

Geom Title=Existing Conditions

River Reach=Salt Branch,Reach-1
Reach XY= 30
      2136145.80     13423929.54      2135959.88     13420982.21
      2136500.80     13420274.54      2136800.80     13418734.54
      2137507.38     13418396.05      2137610.80     13416834.54
      2136930.80     13416154.54      2136570.80     13413254.54
      2136190.80     13413074.54      2136540.80     13411794.54
      2136180.80     13410784.54      2135350.80     13410054.54
      2135430.80     13409714.54      2134860.80     13409334.54
      2133740.80     13407304.54      2133240.80     13407064.54
      2133350.80     13406494.54      2132610.80     13406344.54
      2132538.60     13405516.50      2130917.03     13404254.05
      2130280.80     13402614.54      2129680.05     13402614.51
      2130170.80     13401994.54      2129380.80     13401584.54
      2128031.69     13401876.48      2127832.04     13401163.59
      2127000.80     13400894.54      2126170.80     13401134.54
      2125970.80     13400714.54      2125490.80     13400724.54

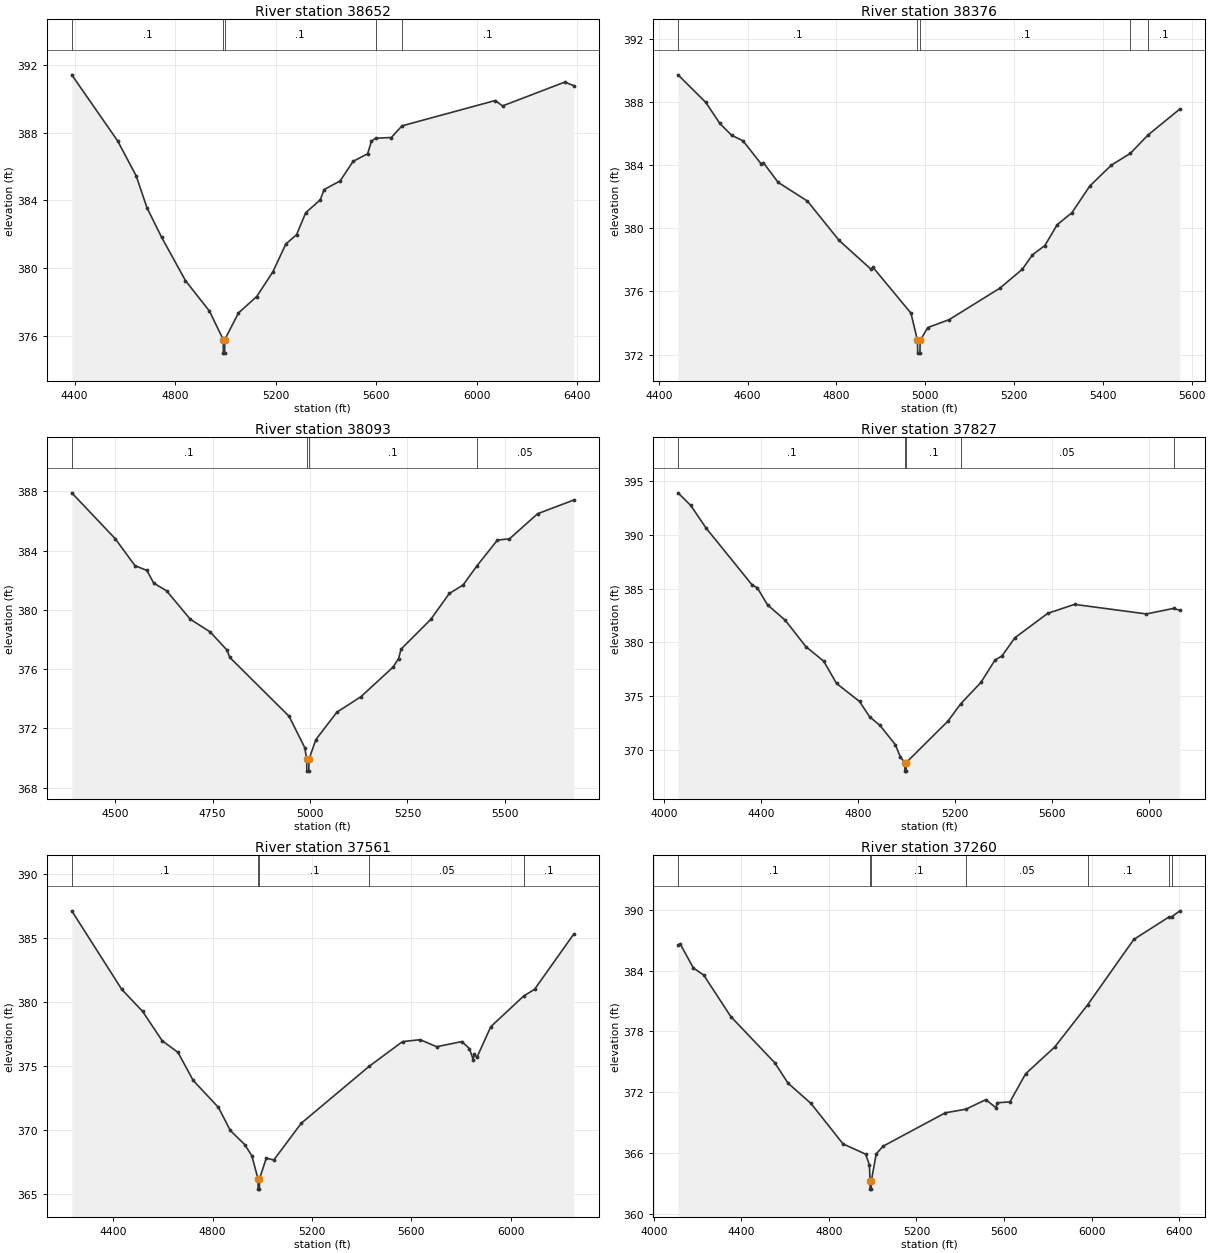
Type RM Length L Ch R = 1,38652,276,276,276
BEGIN DESCRIPTION:
Salt Branch 83.0
END DESCRIPTION:
XS GIS Cut Line= 3
      2136724.97     13423874.98      2136225.00     13423575.00
      2135024.96     13424325.02
#Sta/Elev= 30
  4388.4  391.43  4571.1  387.52  4644.9  385.45  4687.7  383.57  4746.0  381.82
  4841.2  379.25  4936.5  377.45  4991.5  375.76  4992.0  374.96  4997.0  374.96
  4997.5  375.76  5052.2  377.34  5124.8  378.31  5189.0  379.77  5240.9  381.42
  5283.4  381.97  5319.9  383.27  5377.7  384.03  5393.0  384.64  5456.7  385.15
  5508.6  386.31  5566.4  386.76  5581.7  387.51  5598.5  387.68  5660.7  387.72
  5703.2  388.41  6074.6  389.91  6103.5  389.59  6351.2  391.00  6386.6  390.79
#Mann=5,-1,0
  4388.4     0.1       0  4991.5    0.07       0  4997.5     0.1       0
  5598.5    0.08       0  5703.2     0.1       0
Bank Sta=4991.5,4997.5
Exp/Cntr=0.3,0.1

Type RM Length L Ch R = 1,38376,283,283,283
BEGIN DESCRIPTION:
Salt Branch 82.0
END DESCRIPTION:
XS GIS Cut Line= 3
      2136775.01     13423475.00      2136275.00     13423325.00
      2135675.00     13423425.00
#Sta/Elev= 30
  4443.3  389.71  4506.0  387.96  4537.3  386.64  4564.2  385.88  4589.5  385.54
  4630.4  384.08  4635.6  384.15  4668.6  382.91  4734.8  381.72  4806.1  379.23
  4877.5  377.42  4882.7  377.52  4967.9  374.63  4982.6  372.90  4983.1  372.10
  4988.1  372.10  4988.6  372.90  5005.9  373.72  5054.0  374.22  5168.1  376.21
  5218.8  377.41  5241.6  378.32  5269.5  378.91  5297.3  380.23  5330.3  380.98
  5370.8  382.68  5419.0  383.99  5462.0  384.74  5501.3  385.89  5573.6  387.55
#Mann=5,-1,0
  4443.3     0.1       0  4982.6    0.07       0  4988.6     0.1       0
  5462.0    0.05       0  5501.3     0.1       0
Bank Sta=4982.6,4988.6
Exp/Cntr=0.3,0.1

Type RM Length L Ch R = 1,38093,266,266,266
BEGIN DESCRIPTION:
Salt Branch 81.0
END DESCRIPTION:
XS GIS Cut Line= 3
      2136775.04     13423175.01      2136175.00     13423075.00
      2135515.26     13423238.47
#Sta/Elev= 30
  4388.6  387.91  4500.2  384.81  4550.8  382.99  4581.3  382.67  4599.0  381.81
  4631.9  381.29  4692.8  379.37  4743.5  378.52  4786.6  377.30  4794.2  376.79
  4946.2  372.82  4986.8  370.68  4991.4  369.91  4991.9  369.11  4996.9  369.11
  4997.4  369.91  5015.0  371.24  5069.0  373.09  5130.8  374.14  5213.3  376.14
  5227.2  376.71  5233.9  377.36  5309.9  379.36  5357.5  381.11  5392.7  381.68
  5428.2  382.97  5481.1  384.72  5511.8  384.80  5584.2  386.50  5676.6  387.42
#Mann=4,-1,0
  4388.6     0.1       0  4991.4    0.07       0  4997.4     0.1       0
  5428.2    0.05       0
Bank Sta=4991.4,4997.4
Exp/Cntr=0.3,0.1

Type RM Length L Ch R = 1,37827,266,266,266
BEGIN DESCRIPTION:
Salt Branch 80.0
END DESCRIPTION:
XS GIS Cut Line= 3
      2137025.03     13423125.01      2136125.00     13422825.00
      2135030.93     13423069.19
#Sta/Elev= 30
  4057.4  393.93  4110.1  392.75  4173.4  390.64  4363.1  385.35  4384.2  385.09
  4426.4  383.50  4500.1  382.05  4584.5  379.61  4658.3  378.25  4711.0  376.18
  4805.8  374.50  4848.0  373.06  4890.2  372.27  4953.4  370.48  4974.5  369.32
  4992.6  368.81  4993.1  368.01  4998.1  368.01  4998.6  368.81  5171.0  372.68
  5223.2  374.28  5306.4  376.27  5364.7  378.36  5393.3  378.74  5447.0  380.44
  5582.5  382.71  5692.6  383.54  5988.9  382.65  6101.7  383.17  6127.1  382.98
#Mann=5,-1,0
  4057.4     0.1       0  4992.6    0.07       0  4998.6     0.1       0
  5223.2    0.05       0  6101.7     0.1       0
Bank Sta=4992.6,4998.6
Exp/Cntr=0.3,0.1

Type RM Length L Ch R = 1,37561,301,301,301
BEGIN DESCRIPTION:
Salt Branch 79.0
END DESCRIPTION:
XS GIS Cut Line= 3
      2136835.56     13422707.21      2136125.00     13422575.00
      2134839.12     13422756.57
#Sta/Elev= 30
  4232.6  387.13  4433.8  380.99  4518.0  379.26  4597.1  376.96  4660.4  376.06
  4721.4  373.87  4823.5  371.75  4871.1  369.95  4929.0  368.85  4957.9  367.97
  4982.7  366.16  4983.2  365.36  4988.2  365.36  4988.7  366.16  5016.0  367.78
  5046.3  367.64  5157.3  370.52  5430.6  374.97  5564.8  376.90  5635.9  377.05
  5702.0  376.50  5803.7  376.90  5834.0  376.36  5849.3  375.50  5854.3  375.92
  5864.3  375.66  5920.4  378.07  6053.0  380.47  6096.6  380.99  6254.0  385.30
#Mann=5,-1,0
  4232.6     0.1       0  4982.7    0.07       0  4988.7     0.1       0
  5430.6    0.05       0  6053.0     0.1       0
Bank Sta=4982.7,4988.7
Exp/Cntr=0.3,0.1

Type RM Length L Ch R = 1,37260,271,271,271
BEGIN DESCRIPTION:
Salt Branch 78.0
END DESCRIPTION:
XS GIS Cut Line= 3
      2136824.96     13422624.98      2136025.00     13422325.00
      2134612.82     13422600.22
#Sta/Elev= 30
  4110.8  386.52  4120.5  386.64  4181.1  384.25  4228.2  383.56  4351.9  379.47
  4553.1  374.91  4613.6  372.90  4718.6  370.90  4864.6  366.92  4967.7  365.91
  4985.5  364.85  4988.0  363.26  4988.5  362.46  4993.5  362.46  4994.0  363.26
  5016.1  365.92  5047.7  366.69  5331.9  369.98  5426.3  370.34  5517.2  371.28
  5563.8  370.48  5568.8  370.97  5627.4  371.06  5698.7  373.82  5832.0  376.47
  5981.8  380.61  6193.2  387.07  6352.2  389.26  6365.5  389.29  6403.9  389.89
#Mann=7,-1,0
  4110.8     0.1       0  4988.0    0.07       0  4994.0     0.1       0
  5426.3    0.05       0  5981.8     0.1       0  6352.2    0.05       0
  6365.5     0.1       0
Bank Sta=4988,4994
Exp/Cntr=0.3,0.1

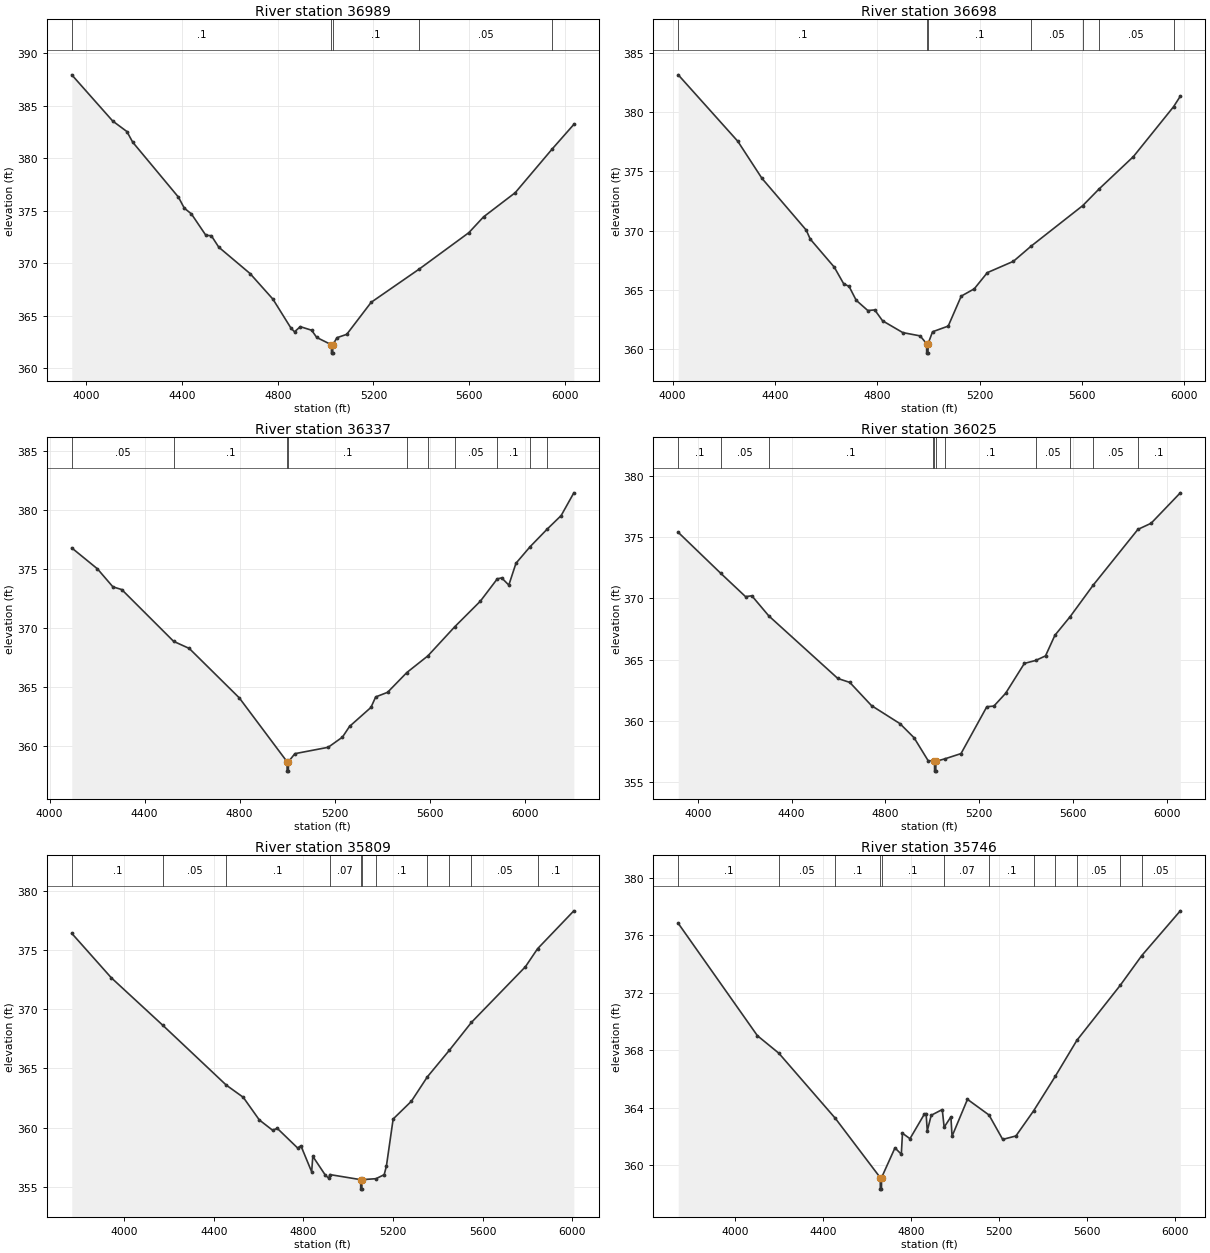
Type RM Length L Ch R = 1,36989,291,291,291
BEGIN DESCRIPTION:
Salt Branch 77.0
END DESCRIPTION:
XS GIS Cut Line= 3
      2136924.98     13422474.99      2135925.00     13422075.00
      2134925.02     13422275.00
#Sta/Elev= 30
  3940.0  387.96  4111.0  383.56  4170.2  382.56  4194.4  381.55  4385.6  376.31
  4409.8  375.27  4439.5  374.72  4500.0  372.68  4522.9  372.64  4553.9  371.55
  4684.5  369.04  4780.1  366.60  4855.5  363.84  4870.3  363.49  4894.5  363.98
  4941.6  363.64  4963.2  362.95  5024.2  362.26  5024.7  361.46  5029.7  361.46
  5030.2  362.26  5047.6  362.93  5088.4  363.25  5190.4  366.30  5390.1  369.45
  5598.3  372.93  5659.5  374.43  5792.1  376.74  5946.8  380.91  6036.8  383.24
#Mann=5,-1,0
  3940.0     0.1       0  5024.2    0.07       0  5030.2     0.1       0
  5390.1    0.05       0  5946.8     0.1       0
Bank Sta=5024.2,5030.2
Exp/Cntr=0.3,0.1

Type RM Length L Ch R = 1,36698,361,361,361
BEGIN DESCRIPTION:
Salt Branch 76.0
END DESCRIPTION:
XS GIS Cut Line= 3
      2136775.02     13422325.01      2135975.00     13421825.00
      2134975.02     13422025.00
#Sta/Elev= 30
  4021.7  383.19  4254.6  377.56  4349.0  374.42  4522.3  370.03  4537.6  369.28
  4632.0  366.89  4668.5  365.49  4689.8  365.26  4717.5  364.09  4762.9  363.22
  4790.0  363.27  4820.7  362.35  4899.7  361.35  4967.7  361.07  4992.7  360.41
  4993.2  359.61  4998.2  359.61  4998.7  360.41  5016.1  361.42  5077.3  361.90
  5128.3  364.44  5179.3  365.06  5230.3  366.43  5332.3  367.39  5401.3  368.67
  5603.5  372.11  5666.8  373.51  5801.4  376.26  5958.6  380.49  5984.9  381.38
#Mann=7,-1,0
  4021.7     0.1       0  4992.7    0.07       0  4998.7     0.1       0
  5401.3    0.05       0  5603.5     0.1       0  5666.8    0.05       0
  5958.6     0.1       0
Bank Sta=4992.7,4998.7
Exp/Cntr=0.3,0.1

Type RM Length L Ch R = 1,36337,312,312,312
BEGIN DESCRIPTION:
Mapping XS 340f263a
END DESCRIPTION:
XS GIS Cut Line= 3
      2136982.27     13421708.79      2136192.30     13421574.23
      2134881.50     13421600.28
#Sta/Elev= 30
  4093.7  376.78  4201.5  375.01  4266.8  373.48  4304.0  373.25  4522.3  368.86
  4588.0  368.26  4798.5  364.07  4999.4  358.66  4999.9  357.86  5004.9  357.86
  5005.4  358.66  5032.4  359.34  5172.4  359.88  5232.4  360.74  5262.4  361.65
  5352.4  363.26  5372.4  364.15  5422.4  364.54  5503.6  366.22  5592.0  367.63
  5705.6  370.11  5812.5  372.26  5884.1  374.16  5902.5  374.24  5932.5  373.63
  5962.6  375.48  6021.9  376.88  6094.2  378.38  6152.6  379.52  6206.1  381.45
#Mann=10,-1,0
  4093.7    0.05       0  4522.3     0.1       0  4999.4    0.07       0
  5005.4     0.1       0  5503.6    0.05       0  5592.0     0.1       0
  5705.6    0.05       0  5884.1     0.1       0  6021.9    0.05       0
  6094.2     0.1       0
Bank Sta=4999.4,5005.4
Exp/Cntr=0.3,0.1

Type RM Length L Ch R = 1,36025,216,216,216
BEGIN DESCRIPTION:
Mapping XS 0c1b147d
END DESCRIPTION:
XS GIS Cut Line= 3
      2137043.04     13421513.48      2136109.83     13421335.52
      2134920.56     13421339.86
#Sta/Elev= 30
  3917.0  375.38  4098.8  372.03  4203.8  370.14  4230.6  370.21  4302.9  368.57
  4597.1  363.47  4648.0  363.15  4740.5  361.26  4861.8  359.79  4921.9  358.64
  4981.9  356.77  5001.3  356.76  5008.9  356.72  5009.4  355.92  5014.4  355.92
  5014.9  356.72  5052.9  356.92  5121.9  357.35  5231.9  361.17  5261.9  361.22
  5311.9  362.26  5391.9  364.70  5440.1  364.94  5481.9  365.31  5521.9  366.99
  5587.3  368.52  5685.6  371.09  5875.6  375.62  5931.9  376.12  6056.3  378.60
#Mann=11,-1,0
  3917.0     0.1       0  4098.8    0.05       0  4302.9     0.1       0
  5001.3    0.07       0  5008.9    0.07       0  5014.9    0.07       0
  5052.9     0.1       0  5440.1    0.05       0  5587.3     0.1       0
  5685.6    0.05       0  5875.6     0.1       0
Bank Sta=5008.9,5014.9
Exp/Cntr=0.3,0.1

Type RM Length L Ch R = 1,35809,63,63,63
BEGIN DESCRIPTION:
Mapping XS b2516eda
END DESCRIPTION:
XS GIS Cut Line= 4
      2137134.11     13421448.36      2136157.57     13421157.57
      2135840.73     13421114.16      2134938.96     13421144.51
#Sta/Elev= 30
  3766.5  376.39  3942.9  372.64  4172.8  368.63  4456.1  363.58  4532.0  362.55
  4603.6  360.64  4662.9  359.77  4683.8  359.93  4774.7  358.27  4789.2  358.46
  4837.3  356.26  4842.3  357.57  4899.0  355.96  4914.5  355.71  4917.8  356.03
  5055.8  355.60  5056.3  354.80  5061.3  354.80  5061.8  355.60  5124.2  355.68
  5161.0  356.02  5171.0  356.76  5201.0  360.72  5282.4  362.22  5353.4  364.27
  5451.8  366.52  5550.2  368.87  5791.3  373.57  5845.5  375.09  6007.5  378.29
#Mann=11,-1,0
  3766.5     0.1       0  4172.8    0.05       0  4456.1     0.1       0
  4917.8    0.07       0  5055.8    0.07       0  5061.8    0.07       0
  5124.2     0.1       0  5353.4    0.05       0  5451.8     0.1       0
  5550.2    0.05       0  5845.5     0.1       0
Bank Sta=5055.8,5061.8
Exp/Cntr=0.3,0.1

Type RM Length L Ch R = 1,35746,60,60,60
BEGIN DESCRIPTION:
Mapping XS ed644b7f
END DESCRIPTION:
XS GIS Cut Line= 3
      2137161.10     13421405.13      2135937.16     13421061.38
      2134928.36     13421063.98
#Sta/Elev= 30
  3743.5  376.82  4103.0  369.00  4200.4  367.78  4456.8  363.25  4660.9  359.12
  4661.4  358.32  4666.4  358.32  4666.9  359.12  4727.7  361.19  4756.6  360.75
  4761.8  362.21  4795.9  361.83  4861.2  363.54  4869.2  363.58  4874.4  362.37
  4892.4  363.46  4942.5  363.86  4951.1  362.63  4981.8  363.35  4987.0  362.00
  5057.0  364.57  5154.8  363.48  5217.0  361.78  5277.0  362.02  5357.4  363.77
  5455.7  366.17  5554.0  368.68  5750.5  372.50  5848.8  374.58  6023.6  377.69
#Mann=12,-1,0
  3743.5     0.1       0  4200.4    0.05       0  4456.8     0.1       0
  4660.9    0.07       0  4666.9     0.1       0  4951.1    0.07       0
  5154.8     0.1       0  5357.4    0.05       0  5455.7     0.1       0
  5554.0    0.05       0  5750.5     0.1       0  5848.8    0.05       0
Bank Sta=4660.9,4666.9
Exp/Cntr=0.3,0.1

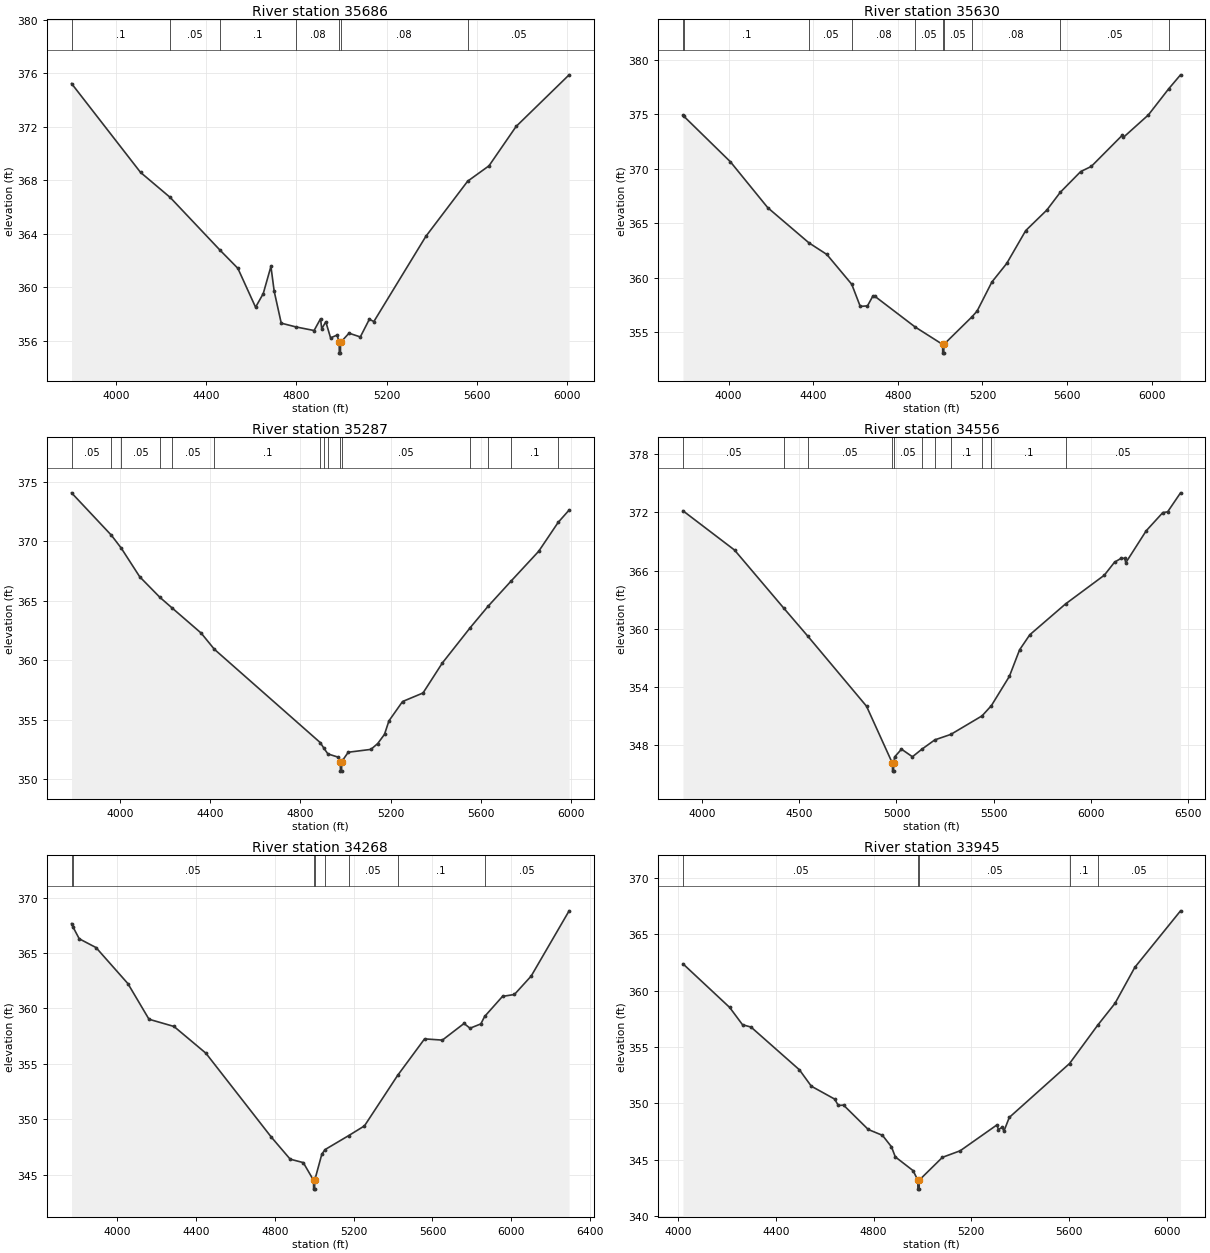
Type RM Length L Ch R = 1,35686,56,56,56
BEGIN DESCRIPTION:
Mapping XS 1d7a90af
END DESCRIPTION:
XS GIS Cut Line= 3
      2137109.05     13421329.62      2135952.79     13421004.09
      2134950.23     13421011.90
#Sta/Elev= 30
  3803.7  375.22  4109.2  368.58  4240.4  366.71  4461.1  362.77  4540.3  361.41
  4618.8  358.50  4652.8  359.52  4686.8  361.55  4701.3  359.69  4732.5  357.31
  4797.1  357.03  4877.9  356.76  4906.6  357.64  4911.8  356.89  4929.9  357.41
  4951.0  356.21  4979.9  356.42  4989.2  355.87  4989.7  355.07  4994.7  355.07
  4995.2  355.87  5032.7  356.56  5082.7  356.28  5122.7  357.60  5142.7  357.43
  5372.7  363.79  5558.1  367.92  5652.7  369.07  5772.7  372.01  6007.5  375.87
#Mann=7,-1,0
  3803.7     0.1       0  4240.4    0.05       0  4461.1     0.1       0
  4797.1    0.08       0  4989.2    0.07       0  4995.2    0.08       0
  5558.1    0.05       0
Bank Sta=4989.2,4995.2
Exp/Cntr=0.3,0.1

Type RM Length L Ch R = 1,35630,343,343,343
BEGIN DESCRIPTION:
Mapping XS 082e2d7a
END DESCRIPTION:
XS GIS Cut Line= 4
      2137151.46     13421222.66      2136305.14     13420988.30
      2136028.31     13420952.01      2134832.98     13420949.40
#Sta/Elev= 30
  3784.0  374.90  3786.9  374.83  4008.6  370.62  4185.0  366.41  4379.9  363.18
  4464.2  362.12  4582.1  359.38  4622.2  357.35  4656.5  357.40  4682.5  358.32
  4692.6  358.26  4881.8  355.46  5011.7  353.86  5012.2  353.06  5017.2  353.06
  5017.7  353.86  5149.8  356.38  5174.7  356.92  5244.7  359.59  5314.7  361.29
  5404.7  364.31  5504.7  366.20  5568.3  367.83  5664.7  369.73  5714.7  370.20
  5861.6  373.07  5866.6  372.87  5984.7  374.93  6080.0  377.31  6136.7  378.61
#Mann=10,-1,0
  3784.0    0.05       0  3786.9     0.1       0  4379.9    0.05       0
  4582.1    0.08       0  4881.8    0.05       0  5011.7    0.03       0
  5017.7    0.05       0  5149.8    0.08       0  5568.3    0.05       0
  6080.0     0.1       0
Bank Sta=5011.7,5017.7
Exp/Cntr=0.3,0.1

Type RM Length L Ch R = 1,35287,731,731,731
BEGIN DESCRIPTION:
Mapping XS 9838d21d
END DESCRIPTION:
XS GIS Cut Line= 2
      2137242.66     13421066.43      2135178.95     13420290.37
#Sta/Elev= 30
  3785.9  374.09  3962.4  370.52  4006.3  369.43  4088.1  367.02  4177.5  365.29
  4231.9  364.39  4360.3  362.28  4418.7  360.92  4888.1  353.06  4904.1  352.59
  4921.8  352.11  4966.5  351.84  4977.0  351.46  4977.5  350.66  4982.5  350.66
  4983.0  351.46  5012.0  352.25  5112.3  352.49  5142.5  352.98  5172.7  353.76
  5192.3  354.89  5252.7  356.52  5343.4  357.24  5428.8  359.76  5552.6  362.74
  5630.7  364.52  5734.5  366.68  5856.0  369.17  5942.1  371.60  5990.7  372.64
#Mann=15,-1,0
  3785.9    0.05       0  3962.4     0.1       0  4006.3    0.05       0
  4177.5     0.1       0  4231.9    0.05       0  4418.7     0.1       0
  4888.1    0.05       0  4904.1     0.1       0  4921.8    0.05       0
  4977.0   0.035       0  4983.0    0.05       0  5552.6     0.1       0
  5630.7    0.05       0  5734.5     0.1       0  5942.1    0.05       0
Bank Sta=4977,4983
Exp/Cntr=0.3,0.1

Type RM Length L Ch R = 1,34556,288,288,288
BEGIN DESCRIPTION:
Mapping XS 146b2f54
END DESCRIPTION:
XS GIS Cut Line= 3
      2137385.89     13420875.47      2136404.97     13420154.96
      2135085.56     13419907.57
#Sta/Elev= 30
  3901.8  372.15  4167.0  368.11  4420.7  362.12  4543.7  359.25  4846.1  352.03
  4979.4  346.15  4979.9  345.35  4984.9  345.35  4985.4  346.15  4990.4  346.81
  5025.9  347.61  5082.2  346.83  5131.6  347.62  5197.6  348.57  5279.5  349.13
  5440.3  351.04  5488.2  352.09  5580.9  355.11  5633.4  357.84  5686.0  359.39
  5869.6  362.56  6069.2  365.52  6121.8  366.86  6156.6  367.27  6174.4  367.25
  6179.5  366.80  6284.6  370.09  6370.3  371.97  6394.8  372.04  6461.3  374.00
#Mann=11,-1,0
  3901.8    0.05       0  4420.7     0.1       0  4543.7    0.05       0
  4979.4    0.03       0  4985.4    0.05       0  5131.6     0.1       0
  5197.6    0.05       0  5279.5     0.1       0  5440.3    0.05       0
  5488.2     0.1       0  5869.6    0.05       0
Bank Sta=4979.4,4985.4
Exp/Cntr=0.3,0.1

Type RM Length L Ch R = 1,34268,323,323,323
BEGIN DESCRIPTION:
Mapping XS 4032e6c7
END DESCRIPTION:
XS GIS Cut Line= 2
      2137572.49     13420415.37      2135211.41     13419521.29
#Sta/Elev= 30
  3768.5  367.65  3774.8  367.38  3807.6  366.28  3892.7  365.49  4054.5  362.24
  4161.5  359.03  4288.2  358.38  4450.2  355.97  4781.6  348.42  4877.9  346.42
  4944.4  346.11  4996.4  344.52  4996.9  343.72  5001.9  343.72  5002.4  344.52
  5038.3  346.86  5054.5  347.28  5175.3  348.55  5254.8  349.42  5423.1  353.97
  5559.8  357.26  5650.2  357.15  5760.2  358.65  5790.3  358.22  5845.3  358.61
  5864.6  359.28  5955.3  361.09  6015.6  361.26  6100.7  362.92  6293.2  368.80
#Mann=8,-1,0
  3768.5    0.08       0  3774.8    0.05       0  4996.4    0.03       0
  5002.4    0.05       0  5054.5     0.1       0  5175.3    0.05       0
  5423.1     0.1       0  5864.6    0.05       0
Bank Sta=4996.4,5002.4
Exp/Cntr=0.3,0.1

Type RM Length L Ch R = 1,33945,193,193,193
BEGIN DESCRIPTION:
Salt Branch 69.0
END DESCRIPTION:
XS GIS Cut Line= 3
      2137364.21     13420198.39      2136575.00     13419725.00
      2135575.03     13419225.02
#Sta/Elev= 30
  4019.1  362.37  4210.5  358.50  4263.0  356.97  4298.0  356.76  4496.2  352.97
  4544.8  351.52  4640.1  350.38  4655.6  349.81  4677.0  349.84  4778.1  347.68
  4836.4  347.16  4873.3  346.14  4888.9  345.25  4961.8  344.03  4981.1  343.19
  4981.6  342.39  4986.6  342.39  4987.1  343.19  5082.0  345.21  5154.6  345.79
  5305.6  348.09  5311.1  347.67  5327.9  347.89  5333.5  347.51  5355.9  348.75
  5602.8  353.53  5718.1  356.93  5789.1  358.87  5870.2  362.06  6057.4  367.07
#Mann=5,-1,0
  4019.1    0.05       0  4981.1    0.03       0  4987.1    0.05       0
  5602.8     0.1       0  5718.1    0.05       0
Bank Sta=4981.1,4987.1
Exp/Cntr=0.3,0.1

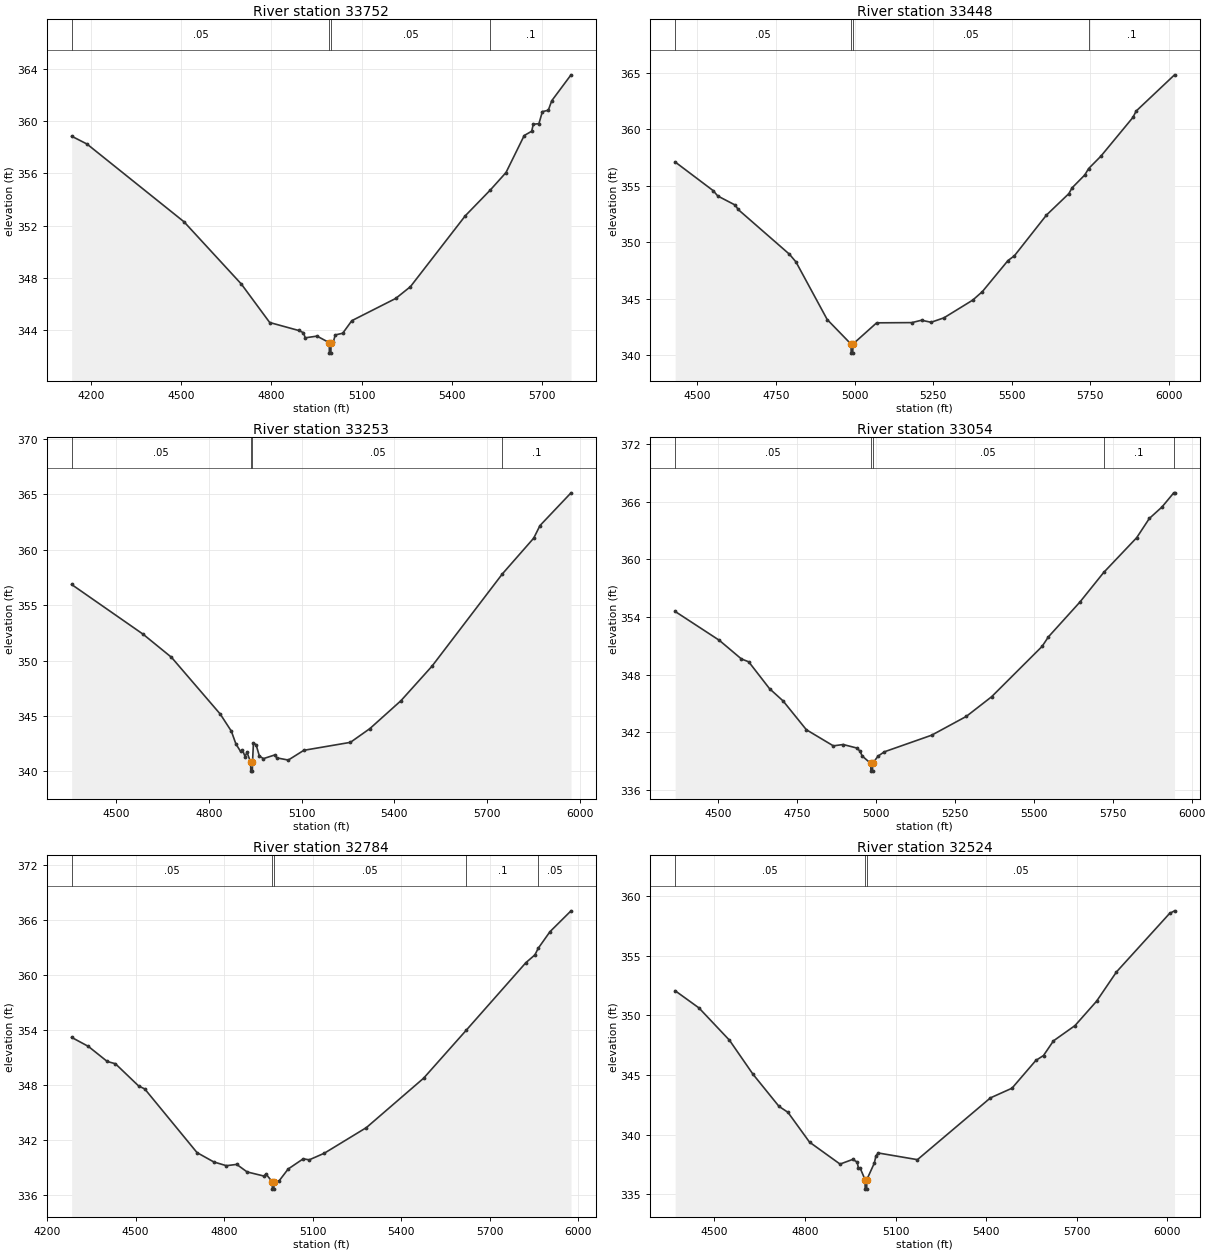
Type RM Length L Ch R = 1,33752,304,304,304
BEGIN DESCRIPTION:
Salt Branch 68.0
END DESCRIPTION:
XS GIS Cut Line= 3
      2137274.99     13419924.99      2136575.00     13419525.00
      2135775.01     13419225.00
#Sta/Elev= 30
  4135.9  358.84  4187.0  358.24  4509.5  352.30  4700.2  347.54  4794.5  344.60
  4891.0  343.99  4906.8  343.82  4912.6  343.43  4951.9  343.56  4992.5  343.06
  4993.0  342.26  4998.0  342.26  4998.5  343.06  5006.2  343.12  5012.4  343.65
  5037.3  343.78  5067.6  344.74  5213.6  346.44  5262.5  347.34  5445.0  352.76
  5528.2  354.73  5580.2  356.06  5640.8  358.89  5665.7  359.22  5671.0  359.75
  5689.7  359.80  5701.3  360.72  5720.9  360.82  5732.4  361.55  5796.5  363.53
#Mann=4,-1,0
  4135.9    0.05       0  4992.5    0.03       0  4998.5    0.05       0
  5528.2     0.1       0
Bank Sta=4992.5,4998.5
Exp/Cntr=0.3,0.1

Type RM Length L Ch R = 1,33448,195,195,195
BEGIN DESCRIPTION:
Salt Branch 67.0
END DESCRIPTION:
XS GIS Cut Line= 3
      2137225.01     13419725.01      2136775.00     13419375.00
      2135775.00     13419175.00
#Sta/Elev= 30
  4428.9  357.09  4550.2  354.55  4564.6  354.08  4620.7  353.27  4628.9  352.90
  4792.7  348.93  4813.5  348.25  4913.0  343.15  4988.8  340.98  4989.3  340.18
  4994.3  340.18  4994.8  340.98  5070.4  342.86  5182.6  342.88  5213.2  343.09
  5243.7  342.91  5284.5  343.30  5376.3  344.87  5406.9  345.62  5488.5  348.37
  5508.9  348.79  5610.9  352.39  5682.3  354.29  5692.5  354.80  5733.3  355.95
  5745.0  356.50  5784.2  357.60  5886.2  361.03  5896.4  361.59  6018.8  364.80
#Mann=4,-1,0
  4428.9    0.05       0  4988.8    0.03       0  4994.8    0.05       0
  5745.0     0.1       0
Bank Sta=4988.8,4994.8
Exp/Cntr=0.3,0.1

Type RM Length L Ch R = 1,33253,199,199,199
BEGIN DESCRIPTION:
Salt Branch 66.0
END DESCRIPTION:
XS GIS Cut Line= 3
      2137324.98     13419574.99      2136825.00     13419225.00
      2135824.99     13419125.00
#Sta/Elev= 30
  4356.4  356.87  4587.0  352.39  4679.4  350.29  4837.2  345.16  4873.0  343.62
  4887.8  342.46  4902.6  341.80  4908.7  341.94  4917.4  341.32  4923.5  341.72
  4935.4  340.81  4935.9  340.01  4940.9  340.01  4941.4  340.81  4944.5  342.57
  4953.2  342.38  4963.7  341.37  4976.8  341.14  5014.4  341.48  5019.5  341.21
  5057.2  341.01  5107.4  341.89  5258.1  342.61  5321.0  343.85  5421.5  346.37
  5522.0  349.49  5749.7  357.83  5851.1  361.06  5871.2  362.19  5971.7  365.15
#Mann=4,-1,0
  4356.4    0.05       0  4935.4    0.03       0  4941.4    0.05       0
  5749.7     0.1       0
Bank Sta=4935.4,4941.4
Exp/Cntr=0.3,0.1

Type RM Length L Ch R = 1,33054,270,270,270
BEGIN DESCRIPTION:
Salt Branch 65.0
END DESCRIPTION:
XS GIS Cut Line= 3
      2137325.00     13419325.00      2136825.00     13419025.00
      2135825.00     13419025.00
#Sta/Elev= 30
  4362.7  354.57  4502.6  351.57  4572.6  349.63  4595.9  349.33  4662.0  346.53
  4704.8  345.26  4778.6  342.26  4864.2  340.58  4895.3  340.72  4938.0  340.36
  4948.3  340.05  4955.8  339.52  4982.8  338.75  4983.3  337.95  4988.3  337.95
  4988.8  338.75  5005.8  339.51  5025.8  339.96  5175.8  341.69  5285.8  343.65
  5365.8  345.69  5525.8  350.93  5545.8  351.92  5645.8  355.55  5721.2  358.63
  5825.8  362.25  5865.8  364.25  5905.8  365.44  5943.3  366.92  5945.8  366.92
#Mann=5,-1,0
  4362.7    0.05       0  4982.8    0.03       0  4988.8    0.05       0
  5721.2     0.1       0  5943.3    0.05       0
Bank Sta=4982.8,4988.8
Exp/Cntr=0.3,0.1

Type RM Length L Ch R = 1,32784,260,260,260
BEGIN DESCRIPTION:
Salt Branch 64.0
END DESCRIPTION:
XS GIS Cut Line= 3
      2137325.02     13419225.02      2136825.00     13418775.00
      2135825.02     13418975.00
#Sta/Elev= 30
  4283.1  353.22  4339.6  352.24  4403.8  350.59  4431.5  350.34  4510.0  347.92
  4530.9  347.59  4708.0  340.64  4764.8  339.62  4807.4  339.21  4842.6  339.35
  4877.7  338.53  4934.5  338.08  4942.0  338.29  4963.0  337.45  4963.5  336.65
  4968.5  336.65  4969.0  337.45  4986.4  337.56  5017.0  338.85  5068.0  339.96
  5088.4  339.85  5139.4  340.57  5282.1  343.37  5475.9  348.76  5620.7  354.01
  5822.6  361.38  5853.2  362.23  5864.4  362.95  5904.2  364.76  5975.6  367.04
#Mann=5,-1,0
  4283.1    0.05       0  4963.0    0.03       0  4969.0    0.05       0
  5620.7     0.1       0  5864.4    0.05       0
Bank Sta=4963,4969
Exp/Cntr=0.3,0.1

Type RM Length L Ch R = 1,32524,302,302,302
BEGIN DESCRIPTION:
Salt Branch 63.0
END DESCRIPTION:
XS GIS Cut Line= 3
      2137324.98     13419124.97      2136975.00     13418625.00
      2135975.02     13418325.01
#Sta/Elev= 30
  4369.9  352.07  4448.8  350.63  4549.9  347.92  4627.5  345.08  4713.8  342.38
  4743.5  341.88  4815.0  339.38  4916.1  337.54  4958.0  337.93  4972.8  337.71
  4977.1  337.20  4982.8  337.20  4998.9  336.24  4999.4  335.44  5004.4  335.44
  5004.9  336.24  5029.8  337.63  5035.0  338.23  5042.8  338.47  5172.5  337.91
  5414.3  343.09  5485.7  343.90  5564.8  346.23  5590.1  346.64  5623.1  347.87
  5694.5  349.15  5765.8  351.19  5831.9  353.65  6007.7  358.55  6024.2  358.77
#Mann=3,-1,0
  4369.9    0.05       0  4998.9    0.03       0  5004.9    0.05       0
Bank Sta=4998.9,5004.9
Exp/Cntr=0.3,0.1

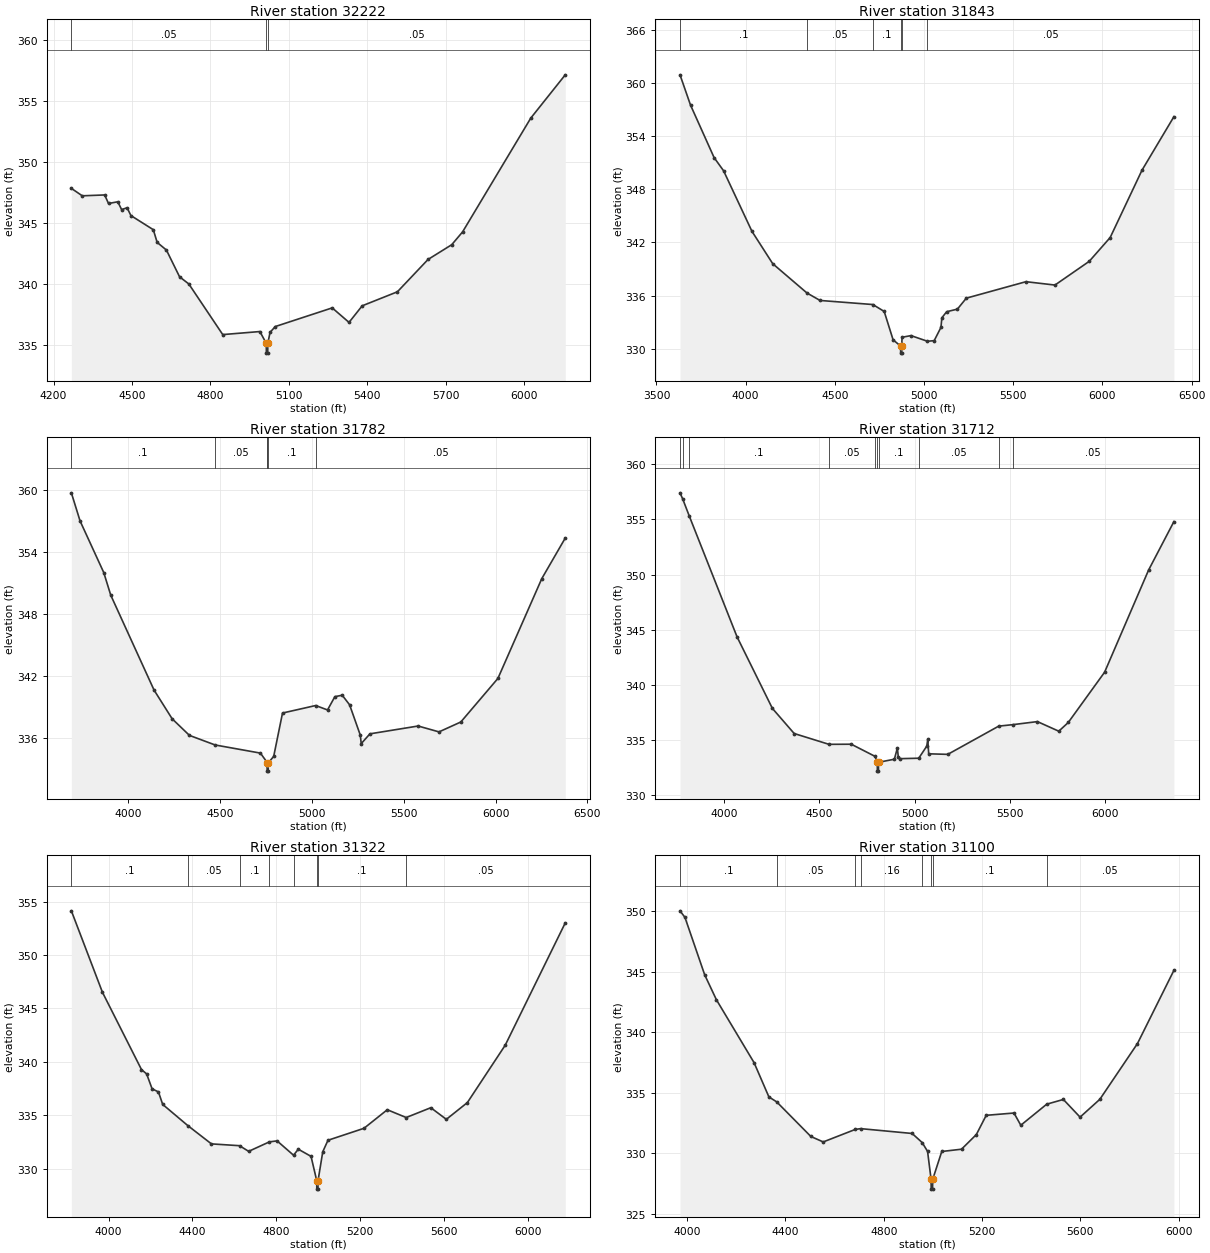
Type RM Length L Ch R = 1,32222,379,379,379
BEGIN DESCRIPTION:
Mapping XS ead0b7b5
END DESCRIPTION:
XS GIS Cut Line= 3
      2137624.69     13419053.60      2137192.37     13418462.43
      2136043.94     13418321.80
#Sta/Elev= 30
  4268.0  347.82  4309.7  347.21  4395.4  347.28  4410.1  346.58  4445.6  346.72
  4460.3  346.08  4481.2  346.23  4495.8  345.59  4581.5  344.43  4596.2  343.39
  4631.7  342.76  4681.9  340.57  4717.4  339.98  4847.1  335.83  4989.2  336.08
  5013.6  335.11  5014.1  334.31  5019.1  334.31  5019.6  335.11  5028.0  336.01
  5048.1  336.49  5265.9  338.02  5330.2  336.83  5380.6  338.19  5515.3  339.34
  5632.4  341.99  5723.1  343.20  5764.6  344.25  6025.4  353.58  6157.4  357.13
#Mann=3,-1,0
  4268.0    0.05       0  5013.6    0.03       0  5019.6    0.05       0
Bank Sta=5013.6,5019.6
Exp/Cntr=0.3,0.1

Type RM Length L Ch R = 1,31843,61,61,61
BEGIN DESCRIPTION:
Mapping XS b539f7d5
END DESCRIPTION:
XS GIS Cut Line= 4
      2138815.12     13418000.15      2137756.10     13418375.15
      2137207.49     13418350.84      2136128.84     13418156.61
#Sta/Elev= 30
  3631.9  360.93  3690.9  357.51  3823.0  351.58  3876.2  350.09  4035.2  343.25
  4151.8  339.59  4343.8  336.28  4417.1  335.44  4712.9  334.98  4776.5  334.20
  4826.5  330.99  4868.4  330.29  4868.9  329.49  4874.3  329.49  4874.8  330.29
  4876.6  331.28  4926.6  331.47  5019.0  330.83  5056.8  330.90  5094.7  332.40
  5099.7  333.48  5126.8  334.17  5186.9  334.46  5236.9  335.70  5571.2  337.56
  5733.8  337.18  5925.9  339.86  6043.3  342.55  6221.5  350.15  6400.5  356.20
#Mann=6,-1,0
  3631.9     0.1       0  4343.8    0.05       0  4712.9     0.1       0
  4868.4    0.07       0  4874.8     0.1       0  5019.0    0.05       0
Bank Sta=4868.4,4874.8
Exp/Cntr=0.3,0.1

Type RM Length L Ch R = 1,31782,70,70,70
BEGIN DESCRIPTION:
Mapping XS 45002517
END DESCRIPTION:
XS GIS Cut Line= 4
      2138780.36     13417979.33      2137679.71     13418312.65
      2137266.51     13418291.81      2136151.93     13418132.09
#Sta/Elev= 30
  3689.9  359.77  3737.3  357.04  3866.3  352.03  3904.5  349.83  4140.2  340.62
  4238.8  337.83  4332.9  336.22  4472.8  335.29  4719.5  334.50  4753.4  333.66
  4755.7  333.55  4756.2  332.75  4761.6  332.75  4762.1  333.55  4791.8  334.18
  4839.8  338.39  5020.5  339.12  5084.9  338.69  5125.0  339.98  5165.0  340.12
  5205.1  339.19  5263.3  336.25  5268.4  335.42  5315.8  336.37  5578.4  337.13
  5692.0  336.56  5810.8  337.52  6012.8  341.75  6251.8  351.44  6379.6  355.38
#Mann=6,-1,0
  3689.9     0.1       0  4472.8    0.05       0  4753.4     0.1       0
  4755.7    0.07       0  4762.1     0.1       0  5020.5    0.05       0
Bank Sta=4755.7,4762.1
Exp/Cntr=0.3,0.1

Type RM Length L Ch R = 1,31712,390,390,390
BEGIN DESCRIPTION:
Mapping XS 4be43d69
END DESCRIPTION:
XS GIS Cut Line= 4
      2138724.86     13417965.42      2137669.29     13418243.20
      2137283.88     13418218.90      2136172.77     13418111.26
#Sta/Elev= 30
  3768.3  357.41  3782.6  356.85  3817.8  355.27  4068.0  344.35  4253.4  337.87
  4367.9  335.59  4550.7  334.61  4667.8  334.62  4792.5  333.52  4804.5  332.98
  4805.0  332.18  4810.4  332.18  4810.9  332.98  4894.2  333.26  4909.9  334.27
  4914.9  333.45  4924.2  333.31  5022.2  333.35  5064.5  334.45  5069.5  335.07
  5074.5  333.75  5174.7  333.70  5442.3  336.26  5514.9  336.39  5645.5  336.67
  5757.7  335.80  5807.5  336.59  5998.4  341.15  6229.4  350.41  6362.3  354.80
#Mann=10,-1,0
  3768.3     0.1       0  3782.6    0.05       0  3817.8     0.1       0
  4550.7    0.05       0  4792.5     0.1       0  4804.5    0.07       0
  4810.9     0.1       0  5022.2    0.05       0  5442.3     0.1       0
  5514.9    0.05       0
Bank Sta=4804.5,4810.9
Exp/Cntr=0.3,0.1

Type RM Length L Ch R = 1,31322,222,222,222
BEGIN DESCRIPTION:
Mapping XS 52ea476e
END DESCRIPTION:
XS GIS Cut Line= 4
      2138585.91     13417818.66      2137627.60     13417957.54
      2136992.18     13418047.82      2136249.58     13417992.30
#Sta/Elev= 30
  3822.8  354.15  3970.9  346.52  4157.2  339.27  4181.6  338.87  4207.7  337.47
  4238.0  337.18  4258.2  336.01  4378.2  334.02  4490.6  332.31  4624.6  332.14
  4668.1  331.61  4767.1  332.50  4803.7  332.59  4882.0  331.25  4904.9  331.81
  4965.5  331.14  4992.6  328.87  4993.1  328.07  4998.5  328.07  4999.0  328.87
  5021.4  331.57  5046.3  332.65  5218.0  333.77  5329.1  335.51  5419.2  334.78
  5536.6  335.70  5610.6  334.61  5710.9  336.18  5891.4  341.56  6177.6  353.02
#Mann=8,-1,0
  3822.8     0.1       0  4378.2    0.05       0  4624.6     0.1       0
  4767.1    0.16       0  4882.0     0.1       0  4992.6    0.07       0
  4999.0     0.1       0  5419.2    0.05       0
Bank Sta=4992.6,4999
Exp/Cntr=0.3,0.1

Type RM Length L Ch R = 1,31100,300,300,300
BEGIN DESCRIPTION:
Salt Branch 61.0
END DESCRIPTION:
XS GIS Cut Line= 3
      2138474.99     13417675.00      2137475.00     13417775.00
      2136474.97     13417875.00
#Sta/Elev= 30
  3970.7  350.03  3990.8  349.49  4071.2  344.74  4118.9  342.68  4272.2  337.48
  4332.5  334.65  4364.3  334.24  4503.3  331.38  4553.6  330.93  4683.5  331.96
  4705.7  332.03  4915.4  331.63  4956.2  330.88  4978.2  330.15  4992.6  327.83
  4993.1  327.03  4998.5  327.03  4999.0  327.83  5036.0  330.14  5116.4  330.33
  5176.7  331.54  5216.9  333.13  5329.9  333.32  5357.6  332.31  5463.1  334.05
  5530.9  334.44  5598.8  332.98  5679.2  334.45  5832.4  339.06  5980.7  345.11
#Mann=8,-1,0
  3970.7     0.1       0  4364.3    0.05       0  4683.5     0.1       0
  4705.7    0.16       0  4956.2     0.1       0  4992.6    0.07       0
  4999.0     0.1       0  5463.1    0.05       0
Bank Sta=4992.6,4999
Exp/Cntr=0.3,0.1