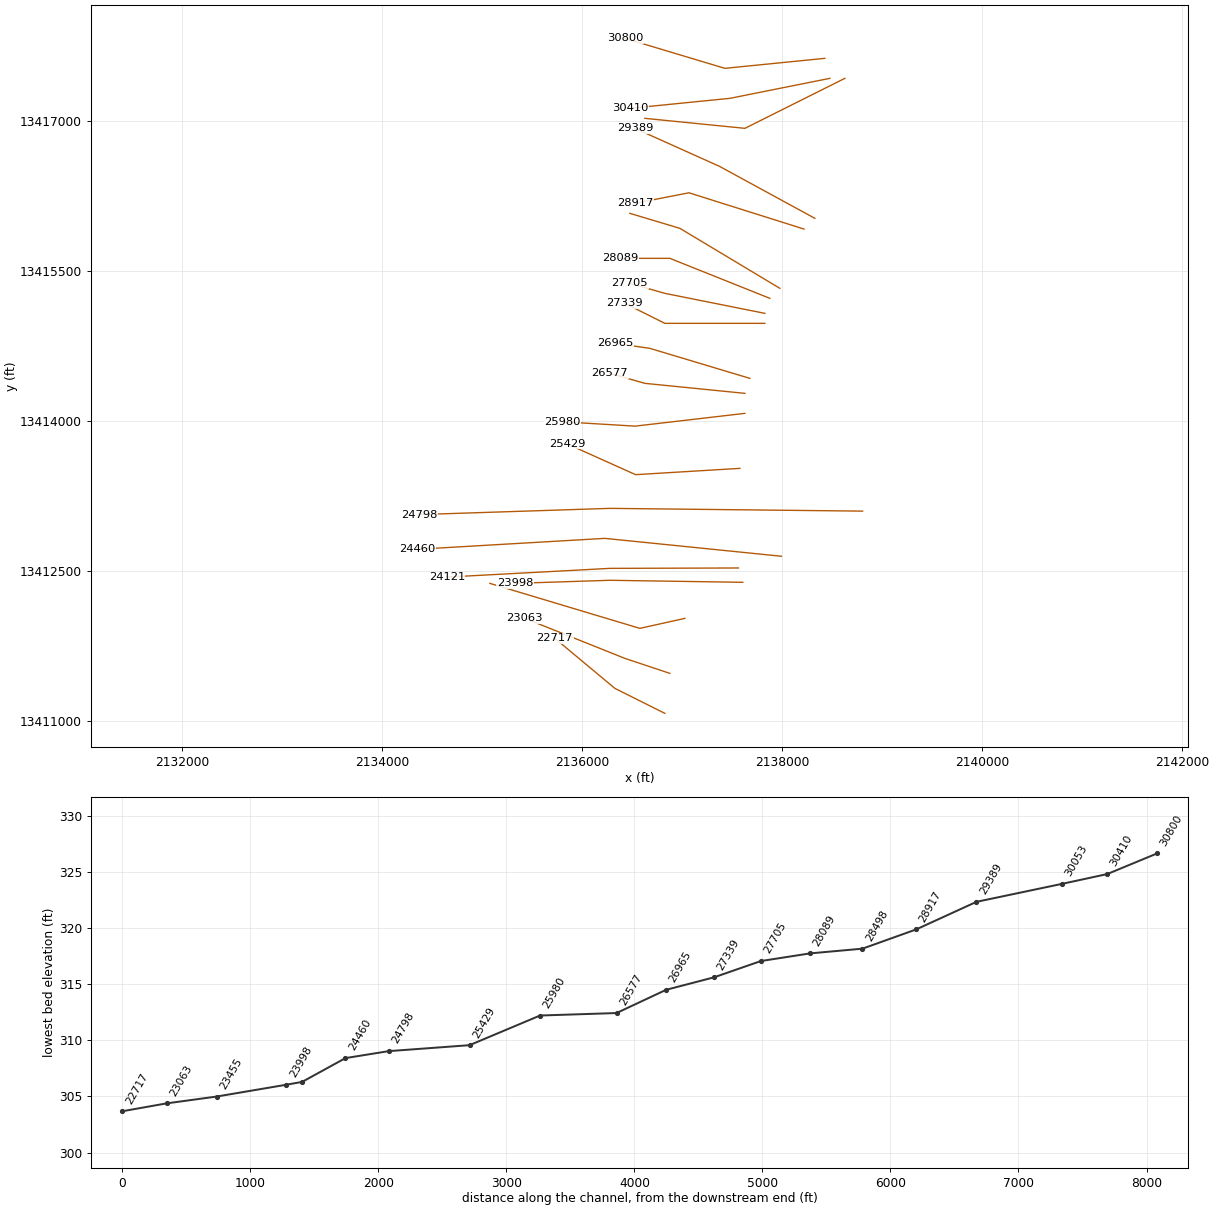
HEC-RAS study Salt Branch.prj: Salt Branch Base Level Engineering

--- Salt Branch.g01 (geometry) --- (continued)

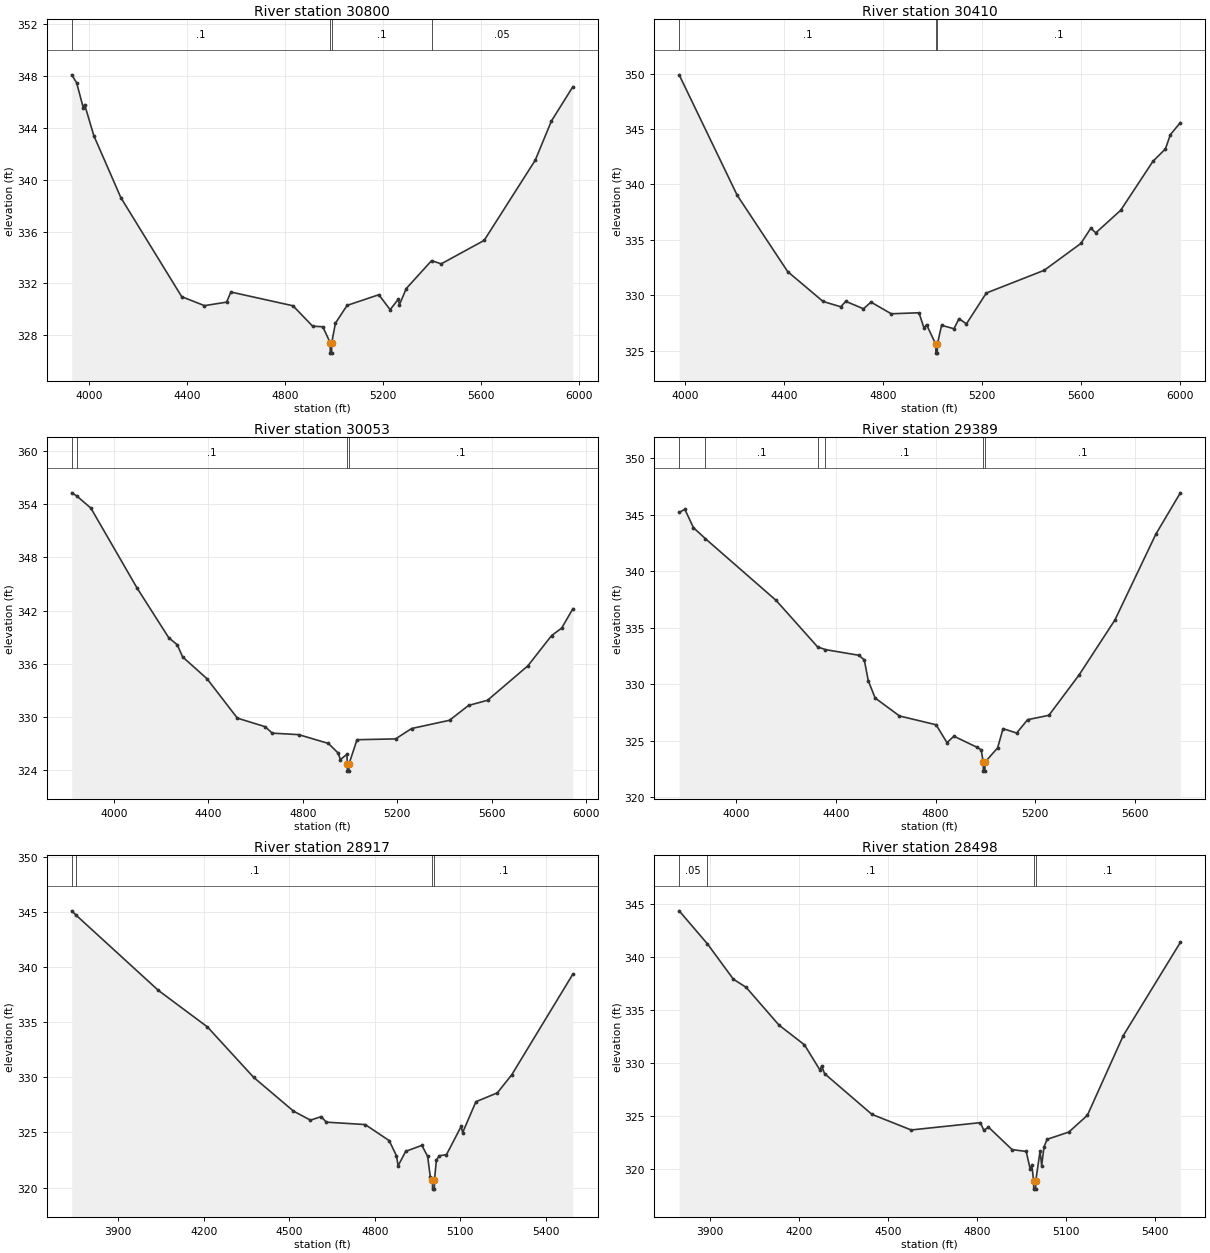
Type RM Length L Ch R = 1,30800,390,390,390
BEGIN DESCRIPTION:
Salt Branch 60.0
END DESCRIPTION:
XS GIS Cut Line= 3
      2138424.98     13417625.00      2137425.00     13417525.00
      2136425.00     13417825.00
#Sta/Elev= 30
  3928.0  348.08  3948.1  347.47  3975.7  345.50  3980.7  345.79  4018.4  343.39
  4129.0  338.61  4377.7  330.98  4470.7  330.29  4561.1  330.56  4578.7  331.34
  4832.5  330.28  4912.9  328.71  4954.7  328.66  4984.6  327.43  4985.1  326.63
  4990.5  326.63  4991.0  327.43  5006.1  328.94  5053.9  330.31  5183.5  331.13
  5229.7  329.98  5262.7  330.77  5267.9  330.37  5295.8  331.61  5399.3  333.76
  5438.5  333.51  5614.2  335.32  5823.0  341.50  5889.1  344.52  5977.0  347.17
#Mann=4,-1,0
  3928.0     0.1       0  4984.6    0.07       0  4991.0     0.1       0
  5399.3    0.05       0
Bank Sta=4984.6,4991
Exp/Cntr=0.3,0.1

Type RM Length L Ch R = 1,30410,357,357,357
BEGIN DESCRIPTION:
Salt Branch 59.0
END DESCRIPTION:
XS GIS Cut Line= 3
      2138475.02     13417425.00      2137475.00     13417225.00
      2136475.01     13417125.00
#Sta/Elev= 30
  3976.0  349.89  4210.6  339.02  4414.5  332.14  4557.3  329.45  4628.7  328.97
  4649.1  329.46  4720.5  328.79  4751.1  329.39  4832.7  328.34  4944.8  328.43
  4965.2  327.05  4975.4  327.36  5012.7  325.59  5013.2  324.79  5018.7  324.79
  5019.2  325.59  5036.0  327.30  5086.3  326.99  5106.4  327.90  5136.5  327.43
  5216.9  330.21  5450.6  332.26  5598.8  334.68  5639.0  336.06  5659.1  335.64
  5759.6  337.67  5890.3  342.10  5940.5  343.21  5960.6  344.50  6000.8  345.58
#Mann=3,-1,0
  3976.0     0.1       0  5012.7    0.07       0  5019.2     0.1       0
Bank Sta=5012.7,5019.2
Exp/Cntr=0.3,0.1

Type RM Length L Ch R = 1,30053,664,664,664
BEGIN DESCRIPTION:
Salt Branch 58.0
END DESCRIPTION:
XS GIS Cut Line= 3
      2138625.02     13417425.01      2137625.00     13416925.00
      2136625.05     13417025.00
#Sta/Elev= 30
  3820.9  355.26  3841.2  354.93  3902.0  353.54  4097.6  344.54  4231.8  338.94
  4268.1  338.14  4290.5  336.78  4393.9  334.32  4522.5  329.88  4639.9  328.92
  4670.6  328.19  4782.4  328.02  4908.2  327.03  4949.0  325.96  4959.1  325.21
  4986.7  325.81  4988.2  324.71  4988.7  323.91  4994.8  323.91  4995.3  324.71
  5029.4  327.45  5192.7  327.54  5260.6  328.71  5421.4  329.64  5501.8  331.31
  5582.2  331.89  5753.0  335.77  5853.5  339.18  5896.2  340.02  5943.9  342.21
#Mann=4,-1,0
  3820.9    0.05       0  3841.2     0.1       0  4988.2    0.07       0
  4995.3     0.1       0
Bank Sta=4988.2,4995.3
Exp/Cntr=0.3,0.1

Type RM Length L Ch R = 1,29389,472,472,472
BEGIN DESCRIPTION:
Salt Branch 57.0
END DESCRIPTION:
XS GIS Cut Line= 3
      2138324.99     13416025.01      2137370.68     13416545.28
      2136525.03     13416924.99
#Sta/Elev= 30
  3770.0  345.21  3792.8  345.48  3827.4  343.86  3875.6  342.88  4159.7  337.42
  4325.9  333.32  4357.5  333.07  4492.0  332.57  4513.8  332.16  4530.0  330.31
  4557.5  328.79  4655.3  327.20  4802.4  326.42  4846.1  324.84  4874.1  325.41
  4966.7  324.43  4983.7  324.20  4991.7  323.12  4992.3  322.32  4998.4  322.32
  4998.9  323.12  5049.5  324.37  5071.4  326.08  5126.2  325.69  5170.1  326.87
  5255.7  327.26  5377.0  330.83  5520.9  335.69  5685.3  343.28  5783.9  346.94
#Mann=6,-1,0
  3770.0    0.05       0  3875.6     0.1       0  4325.9    0.05       0
  4357.5     0.1       0  4991.7    0.07       0  4998.9     0.1       0
Bank Sta=4991.7,4998.9
Exp/Cntr=0.3,0.1

Type RM Length L Ch R = 1,28917,419,419,419
BEGIN DESCRIPTION:
Salt Branch 56.0
END DESCRIPTION:
XS GIS Cut Line= 3
      2138216.72     13415917.71      2137065.64     13416280.57
      2136524.97     13416174.99
#Sta/Elev= 30
  3737.2  345.12  3753.2  344.71  4041.0  337.90  4213.3  334.58  4375.1  330.01
  4515.0  326.94  4574.5  326.12  4612.1  326.44  4630.2  325.94  4766.5  325.72
  4850.4  324.27  4876.2  322.89  4881.9  321.98  4908.5  323.29  4965.2  323.83
  4985.5  322.84  4994.9  320.96  5002.3  320.66  5002.8  319.86  5009.0  319.86
  5009.5  320.66  5016.1  322.49  5026.3  322.89  5051.6  322.99  5103.2  325.56
  5108.3  324.99  5154.7  327.79  5230.1  328.60  5281.0  330.26  5495.0  339.38
#Mann=4,-1,0
  3737.2    0.05       0  3753.2     0.1       0  5002.3    0.07       0
  5009.5     0.1       0
Bank Sta=5002.3,5009.5
Exp/Cntr=0.3,0.1

Type RM Length L Ch R = 1,28498,409,409,409
BEGIN DESCRIPTION:
Salt Branch 55.0
END DESCRIPTION:
XS GIS Cut Line= 3
      2137975.02     13415324.99      2136975.00     13415925.00
      2136475.03     13416074.99
#Sta/Elev= 30
  3797.0  344.35  3892.2  341.24  3979.7  337.91  4022.5  337.15  4133.3  333.59
  4218.8  331.74  4271.3  329.36  4277.1  329.74  4286.8  329.02  4446.2  325.19
  4578.4  323.72  4811.6  324.41  4823.3  323.68  4838.8  323.99  4918.5  321.87
  4965.8  321.70  4979.7  320.01  4985.0  320.39  4990.9  318.95  4991.4  318.15
  4997.6  318.15  4998.2  318.95  5012.8  321.75  5018.0  320.36  5025.9  322.12
  5036.3  322.84  5109.4  323.52  5172.0  325.10  5293.0  332.61  5485.2  341.38
#Mann=4,-1,0
  3797.0    0.05       0  3892.2     0.1       0  4990.9    0.07       0
  4998.2     0.1       0
Bank Sta=4990.9,4998.2
Exp/Cntr=0.3,0.1

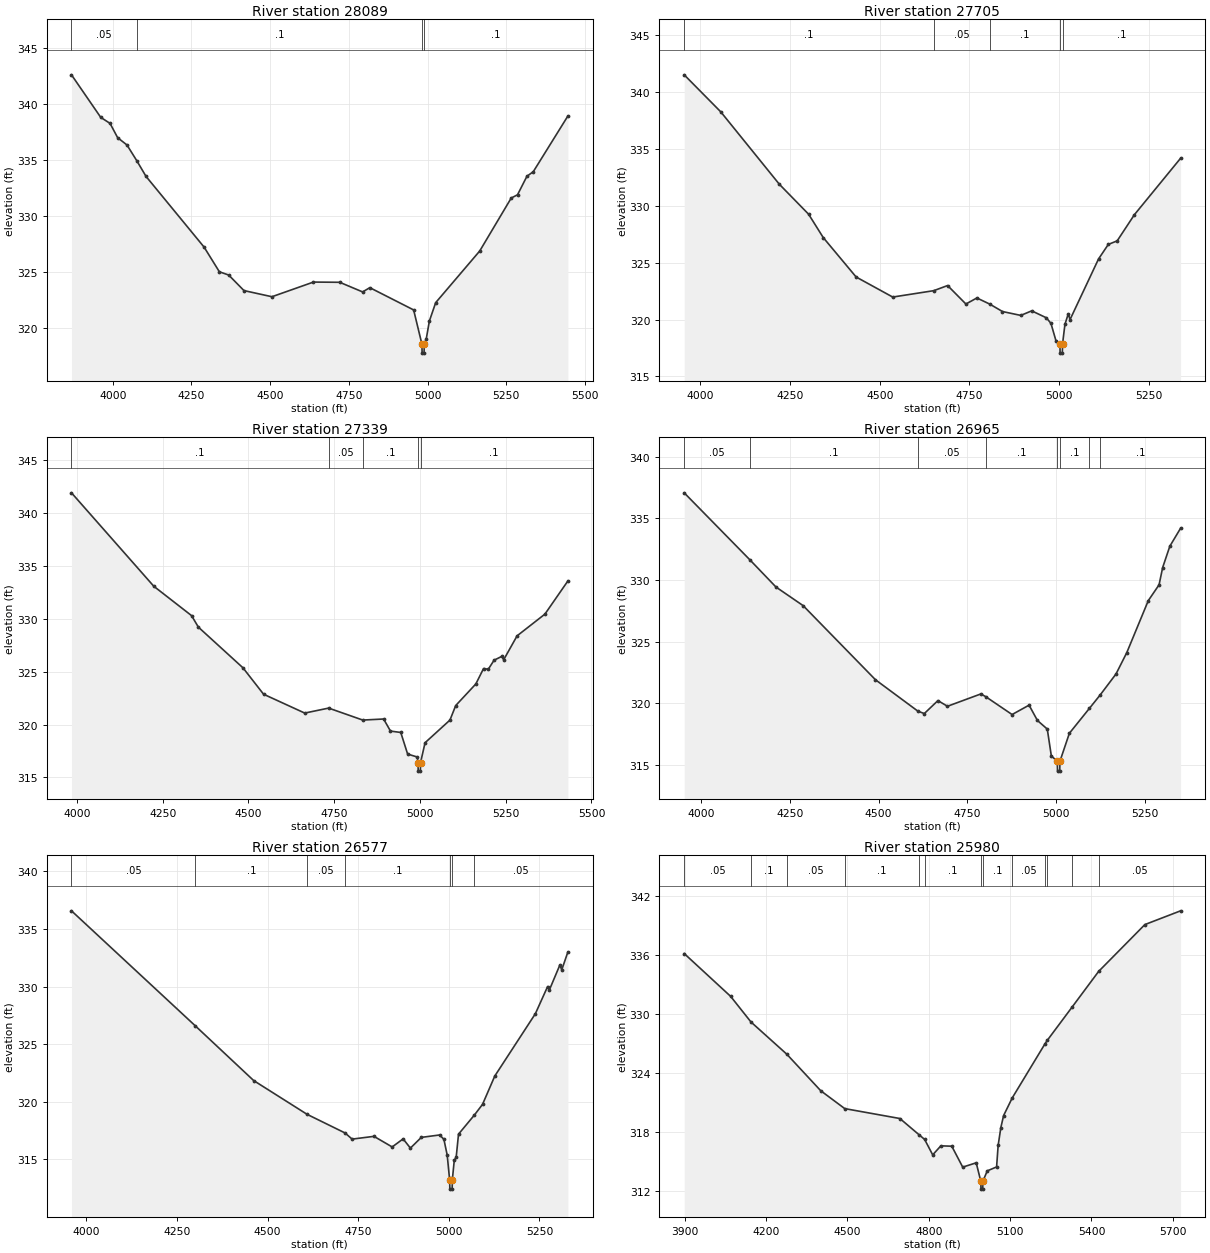
Type RM Length L Ch R = 1,28089,384,384,384
BEGIN DESCRIPTION:
Salt Branch 54.0
END DESCRIPTION:
XS GIS Cut Line= 3
      2137874.97     13415225.01      2136875.00     13415625.00
      2136375.00     13415625.00
#Sta/Elev= 30
  3868.8  342.60  3961.7  338.80  3991.3  338.26  4015.5  336.98  4045.1  336.33
  4075.9  334.94  4105.7  333.52  4290.2  327.20  4338.6  325.00  4368.2  324.71
  4416.7  323.32  4505.6  322.77  4637.5  324.08  4721.0  324.06  4793.7  323.20
  4816.6  323.58  4955.8  321.59  4982.1  318.53  4982.7  317.73  4988.9  317.73
  4989.4  318.53  4995.8  318.99  5005.8  320.60  5025.8  322.24  5165.8  326.86
  5265.8  331.59  5285.8  331.88  5315.8  333.54  5335.8  333.94  5445.8  338.92
#Mann=4,-1,0
  3868.8    0.05       0  4075.9     0.1       0  4982.1    0.07       0
  4989.4     0.1       0
Bank Sta=4982.1,4989.4
Exp/Cntr=0.3,0.1

Type RM Length L Ch R = 1,27705,366,366,366
BEGIN DESCRIPTION:
Salt Branch 53.0
END DESCRIPTION:
XS GIS Cut Line= 3
      2137825.03     13415074.99      2136825.00     13415275.00
      2136475.03     13415374.99
#Sta/Elev= 30
  3955.0  341.47  4057.0  338.22  4220.2  331.87  4301.8  329.24  4342.6  327.19
  4434.3  323.73  4536.3  321.97  4650.6  322.53  4689.3  322.98  4740.3  321.36
  4770.9  321.89  4806.9  321.35  4842.3  320.70  4893.2  320.36  4923.8  320.76
  4964.6  320.15  4977.4  319.66  4991.7  318.10  5002.4  317.85  5002.9  317.05
  5009.1  317.05  5009.7  317.85  5016.4  319.58  5025.5  320.48  5030.7  320.00
  5110.0  325.31  5137.3  326.59  5162.0  326.90  5210.1  329.20  5338.8  334.15
#Mann=5,-1,0
  3955.0     0.1       0  4650.6    0.05       0  4806.9     0.1       0
  5002.4    0.07       0  5009.7     0.1       0
Bank Sta=5002.4,5009.7
Exp/Cntr=0.3,0.1

Type RM Length L Ch R = 1,27339,374,374,374
BEGIN DESCRIPTION:
Salt Branch 52.0
END DESCRIPTION:
XS GIS Cut Line= 3
      2137825.02     13414975.00      2136825.00     13414975.00
      2136425.03     13415174.98
#Sta/Elev= 30
  3984.1  341.87  4224.1  333.05  4334.1  330.28  4354.1  329.19  4484.1  325.35
  4544.1  322.86  4664.1  321.08  4733.9  321.55  4833.3  320.42  4894.1  320.52
  4914.1  319.38  4944.1  319.25  4964.1  317.21  4992.5  316.93  4994.4  316.40
  4995.0  315.60  5001.2  315.60  5001.7  316.40  5014.9  318.28  5087.5  320.42
  5104.3  321.79  5163.0  323.83  5185.4  325.28  5199.3  325.22  5216.1  326.07
  5238.5  326.43  5244.1  326.11  5283.2  328.37  5364.3  330.42  5431.3  333.55
#Mann=5,-1,0
  3984.1     0.1       0  4733.9    0.05       0  4833.3     0.1       0
  4994.4    0.07       0  5001.7     0.1       0
Bank Sta=4994.4,5001.7
Exp/Cntr=0.3,0.1

Type RM Length L Ch R = 1,26965,388,388,388
BEGIN DESCRIPTION:
Salt Branch 51.0
END DESCRIPTION:
XS GIS Cut Line= 3
      2137674.97     13414425.01      2136675.00     13414725.00
      2136325.05     13414774.99
#Sta/Elev= 30
  3952.7  337.06  4137.5  331.63  4211.1  329.42  4287.6  327.91  4491.2  321.90
  4610.8  319.35  4628.7  319.16  4667.0  320.21  4693.9  319.75  4787.9  320.75
  4801.5  320.53  4875.8  319.08  4923.6  319.84  4947.1  318.60  4974.9  317.90
  4986.3  315.72  5003.1  315.29  5003.7  314.49  5009.9  314.49  5010.5  315.29
  5037.1  317.56  5093.5  319.58  5123.6  320.66  5168.4  322.37  5198.7  324.10
  5259.3  328.32  5289.6  329.60  5299.7  331.00  5319.9  332.73  5350.2  334.19
#Mann=8,-1,0
  3952.7    0.05       0  4137.5     0.1       0  4610.8    0.05       0
  4801.5     0.1       0  5003.1    0.07       0  5010.5     0.1       0
  5093.5    0.05       0  5123.6     0.1       0
Bank Sta=5003.1,5010.5
Exp/Cntr=0.3,0.1

Type RM Length L Ch R = 1,26577,597,597,597
BEGIN DESCRIPTION:
Salt Branch 50.0
END DESCRIPTION:
XS GIS Cut Line= 3
      2137625.04     13414275.00      2136625.00     13414375.00
      2136275.03     13414474.99
#Sta/Elev= 30
  3959.4  336.57  4301.2  326.58  4461.9  321.84  4609.2  318.91  4714.1  317.29
  4733.3  316.76  4793.6  317.00  4843.8  316.08  4874.0  316.78  4894.1  315.98
  4924.2  316.91  4974.8  317.12  4986.5  316.74  4995.6  315.37  5002.3  313.22
  5002.9  312.42  5009.2  312.42  5009.7  313.22  5015.1  314.93  5020.3  315.17
  5026.8  317.19  5070.6  318.85  5093.1  319.78  5126.9  322.24  5238.7  327.64
  5272.5  330.00  5277.7  329.73  5306.3  331.87  5311.5  331.45  5328.4  333.00
#Mann=7,-1,0
  3959.4    0.05       0  4301.2     0.1       0  4609.2    0.05       0
  4714.1     0.1       0  5002.3    0.07       0  5009.7     0.1       0
  5070.6    0.05       0
Bank Sta=5002.3,5009.7
Exp/Cntr=0.3,0.1

Type RM Length L Ch R = 1,25980,551,551,551
BEGIN DESCRIPTION:
Salt Branch 49.0
END DESCRIPTION:
XS GIS Cut Line= 3
      2137625.01     13414075.00      2136527.44     13413947.23
      2135803.52     13413990.64
#Sta/Elev= 30
  3898.4  336.19  4069.6  331.83  4144.6  329.22  4276.7  325.94  4401.8  322.22
  4490.3  320.40  4693.7  319.39  4764.2  317.74  4784.9  317.26  4814.6  315.69
  4844.8  316.61  4885.0  316.57  4925.3  314.44  4975.0  314.88  4992.0  313.00
  4992.6  312.20  4999.0  312.20  4999.6  313.00  5015.8  314.06  5050.2  314.46
  5055.9  316.65  5065.9  318.47  5076.0  319.69  5107.9  321.49  5229.1  327.02
  5237.6  327.37  5327.8  330.71  5426.4  334.37  5596.9  339.14  5728.6  340.54
#Mann=13,-1,0
  3898.4    0.05       0  4144.6     0.1       0  4276.7    0.05       0
  4490.3     0.1       0  4764.2    0.05       0  4784.9     0.1       0
  4992.0    0.07       0  4999.6     0.1       0  5107.9    0.05       0
  5229.1     0.1       0  5237.6    0.05       0  5327.8     0.1       0
  5426.4    0.05       0
Bank Sta=4992,4999.6
Exp/Cntr=0.3,0.1

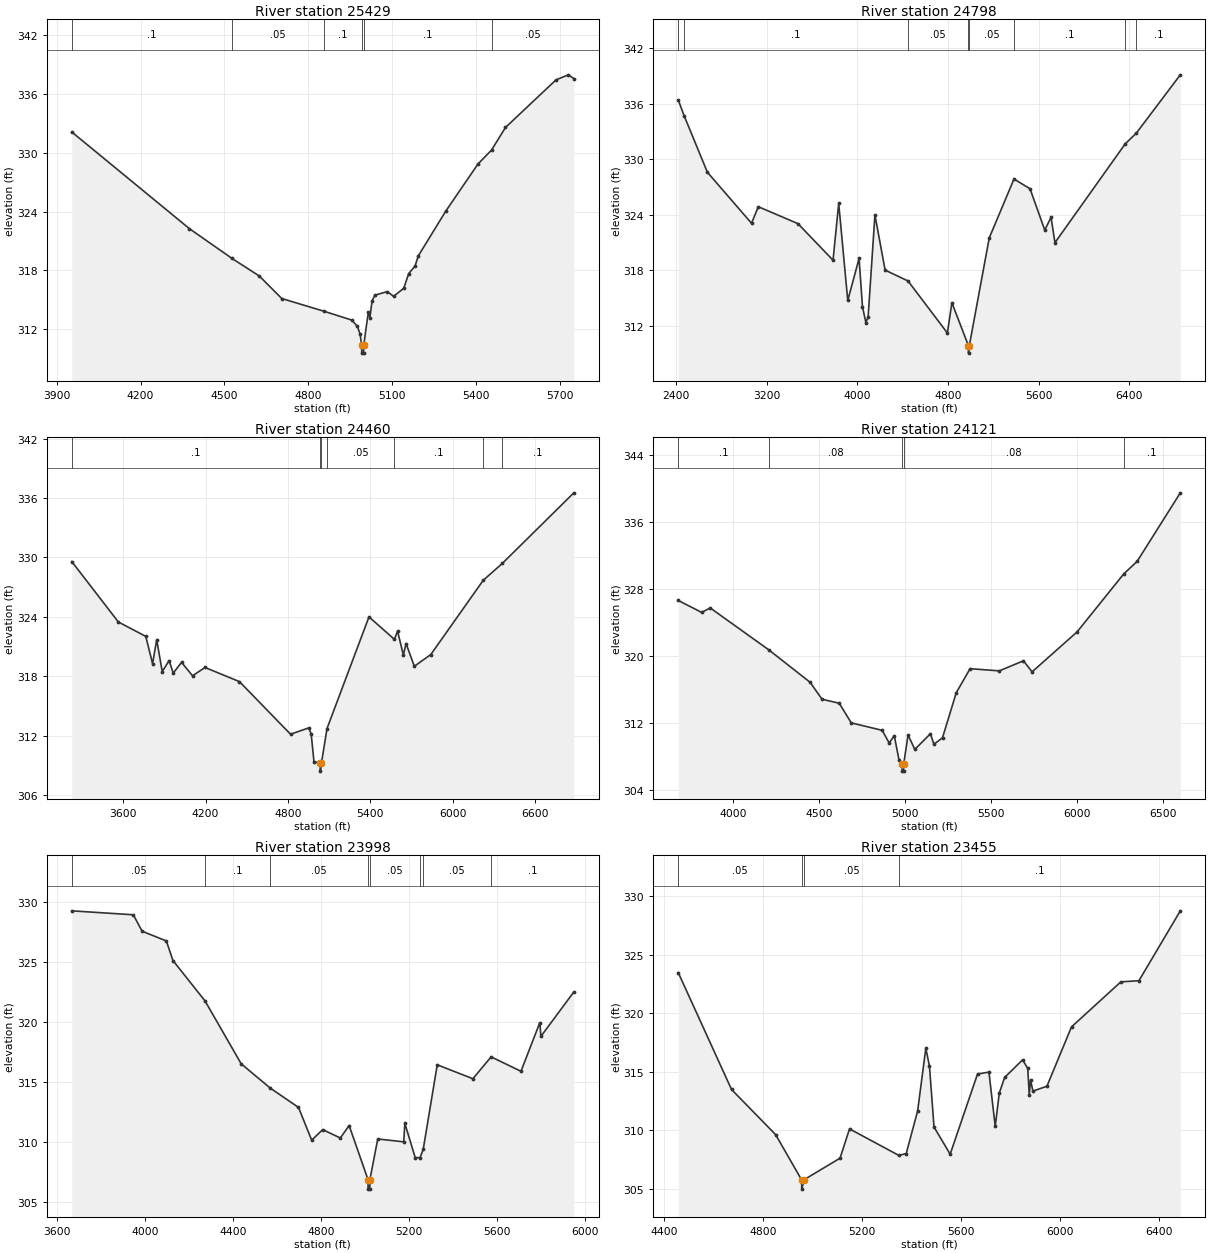
Type RM Length L Ch R = 1,25429,631,631,631
BEGIN DESCRIPTION:
Salt Branch 47.0
END DESCRIPTION:
XS GIS Cut Line= 3
      2137575.05     13413525.00      2136532.36     13413461.99
      2135846.60     13413770.15
#Sta/Elev= 30
  3953.7  332.12  4374.5  322.26  4526.5  319.23  4625.0  317.42  4705.1  315.13
  4855.2  313.84  4955.6  312.93  4975.6  312.29  4985.6  311.48  4990.7  310.36
  4991.3  309.56  4997.7  309.56  4998.3  310.36  5014.8  313.75  5020.3  313.17
  5028.3  314.89  5038.0  315.47  5083.1  315.84  5105.0  315.35  5141.6  316.18
  5159.3  317.68  5181.8  318.43  5193.4  319.47  5291.5  324.03  5407.3  328.86
  5455.8  330.28  5505.5  332.58  5686.1  337.43  5730.4  337.95  5750.1  337.57
#Mann=6,-1,0
  3953.7     0.1       0  4526.5    0.05       0  4855.2     0.1       0
  4990.7    0.07       0  4998.3     0.1       0  5455.8    0.05       0
Bank Sta=4990.7,4998.3
Exp/Cntr=0.3,0.1

Type RM Length L Ch R = 1,24798,338,338,338
BEGIN DESCRIPTION:
Salt Branch 46.0
END DESCRIPTION:
XS GIS Cut Line= 3
      2138802.37     13413097.41      2136275.00     13413125.00
      2134368.23     13413062.74
#Sta/Elev= 30
  2416.9  336.42  2469.3  334.70  2674.3  328.60  3064.3  323.08  3124.3  324.87
  3474.3  323.04  3784.3  319.08  3834.4  325.23  3914.4  314.73  4014.4  319.27
  4044.4  314.06  4074.4  312.33  4094.4  312.96  4154.4  323.98  4244.4  318.01
  4446.5  316.84  4794.4  311.21  4834.4  314.48  4980.6  309.83  4981.2  309.03
  4988.2  309.83  5164.5  321.50  5383.0  327.87  5524.7  326.81  5654.8  322.34
  5710.2  323.73  5744.8  320.98  6365.2  331.67  6463.5  332.83  6852.2  339.14
#Mann=8,-1,0
  2416.9    0.05       0  2469.3     0.1       0  4446.5    0.05       0
  4980.6   0.035       0  4988.2    0.05       0  5383.0     0.1       0
  6365.2    0.05       0  6463.5     0.1       0
Bank Sta=4980.6,4988.2
Exp/Cntr=0.3,0.1

Type RM Length L Ch R = 1,24460,339,339,339
BEGIN DESCRIPTION:
Salt Branch 45.0
END DESCRIPTION:
XS GIS Cut Line= 3
      2137990.65     13412646.02      2136225.00     13412825.00
      2134344.89     13412715.47
#Sta/Elev= 30
  3225.3  329.58  3565.0  323.47  3764.6  322.02  3814.0  319.26  3844.1  321.69
  3884.3  318.47  3934.6  319.57  3964.7  318.31  4025.0  319.40  4105.4  318.04
  4195.9  318.88  4447.2  317.45  4819.1  312.14  4952.6  312.78  4969.8  312.15
  4989.9  309.37  5035.6  309.21  5036.4  308.41  5044.5  309.21  5084.9  312.71
  5390.7  323.99  5576.2  321.72  5598.9  322.55  5641.1  320.15  5661.1  321.30
  5721.2  319.00  5841.4  320.19  6223.5  327.69  6362.2  329.39  6883.3  336.52
#Mann=7,-1,0
  3225.3     0.1       0  5035.6    0.07       0  5044.5     0.1       0
  5084.9    0.05       0  5576.2     0.1       0  6223.5    0.05       0
  6362.2     0.1       0
Bank Sta=5035.6,5044.5
Exp/Cntr=0.3,0.1

Type RM Length L Ch R = 1,24121,123,123,123
BEGIN DESCRIPTION:
Salt Branch 44.0
END DESCRIPTION:
XS GIS Cut Line= 3
      2137561.00     13412528.83      2136275.00     13412525.00
      2134644.34     13412437.69
#Sta/Elev= 30
  3681.1  326.63  3817.1  325.21  3867.1  325.74  4208.5  320.73  4447.1  316.89
  4517.1  314.86  4617.1  314.38  4687.1  312.04  4867.1  311.15  4907.1  309.65
  4937.1  310.51  4964.6  307.63  4982.7  307.09  4983.5  306.29  4990.8  306.29
  4991.6  307.09  5017.2  310.60  5056.4  308.88  5147.4  310.75  5167.4  309.49
  5217.5  310.27  5297.6  315.64  5377.7  318.50  5547.9  318.24  5688.1  319.44
  5738.2  318.12  5999.7  322.88  6271.8  329.81  6349.1  331.29  6600.1  339.46
#Mann=5,-1,0
  3681.1     0.1       0  4208.5    0.08       0  4982.7    0.07       0
  4991.6    0.08       0  6271.8     0.1       0
Bank Sta=4982.7,4991.6
Exp/Cntr=0.3,0.1

Type RM Length L Ch R = 1,23998,543,543,543
BEGIN DESCRIPTION:
Salt Branch 43.0
END DESCRIPTION:
XS GIS Cut Line= 3
      2137604.44     13412385.60      2136272.99     13412405.81
      2135324.99     13412375.00
#Sta/Elev= 30
  3668.4  329.23  3947.9  328.90  3987.9  327.53  4097.9  326.72  4127.9  325.09
  4273.7  321.72  4437.9  316.48  4569.8  314.46  4698.0  312.85  4758.0  310.12
  4808.0  311.00  4888.0  310.30  4928.0  311.34  5013.6  306.84  5014.4  306.04
  5021.7  306.04  5022.5  306.84  5058.0  310.22  5176.0  309.98  5181.0  311.52
  5228.1  308.67  5250.0  308.66  5264.5  309.35  5328.2  316.40  5490.0  315.24
  5572.9  317.06  5708.4  315.86  5794.0  319.91  5799.0  318.77  5948.5  322.47
#Mann=8,-1,0
  3668.4    0.05       0  4273.7     0.1       0  4569.8    0.05       0
  5013.6   0.035       0  5022.5    0.05       0  5250.0     0.1       0
  5264.5    0.05       0  5572.9     0.1       0
Bank Sta=5013.6,5022.5
Exp/Cntr=0.3,0.1

Type RM Length L Ch R = 1,23455,392,392,392
BEGIN DESCRIPTION:
Salt Branch 42.0
END DESCRIPTION:
XS GIS Cut Line= 3
      2137024.99     13412025.00      2136575.00     13411925.00
      2135075.02     13412375.00
#Sta/Elev= 30
  4457.5  323.46  4672.6  313.49  4850.6  309.64  4955.3  305.79  4956.3  304.99
  4965.2  305.79  5110.7  307.63  5149.0  310.13  5347.8  307.87  5377.8  308.02
  5424.0  311.66  5457.0  317.01  5471.8  315.48  5490.1  310.29  5555.3  307.97
  5665.8  314.81  5711.9  314.97  5737.2  310.35  5753.7  313.19  5775.4  314.52
  5847.7  316.02  5868.5  315.29  5874.6  313.03  5879.8  314.31  5889.4  313.35
  5946.0  313.77  6045.2  318.83  6244.4  322.67  6317.5  322.77  6484.5  328.73
#Mann=4,-1,0
  4457.5    0.05       0  4955.3    0.03       0  4965.2    0.05       0
  5347.8     0.1       0
Bank Sta=4955.3,4965.2
Exp/Cntr=0.3,0.1

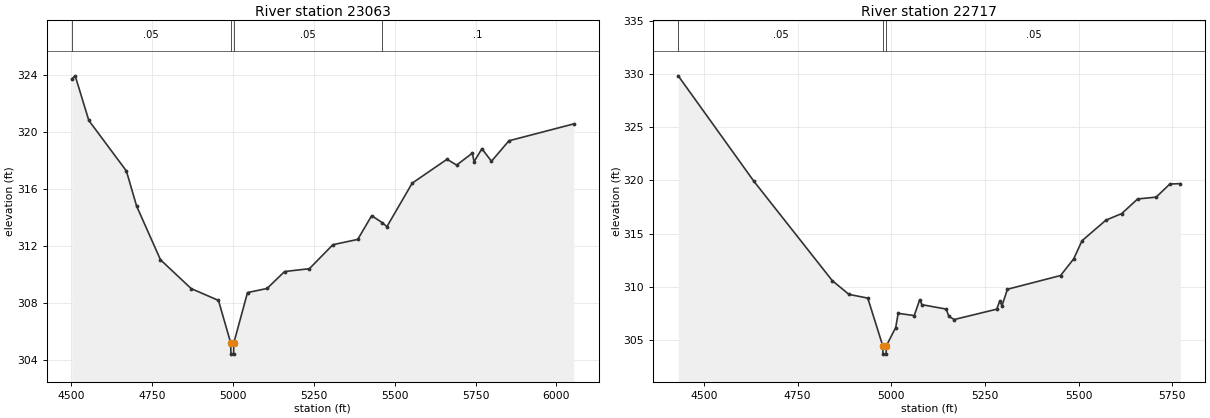
Type RM Length L Ch R = 1,23063,346,346,346
BEGIN DESCRIPTION:
Salt Branch 41.0
END DESCRIPTION:
XS GIS Cut Line= 3
      2136875.02     13411474.99      2136425.00     13411625.00
      2135424.99     13412025.00
#Sta/Elev= 30
  4502.2  323.74  4512.8  323.96  4554.9  320.82  4670.9  317.27  4702.5  314.80
  4776.3  311.02  4871.2  308.99  4955.5  308.16  4993.1  305.18  4994.1  304.38
  5002.1  304.38  5003.1  305.18  5045.2  308.71  5105.8  309.00  5159.7  310.19
  5236.4  310.39  5309.1  312.08  5385.8  312.45  5428.9  314.12  5461.6  313.63
  5476.0  313.35  5554.1  316.41  5661.8  318.09  5691.4  317.68  5739.9  318.52
  5745.3  317.92  5769.5  318.83  5799.1  317.95  5853.0  319.39  6053.6  320.58
#Mann=4,-1,0
  4502.2    0.05       0  4993.1   0.035       0  5003.1    0.05       0
  5461.6     0.1       0
Bank Sta=4993.1,5003.1
Exp/Cntr=0.3,0.1

Type RM Length L Ch R = 1,22717,358,358,358
BEGIN DESCRIPTION:
Salt Branch 40.0
END DESCRIPTION:
XS GIS Cut Line= 3
      2136825.03     13411074.99      2136325.00     13411325.00
      2135724.98     13411825.02
#Sta/Elev= 30
  4431.2  329.81  4632.5  319.94  4842.1  310.59  4886.8  309.29  4937.1  308.94
  4976.9  304.48  4977.9  303.68  4985.9  303.68  4986.9  304.48  5011.7  306.18
  5018.2  307.51  5061.2  307.30  5075.5  308.77  5082.0  308.32  5146.4  307.91
  5153.6  307.22  5167.9  306.93  5281.2  307.90  5289.0  308.63  5295.5  308.24
  5309.8  309.77  5451.7  311.06  5486.8  312.63  5509.0  314.33  5572.8  316.26
  5615.1  316.88  5657.4  318.25  5706.8  318.42  5743.3  319.65  5771.3  319.69
#Mann=3,-1,0
  4431.2    0.05       0  4976.9   0.035       0  4986.9    0.05       0
Bank Sta=4976.9,4986.9
Exp/Cntr=0.3,0.1