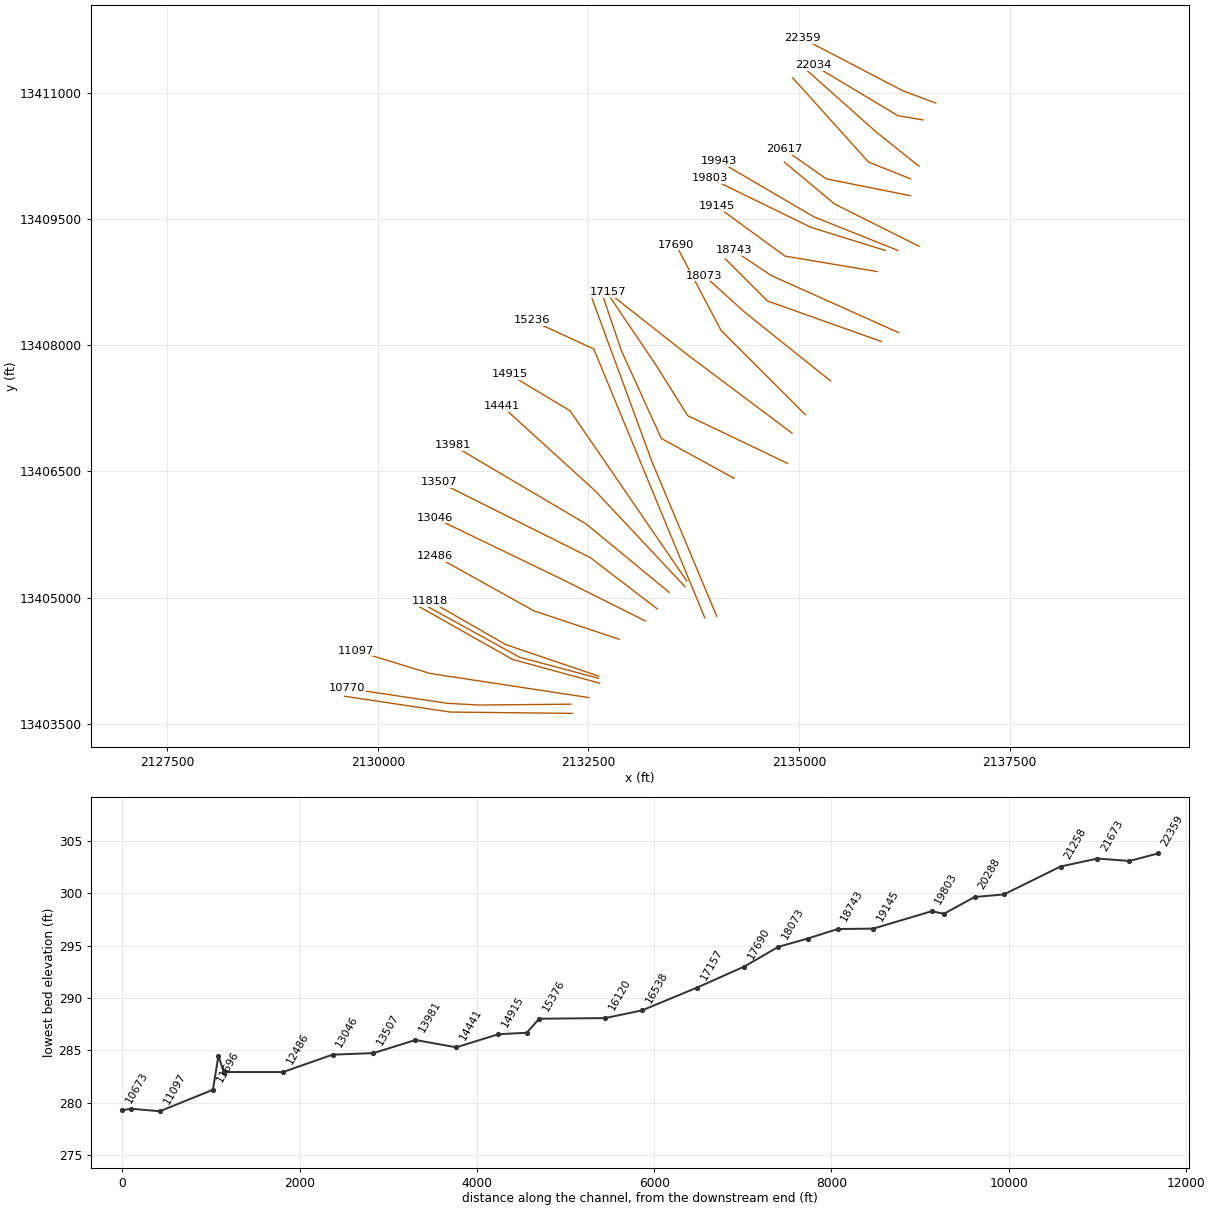
HEC-RAS study Salt Branch.prj: Salt Branch Base Level Engineering

--- Salt Branch.g01 (geometry) --- (continued)

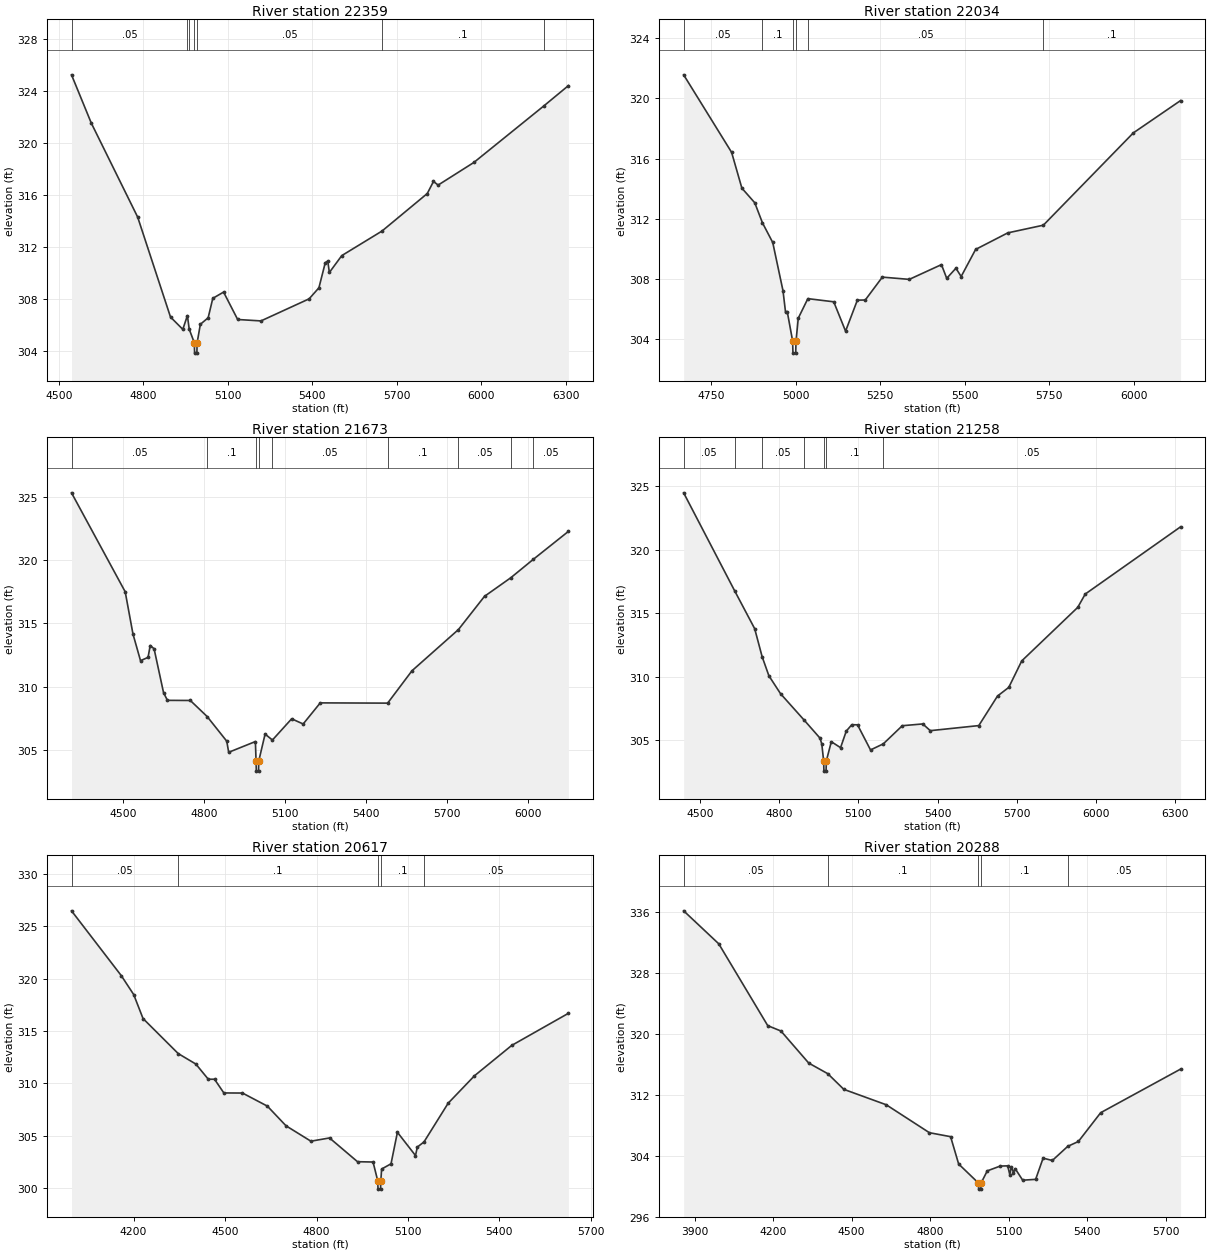
Type RM Length L Ch R = 1,22359,325,325,325
BEGIN DESCRIPTION:
Salt Branch 39.0
END DESCRIPTION:
XS GIS Cut Line= 3
      2136625.00     13410875.00      2136225.00     13411025.00
      2135039.64     13411644.11
#Sta/Elev= 30
  4545.5  325.23  4615.8  321.51  4780.5  314.27  4897.0  306.58  4940.7  305.63
  4957.0  306.69  4963.5  305.64  4981.6  304.60  4982.5  303.80  4990.6  303.80
  4991.6  304.60  5003.0  306.02  5030.7  306.52  5047.2  308.02  5085.5  308.50
  5135.5  306.39  5218.2  306.28  5389.2  307.98  5424.0  308.83  5446.5  310.76
  5455.4  310.89  5461.1  310.01  5505.2  311.31  5648.0  313.20  5808.8  316.09
  5830.8  317.02  5847.3  316.74  5974.1  318.48  6221.8  322.82  6310.0  324.40
#Mann=7,-1,0
  4545.5    0.05       0  4957.0     0.1       0  4963.5    0.05       0
  4981.6   0.035       0  4991.6    0.05       0  5648.0     0.1       0
  6221.8    0.05       0
Bank Sta=4981.6,4991.6
Exp/Cntr=0.3,0.1

Type RM Length L Ch R = 1,22034,361,361,361
BEGIN DESCRIPTION:
Salt Branch 38.0
END DESCRIPTION:
XS GIS Cut Line= 3
      2136474.99     13410675.00      2136175.00     13410725.00
      2135175.01     13411324.99
#Sta/Elev= 30
  4668.0  321.57  4809.9  316.42  4840.3  314.04  4878.4  313.07  4901.1  311.74
  4931.6  310.43  4962.0  307.22  4969.6  305.78  4975.0  305.78  4990.5  303.88
  4991.4  303.08  4999.5  303.08  5000.5  303.88  5007.1  305.40  5035.5  306.70
  5112.1  306.49  5147.1  304.54  5182.0  306.60  5205.4  306.61  5255.9  308.13
  5335.6  307.98  5430.8  308.96  5446.4  308.05  5473.6  308.72  5489.1  308.17
  5531.9  309.97  5627.1  311.07  5732.3  311.58  5998.4  317.71  6138.3  319.86
#Mann=6,-1,0
  4668.0    0.05       0  4901.1     0.1       0  4990.5    0.07       0
  5000.5     0.1       0  5035.5    0.05       0  5732.3     0.1       0
Bank Sta=4990.5,5000.5
Exp/Cntr=0.3,0.1

Type RM Length L Ch R = 1,21673,415,415,415
BEGIN DESCRIPTION:
Salt Branch 37.0
END DESCRIPTION:
XS GIS Cut Line= 3
      2136424.97     13410125.03      2135925.00     13410525.00
      2135025.02     13411324.98
#Sta/Elev= 30
  4307.5  325.33  4506.8  317.50  4535.6  314.16  4563.6  312.05  4591.6  312.31
  4599.6  313.25  4614.0  312.99  4649.2  309.51  4663.6  308.91  4748.5  308.90
  4810.9  307.63  4883.7  305.68  4890.9  304.80  4990.0  305.65  4992.5  304.11
  4993.5  303.31  5001.6  303.31  5002.5  304.11  5026.0  306.24  5053.2  305.77
  5124.6  307.45  5167.3  307.04  5230.8  308.71  5480.9  308.69  5571.2  311.25
  5743.6  314.51  5840.4  317.14  5937.9  318.61  6021.1  320.06  6151.9  322.28
#Mann=9,-1,0
  4307.5    0.05       0  4810.9     0.1       0  4992.5    0.07       0
  5002.5     0.1       0  5053.2    0.05       0  5480.9     0.1       0
  5743.6    0.05       0  5937.9     0.1       0  6021.1    0.05       0
Bank Sta=4992.5,5002.5
Exp/Cntr=0.3,0.1

Type RM Length L Ch R = 1,21258,641,641,641
BEGIN DESCRIPTION:
Salt Branch 36.0
END DESCRIPTION:
XS GIS Cut Line= 3
      2136324.99     13409975.00      2135825.00     13410175.00
      2134924.98     13411175.02
#Sta/Elev= 30
  4437.6  324.49  4631.6  316.74  4706.9  313.78  4735.0  311.58  4760.7  310.07
  4805.1  308.65  4892.4  306.62  4954.6  305.15  4961.3  304.69  4968.4  303.35
  4969.4  302.55  4977.5  302.55  4978.5  303.35  4997.4  304.87  5032.5  304.40
  5054.2  305.71  5075.1  306.21  5096.8  306.20  5146.1  304.22  5194.5  304.70
  5266.5  306.13  5344.2  306.27  5372.6  305.74  5556.5  306.14  5627.5  308.47
  5670.1  309.15  5719.4  311.24  5931.7  315.46  5960.1  316.51  6321.5  321.81
#Mann=7,-1,0
  4437.6    0.05       0  4631.6     0.1       0  4735.0    0.05       0
  4892.4     0.1       0  4968.4    0.07       0  4978.5     0.1       0
  5194.5    0.05       0
Bank Sta=4968.4,4978.5
Exp/Cntr=0.3,0.1

Type RM Length L Ch R = 1,20617,329,329,329
BEGIN DESCRIPTION:
Salt Branch 35.0
END DESCRIPTION:
XS GIS Cut Line= 3
      2136325.01     13409775.00      2135325.00     13409975.00
      2134825.03     13410324.98
#Sta/Elev= 30
  3996.3  326.47  4159.5  320.28  4200.3  318.47  4230.9  316.18  4346.4  312.83
  4404.2  311.83  4445.0  310.38  4465.4  310.38  4496.0  309.07  4557.2  309.06
  4638.8  307.81  4700.0  305.93  4781.6  304.46  4842.7  304.77  4934.5  302.50
  4985.5  302.47  5000.8  300.68  5001.8  299.88  5010.0  299.88  5011.0  300.68
  5013.6  301.80  5044.4  302.30  5065.4  305.31  5124.7  303.09  5130.8  303.90
  5152.6  304.39  5231.9  308.09  5318.2  310.71  5440.3  313.61  5626.4  316.68
#Mann=5,-1,0
  3996.3    0.05       0  4346.4     0.1       0  5000.8    0.07       0
  5011.0     0.1       0  5152.6    0.05       0
Bank Sta=5000.8,5011
Exp/Cntr=0.3,0.1

Type RM Length L Ch R = 1,20288,345,345,345
BEGIN DESCRIPTION:
Salt Branch 34.0
END DESCRIPTION:
XS GIS Cut Line= 3
      2136425.01     13409175.00      2135425.00     13409675.00
      2134824.98     13410175.02
#Sta/Elev= 30
  3858.0  336.09  3992.2  331.77  4179.4  321.05  4229.8  320.35  4336.0  316.15
  4408.8  314.76  4470.1  312.71  4632.2  310.69  4797.2  307.03  4878.2  306.51
  4909.0  302.93  4984.6  300.44  4985.6  299.64  4993.8  299.64  4994.8  300.44
  5018.3  302.03  5067.8  302.66  5096.5  302.69  5104.3  301.55  5110.8  302.57
  5118.6  301.79  5125.1  302.32  5153.7  300.81  5203.2  300.92  5231.8  303.70
  5267.0  303.39  5325.8  305.24  5366.6  305.88  5451.8  309.65  5757.1  315.36
#Mann=5,-1,0
  3858.0    0.05       0  4408.8     0.1       0  4984.6    0.07       0
  4994.8     0.1       0  5325.8    0.05       0
Bank Sta=4984.6,4994.8
Exp/Cntr=0.3,0.1

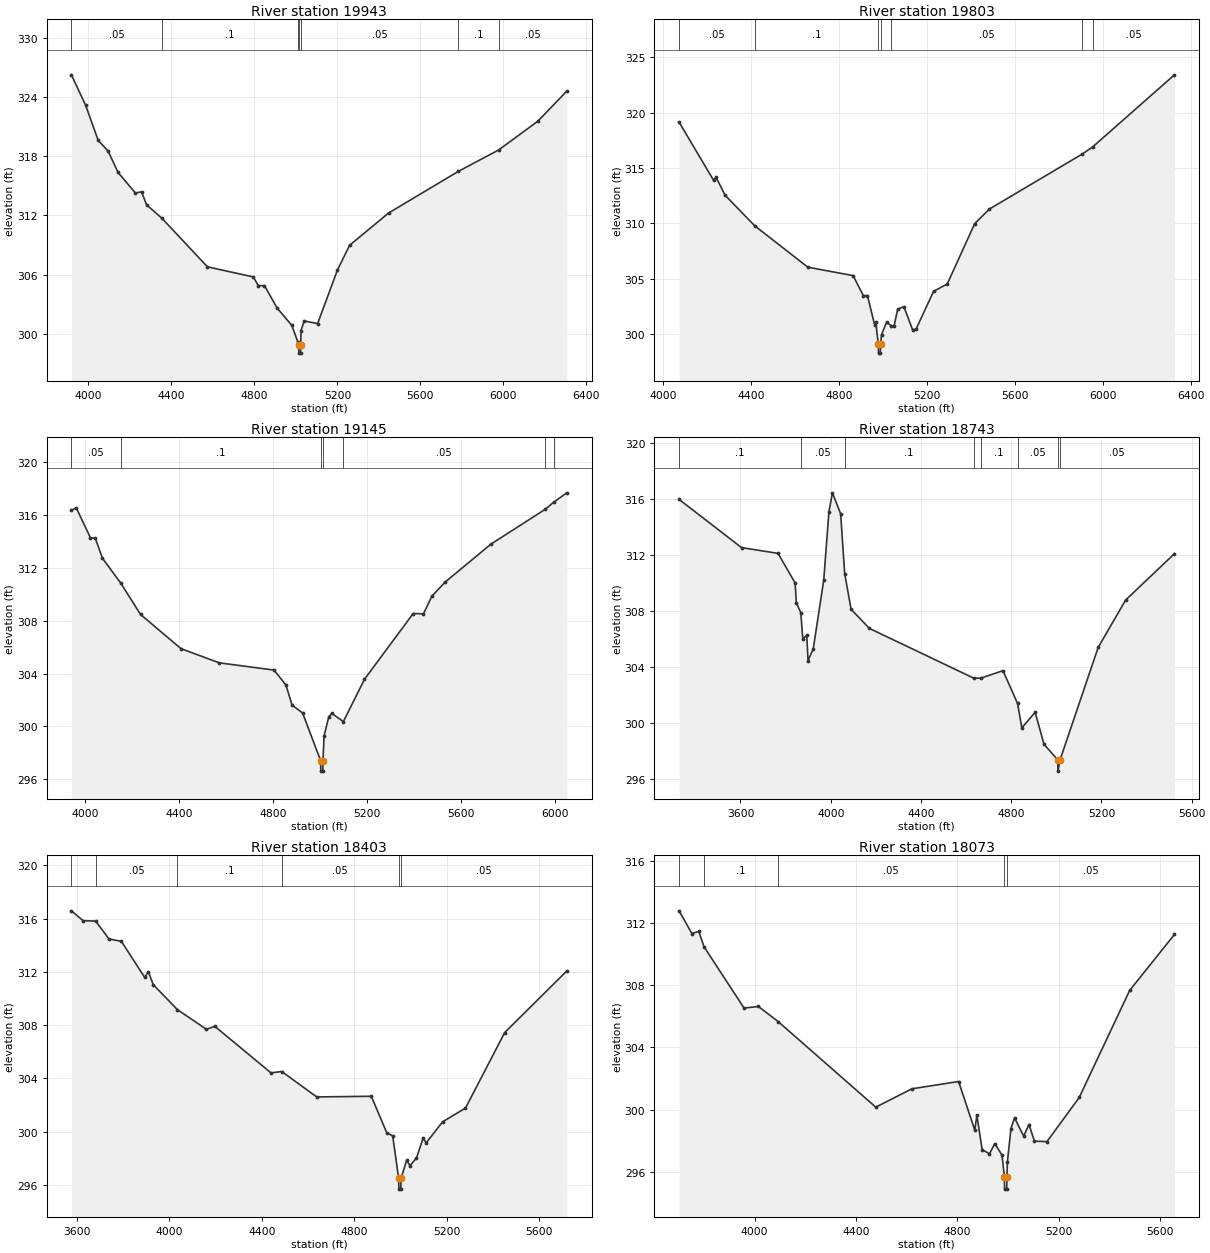
Type RM Length L Ch R = 1,19943,140,140,140
BEGIN DESCRIPTION:
Salt Branch 33.0
END DESCRIPTION:
XS GIS Cut Line= 3
      2136175.00     13409125.00      2135175.00     13409525.00
      2134044.54     13410187.67
#Sta/Elev= 30
  3918.1  326.23  3986.8  323.13  4047.3  319.58  4094.5  318.52  4142.9  316.34
  4226.4  314.26  4256.0  314.38  4280.2  313.07  4354.6  311.69  4573.7  306.78
  4794.5  305.76  4818.8  304.87  4848.4  304.88  4909.0  302.62  4980.3  300.85
  5010.1  299.12  5013.2  298.84  5014.2  298.04  5022.5  298.04  5023.4  298.84
  5024.4  300.32  5040.1  301.30  5104.6  301.03  5200.4  306.47  5259.0  308.97
  5447.2  312.24  5782.8  316.45  5977.2  318.62  6165.9  321.53  6305.5  324.58
#Mann=7,-1,0
  3918.1    0.05       0  4354.6     0.1       0  5010.1    0.05       0
  5013.2    0.07       0  5023.4    0.05       0  5782.8     0.1       0
  5977.2    0.05       0
Bank Sta=5013.2,5023.4
Exp/Cntr=0.3,0.1

Type RM Length L Ch R = 1,19803,658,658,658
BEGIN DESCRIPTION:
Salt Branch 32.0
END DESCRIPTION:
XS GIS Cut Line= 3
      2136025.02     13409124.99      2135141.74     13409399.49
      2133948.67     13409982.15
#Sta/Elev= 30
  4074.0  319.14  4231.1  313.87  4241.6  314.18  4283.5  312.53  4417.7  309.78
  4659.5  306.04  4865.3  305.28  4911.8  303.47  4930.4  303.48  4962.9  300.86
  4968.2  301.09  4980.0  299.08  4980.9  298.28  4989.2  298.28  4990.2  299.08
  4994.6  299.95  5017.5  301.07  5037.9  300.77  5051.1  300.69  5068.1  302.24
  5096.2  302.48  5135.6  300.40  5151.1  300.43  5231.3  303.86  5293.3  304.52
  5418.2  309.97  5485.0  311.29  5906.9  316.25  5955.2  316.91  6326.7  323.41
#Mann=7,-1,0
  4074.0    0.05       0  4417.7     0.1       0  4980.0    0.07       0
  4990.2     0.1       0  5037.9    0.05       0  5906.9     0.1       0
  5955.2    0.05       0
Bank Sta=4980,4990.2
Exp/Cntr=0.3,0.1

Type RM Length L Ch R = 1,19145,402,402,402
BEGIN DESCRIPTION:
Salt Branch 31.0
END DESCRIPTION:
XS GIS Cut Line= 3
      2135924.98     13408875.00      2134834.44     13409057.48
      2134025.40     13409647.77
#Sta/Elev= 30
  3941.3  316.36  3961.6  316.56  4022.4  314.28  4042.7  314.26  4073.1  312.74
  4150.6  310.87  4235.3  308.48  4407.7  305.89  4569.9  304.82  4803.1  304.27
  4853.8  303.14  4879.8  301.62  4924.8  301.02  5001.2  297.42  5002.2  296.62
  5010.5  296.62  5011.4  297.42  5016.0  299.28  5036.3  300.75  5049.1  300.99
  5098.0  300.37  5187.8  303.57  5394.9  308.55  5438.9  308.53  5474.4  309.86
  5530.8  310.93  5725.4  313.80  5956.5  316.44  5992.2  316.97  6048.5  317.69
#Mann=7,-1,0
  3941.3    0.05       0  4150.6     0.1       0  5001.2    0.07       0
  5011.4     0.1       0  5098.0    0.05       0  5956.5     0.1       0
  5992.2    0.05       0
Bank Sta=5001.2,5011.4
Exp/Cntr=0.3,0.1

Type RM Length L Ch R = 1,18743,340,340,340
BEGIN DESCRIPTION:
Salt Branch 30.0
END DESCRIPTION:
XS GIS Cut Line= 3
      2136185.13     13408147.76      2134675.00     13408825.00
      2134224.97     13409125.02
#Sta/Elev= 30
  3327.9  315.97  3604.8  312.53  3766.4  312.12  3842.1  310.01  3847.6  308.61
  3867.2  307.89  3876.3  306.01  3893.9  306.27  3899.4  304.46  3922.6  305.31
  3969.0  310.20  3992.1  315.08  4007.5  316.44  4044.0  314.94  4061.9  310.68
  4090.3  308.13  4171.9  306.76  4633.5  303.22  4664.5  303.21  4763.7  303.75
  4828.2  301.41  4847.2  299.67  4906.2  300.78  4945.4  298.50  5006.4  297.38
  5007.3  296.58  5016.6  297.38  5185.7  305.41  5307.4  308.79  5523.8  312.10
#Mann=8,-1,0
  3327.9     0.1       0  3867.2    0.05       0  4061.9     0.1       0
  4633.5    0.05       0  4664.5     0.1       0  4828.2    0.05       0
  5006.4   0.035       0  5016.6    0.05       0
Bank Sta=5006.4,5016.6
Exp/Cntr=0.3,0.1

Type RM Length L Ch R = 1,18403,330,330,330
BEGIN DESCRIPTION:
Salt Branch 29.0
END DESCRIPTION:
XS GIS Cut Line= 3
      2135978.57     13408043.58      2134625.00     13408525.00
      2134125.03     13409024.97
#Sta/Elev= 30
  3576.1  316.59  3626.4  315.85  3680.6  315.82  3739.1  314.47  3792.2  314.30
  3893.3  311.58  3908.9  312.02  3930.1  311.04  4034.4  309.17  4160.3  307.68
  4196.4  307.91  4439.6  304.41  4486.3  304.51  4637.8  302.60  4873.9  302.65
  4940.9  299.90  4966.5  299.67  4992.2  296.47  4993.2  295.67  5001.5  295.67
  5002.4  296.47  5026.9  297.84  5041.0  297.44  5069.3  298.00  5097.6  299.49
  5111.7  299.16  5182.4  300.73  5281.4  301.76  5451.1  307.44  5719.8  312.07
#Mann=6,-1,0
  3576.1     0.1       0  3680.6    0.05       0  4034.4     0.1       0
  4486.3    0.05       0  4992.2   0.035       0  5002.4    0.05       0
Bank Sta=4992.2,5002.4
Exp/Cntr=0.3,0.1

Type RM Length L Ch R = 1,18073,383,383,383
BEGIN DESCRIPTION:
Salt Branch 28.0
END DESCRIPTION:
XS GIS Cut Line= 3
      2135374.97     13407575.02      2134375.00     13408375.00
      2133874.98     13408825.02
#Sta/Elev= 30
  3702.6  312.80  3753.0  311.34  3780.2  311.47  3800.7  310.49  3958.7  306.54
  4015.5  306.64  4093.1  305.67  4478.1  300.16  4620.6  301.34  4804.7  301.81
  4868.7  298.67  4876.7  299.65  4897.5  297.43  4926.4  297.15  4947.2  297.81
  4976.0  297.07  4985.2  295.68  4986.1  294.88  4994.4  294.88  4995.4  295.68
  4997.0  296.61  5011.2  298.78  5025.4  299.47  5061.3  298.29  5082.2  299.04
  5103.9  297.97  5153.2  297.94  5280.3  300.78  5479.1  307.67  5655.9  311.28
#Mann=5,-1,0
  3702.6    0.05       0  3800.7     0.1       0  4093.1    0.05       0
  4985.2   0.035       0  4995.4    0.05       0
Bank Sta=4985.2,4995.4
Exp/Cntr=0.3,0.1

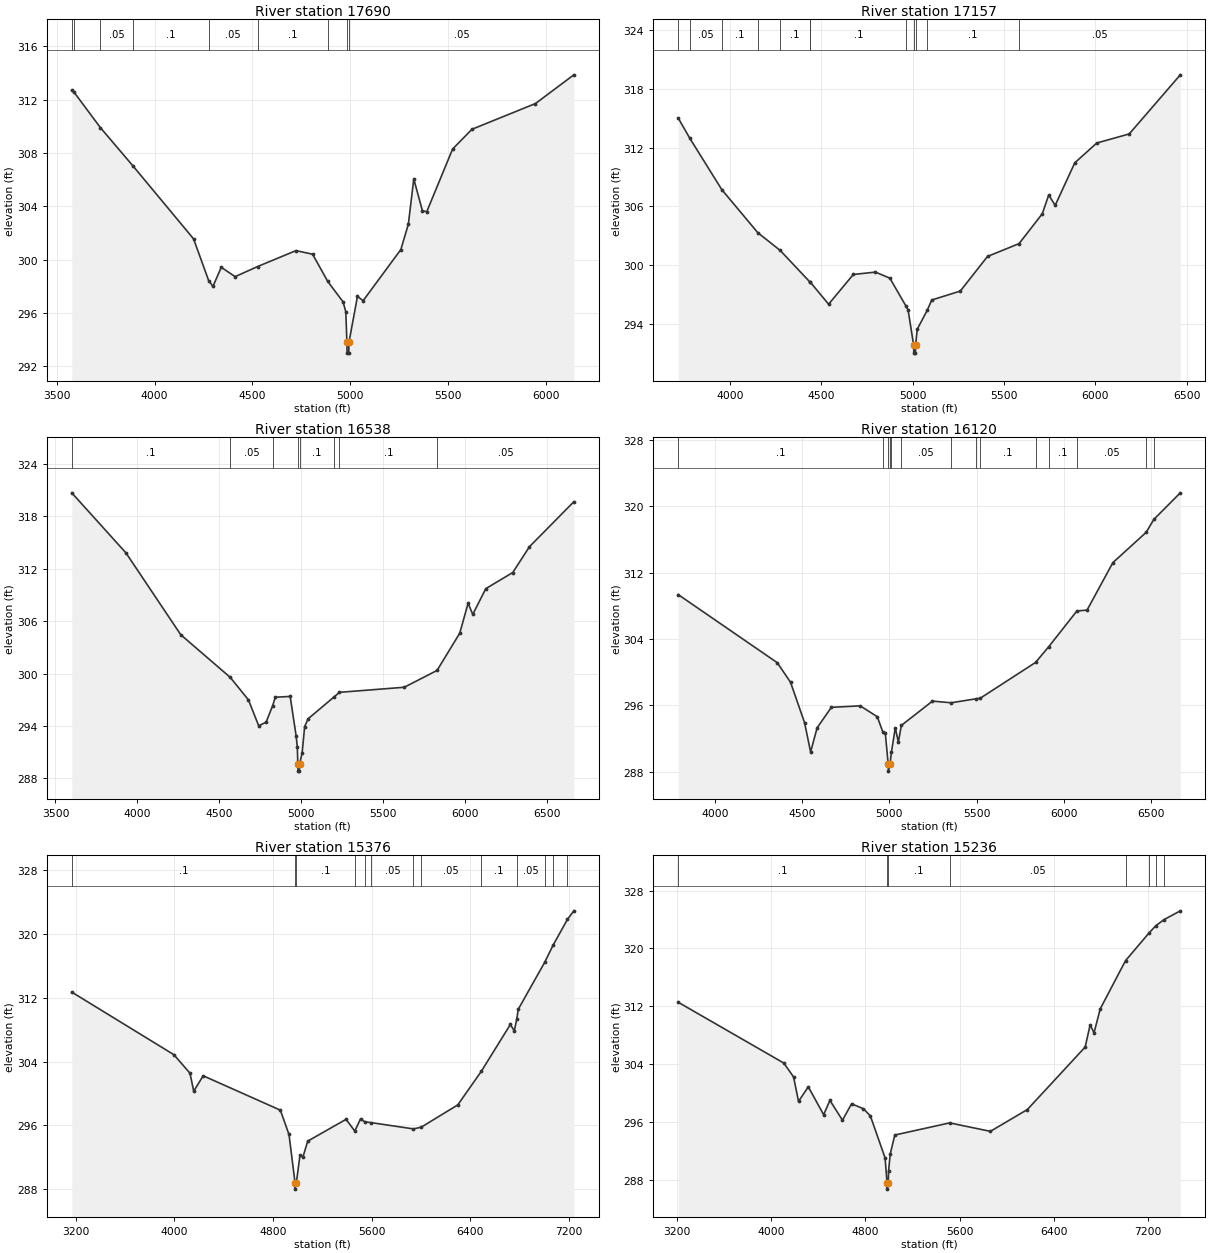
Type RM Length L Ch R = 1,17690,533,533,533
BEGIN DESCRIPTION:
Salt Branch 27.0
END DESCRIPTION:
XS GIS Cut Line= 3
      2135074.98     13407175.02      2134075.00     13408175.00
      2133538.46     13409192.85
#Sta/Elev= 30
  3576.8  312.68  3586.9  312.58  3722.7  309.90  3888.0  307.05  4199.0  301.56
  4276.0  298.44  4298.0  298.00  4340.5  299.43  4411.2  298.73  4526.6  299.49
  4722.3  300.68  4807.1  300.41  4884.4  298.37  4962.7  296.84  4976.8  296.09
  4982.3  293.80  4983.2  293.00  4991.8  293.00  4992.7  293.80  5036.2  297.25
  5065.3  296.93  5257.8  300.76  5296.2  302.66  5323.9  306.05  5368.0  303.67
  5390.0  303.59  5522.3  308.29  5621.0  309.77  5945.7  311.70  6141.6  313.85
#Mann=9,-1,0
  3576.8    0.05       0  3586.9     0.1       0  3722.7    0.05       0
  3888.0     0.1       0  4276.0    0.05       0  4526.6     0.1       0
  4884.4    0.05       0  4982.3   0.035       0  4992.7    0.05       0
Bank Sta=4982.3,4992.7
Exp/Cntr=0.3,0.1

Type RM Length L Ch R = 1,17157,619,619,619
BEGIN DESCRIPTION:
Mapping XS aeb5122b
END DESCRIPTION:
XS GIS Cut Line= 3
      2134917.52     13406955.03      2133667.56     13407892.51
      2132735.30     13408626.85
#Sta/Elev= 30
  3716.6  315.01  3780.5  312.93  3955.1  307.70  4152.2  303.30  4274.6  301.49
  4438.1  298.25  4440.7  298.22  4540.0  295.99  4675.4  299.03  4796.3  299.27
  4875.4  298.65  4963.9  295.79  4975.4  295.39  5005.7  291.79  5006.6  290.99
  5015.2  290.99  5016.1  291.79  5025.4  293.44  5080.7  295.39  5104.6  296.42
  5260.9  297.33  5410.1  300.87  5582.8  302.18  5710.0  305.23  5745.3  307.15
  5780.6  306.09  5888.0  310.44  6008.3  312.46  6186.2  313.39  6465.8  319.43
#Mann=12,-1,0
  3716.6     0.1       0  3780.5    0.05       0  3955.1     0.1       0
  4152.2    0.05       0  4274.6     0.1       0  4438.1    0.05       0
  4440.7     0.1       0  4963.9    0.05       0  5005.7   0.035       0
  5016.1    0.05       0  5080.7     0.1       0  5582.8    0.05       0
Bank Sta=5005.7,5016.1
Exp/Cntr=0.3,0.1

Type RM Length L Ch R = 1,16538,418,418,418
BEGIN DESCRIPTION:
Mapping XS 30aede6f
END DESCRIPTION:
XS GIS Cut Line= 4
      2134865.45     13406595.64      2133677.97     13407163.34
      2133302.97     13407762.30      2132719.82     13408626.61
#Sta/Elev= 30
  3599.8  320.71  3930.9  313.82  4265.3  304.45  4567.6  299.56  4678.7  296.98
  4741.2  294.01  4786.3  294.43  4825.8  296.30  4843.0  297.29  4933.3  297.38
  4969.9  292.84  4976.9  291.59  4980.0  289.62  4980.9  288.82  4989.5  288.82
  4990.4  289.62  5006.4  290.90  5021.7  293.93  5043.0  294.82  5203.7  297.36
  5234.4  297.85  5630.0  298.43  5830.2  300.36  5968.7  304.63  6019.7  308.06
  6048.1  306.78  6127.6  309.73  6292.5  311.58  6394.4  314.54  6665.3  319.69
#Mann=8,-1,0
  3599.8     0.1       0  4567.6    0.05       0  4825.8     0.1       0
  4980.0    0.07       0  4990.4     0.1       0  5203.7    0.05       0
  5234.4     0.1       0  5830.2    0.05       0
Bank Sta=4980,4990.4
Exp/Cntr=0.3,0.1

Type RM Length L Ch R = 1,16120,744,744,744
BEGIN DESCRIPTION:
Mapping XS 80bc2812
END DESCRIPTION:
XS GIS Cut Line= 4
      2134230.05     13406418.55      2133365.47     13406892.51
      2132891.51     13407934.17      2132652.36     13408641.24
#Sta/Elev= 30
  3790.0  309.36  4357.5  301.15  4433.3  298.80  4514.2  293.90  4548.4  290.39
  4585.9  293.31  4667.4  295.77  4832.8  295.95  4930.5  294.64  4961.4  292.85
  4976.5  292.66  4993.2  288.88  4994.1  288.08  5003.6  288.88  5011.3  290.33
  5033.8  293.31  5051.3  291.57  5068.3  293.59  5246.8  296.52  5354.2  296.32
  5495.9  296.80  5519.9  296.86  5837.3  301.18  5913.7  303.10  6074.4  307.39
  6132.4  307.49  6280.2  313.21  6470.8  316.86  6515.4  318.43  6666.8  321.63
#Mann=14,-1,0
  3790.0     0.1       0  4961.4    0.05       0  4993.2   0.035       0
  5003.6    0.05       0  5011.3     0.1       0  5068.3    0.05       0
  5354.2     0.1       0  5495.9    0.05       0  5519.9     0.1       0
  5837.3    0.05       0  5913.7     0.1       0  6074.4    0.05       0
  6470.8     0.1       0  6515.4    0.05       0
Bank Sta=4993.2,5003.6
Exp/Cntr=0.3,0.1

Type RM Length L Ch R = 1,15376,140,140,140
BEGIN DESCRIPTION:
Salt Branch 22.0
END DESCRIPTION:
XS GIS Cut Line= 3
      2134022.81     13404781.44      2133251.04     13406625.00
      2132538.45     13408567.85
#Sta/Elev= 30
  3169.7  312.72  3997.5  304.87  4127.6  302.55  4157.8  300.30  4234.6  302.23
  4859.8  297.92  4929.8  294.87  4978.7  288.82  4979.5  288.02  4989.3  288.82
  5018.8  292.27  5042.6  292.05  5081.6  294.04  5392.0  296.77  5462.8  295.30
  5509.1  296.82  5544.2  296.46  5598.1  296.35  5938.4  295.57  6001.7  295.79
  6297.3  298.58  6487.5  302.78  6723.4  308.66  6755.3  307.86  6775.6  309.36
  6787.3  310.57  7002.1  316.47  7069.0  318.59  7185.5  321.83  7237.7  322.91
#Mann=13,-1,0
  3169.7     0.1       0  4978.7    0.07       0  4989.3     0.1       0
  5462.8    0.05       0  5544.2     0.1       0  5598.1    0.05       0
  5938.4     0.1       0  6001.7    0.05       0  6487.5     0.1       0
  6775.6    0.05       0  7002.1     0.1       0  7069.0    0.05       0
  7185.5     0.1       0
Bank Sta=4978.7,4989.3
Exp/Cntr=0.3,0.1

Type RM Length L Ch R = 1,15236,321,321,321
BEGIN DESCRIPTION:
Salt Branch 20.0
END DESCRIPTION:
XS GIS Cut Line= 3
      2133882.17     13404760.64      2132563.39     13407955.01
      2131829.50     13408293.32
#Sta/Elev= 30
  3210.7  312.55  4107.7  304.13  4190.2  302.21  4232.4  298.83  4315.3  300.85
  4445.7  296.98  4498.9  298.97  4605.4  296.22  4682.6  298.49  4783.7  297.81
  4842.4  296.82  4967.4  291.00  4984.4  287.48  4985.2  286.68  4995.0  287.48
  4996.7  289.15  5011.3  291.56  5050.0  294.17  5515.9  295.85  5861.8  294.68
  6175.9  297.70  6666.6  306.35  6708.9  309.42  6741.9  308.32  6794.7  311.64
  7009.4  318.31  7211.8  322.20  7266.8  323.15  7335.2  323.98  7474.7  325.21
#Mann=8,-1,0
  3210.7     0.1       0  4984.4    0.07       0  4995.0     0.1       0
  5515.9    0.05       0  7009.4     0.1       0  7211.8    0.05       0
  7266.8     0.1       0  7335.2    0.05       0
Bank Sta=4984.4,4995
Exp/Cntr=0.3,0.1

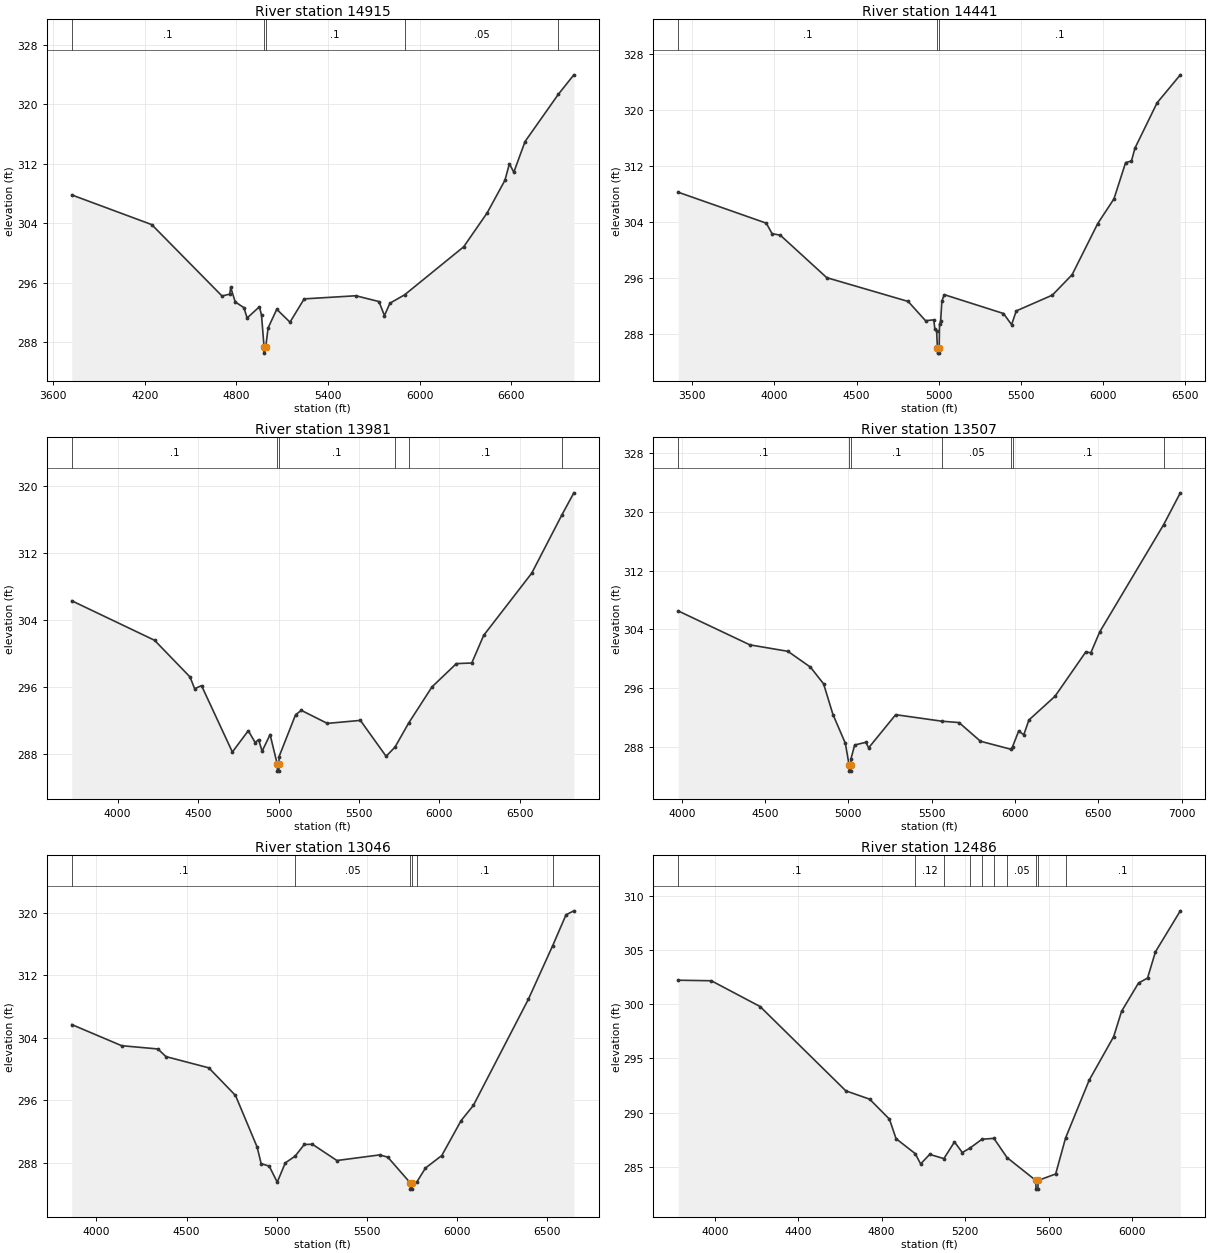
Type RM Length L Ch R = 1,14915,474,474,474
BEGIN DESCRIPTION:
Mapping XS d737f577
END DESCRIPTION:
XS GIS Cut Line= 3
      2133667.55     13405199.80      2132282.14     13407220.63
      2131563.36     13407652.94
#Sta/Elev= 30
  3721.2  307.80  4245.1  303.81  4705.4  294.22  4756.2  294.47  4762.2  295.38
  4792.0  293.42  4848.9  292.65  4869.8  291.26  4950.4  292.77  4964.2  291.64
  4980.9  287.34  4981.8  286.54  4991.6  287.34  5007.3  289.93  5064.1  292.43
  5150.7  290.70  5243.5  293.83  5582.5  294.25  5733.5  293.47  5769.4  291.58
  5805.3  293.25  5901.8  294.38  6288.5  300.83  6442.0  305.38  6558.5  309.76
  6588.1  311.99  6616.8  310.85  6690.6  314.98  6908.7  321.33  7010.1  323.94
#Mann=5,-1,0
  3721.2     0.1       0  4980.9    0.07       0  4991.6     0.1       0
  5901.8    0.05       0  6908.7     0.1       0
Bank Sta=4980.9,4991.6
Exp/Cntr=0.3,0.1

Type RM Length L Ch R = 1,14441,460,460,460
BEGIN DESCRIPTION:
Salt Branch 19.0
END DESCRIPTION:
XS GIS Cut Line= 3
      2133647.83     13405130.38      2132575.00     13406275.00
      2131475.00     13407275.00
#Sta/Elev= 30
  3414.4  308.23  3950.3  303.82  3985.5  302.32  4035.3  302.11  4318.2  296.05
  4813.5  292.66  4919.5  289.91  4969.3  290.04  4976.1  288.75  4986.6  288.49
  4991.7  286.09  4992.5  285.29  5001.6  285.29  5002.4  286.09  5004.5  289.41
  5011.2  289.82  5018.7  292.69  5032.9  293.63  5393.7  290.94  5443.0  289.35
  5471.4  291.31  5691.0  293.56  5811.3  296.47  5967.4  303.77  6066.1  307.29
  6137.0  312.46  6172.5  312.68  6193.8  314.52  6328.2  320.97  6469.8  324.97
#Mann=3,-1,0
  3414.4     0.1       0  4991.7    0.07       0  5002.4     0.1       0
Bank Sta=4991.7,5002.4
Exp/Cntr=0.3,0.1

Type RM Length L Ch R = 1,13981,474,474,474
BEGIN DESCRIPTION:
Salt Branch 18.0
END DESCRIPTION:
XS GIS Cut Line= 3
      2133459.22     13405064.38      2132475.00     13405875.00
      2130886.31     13406814.38
#Sta/Elev= 30
  3714.9  306.30  4229.6  301.59  4449.8  297.22  4478.5  295.82  4521.5  296.18
  4713.1  288.27  4812.1  290.81  4855.1  289.39  4875.9  289.75  4898.1  288.37
  4947.6  290.35  4992.4  286.79  4993.2  285.99  5002.3  285.99  5003.1  286.79
  5003.6  287.73  5106.1  292.72  5142.1  293.23  5303.6  291.68  5508.8  292.04
  5668.7  287.76  5724.2  288.86  5809.1  291.73  5954.2  296.04  6105.5  298.81
  6201.1  298.88  6275.3  302.18  6573.7  309.59  6762.4  316.58  6835.6  319.17
#Mann=6,-1,0
  3714.9     0.1       0  4992.4    0.07       0  5003.1     0.1       0
  5724.2    0.05       0  5809.1     0.1       0  6762.4    0.05       0
Bank Sta=4992.4,5003.1
Exp/Cntr=0.3,0.1

Type RM Length L Ch R = 1,13507,461,461,461
BEGIN DESCRIPTION:
Salt Branch 17.0
END DESCRIPTION:
XS GIS Cut Line= 3
      2133318.58     13404866.48      2132525.00     13405475.00
      2130724.99     13406375.00
#Sta/Elev= 30
  3979.0  306.51  4408.9  301.90  4637.3  301.02  4772.4  298.87  4851.2  296.60
  4907.4  292.43  4981.8  288.52  5004.4  285.54  5005.2  284.74  5014.3  284.74
  5015.1  285.54  5015.4  286.42  5037.7  288.29  5104.8  288.66  5121.6  287.91
  5283.7  292.41  5562.7  291.52  5663.8  291.34  5792.4  288.80  5975.6  287.71
  5985.0  288.06  6021.6  290.19  6052.3  289.68  6083.1  291.69  6239.6  294.91
  6424.1  300.93  6454.8  300.83  6507.9  303.66  6891.9  318.25  6991.5  322.56
#Mann=7,-1,0
  3979.0     0.1       0  5004.4    0.07       0  5015.1     0.1       0
  5562.7    0.05       0  5975.6    0.08       0  5985.0     0.1       0
  6891.9    0.05       0
Bank Sta=5004.4,5015.1
Exp/Cntr=0.3,0.1

Type RM Length L Ch R = 1,13046,560,560,560
BEGIN DESCRIPTION:
Salt Branch 16.0
END DESCRIPTION:
XS GIS Cut Line= 3
      2133174.96     13404725.02      2132175.00     13405225.00
      2130672.79     13405949.78
#Sta/Elev= 30
  3862.9  305.70  4139.6  302.99  4340.8  302.57  4385.5  301.59  4623.1  300.15
  4771.3  296.61  4891.4  289.99  4913.8  287.86  4958.5  287.54  5003.1  285.48
  5047.5  287.95  5102.1  288.82  5153.2  290.32  5198.5  290.34  5334.1  288.26
  5571.3  288.98  5616.5  288.69  5741.3  285.39  5742.1  284.59  5751.2  284.59
  5752.0  285.39  5778.0  285.52  5825.6  287.30  5916.0  288.90  6023.5  293.39
  6091.2  295.33  6396.3  308.94  6531.7  315.84  6605.4  319.78  6648.8  320.29
#Mann=6,-1,0
  3862.9     0.1       0  5102.1    0.05       0  5741.3    0.07       0
  5752.0    0.05       0  5778.0     0.1       0  6531.7    0.08       0
Bank Sta=5741.3,5752
Exp/Cntr=0.3,0.1

Type RM Length L Ch R = 1,12486,668,668,668
BEGIN DESCRIPTION:
Salt Branch 15.0
END DESCRIPTION:
XS GIS Cut Line= 3
      2132865.51     13404507.08      2131849.85     13404845.63
      2130683.20     13405496.66
#Sta/Elev= 30
  3825.1  302.23  3983.7  302.18  4217.4  299.80  4628.5  292.01  4742.7  291.24
  4837.6  289.39  4869.2  287.59  4961.1  286.21  4986.9  285.26  5030.4  286.14
  5098.4  285.75  5149.2  287.29  5186.9  286.31  5223.9  286.73  5281.1  287.54
  5338.3  287.62  5400.8  285.85  5539.2  283.73  5540.0  282.93  5549.1  282.93
  5549.9  283.73  5634.2  284.33  5681.8  287.66  5794.5  292.98  5912.5  297.03
  5950.2  299.36  6031.3  301.97  6074.7  302.43  6112.4  304.85  6231.7  308.64
#Mann=10,-1,0
  3825.1     0.1       0  4961.1    0.12       0  5098.4    0.05       0
  5223.9    0.07       0  5281.1    0.05       0  5338.3    0.07       0
  5400.8    0.05       0  5539.2    0.07       0  5549.9    0.05       0
  5681.8     0.1       0
Bank Sta=5539.2,5549.9
Exp/Cntr=0.3,0.1

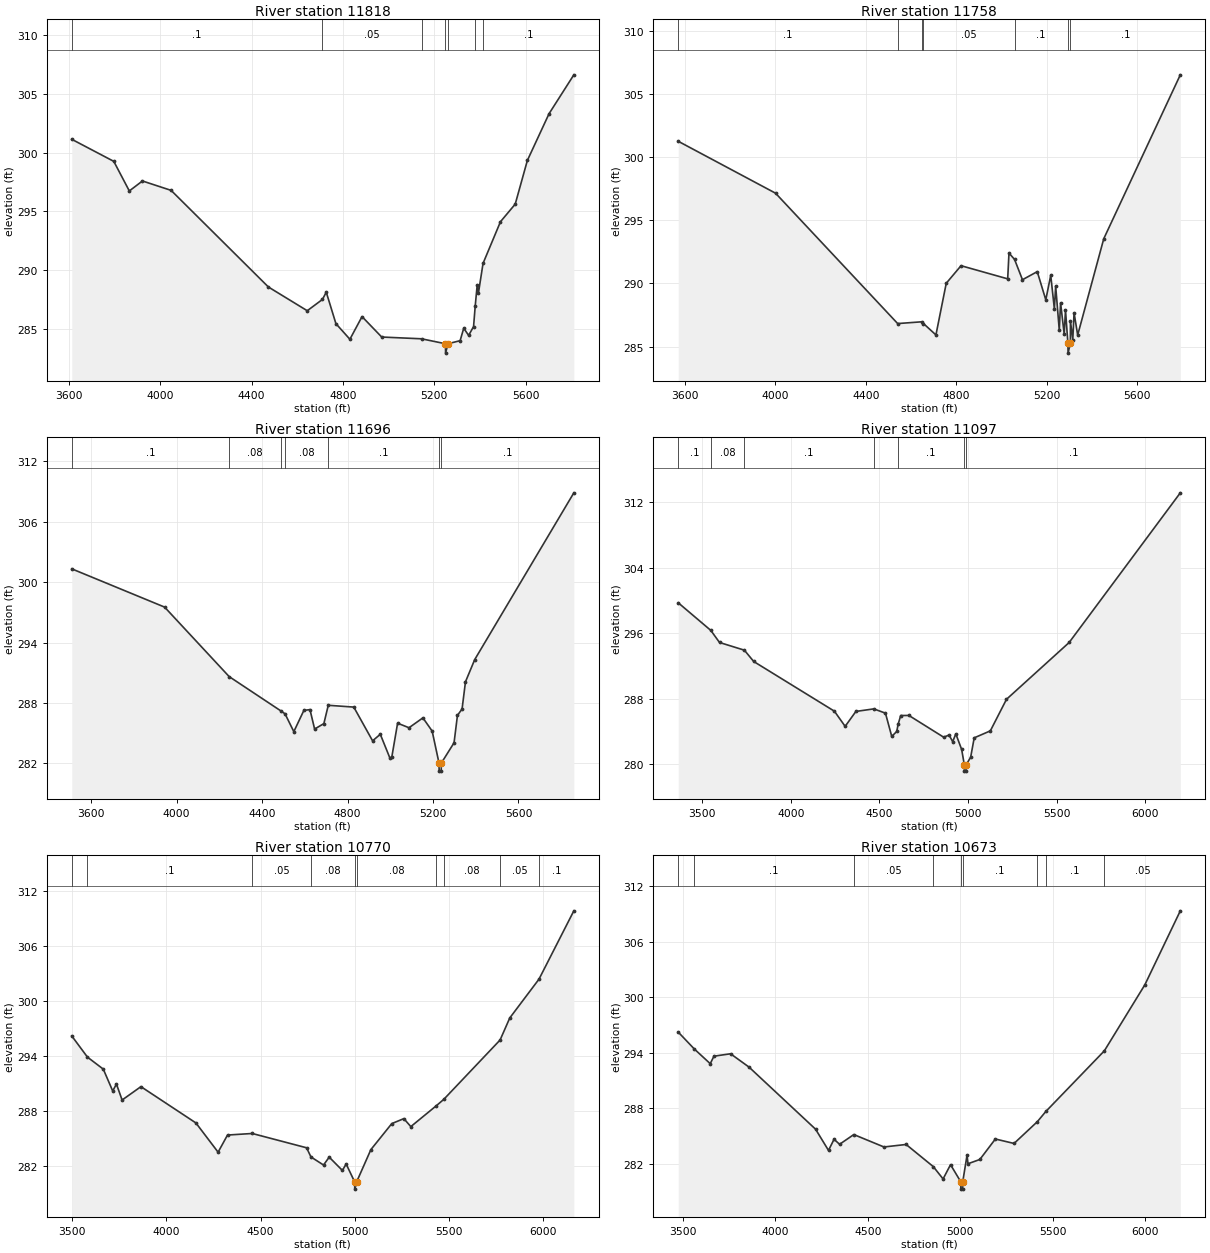
Type RM Length L Ch R = 1,11818,60,60,60
BEGIN DESCRIPTION:
Mapping XS 06c3c35e
END DESCRIPTION:
XS GIS Cut Line= 3
      2132620.70     13404069.58      2131516.51     13404444.59
      2130620.91     13404960.09
#Sta/Elev= 30
  3612.2  301.14  3796.3  299.26  3864.3  296.74  3921.8  297.59  4047.4  296.79
  4473.7  288.56  4643.8  286.54  4710.2  287.50  4727.1  288.12  4769.4  285.44
  4830.6  284.11  4883.8  286.04  4970.0  284.30  5144.5  284.15  5249.1  283.73
  5249.9  282.93  5260.0  283.73  5313.5  283.99  5329.3  285.05  5350.8  284.44
  5372.4  285.19  5379.5  286.91  5388.2  288.71  5394.0  288.08  5413.9  290.57
  5490.2  294.12  5554.9  295.62  5608.1  299.34  5703.1  303.32  5811.7  306.63
#Mann=7,-1,0
  3612.2     0.1       0  4710.2    0.05       0  5144.5     0.1       0
  5249.1   0.033       0  5260.0     0.1       0  5379.5    0.05       0
  5413.9     0.1       0
Bank Sta=5249.1,5260
Exp/Cntr=0.3,0.1

Type RM Length L Ch R = 1,11758,62,62,62
BEGIN DESCRIPTION:
Salt Branch 13.0
END DESCRIPTION:
XS GIS Cut Line= 3
      2132620.72     13404043.54      2131683.18     13404293.55
      2130588.66     13404896.88
#Sta/Elev= 30
  3570.1  301.25  4000.4  297.14  4540.4  286.82  4647.2  286.96  4654.5  286.82
  4709.6  285.92  4755.2  290.01  4820.6  291.40  5026.9  290.36  5032.6  292.40
  5057.2  291.90  5092.2  290.29  5157.6  290.93  5195.4  288.70  5217.2  290.64
  5233.3  287.99  5239.0  289.79  5255.0  286.30  5260.7  288.46  5276.8  285.99
  5282.5  287.88  5293.1  285.28  5293.9  284.48  5304.0  285.28  5304.3  287.02
  5314.7  285.55  5320.4  287.67  5336.4  285.91  5451.8  293.54  5790.2  306.51
#Mann=7,-1,0
  3570.1     0.1       0  4540.4    0.08       0  4647.2     0.1       0
  4654.5    0.05       0  5057.2     0.1       0  5293.1   0.033       0
  5304.0     0.1       0
Bank Sta=5293.1,5304
Exp/Cntr=0.3,0.1

Type RM Length L Ch R = 1,11696,599,599,599
BEGIN DESCRIPTION:
Mapping XS 08e35436
END DESCRIPTION:
XS GIS Cut Line= 3
      2132631.08     13403986.26      2131599.85     13404267.51
      2130485.28     13404897.71
#Sta/Elev= 30
  3509.8  301.33  3944.2  297.53  4246.2  290.63  4487.6  287.23  4507.8  286.93
  4548.8  285.16  4595.8  287.27  4624.4  287.35  4646.1  285.42  4689.4  285.96
  4710.0  287.78  4829.4  287.60  4917.4  284.25  4953.5  284.90  4997.8  282.57
  5007.0  282.60  5034.4  286.00  5087.8  285.55  5152.8  286.53  5196.1  285.22
  5228.2  282.04  5228.9  281.24  5238.3  281.24  5239.1  282.04  5298.6  284.06
  5314.5  286.78  5336.1  287.41  5352.0  290.11  5395.3  292.32  5859.1  308.88
#Mann=7,-1,0
  3509.8     0.1       0  4246.2    0.08       0  4487.6     0.1       0
  4507.8    0.08       0  4710.0     0.1       0  5228.2    0.07       0
  5239.1     0.1       0
Bank Sta=5228.2,5239.1
Exp/Cntr=0.3,0.1

Type RM Length L Ch R = 1,11097,327,327,327
BEGIN DESCRIPTION:
Mapping XS 83be04ad
END DESCRIPTION:
XS GIS Cut Line= 3
      2132506.07     13403814.39      2130620.68     13404100.84
      2129735.30     13404371.66
#Sta/Elev= 30
  3365.3  299.72  3549.2  296.35  3598.2  294.88  3738.5  293.94  3791.2  292.56
  4246.4  286.50  4307.1  284.65  4367.7  286.47  4468.7  286.78  4534.5  286.26
  4570.0  283.42  4598.2  284.03  4605.9  284.89  4620.6  285.97  4666.8  285.98
  4862.8  283.33  4893.7  283.59  4913.9  282.78  4931.5  283.74  4964.5  281.83
  4979.3  279.99  4980.0  279.19  4989.4  279.19  4990.2  279.99  5015.1  280.87
  5035.3  283.25  5126.3  284.10  5217.4  287.95  5571.1  294.88  6198.2  313.13
#Mann=7,-1,0
  3365.3     0.1       0  3549.2    0.08       0  3738.5     0.1       0
  4468.7    0.08       0  4605.9     0.1       0  4979.3    0.07       0
  4990.2     0.1       0
Bank Sta=4979.3,4990.2
Exp/Cntr=0.3,0.1

Type RM Length L Ch R = 1,10770,97,97,97
BEGIN DESCRIPTION:
Mapping XS be965b3e
END DESCRIPTION:
XS GIS Cut Line= 4
      2132292.52     13403736.26      2131198.81     13403725.84
      2130823.81     13403746.67      2129638.16     13403923.48
#Sta/Elev= 30
  3496.9  296.14  3580.3  293.83  3664.4  292.52  3714.4  290.14  3734.4  290.89
  3764.4  289.15  3864.4  290.61  4156.6  286.65  4274.5  283.46  4324.5  285.33
  4455.9  285.50  4744.7  283.94  4768.0  282.94  4834.8  282.06  4864.9  282.92
  4935.0  281.47  4955.0  282.17  5000.0  280.23  5000.8  279.43  5010.9  280.23
  5086.4  283.74  5197.6  286.58  5261.6  287.12  5298.7  286.25  5433.7  288.52
  5473.7  289.22  5773.1  295.70  5824.4  298.10  5979.9  302.34  6165.0  309.79
#Mann=10,-1,0
  3496.9    0.08       0  3580.3     0.1       0  4455.9    0.05       0
  4768.0    0.08       0  5000.0    0.07       0  5010.9    0.08       0
  5433.7     0.1       0  5473.7    0.08       0  5773.1    0.05       0
  5979.9     0.1       0
Bank Sta=5000,5010.9
Exp/Cntr=0.3,0.1

Type RM Length L Ch R = 1,10673,199,199,199
BEGIN DESCRIPTION:
Mapping XS b2dd7ebe
END DESCRIPTION:
XS GIS Cut Line= 3
      2132308.20     13403626.88      2130860.26     13403642.51
      2129605.11     13403830.00
#Sta/Elev= 30
  3474.0  296.23  3560.8  294.41  3647.2  292.82  3667.2  293.63  3757.2  293.89
  3857.2  292.45  4217.2  285.75  4287.2  283.46  4317.2  284.66  4347.2  284.12
  4424.2  285.17  4587.3  283.83  4707.3  284.10  4854.3  281.71  4907.3  280.38
  4947.6  281.92  5002.8  280.08  5003.5  279.28  5012.9  279.28  5013.7  280.08
  5037.0  282.95  5042.0  282.02  5106.2  282.48  5190.2  284.69  5291.3  284.21
  5417.4  286.56  5463.3  287.66  5780.1  294.21  5999.1  301.33  6191.1  309.32
#Mann=9,-1,0
  3474.0    0.08       0  3560.8     0.1       0  4424.2    0.05       0
  4854.3     0.1       0  5002.8    0.07       0  5013.7     0.1       0
  5417.4    0.08       0  5463.3     0.1       0  5780.1    0.05       0
Bank Sta=5002.8,5013.7
Exp/Cntr=0.3,0.1