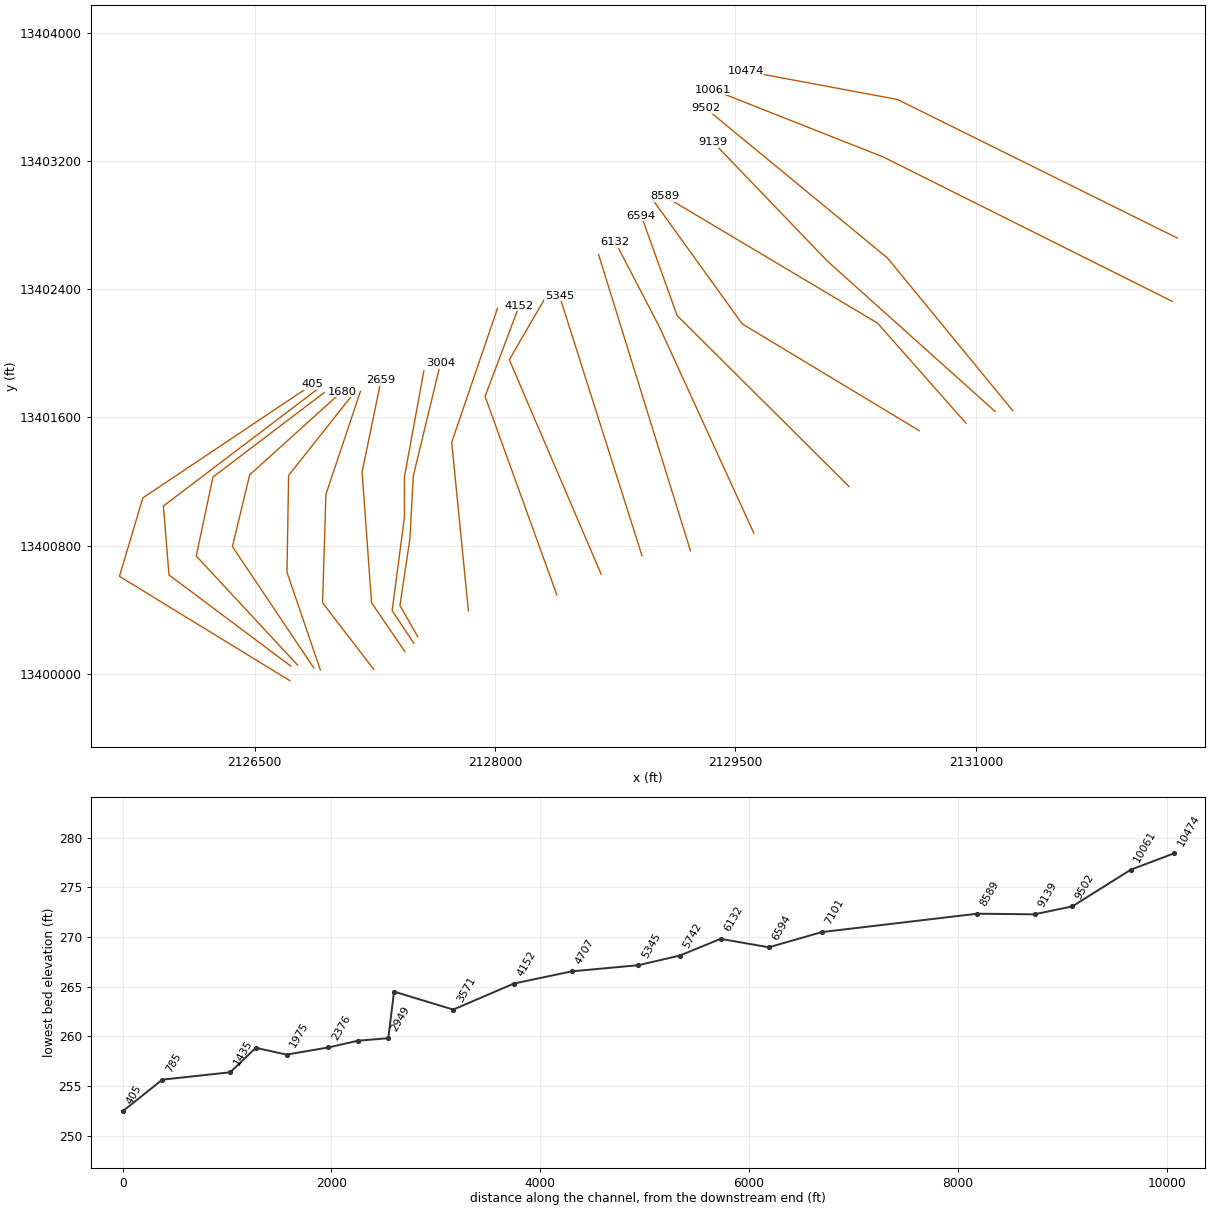
HEC-RAS study Salt Branch.prj: Salt Branch Base Level Engineering

--- Salt Branch.g01 (geometry) --- (continued)

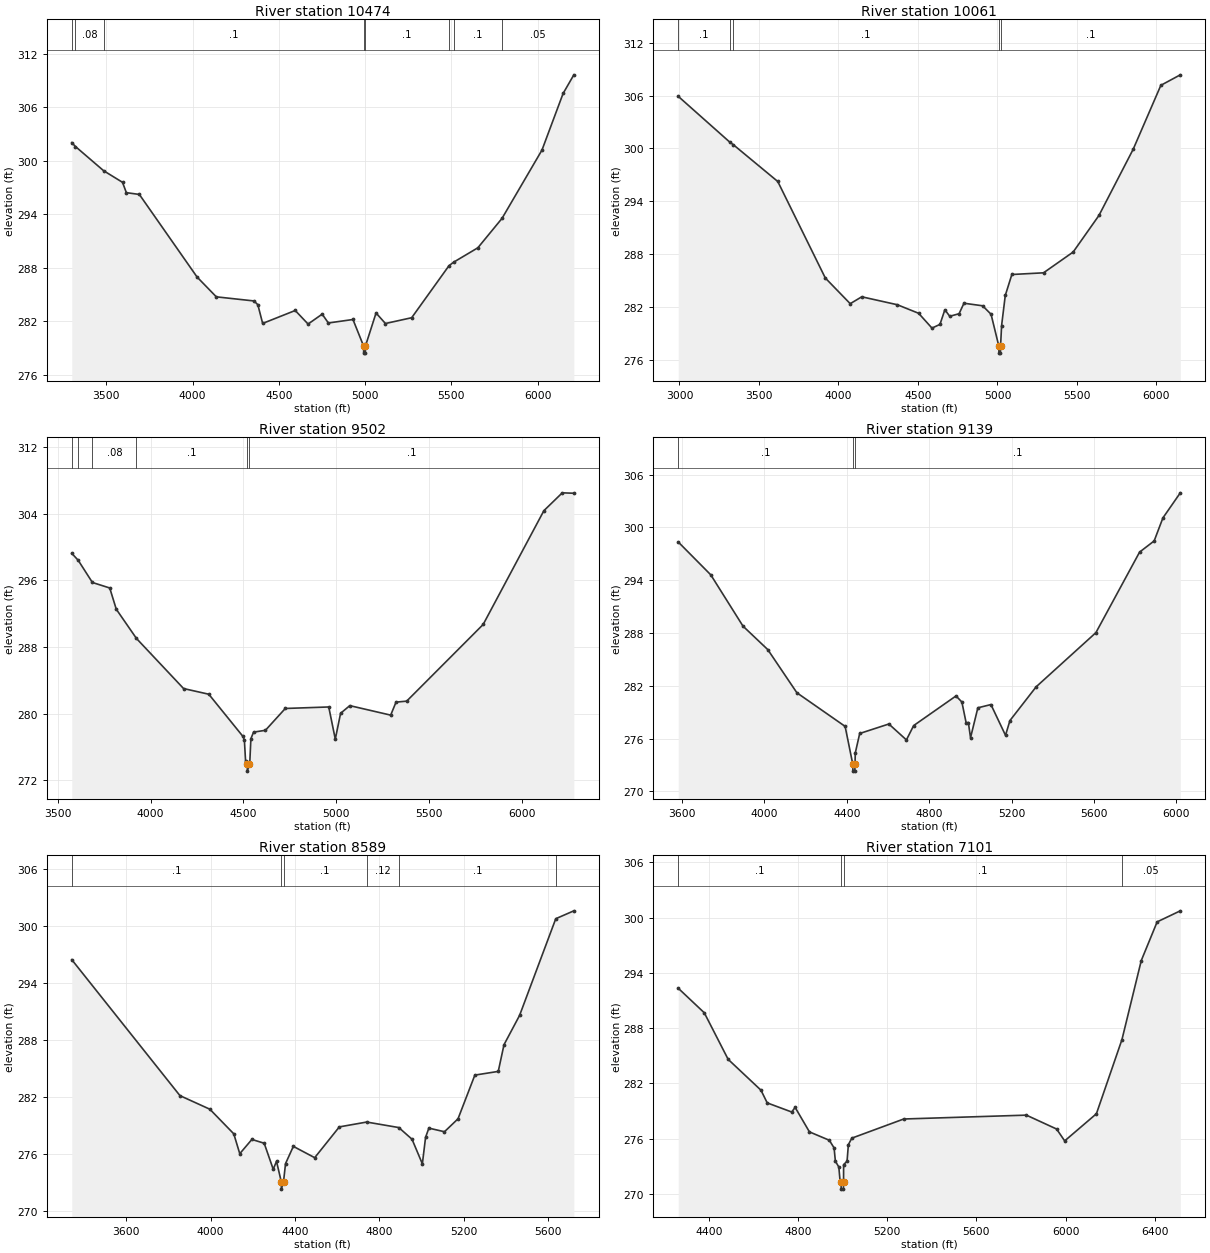
Type RM Length L Ch R = 1,10474,413,413,413
BEGIN DESCRIPTION:
Mapping XS c3a1583d
END DESCRIPTION:
XS GIS Cut Line= 3
      2132256.13     13402720.62      2130511.31     13403585.21
      2129563.39     13403762.30
#Sta/Elev= 30
  3299.1  302.02  3320.6  301.58  3483.8  298.87  3593.3  297.57  3615.7  296.41
  3691.0  296.21  4025.8  286.95  4137.4  284.73  4355.6  284.27  4378.1  283.85
  4406.1  281.75  4595.0  283.20  4669.5  281.68  4751.2  282.79  4787.2  281.80
  4929.8  282.19  4991.3  279.22  4992.0  278.42  5001.4  278.42  5002.2  279.22
  5063.7  282.92  5118.0  281.74  5270.3  282.39  5486.6  288.22  5514.0  288.62
  5654.1  290.23  5794.3  293.53  6026.0  301.19  6148.4  307.53  6210.7  309.62
#Mann=8,-1,0
  3299.1     0.1       0  3320.6    0.08       0  3483.8     0.1       0
  4991.3    0.07       0  5002.2     0.1       0  5486.6    0.05       0
  5514.0     0.1       0  5794.3    0.05       0
Bank Sta=4991.3,5002.2
Exp/Cntr=0.3,0.1

Type RM Length L Ch R = 1,10061,559,559,559
BEGIN DESCRIPTION:
Salt Branch 9.0
END DESCRIPTION:
XS GIS Cut Line= 3
      2132225.00     13402325.00      2130425.00     13403225.00
      2129359.69     13403646.42
#Sta/Elev= 30
  2992.2  305.91  3316.1  300.72  3339.6  300.41  3618.3  296.25  3917.4  285.30
  4073.9  282.39  4146.6  283.17  4370.2  282.27  4504.3  281.30  4588.2  279.62
  4638.5  280.04  4669.3  281.70  4700.0  280.96  4758.7  281.25  4789.4  282.44
  4906.8  282.15  4959.9  281.19  5008.7  277.58  5009.5  276.78  5018.9  276.78
  5019.7  277.58  5026.2  279.91  5049.3  283.32  5090.7  285.70  5289.9  285.89
  5476.4  288.25  5638.6  292.40  5854.2  299.92  6027.9  307.16  6150.3  308.35
#Mann=5,-1,0
  2992.2     0.1       0  3316.1    0.08       0  3339.6     0.1       0
  5008.7    0.07       0  5019.7     0.1       0
Bank Sta=5008.7,5019.7
Exp/Cntr=0.3,0.1

Type RM Length L Ch R = 1,9502,363,363,363
BEGIN DESCRIPTION:
Salt Branch 8.0
END DESCRIPTION:
XS GIS Cut Line= 3
      2131230.07     13401642.49      2130448.81     13402595.63
      2129313.74     13403530.96
#Sta/Elev= 30
  3575.8  299.23  3610.5  298.39  3686.9  295.73  3780.2  295.07  3815.4  292.52
  3924.2  289.01  4177.8  283.00  4313.5  282.32  4497.2  277.26  4505.1  276.83
  4511.5  274.32  4520.4  273.89  4521.2  273.09  4531.4  273.89  4533.8  273.90
  4540.2  276.98  4554.6  277.77  4618.5  277.99  4725.4  280.61  4959.4  280.79
  4994.6  276.93  5023.2  280.03  5072.7  280.95  5292.9  279.81  5321.6  281.37
  5379.0  281.49  5790.7  290.69  6117.8  304.35  6216.8  306.49  6279.0  306.44
#Mann=6,-1,0
  3575.8    0.08       0  3610.5     0.1       0  3686.9    0.08       0
  3924.2     0.1       0  4520.4    0.07       0  4531.4     0.1       0
Bank Sta=4520.4,4531.4
Exp/Cntr=0.3,0.1

Type RM Length L Ch R = 1,9139,550,550,550
BEGIN DESCRIPTION:
Salt Branch 7.0
END DESCRIPTION:
XS GIS Cut Line= 3
      2131120.71     13401637.27      2130075.00     13402575.00
      2129360.26     13403319.59
#Sta/Elev= 30
  3582.2  298.35  3740.2  294.61  3896.5  288.78  4016.8  286.11  4158.1  281.20
  4392.1  277.38  4429.2  273.09  4430.0  272.29  4439.4  272.29  4440.2  273.09
  4441.4  274.35  4462.9  276.57  4604.4  277.65  4689.6  275.84  4724.8  277.47
  4930.3  280.84  4958.8  280.15  4979.7  277.76  4990.2  277.82  5000.8  276.09
  5036.3  279.49  5099.8  279.86  5170.6  276.36  5192.0  278.04  5319.3  281.88
  5609.3  288.04  5821.3  297.20  5892.0  298.47  5934.5  301.09  6018.9  303.94
#Mann=3,-1,0
  3582.2     0.1       0  4429.2    0.07       0  4440.2     0.1       0
Bank Sta=4429.2,4440.2
Exp/Cntr=0.3,0.1

Type RM Length L Ch R = 1,8589,1488,1488,1488
BEGIN DESCRIPTION:
Salt Branch 6.0
END DESCRIPTION:
XS GIS Cut Line= 3
      2130938.38     13401564.40      2130386.31     13402189.38
      2129058.16     13402981.06
#Sta/Elev= 30
  3341.9  296.50  3854.7  282.19  3996.5  280.76  4109.9  278.17  4138.3  276.08
  4195.7  277.58  4254.1  277.18  4296.9  274.44  4312.5  275.28  4334.8  273.15
  4335.6  272.35  4345.8  273.15  4355.3  275.04  4392.3  276.85  4493.5  275.66
  4610.3  278.90  4740.0  279.41  4892.2  278.83  4954.9  277.60  5003.9  275.01
  5019.1  277.80  5034.7  278.77  5108.7  278.39  5172.9  279.75  5252.7  284.35
  5363.7  284.74  5390.9  287.55  5464.9  290.64  5636.3  300.81  5722.0  301.64
#Mann=6,-1,0
  3341.9     0.1       0  4334.8    0.07       0  4345.8     0.1       0
  4740.0    0.12       0  4892.2     0.1       0  5636.3    0.05       0
Bank Sta=4334.8,4345.8
Exp/Cntr=0.3,0.1

Type RM Length L Ch R = 1,7101,507,507,507
BEGIN DESCRIPTION:
Mapping XS a89d7d5e
END DESCRIPTION:
XS GIS Cut Line= 3
      2130646.72     13401517.51      2129542.56     13402184.17
      2128980.05     13402965.43
#Sta/Elev= 30
  4262.2  292.33  4379.1  289.66  4486.2  284.60  4633.4  281.25  4661.4  279.87
  4771.2  278.88  4786.7  279.38  4850.8  276.72  4940.0  275.81  4961.4  274.98
  4967.2  273.54  4982.7  272.90  4988.6  271.30  4992.7  271.30  4993.3  270.50
  5003.2  270.50  5003.9  271.30  5004.1  273.16  5019.6  273.53  5025.5  275.33
  5041.0  276.04  5273.9  278.12  5824.1  278.54  5959.7  277.03  5995.9  275.74
  6138.3  278.69  6252.9  286.75  6339.6  295.34  6410.8  299.54  6514.7  300.74
#Mann=4,-1,0
  4262.2     0.1       0  4992.7    0.07       0  5003.9     0.1       0
  6252.9    0.05       0
Bank Sta=4992.7,5003.9
Exp/Cntr=0.3,0.1

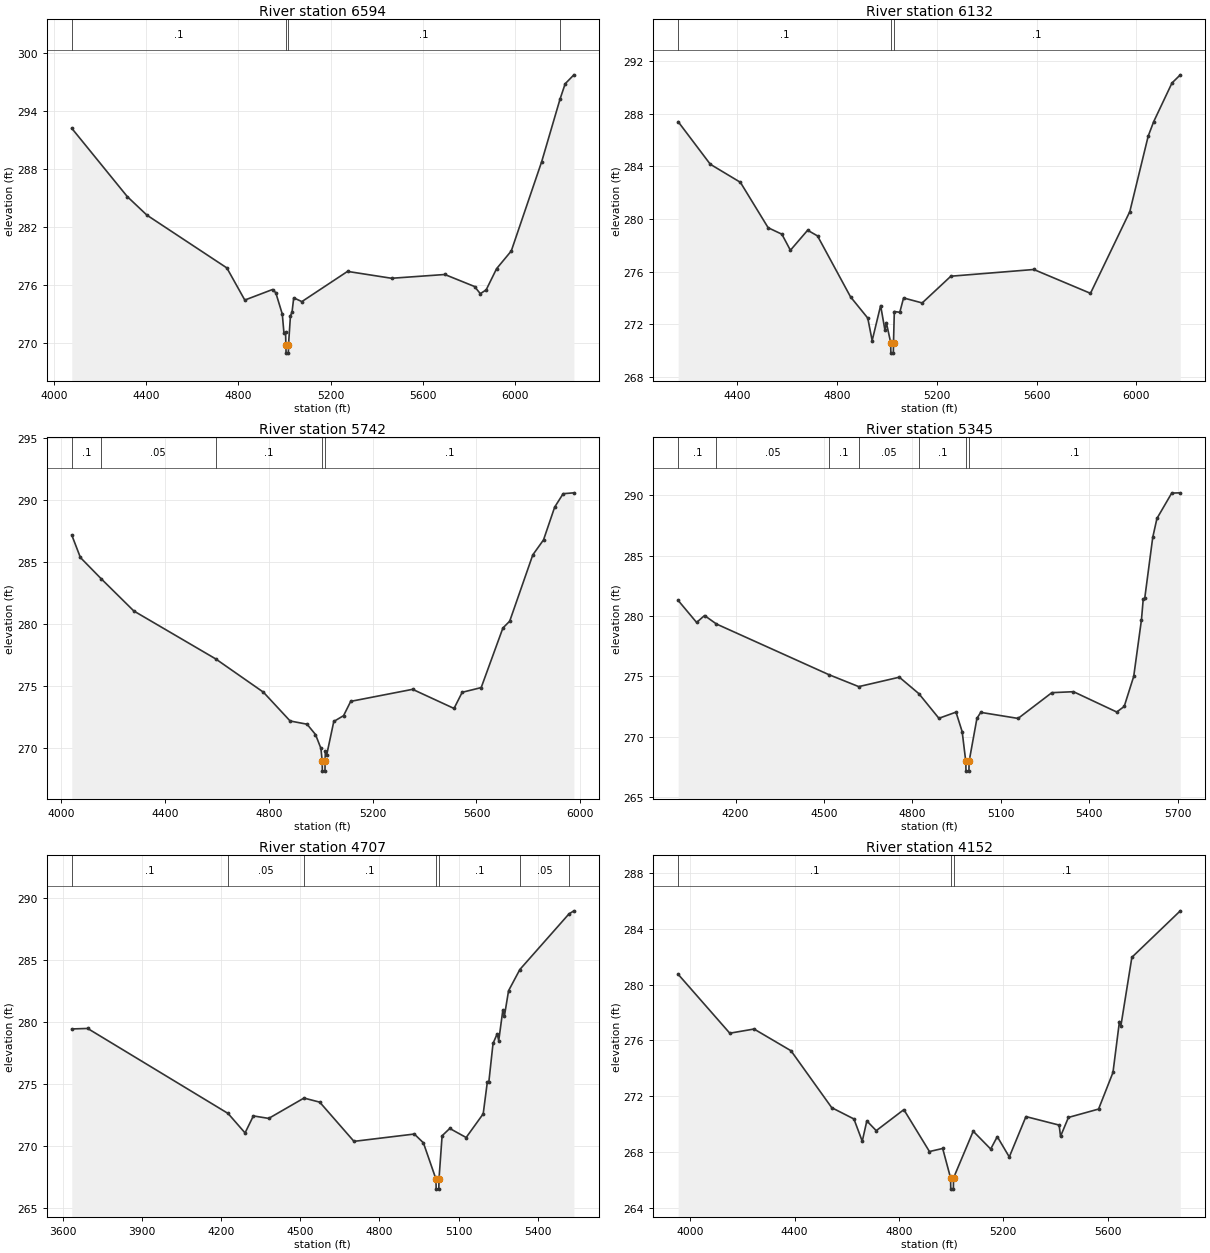
Type RM Length L Ch R = 1,6594,462,462,462
BEGIN DESCRIPTION:
Mapping XS 82fe8b6c
END DESCRIPTION:
XS GIS Cut Line= 3
      2130209.25     13401168.52      2129136.31     13402236.26
      2128912.59     13402860.59
#Sta/Elev= 30
  4077.6  292.19  4318.5  285.13  4403.4  283.22  4749.9  277.77  4827.7  274.45
  4947.9  275.54  4962.0  275.21  4990.3  273.00  4997.4  271.06  5004.4  271.12
  5005.9  269.77  5006.6  268.97  5016.5  268.97  5017.1  269.77  5025.6  272.81
  5032.7  273.24  5039.8  274.68  5075.1  274.29  5273.1  277.41  5464.1  276.70
  5694.9  277.09  5823.7  275.85  5848.7  275.11  5874.1  275.50  5919.3  277.69
  5983.0  279.52  6114.9  288.75  6194.2  295.19  6216.7  296.79  6254.5  297.71
#Mann=4,-1,0
  4077.6     0.1       0  5005.9    0.07       0  5017.1     0.1       0
  6194.2    0.05       0
Bank Sta=5005.9,5017.1
Exp/Cntr=0.3,0.1

Type RM Length L Ch R = 1,6132,390,390,390
BEGIN DESCRIPTION:
Mapping XS 491c9b0b
END DESCRIPTION:
XS GIS Cut Line= 3
      2129615.46     13400876.90      2129026.93     13402163.34
      2128750.87     13402694.63
#Sta/Elev= 30
  4162.9  287.39  4291.7  284.16  4412.3  282.79  4523.7  279.34  4578.7  278.85
  4612.9  277.63  4682.0  279.15  4721.6  278.72  4854.1  274.09  4923.1  272.48
  4940.7  270.77  4974.7  273.43  4992.2  271.54  4997.7  272.13  5015.0  270.62
  5015.7  269.82  5025.6  269.82  5026.3  270.62  5029.6  272.98  5051.5  272.92
  5066.7  274.01  5141.3  273.63  5256.3  275.66  5588.8  276.17  5816.1  274.36
  5973.9  280.57  6047.6  286.30  6069.7  287.40  6142.9  290.33  6176.3  290.95
#Mann=3,-1,0
  4162.9     0.1       0  5015.0    0.07       0  5026.3     0.1       0
Bank Sta=5015,5026.3
Exp/Cntr=0.3,0.1

Type RM Length L Ch R = 1,5742,397,397,397
BEGIN DESCRIPTION:
Mapping XS 3142e49c
END DESCRIPTION:
XS GIS Cut Line= 2
      2129219.63     13400767.55      2128646.73     13402616.43
#Sta/Elev= 30
  4040.0  287.16  4073.2  285.35  4152.8  283.65  4279.3  281.04  4594.1  277.19
  4778.7  274.50  4881.7  272.18  4946.9  271.92  4979.5  271.09  5000.5  269.97
  5005.3  268.94  5006.0  268.14  5016.0  268.14  5016.6  268.94  5017.4  269.78
  5022.6  269.44  5050.0  272.14  5087.8  272.61  5115.2  273.76  5353.8  274.73
  5513.5  273.19  5544.9  274.49  5618.2  274.87  5701.9  279.67  5728.1  280.22
  5817.1  285.56  5858.5  286.77  5901.5  289.41  5934.1  290.49  5975.6  290.56
#Mann=5,-1,0
  4040.0     0.1       0  4152.8    0.05       0  4594.1     0.1       0
  5005.3    0.07       0  5016.6     0.1       0
Bank Sta=5005.3,5016.6
Exp/Cntr=0.3,0.1

Type RM Length L Ch R = 1,5345,638,638,638
BEGIN DESCRIPTION:
Mapping XS f9c364a7
END DESCRIPTION:
XS GIS Cut Line= 2
      2128917.56     13400736.23      2128402.13     13402360.62
#Sta/Elev= 30
  4005.1  281.29  4067.6  279.47  4094.6  280.04  4135.0  279.34  4516.5  275.15
  4618.0  274.16  4755.7  274.94  4821.9  273.58  4890.0  271.54  4948.0  272.05
  4969.0  270.43  4981.2  267.97  4981.9  267.17  4991.9  267.17  4992.5  267.97
  5019.1  271.54  5032.0  272.03  5158.7  271.53  5273.3  273.66  5346.7  273.74
  5493.6  272.06  5518.9  272.52  5551.2  275.01  5577.5  279.70  5583.4  281.38
  5588.7  281.49  5615.7  286.50  5630.0  288.07  5680.2  290.17  5709.3  290.19
#Mann=7,-1,0
  4005.1     0.1       0  4135.0    0.05       0  4516.5     0.1       0
  4618.0    0.05       0  4821.9     0.1       0  4981.2    0.07       0
  4992.5     0.1       0
Bank Sta=4981.2,4992.5
Exp/Cntr=0.3,0.1

Type RM Length L Ch R = 1,4707,555,555,555
BEGIN DESCRIPTION:
Mapping XS 94fc4025
END DESCRIPTION:
XS GIS Cut Line= 3
      2128662.36     13400621.63      2128089.43     13401960.21
      2128313.39     13402345.63
#Sta/Elev= 30
  3635.0  279.46  3695.2  279.50  4226.9  272.65  4291.3  271.08  4322.8  272.45
  4380.9  272.25  4514.5  273.89  4574.1  273.56  4703.8  270.40  4932.4  270.99
  4966.8  270.28  5014.5  267.35  5015.1  266.55  5025.1  266.55  5025.8  267.35
  5037.6  270.85  5066.6  271.44  5128.7  270.71  5193.3  272.62  5209.0  275.20
  5214.8  275.22  5230.5  278.29  5246.3  279.07  5252.1  278.52  5267.8  281.00
  5273.6  280.50  5289.3  282.54  5332.1  284.25  5518.0  288.73  5536.8  288.98
#Mann=7,-1,0
  3635.0     0.1       0  4226.9    0.05       0  4514.5     0.1       0
  5014.5    0.07       0  5025.8     0.1       0  5332.1    0.05       0
  5518.0     0.1       0
Bank Sta=5014.5,5025.8
Exp/Cntr=0.3,0.1

Type RM Length L Ch R = 1,4152,581,581,581
BEGIN DESCRIPTION:
Mapping XS ebb66a8b
END DESCRIPTION:
XS GIS Cut Line= 3
      2128386.30     13400491.47      2127938.39     13401731.05
      2128151.94     13402298.79
#Sta/Elev= 30
  3953.9  280.75  4151.7  276.52  4244.7  276.82  4386.3  275.26  4542.5  271.17
  4627.5  270.36  4659.4  268.76  4677.0  270.22  4713.0  269.52  4818.9  271.03
  4917.0  268.02  4967.7  268.24  4998.0  266.12  4998.7  265.32  5008.7  265.32
  5009.3  266.12  5084.7  269.48  5151.7  268.20  5177.0  269.09  5223.0  267.63
  5286.8  270.53  5414.1  269.92  5419.4  269.11  5449.7  270.47  5565.2  271.07
  5620.4  273.70  5645.2  277.36  5650.6  277.03  5692.8  281.97  5878.5  285.31
#Mann=3,-1,0
  3953.9     0.1       0  4998.0    0.07       0  5009.3     0.1       0
Bank Sta=4998,5009.3
Exp/Cntr=0.3,0.1

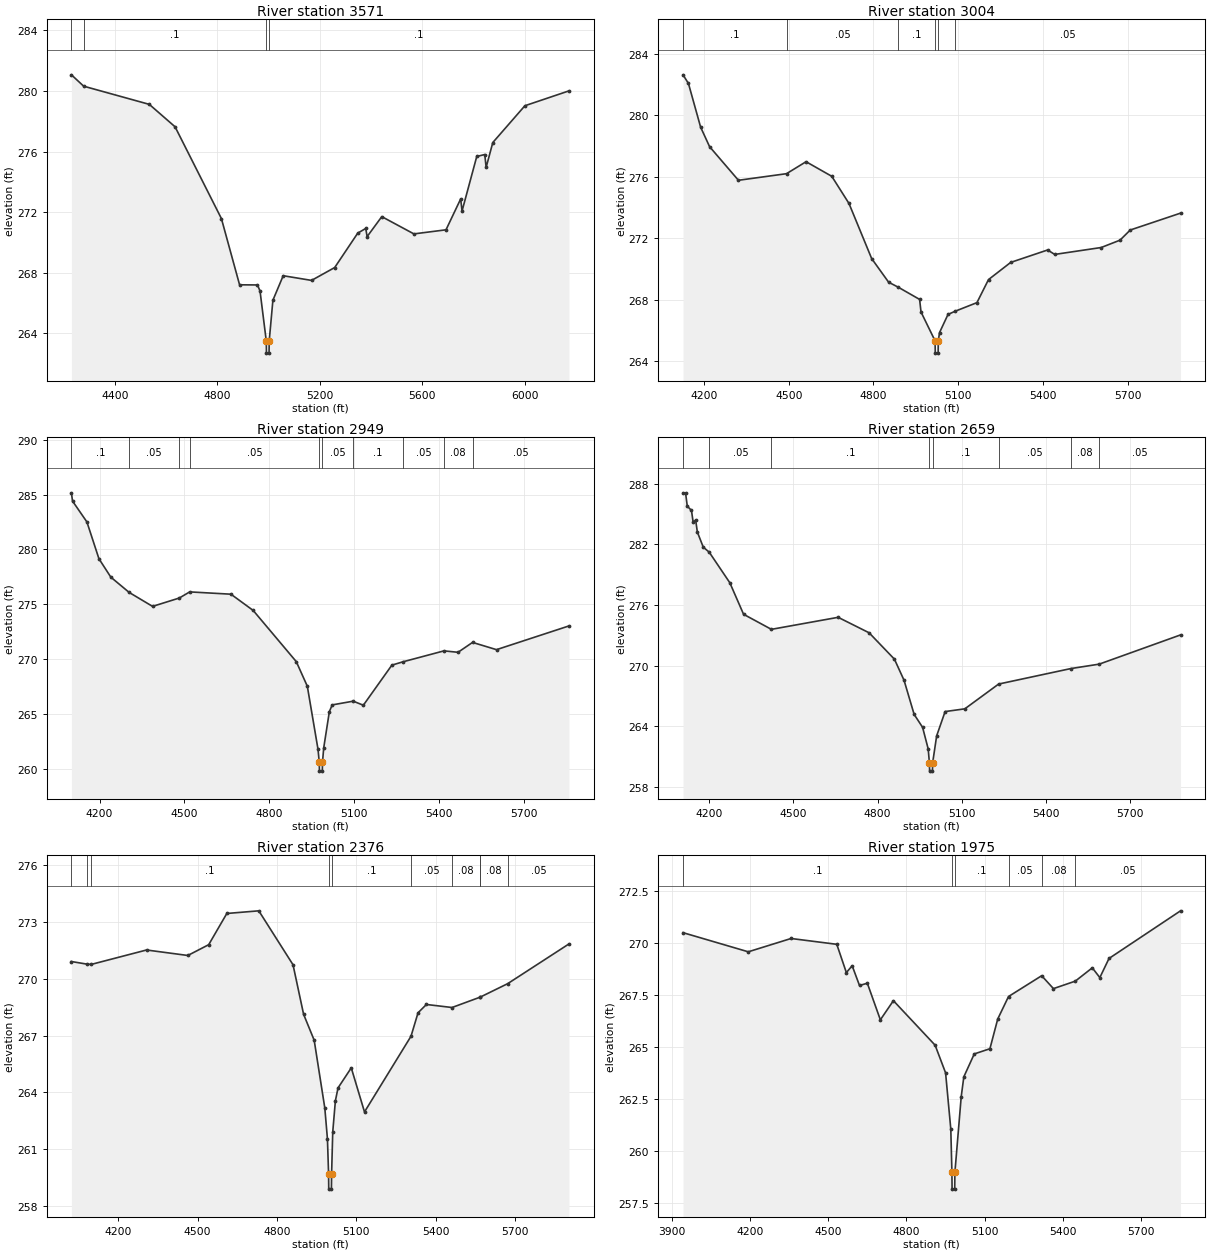
Type RM Length L Ch R = 1,3571,567,567,567
BEGIN DESCRIPTION:
Mapping XS 40453a86
END DESCRIPTION:
XS GIS Cut Line= 3
      2127834.23     13400392.48      2127730.06     13401444.59
      2128015.97     13402281.55
#Sta/Elev= 30
  4230.3  281.07  4278.1  280.32  4534.3  279.12  4634.8  277.64  4815.7  271.58
  4886.6  267.21  4956.4  267.20  4966.4  266.80  4990.8  263.50  4991.5  262.70
  5001.6  262.70  5002.2  263.50  5016.6  266.19  5056.8  267.81  5167.4  267.50
  5257.8  268.35  5347.7  270.62  5379.0  270.93  5384.3  270.39  5441.6  271.71
  5566.9  270.57  5692.2  270.84  5749.5  272.88  5754.8  272.08  5812.2  275.68
  5843.5  275.81  5848.8  274.96  5874.8  276.60  6000.1  279.03  6172.0  280.01
#Mann=4,-1,0
  4230.3    0.05       0  4278.1     0.1       0  4990.8    0.07       0
  5002.2     0.1       0
Bank Sta=4990.8,5002.2
Exp/Cntr=0.3,0.1

Type RM Length L Ch R = 1,3004,55,55,55
BEGIN DESCRIPTION:
Mapping XS 81db1eda
END DESCRIPTION:
XS GIS Cut Line= 5
      2127518.25     13400231.05      2127407.14     13400425.49
      2127469.64     13400845.63      2127490.47     13401234.52
      2127660.31     13401938.15
#Sta/Elev= 30
  4125.6  282.64  4144.8  282.08  4188.0  279.23  4219.7  277.96  4321.9  275.77
  4492.2  276.20  4561.4  276.98  4652.4  276.03  4713.4  274.26  4793.7  270.67
  4853.8  269.13  4888.3  268.80  4963.5  268.01  4968.5  267.19  5018.3  265.31
  5019.0  264.51  5029.1  264.51  5029.7  265.31  5034.1  265.85  5064.1  267.03
  5089.5  267.24  5166.6  267.80  5207.5  269.30  5286.1  270.42  5416.9  271.23
  5442.0  270.94  5606.6  271.39  5673.3  271.87  5709.5  272.53  5887.6  273.63
#Mann=6,-1,0
  4125.6     0.1       0  4492.2    0.05       0  4888.3     0.1       0
  5018.3    0.07       0  5029.7     0.1       0  5089.5    0.05       0
Bank Sta=5018.3,5029.7
Exp/Cntr=0.3,0.1

Type RM Length L Ch R = 1,2949,290,290,290
BEGIN DESCRIPTION:
Mapping XS 42f2bd9f
END DESCRIPTION:
XS GIS Cut Line= 5
      2127493.93     13400189.40      2127358.53     13400394.24
      2127434.92     13400974.10      2127434.92     13401227.58
      2127556.37     13401890.35
#Sta/Elev= 30
  4100.7  285.16  4104.6  284.41  4155.4  282.51  4197.9  279.16  4240.0  277.48
  4304.8  276.09  4387.4  274.82  4481.7  275.58  4518.6  276.14  4664.3  275.93
  4742.9  274.45  4895.1  269.79  4934.1  267.55  4972.0  261.79  4976.3  260.62
  4977.0  259.82  4987.1  259.82  4987.7  260.62  4992.0  261.93  5012.0  265.24
  5022.0  265.85  5096.3  266.19  5132.0  265.82  5232.8  269.47  5271.4  269.77
  5416.9  270.77  5466.6  270.64  5517.8  271.54  5602.5  270.88  5858.4  273.04
#Mann=10,-1,0
  4100.7     0.1       0  4304.8    0.05       0  4481.7     0.1       0
  4518.6    0.05       0  4976.3    0.04       0  4987.7    0.05       0
  5096.3     0.1       0  5271.4    0.05       0  5416.9    0.08       0
  5517.8    0.05       0
Bank Sta=4976.3,4987.7
Exp/Cntr=0.3,0.1

Type RM Length L Ch R = 1,2659,283,283,283
BEGIN DESCRIPTION:
Mapping XS 7dd4f301
END DESCRIPTION:
XS GIS Cut Line= 4
      2127438.41     13400137.27      2127230.06     13400442.85
      2127171.03     13401258.83      2127288.90     13401830.85
#Sta/Elev= 30
  4107.1  287.09  4116.2  287.08  4122.3  285.77  4137.2  285.35  4143.2  284.19
  4152.1  284.40  4158.2  283.21  4179.2  281.72  4200.5  281.22  4273.8  278.20
  4322.8  275.08  4421.9  273.59  4659.6  274.78  4769.9  273.25  4860.1  270.64
  4894.4  268.55  4930.3  265.18  4960.4  263.90  4980.4  261.76  4984.7  260.37
  4985.4  259.57  4995.5  259.57  4996.1  260.37  5010.5  263.06  5040.6  265.46
  5110.8  265.73  5231.2  268.18  5488.1  269.71  5589.5  270.15  5879.1  273.04
#Mann=8,-1,0
  4107.1     0.1       0  4200.5    0.05       0  4421.9     0.1       0
  4984.7    0.07       0  4996.1     0.1       0  5231.2    0.05       0
  5488.1    0.08       0  5589.5    0.05       0
Bank Sta=4984.7,4996.1
Exp/Cntr=0.3,0.1

Type RM Length L Ch R = 1,2376,401,401,401
BEGIN DESCRIPTION:
Mapping XS bbb3c1c7
END DESCRIPTION:
XS GIS Cut Line= 4
      2127243.93     13400026.21      2126924.50     13400442.85
      2126945.33     13401119.94      2127160.62     13401762.32
#Sta/Elev= 30
  4023.1  270.92  4082.7  270.78  4098.7  270.77  4307.0  271.53  4462.9  271.24
  4541.8  271.81  4610.3  273.46  4731.1  273.60  4860.4  270.75  4900.4  268.13
  4940.4  266.76  4980.5  263.18  4990.5  261.54  4994.8  259.69  4995.4  258.89
  5005.5  258.89  5006.2  259.69  5010.5  261.91  5020.5  263.56  5030.5  264.24
  5080.5  265.30  5130.5  262.97  5306.2  266.97  5332.8  268.21  5364.4  268.65
  5461.2  268.49  5566.1  269.03  5566.4  269.03  5671.5  269.75  5903.0  271.85
#Mann=10,-1,0
  4023.1     0.1       0  4082.7    0.05       0  4098.7     0.1       0
  4994.8    0.07       0  5006.2     0.1       0  5306.2    0.05       0
  5461.2    0.08       0  5566.1    0.05       0  5566.4    0.08       0
  5671.5    0.05       0
Bank Sta=4994.8,5006.2
Exp/Cntr=0.3,0.1

Type RM Length L Ch R = 1,1975,295,295,295
BEGIN DESCRIPTION:
Mapping XS 9ed23734
END DESCRIPTION:
XS GIS Cut Line= 4
      2126910.60     13400022.73      2126702.28     13400633.83
      2126712.69     13401237.99      2127121.22     13401753.84
#Sta/Elev= 30
  3943.6  270.50  4193.8  269.58  4358.0  270.22  4533.3  269.94  4570.0  268.58
  4592.3  268.91  4620.4  267.96  4650.4  268.07  4700.4  266.31  4750.4  267.23
  4910.4  265.09  4950.5  263.76  4970.5  261.06  4974.8  258.97  4975.4  258.17
  4985.5  258.17  4986.2  258.97  5010.5  262.62  5020.5  263.57  5060.5  264.67
  5120.5  264.92  5150.5  266.35  5191.9  267.43  5319.0  268.43  5364.1  267.81
  5448.0  268.17  5513.1  268.81  5542.0  268.34  5577.2  269.26  5851.5  271.55
#Mann=6,-1,0
  3943.6     0.1       0  4974.8    0.07       0  4986.2     0.1       0
  5191.9    0.05       0  5319.0    0.08       0  5448.0    0.05       0
Bank Sta=4974.8,4986.2
Exp/Cntr=0.3,0.1

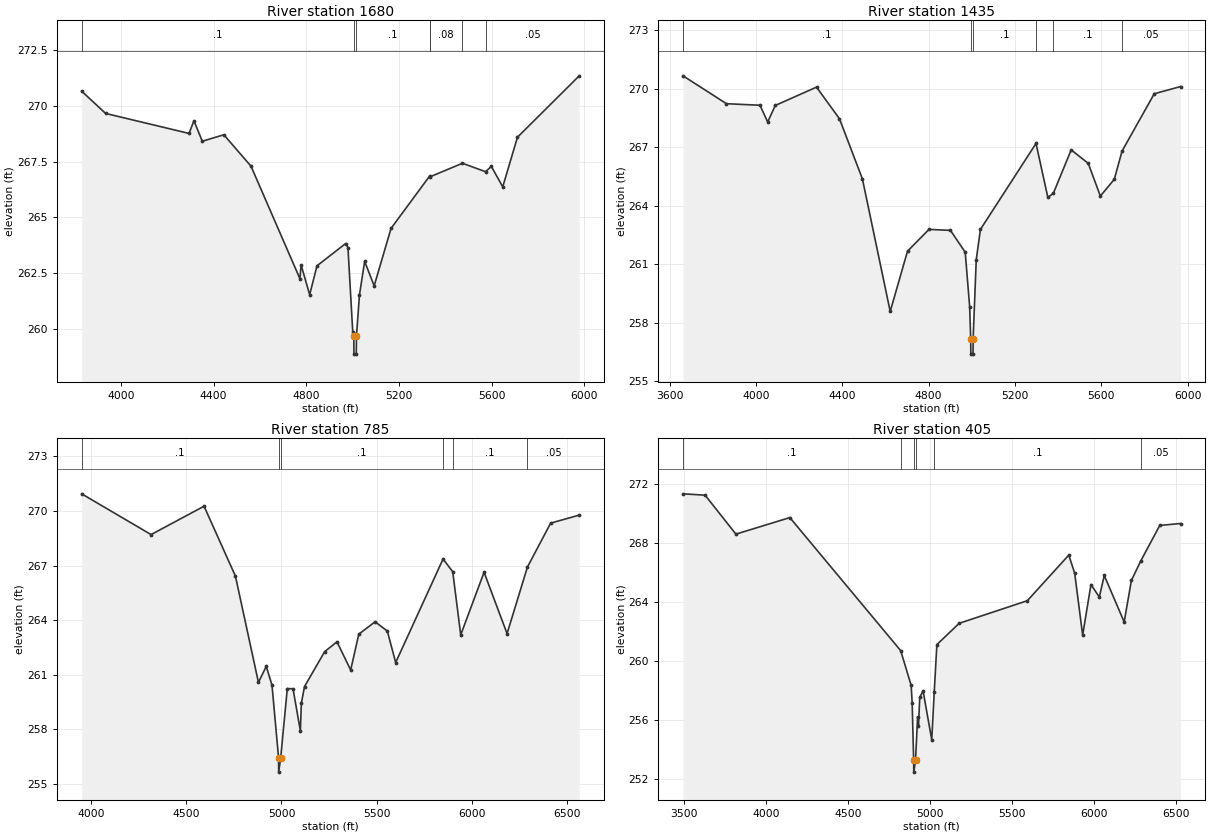
Type RM Length L Ch R = 1,1680,245,245,245
BEGIN DESCRIPTION:
Mapping XS 9b7b9b6b
END DESCRIPTION:
XS GIS Cut Line= 4
      2126868.97     13400036.57      2126362.00     13400793.55
      2126469.64     13401241.46      2127044.78     13401761.17
#Sta/Elev= 30
  3830.8  270.67  3934.0  269.67  4294.2  268.77  4315.3  269.34  4351.3  268.42
  4444.3  268.71  4561.4  267.30  4772.6  262.24  4777.7  262.86  4814.6  261.52
  4846.2  262.82  4969.6  263.82  4979.9  263.64  5000.5  259.85  5005.1  259.65
  5005.7  258.85  5015.8  258.85  5016.5  259.65  5029.5  261.51  5051.9  263.02
  5093.0  261.92  5165.7  264.50  5332.7  266.86  5333.8  266.82  5474.0  267.43
  5573.5  267.05  5598.5  267.29  5647.8  266.37  5711.3  268.60  5977.7  271.36
#Mann=7,-1,0
  3830.8     0.1       0  5005.1    0.07       0  5016.5     0.1       0
  5332.7    0.05       0  5333.8    0.08       0  5474.0     0.1       0
  5573.5    0.05       0
Bank Sta=5005.1,5016.5
Exp/Cntr=0.3,0.1

Type RM Length L Ch R = 1,1435,650,650,650
BEGIN DESCRIPTION:
Mapping XS 1853c8d5
END DESCRIPTION:
XS GIS Cut Line= 4
      2126768.28     13400053.94      2126136.31     13400734.52
      2126240.47     13401227.58      2126934.89     13401755.33
#Sta/Elev= 30
  3662.4  270.67  3863.7  269.24  4019.0  269.16  4054.7  268.30  4089.9  269.15
  4280.9  270.09  4387.1  268.47  4493.5  265.38  4622.3  258.58  4702.4  261.67
  4801.9  262.79  4901.3  262.74  4969.8  261.62  4990.3  258.83  4995.1  257.19
  4995.8  256.39  5005.9  256.39  5006.5  257.19  5020.9  261.24  5040.3  262.79
  5297.8  267.20  5352.6  264.43  5378.0  264.64  5460.7  266.87  5539.7  266.18
  5595.9  264.50  5660.4  265.36  5696.4  266.81  5845.5  269.75  5967.3  270.12
#Mann=6,-1,0
  3662.4     0.1       0  4995.1    0.07       0  5006.5     0.1       0
  5297.8    0.08       0  5378.0     0.1       0  5696.4    0.05       0
Bank Sta=4995.1,5006.5
Exp/Cntr=0.3,0.1

Type RM Length L Ch R = 1,785,380,380,380
BEGIN DESCRIPTION:
Mapping XS b0399457
END DESCRIPTION:
XS GIS Cut Line= 4
      2126726.59     13400047.02      2125966.17     13400616.46
      2125931.44     13401047.02      2126910.25     13401789.80
#Sta/Elev= 30
  3951.6  270.94  4315.9  268.70  4593.8  270.26  4758.4  266.42  4879.2  260.58
  4920.2  261.46  4950.3  260.43  4984.7  256.45  4985.4  255.65  4996.1  256.45
  5030.6  260.24  5060.7  260.23  5099.3  257.91  5104.3  259.43  5120.9  260.35
  5226.7  262.27  5291.4  262.81  5363.1  261.26  5405.9  263.23  5491.2  263.91
  5555.6  263.40  5599.3  261.67  5847.9  267.36  5898.7  266.66  5940.6  263.19
  6063.1  266.63  6183.8  263.26  6290.8  266.92  6412.5  269.33  6562.3  269.77
#Mann=6,-1,0
  3951.6     0.1       0  4984.7    0.07       0  4996.1     0.1       0
  5847.9    0.08       0  5898.7     0.1       0  6290.8    0.05       0
Bank Sta=4984.7,4996.1
Exp/Cntr=0.3,0.1

Type RM Length L Ch R = 1,405,0,0,0
BEGIN DESCRIPTION:
Mapping XS 8d3818bd
END DESCRIPTION:
XS GIS Cut Line= 4
      2126719.64     13399956.74      2125657.14     13400607.78
      2125802.97     13401097.37      2126860.11     13401805.60
#Sta/Elev= 30
  3496.3  271.32  3630.7  271.23  3818.4  268.59  4146.8  269.71  4821.7  260.70
  4885.6  258.34  4891.7  257.13  4900.7  253.27  4901.4  252.47  4912.1  253.27
  4924.8  256.22  4930.1  255.58  4937.7  257.53  4958.0  257.98  5010.8  254.66
  5026.0  257.89  5042.1  261.11  5177.9  262.55  5592.7  264.08  5845.2  267.17
  5881.2  265.94  5929.7  261.75  5980.3  265.17  6031.3  264.33  6061.3  265.79
  6182.5  262.64  6226.4  265.45  6283.3  266.77  6399.2  269.18  6525.7  269.31
#Mann=6,-1,0
  3496.3     0.1       0  4821.7    0.12       0  4900.7    0.07       0
  4912.1    0.12       0  5026.0     0.1       0  6283.3    0.05       0
Bank Sta=4900.7,4912.1
Exp/Cntr=0.3,0.1

Chan Stop Cuts=-1