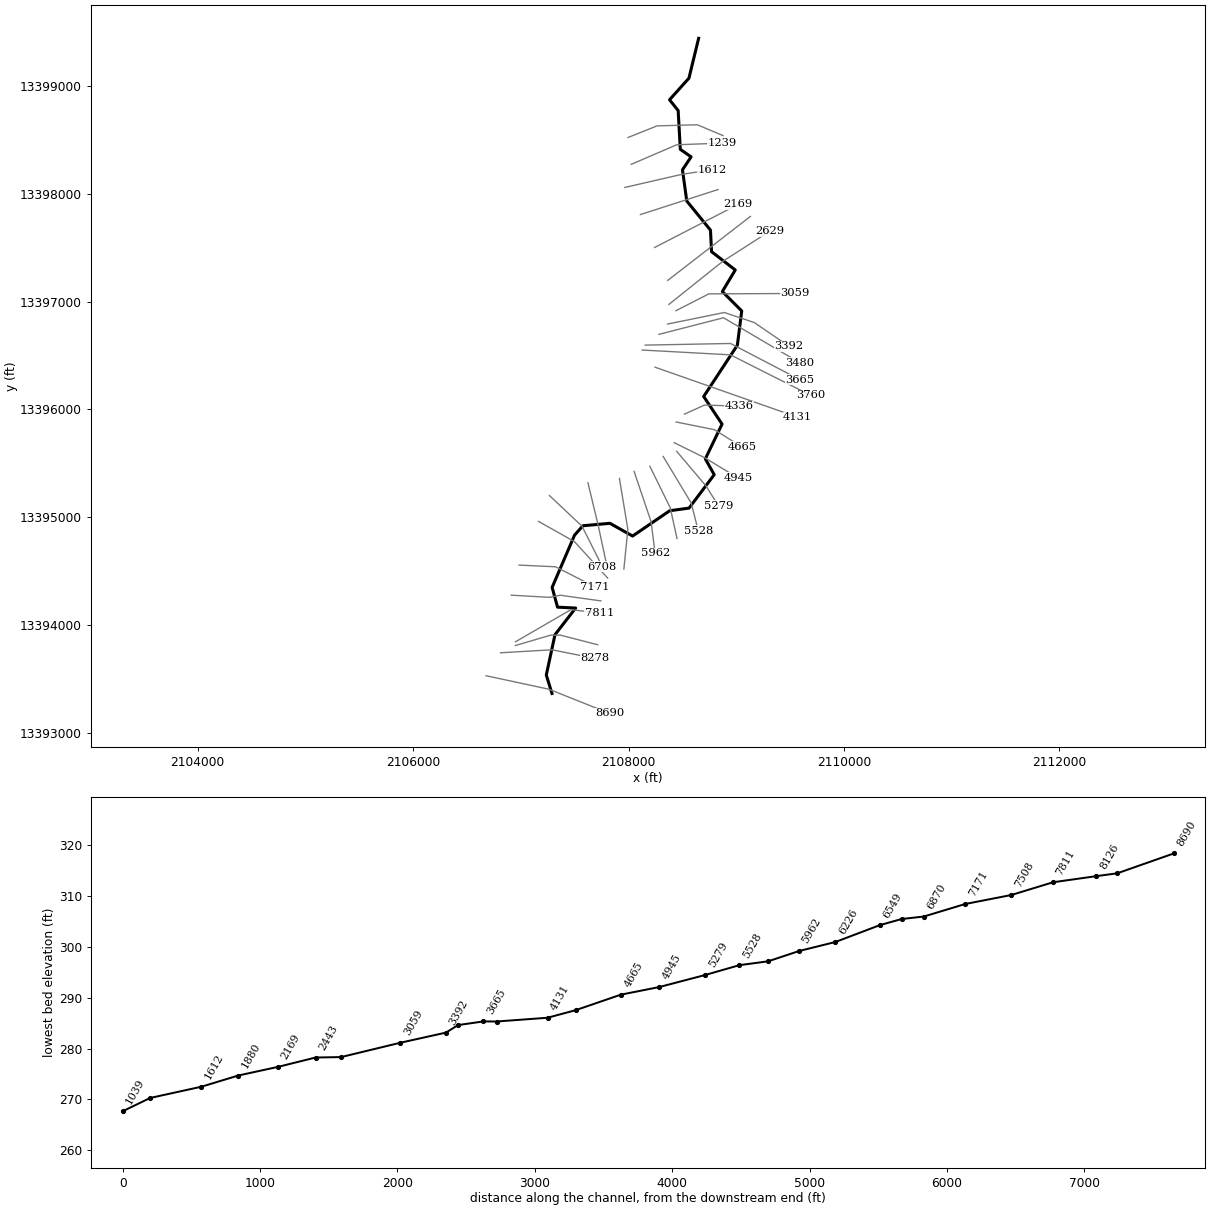
--- UNT 001 in La Jarita Watershed.prj (project) ---

Proj Title=UNT 001 in La Jarita Watershed Base Level Engineering
Current Plan=p01
Default Exp/Contr=0.3,0.1
English Units
Geom File=g01
Flow File=f01
Plan File=p01
Y Axis Title=Elevation
X Axis Title(PF)=Main Channel Distance
X Axis Title(XS)=Station
BEGIN DESCRIPTION:
UNT 001 in La Jarita Watershed
END DESCRIPTION:
DSS Export Rating Curves= 0
DSS Export Rating Curve Sorted= 0
DSS Export Volume Flow Curves= 0
DXF OffsetX= 0
DXF OffsetY= 0
DXF ScaleX= 1
DXF ScaleY= 10

--- UNT 001 in La Jarita Watershed.p01 (plan) ---

Plan Title=Multiple Run
Short Identifier=Multiple
Geom File=g01
Flow File=f01
Subcritical Flow
K Sum by GR= 0
Std Step Tol= 0.01
Critical Tol= 0.01
Num of Std Step Trials= 20
Max Error Tol= 0.3
Flow Tol Ratio= 0.001
Split Flow NTrial= 30
Split Flow Tol= 0.02
Split Flow Ratio= 0.02
Log Output Level= 0
Friction Slope Method= 1
Unsteady Friction Slope Method= 2
Unsteady Bridges Friction Slope Method= 1
Parabolic Critical Depth
Global Vel Dist=  1 , 1 , 1
Global Log Level= 0
CheckData=True
Encroach Param= -1, 0, 0, 0
BEGIN DESCRIPTION:
Multiple Run
END DESCRIPTION:

--- UNT 001 in La Jarita Watershed.f01 (steady flow) ---

Flow Title=Multiple
Program Version=5.05
Number of Profiles= 7
Profile Names=10-year,25-year,50-year,1pct_min,100-year,1pct_plu,500-year
River Rch & RM=UNT 001 in La Ja,Reach-1         ,8690
     170     233     284     173     346     691     520
River Rch & RM=UNT 001 in La Ja,Reach-1         ,3760
     223     309     381     234     467     933     715
Boundary for River Rch & Prof#=UNT 001 in La Ja,Reach-1         , 1
Up Type= 0
Dn Type= 3
Dn Slope=0.005
Boundary for River Rch & Prof#=UNT 001 in La Ja,Reach-1         , 2
Up Type= 0
Dn Type= 3
Dn Slope=0.005
Boundary for River Rch & Prof#=UNT 001 in La Ja,Reach-1         , 3
Up Type= 0
Dn Type= 3
Dn Slope=0.005
Boundary for River Rch & Prof#=UNT 001 in La Ja,Reach-1         , 4
Up Type= 0
Dn Type= 3
Dn Slope=0.005
Boundary for River Rch & Prof#=UNT 001 in La Ja,Reach-1         , 5
Up Type= 0
Dn Type= 3
Dn Slope=0.005
Boundary for River Rch & Prof#=UNT 001 in La Ja,Reach-1         , 6
Up Type= 0
Dn Type= 3
Dn Slope=0.005
Boundary for River Rch & Prof#=UNT 001 in La Ja,Reach-1         , 7
Up Type= 0
Dn Type= 3
Dn Slope=0.005
DSS Import GetInterval= 0
DSS Import GetPeak= 0
DSS Import FillOption= 0

--- UNT 001 in La Jarita Watershed.g01 (geometry) ---

Geom Title=Existing Conditions
Program Version=5.05

River Reach=UNT 001 in La Ja,Reach-1
Reach XY= 30
      2107289.62     13393364.43      2107236.92     13393535.42
      2107317.64      13393909.9      2107509.56     13394157.18
      2107341.52     13394165.21       2107291.2     13394348.87
      2107499.42     13394834.13      2107577.37     13394920.93
       2107827.4     13394943.49      2108037.85     13394825.31
      2108382.55     13395060.19      2108561.93     13395084.65
       2108795.6     13395394.82      2108712.96     13395541.58
       2108868.3     13395864.44      2108697.72     13396120.71
      2109010.34     13396596.55       2109050.8     13396914.54
       2108870.8     13397094.54       2108990.8     13397294.54
       2108770.8     13397464.54       2108760.8     13397664.54
       2108540.8     13397934.54       2108500.8     13398224.54
       2108580.8     13398344.54       2108480.8     13398414.54
       2108460.8     13398774.54       2108380.8     13398874.54
       2108560.8     13399074.54       2108650.8     13399444.54

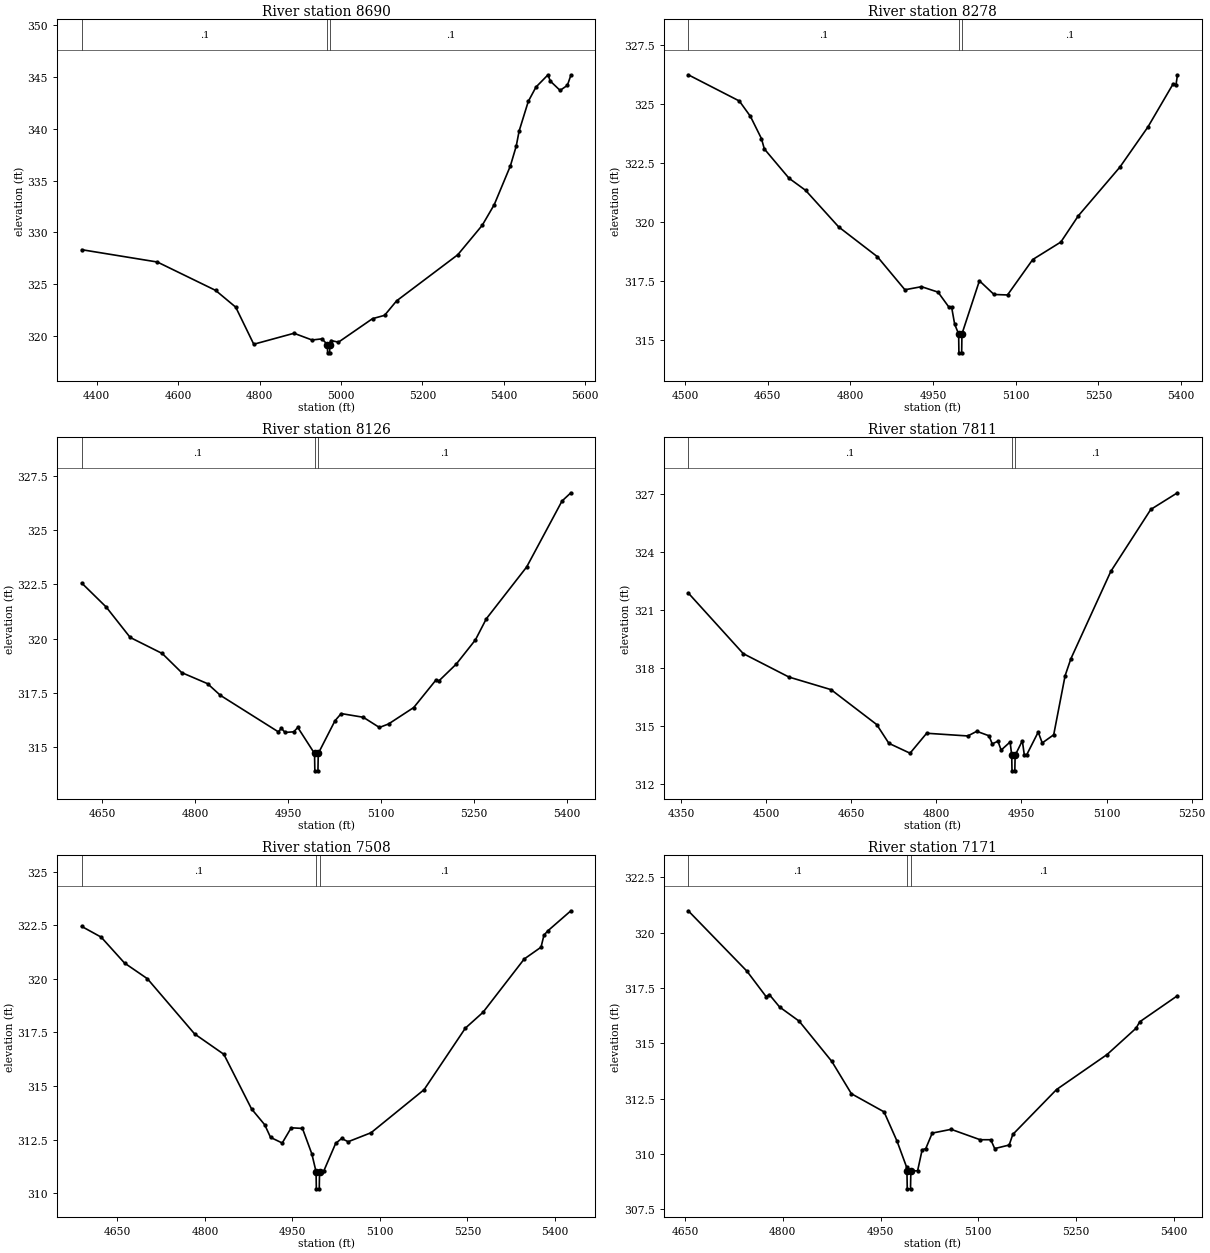
Type RM Length L Ch R = 1 ,8690    ,412,412,412
BEGIN DESCRIPTION:
Mapping XS 63cd36f4
END DESCRIPTION:
XS GIS Cut Line= 3
      2106677.98     13393528.89       2107261.4     13393403.75
      2107823.01     13393179.53
#Sta/Elev= 30
  4363.3  328.33  4549.1  327.14  4692.2   324.4  4741.6  322.78  4785.9   319.2
  4884.7  320.26    4929  319.61  4953.4  319.72  4966.7  319.17  4967.2  318.37
  4972.2  318.37  4972.7  319.17  4975.1  319.56  4993.9   319.4  5077.5  321.67
  5107.1  321.99  5136.7  323.39  5286.9  327.84  5346.9  330.68  5376.5  332.68
  5416.1  336.42  5430.4  338.32  5437.6  339.79  5460.1  342.65  5478.9  344.03
  5508.6  345.22  5513.9  344.62  5538.2  343.71  5556.1   344.2  5564.7  345.18
#Mann= 3 ,-1 , 0
  4363.3      .1       0  4966.7     .07       0  4972.7      .1       0
Bank Sta=4966.7,4972.7
XS Rating Curve= 0 ,0
Exp/Cntr=0.3,0.1

Type RM Length L Ch R = 1 ,8278    ,152,152,152
BEGIN DESCRIPTION:
Mapping XS 65ac5726
END DESCRIPTION:
XS GIS Cut Line= 3
      2106812.42     13393741.98      2107289.65      13393769.7
      2107691.45     13393689.27
#Sta/Elev= 30
  4505.8  326.23  4598.5  325.12  4618.6  324.47  4638.6  323.53  4643.9  323.09
  4688.7  321.85  4718.7  321.34  4778.8  319.79    4849  318.53    4899  317.13
  4929.1  317.26  4959.1  317.03    4979  316.39  4983.8  316.39  4989.3  315.67
  4996.5  315.26    4997  314.46    5002  314.46  5002.5  315.26  5034.2  317.51
  5060.7  316.93  5085.2  316.91    5131  318.41    5182  319.15  5213.7  320.26
  5289.1  322.32    5340  324.02  5385.9  325.85    5391  325.81  5393.6  326.22
#Mann= 3 ,-1 , 0
  4505.8      .1       0  4996.5     .07       0  5002.5      .1       0
Bank Sta=4996.5,5002.5
XS Rating Curve= 0 ,0
Exp/Cntr=0.3,0.1

Type RM Length L Ch R = 1 ,8126    ,315,315,315
BEGIN DESCRIPTION:
Mapping XS a110767c
END DESCRIPTION:
XS GIS Cut Line= 4
      2106950.37     13393809.31      2107278.46      13393905.7
      2107366.29     13393906.03      2107714.06     13393816.48
#Sta/Elev= 30
  4617.2  322.56  4656.8  321.45  4695.4  320.05  4747.1  319.31  4778.4  318.43
  4820.1  317.92  4840.9  317.38  4934.2   315.7  4939.4  315.86  4945.1  315.67
  4959.2   315.7  4965.7   315.9  4992.7   314.7  4993.2   313.9  4998.2   313.9
  4998.7   314.7  5025.7  316.21  5035.7  316.54  5071.3  316.37  5097.3   315.9
    5112  316.06  5152.7  316.82  5188.3  318.08  5193.4  318.05  5221.2  318.82
  5252.2  319.94  5269.7  320.91  5334.8   323.3  5391.8  326.34  5406.1  326.72
#Mann= 3 ,-1 , 0
  4617.2      .1       0  4992.7     .07       0  4998.7      .1       0
Bank Sta=4992.7,4998.7
XS Rating Curve= 0 ,0
Exp/Cntr=0.3,0.1

Type RM Length L Ch R = 1 ,7811    ,303,303,303
BEGIN DESCRIPTION:
Mapping XS 6f1f478e
END DESCRIPTION:
XS GIS Cut Line= 3
      2106951.47     13393844.17      2107465.84     13394142.37
      2107731.65      13394111.1
#Sta/Elev= 30
  4362.7  321.88  4459.6  318.75  4540.2  317.54  4614.4  316.89  4694.8  315.09
  4716.3  314.12  4753.6  313.61  4782.9  314.64  4855.4   314.5  4871.2  314.74
  4892.7  314.51  4898.5  314.09  4908.5  314.23  4914.2  313.77    4930  314.19
  4932.8   313.5  4933.3   312.7  4938.3   312.7  4938.8   313.5  4951.5  314.25
  4954.9  313.54  4959.4  313.54  4979.5   314.7  4986.6  314.14  5006.8  314.56
  5026.9  317.61    5037  318.48  5107.4  322.99  5177.9  326.19  5224.9  327.05
#Mann= 3 ,-1 , 0
  4362.7      .1       0  4932.8     .07       0  4938.8      .1       0
Bank Sta=4932.8,4938.8
XS Rating Curve= 0 ,0
Exp/Cntr=0.3,0.1

Type RM Length L Ch R = 1 ,7508    ,337,337,337
BEGIN DESCRIPTION:
Mapping XS a9ceddf1
END DESCRIPTION:
XS GIS Cut Line= 4
      2106911.64     13394276.58      2107270.67     13394256.28
      2107366.06      13394276.1      2107744.28     13394223.43
#Sta/Elev= 30
  4588.7  322.45  4622.1  321.95  4662.2  320.74  4701.3  320.01  4782.4  317.43
  4832.5  316.48    4880  313.93  4902.6  313.19  4912.6   312.6  4932.6  312.34
    4948  313.05  4967.3  313.02  4983.4  311.83  4990.6     311  4991.1   310.2
  4996.1   310.2  4996.6     311  5003.8  311.03  5024.2  312.32  5034.4  312.55
  5045.7   312.4    5085  312.82  5175.9  314.83  5246.6   317.7  5276.9  318.44
  5347.6  320.93  5376.4  321.48  5381.4  322.04  5387.9  322.24  5427.6  323.18
#Mann= 3 ,-1 , 0
  4588.7      .1       0  4990.6     .07       0  4996.6      .1       0
Bank Sta=4990.6,4996.6
XS Rating Curve= 0 ,0
Exp/Cntr=0.3,0.1

Type RM Length L Ch R = 1 ,7171    ,301,301,301
BEGIN DESCRIPTION:
Mapping XS e66d5f45
END DESCRIPTION:
XS GIS Cut Line= 3
      2106985.06     13394555.87      2107323.08     13394539.81
      2107690.22     13394353.07
#Sta/Elev= 30
  4655.1  320.99  4745.1  318.26  4774.5  317.11  4779.5   317.2  4795.2  316.64
  4825.2     316  4875.3  314.18  4905.3  312.72  4955.4   311.9  4975.4  310.57
    4990   309.4  4990.5  309.22    4991  308.42    4996  308.42  4996.5  309.22
  5006.9  309.24  5013.8  310.18  5019.4  310.24  5029.3  310.94  5058.3  311.11
  5102.8  310.64  5119.1  310.64  5125.1  310.24  5147.3   310.4  5152.9  310.88
    5220  312.91  5297.4  314.49  5341.9  315.68  5347.5  315.97  5405.4  317.15
#Mann= 3 ,-1 , 0
  4655.1      .1       0  4990.5     .07       0  4996.5      .1       0
Bank Sta=4990.5,4996.5
XS Rating Curve= 0 ,0
Exp/Cntr=0.3,0.1

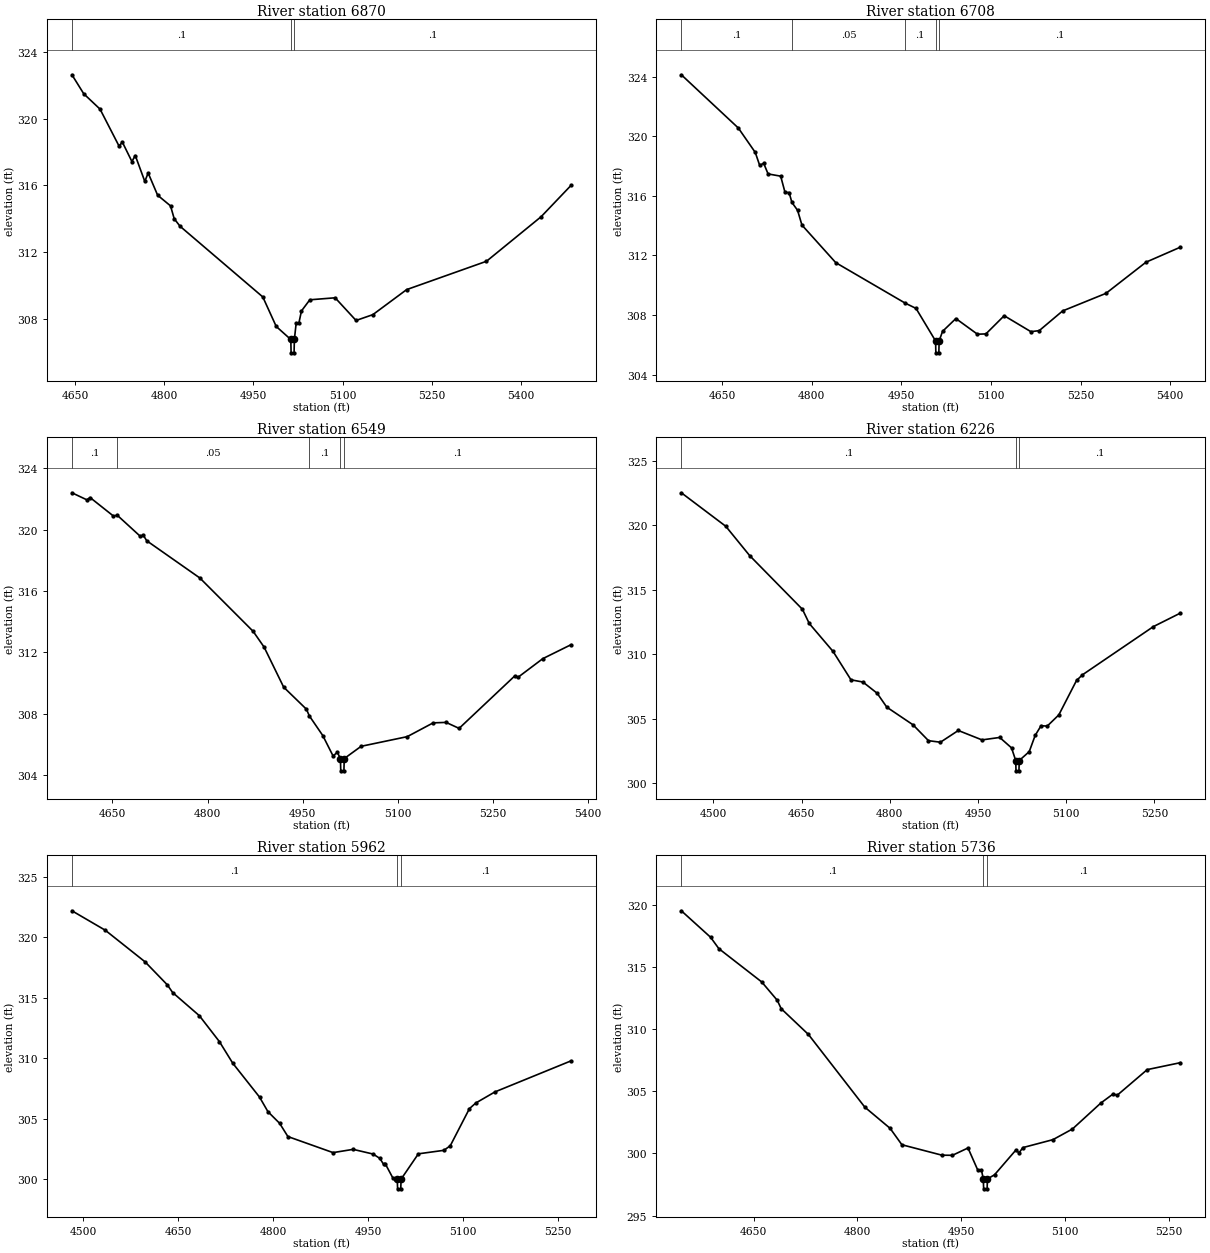
Type RM Length L Ch R = 1 ,6870    ,162,162,162
BEGIN DESCRIPTION:
Mapping XS 0927d3ff
END DESCRIPTION:
XS GIS Cut Line= 3
      2107164.93     13394961.01      2107497.87     13394774.05
      2107806.53      13394435.6
#Sta/Elev= 30
  4644.7  322.63  4664.6  321.49    4692  320.57  4723.9  318.36  4729.6  318.59
  4745.6  317.43  4751.3  317.79  4767.3  316.24    4773  316.74  4788.9  315.41
  4810.6  314.77  4816.8     314  4826.6  313.55  4965.9  309.31  4988.5  307.54
    5013  306.76  5013.5  305.96  5018.5  305.96    5019  306.76    5022  307.73
  5026.5  307.73  5030.9  308.47    5045  309.14  5087.6  309.26  5122.8   307.9
  5151.1  308.25  5207.9  309.75  5342.3  311.45  5434.2  314.12  5484.6     316
#Mann= 3 ,-1 , 0
  4644.7      .1       0    5013     .07       0    5019      .1       0
Bank Sta=5013,5019
XS Rating Curve= 0 ,0
Exp/Cntr=0.3,0.1

Type RM Length L Ch R = 1 ,6708    ,159,159,159
BEGIN DESCRIPTION:
Mapping XS e3d63779
END DESCRIPTION:
XS GIS Cut Line= 3
      2107266.05     13395201.22      2107568.74     13394916.85
      2107757.24     13394541.21
#Sta/Elev= 30
  4581.5  324.12  4676.9  320.55  4705.3  318.91  4712.6  318.05  4719.4  318.18
  4726.7  317.47  4747.8  317.32  4755.1  316.23  4761.9  316.22  4766.6  315.56
  4776.1  315.03  4783.4  314.04    4840  311.52    4956  308.81  4974.4  308.45
  5007.1  306.27  5007.6  305.47  5012.6  305.47  5013.1  306.27  5018.8  306.91
  5041.1  307.77  5077.2  306.72  5091.4  306.74    5122  307.96  5166.7  306.89
  5180.7  306.96  5219.8  308.28  5292.4  309.46  5359.4  311.55  5417.1  312.56
#Mann= 5 ,-1 , 0
  4581.5      .1       0  4766.6     .05       0    4956      .1       0
  5007.1     .07       0  5013.1      .1       0
Bank Sta=5007.1,5013.1
XS Rating Curve= 0 ,0
Exp/Cntr=0.3,0.1

Type RM Length L Ch R = 1 ,6549    ,323,323,323
BEGIN DESCRIPTION:
Mapping XS ce7b071a
END DESCRIPTION:
XS GIS Cut Line= 3
      2107623.75     13395319.61      2107720.72     13394915.47
      2107798.44     13394552.41
#Sta/Elev= 30
  4586.1   322.4  4609.6  321.94  4614.7  322.09  4651.6  320.88  4657.4  320.94
  4693.6  319.57  4698.7  319.63    4704  319.27  4787.8  316.84  4871.8  313.36
  4889.1  312.33  4919.9  309.72  4955.8  308.28  4960.3  307.85  4981.6  306.56
  4997.8  305.23  5004.5  305.47  5009.4  305.06  5009.9  304.26  5014.9  304.26
  5015.4  305.06    5042  305.86  5114.7  306.49  5155.6  307.39    5176  307.42
  5196.5  307.03  5284.2  310.45  5289.3  310.36  5328.5  311.58    5373  312.49
#Mann= 5 ,-1 , 0
  4586.1      .1       0  4657.4     .05       0  4960.3      .1       0
  5009.4     .07       0  5015.4      .1       0
Bank Sta=5009.4,5015.4
XS Rating Curve= 0 ,0
Exp/Cntr=0.3,0.1

Type RM Length L Ch R = 1 ,6226    ,264,264,264
BEGIN DESCRIPTION:
Mapping XS 06519e95
END DESCRIPTION:
XS GIS Cut Line= 3
      2107915.73     13395359.56      2107993.84     13394888.36
      2107957.12     13394519.21
#Sta/Elev= 30
  4445.7  322.52  4521.3  319.92  4561.8  317.65  4651.6  313.48  4663.2  312.38
  4703.7  310.21  4734.1  308.01  4754.4  307.84  4778.6  306.97    4795  305.89
  4839.6  304.52  4865.9  303.29  4886.2  303.17  4916.6  304.08  4956.9  303.35
    4987  303.54  5007.1  302.73  5014.2  301.75  5014.7  300.95  5019.7  300.95
  5020.2  301.75  5037.2  302.44  5047.3   303.7  5057.3  304.45  5067.8  304.42
  5087.5  305.29  5117.6  307.96  5127.7   308.4  5248.3  312.14  5294.3  313.19
#Mann= 3 ,-1 , 0
  4445.7      .1       0  5014.2     .07       0  5020.2      .1       0
Bank Sta=5014.2,5020.2
XS Rating Curve= 0 ,0
Exp/Cntr=0.3,0.1

Type RM Length L Ch R = 1 ,5962    ,226,226,226
BEGIN DESCRIPTION:
Mapping XS a4660ab6
END DESCRIPTION:
XS GIS Cut Line= 3
      2108051.79     13395425.65      2108209.32     13394959.03
      2108247.08     13394665.84
#Sta/Elev= 30
  4482.4  322.21    4535   320.6  4597.9  317.98  4633.1  316.07  4641.4  315.44
  4683.6  313.52  4715.3  311.37  4736.4  309.58  4778.6  306.78  4791.9  305.57
  4810.3  304.61  4823.4  303.51  4894.7  302.18  4926.4  302.45    4958  302.06
  4968.6   301.7  4974.4  301.22  4977.5  301.22    4989  300.09  4996.1  299.98
  4996.6  299.18  5001.6  299.18  5002.1  299.98  5029.4  302.08  5069.7  302.37
  5079.8  302.75    5110  305.82  5120.1  306.29  5150.4  307.21  5270.5  309.78
#Mann= 3 ,-1 , 0
  4482.4      .1       0  4996.1     .07       0  5002.1      .1       0
Bank Sta=4996.1,5002.1
XS Rating Curve= 0 ,0
Exp/Cntr=0.3,0.1

Type RM Length L Ch R = 1 ,5736    ,208,208,208
BEGIN DESCRIPTION:
Mapping XS f5e435af
END DESCRIPTION:
XS GIS Cut Line= 3
      2108198.23     13395472.93      2108387.55     13395086.87
      2108450.23     13394802.69
#Sta/Elev= 30
  4545.7  319.54  4587.9  317.41  4599.9  316.49  4661.8  313.81  4684.3  312.33
  4689.9  311.66  4729.3  309.58  4810.7  303.73  4847.3  302.02  4864.3   300.7
  4922.1  299.86  4937.3  299.85  4959.8  300.44  4973.9  298.66  4979.2  298.66
  4981.9  297.95  4982.4  297.15  4987.4  297.15  4987.9  297.95  4998.1  298.28
  5028.6  300.25  5033.7  300.06    5039  300.47  5082.5  301.11  5110.7  301.97
  5151.7  304.06  5169.9  304.81    5175  304.67  5218.7  306.75  5266.7  307.31
#Mann= 3 ,-1 , 0
  4545.7      .1       0  4981.9     .07       0  4987.9      .1       0
Bank Sta=4981.9,4987.9
XS Rating Curve= 0 ,0
Exp/Cntr=0.3,0.1

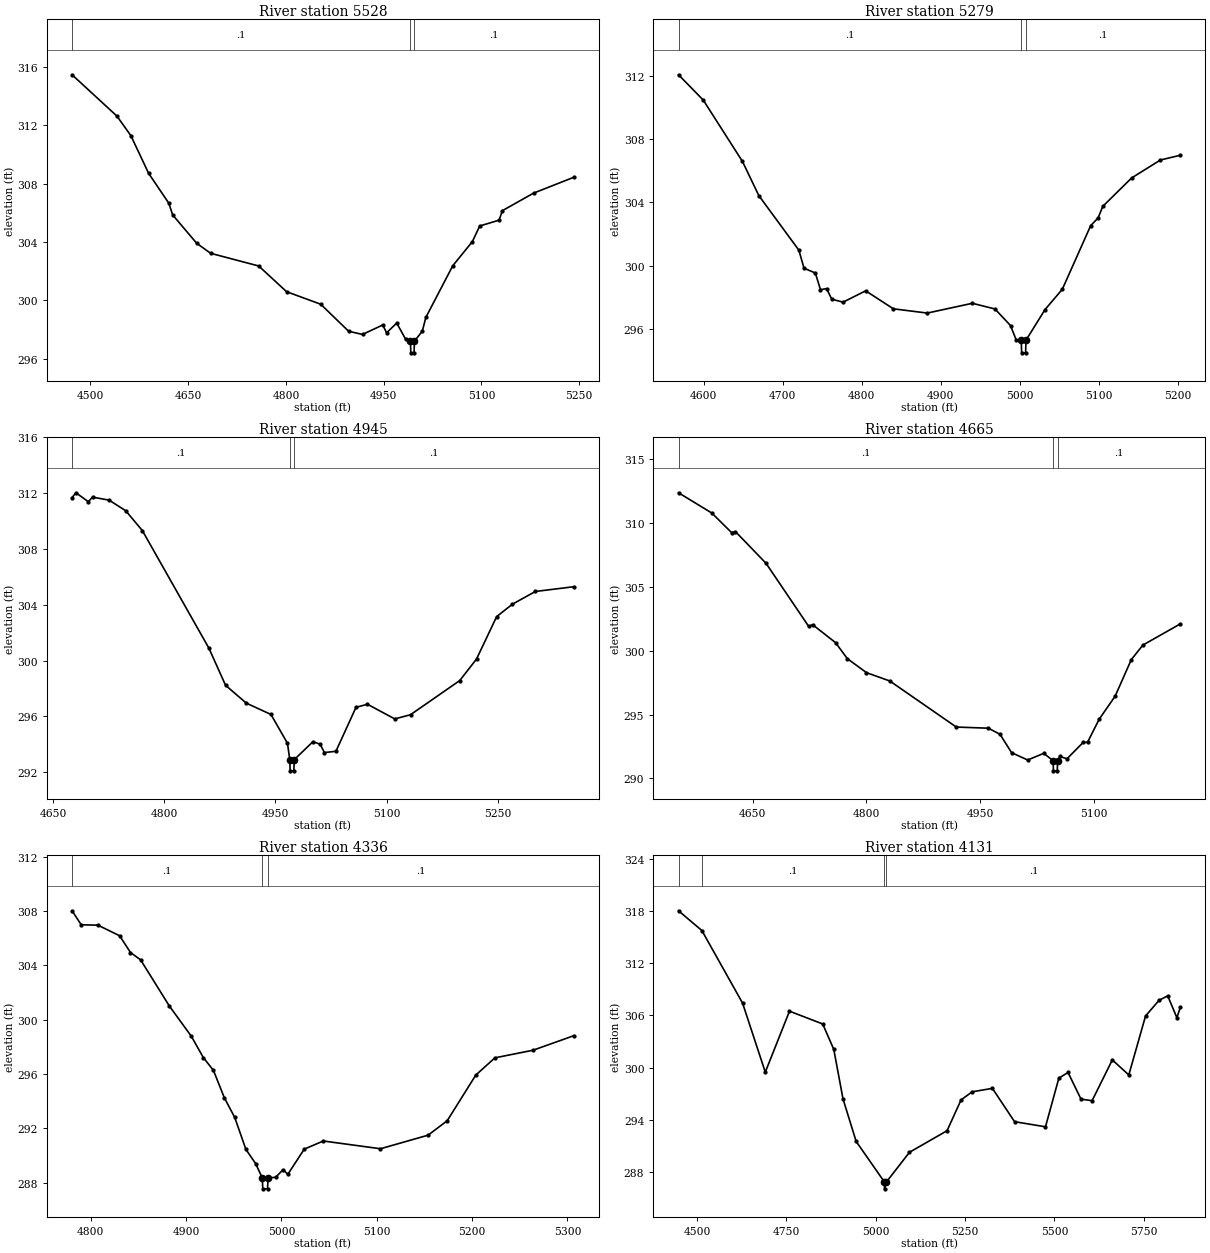
Type RM Length L Ch R = 1 ,5528    ,249,249,249
BEGIN DESCRIPTION:
Mapping XS 53955481
END DESCRIPTION:
XS GIS Cut Line= 3
      2108321.64     13395564.17      2108582.13     13395131.72
      2108647.24     13394874.99
#Sta/Elev= 30
    4472  315.45  4540.8  312.62  4562.2  311.28  4589.4   308.7  4620.4  306.65
  4626.3  305.85  4663.1  303.91  4684.5  303.22  4758.3  302.35    4801  300.59
  4853.4  299.73  4896.2  297.88  4917.5  297.66  4948.6  298.31  4954.4  297.77
    4970  298.44  4983.8  297.32  4991.1   297.2  4991.6   296.4  4996.6   296.4
  4997.1   297.2  5009.2  297.88  5014.7  298.83    5056  302.37    5086  304.02
  5097.3  305.09    5127  305.49  5132.1  306.14  5179.8  307.34  5241.7  308.43
#Mann= 3 ,-1 , 0
    4472      .1       0  4991.1     .07       0  4997.1      .1       0
Bank Sta=4991.1,4997.1
XS Rating Curve= 0 ,0
Exp/Cntr=0.3,0.1

Type RM Length L Ch R = 1 ,5279    ,334,334,334
BEGIN DESCRIPTION:
Mapping XS ae5f95d3
END DESCRIPTION:
XS GIS Cut Line= 3
      2108447.46     13395611.38        2108719.     13395290.55
      2108833.18     13395108.39
#Sta/Elev= 30
  4568.1  312.09  4599.5  310.48    4649   306.6  4669.8  304.43  4720.4  300.98
    4727  299.83  4741.3  299.53  4747.8  298.47  4755.5  298.54  4762.1  297.87
  4776.4  297.68    4805   298.4  4840.1  297.26    4883  296.99  4940.1  297.61
  4968.7  297.25  4988.4   296.2  4995.6  295.29    5002  295.27  5002.5  294.47
  5007.5  294.47    5008  295.27  5032.1  297.21    5054   298.5  5089.9  302.53
  5099.3  303.02  5105.2  303.75  5141.7  305.55  5178.2  306.69  5203.4  306.99
#Mann= 3 ,-1 , 0
  4568.1      .1       0    5002     .07       0    5008      .1       0
Bank Sta=5002,5008
XS Rating Curve= 0 ,0
Exp/Cntr=0.3,0.1

Type RM Length L Ch R = 1 ,4945    ,280,280,280
BEGIN DESCRIPTION:
Mapping XS f57bd3a0
END DESCRIPTION:
XS GIS Cut Line= 3
      2108424.27     13395691.74      2108711.15     13395550.07
      2109016.55     13395364.34
#Sta/Elev= 30
  4675.5  311.68  4680.7  312.02  4697.5  311.38  4703.1  311.71  4725.6  311.49
    4748  310.73  4770.4  309.31  4860.2  300.89  4882.7  298.23  4910.7  296.95
    4944  296.14  4966.3  294.07  4969.4   292.9  4969.9   292.1  4974.9   292.1
  4975.4   292.9  5000.7  294.19  5010.3  294.01  5016.2  293.41  5031.7   293.5
  5058.8  296.65  5074.3  296.87  5111.1  295.82  5132.4  296.12  5198.9  298.57
  5221.5  300.11  5248.7  303.15    5270  304.04    5301  304.95  5352.9  305.29
#Mann= 3 ,-1 , 0
  4675.5      .1       0  4969.4     .07       0  4975.4      .1       0
Bank Sta=4969.4,4975.4
XS Rating Curve= 0 ,0
Exp/Cntr=0.3,0.1

Type RM Length L Ch R = 1 ,4665    ,329,329,329
BEGIN DESCRIPTION:
Mapping XS c1f95c33
END DESCRIPTION:
XS GIS Cut Line= 3
      2108441.89     13395883.88      2108797.23     13395812.54
      2109051.06     13395653.25
#Sta/Elev= 30
  4552.1  312.38  4596.1  310.79  4622.1  309.26  4627.2  309.34  4667.5  306.86
  4723.9  301.91    4729  302.05  4759.3  300.64  4774.8  299.39  4800.1  298.29
  4830.8  297.64  4918.6  294.03    4961  293.94  4976.3  293.46  4991.6  292.02
  5012.8  291.45    5034  291.97  5046.3   291.4  5046.8   290.6  5051.8   290.6
  5052.3   291.4  5055.2  291.73  5064.6  291.54  5085.9  292.82  5091.8  292.84
  5107.1  294.64  5128.3  296.46  5149.5  299.31  5164.8  300.45  5214.2  302.11
#Mann= 3 ,-1 , 0
  4552.1      .1       0  5046.3     .07       0  5052.3      .1       0
Bank Sta=5046.3,5052.3
XS Rating Curve= 0 ,0
Exp/Cntr=0.3,0.1

Type RM Length L Ch R = 1 ,4336    ,205,205,205
BEGIN DESCRIPTION:
Mapping XS 6b3883ec
END DESCRIPTION:
XS GIS Cut Line= 3
      2108519.49     13395956.85      2108704.74     13396040.59
      2109027.81     13396031.42
#Sta/Elev= 30
  4780.3  308.01  4789.9  306.98  4807.5  306.95  4830.2  306.17  4841.6  304.94
  4852.2   304.4  4882.3  301.01  4905.5  298.77    4918  297.21  4928.6  296.27
    4940  294.26    4951   292.8  4962.7  290.45  4972.9  289.41  4979.9  288.35
  4980.4  287.55  4985.4  287.55  4985.9  288.35  4993.9   288.4  5001.7  288.96
  5006.7  288.62  5023.9  290.47  5043.9  291.07  5103.9   290.5  5153.9   291.5
  5173.9  292.56  5203.9  295.92    5224  297.19    5264  297.75  5306.8  298.82
#Mann= 3 ,-1 , 0
  4780.3      .1       0  4979.9     .07       0  4985.9      .1       0
Bank Sta=4979.9,4985.9
XS Rating Curve= 0 ,0
Exp/Cntr=0.3,0.1

Type RM Length L Ch R = 1 ,4131    ,371,371,371
BEGIN DESCRIPTION:
Mapping XS 2e39a9b9
END DESCRIPTION:
XS GIS Cut Line= 2
      2108245.89     13396392.42      2109571.12     13395927.54
#Sta/Elev= 30
  4448.1  318.02  4513.4  315.75  4627.3  307.41  4690.9  299.47  4758.6  306.48
  4851.6  305.01  4882.6  302.09  4908.4   296.4  4945.2  291.51  5024.1  286.86
  5024.6  286.06  5030.1  286.86  5094.4  290.26  5199.6  292.74  5238.8  296.28
  5269.8  297.21  5326.5  297.61  5388.5  293.78  5475.1  293.19  5512.5  298.78
  5538.2  299.44  5574.5  296.37  5605.5  296.19  5662.2  300.88  5708.3  299.15
  5755.2  305.93    5793  307.73  5817.2  308.24  5842.9  305.73  5852.5  306.92
#Mann= 4 ,-1 , 0
  4448.1     .05       0  4513.4      .1       0  5024.1     .07       0
  5030.1      .1       0
Bank Sta=5024.1,5030.1
XS Rating Curve= 0 ,0
Exp/Cntr=0.3,0.1

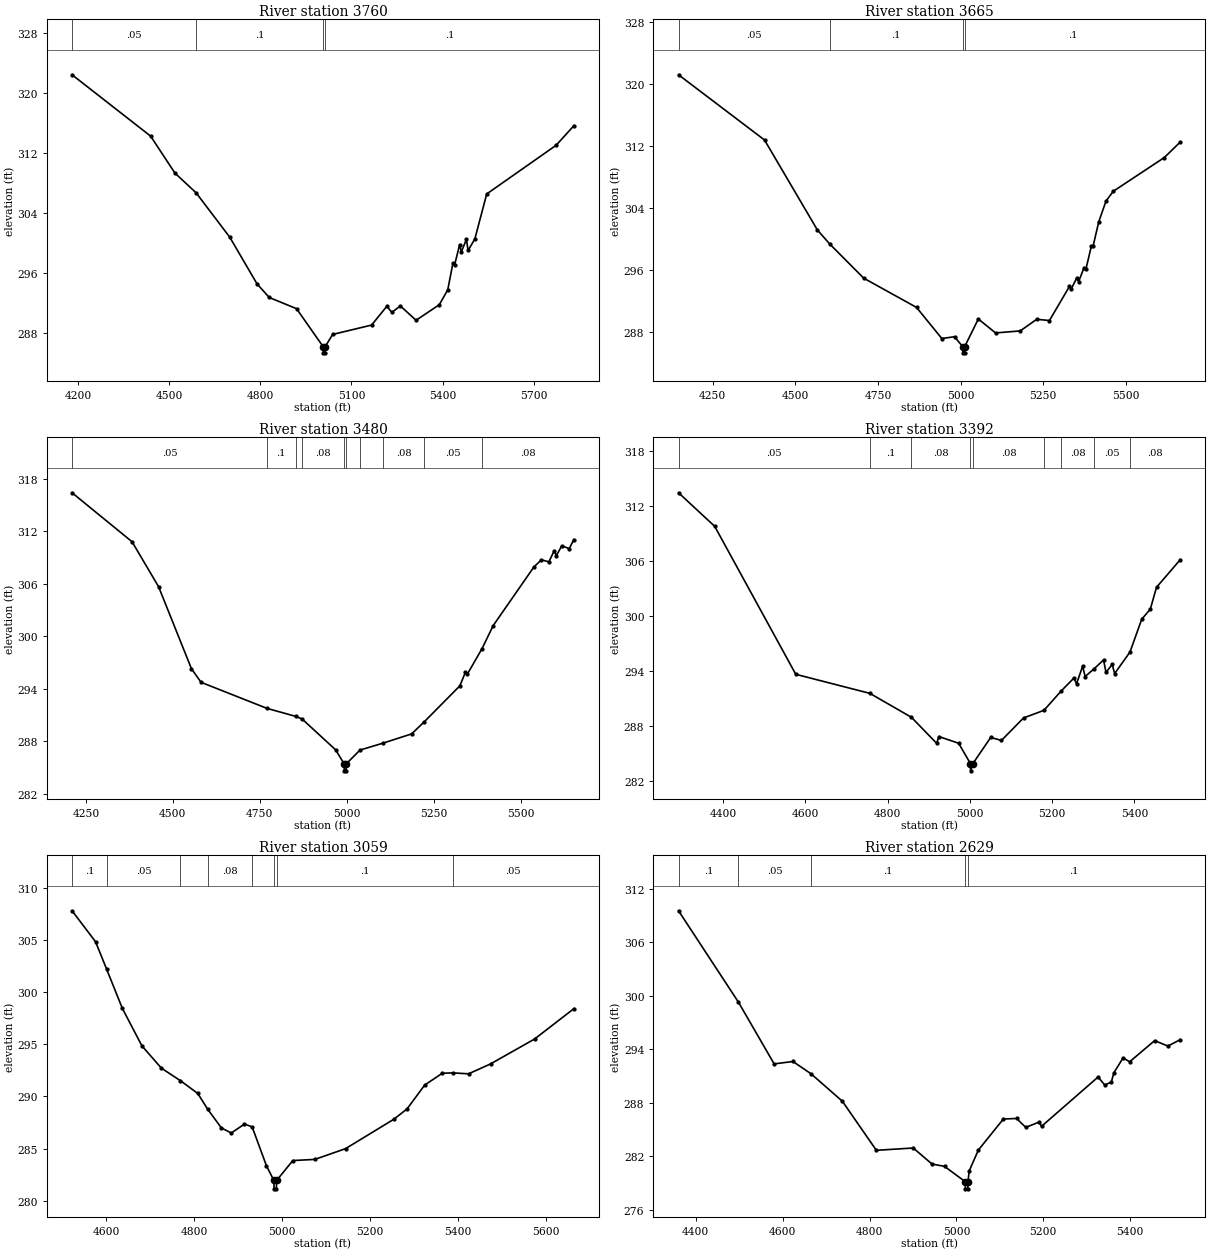
Type RM Length L Ch R = 1 ,3760    ,95,95,95
BEGIN DESCRIPTION:
UNT 001 in La Jarita Watershed 9.0
END DESCRIPTION:
XS GIS Cut Line= 3
      2108126.59     13396551.77      2108945.76     13396506.97
      2109689.29     13396132.29
#Sta/Elev= 30
  4179.6  322.48  4438.4  314.28  4518.5  309.34  4588.1  306.71  4698.8  300.79
  4788.9  294.54    4829  292.72  4919.1  291.22  5007.1  286.12  5007.6  285.32
  5012.6  285.32  5013.1  286.12    5038  287.78  5166.3  289.03  5216.5  291.54
  5233.2  290.73  5261.1  291.59  5312.7  289.67  5389.4  291.75  5417.3  293.76
    5434  297.27  5439.6  297.03  5456.3  299.78  5461.9   298.8  5478.6  300.49
  5484.2     299  5506.5  300.55  5545.5  306.55  5774.2  313.06  5832.6  315.67
#Mann= 4 ,-1 , 0
  4179.6     .05       0  4588.1      .1       0  5007.1     .07       0
  5013.1      .1       0
Bank Sta=5007.1,5013.1
XS Rating Curve= 0 ,0
Exp/Cntr=0.3,0.1

Type RM Length L Ch R = 1 ,3665    ,185,185,185
BEGIN DESCRIPTION:
Mapping XS 659c2ff8
END DESCRIPTION:
XS GIS Cut Line= 3
      2108154.79     13396597.34      2108946.88     13396612.53
      2109590.73     13396276.52
#Sta/Elev= 30
  4146.3  321.23  4406.6  312.81  4566.6  301.19  4603.6   299.4  4706.6  294.98
  4866.6   291.2    4943  287.19  4981.5  287.42  5006.3  286.14  5006.8  285.34
  5011.8  285.34  5012.3  286.14  5053.5  289.71  5105.6  287.91  5180.4  288.17
  5230.2  289.67  5268.7  289.51  5329.3  293.91    5335  293.61  5351.4  295.01
    5357  294.53  5373.5  296.34  5379.1  296.14  5395.6  299.13  5401.2  299.17
  5417.7  302.22  5439.8  304.92  5461.8  306.19  5616.4  310.55  5664.8  312.56
#Mann= 4 ,-1 , 0
  4146.3     .05       0  4603.6      .1       0  5006.3     .07       0
  5012.3      .1       0
Bank Sta=5006.3,5012.3
XS Rating Curve= 0 ,0
Exp/Cntr=0.3,0.1

Type RM Length L Ch R = 1 ,3480    ,88,88,88
BEGIN DESCRIPTION:
Mapping XS 7f21c393
END DESCRIPTION:
XS GIS Cut Line= 3
      2108282.81     13396697.17      2108881.77     13396851.25
      2109590.73     13396432.81
#Sta/Elev= 30
  4210.5  316.38  4382.8  310.79  4459.1  305.65  4553.5  296.28  4581.2  294.73
  4770.2  291.76  4853.1  290.84  4871.2  290.55  4967.7  287.02  4992.2  285.42
  4992.7  284.62  4997.9  284.62  4998.4  285.42  5037.6  286.99  5103.6  287.78
  5186.2  288.84  5222.1  290.21  5324.7  294.33  5340.4  295.86  5346.2  295.67
  5388.4  298.58  5420.4  301.21  5537.5  307.91  5558.9  308.72  5580.4  308.49
    5596  309.78  5601.8  309.18  5617.4  310.32  5638.9     310  5652.2  311.03
#Mann= 10 ,-1 , 0
  4210.5     .05       0  4770.2      .1       0  4853.1     .05       0
  4871.2     .08       0  4992.2     .07       0  4998.4     .08       0
  5037.6     .05       0  5103.6     .08       0  5222.1     .05       0
  5388.4     .08       0
Bank Sta=4992.2,4998.4
XS Rating Curve= 0 ,0
Exp/Cntr=0.3,0.1

Type RM Length L Ch R = 1 ,3392    ,333,333,333
BEGIN DESCRIPTION:
UNT 001 in La Jarita Watershed 8.0
END DESCRIPTION:
XS GIS Cut Line= 4
      2108362.63      13396792.7      2108889.34      13396900.1
      2109167.99     13396806.35      2109488.28     13396587.61
#Sta/Elev= 30
  4292.1  313.47    4380  309.81    4577  293.67  4757.1  291.59  4858.1  288.98
  4919.4  286.14  4924.7  286.88  4972.8  286.15  5001.3  283.94  5001.8  283.14
  5007.5  283.94  5050.7  286.78  5076.9  286.46  5130.5  288.91  5180.1  289.74
  5221.8  291.84  5253.1  293.27  5259.2  292.63  5274.1  294.55  5280.1  293.43
  5301.7  294.26  5324.9  295.23  5330.9  293.88  5345.9  294.74  5351.9  293.75
  5389.2   296.1  5417.7  299.68  5438.6  300.78  5453.6  303.16  5511.5  306.18
#Mann= 9 ,-1 , 0
  4292.1     .05       0  4757.1      .1       0  4858.1     .08       0
  5001.3     .07       0  5007.5     .08       0  5180.1     .05       0
  5221.8     .08       0  5301.7     .05       0  5389.2     .08       0
Bank Sta=5001.3,5007.5
XS Rating Curve= 0 ,0
Exp/Cntr=0.3,0.1

Type RM Length L Ch R = 1 ,3059    ,430,430,430
BEGIN DESCRIPTION:
Mapping XS c5c91627
END DESCRIPTION:
XS GIS Cut Line= 3
      2108440.33     13396916.71       2108745.9     13397072.97
      2109544.49     13397076.44
#Sta/Elev= 30
  4521.9  307.78  4575.4  304.81  4600.5  302.19  4636.4  298.42  4680.8  294.84
  4725.2   292.7  4768.2  291.51  4807.9  290.28  4830.1  288.79  4861.8  286.97
  4884.2  286.49  4914.2  287.35  4931.7  287.07  4964.2  283.35  4981.1  281.94
  4981.6  281.14  4986.8  281.14  4987.3  281.94  5024.2  283.85  5074.2  283.96
  5144.2  284.99  5254.2  287.81  5284.2   288.8  5324.2  291.08  5364.2  292.21
  5387.7  292.25  5424.2  292.16  5474.2  293.11  5574.2  295.49  5663.7   298.4
#Mann= 8 ,-1 , 0
  4521.9      .1       0  4600.5     .05       0  4768.2      .1       0
  4830.1     .08       0  4931.7      .1       0  4981.1     .07       0
  4987.3      .1       0  5387.7     .05       0
Bank Sta=4981.1,4987.3
XS Rating Curve= 0 ,0
Exp/Cntr=0.3,0.1

Type RM Length L Ch R = 1 ,2629    ,186,186,186
BEGIN DESCRIPTION:
UNT 001 in La Jarita Watershed 6.0
END DESCRIPTION:
XS GIS Cut Line= 3
      2108374.98     13396974.98        2108875.       13397375.
      2109308.36     13397652.81
#Sta/Elev= 30
  4360.4  309.51  4498.2  299.27  4580.5  292.34  4623.8  292.61  4665.4  291.23
  4737.4  288.16  4815.8  282.65  4900.7  282.91  4943.9  281.11  4972.7  280.85
  5020.4  279.13  5020.9  278.33  5026.2  278.33  5026.7  279.13  5029.5  280.34
  5050.6  282.68  5108.1  286.16  5138.5  286.22  5159.7  285.22  5190.1  285.81
    5196  285.34  5326.2  290.87  5341.4  289.98  5356.6  290.29  5362.5  291.34
  5383.7  293.01  5398.9  292.58  5456.4  294.95  5486.8  294.34  5515.5  295.06
#Mann= 5 ,-1 , 0
  4360.4      .1       0  4498.2     .05       0  4665.4      .1       0
  5020.4     .07       0  5026.7      .1       0
Bank Sta=5020.4,5026.7
XS Rating Curve= 0 ,0
Exp/Cntr=0.3,0.1

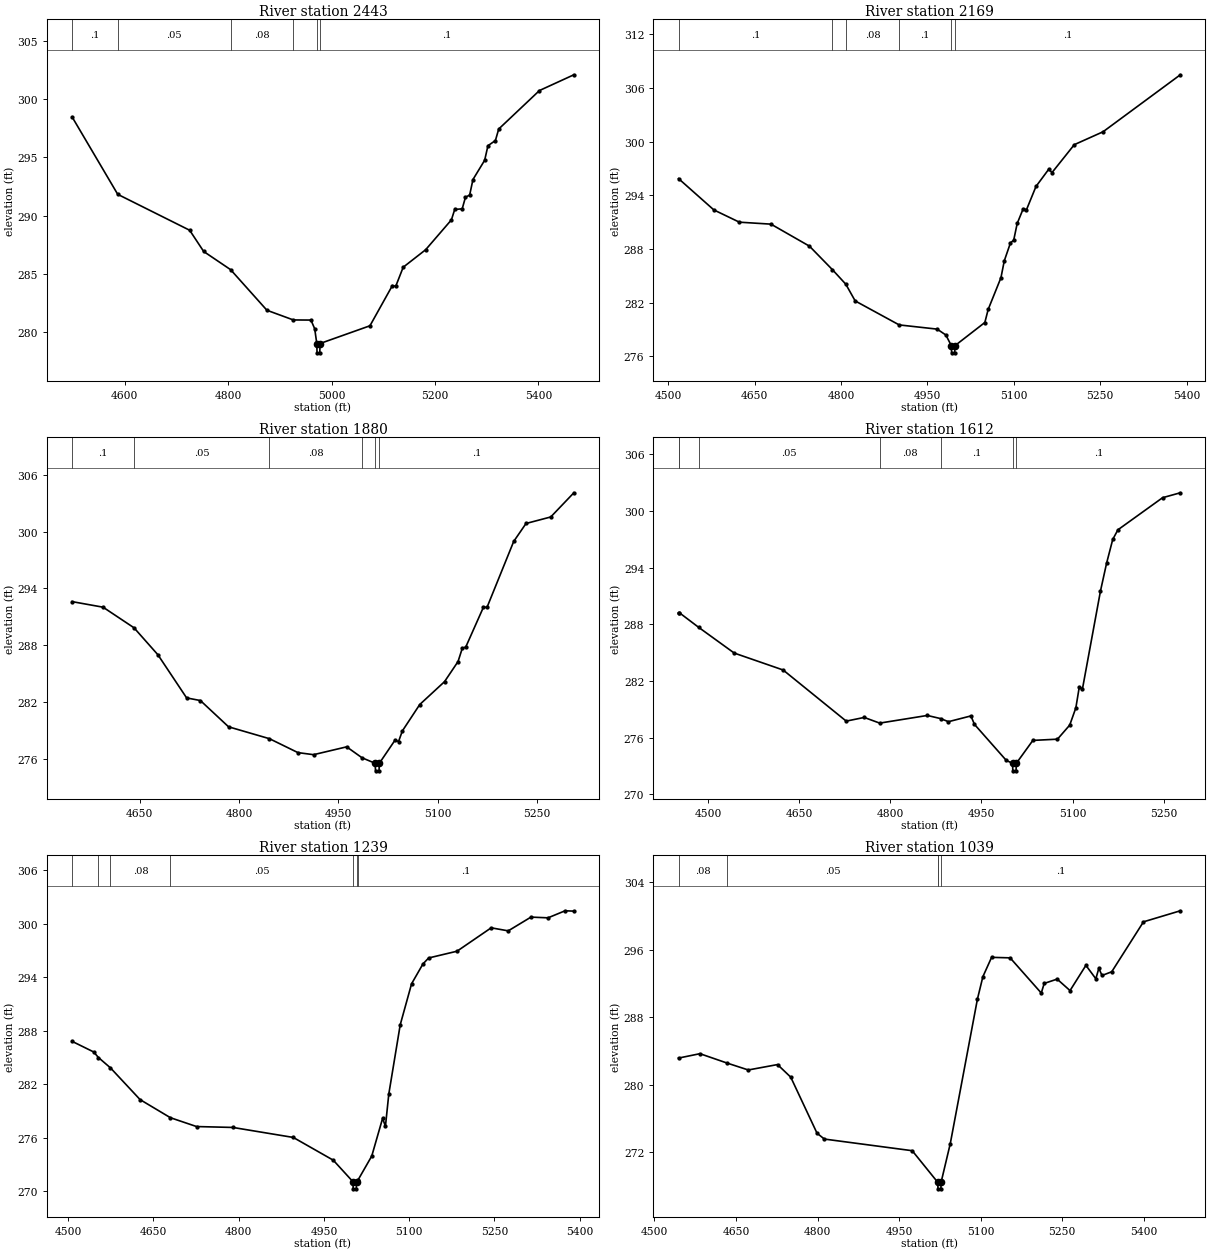
Type RM Length L Ch R = 1 ,2443    ,274,274,274
BEGIN DESCRIPTION:
Mapping XS 59da8841
END DESCRIPTION:
XS GIS Cut Line= 2
      2108363.93     13397197.95      2109131.33     13397791.73
#Sta/Elev= 30
  4498.2  298.47  4586.5  291.83  4725.6  288.75  4752.7  286.93  4804.8  285.37
    4875  281.89  4926.1  281.06  4960.1  281.05  4967.4   280.3  4971.4  279.04
  4971.9  278.24  4977.2  278.24  4977.7  279.04  5074.2  280.56  5117.6  284.01
    5124  283.94  5138.5  285.58  5181.9  287.08  5231.7  289.64  5238.1  290.53
  5252.6  290.59  5258.9  291.58    5267  291.77  5273.4   293.1    5296  294.75
  5302.4     296  5316.8  296.44  5323.2  297.43    5402  300.73  5468.5  302.08
#Mann= 6 ,-1 , 0
  4498.2      .1       0  4586.5     .05       0  4804.8     .08       0
  4926.1      .1       0  4971.4     .07       0  4977.7      .1       0
Bank Sta=4971.4,4977.7
XS Rating Curve= 0 ,0
Exp/Cntr=0.3,0.1

Type RM Length L Ch R = 1 ,2169    ,289,289,289
BEGIN DESCRIPTION:
Mapping XS 9a850dc4
END DESCRIPTION:
XS GIS Cut Line= 2
      2108242.39      13397503.5      2109016.69     13397902.81
#Sta/Elev= 30
  4517.9  295.87  4579.2  292.37  4623.5     291  4678.4  290.78  4745.2  288.32
  4785.1  285.69  4808.3  284.07  4824.6   282.2    4901  279.52  4966.9  279.05
  4982.1  278.39  4991.5   277.2    4992   276.4  4997.3   276.4  4997.8   277.2
  5049.7  279.79  5055.5  281.25  5077.7   284.8  5083.4  286.67  5094.2  288.69
  5099.8  288.99  5105.9  290.86  5116.3   292.5    5122  292.39  5138.5  294.99
  5160.7  296.92  5166.3  296.54    5205  299.66  5254.9   301.1  5389.1  307.47
#Mann= 6 ,-1 , 0
  4517.9      .1       0  4785.1     .05       0  4808.3     .08       0
    4901      .1       0  4991.5     .07       0  4997.8      .1       0
Bank Sta=4991.5,4997.8
XS Rating Curve= 0 ,0
Exp/Cntr=0.3,0.1

Type RM Length L Ch R = 1 ,1880    ,268,268,268
BEGIN DESCRIPTION:
Mapping XS f05a8d97
END DESCRIPTION:
XS GIS Cut Line= 2
      2108110.47     13397809.08      2108831.39      13398041.3
#Sta/Elev= 30
  4547.9  292.61  4594.7  292.02  4641.4  289.84  4677.4  286.99  4720.8  282.42
  4741.6  282.14  4784.1  279.36  4845.9   278.1  4888.8  276.63  4912.4  276.41
  4962.4  277.24  4985.6  276.08  5005.4   275.5  5005.9   274.7  5011.2   274.7
  5011.7   275.5  5035.4  277.95  5040.7   277.8  5046.4  278.92  5072.7  281.72
  5110.1  284.14  5130.5  286.27  5136.9  287.67  5142.1   287.8  5168.9  292.03
  5174.2     292  5214.5  298.98  5233.1  300.88  5270.4  301.57  5305.3  304.13
#Mann= 6 ,-1 , 0
  4547.9      .1       0  4641.4     .05       0  4845.9     .08       0
  4985.6      .1       0  5005.4     .07       0  5011.7      .1       0
Bank Sta=5005.4,5011.7
XS Rating Curve= 0 ,0
Exp/Cntr=0.3,0.1

Type RM Length L Ch R = 1 ,1612    ,373,373,373
BEGIN DESCRIPTION:
UNT 001 in La Jarita Watershed 3.0
END DESCRIPTION:
XS GIS Cut Line= 3
      2107965.89     13398060.51      2108493.68     13398182.04
      2108775.02       13398225.
#Sta/Elev= 30
  4451.2  289.22  4452.7  289.22  4484.6  287.67  4542.9  284.96  4623.4  283.17
  4727.3  277.76  4756.9  278.15  4782.4  277.55  4860.8  278.36  4882.6  278.03
  4895.6   277.7  4932.6  278.31  4938.4  277.42  4990.9   273.6  5001.1   273.3
  5001.6   272.5  5006.9   272.5  5007.4   273.3  5034.6  275.72  5075.1  275.85
  5095.3  277.34  5105.4  279.17  5111.1   281.4  5116.2  281.15  5145.9  291.52
    5156  294.47  5166.1  296.98  5174.6     298  5248.2   301.4  5277.4  301.92
#Mann= 7 ,-1 , 0
  4451.2     .05       0  4452.7      .1       0  4484.6     .05       0
  4782.4     .08       0  4882.6      .1       0  5001.1     .07       0
  5007.4      .1       0
Bank Sta=5001.1,5007.4
XS Rating Curve= 0 ,0
Exp/Cntr=0.3,0.1

Type RM Length L Ch R = 1 ,1239    ,200,200,200
BEGIN DESCRIPTION:
UNT 001 in La Jarita Watershed 2.0
END DESCRIPTION:
XS GIS Cut Line= 3
      2108025.03     13398275.01      2108447.29     13398456.65
      2108870.43     13398472.26
#Sta/Elev= 30
  4506.8  286.82  4544.8  285.63  4553.3     285  4574.3  283.85  4626.5  280.29
  4679.9  278.26  4725.9  277.27  4789.8  277.17  4896.1  276.05  4966.5   273.5
  5001.1  271.09  5001.6  270.29  5006.9  270.29  5007.4  271.09  5010.4  271.32
  5034.2  273.96  5053.3  278.19  5058.3   277.3  5064.2  280.91  5084.3  288.67
  5104.3  293.27  5124.3  295.49  5134.3  296.16  5184.3  296.92  5244.4  299.54
  5274.4   299.2  5314.4  300.74  5344.4  300.66  5374.5  301.45  5389.9  301.41
#Mann= 7 ,-1 , 0
  4506.8      .1       0  4553.3     .05       0  4574.3     .08       0
  4679.9     .05       0  5001.1    .035       0  5007.4     .05       0
  5010.4      .1       0
Bank Sta=5001.1,5007.4
XS Rating Curve= 0 ,0
Exp/Cntr=0.3,0.1

Type RM Length L Ch R = 1 ,1039    ,174,174,174
BEGIN DESCRIPTION:
Mapping XS 6501ee7b
END DESCRIPTION:
XS GIS Cut Line= 4
      2107995.89     13398524.35      2108264.99       13398632.
      2108638.26     13398642.41      2108877.82     13398541.73
#Sta/Elev= 30
  4544.3  283.18  4583.7   283.7    4634  282.58  4672.6  281.77  4726.4  282.41
  4750.7  280.92  4799.1  274.27  4812.6  273.58  4974.2   272.2  5020.7  268.49
  5021.1  268.48  5021.6  267.68  5026.9  267.68  5027.4  268.48  5044.2  273.04
  5094.2  290.19  5104.2  292.83  5120.2  295.12  5154.3  295.06  5211.6  290.89
    5217  292.03  5240.8  292.54  5264.5  291.18  5293.7  294.17    5312  292.58
  5317.5  293.83  5323.3  292.97  5341.2  293.41  5399.6  299.33  5467.4  300.64
#Mann= 5 ,-1 , 0
  4544.3     .08       0    4634     .05       0  5020.7      .1       0
  5021.1    .035       0  5027.4      .1       0
Bank Sta=5021.1,5027.4
XS Rating Curve= 0 ,0
Exp/Cntr=0.3,0.1