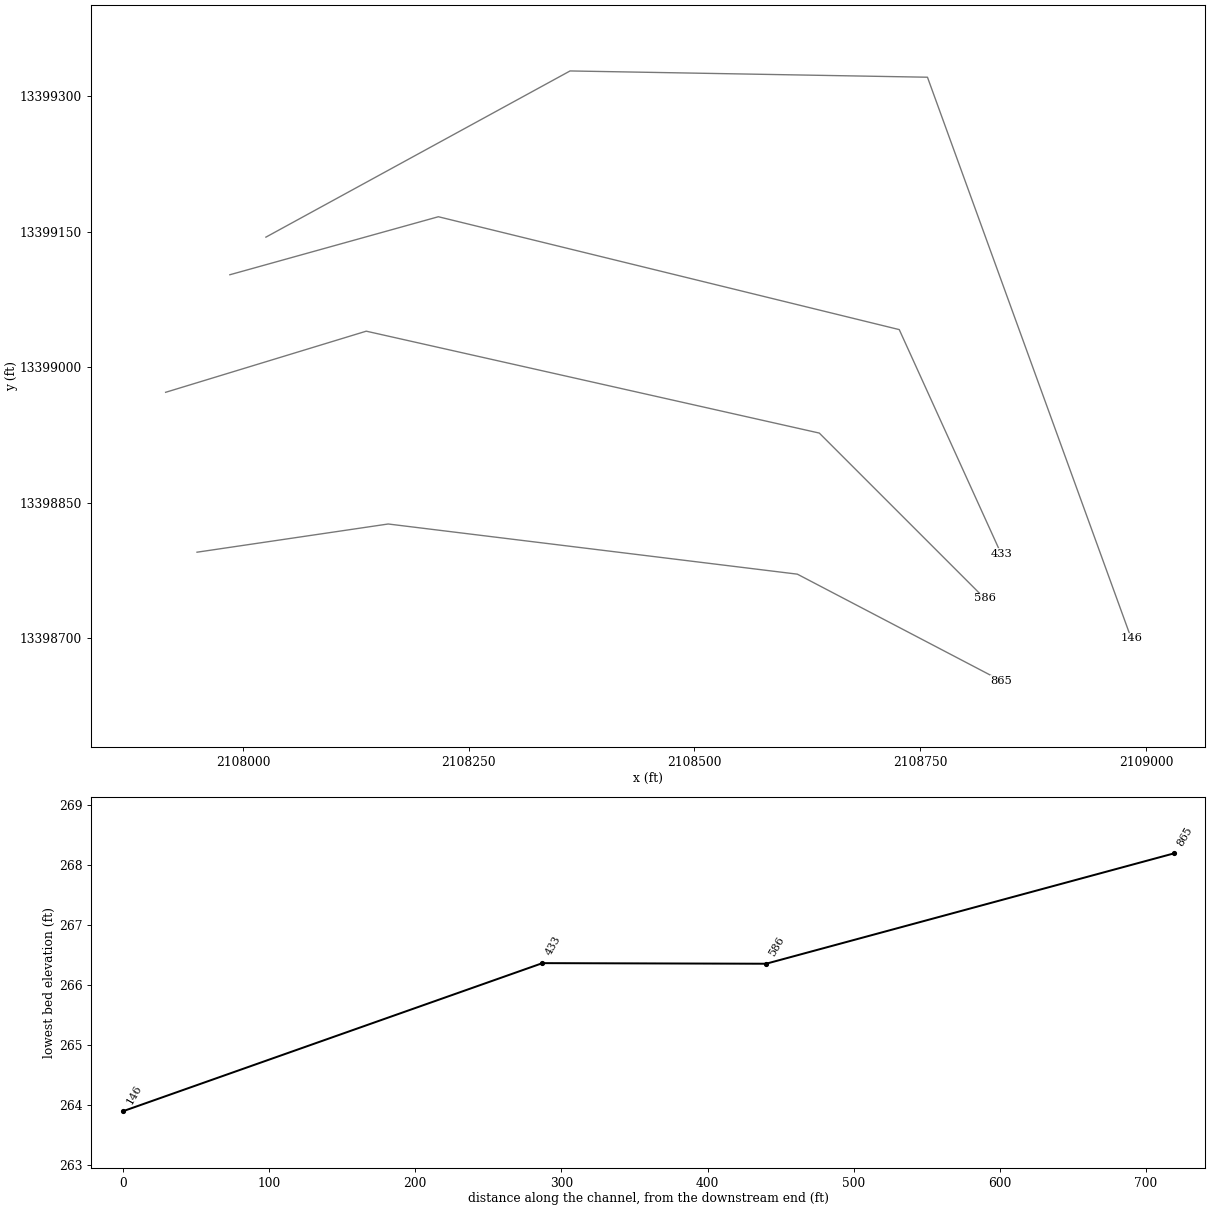
HEC-RAS study UNT 001 in La Jarita Watershed.prj: UNT 001 in La Jarita Watershed Base Level Engineering

--- UNT 001 in La Jarita Watershed.g01 (geometry) --- (continued)

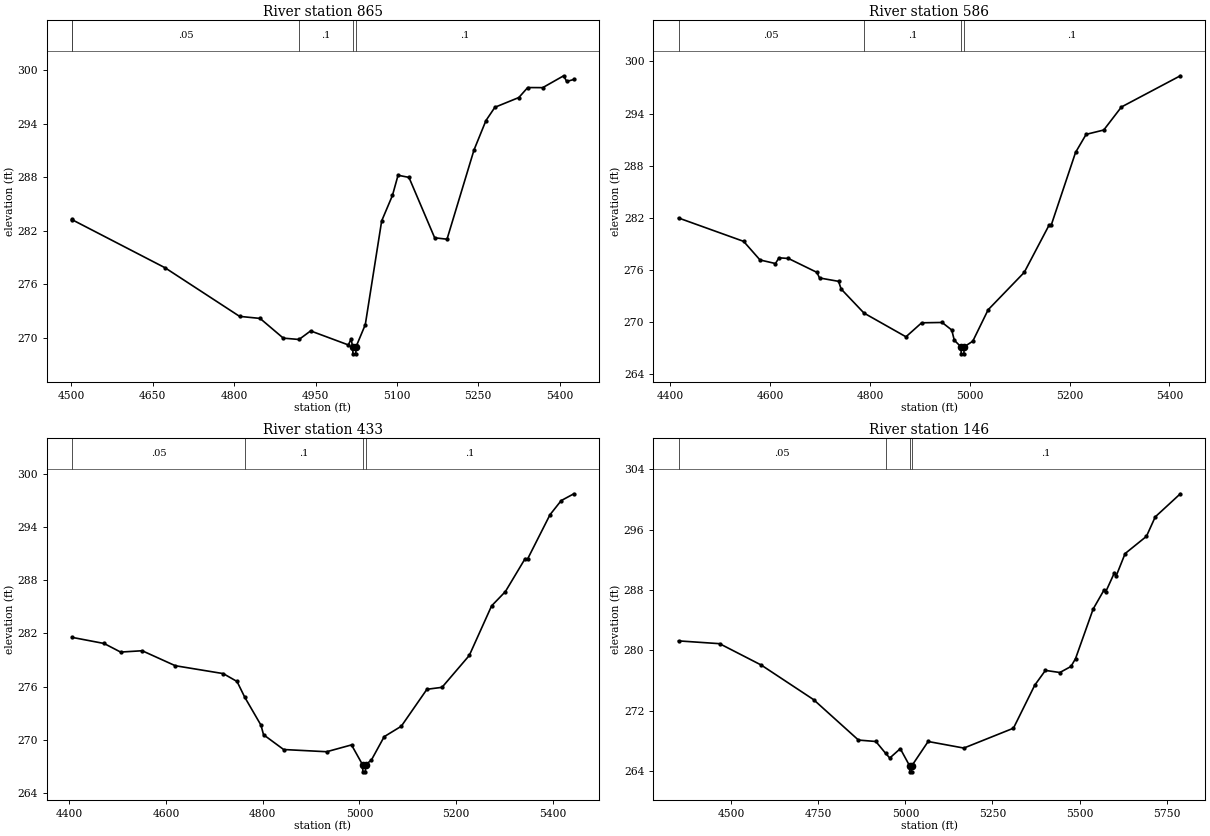
Type RM Length L Ch R = 1 ,865     ,279,279,279
BEGIN DESCRIPTION:
Mapping XS ff977518
END DESCRIPTION:
XS GIS Cut Line= 4
      2107949.07      13398795.2      2108160.83     13398826.44
      2108613.95     13398770.88      2108839.67     13398652.82
#Sta/Elev= 30
  4501.1  283.26  4501.7  283.22  4672.5  277.85    4810   272.4  4847.8  272.17
  4890.6  269.96  4919.6  269.81    4941  270.77  5010.5   269.2  5015.6  269.85
  5018.5     269    5019   268.2  5024.3   268.2  5024.8     269  5041.8  271.47
    5072   283.1  5091.9  285.96  5102.2  288.22  5122.3  287.98  5169.7  281.21
  5192.5  281.05  5242.3  291.06  5264.3  294.35  5280.8  295.84  5324.9  296.93
  5341.3  298.05    5369  298.04  5407.6  299.37  5413.2  298.73  5426.4  298.96
#Mann= 5 ,-1 , 0
  4501.1     .08       0  4501.7     .05       0  4919.6      .1       0
  5018.5     .07       0  5024.8      .1       0
Bank Sta=5018.5,5024.8
XS Rating Curve= 0 ,0
Exp/Cntr=0.3,0.1

Type RM Length L Ch R = 1 ,586     ,153,153,153
BEGIN DESCRIPTION:
Mapping XS 7e3ebf02
END DESCRIPTION:
XS GIS Cut Line= 4
      2107914.32     13398972.28      2108136.52     13399039.98
      2108638.26     13398927.13      2108821.15     13398744.25
#Sta/Elev= 30
  4416.5  281.99  4546.9   279.3  4579.7  277.16  4610.6  276.75  4617.8  277.41
  4636.7  277.33  4693.8  275.73  4698.9  275.09  4737.1   274.7  4742.2  273.82
    4788  271.05  4872.1  268.32  4903.5  269.93  4944.5  269.97  4963.8   269.1
  4968.9  267.93  4982.3  267.16  4982.8  266.36  4988.1  266.36  4988.6  267.16
    5006  267.82  5036.7  271.43    5109  275.73  5158.8  281.17  5163.1  281.17
  5211.8  289.53    5233  291.61  5268.3  292.11  5303.7  294.76  5421.7  298.35
#Mann= 4 ,-1 , 0
  4416.5     .05       0    4788      .1       0  4982.3     .07       0
  4988.6      .1       0
Bank Sta=4982.3,4988.6
XS Rating Curve= 0 ,0
Exp/Cntr=0.3,0.1

Type RM Length L Ch R = 1 ,433     ,287,287,287
BEGIN DESCRIPTION:
Mapping XS 72aa19e6
END DESCRIPTION:
XS GIS Cut Line= 4
      2107985.45     13399102.47      2108216.38     13399166.72
       2108726.8     13399041.72      2108839.64     13398793.47
#Sta/Elev= 30
  4405.7  281.55  4471.9  280.86  4506.1  279.89  4550.7  280.04  4619.2  278.35
  4718.4  277.46  4746.9  276.57  4762.8   274.8  4796.5  271.63  4801.7  270.56
  4843.3  268.89  4932.3  268.64  4983.7  269.41  5006.6  267.17  5007.1  266.37
  5012.4  266.37  5012.9  267.17  5024.9  267.71  5051.3  270.34  5086.7  271.52
  5139.7  275.69  5170.9  275.91  5227.3  279.51  5273.5  285.11    5302  286.72
  5342.7  290.43  5348.2  290.43  5394.3   295.4  5417.4  296.99  5443.6  297.76
#Mann= 4 ,-1 , 0
  4405.7     .05       0  4762.8      .1       0  5006.6     .07       0
  5012.9      .1       0
Bank Sta=5006.6,5012.9
XS Rating Curve= 0 ,0
Exp/Cntr=0.3,0.1

Type RM Length L Ch R = 1 ,146     ,0,0,0
BEGIN DESCRIPTION:
UNT 001 in La Jarita Watershed 1.0
END DESCRIPTION:
XS GIS Cut Line= 4
      2108025.39     13399144.13      2108362.22     13399328.18
      2108758.05     13399321.23      2108983.69     13398699.86
#Sta/Elev= 30
  4348.6  281.25  4466.5  280.88    4586  278.05  4736.3  273.47  4865.2  268.11
  4915.2  267.92  4943.6  266.33  4955.2  265.73  4985.3  266.97  5012.1   264.7
  5012.6   263.9  5017.9   263.9  5018.4   264.7  5065.3  267.92  5167.8  267.05
  5310.2  269.68  5371.4  275.38    5402  277.34  5443.5  277.06  5475.4  277.86
  5488.5   278.9  5539.1  285.47  5569.7  287.94    5575  287.73  5600.3  290.29
  5605.6   289.9  5630.9  292.82  5692.1   295.1  5717.4  297.68  5789.4  300.74
#Mann= 4 ,-1 , 0
  4348.6     .05       0  4943.6      .1       0  5012.1     .07       0
  5018.4      .1       0
Bank Sta=5012.1,5018.4
XS Rating Curve= 0 ,0
Exp/Cntr=0.3,0.1
LCMann Table=0

Chan Stop Cuts=-1
Use User Specified Reach Order=0
Composite Channel Slope=5