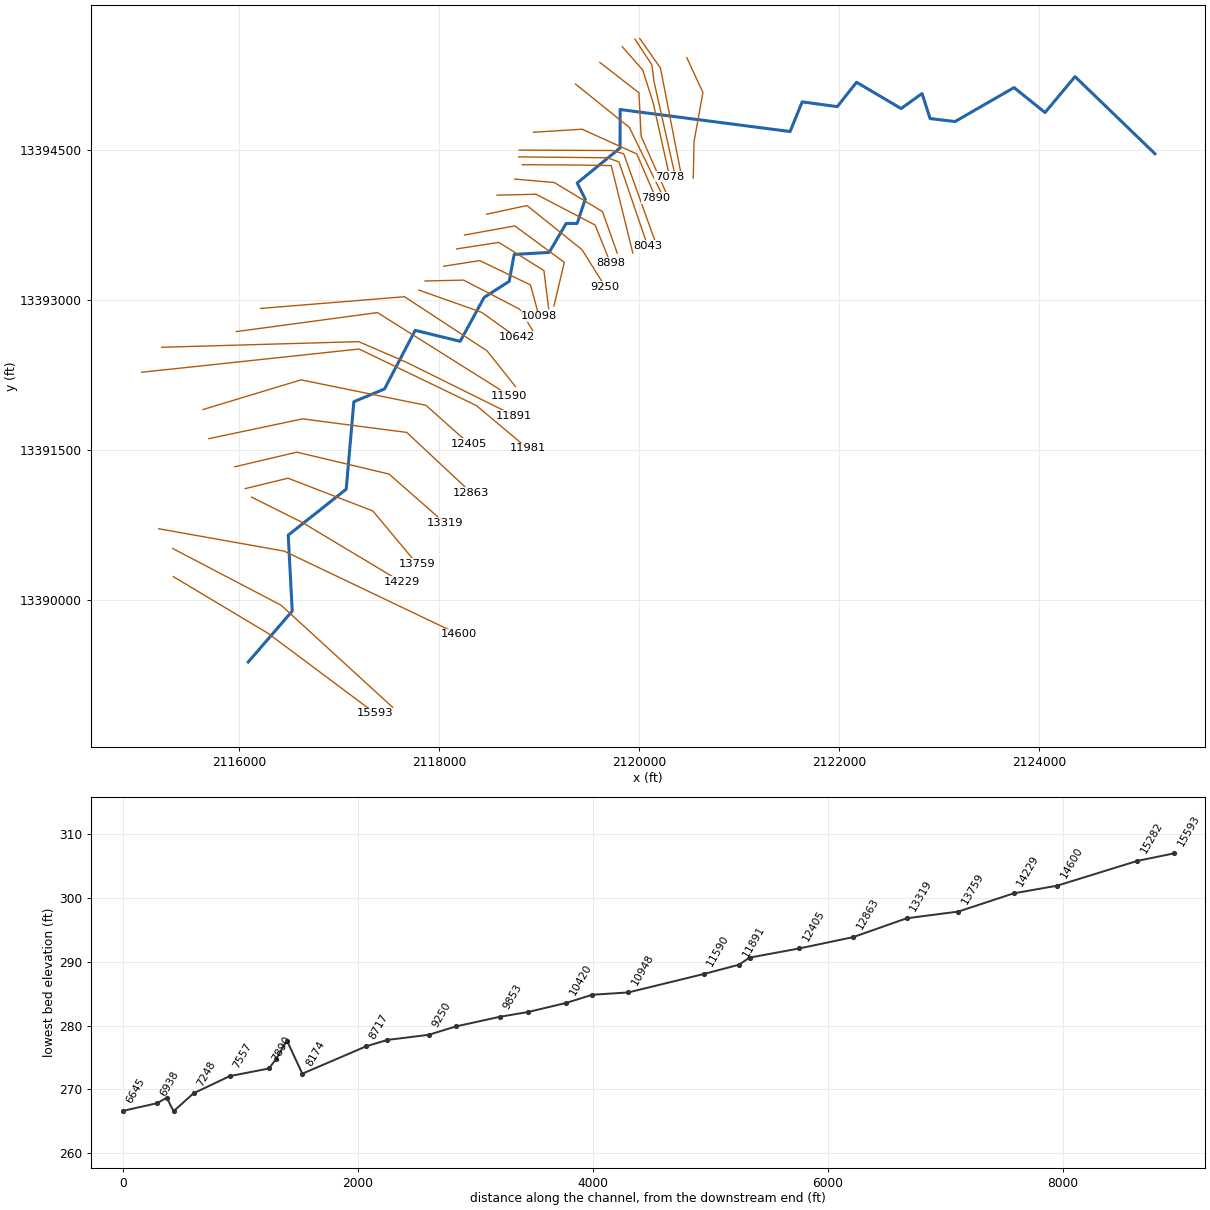
--- UNT 003 in La Jarita Watershed.prj (project) ---

Proj Title=UNT 003 in La Jarita Watershed Base Level Engineering
Current Plan=p01
Default Exp/Contr=0.3,0.1
English Units
Geom File=g01
Flow File=f01
Plan File=p01
BEGIN DESCRIPTION:
UNT 003 in La Jarita Watershed
END DESCRIPTION:

--- UNT 003 in La Jarita Watershed.p01 (plan) ---

Plan Title=Multiple Run
Short Identifier=Multiple
Geom File=g01
Flow File=f01
Subcritical Flow
K Sum by GR= 0
Std Step Tol= 0.01
Critical Tol= 0.01
Num of Std Step Trials= 20
Max Error Tol= 0.3
Flow Tol Ratio= 0.001
Split Flow NTrial= 30
Split Flow Tol= 0.02
Split Flow Ratio= 0.02
Log Output Level= 0
Friction Slope Method= 1
Unsteady Friction Slope Method= 2
Unsteady Bridges Friction Slope Method= 1
Parabolic Critical Depth
Global Vel Dist=  1 , 1 , 1
Global Log Level= 0
CheckData=True
Encroach Param= -1, 0, 0, 0
BEGIN DESCRIPTION:
Multiple Run
END DESCRIPTION:

--- UNT 003 in La Jarita Watershed.f01 (steady flow) ---

Flow Title=Multiple
Number of Profiles=7
Profile Names=10-year,25-year,50-year,1pct_min,100-year,1pct_plu,500-year
River Rch & RM= UNT 003 in La Ja,Reach-1,15593
     185     255     312     191     381     761     577
River Rch & RM= UNT 003 in La Ja,Reach-1,14600
     261     364     449     277     552    1101     845
Boundary for River Rch & Prof#=UNT 003 in La Ja,Reach-1,1
Up Type=0
Dn Type=3
Dn Slope=0.005
Boundary for River Rch & Prof#=UNT 003 in La Ja,Reach-1,2
Up Type=0
Dn Type=3
Dn Slope=0.005
Boundary for River Rch & Prof#=UNT 003 in La Ja,Reach-1,3
Up Type=0
Dn Type=3
Dn Slope=0.005
Boundary for River Rch & Prof#=UNT 003 in La Ja,Reach-1,4
Up Type=0
Dn Type=3
Dn Slope=0.005
Boundary for River Rch & Prof#=UNT 003 in La Ja,Reach-1,5
Up Type=0
Dn Type=3
Dn Slope=0.005
Boundary for River Rch & Prof#=UNT 003 in La Ja,Reach-1,6
Up Type=0
Dn Type=3
Dn Slope=0.005
Boundary for River Rch & Prof#=UNT 003 in La Ja,Reach-1,7
Up Type=0
Dn Type=3
Dn Slope=0.005

--- UNT 003 in La Jarita Watershed.g01 (geometry) ---

Geom Title=Existing Conditions

River Reach=UNT 003 in La Ja,Reach-1
Reach XY= 30
      2116090.80     13389374.54      2116530.80     13389884.54
      2116490.80     13390644.54      2117070.80     13391104.54
      2117147.19     13391980.40      2117453.44     13392107.49
      2117760.80     13392694.54      2118210.80     13392584.54
      2118450.80     13393024.54      2118700.80     13393184.54
      2118750.80     13393454.54      2119100.80     13393474.54
      2119270.80     13393764.54      2119380.80     13393764.54
      2119461.77     13394007.49      2119381.04     13394168.94
      2119809.86     13394519.64      2119810.80     13394904.54
      2121510.80     13394684.54      2121631.48     13394981.44
      2121982.17     13394933.70      2122175.75     13395177.63
      2122620.80     13394914.54      2122830.80     13395064.54
      2122910.80     13394814.54      2123160.80     13394784.54
      2123750.80     13395124.54      2124060.80     13394874.54
      2124360.80     13395234.54      2125159.60     13394462.55

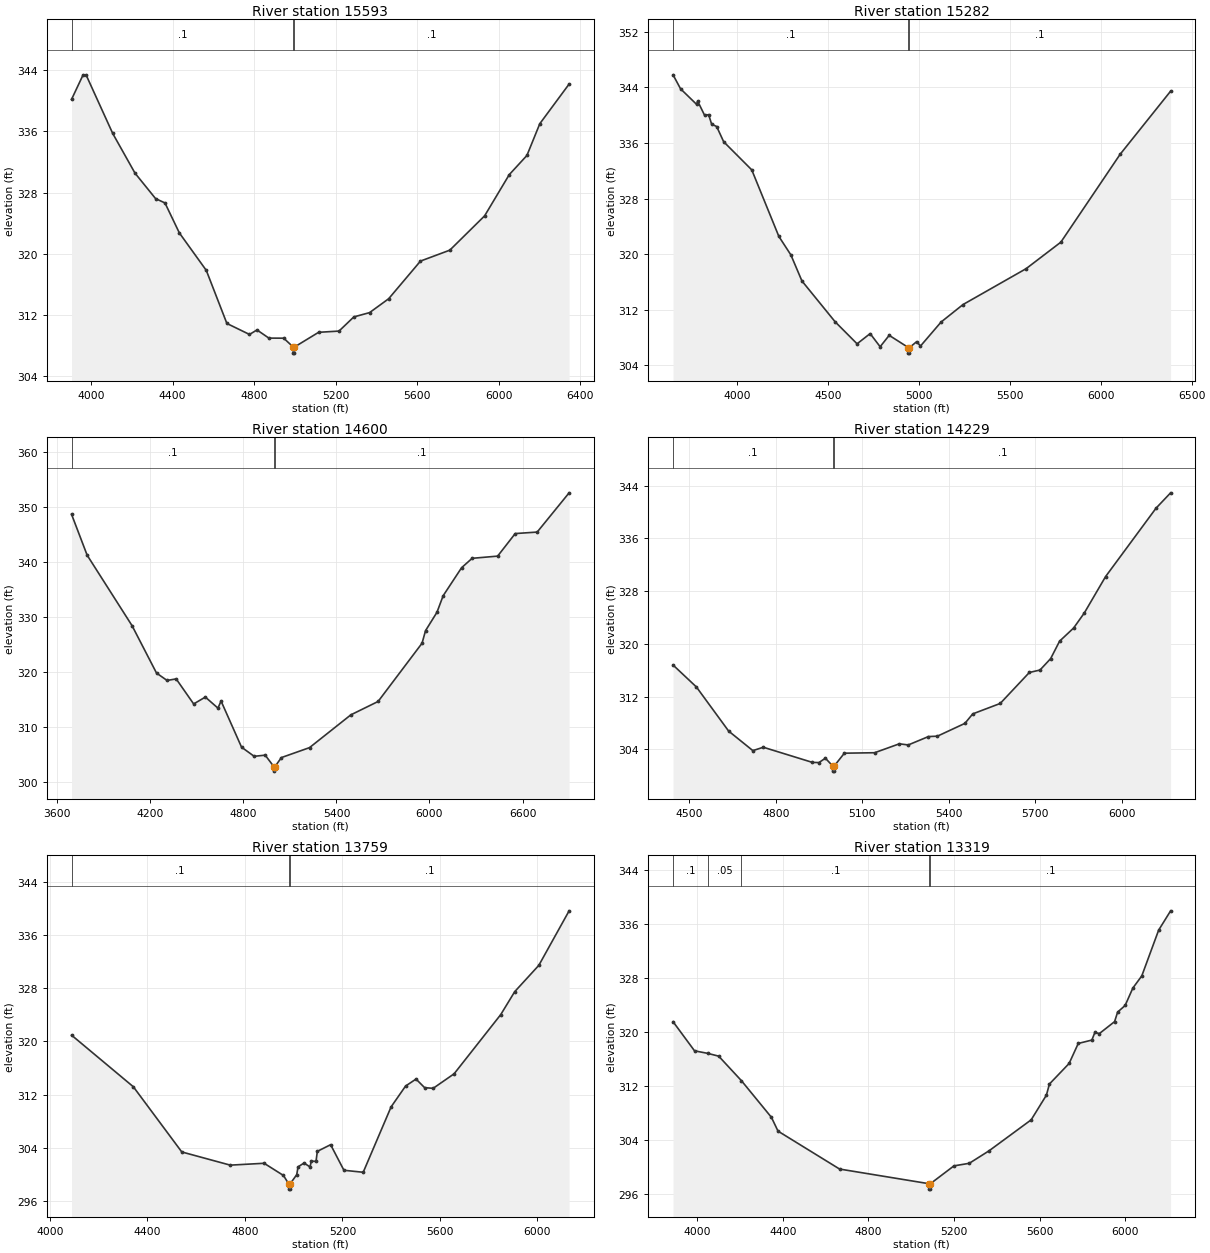
Type RM Length L Ch R = 1,15593,311,311,311
BEGIN DESCRIPTION:
UNT 003 in La Jarita Watershed 23.0
END DESCRIPTION:
XS GIS Cut Line= 3
      2115341.50     13390229.32      2116289.42     13389661.62
      2117360.90     13388860.61
#Sta/Elev= 30
  3903.5  340.21  3960.3  343.43  3975.9  343.36  4105.7  335.74  4215.0  330.54
  4316.1  327.20  4362.2  326.63  4432.8  322.70  4565.0  317.79  4666.1  310.83
  4777.0  309.39  4813.9  309.98  4872.3  308.91  4945.0  308.90  4991.8  307.74
  4992.3  306.94  4997.3  306.94  4997.8  307.74  5116.4  309.67  5216.5  309.83
  5289.4  311.69  5366.5  312.25  5460.3  314.07  5616.6  319.01  5760.5  320.44
  5931.4  324.94  6052.3  330.34  6139.1  332.86  6202.3  337.02  6346.2  342.22
#Mann=3,-1,0
  3903.5     0.1       0  4991.8    0.07       0  4997.8     0.1       0
Bank Sta=4991.8,4997.8
Exp/Cntr=0.3,0.1

Type RM Length L Ch R = 1,15282,682,682,682
BEGIN DESCRIPTION:
Mapping XS ef266b6a
END DESCRIPTION:
XS GIS Cut Line= 3
      2115336.31     13390510.57      2116419.62     13389942.87
      2117534.23     13388922.02
#Sta/Elev= 30
  3649.9  345.82  3691.1  343.81  3779.3  341.57  3785.0  342.04  3823.4  339.99
  3845.5  340.09  3861.9  338.72  3889.6  338.38  3928.1  336.19  4082.5  332.14
  4231.3  322.57  4297.5  319.90  4358.1  316.16  4540.3  310.29  4661.3  307.11
  4733.1  308.58  4788.0  306.69  4837.8  308.33  4943.2  306.57  4943.7  305.77
  4948.7  305.77  4949.2  306.57  4988.7  307.42  5009.8  306.79  5123.2  310.25
  5243.5  312.76  5590.0  317.92  5781.2  321.74  6106.8  334.38  6384.4  343.47
#Mann=3,-1,0
  3649.9     0.1       0  4943.2    0.07       0  4949.2     0.1       0
Bank Sta=4943.2,4949.2
Exp/Cntr=0.3,0.1

Type RM Length L Ch R = 1,14600,371,371,371
BEGIN DESCRIPTION:
Mapping XS b0173ca9
END DESCRIPTION:
XS GIS Cut Line= 3
      2115195.66     13390708.50      2116450.87     13390484.54
      2118195.65     13389651.21
#Sta/Elev= 30
  3691.8  348.68  3792.4  341.23  4082.0  328.39  4239.7  319.76  4307.6  318.41
  4366.5  318.69  4479.3  314.13  4554.6  315.38  4635.8  313.37  4656.1  314.65
  4788.2  306.25  4869.4  304.59  4940.7  304.80  4996.8  302.69  4997.3  301.89
  5002.8  302.69  5045.2  304.36  5226.3  306.17  5492.8  312.14  5668.7  314.58
  5952.0  325.19  5974.7  327.49  6048.3  330.83  6088.1  333.84  6207.1  338.95
  6275.1  340.66  6439.5  341.06  6552.9  345.17  6694.5  345.44  6900.4  352.59
#Mann=3,-1,0
  3691.8     0.1       0  4996.8    0.07       0  5002.8     0.1       0
Bank Sta=4996.8,5002.8
Exp/Cntr=0.3,0.1

Type RM Length L Ch R = 1,14229,470,470,470
BEGIN DESCRIPTION:
UNT 003 in La Jarita Watershed 22.0
END DESCRIPTION:
XS GIS Cut Line= 3
      2116125.03     13391024.99      2116625.00     13390775.00
      2117625.02     13390174.99
#Sta/Elev= 30
  4443.8  316.78  4524.8  313.45  4636.6  306.76  4720.5  303.80  4756.8  304.31
  4927.3  302.01  4949.7  301.99  4972.0  302.65  4996.9  301.49  4997.4  300.69
  5002.5  300.69  5003.0  301.49  5037.8  303.41  5142.7  303.48  5228.3  304.83
  5259.3  304.66  5329.3  305.93  5360.4  305.99  5455.7  307.93  5482.9  309.37
  5578.1  310.95  5679.2  315.65  5716.1  316.02  5753.0  317.75  5784.1  320.40
  5832.7  322.39  5869.7  324.67  5943.5  330.19  6118.4  340.56  6169.0  342.89
#Mann=3,-1,0
  4443.8     0.1       0  4996.9    0.07       0  5003.0     0.1       0
Bank Sta=4996.9,5003
Exp/Cntr=0.3,0.1

Type RM Length L Ch R = 1,13759,440,440,440
BEGIN DESCRIPTION:
Mapping XS 9d9428ce
END DESCRIPTION:
XS GIS Cut Line= 4
      2116061.44     13391110.44      2116488.56     13391214.61
      2117337.52     13390886.49      2117780.14     13390355.34
#Sta/Elev= 30
  4088.6  320.95  4342.2  313.20  4540.8  303.42  4739.7  301.44  4878.7  301.72
  4957.9  299.89  4979.4  298.64  4979.9  297.84  4985.0  297.84  4985.5  298.64
  5012.4  300.01  5017.8  301.18  5042.4  301.76  5066.9  301.17  5072.3  302.05
  5091.5  302.00  5096.9  303.51  5151.4  304.51  5206.0  300.67  5285.1  300.37
  5399.6  310.19  5458.9  313.31  5501.8  314.36  5537.0  313.07  5572.1  312.97
  5658.0  315.15  5849.4  324.04  5906.7  327.48  6005.6  331.43  6129.8  339.61
#Mann=3,-1,0
  4088.6     0.1       0  4979.4    0.07       0  4985.5     0.1       0
Bank Sta=4979.4,4985.5
Exp/Cntr=0.3,0.1

Type RM Length L Ch R = 1,13319,456,456,456
BEGIN DESCRIPTION:
Mapping XS f0e6b1df
END DESCRIPTION:
XS GIS Cut Line= 4
      2115957.30     13391329.19      2116577.10     13391475.03
      2117498.98     13391256.28      2118056.27     13390766.70
#Sta/Elev= 30
  3886.7  321.56  3987.1  317.25  4048.0  316.88  4100.1  316.46  4206.4  312.83
  4346.6  307.41  4377.4  305.37  4665.2  299.76  5083.5  297.59  5084.0  296.79
  5089.1  296.79  5089.6  297.59  5199.8  300.23  5271.5  300.61  5363.5  302.45
  5560.8  307.04  5632.0  310.69  5646.2  312.34  5738.2  315.38  5780.9  318.34
  5844.5  318.84  5858.7  319.97  5879.6  319.80  5950.8  321.57  5965.0  322.98
  6000.1  323.96  6036.2  326.54  6077.9  328.33  6156.7  335.10  6212.7  337.96
#Mann=5,-1,0
  3886.7     0.1       0  4048.0    0.05       0  4206.4     0.1       0
  5083.5    0.07       0  5089.6     0.1       0
Bank Sta=5083.5,5089.6
Exp/Cntr=0.3,0.1

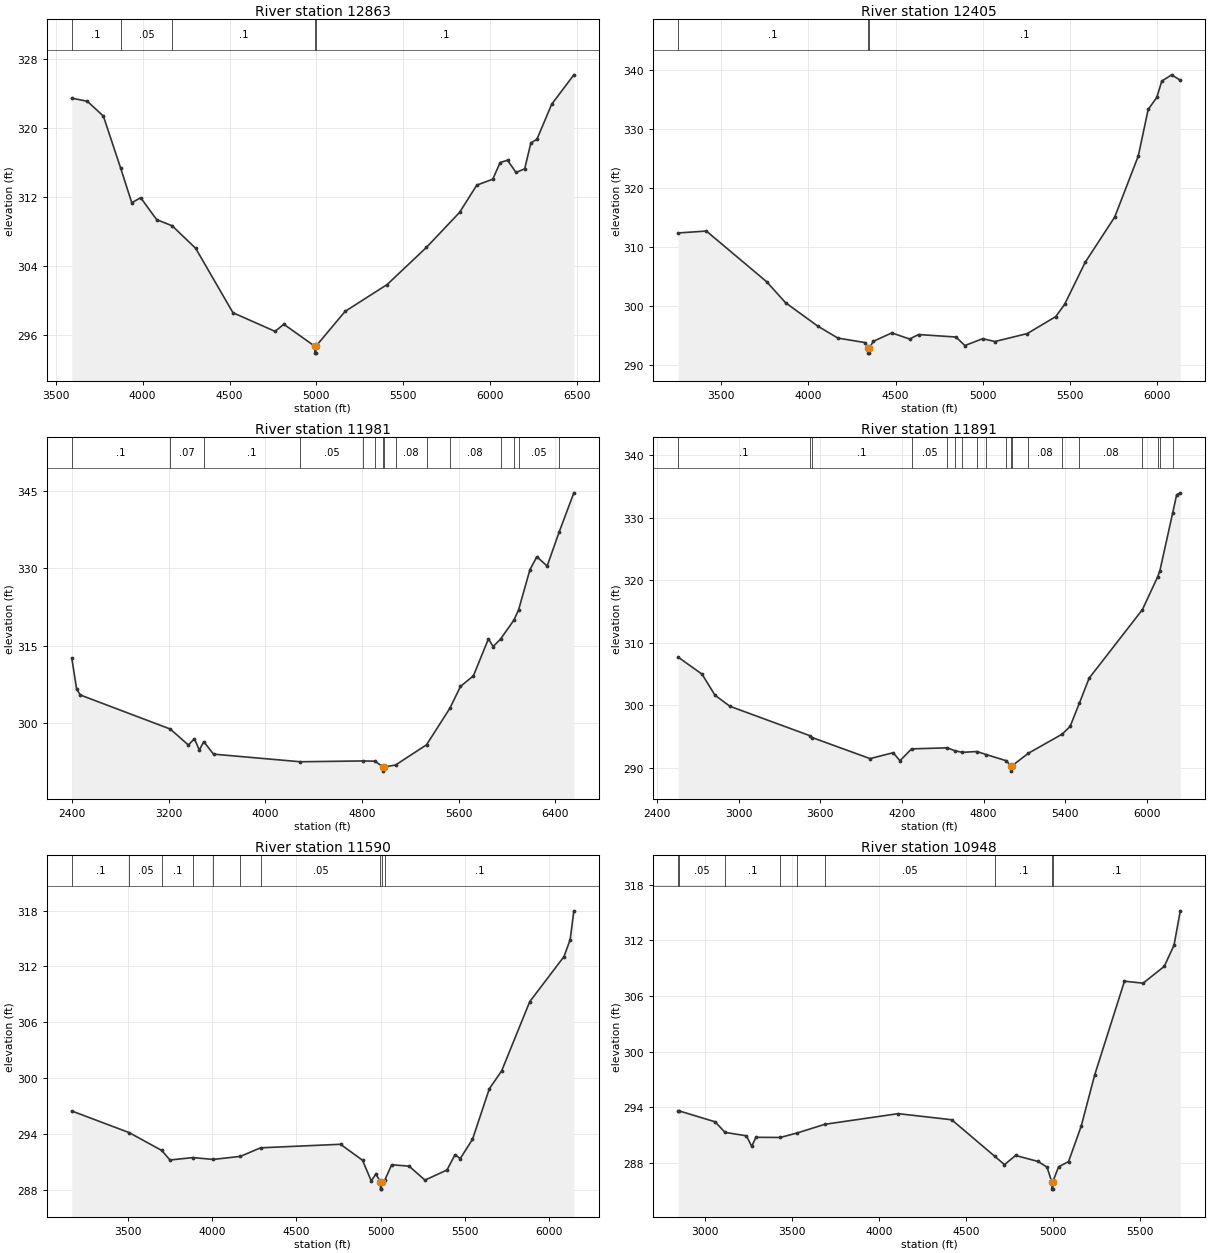
Type RM Length L Ch R = 1,12863,458,458,458
BEGIN DESCRIPTION:
Mapping XS 2bf6a60e
END DESCRIPTION:
XS GIS Cut Line= 4
      2115696.92     13391610.45      2116634.40     13391808.36
      2117676.06     13391672.95      2118320.33     13391070.25
#Sta/Elev= 30
  3591.7  323.50  3681.5  323.13  3773.7  321.41  3873.2  315.36  3937.2  311.33
  3988.3  311.92  4080.3  309.37  4169.9  308.65  4305.2  306.03  4519.8  298.54
  4762.2  296.37  4812.6  297.20  4991.1  294.64  4991.6  293.84  4996.8  293.84
  4997.3  294.64  5165.6  298.70  5407.6  301.82  5633.5  306.13  5824.5  310.21
  5923.6  313.38  6015.5  314.07  6058.0  316.00  6100.5  316.28  6149.8  314.85
  6199.6  315.28  6234.8  318.28  6270.0  318.72  6355.0  322.79  6482.5  326.21
#Mann=5,-1,0
  3591.7     0.1       0  3873.2    0.05       0  4169.9     0.1       0
  4991.1    0.07       0  4997.3     0.1       0
Bank Sta=4991.1,4997.3
Exp/Cntr=0.3,0.1

Type RM Length L Ch R = 1,12405,424,424,424
BEGIN DESCRIPTION:
Mapping XS d26bc523
END DESCRIPTION:
XS GIS Cut Line= 4
      2115639.61     13391902.12      2116618.77     13392198.99
      2117868.77     13391943.78      2118299.63     13391559.64
#Sta/Elev= 30
  3254.6  312.44  3415.7  312.76  3760.4  304.19  3869.6  300.61  4054.4  296.64
  4169.3  294.62  4326.4  293.85  4342.3  292.87  4342.8  292.07  4348.0  292.07
  4348.5  292.87  4371.8  294.07  4478.1  295.50  4580.1  294.46  4631.1  295.22
  4845.5  294.80  4896.5  293.36  4998.6  294.51  5068.7  294.04  5253.7  295.38
  5417.0  298.26  5467.7  300.32  5585.6  307.45  5755.4  315.16  5890.0  325.48
  5946.8  333.38  5996.2  335.42  6024.6  338.18  6081.4  339.24  6130.8  338.32
#Mann=3,-1,0
  3254.6     0.1       0  4342.3    0.07       0  4348.5     0.1       0
Bank Sta=4342.3,4348.5
Exp/Cntr=0.3,0.1

Type RM Length L Ch R = 1,11981,90,90,90
BEGIN DESCRIPTION:
UNT 003 in La Jarita Watershed 18.0
END DESCRIPTION:
XS GIS Cut Line= 4
      2115024.98     13392275.00      2117199.50     13392507.58
      2118373.55     13391941.18      2118884.45     13391512.93
#Sta/Elev= 30
  2397.9  312.58  2438.1  306.60  2468.3  305.42  3213.6  298.80  3363.4  295.70
  3413.7  296.93  3453.9  294.72  3490.7  296.36  3571.4  293.93  4289.0  292.45
  4813.2  292.61  4908.1  292.56  4976.4  291.43  4976.9  290.63  4982.6  291.43
  5079.0  291.82  5335.1  295.74  5528.2  302.83  5616.4  307.08  5723.4  309.15
  5848.1  316.33  5886.4  314.82  5948.9  316.30  6058.1  319.94  6097.0  321.92
  6191.4  329.76  6248.7  332.27  6333.9  330.46  6432.1  336.99  6555.0  344.68
#Mann=15,-1,0
  2397.9     0.1       0  3213.6    0.07       0  3490.7     0.1       0
  4289.0    0.05       0  4813.2    0.08       0  4908.1    0.05       0
  4976.4    0.03       0  4982.6    0.05       0  5079.0    0.08       0
  5335.1     0.1       0  5528.2    0.08       0  5948.9    0.05       0
  6058.1    0.08       0  6097.0    0.05       0  6432.1     0.1       0
Bank Sta=4976.4,4982.6
Exp/Cntr=0.3,0.1

Type RM Length L Ch R = 1,11891,301,301,301
BEGIN DESCRIPTION:
UNT 003 in La Jarita Watershed 17.0
END DESCRIPTION:
XS GIS Cut Line= 4
      2115224.99     13392525.00      2117195.16     13392581.37
      2117676.93     13392373.03      2118748.97     13391841.35
#Sta/Elev= 30
  2554.4  307.70  2729.4  305.00  2824.5  301.64  2934.6  299.87  3519.8  295.20
  3539.4  294.88  3965.0  291.52  4135.1  292.46  4185.1  291.18  4270.4  293.07
  4534.5  293.24  4586.6  292.79  4643.0  292.52  4751.5  292.65  4818.7  292.17
  4968.4  291.17  5000.2  290.32  5000.7  289.52  5006.4  290.32  5129.3  292.37
  5378.4  295.43  5436.5  296.66  5503.9  300.33  5576.5  304.36  5968.5  315.31
  6079.9  320.52  6096.3  321.48  6191.2  330.77  6220.1  333.64  6246.9  333.94
#Mann=19,-1,0
  2554.4     0.1       0  3519.8    0.07       0  3539.4     0.1       0
  4270.4    0.05       0  4534.5    0.08       0  4586.6    0.05       0
  4643.0    0.08       0  4751.5    0.05       0  4818.7    0.08       0
  4968.4     0.1       0  5000.2    0.07       0  5006.4     0.1       0
  5129.3    0.08       0  5378.4     0.1       0  5503.9    0.08       0
  5968.5    0.05       0  6079.9     0.1       0  6096.3    0.08       0
  6191.2     0.1       0
Bank Sta=5000.2,5006.4
Exp/Cntr=0.3,0.1

Type RM Length L Ch R = 1,11590,642,642,642
BEGIN DESCRIPTION:
Mapping XS 76a5781e
END DESCRIPTION:
XS GIS Cut Line= 3
      2115971.64     13392682.06      2117383.09     13392872.16
      2118703.40     13392041.44
#Sta/Elev= 30
  3165.0  296.46  3505.2  294.14  3699.6  292.22  3748.7  291.19  3885.5  291.45
  4004.8  291.25  4167.1  291.58  4287.2  292.50  4762.5  292.88  4893.2  291.16
  4945.0  288.94  4972.1  289.68  4999.6  288.86  5000.1  288.06  5005.4  288.06
  5005.9  288.86  5025.4  289.03  5066.3  290.68  5169.9  290.53  5264.1  289.03
  5394.8  290.11  5443.1  291.77  5473.7  291.34  5546.7  293.41  5646.8  298.85
  5719.8  300.76  5887.0  308.21  6090.7  313.06  6127.2  314.87  6149.1  317.97
#Mann=10,-1,0
  3165.0     0.1       0  3505.2    0.05       0  3699.6     0.1       0
  3885.5    0.05       0  4004.8     0.1       0  4167.1    0.08       0
  4287.2    0.05       0  4999.6    0.03       0  5005.9    0.05       0
  5025.4     0.1       0
Bank Sta=4999.6,5005.9
Exp/Cntr=0.3,0.1

Type RM Length L Ch R = 1,10948,306,306,306
BEGIN DESCRIPTION:
Mapping XS aaa30981
END DESCRIPTION:
XS GIS Cut Line= 4
      2116213.85     13392913.83      2117653.93     13393031.02
      2118479.45     13392489.35      2118763.29     13392132.59
#Sta/Elev= 30
  2845.0  293.63  2849.4  293.62  3056.8  292.44  3114.4  291.30  3237.4  290.93
  3267.5  289.79  3291.8  290.77  3431.9  290.75  3530.2  291.24  3688.0  292.17
  4110.3  293.32  4418.0  292.66  4665.8  288.72  4721.7  287.82  4785.7  288.81
  4915.3  288.16  4966.5  287.55  4993.6  285.98  4994.1  285.18  4999.4  285.18
  4999.9  285.98  5032.7  287.58  5090.1  288.15  5162.5  291.94  5240.8  297.51
  5411.8  307.60  5519.1  307.39  5640.6  309.20  5696.9  311.48  5733.1  315.19
#Mann=9,-1,0
  2845.0     0.1       0  2849.4    0.05       0  3114.4     0.1       0
  3431.9    0.05       0  3530.2    0.08       0  3688.0    0.05       0
  4665.8     0.1       0  4993.6    0.07       0  4999.9     0.1       0
Bank Sta=4993.6,4999.9
Exp/Cntr=0.3,0.1

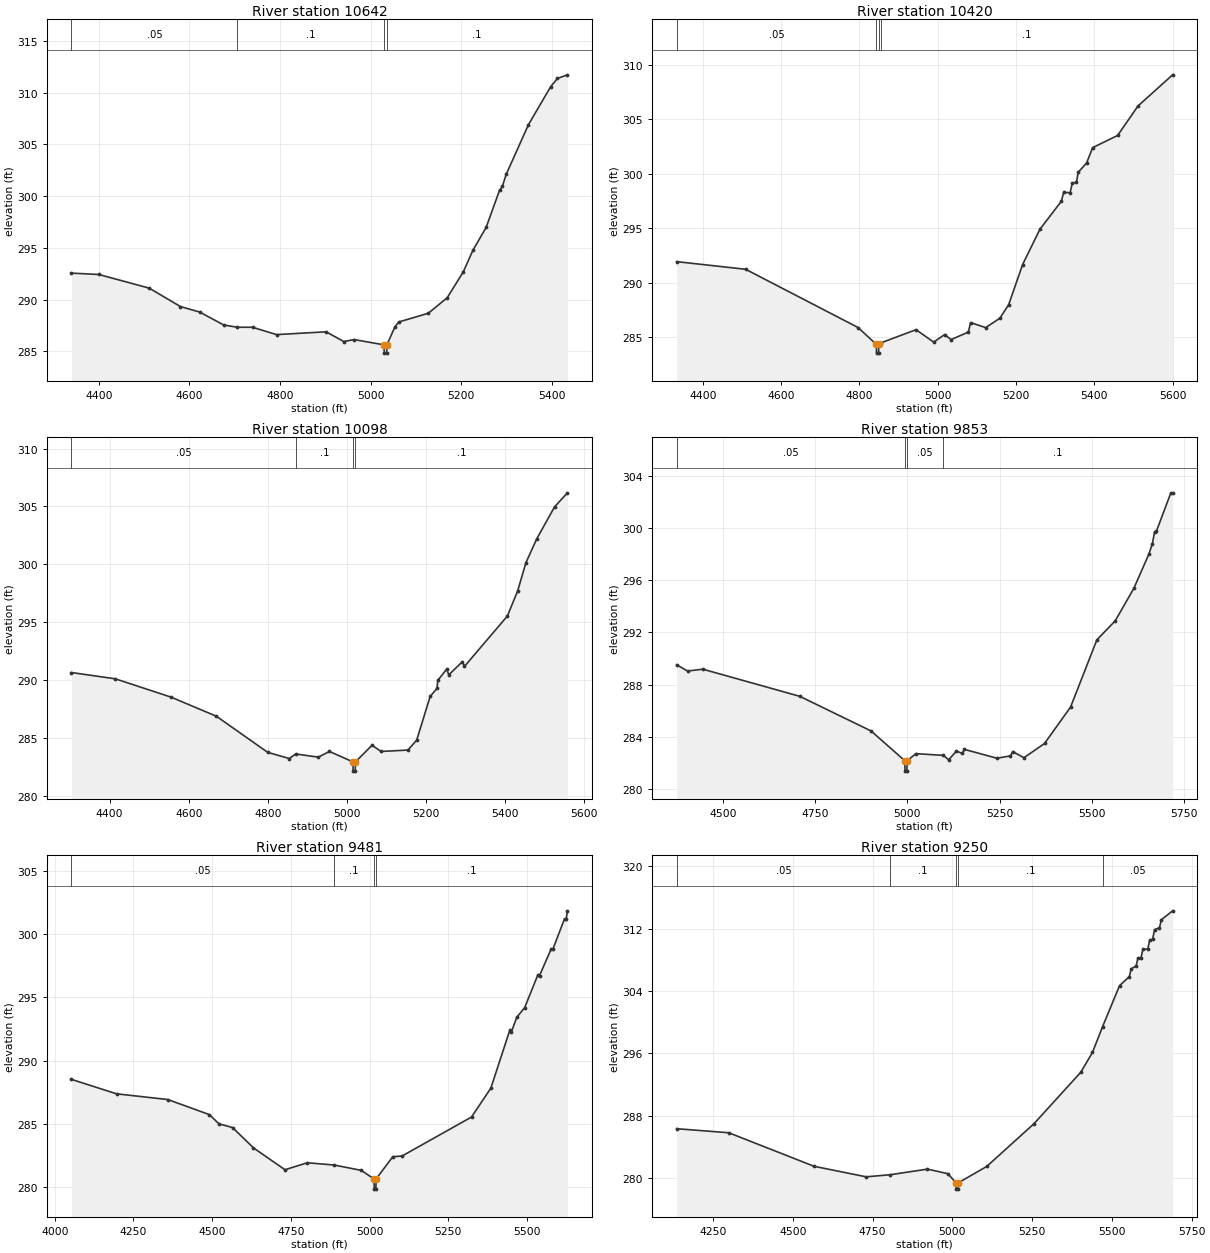
Type RM Length L Ch R = 1,10642,222,222,222
BEGIN DESCRIPTION:
UNT 003 in La Jarita Watershed 16.0
END DESCRIPTION:
XS GIS Cut Line= 3
      2117798.24     13393097.43      2118425.00     13392875.00
      2118775.02     13392624.99
#Sta/Elev= 30
  4339.4  292.55  4399.6  292.42  4511.1  291.10  4580.0  289.32  4622.5  288.79
  4675.5  287.54  4705.8  287.32  4739.2  287.32  4792.2  286.61  4901.7  286.88
  4940.8  285.94  4963.5  286.13  5029.6  285.62  5030.1  284.82  5035.4  284.82
  5035.9  285.62  5053.6  287.35  5062.2  287.83  5127.3  288.67  5169.1  290.17
  5204.8  292.69  5225.7  294.74  5255.2  296.98  5284.6  300.55  5290.8  300.92
  5299.4  302.10  5348.6  306.90  5397.7  310.57  5412.5  311.36  5434.6  311.71
#Mann=4,-1,0
  4339.4    0.05       0  4705.8     0.1       0  5029.6    0.07       0
  5035.9     0.1       0
Bank Sta=5029.6,5035.9
Exp/Cntr=0.3,0.1

Type RM Length L Ch R = 1,10420,322,322,322
BEGIN DESCRIPTION:
Mapping XS 75bbd138
END DESCRIPTION:
XS GIS Cut Line= 4
      2117858.99     13393188.57      2118245.29     13393197.25
      2118805.19     13392906.45      2118935.41     13392693.76
#Sta/Elev= 30
  4333.1  291.93  4509.2  291.23  4796.4  285.89  4843.1  284.34  4843.6  283.54
  4848.9  283.54  4849.4  284.34  4855.7  284.49  4944.5  285.69  4989.6  284.55
  5017.5  285.24  5034.0  284.78  5078.2  285.47  5083.9  286.34  5122.5  285.88
  5158.6  286.74  5181.2  287.99  5216.6  291.65  5260.8  294.89  5315.9  297.48
  5321.5  298.28  5338.0  298.25  5343.6  299.12  5354.2  299.21  5358.8  300.13
  5380.1  300.97  5395.5  302.38  5459.4  303.50  5511.6  306.21  5599.8  309.06
#Mann=4,-1,0
  4333.1    0.05       0  4843.1    0.07       0  4849.4    0.05       0
  4855.7     0.1       0
Bank Sta=4843.1,4849.4
Exp/Cntr=0.3,0.1

Type RM Length L Ch R = 1,10098,245,245,245
BEGIN DESCRIPTION:
Mapping XS 2ca9b95f
END DESCRIPTION:
XS GIS Cut Line= 4
      2118045.68     13393336.15      2118405.88     13393392.56
      2118913.69     13393149.51      2119000.24     13392833.62
#Sta/Elev= 30
  4303.3  290.65  4414.0  290.11  4555.7  288.52  4670.2  286.87  4800.0  283.75
  4854.5  283.22  4871.0  283.61  4928.0  283.34  4956.2  283.83  5015.6  282.93
  5016.1  282.13  5021.4  282.13  5021.9  282.93  5064.0  284.37  5086.7  283.83
  5154.7  283.95  5176.9  284.81  5211.1  288.59  5228.3  289.28  5230.3  289.97
  5252.9  290.95  5258.1  290.45  5292.6  291.59  5297.8  291.18  5406.4  295.53
  5432.5  297.71  5453.3  300.14  5480.5  302.19  5525.9  304.97  5558.4  306.18
#Mann=4,-1,0
  4303.3    0.05       0  4871.0     0.1       0  5015.6    0.07       0
  5021.9     0.1       0
Bank Sta=5015.6,5021.9
Exp/Cntr=0.3,0.1

Type RM Length L Ch R = 1,9853,372,372,372
BEGIN DESCRIPTION:
Mapping XS ed5d1d3e
END DESCRIPTION:
XS GIS Cut Line= 4
      2118175.89     13393509.76      2118596.85     13393574.86
      2119048.24     13393292.74      2119095.99     13392910.78
#Sta/Elev= 30
  4375.0  289.52  4404.5  289.04  4446.0  289.18  4708.4  287.10  4901.7  284.44
  4992.9  282.16  4993.4  281.36  4998.7  281.36  4999.2  282.16  5023.2  282.70
  5097.4  282.57  5111.7  282.23  5132.9  282.90  5148.2  282.72  5154.1  283.03
  5242.5  282.35  5279.1  282.53  5285.0  282.86  5315.7  282.39  5371.3  283.48
  5441.8  286.27  5513.1  291.43  5562.8  292.89  5613.2  295.38  5653.5  297.98
  5663.6  298.82  5669.3  299.70  5674.3  299.76  5713.5  302.71  5718.2  302.71
#Mann=4,-1,0
  4375.0    0.05       0  4992.9    0.03       0  4999.2    0.05       0
  5097.4     0.1       0
Bank Sta=4992.9,4999.2
Exp/Cntr=0.3,0.1

Type RM Length L Ch R = 1,9481,231,231,231
BEGIN DESCRIPTION:
Mapping XS e7262449
END DESCRIPTION:
XS GIS Cut Line= 4
      2118253.99     13393648.64      2118757.44     13393739.79
      2119252.23     13393375.20      2119148.44     13392938.41
#Sta/Elev= 30
  4053.1  288.52  4196.4  287.38  4359.0  286.93  4491.1  285.74  4521.6  285.01
  4564.7  284.72  4630.9  283.12  4731.2  281.39  4802.2  281.94  4888.0  281.76
  4973.4  281.34  5014.2  280.66  5014.7  279.86  5020.0  279.86  5020.5  280.66
  5073.7  282.42  5102.9  282.47  5323.7  285.55  5385.1  287.83  5445.1  292.39
  5450.2  292.25  5467.4  293.42  5492.4  294.18  5534.6  296.78  5539.7  296.71
  5576.8  298.82  5581.9  298.78  5619.0  301.19  5624.1  301.14  5628.3  301.82
#Mann=4,-1,0
  4053.1    0.05       0  4888.0     0.1       0  5014.2    0.07       0
  5020.5     0.1       0
Bank Sta=5014.2,5020.5
Exp/Cntr=0.3,0.1

Type RM Length L Ch R = 1,9250,352,352,352
BEGIN DESCRIPTION:
Mapping XS 4c834007
END DESCRIPTION:
XS GIS Cut Line= 4
      2118475.35     13393856.98      2118878.97     13393943.78
      2119430.19     13393501.07      2119660.12     13393132.32
#Sta/Elev= 30
  4135.9  286.31  4299.2  285.79  4566.8  281.48  4730.0  280.13  4805.5  280.40
  4922.1  281.12  4986.1  280.53  5011.7  279.35  5012.2  278.55  5017.6  278.55
  5018.1  279.35  5107.7  281.46  5255.6  286.94  5402.5  293.56  5439.1  296.10
  5471.0  299.43  5524.0  304.68  5554.7  305.84  5560.6  306.84  5575.9  307.21
  5581.8  308.26  5591.3  308.27  5597.2  309.33  5612.5  309.39  5618.4  310.50
  5627.9  310.66  5633.7  311.88  5649.1  312.11  5655.0  313.14  5690.3  314.29
#Mann=5,-1,0
  4135.9    0.05       0  4805.5     0.1       0  5011.7    0.07       0
  5018.1     0.1       0  5471.0    0.05       0
Bank Sta=5011.7,5018.1
Exp/Cntr=0.3,0.1

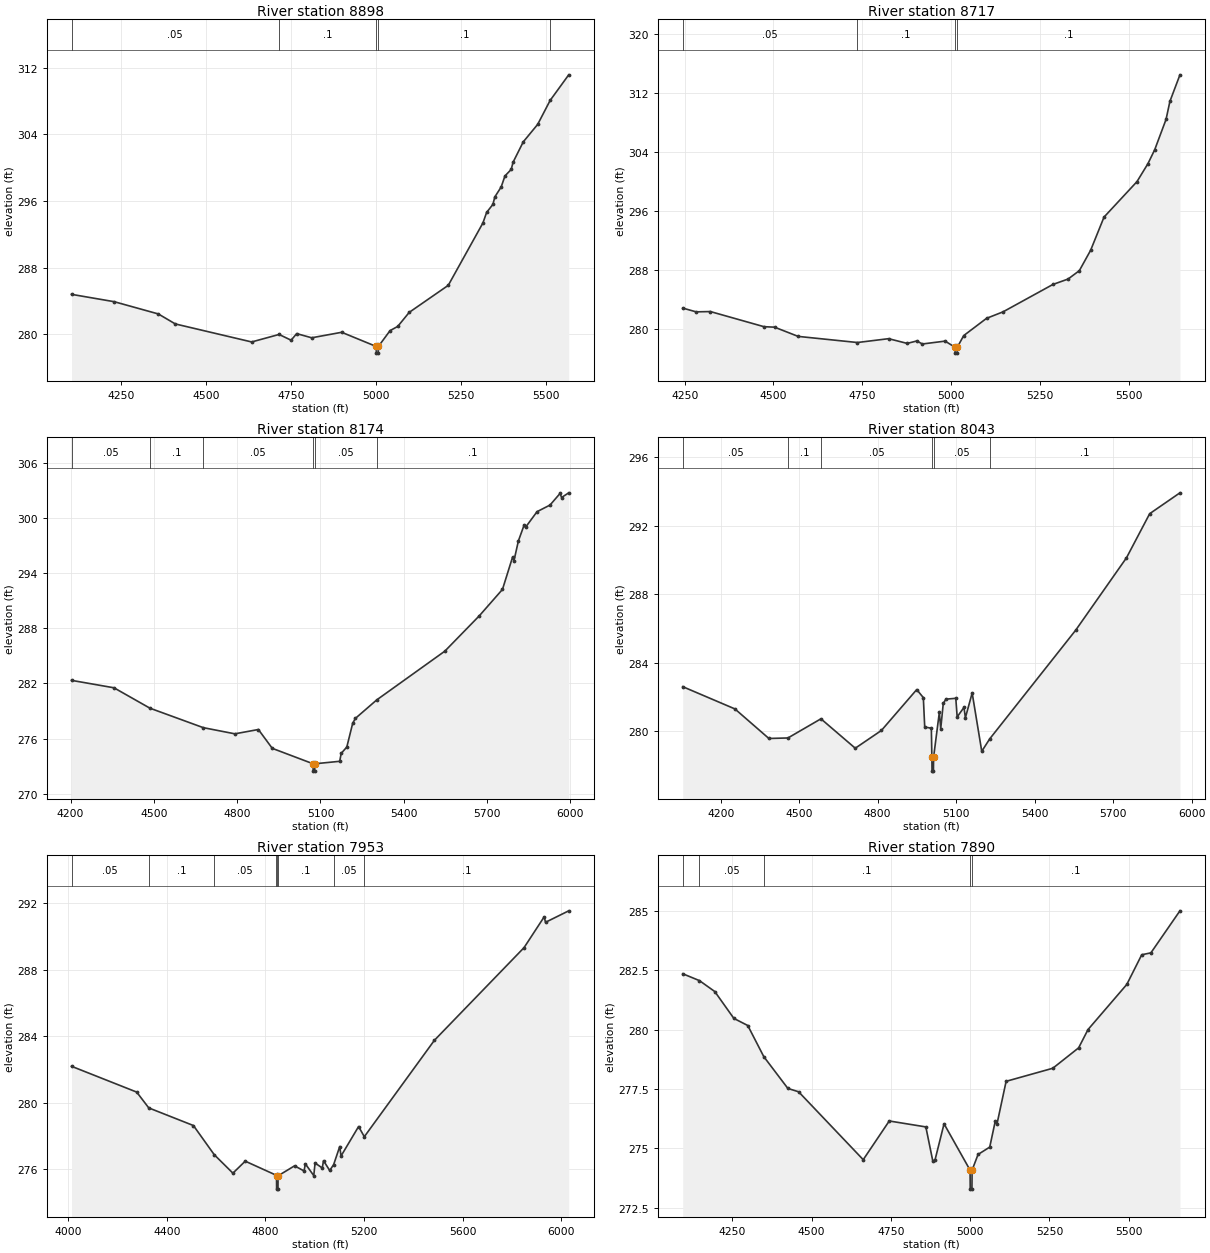
Type RM Length L Ch R = 1,8898,181,181,181
BEGIN DESCRIPTION:
Mapping XS 0db35407
END DESCRIPTION:
XS GIS Cut Line= 4
      2118579.52     13394047.95      2118970.12     13394056.63
      2119560.39     13393748.47      2119712.31     13393370.85
#Sta/Elev= 30
  4102.9  284.80  4228.4  283.92  4358.4  282.45  4408.5  281.25  4633.2  279.09
  4713.9  279.99  4749.3  279.30  4765.7  280.09  4809.9  279.59  4898.2  280.25
  4999.8  278.55  5000.3  277.75  5005.7  277.75  5006.2  278.55  5040.6  280.45
  5063.1  280.95  5097.0  282.64  5211.9  285.88  5313.9  293.36  5324.9  294.63
  5343.5  295.60  5348.9  296.48  5367.7  297.68  5378.8  299.00  5397.3  299.79
  5402.6  300.64  5432.7  303.09  5475.2  305.19  5511.8  308.06  5566.5  311.13
#Mann=5,-1,0
  4102.9    0.05       0  4713.9     0.1       0  4999.8    0.07       0
  5006.2     0.1       0  5511.8    0.05       0
Bank Sta=4999.8,5006.2
Exp/Cntr=0.3,0.1

Type RM Length L Ch R = 1,8717,543,543,543
BEGIN DESCRIPTION:
Mapping XS 6d1cd0ae
END DESCRIPTION:
XS GIS Cut Line= 4
      2118757.49     13394208.53      2119152.41     13394173.81
      2119634.18     13393883.02      2119781.11     13393468.14
#Sta/Elev= 30
  4244.6  282.86  4282.3  282.35  4322.4  282.39  4473.0  280.34  4503.1  280.27
  4569.4  279.02  4736.2  278.19  4823.9  278.71  4876.2  278.07  4903.4  278.40
  4919.0  277.99  4983.0  278.38  5010.9  277.55  5011.4  276.75  5016.8  276.75
  5017.3  277.55  5035.4  279.13  5099.6  281.47  5146.0  282.35  5286.5  286.07
  5329.0  286.80  5360.8  287.94  5392.6  290.71  5430.3  295.21  5523.0  300.02
  5553.9  302.46  5573.0  304.36  5604.8  308.46  5615.7  310.91  5643.9  314.51
#Mann=4,-1,0
  4244.6    0.05       0  4736.2     0.1       0  5010.9    0.07       0
  5017.3     0.1       0
Bank Sta=5010.9,5017.3
Exp/Cntr=0.3,0.1

Type RM Length L Ch R = 1,8174,131,131,131
BEGIN DESCRIPTION:
UNT 003 in La Jarita Watershed 13.0
END DESCRIPTION:
XS GIS Cut Line= 4
      2118832.10     13394352.63      2119420.49     13394348.86
      2119721.71     13394343.65      2119937.21     13393469.08
#Sta/Elev= 30
  4203.6  282.34  4356.5  281.53  4486.0  279.31  4678.2  277.19  4791.8  276.52
  4876.5  276.99  4926.5  274.94  5073.4  273.26  5073.9  272.46  5079.3  272.46
  5079.8  273.26  5169.4  273.53  5174.6  274.39  5194.9  275.08  5216.1  277.67
  5225.8  278.20  5302.6  280.21  5548.0  285.52  5672.5  289.38  5755.5  292.24
  5791.9  295.76  5797.0  295.38  5812.8  297.52  5833.4  299.24  5838.5  299.00
  5880.0  300.70  5926.7  301.42  5963.0  302.69  5968.2  302.24  5994.0  302.75
#Mann=6,-1,0
  4203.6    0.05       0  4486.0     0.1       0  4678.2    0.05       0
  5073.4   0.035       0  5079.8    0.05       0  5302.6     0.1       0
Bank Sta=5073.4,5079.8
Exp/Cntr=0.3,0.1

Type RM Length L Ch R = 1,8043,90,90,90
BEGIN DESCRIPTION:
Mapping XS ccf99d88
END DESCRIPTION:
XS GIS Cut Line= 4
      2118795.67     13394430.76      2119684.38     13394421.78
      2119798.96     13394380.11      2120086.55     13393538.15
#Sta/Elev= 30
  4054.9  282.59  4254.2  281.29  4384.2  279.56  4457.0  279.59  4583.1  280.71
  4714.3  278.99  4814.3  280.03  4949.2  282.42  4974.5  281.95  4979.8  280.23
  5005.1  280.16  5007.2  278.45  5007.7  277.65  5013.1  277.65  5013.6  278.45
  5035.7  281.09  5041.0  280.14  5050.7  281.61  5060.8  281.86  5098.6  281.91
  5103.8  280.82  5129.9  281.38  5135.2  280.77  5161.2  282.22  5197.8  278.81
  5228.4  279.54  5557.1  285.90  5751.0  290.13  5839.7  292.71  5955.3  293.93
#Mann=6,-1,0
  4054.9    0.05       0  4457.0     0.1       0  4583.1    0.05       0
  5007.2   0.035       0  5013.6    0.05       0  5228.4     0.1       0
Bank Sta=5007.2,5013.6
Exp/Cntr=0.3,0.1

Type RM Length L Ch R = 1,7953,63,63,63
BEGIN DESCRIPTION:
UNT 003 in La Jarita Watershed 12.0
END DESCRIPTION:
XS GIS Cut Line= 4
      2118800.84     13394498.47      2119729.09     13394494.69
      2119846.27     13394462.14      2120172.38     13393553.14
#Sta/Elev= 30
  4013.9  282.20  4278.1  280.65  4327.0  279.70  4508.1  278.64  4592.4  276.89
  4668.1  275.78  4718.1  276.50  4841.5  275.67  4844.9  275.62  4845.4  274.82
  4850.8  274.82  4851.3  275.62  4918.1  276.22  4956.6  275.91  4961.8  276.34
  4996.0  275.63  5001.2  276.39  5030.3  276.09  5035.5  276.53  5060.5  275.94
  5076.5  276.29  5101.2  277.38  5106.5  276.81  5177.6  278.58  5200.9  277.97
  5484.9  283.76  5848.5  289.33  5930.1  291.18  5935.4  290.85  6029.5  291.54
#Mann=8,-1,0
  4013.9    0.05       0  4327.0     0.1       0  4592.4    0.05       0
  4841.5     0.1       0  4844.9    0.07       0  4851.3     0.1       0
  5076.5    0.05       0  5200.9     0.1       0
Bank Sta=4844.9,4851.3
Exp/Cntr=0.3,0.1

Type RM Length L Ch R = 1,7890,333,333,333
BEGIN DESCRIPTION:
Mapping XS 11cc697f
END DESCRIPTION:
XS GIS Cut Line= 4
      2118944.09     13394677.29      2119430.19     13394707.67
      2119977.06     13394460.27      2120167.51     13394018.77
#Sta/Elev= 30
  4093.6  282.35  4146.4  282.06  4194.7  281.60  4254.8  280.47  4298.7  280.17
  4349.2  278.86  4425.2  277.52  4459.0  277.38  4662.8  274.52  4744.9  276.15
  4860.3  275.90  4882.3  274.46  4889.1  274.50  4917.7  276.03  4999.8  274.08
  5000.3  273.28  5005.7  273.28  5006.2  274.08  5025.0  274.74  5061.8  275.05
  5079.4  276.15  5084.5  276.01  5113.5  277.82  5260.7  278.37  5342.2  279.23
  5371.8  280.00  5494.1  281.90  5541.2  283.15  5570.1  283.23  5661.7  285.00
#Mann=5,-1,0
  4093.6     0.1       0  4146.4    0.05       0  4349.2     0.1       0
  4999.8    0.07       0  5006.2     0.1       0
Bank Sta=4999.8,5006.2
Exp/Cntr=0.3,0.1

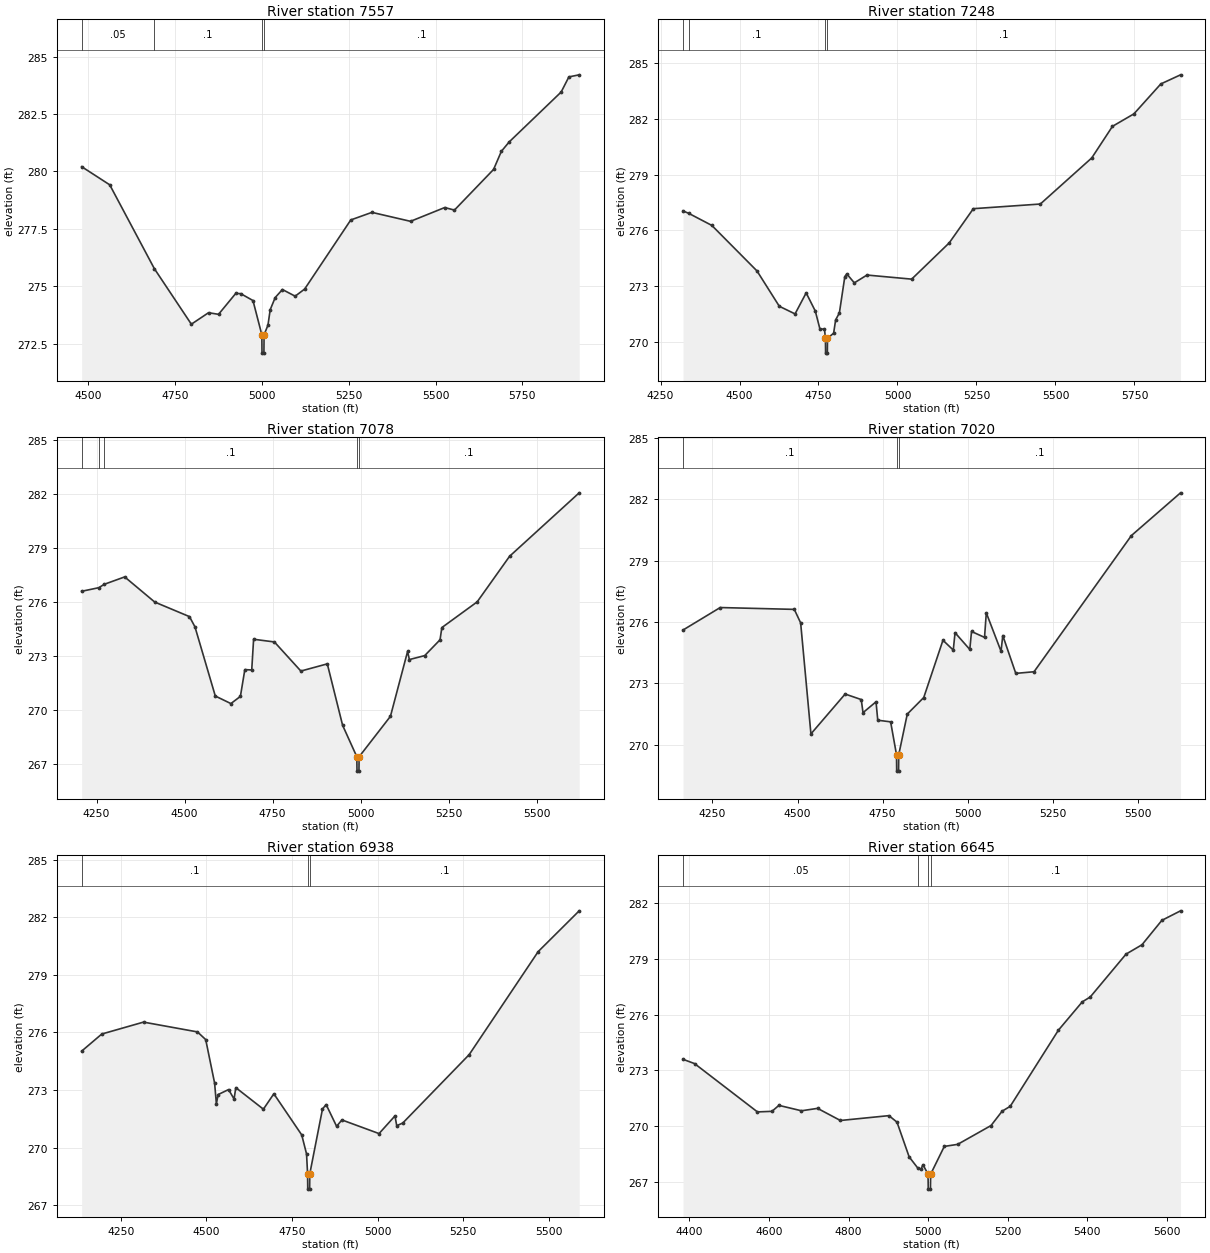
Type RM Length L Ch R = 1,7557,309,309,309
BEGIN DESCRIPTION:
Mapping XS 65b8c3a1
END DESCRIPTION:
XS GIS Cut Line= 3
      2119365.09     13395159.05      2119903.28     13394725.03
      2120227.99     13394058.29
#Sta/Elev= 30
  4480.7  280.21  4561.5  279.42  4690.0  275.77  4796.6  273.35  4846.1  273.85
  4874.9  273.78  4924.5  274.69  4938.9  274.68  4974.1  274.38  4999.6  272.89
  5000.1  272.09  5005.6  272.09  5006.1  272.89  5017.3  273.31  5023.7  273.98
  5038.1  274.51  5058.9  274.86  5095.6  274.57  5122.9  274.88  5255.8  277.89
  5316.7  278.22  5427.9  277.83  5526.3  278.43  5554.4  278.32  5667.1  280.09
  5689.6  280.88  5712.2  281.29  5861.7  283.46  5884.0  284.12  5913.7  284.21
#Mann=4,-1,0
  4480.7    0.05       0  4690.0     0.1       0  4999.6    0.07       0
  5006.1     0.1       0
Bank Sta=4999.6,5006.1
Exp/Cntr=0.3,0.1

Type RM Length L Ch R = 1,7248,170,170,170
BEGIN DESCRIPTION:
Mapping XS 5032f5b6
END DESCRIPTION:
XS GIS Cut Line= 4
      2119608.10     13395376.10      2119998.76     13395072.25
      2120020.46     13394638.22      2120280.90     13394047.90
#Sta/Elev= 30
  4321.2  277.05  4339.2  276.92  4412.4  276.27  4555.4  273.82  4626.0  271.92
  4675.8  271.51  4711.0  272.64  4740.0  271.66  4754.5  270.70  4769.0  270.69
  4772.0  270.20  4772.5  269.40  4778.0  269.40  4778.5  270.20  4797.9  270.47
  4804.3  271.19  4816.1  271.56  4833.4  273.52  4839.6  273.66  4863.4  273.18
  4903.5  273.60  5044.9  273.38  5163.8  275.33  5240.1  277.17  5452.1  277.42
  5614.9  279.90  5680.5  281.60  5748.3  282.27  5833.5  283.88  5895.9  284.37
#Mann=4,-1,0
  4321.2    0.05       0  4339.2     0.1       0  4772.0    0.07       0
  4778.5     0.1       0
Bank Sta=4772,4778.5
Exp/Cntr=0.3,0.1

Type RM Length L Ch R = 1,7078,58,58,58
BEGIN DESCRIPTION:
Mapping XS 7fd529bf
END DESCRIPTION:
XS GIS Cut Line= 4
      2119831.25     13395534.03      2120036.96     13395299.68
      2120141.12     13394971.56      2120305.18     13394232.02
#Sta/Elev= 30
  4207.7  276.60  4256.4  276.80  4272.1  276.99  4329.9  277.40  4415.3  276.00
  4514.0  275.19  4529.6  274.62  4587.4  270.77  4631.7  270.35  4658.7  270.75
  4671.3  272.24  4690.9  272.22  4696.2  273.93  4755.3  273.78  4830.5  272.16
  4905.6  272.56  4949.1  269.14  4989.5  267.39  4990.0  266.59  4995.5  266.59
  4996.0  267.39  5085.0  269.64  5133.7  273.25  5138.8  272.80  5182.4  273.02
  5225.9  273.90  5231.1  274.58  5331.4  276.01  5423.6  278.55  5621.3  282.08
#Mann=5,-1,0
  4207.7     0.1       0  4256.4    0.05       0  4272.1     0.1       0
  4989.5    0.07       0  4996.0     0.1       0
Bank Sta=4989.5,4996
Exp/Cntr=0.3,0.1

Type RM Length L Ch R = 1,7020,82,82,82
BEGIN DESCRIPTION:
Mapping XS caf7481c
END DESCRIPTION:
XS GIS Cut Line= 4
      2119958.82     13395609.60      2120128.10     13395351.77
      2120148.94     13395187.70      2120365.08     13394224.17
#Sta/Elev= 30
  4163.7  275.61  4273.0  276.71  4490.6  276.62  4509.2  275.96  4539.4  270.53
  4639.9  272.48  4687.2  272.21  4692.4  271.57  4730.6  272.10  4735.7  271.20
  4773.5  271.12  4790.8  269.51  4791.3  268.71  4796.8  268.71  4797.3  269.51
  4822.4  271.50  4870.8  272.31  4927.2  275.11  4957.5  274.63  4962.7  275.48
  5006.0  274.66  5011.1  275.54  5049.3  275.25  5054.5  276.45  5097.8  274.57
  5102.9  275.34  5141.1  273.49  5194.7  273.57  5480.7  280.23  5625.0  282.32
#Mann=3,-1,0
  4163.7     0.1       0  4790.8    0.07       0  4797.3     0.1       0
Bank Sta=4790.8,4797.3
Exp/Cntr=0.3,0.1

Type RM Length L Ch R = 1,6938,293,293,293
BEGIN DESCRIPTION:
Mapping XS cf3a9a70
END DESCRIPTION:
XS GIS Cut Line= 3
      2120005.73     13395617.36      2120214.04     13395320.52
      2120422.15     13394248.77
#Sta/Elev= 30
  4135.2  275.03  4194.0  275.92  4316.0  276.54  4473.7  276.03  4497.8  275.63
  4523.8  273.37  4529.0  272.29  4534.1  272.77  4564.6  273.03  4580.7  272.54
  4585.8  273.13  4666.4  272.01  4697.0  272.81  4778.5  270.67  4792.6  269.68
  4795.6  268.65  4796.1  267.85  4801.6  267.85  4802.1  268.65  4839.2  272.02
  4849.8  272.25  4880.4  271.12  4896.0  271.45  5004.5  270.74  5051.1  271.66
  5056.2  271.15  5073.9  271.29  5268.1  274.85  5469.8  280.21  5589.6  282.33
#Mann=3,-1,0
  4135.2     0.1       0  4795.6    0.07       0  4802.1     0.1       0
Bank Sta=4795.6,4802.1
Exp/Cntr=0.3,0.1

Type RM Length L Ch R = 1,6645,397,397,397
BEGIN DESCRIPTION:
Mapping XS 3fe18919
END DESCRIPTION:
XS GIS Cut Line= 4
      2120477.05     13395424.71      2120638.52     13395075.72
      2120549.98     13394583.54      2120542.20     13394218.14
#Sta/Elev= 30
  4383.9  273.60  4412.9  273.37  4570.9  270.78  4607.4  270.81  4624.8  271.13
  4681.6  270.84  4722.0  270.97  4779.3  270.32  4901.3  270.58  4921.6  270.23
  4952.1  268.37  4973.8  267.77  4981.7  267.70  4986.8  267.95  4999.6  267.44
  5000.1  266.64  5005.6  266.64  5006.1  267.44  5040.4  268.93  5074.0  269.04
  5157.9  270.05  5185.8  270.82  5206.1  271.08  5327.1  275.16  5387.1  276.68
  5407.1  276.94  5497.1  279.24  5537.1  279.74  5587.1  281.05  5634.0  281.56
#Mann=4,-1,0
  4383.9    0.05       0  4973.8     0.1       0  4999.6    0.07       0
  5006.1     0.1       0
Bank Sta=4999.6,5006.1
Exp/Cntr=0.3,0.1