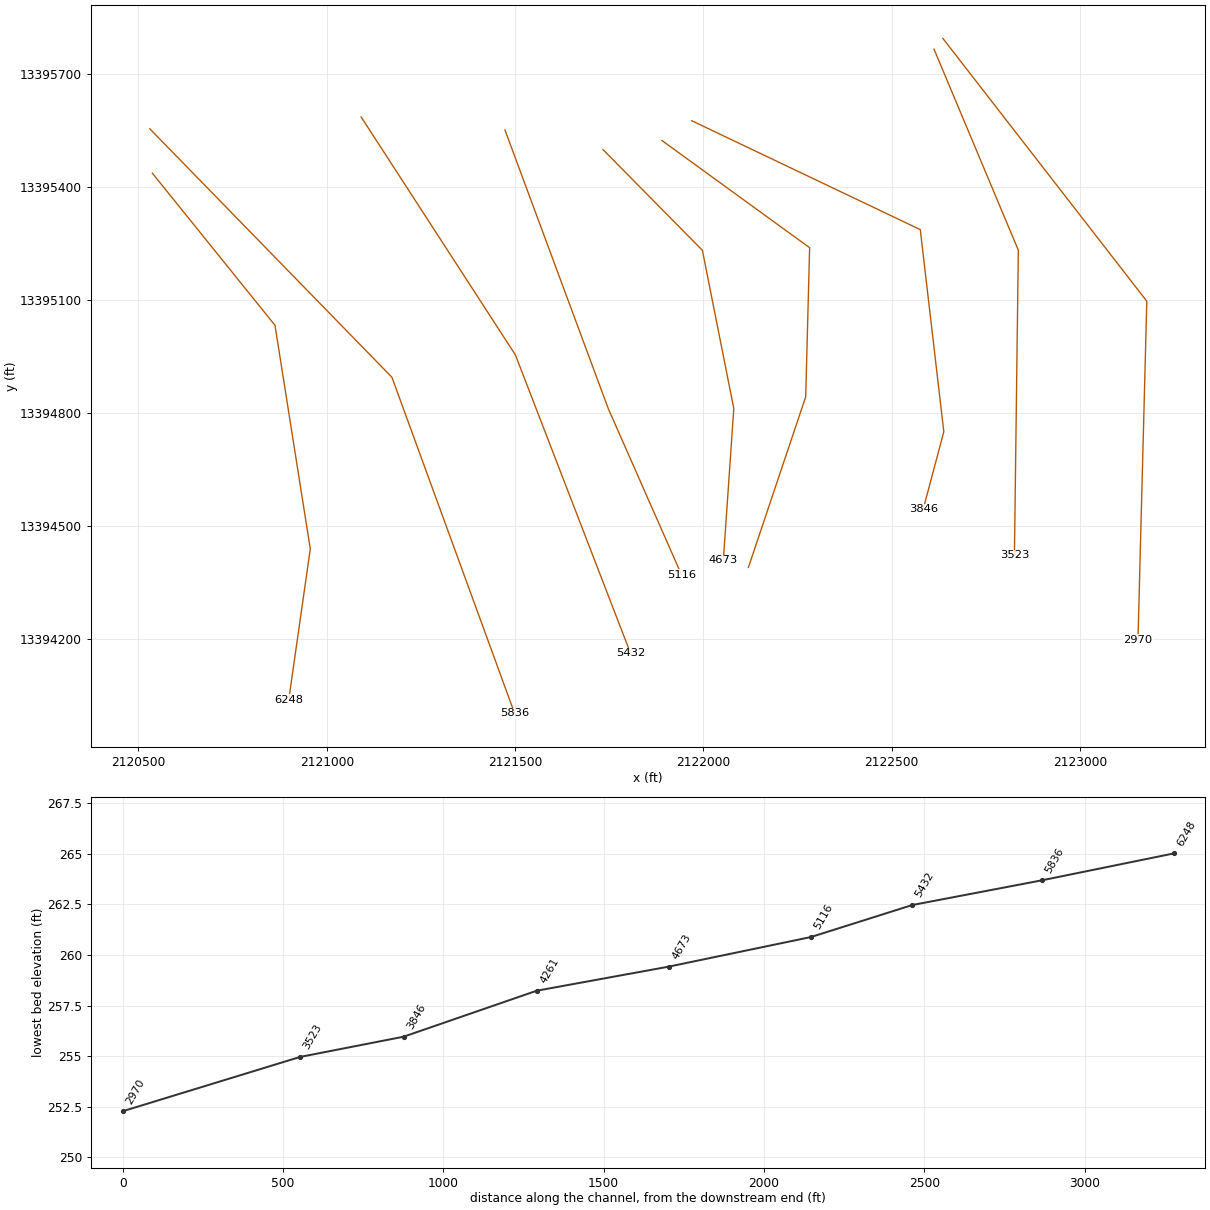
HEC-RAS study UNT 003 in La Jarita Watershed.prj: UNT 003 in La Jarita Watershed Base Level Engineering

--- UNT 003 in La Jarita Watershed.g01 (geometry) --- (continued)

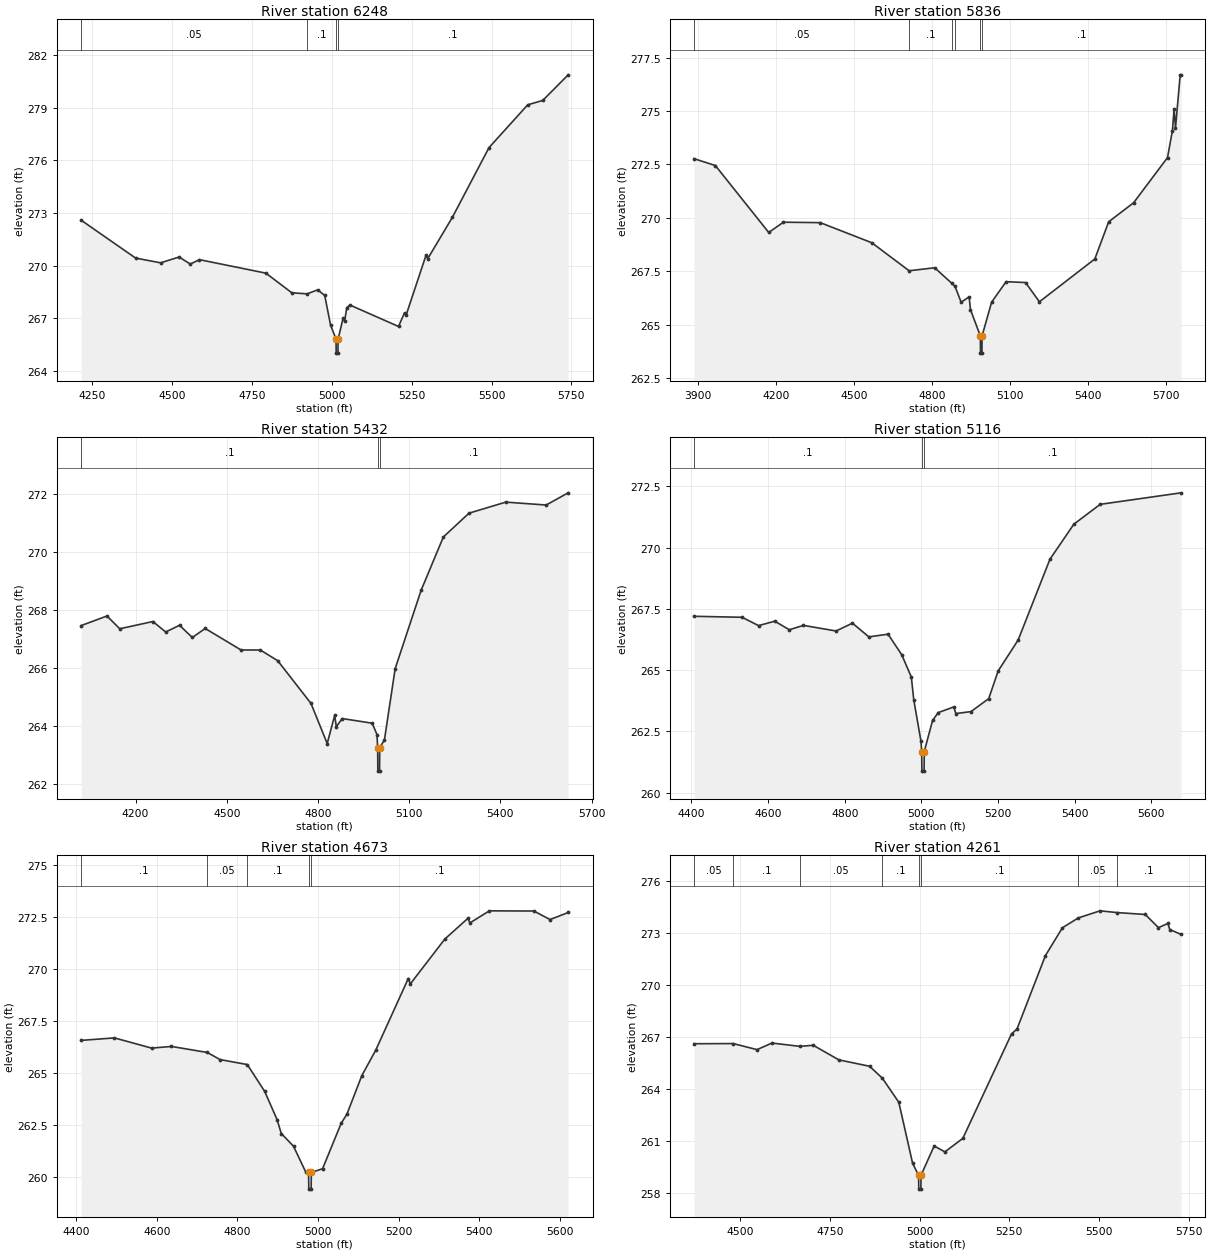
Type RM Length L Ch R = 1,6248,412,412,412
BEGIN DESCRIPTION:
Mapping XS 8b7e8778
END DESCRIPTION:
XS GIS Cut Line= 4
      2120536.94     13395437.72      2120862.48     13395034.06
      2120956.23     13394440.31      2120898.99     13394039.65
#Sta/Elev= 30
  4215.5  272.59  4386.0  270.43  4464.4  270.16  4522.0  270.49  4557.2  270.09
  4585.9  270.34  4793.9  269.57  4874.9  268.45  4923.0  268.39  4955.8  268.62
  4977.9  268.30  4996.3  266.60  5013.3  265.81  5013.8  265.01  5019.3  265.01
  5019.8  265.81  5035.3  267.00  5040.3  266.84  5047.0  267.61  5057.1  267.75
  5208.9  266.53  5227.6  267.31  5232.7  267.18  5295.1  270.60  5300.2  270.39
  5377.6  272.76  5492.1  276.73  5613.3  279.17  5660.4  279.42  5739.9  280.88
#Mann=4,-1,0
  4215.5    0.05       0  4923.0     0.1       0  5013.3    0.07       0
  5019.8     0.1       0
Bank Sta=5013.3,5019.8
Exp/Cntr=0.3,0.1

Type RM Length L Ch R = 1,5836,404,404,404
BEGIN DESCRIPTION:
UNT 003 in La Jarita Watershed 10.0
END DESCRIPTION:
XS GIS Cut Line= 3
      2120529.98     13395555.79      2121173.05     13394895.99
      2121498.75     13394003.71
#Sta/Elev= 30
  3885.5  272.77  3967.4  272.45  4172.5  269.32  4229.0  269.80  4370.5  269.78
  4568.5  268.84  4711.9  267.53  4810.0  267.67  4876.4  266.94  4888.2  266.80
  4911.8  266.06  4942.4  266.31  4947.7  265.71  4985.6  264.48  4986.1  263.68
  4991.6  263.68  4992.1  264.48  5028.7  266.06  5084.5  267.02  5159.2  266.98
  5212.4  266.08  5425.3  268.08  5478.6  269.82  5574.4  270.71  5704.7  272.82
  5723.4  274.08  5730.0  275.10  5735.3  274.21  5753.4  276.69  5756.7  276.69
#Mann=6,-1,0
  3885.5    0.05       0  4711.9     0.1       0  4876.4    0.05       0
  4888.2     0.1       0  4985.6    0.07       0  4992.1     0.1       0
Bank Sta=4985.6,4992.1
Exp/Cntr=0.3,0.1

Type RM Length L Ch R = 1,5432,316,316,316
BEGIN DESCRIPTION:
Mapping XS 8410fbb3
END DESCRIPTION:
XS GIS Cut Line= 3
      2121091.23     13395587.19      2121500.93     13394955.28
      2121806.49     13394163.61
#Sta/Elev= 30
  4021.2  267.47  4106.1  267.80  4148.3  267.36  4257.1  267.61  4299.3  267.25
  4344.7  267.48  4386.9  267.06  4429.2  267.37  4547.1  266.63  4610.4  266.63
  4667.8  266.26  4777.1  264.79  4830.4  263.41  4855.0  264.38  4860.4  263.99
  4879.6  264.27  4978.3  264.11  4994.1  263.72  4996.4  263.26  4996.9  262.46
  5002.6  262.46  5003.1  263.26  5018.7  263.54  5054.0  265.99  5139.1  268.68
  5212.4  270.52  5296.9  271.34  5417.7  271.72  5550.5  271.62  5622.9  272.04
#Mann=3,-1,0
  4021.2     0.1       0  4996.4    0.07       0  5003.1     0.1       0
Bank Sta=4996.4,5003.1
Exp/Cntr=0.3,0.1

Type RM Length L Ch R = 1,5116,443,443,443
BEGIN DESCRIPTION:
Mapping XS c3868aca
END DESCRIPTION:
XS GIS Cut Line= 3
      2121473.17     13395552.46      2121747.46     13394812.92
      2121941.90     13394371.95
#Sta/Elev= 30
  4406.7  267.20  4532.0  267.16  4575.0  266.82  4617.3  267.00  4655.5  266.65
  4692.0  266.83  4777.3  266.60  4820.0  266.92  4862.8  266.36  4912.9  266.47
  4948.6  265.63  4973.7  264.72  4979.9  263.80  4998.7  262.11  5000.7  261.68
  5001.2  260.88  5006.9  260.88  5007.4  261.68  5029.1  262.95  5043.9  263.27
  5084.5  263.50  5089.8  263.23  5129.3  263.31  5175.6  263.84  5200.2  264.97
  5252.3  266.23  5335.3  269.53  5397.7  270.96  5466.4  271.77  5677.4  272.24
#Mann=3,-1,0
  4406.7     0.1       0  5000.7    0.07       0  5007.4     0.1       0
Bank Sta=5000.7,5007.4
Exp/Cntr=0.3,0.1

Type RM Length L Ch R = 1,4673,412,412,412
BEGIN DESCRIPTION:
Mapping XS 951cde9f
END DESCRIPTION:
XS GIS Cut Line= 4
      2121733.57     13395500.42      2121997.46     13395233.06
      2122080.79     13394812.92      2122053.02     13394410.16
#Sta/Elev= 30
  4412.5  266.56  4495.1  266.68  4587.1  266.19  4636.5  266.27  4725.4  265.98
  4756.8  265.64  4824.5  265.40  4867.7  264.11  4898.3  262.76  4908.8  262.09
  4939.1  261.48  4969.7  260.23  4976.5  260.22  4977.0  259.42  4982.8  259.42
  4983.3  260.22  5011.2  260.40  5057.3  262.58  5071.6  263.02  5108.5  264.87
  5143.0  266.09  5223.7  269.53  5228.7  269.27  5314.6  271.43  5371.6  272.42
  5376.6  272.20  5424.9  272.78  5535.2  272.77  5575.3  272.36  5620.2  272.70
#Mann=5,-1,0
  4412.5     0.1       0  4725.4    0.05       0  4824.5     0.1       0
  4976.5    0.07       0  4983.3     0.1       0
Bank Sta=4976.5,4983.3
Exp/Cntr=0.3,0.1

Type RM Length L Ch R = 1,4261,415,415,415
BEGIN DESCRIPTION:
Mapping XS d999beb1
END DESCRIPTION:
XS GIS Cut Line= 4
      2121889.78     13395524.75      2122282.18     13395240.00
      2122271.77     13394844.17      2122119.60     13394391.14
#Sta/Elev= 30
  4370.5  266.62  4479.7  266.63  4546.3  266.28  4588.0  266.66  4665.1  266.47
  4703.2  266.53  4774.4  265.69  4860.3  265.32  4896.0  264.63  4941.8  263.24
  4980.4  259.71  4997.0  259.03  4997.5  258.23  5003.3  258.23  5003.8  259.03
  5040.4  260.72  5070.4  260.38  5120.4  261.16  5256.3  267.19  5271.5  267.47
  5350.9  271.71  5398.1  273.31  5442.5  273.88  5503.2  274.29  5549.9  274.19
  5629.3  274.08  5666.1  273.32  5692.4  273.56  5697.7  273.21  5729.2  272.93
#Mann=8,-1,0
  4370.5    0.05       0  4479.7     0.1       0  4665.1    0.05       0
  4896.0     0.1       0  4997.0    0.07       0  5003.8     0.1       0
  5442.5    0.05       0  5549.9     0.1       0
Bank Sta=4997,5003.8
Exp/Cntr=0.3,0.1

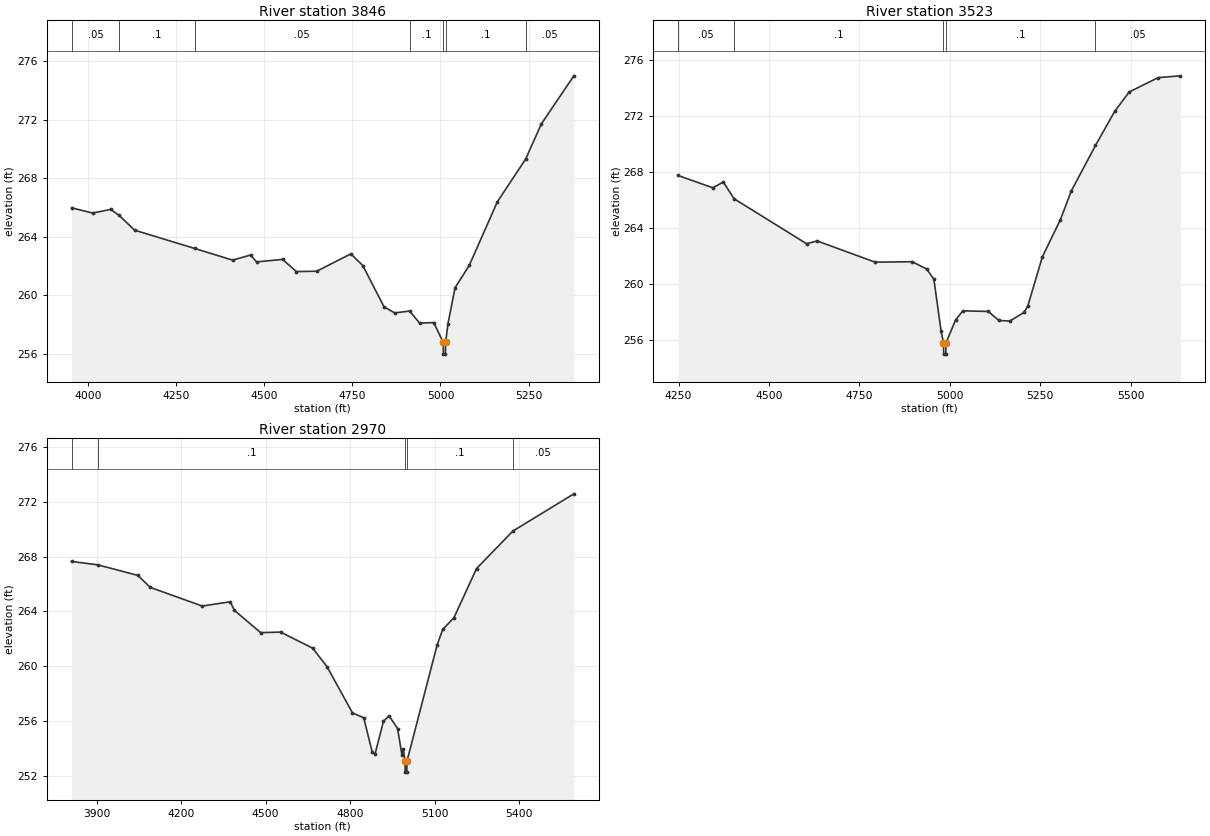
Type RM Length L Ch R = 1,3846,323,323,323
BEGIN DESCRIPTION:
Mapping XS db4ef72d
END DESCRIPTION:
XS GIS Cut Line= 4
      2121969.17     13395577.13      2122575.98     13395288.05
      2122638.48     13394751.59      2122583.79     13394545.87
#Sta/Elev= 30
  3953.3  265.97  4013.0  265.61  4063.9  265.86  4087.6  265.46  4132.0  264.44
  4302.5  263.19  4410.0  262.39  4461.0  262.74  4478.1  262.27  4551.8  262.44
  4591.1  261.61  4648.7  261.63  4745.5  262.82  4779.5  262.02  4839.9  259.19
  4870.1  258.78  4912.7  258.91  4940.6  258.08  4980.9  258.12  5007.7  256.76
  5008.2  255.96  5014.0  255.96  5014.5  256.76  5021.2  258.04  5041.3  260.50
  5081.6  262.03  5161.3  266.38  5241.7  269.31  5286.2  271.71  5378.4  275.00
#Mann=7,-1,0
  3953.3    0.05       0  4087.6     0.1       0  4302.5    0.05       0
  4912.7     0.1       0  5007.7    0.07       0  5014.5     0.1       0
  5241.7    0.05       0
Bank Sta=5007.7,5014.5
Exp/Cntr=0.3,0.1

Type RM Length L Ch R = 1,3523,553,553,553
BEGIN DESCRIPTION:
Mapping XS f3fa896a
END DESCRIPTION:
XS GIS Cut Line= 3
      2122612.45     13395767.17      2122836.39     13395233.36
      2122825.98     13394423.51
#Sta/Elev= 30
  4248.9  267.76  4344.7  266.88  4373.9  267.29  4403.8  266.09  4604.1  262.87
  4633.3  263.07  4793.5  261.55  4896.2  261.58  4936.2  261.06  4956.2  260.33
  4976.2  256.60  4982.8  255.76  4983.3  254.96  4989.1  254.96  4989.6  255.76
  5016.2  257.41  5036.2  258.06  5106.2  258.02  5136.2  257.37  5166.2  257.33
  5206.2  257.96  5216.2  258.43  5256.2  261.93  5306.2  264.60  5336.2  266.65
  5403.1  269.91  5456.2  272.35  5496.2  273.74  5576.2  274.77  5637.7  274.90
#Mann=5,-1,0
  4248.9    0.05       0  4403.8     0.1       0  4982.8    0.07       0
  4989.6     0.1       0  5403.1    0.05       0
Bank Sta=4982.8,4989.6
Exp/Cntr=0.3,0.1

Type RM Length L Ch R = 1,2970,0,0,0
BEGIN DESCRIPTION:
UNT 003 in La Jarita Watershed 8.0
END DESCRIPTION:
XS GIS Cut Line= 3
      2122635.85     13395795.88      2123177.54     13395097.95
      2123154.11     13394199.73
#Sta/Elev= 30
  3811.8  267.64  3905.2  267.39  4047.0  266.62  4090.5  265.75  4275.1  264.39
  4374.7  264.70  4389.1  264.08  4482.4  262.45  4553.0  262.49  4667.0  261.32
  4718.2  259.96  4808.3  256.60  4848.3  256.24  4878.3  253.75  4888.3  253.59
  4918.3  256.00  4938.3  256.38  4968.3  255.46  4983.8  253.54  4988.8  253.97
  4994.9  253.08  4995.4  252.28  5001.2  252.28  5001.7  253.08  5108.4  261.53
  5128.4  262.68  5168.4  263.54  5248.4  267.12  5377.1  269.85  5593.8  272.57
#Mann=5,-1,0
  3811.8    0.05       0  3905.2     0.1       0  4994.9    0.07       0
  5001.7     0.1       0  5377.1    0.05       0
Bank Sta=4994.9,5001.7
Exp/Cntr=0.3,0.1

Chan Stop Cuts=-1