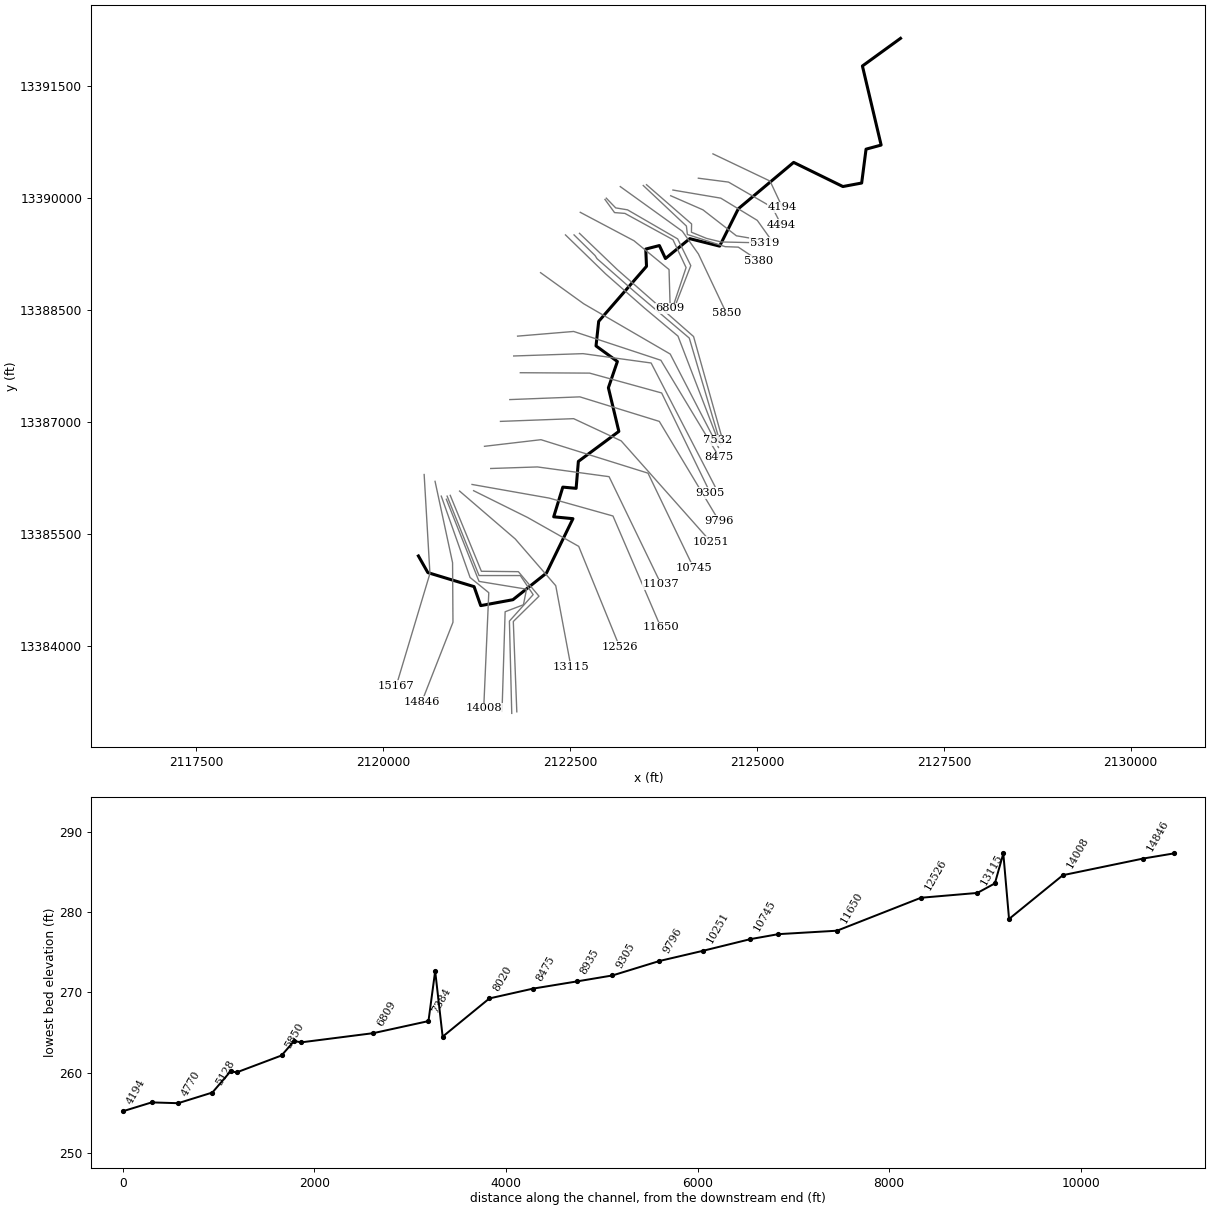
--- UNT 005 in La Jarita Watershed.prj (project) ---

Proj Title=UNT 005 in La Jarita Watershed Base Level Engineering
Current Plan=p01
Default Exp/Contr=0.3,0.1
English Units
Geom File=g01
Flow File=f01
Plan File=p01
BEGIN DESCRIPTION:
UNT 005 in La Jarita Watershed
END DESCRIPTION:

--- UNT 005 in La Jarita Watershed.p01 (plan) ---

Plan Title=Multiple Run
Short Identifier=Multiple
Geom File=g01
Flow File=f01
Subcritical Flow
K Sum by GR= 0
Std Step Tol= 0.01
Critical Tol= 0.01
Num of Std Step Trials= 20
Max Error Tol= 0.3
Flow Tol Ratio= 0.001
Split Flow NTrial= 30
Split Flow Tol= 0.02
Split Flow Ratio= 0.02
Log Output Level= 0
Friction Slope Method= 1
Unsteady Friction Slope Method= 2
Unsteady Bridges Friction Slope Method= 1
Parabolic Critical Depth
Global Vel Dist=  1 , 1 , 1
Global Log Level= 0
CheckData=True
Encroach Param= -1, 0, 0, 0
BEGIN DESCRIPTION:
Multiple Run
END DESCRIPTION:

--- UNT 005 in La Jarita Watershed.f01 (steady flow) ---

Flow Title=Multiple
Number of Profiles=7
Profile Names=10-year,25-year,50-year,1pct_min,100-year,1pct_plu,500-year
River Rch & RM= UNT 005 in La Ja,Reach-1,15167
     186     256     313     192     382     763     579
River Rch & RM= UNT 005 in La Ja,Reach-1,14008
     275     384     476     294     586    1170     904
River Rch & RM= UNT 005 in La Ja,Reach-1,8475
     358     507     633     393     785    1566    1226
Boundary for River Rch & Prof#=UNT 005 in La Ja,Reach-1,1
Up Type=0
Dn Type=3
Dn Slope=0.005
Boundary for River Rch & Prof#=UNT 005 in La Ja,Reach-1,2
Up Type=0
Dn Type=3
Dn Slope=0.005
Boundary for River Rch & Prof#=UNT 005 in La Ja,Reach-1,3
Up Type=0
Dn Type=3
Dn Slope=0.005
Boundary for River Rch & Prof#=UNT 005 in La Ja,Reach-1,4
Up Type=0
Dn Type=3
Dn Slope=0.005
Boundary for River Rch & Prof#=UNT 005 in La Ja,Reach-1,5
Up Type=0
Dn Type=3
Dn Slope=0.005
Boundary for River Rch & Prof#=UNT 005 in La Ja,Reach-1,6
Up Type=0
Dn Type=3
Dn Slope=0.005
Boundary for River Rch & Prof#=UNT 005 in La Ja,Reach-1,7
Up Type=0
Dn Type=3
Dn Slope=0.005

--- UNT 005 in La Jarita Watershed.g01 (geometry) ---

Geom Title=Existing Conditions

River Reach=UNT 005 in La Ja,Reach-1
Reach XY= 30
      2120470.80     13385209.54      2120597.05     13384986.89
      2121215.54     13384799.17      2121304.52     13384545.26
      2121735.70     13384624.53      2122183.42     13384980.38
      2122538.24     13385708.46      2122280.80     13385733.42
      2122402.61     13386130.55      2122580.80     13386114.54
      2122610.80     13386474.54      2123152.39     13386875.99
      2123012.42     13387459.76      2123132.86     13387811.32
      2122847.05     13388019.44      2122882.64     13388348.43
      2123522.40     13389084.54      2123512.30     13389315.35
      2123694.58     13389362.43      2123775.96     13389188.82
      2124100.80     13389454.54      2124500.80     13389354.54
      2124750.80     13389854.54      2125490.68     13390474.79
      2126149.53     13390151.87      2126400.83     13390198.74
      2126459.43     13390651.87      2126661.25     13390706.56
      2126410.80     13391764.54      2126920.80     13392134.54

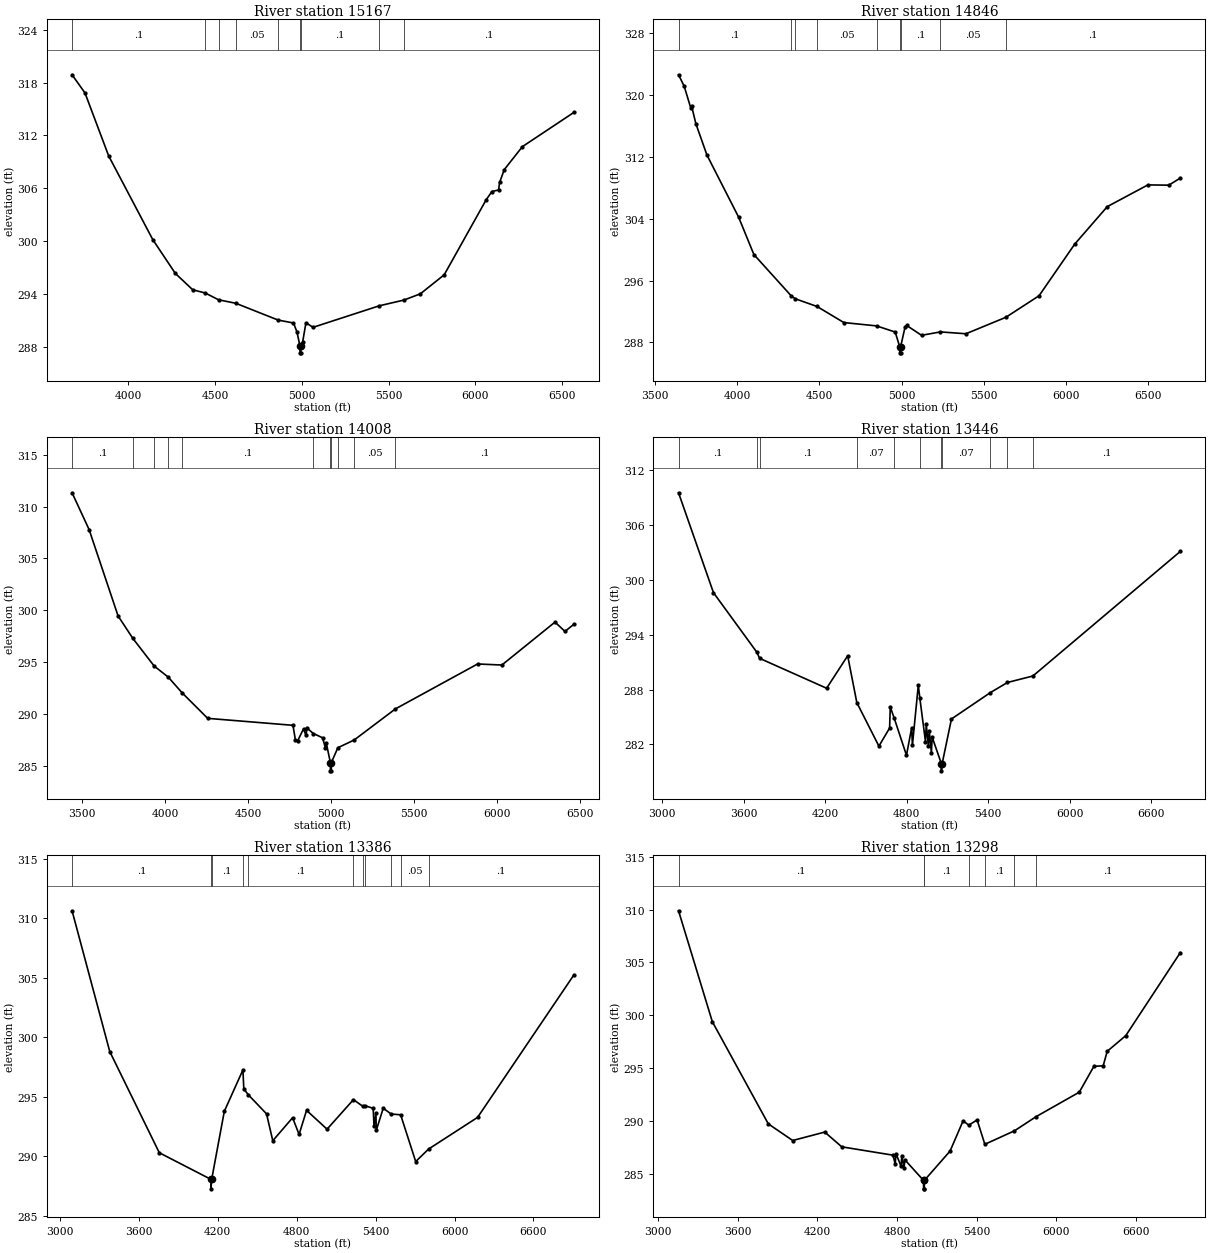
Type RM Length L Ch R = 1,15167,321,321,321
BEGIN DESCRIPTION:
UNT 005 in La Jarita Watershed 27.0
END DESCRIPTION:
XS GIS Cut Line= 3
      2120547.62     13386299.19      2120625.00     13384975.00
      2120175.00     13383475.00
#Sta/Elev= 30
  3675.7  318.89  3750.0  316.83  3886.6  309.67  4140.7  300.16  4270.9  296.31
  4371.1  294.45  4443.7  294.08  4520.0  293.31  4618.6  292.92  4862.8  291.01
  4952.1  290.67  4972.1  289.66  4989.1  288.08  4989.6  287.28  4994.6  287.28
  4995.1  288.08  5004.8  288.51  5023.9  290.70  5064.8  290.18  5447.0  292.63
  5588.7  293.28  5683.4  293.99  5820.8  296.15  6062.7  304.68  6095.8  305.62
  6134.1  305.79  6140.1  306.65  6167.1  308.11  6271.5  310.72  6568.2  314.61
#Mann=9,-1,0
  3675.7     0.1       0  4443.7    0.05       0  4520.0     0.1       0
  4618.6    0.05       0  4862.8     0.1       0  4989.1    0.07       0
  4995.1     0.1       0  5447.0    0.05       0  5588.7     0.1       0
Bank Sta=4989.1,4995.1
Exp/Cntr=0.3,0.1

Type RM Length L Ch R = 1,14846,838,838,838
BEGIN DESCRIPTION:
Mapping XS c44f29dc
END DESCRIPTION:
XS GIS Cut Line= 4
      2120693.53     13386207.85      2120927.89     13385119.36
      2120933.10     13384322.48      2120516.44     13383259.99
#Sta/Elev= 30
  3643.7  322.64  3678.4  321.14  3717.5  318.38  3722.6  318.65  3748.9  316.32
  3816.2  312.26  4008.4  304.24  4101.9  299.37  4329.3  294.01  4354.9  293.63
  4486.2  292.64  4649.1  290.56  4847.7  290.13  4961.5  289.33  4988.5  287.44
  4989.0  286.64  4994.0  286.64  4994.5  287.44  5021.5  290.00  5031.5  290.18
  5121.5  288.91  5236.7  289.35  5391.5  289.11  5634.1  291.24  5836.2  294.03
  6053.2  300.72  6251.1  305.57  6497.9  308.38  6625.4  308.35  6695.3  309.27
#Mann=9,-1,0
  3643.7     0.1       0  4329.3    0.05       0  4354.9     0.1       0
  4486.2    0.05       0  4847.7     0.1       0  4988.5    0.07       0
  4994.5     0.1       0  5236.7    0.05       0  5634.1     0.1       0
Bank Sta=4988.5,4994.5
Exp/Cntr=0.3,0.1

Type RM Length L Ch R = 1,14008,562,562,562
BEGIN DESCRIPTION:
Mapping XS b810e72f
END DESCRIPTION:
XS GIS Cut Line= 4
      2120776.85     13386009.98      2121162.27     13384921.44
      2121412.27     13384718.31      2121344.56     13383171.47
#Sta/Elev= 30
  3438.2  311.32  3540.9  307.78  3715.6  299.47  3804.7  297.31  3933.2  294.65
  4018.5  293.58  4101.3  292.08  4255.8  289.62  4770.0  288.95  4784.4  287.56
  4798.8  287.48  4834.0  288.62  4848.3  287.97  4854.8  288.68  4893.0  288.16
  4948.4  287.75  4965.2  286.80  4970.2  287.29  4995.4  285.37  4995.9  284.57
  5001.0  284.57  5001.5  285.37  5040.4  286.79  5139.3  287.54  5387.8  290.53
  5883.0  294.85  6029.5  294.75  6349.8  298.88  6409.8  297.98  6463.4  298.67
#Mann=11,-1,0
  3438.2     0.1       0  3804.7    0.05       0  3933.2     0.1       0
  4018.5    0.05       0  4101.3     0.1       0  4893.0    0.07       0
  4995.4    0.07       0  5001.5    0.07       0  5040.4     0.1       0
  5139.3    0.05       0  5387.8     0.1       0
Bank Sta=4995.4,5001.5
Exp/Cntr=0.3,0.1

Type RM Length L Ch R = 1,13446,60,60,60
BEGIN DESCRIPTION:
Mapping XS 7848847b
END DESCRIPTION:
XS GIS Cut Line= 6
      2120844.58     13385968.27      2121282.06     13384869.36
      2121917.48     13384765.19      2121875.81     13384556.86
      2121631.02     13384463.11      2121589.36     13383129.89
#Sta/Elev= 30
  3120.2  309.52  3377.4  298.60  3697.8  292.07  3717.2  291.42  4210.8  288.15
  4365.9  291.70  4433.3  286.58  4595.9  281.82  4674.7  283.80  4679.7  286.10
  4708.3  284.89  4799.0  280.82  4837.4  283.85  4842.5  281.90  4886.1  288.49
  4897.6  287.04  4938.9  282.32  4944.6  284.20  4960.6  281.83  4966.4  283.52
  4982.4  281.12  4988.1  282.81  5055.6  279.92  5056.1  279.12  5061.9  279.92
  5130.2  284.79  5417.5  287.68  5542.5  288.78  5730.1  289.49  6815.8  303.11
#Mann=11,-1,0
  3120.2     0.1       0  3697.8    0.05       0  3717.2     0.1       0
  4433.3    0.07       0  4708.3     0.1       0  4897.6    0.07       0
  5055.6    0.07       0  5061.9    0.07       0  5417.5     0.1       0
  5542.5    0.05       0  5730.1     0.1       0
Bank Sta=5055.6,5061.9
Exp/Cntr=0.3,0.1

Type RM Length L Ch R = 1,13386,88,88,88
BEGIN DESCRIPTION:
Mapping XS 6dc26437
END DESCRIPTION:
XS GIS Cut Line= 6
      2120854.98     13386009.96      2121282.06     13384947.48
      2121834.14     13384947.48      2122006.02     13384692.27
      2121688.31     13384338.11      2121719.56     13383103.72
#Sta/Elev= 30
  3094.2  310.62  3380.5  298.80  3757.0  290.30  4148.7  288.07  4149.2  287.27
  4155.0  288.07  4250.9  293.78  4392.1  297.25  4399.2  295.66  4433.9  295.16
  4571.6  293.57  4619.2  291.31  4769.7  293.24  4819.1  291.84  4875.8  293.86
  5031.5  292.28  5232.1  294.76  5303.2  294.20  5317.8  294.26  5382.0  294.03
  5388.3  292.55  5402.9  293.62  5405.2  292.17  5458.3  294.04  5518.9  293.55
  5590.5  293.49  5705.0  289.56  5802.9  290.61  6175.2  293.27  6906.7  305.23
#Mann=11,-1,0
  3094.2     0.1       0  4148.7    0.07       0  4155.0     0.1       0
  4392.1    0.07       0  4433.9     0.1       0  5232.1    0.05       0
  5303.2    0.07       0  5317.8    0.05       0  5518.9     0.1       0
  5590.5    0.05       0  5802.9     0.1       0
Bank Sta=4148.7,4155
Exp/Cntr=0.3,0.1

Type RM Length L Ch R = 1,13298,183,183,183
BEGIN DESCRIPTION:
Mapping XS e72b8bc2
END DESCRIPTION:
XS GIS Cut Line= 6
      2120896.63     13386020.44      2121313.31     13385004.77
      2121808.10     13384999.56      2122084.14     13384671.44
      2121740.39     13384332.90      2121787.27     13383124.54
#Sta/Elev= 30
  3155.0  309.90  3409.5  299.39  3831.0  289.71  4014.8  288.13  4256.2  288.93
  4384.6  287.53  4770.5  286.74  4787.0  285.90  4792.7  286.89  4831.4  285.68
  4837.0  286.70  4853.6  285.50  4859.2  286.31  5000.3  284.35  5000.8  283.55
  5006.1  283.55  5006.6  284.35  5200.3  287.13  5298.6  290.00  5341.0  289.58
  5404.0  290.08  5462.2  287.77  5685.5  289.05  5849.5  290.40  6173.6  292.71
  6283.6  295.16  6353.7  295.21  6383.7  296.58  6523.8  298.07  6934.6  305.94
#Mann=7,-1,0
  3155.0     0.1       0  5000.3    0.07       0  5006.6     0.1       0
  5341.0    0.05       0  5462.2     0.1       0  5685.5    0.05       0
  5849.5     0.1       0
Bank Sta=5000.3,5006.6
Exp/Cntr=0.3,0.1

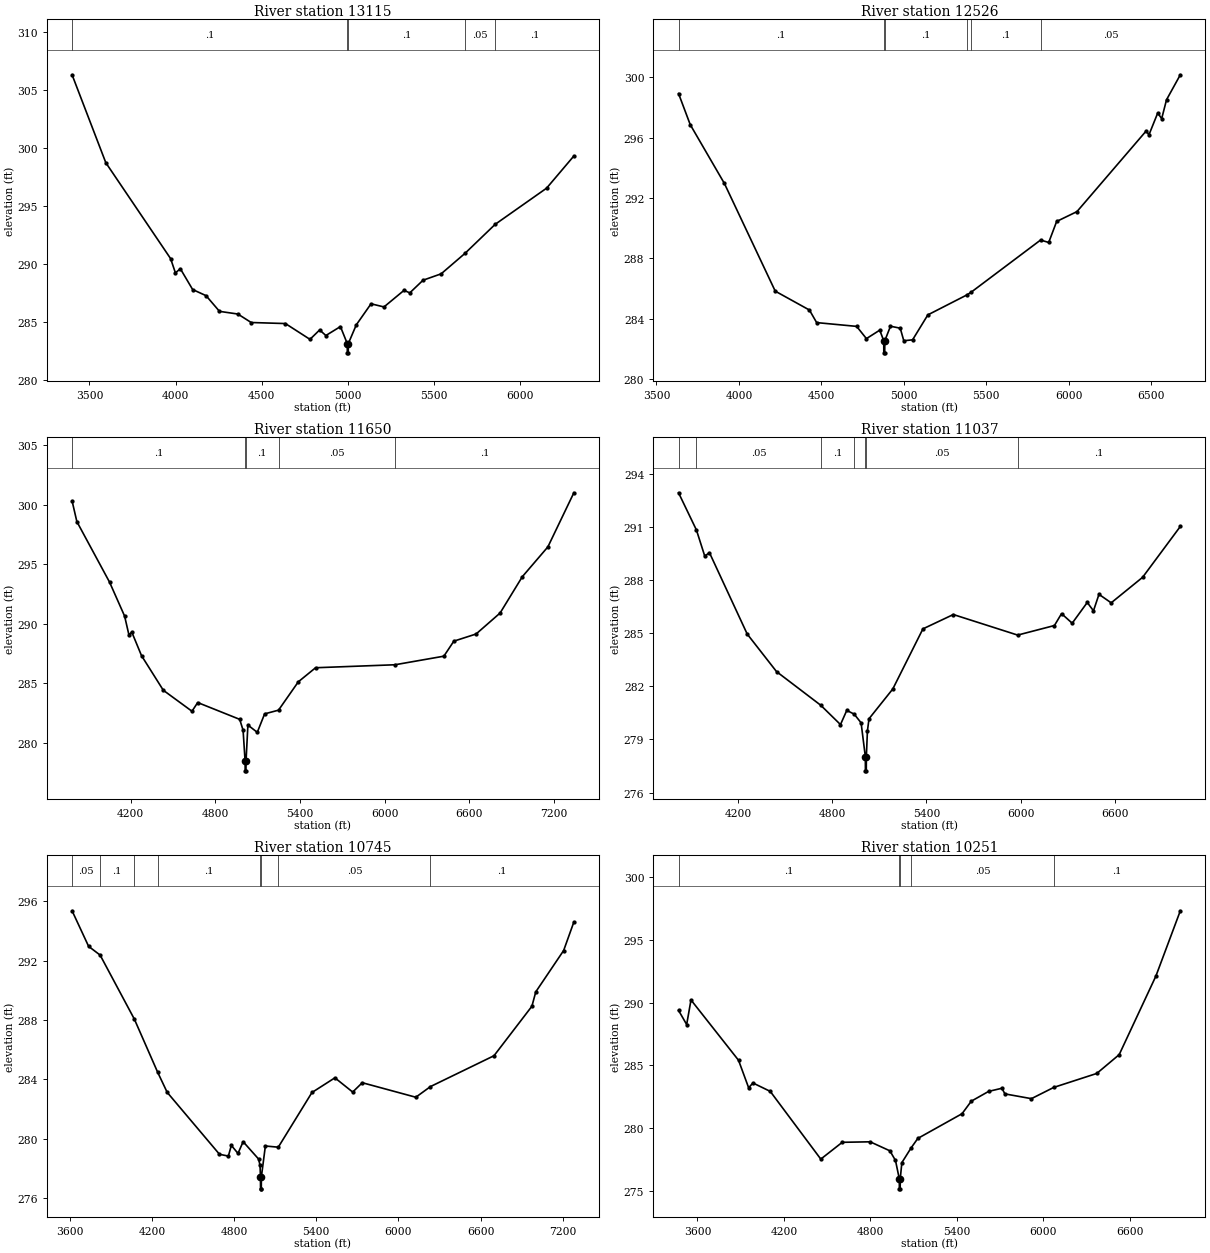
Type RM Length L Ch R = 1,13115,589,589,589
BEGIN DESCRIPTION:
Mapping XS 774a2820
END DESCRIPTION:
XS GIS Cut Line= 4
      2121021.63     13386077.70      2121766.44     13385437.06
      2122308.10     13384812.06      2122511.10     13383729.41
#Sta/Elev= 30
  3399.6  306.29  3595.4  298.72  3971.2  290.47  3999.2  289.24  4027.7  289.60
  4099.0  287.81  4176.9  287.28  4254.8  285.93  4361.3  285.70  4438.8  284.97
  4637.3  284.88  4779.8  283.52  4835.8  284.33  4871.9  283.85  4956.4  284.62
  4996.0  283.16  4996.5  282.36  5001.8  282.36  5002.3  283.16  5048.5  284.77
  5134.0  286.58  5209.1  286.31  5325.5  287.74  5358.7  287.52  5435.7  288.61
  5540.8  289.16  5679.0  290.92  5854.2  293.42  6152.3  296.53  6310.6  299.30
#Mann=5,-1,0
  3399.6     0.1       0  4996.0    0.07       0  5002.3     0.1       0
  5679.0    0.05       0  5854.2     0.1       0
Bank Sta=4996,5002.3
Exp/Cntr=0.3,0.1

Type RM Length L Ch R = 1,12526,876,876,876
BEGIN DESCRIPTION:
Mapping XS a05d9ac7
END DESCRIPTION:
XS GIS Cut Line= 4
      2121209.14     13386082.90      2121933.10     13385723.52
      2122615.39     13385338.11      2123162.25     13383994.40
#Sta/Elev= 30
  3633.9  298.91  3704.9  296.85  3912.1  292.96  4220.3  285.84  4427.6  284.59
  4471.3  283.76  4713.9  283.51  4773.1  282.70  4854.0  283.26  4878.1  282.56
  4878.6  281.76  4884.1  281.76  4884.6  282.56  4919.0  283.52  4978.2  283.39
  4999.8  282.56  5053.0  282.62  5145.6  284.27  5384.1  285.60  5409.4  285.78
  5829.1  289.22  5878.5  289.06  5926.6  290.45  6049.7  291.10  6470.7  296.45
  6485.9  296.17  6539.4  297.62  6563.5  297.25  6592.9  298.50  6676.5  300.15
#Mann=6,-1,0
  3633.9     0.1       0  4878.1    0.07       0  4884.6     0.1       0
  5384.1    0.05       0  5409.4     0.1       0  5829.1    0.05       0
Bank Sta=4878.1,4884.6
Exp/Cntr=0.3,0.1

Type RM Length L Ch R = 1,11650,613,613,613
BEGIN DESCRIPTION:
Mapping XS 9dad093d
END DESCRIPTION:
XS GIS Cut Line= 4
      2121188.31     13386166.23      2122219.56     13385983.94
      2123073.73     13385744.36      2123714.36     13384254.74
#Sta/Elev= 30
  3785.3  300.31  3819.3  298.57  4051.0  293.49  4157.7  290.64  4188.1  289.07
  4208.5  289.30  4277.6  287.32  4431.9  284.42  4635.0  282.66  4675.6  283.39
  4973.2  281.98  4997.2  281.07  5011.5  278.46  5012.0  277.66  5017.5  277.66
  5018.0  278.46  5031.3  281.50  5097.8  280.89  5149.8  282.44  5248.2  282.75
  5388.6  285.13  5510.9  286.31  6073.6  286.56  6420.0  287.28  6490.6  288.54
  6648.2  289.14  6818.4  290.90  6976.0  293.95  7157.1  296.45  7341.2  300.99
#Mann=5,-1,0
  3785.3     0.1       0  5011.5    0.07       0  5018.0     0.1       0
  5248.2    0.05       0  6073.6     0.1       0
Bank Sta=5011.5,5018
Exp/Cntr=0.3,0.1

Type RM Length L Ch R = 1,11037,292,292,292
BEGIN DESCRIPTION:
Mapping XS 210a9a74
END DESCRIPTION:
XS GIS Cut Line= 4
      2121438.28     13386379.77      2122063.31     13386400.61
      2123021.64     13386270.40      2123719.01     13384828.84
#Sta/Elev= 30
  3822.1  292.92  3936.0  290.82  3988.9  289.35  4018.9  289.54  4259.1  284.95
  4445.8  282.83  4727.4  280.93  4852.9  279.84  4892.9  280.64  4940.1  280.43
  4984.1  279.94  5011.1  278.03  5011.6  277.23  5017.1  277.23  5017.6  278.03
  5024.4  279.48  5034.5  280.17  5185.9  281.85  5377.6  285.24  5571.1  286.05
  5980.6  284.89  6214.7  285.43  6259.9  286.10  6327.7  285.56  6423.6  286.73
  6463.2  286.26  6498.2  287.19  6575.9  286.71  6775.9  288.15  7016.0  291.02
#Mann=7,-1,0
  3822.1     0.1       0  3936.0    0.05       0  4727.4     0.1       0
  4940.1    0.05       0  5011.1    0.03       0  5017.6    0.05       0
  5980.6     0.1       0
Bank Sta=5011.1,5017.6
Exp/Cntr=0.3,0.1

Type RM Length L Ch R = 1,10745,494,494,494
BEGIN DESCRIPTION:
Mapping XS 8816bee9
END DESCRIPTION:
XS GIS Cut Line= 4
      2121354.93     13386676.64      2122110.19     13386765.19
      2123542.48     13386317.27      2124151.85     13385051.66
#Sta/Elev= 30
  3616.0  295.37  3736.9  292.97  3820.9  292.38  4071.0  288.06  4241.6  284.47
  4310.8  283.12  4693.0  278.94  4757.9  278.82  4779.6  279.54  4828.1  279.00
  4865.8  279.79  4978.7  278.62  4989.2  278.19  4992.3  277.41  4992.8  276.61
  4998.4  276.61  4998.9  277.41  5028.1  279.50  5122.5  279.42  5368.5  283.11
  5536.1  284.10  5666.0  283.14  5736.1  283.77  6127.2  282.79  6234.4  283.51
  6698.3  285.59  6975.4  288.93  7003.6  289.90  7207.2  292.69  7281.8  294.61
#Mann=8,-1,0
  3616.0    0.05       0  3820.9     0.1       0  4071.0    0.05       0
  4241.6     0.1       0  4992.3    0.07       0  4998.9     0.1       0
  5122.5    0.05       0  6234.4     0.1       0
Bank Sta=4992.3,4998.9
Exp/Cntr=0.3,0.1

Type RM Length L Ch R = 1,10251,455,455,455
BEGIN DESCRIPTION:
Mapping XS ef81140a
END DESCRIPTION:
XS GIS Cut Line= 4
      2121568.57     13387009.98      2122547.69     13387046.44
      2123183.10     13386749.56      2124380.54     13385401.14
#Sta/Elev= 30
  3468.4  289.39  3524.9  288.26  3554.9  290.22  3885.1  285.41  3955.2  283.22
  3985.2  283.60  4105.3  282.93  4456.3  277.53  4605.2  278.87  4799.1  278.91
  4936.2  278.19  4975.0  277.42  5001.4  275.96  5001.9  275.16  5007.5  275.16
  5008.0  275.96  5019.2  277.25  5083.2  278.42  5130.0  279.18  5437.1  281.15
  5501.5  282.15  5621.9  282.93  5713.9  283.18  5734.8  282.73  5918.8  282.35
  6074.6  283.25  6372.7  284.36  6528.4  285.86  6783.5  292.13  6952.9  297.33
#Mann=5,-1,0
  3468.4     0.1       0  5001.4    0.07       0  5008.0     0.1       0
  5083.2    0.05       0  6074.6     0.1       0
Bank Sta=5001.4,5008
Exp/Cntr=0.3,0.1

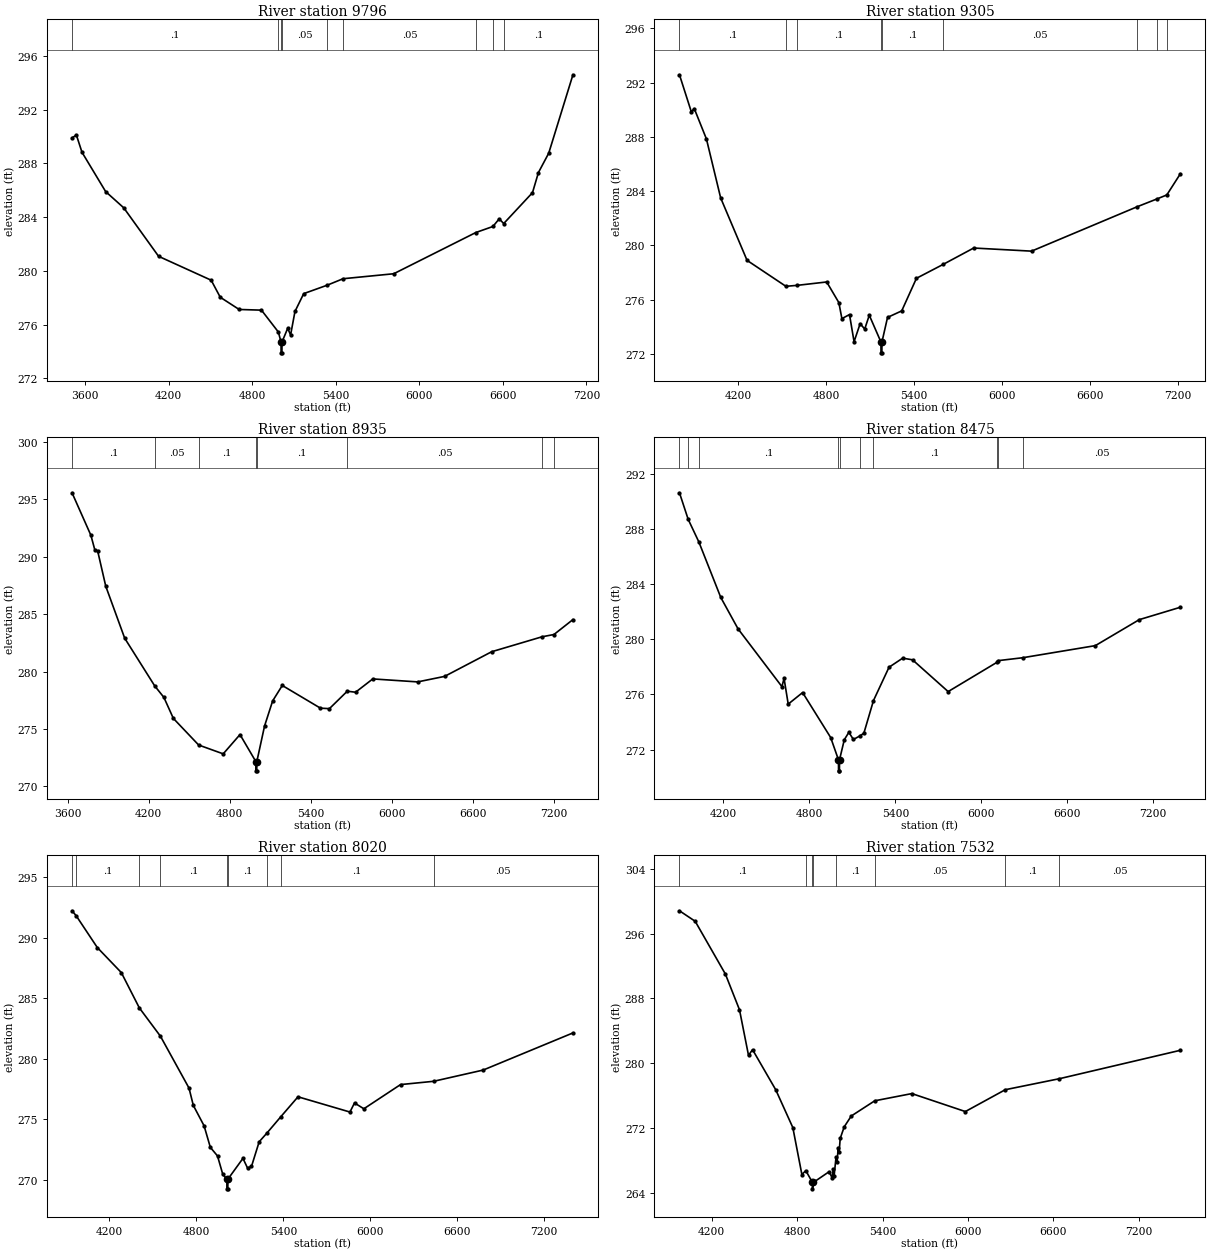
Type RM Length L Ch R = 1,9796,491,491,491
BEGIN DESCRIPTION:
Mapping XS bb854da6
END DESCRIPTION:
XS GIS Cut Line= 4
      2121693.55     13387301.65      2122631.02     13387338.11
      2123693.52     13387009.98      2124490.22     13385682.14
#Sta/Elev= 30
  3505.0  289.90  3536.5  290.11  3576.5  288.83  3746.6  285.90  3876.7  284.69
  4126.9  281.08  4504.7  279.30  4570.0  278.03  4705.8  277.12  4866.0  277.07
  4987.5  275.44  5006.6  274.69  5007.1  273.89  5013.0  273.89  5013.5  274.69
  5054.4  275.72  5075.3  275.22  5106.7  276.97  5169.5  278.30  5338.7  278.93
  5452.3  279.41  5816.1  279.78  6406.0  282.85  6528.7  283.30  6574.1  283.87
  6606.4  283.52  6813.2  285.82  6855.9  287.32  6929.8  288.76  7103.7  294.60
#Mann=9,-1,0
  3505.0     0.1       0  4987.5    0.05       0  5006.6    0.03       0
  5013.5    0.05       0  5338.7     0.1       0  5452.3    0.05       0
  6406.0     0.1       0  6528.7    0.05       0  6606.4     0.1       0
Bank Sta=5006.6,5013.5
Exp/Cntr=0.3,0.1

Type RM Length L Ch R = 1,9305,370,370,370
BEGIN DESCRIPTION:
Mapping XS 7d84df9c
END DESCRIPTION:
XS GIS Cut Line= 4
      2121834.10     13387661.02      2122761.23     13387655.81
      2123724.77     13387390.19      2124375.81     13386051.65
#Sta/Elev= 30
  3800.6  292.57  3881.5  289.84  3901.5  290.08  3984.5  287.84  4081.5  283.50
  4261.5  278.90  4526.3  276.99  4602.9  277.06  4804.3  277.31  4887.3  275.79
  4908.0  274.61  4959.9  274.91  4991.0  272.91  5032.5  274.24  5063.6  273.84
  5094.7  274.86  5174.2  272.89  5174.7  272.09  5180.6  272.09  5181.1  272.89
  5219.2  274.70  5315.9  275.18  5416.3  277.58  5597.7  278.60  5806.5  279.81
  6201.0  279.58  6921.1  282.85  7057.2  283.43  7123.3  283.72  7215.7  285.28
#Mann=9,-1,0
  3800.6     0.1       0  4526.3    0.05       0  4602.9     0.1       0
  5174.2    0.07       0  5181.1     0.1       0  5597.7    0.05       0
  6921.1     0.1       0  7057.2    0.05       0  7123.3     0.1       0
Bank Sta=5174.2,5181.1
Exp/Cntr=0.3,0.1

Type RM Length L Ch R = 1,8935,460,460,460
BEGIN DESCRIPTION:
Mapping XS 55cb03fe
END DESCRIPTION:
XS GIS Cut Line= 4
      2121745.59     13387884.98      2122672.69     13387916.23
      2123584.14     13387791.23      2124438.30     13386140.21
#Sta/Elev= 30
  3632.9  295.58  3772.4  291.88  3802.4  290.57  3822.4  290.52  3882.5  287.44
  4022.5  282.91  4244.8  278.75  4312.7  277.75  4382.7  275.92  4569.9  273.60
  4751.6  272.83  4875.8  274.51  4993.4  272.15  4993.9  271.35  4999.8  271.35
  5000.3  272.15  5057.4  275.25  5117.3  277.44  5188.7  278.79  5471.3  276.81
  5537.5  276.77  5669.7  278.29  5731.1  278.20  5858.3  279.36  6190.4  279.10
  6389.7  279.58  6738.3  281.73  7110.5  283.03  7199.1  283.23  7339.4  284.53
#Mann=8,-1,0
  3632.9     0.1       0  4244.8    0.05       0  4569.9     0.1       0
  4993.4    0.07       0  5000.3     0.1       0  5669.7    0.05       0
  7110.5     0.1       0  7199.1    0.05       0
Bank Sta=4993.4,5000.3
Exp/Cntr=0.3,0.1

Type RM Length L Ch R = 1,8475,455,455,455
BEGIN DESCRIPTION:
Mapping XS 296dd81b
END DESCRIPTION:
XS GIS Cut Line= 4
      2121797.64     13388150.60      2122547.69     13388213.11
      2123714.35     13387827.69      2124495.58     13386530.84
#Sta/Elev= 30
  3893.6  290.66  3954.4  288.73  4029.2  287.08  4182.0  283.05  4302.4  280.77
  4608.6  276.57  4623.5  277.17  4652.4  275.30  4752.9  276.14  4948.8  272.87
  5003.1  271.25  5003.7  270.45  5009.9  270.45  5010.4  271.25  5043.8  272.71
  5075.5  273.25  5107.3  272.73  5151.2  272.98  5180.5  273.19  5247.5  275.56
  5355.9  277.98  5451.1  278.64  5519.8  278.52  5768.5  276.21  6107.8  278.33
  6117.8  278.46  6288.1  278.67  6795.6  279.55  7102.4  281.44  7388.9  282.34
#Mann=10,-1,0
  3893.6     0.1       0  3954.4    0.05       0  4029.2     0.1       0
  5003.1    0.07       0  5010.4     0.1       0  5151.2    0.05       0
  5247.5     0.1       0  6107.8    0.05       0  6117.8     0.1       0
  6288.1    0.05       0
Bank Sta=5003.1,5010.4
Exp/Cntr=0.3,0.1

Type RM Length L Ch R = 1,8020,488,488,488
BEGIN DESCRIPTION:
Mapping XS 18dbbcd4
END DESCRIPTION:
XS GIS Cut Line= 4
      2122104.97     13388999.57      2122683.10     13388582.90
      2123839.35     13387911.02      2124485.18     13386661.03
#Sta/Elev= 30
  3941.6  292.22  3969.7  291.82  4116.1  289.18  4281.8  287.11  4406.2  284.19
  4551.7  281.85  4749.0  277.56  4778.6  276.13  4853.0  274.44  4896.2  272.66
  4945.6  271.95  4982.3  270.42  5010.1  270.03  5010.6  269.23  5016.8  269.23
  5017.4  270.03  5121.3  271.75  5152.8  270.95  5180.1  271.08  5233.1  273.12
  5287.3  273.85  5383.8  275.21  5501.2  276.84  5859.6  275.58  5891.1  276.33
  5955.7  275.85  6208.7  277.85  6436.5  278.12  6778.9  279.05  7398.5  282.12
#Mann=9,-1,0
  3941.6    0.05       0  3969.7     0.1       0  4406.2    0.05       0
  4551.7     0.1       0  5010.1    0.07       0  5017.4     0.1       0
  5287.3    0.05       0  5383.8     0.1       0  6436.5    0.05       0
Bank Sta=5010.1,5017.4
Exp/Cntr=0.3,0.1

Type RM Length L Ch R = 1,7532,78,78,78
BEGIN DESCRIPTION:
Mapping XS 46c52b27
END DESCRIPTION:
XS GIS Cut Line= 5
      2122438.29     13389504.80      2122974.77     13388983.94
      2123495.60     13388525.61      2123943.52     13388150.61
      2124479.99     13386754.74
#Sta/Elev= 30
  3972.7  298.83  4083.3  297.53  4295.5  291.01  4394.6  286.60  4458.1  280.96
  4486.4  281.67  4649.2  276.72  4769.6  272.04  4833.2  266.24  4860.8  266.72
  4907.3  265.27  4907.8  264.47  4914.7  265.27  5024.8  266.59  5045.7  265.83
  5053.3  266.89  5059.9  266.08  5073.6  268.44  5080.8  267.80  5088.4  269.57
  5095.0  268.97  5102.6  270.70  5131.1  272.14  5180.4  273.47  5345.6  275.35
  5606.2  276.24  5982.3  274.02  6263.1  276.72  6643.6  278.08  7493.8  281.59
#Mann=8,-1,0
  3972.7     0.1       0  4860.8    0.07       0  4907.3    0.07       0
  4914.7    0.07       0  5073.6     0.1       0  5345.6    0.05       0
  6263.1     0.1       0  6643.6    0.05       0
Bank Sta=4907.3,4914.7
Exp/Cntr=0.3,0.1

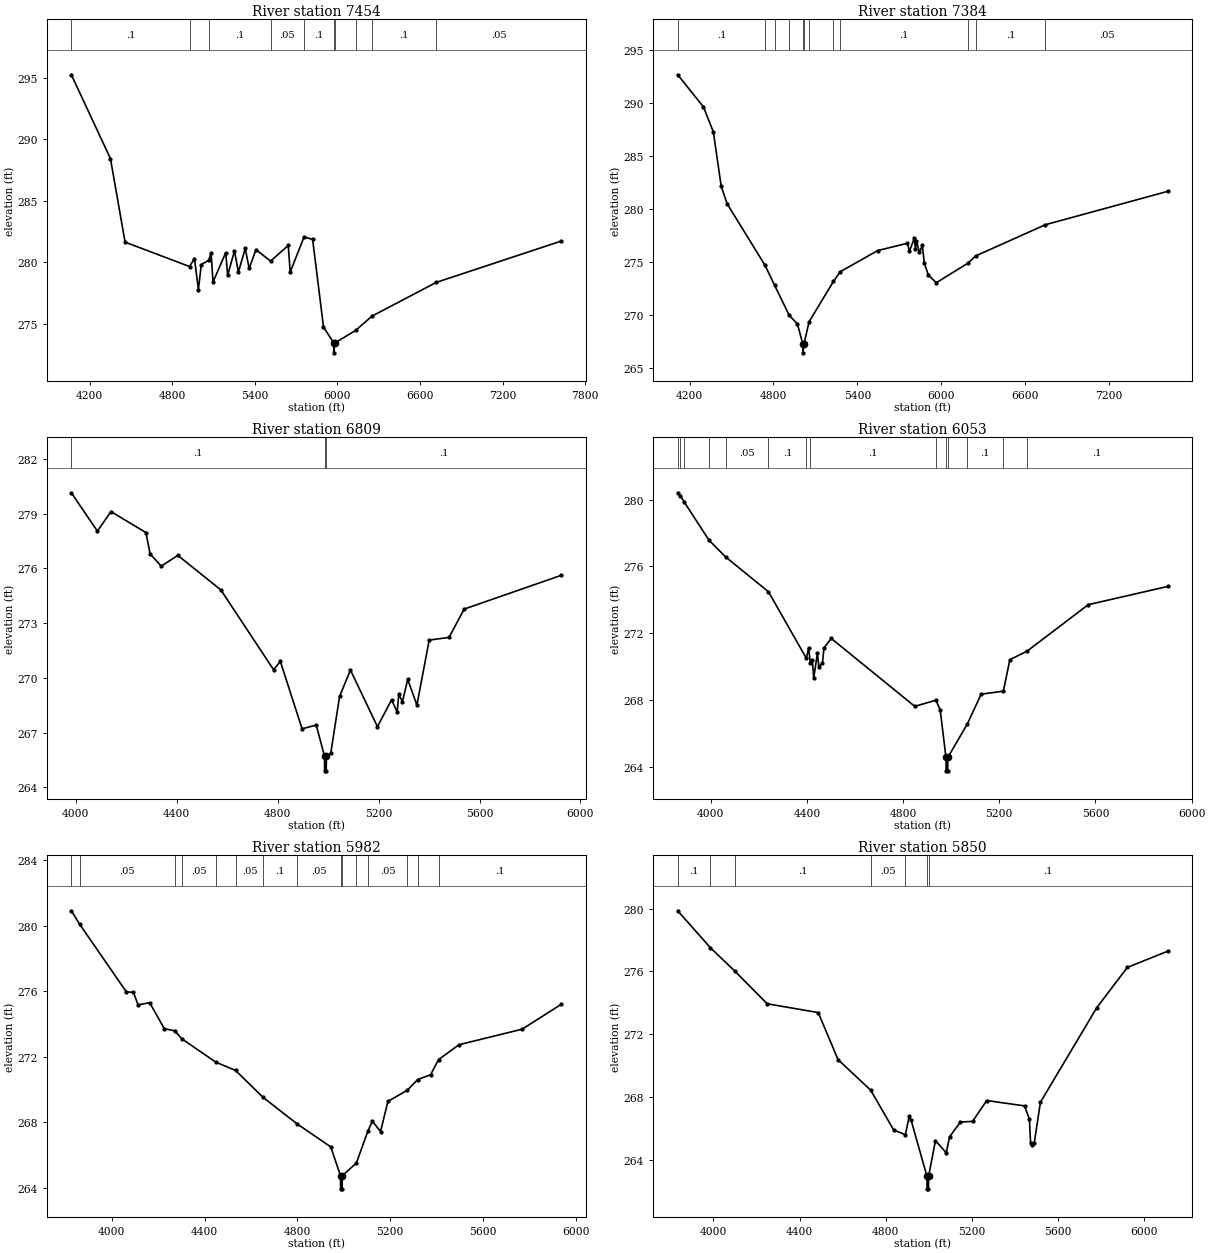
Type RM Length L Ch R = 1,7454,70,70,70
BEGIN DESCRIPTION:
Mapping XS eca236e6
END DESCRIPTION:
XS GIS Cut Line= 6
      2122552.90     13389504.77      2122834.14     13389228.73
      2122860.19     13389187.06      2123375.81     13388733.94
      2124094.56     13388124.56      2124516.07     13386698.72
#Sta/Elev= 30
  4068.1  295.25  4352.2  288.43  4458.4  281.64  4926.4  279.66  4962.5  280.30
  4991.0  277.79  5011.9  279.82  5066.4  280.16  5083.0  280.77  5097.2  278.40
  5189.3  280.78  5203.5  278.94  5253.0  280.93  5281.7  279.20  5331.2  281.13
  5359.8  279.50  5409.3  281.03  5515.1  280.10  5643.7  281.37  5658.0  279.21
  5758.6  282.07  5820.8  281.86  5899.7  274.74  5973.8  273.44  5974.3  272.64
  5981.2  273.44  6132.8  274.46  6252.5  275.63  6719.3  278.37  7627.0  281.73
#Mann=10,-1,0
  4068.1     0.1       0  4926.4    0.07       0  5066.4     0.1       0
  5515.1    0.05       0  5758.6     0.1       0  5973.8    0.07       0
  5981.2     0.1       0  6132.8    0.05       0  6252.5     0.1       0
  6719.3    0.05       0
Bank Sta=5973.8,5981.2
Exp/Cntr=0.3,0.1

Type RM Length L Ch R = 1,7384,575,575,575
BEGIN DESCRIPTION:
Mapping XS 7fa5ae3d
END DESCRIPTION:
XS GIS Cut Line= 4
      2122625.83     13389525.59      2123131.02     13389041.23
      2124151.85     13388145.40      2124542.48     13386754.76
#Sta/Elev= 30
  4115.7  292.67  4299.4  289.64  4370.1  287.29  4426.7  282.13  4469.2  280.48
  4739.7  274.68  4808.6  272.78  4912.9  269.95  4971.5  269.14  5010.5  267.21
  5011.0  266.41  5017.9  267.21  5054.5  269.34  5228.7  273.15  5277.4  274.07
  5545.6  276.07  5758.1  276.76  5772.4  276.01  5807.5  277.25  5815.1  276.18
  5821.7  277.01  5843.5  275.89  5864.4  276.57  5878.6  274.89  5907.1  273.77
  5964.0  273.03  6188.1  274.86  6246.9  275.57  6744.4  278.51  7618.2  281.66
#Mann=12,-1,0
  4115.7     0.1       0  4739.7    0.12       0  4808.6     0.1       0
  4912.9    0.07       0  5010.5    0.07       0  5017.9    0.07       0
  5054.5     0.1       0  5228.7    0.12       0  5277.4     0.1       0
  6188.1    0.05       0  6246.9     0.1       0  6744.4    0.05       0
Bank Sta=5010.5,5017.9
Exp/Cntr=0.3,0.1

Type RM Length L Ch R = 1,6809,756,756,756
BEGIN DESCRIPTION:
Mapping XS 0fcab87a
END DESCRIPTION:
XS GIS Cut Line= 4
      2122636.23     13389806.86      2123354.98     13389426.65
      2123823.73     13389041.23      2123839.35     13388520.44
#Sta/Elev= 30
  3982.9  280.14  4086.0  278.04  4139.9  279.11  4278.4  277.96  4294.8  276.80
  4338.8  276.12  4404.8  276.71  4575.2  274.82  4784.0  270.45  4811.0  270.90
  4897.0  267.21  4953.0  267.42  4985.9  265.71  4986.4  264.91  4992.7  264.91
  4993.3  265.71  5010.4  265.86  5045.6  268.99  5088.6  270.43  5195.5  267.33
  5251.5  268.80  5273.7  268.13  5280.2  269.11  5294.5  268.69  5315.4  269.92
  5351.9  268.51  5400.5  272.07  5479.1  272.22  5539.2  273.77  5923.9  275.62
#Mann=3,-1,0
  3982.9     0.1       0  4985.9    0.07       0  4993.3     0.1       0
Bank Sta=4985.9,4993.3
Exp/Cntr=0.3,0.1

Type RM Length L Ch R = 1,6053,71,71,71
BEGIN DESCRIPTION:
Mapping XS cf24ea3f
END DESCRIPTION:
XS GIS Cut Line= 6
      2122966.73     13389979.04      2123094.73     13389803.30
      2123233.62     13389792.45      2123875.98     13389440.88
      2124051.77     13389067.62      2123882.51     13388562.01
#Sta/Elev= 30
  3863.2  280.41  3874.3  280.23  3889.7  279.87  3993.7  277.56  4063.9  276.55
  4240.6  274.48  4398.0  270.50  4407.5  271.12  4414.5  270.22  4422.7  270.40
  4428.7  269.31  4443.9  270.81  4449.8  269.99  4465.0  270.22  4471.3  271.12
  4501.3  271.69  4848.9  267.62  4936.5  267.99  4954.4  267.41  4978.6  264.56
  4979.2  263.76  4985.6  263.76  4986.2  264.56  5067.1  266.56  5124.7  268.35
  5217.0  268.53  5244.2  270.42  5315.2  270.92  5570.1  273.71  5900.2  274.80
#Mann=14,-1,0
  3863.2    0.05       0  3874.3     0.1       0  3889.7    0.05       0
  3993.7     0.1       0  4063.9    0.05       0  4240.6     0.1       0
  4398.0    0.05       0  4414.5     0.1       0  4936.5    0.05       0
  4978.6    0.04       0  4986.2    0.05       0  5067.1     0.1       0
  5217.0    0.05       0  5315.2     0.1       0
Bank Sta=4978.6,4986.2
Exp/Cntr=0.3,0.1

Type RM Length L Ch R = 1,5982,132,132,132
BEGIN DESCRIPTION:
Mapping XS 67038959
END DESCRIPTION:
XS GIS Cut Line= 6
      2122984.07     13389996.43      2123109.93     13389866.23
      2123268.35     13389840.19      2123938.92     13389451.73
      2124114.70     13389093.66      2123899.93     13388540.47
#Sta/Elev= 30
  3826.2  280.92  3861.3  280.11  4063.1  275.97  4093.5  275.94  4113.8  275.17
  4163.6  275.31  4226.6  273.72  4271.7  273.59  4301.4  273.11  4447.8  271.68
  4533.5  271.17  4652.6  269.52  4797.3  267.92  4943.7  266.50  4985.6  264.74
  4986.2  263.94  4992.6  263.94  4993.2  264.74  5054.1  265.52  5103.9  267.48
  5122.7  268.07  5158.0  267.44  5189.8  269.28  5273.1  269.96  5318.1  270.61
  5373.9  270.91  5407.8  271.83  5495.8  272.74  5768.0  273.69  5936.6  275.21
#Mann=15,-1,0
  3826.2     0.1       0  3861.3    0.05       0  4271.7     0.1       0
  4301.4    0.05       0  4447.8     0.1       0  4533.5    0.05       0
  4652.6     0.1       0  4797.3    0.05       0  4985.6    0.04       0
  4993.2    0.05       0  5054.1     0.1       0  5103.9    0.05       0
  5273.1     0.1       0  5318.1    0.05       0  5407.8     0.1       0
Bank Sta=4985.6,4993.2
Exp/Cntr=0.3,0.1

Type RM Length L Ch R = 1,5850,470,470,470
BEGIN DESCRIPTION:
Mapping XS a0c04121
END DESCRIPTION:
XS GIS Cut Line= 4
      2123171.35     13390151.14      2124001.85     13389553.73
      2124216.70     13389249.91      2124592.14     13388455.63
#Sta/Elev= 30
  3834.8  279.86  3986.6  277.50  4100.2  276.01  4249.9  273.93  4486.8  273.37
  4578.8  270.37  4730.4  268.42  4837.1  265.88  4891.3  265.58  4909.0  266.75
  4917.5  266.53  4991.3  262.93  4992.0  262.13  4998.4  262.13  4999.0  262.93
  5030.9  265.20  5081.3  264.43  5096.1  265.44  5146.6  266.39  5203.2  266.43
  5268.6  267.76  5444.2  267.42  5466.9  266.56  5472.4  265.05  5478.7  264.92
  5489.7  265.08  5518.0  267.65  5779.4  273.68  5921.5  276.25  6108.5  277.28
#Mann=7,-1,0
  3834.8     0.1       0  3986.6    0.05       0  4100.2     0.1       0
  4730.4    0.05       0  4891.3     0.1       0  4991.3    0.07       0
  4999.0     0.1       0
Bank Sta=4991.3,4999
Exp/Cntr=0.3,0.1

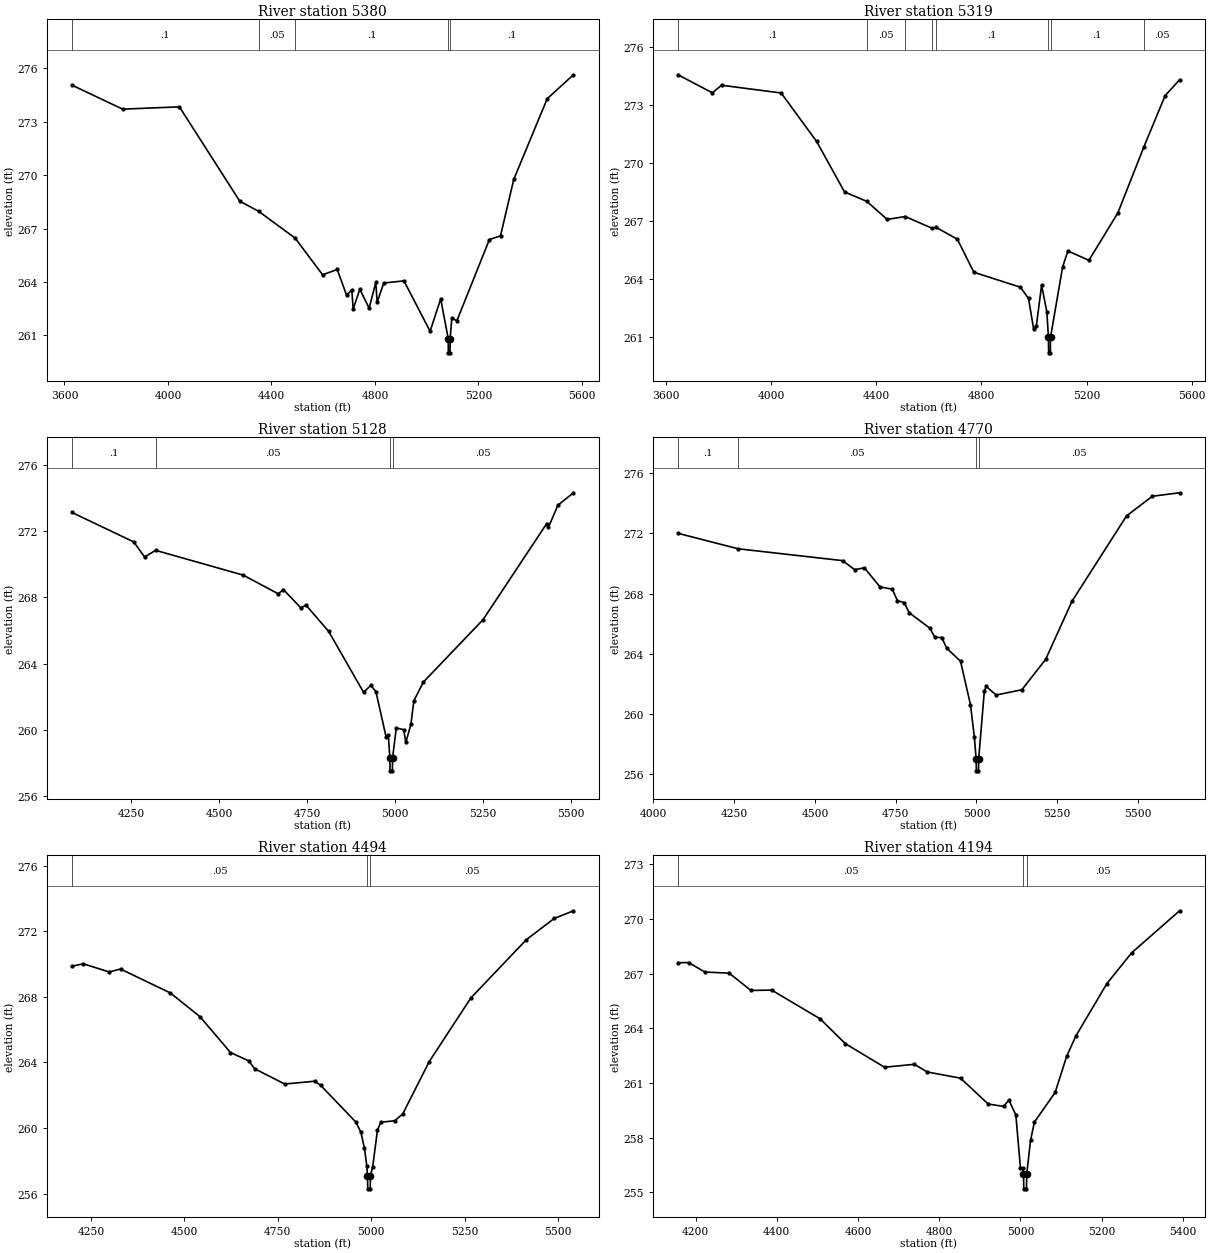
Type RM Length L Ch R = 1,5380,61,61,61
BEGIN DESCRIPTION:
Mapping XS 9f52e726
END DESCRIPTION:
XS GIS Cut Line= 6
      2123478.81     13390165.74      2124056.11     13389623.18
      2124069.13     13389510.33      2124574.77     13389347.57
      2124750.55     13389341.06      2125020.95     13389161.51
#Sta/Elev= 30
  3629.1  275.05  3825.1  273.70  4044.4  273.83  4277.8  268.53  4350.1  267.97
  4491.7  266.46  4597.7  264.40  4654.1  264.70  4690.3  263.26  4710.6  263.55
  4715.9  262.48  4741.5  263.59  4777.6  262.53  4803.2  263.97  4808.5  262.86
  4834.1  263.94  4912.1  264.06  5013.1  261.23  5054.1  263.05  5083.0  260.82
  5083.7  260.02  5090.1  260.02  5090.7  260.82  5096.9  261.95  5116.9  261.83
  5242.2  266.38  5285.2  266.59  5336.4  269.76  5465.7  274.29  5567.1  275.63
#Mann=5,-1,0
  3629.1     0.1       0  4350.1    0.05       0  4491.7     0.1       0
  5083.0    0.07       0  5090.7     0.1       0
Bank Sta=5083,5090.7
Exp/Cntr=0.3,0.1

Type RM Length L Ch R = 1,5319,191,191,191
BEGIN DESCRIPTION:
Mapping XS 4153bf6f
END DESCRIPTION:
XS GIS Cut Line= 6
      2123522.28     13390176.53      2124125.55     13389651.39
      2124123.38     13389540.71      2124325.20     13389458.24
      2124520.52     13389410.50      2125099.96     13389397.48
#Sta/Elev= 30
  3644.8  274.54  3775.5  273.61  3810.6  274.00  4037.5  273.60  4172.3  271.10
  4278.7  268.49  4363.8  268.00  4440.9  267.07  4509.9  267.22  4610.6  266.62
  4627.0  266.66  4708.2  266.05  4771.1  264.34  4948.1  263.57  4979.1  262.99
  4998.9  261.39  5008.9  261.57  5028.9  263.67  5048.9  262.30  5055.0  260.98
  5055.6  260.18  5062.2  260.18  5062.8  260.98  5108.9  264.61  5128.9  265.44
  5209.0  264.96  5319.0  267.40  5418.4  270.82  5499.0  273.46  5554.0  274.28
#Mann=8,-1,0
  3644.8     0.1       0  4363.8    0.05       0  4509.9     0.1       0
  4610.6    0.05       0  4627.0     0.1       0  5055.0    0.07       0
  5062.8     0.1       0  5418.4    0.05       0
Bank Sta=5055,5062.8
Exp/Cntr=0.3,0.1

Type RM Length L Ch R = 1,5128,358,358,358
BEGIN DESCRIPTION:
Mapping XS d17d71c0
END DESCRIPTION:
XS GIS Cut Line= 4
      2123845.62     13390028.98      2124277.46     13389840.19
      2124724.51     13389492.97      2125108.58     13389427.87
#Sta/Elev= 30
  4081.3  273.14  4257.1  271.36  4288.0  270.45  4319.5  270.85  4568.8  269.35
  4668.4  268.22  4682.9  268.48  4732.7  267.37  4747.1  267.54  4811.4  265.96
  4911.0  262.27  4931.8  262.69  4946.3  262.30  4975.2  259.56  4981.5  259.66
  4985.8  258.32  4986.4  257.52  4993.0  257.52  4993.6  258.32  5004.2  260.11
  5025.0  260.01  5031.3  259.24  5045.8  260.34  5054.0  261.75  5081.3  262.89
  5251.0  266.66  5432.1  272.47  5437.1  272.25  5464.0  273.58  5508.2  274.33
#Mann=4,-1,0
  4081.3     0.1       0  4319.5    0.05       0  4985.8    0.04       0
  4993.6    0.05       0
Bank Sta=4985.8,4993.6
Exp/Cntr=0.3,0.1

Type RM Length L Ch R = 1,4770,276,276,276
BEGIN DESCRIPTION:
UNT 005 in La Jarita Watershed 9.0
END DESCRIPTION:
XS GIS Cut Line= 4
      2123876.00     13390104.94      2124516.18     13389996.44
      2125004.46     13389699.13      2125196.86     13389428.91
#Sta/Elev= 30
  4076.0  272.01  4262.2  270.98  4585.8  270.19  4622.7  269.59  4653.1  269.71
  4701.4  268.44  4739.6  268.29  4755.1  267.53  4776.4  267.39  4791.8  266.72
  4855.8  265.69  4871.3  265.08  4892.6  265.07  4908.1  264.35  4950.7  263.49
  4981.5  260.59  4993.4  258.46  4999.0  256.99  4999.7  256.19  5006.3  256.19
  5006.9  256.99  5024.3  261.48  5030.1  261.81  5061.1  261.24  5140.5  261.59
  5214.1  263.61  5296.1  267.50  5464.7  273.17  5544.7  274.48  5628.7  274.71
#Mann=4,-1,0
  4076.0     0.1       0  4262.2    0.05       0  4999.0    0.03       0
  5006.9    0.05       0
Bank Sta=4999,5006.9
Exp/Cntr=0.3,0.1

Type RM Length L Ch R = 1,4494,300,300,300
BEGIN DESCRIPTION:
Mapping XS 664b333a
END DESCRIPTION:
XS GIS Cut Line= 4
      2124216.02     13390263.36      2124619.62     13390211.28
      2125205.56     13389872.74      2125322.74     13389642.72
#Sta/Elev= 30
  4199.3  269.86  4229.6  270.01  4298.9  269.51  4329.3  269.69  4462.7  268.23
  4542.1  266.78  4623.5  264.60  4672.4  264.09  4688.1  263.61  4768.5  262.68
  4848.9  262.85  4864.7  262.60  4958.9  260.36  4972.4  259.74  4982.0  258.75
  4988.2  257.69  4990.0  257.09  4990.7  256.29  4997.3  256.29  4997.9  257.09
  5004.0  257.65  5016.7  259.86  5025.5  260.35  5062.8  260.44  5084.4  260.86
  5155.3  264.05  5266.7  267.93  5415.1  271.48  5489.5  272.77  5541.1  273.24
#Mann=3,-1,0
  4199.3    0.05       0  4990.0   0.035       0  4997.9    0.05       0
Bank Sta=4990,4997.9
Exp/Cntr=0.3,0.1

Type RM Length L Ch R = 1,4194,348,348,348
BEGIN DESCRIPTION:
UNT 005 in La Jarita Watershed 8.0
END DESCRIPTION:
XS GIS Cut Line= 3
      2124411.26     13390588.90      2125175.00     13390225.00
      2125340.05     13389872.87
#Sta/Elev= 30
  4156.8  267.59  4183.1  267.60  4222.9  267.08  4282.8  267.02  4336.4  266.07
  4387.4  266.09  4506.4  264.52  4569.0  263.15  4665.3  261.86  4739.0  262.02
  4770.2  261.60  4852.5  261.26  4920.6  259.84  4958.5  259.71  4971.5  260.06
  4988.7  259.24  5000.0  256.32  5005.6  256.32  5007.5  255.99  5008.2  255.19
  5014.8  255.19  5015.4  255.99  5024.9  257.85  5034.3  258.85  5085.5  260.48
  5113.8  262.46  5136.6  263.58  5212.6  266.44  5273.6  268.13  5391.7  270.44
#Mann=3,-1,0
  4156.8    0.05       0  5007.5    0.03       0  5015.4    0.05       0
Bank Sta=5007.5,5015.4
Exp/Cntr=0.3,0.1