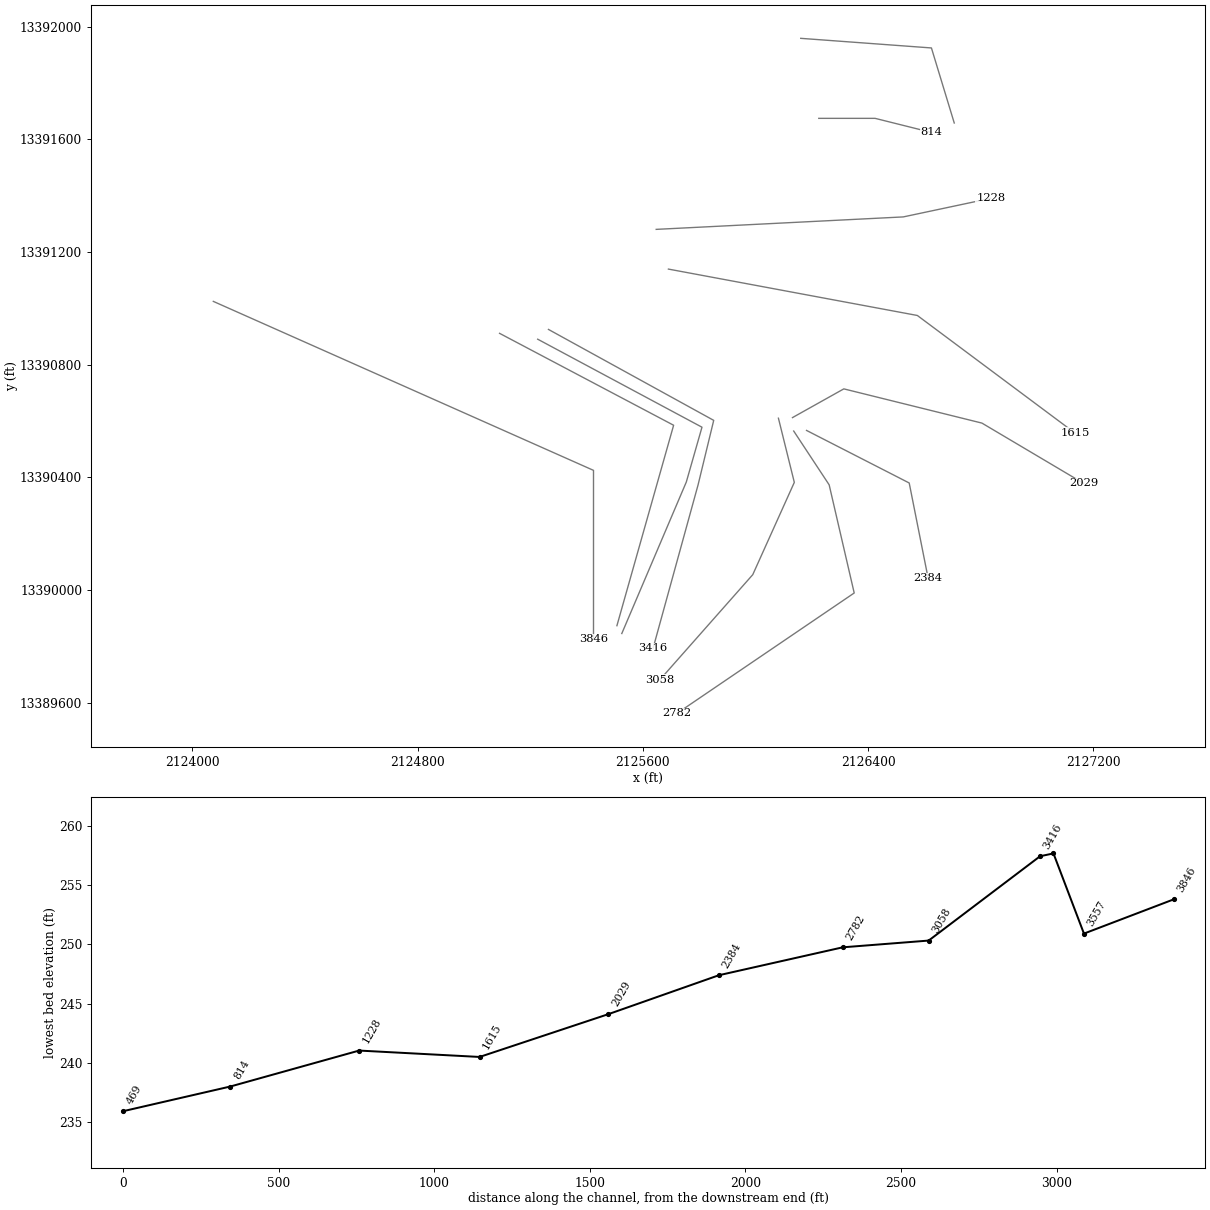
HEC-RAS study UNT 005 in La Jarita Watershed.prj: UNT 005 in La Jarita Watershed Base Level Engineering

--- UNT 005 in La Jarita Watershed.g01 (geometry) --- (continued)

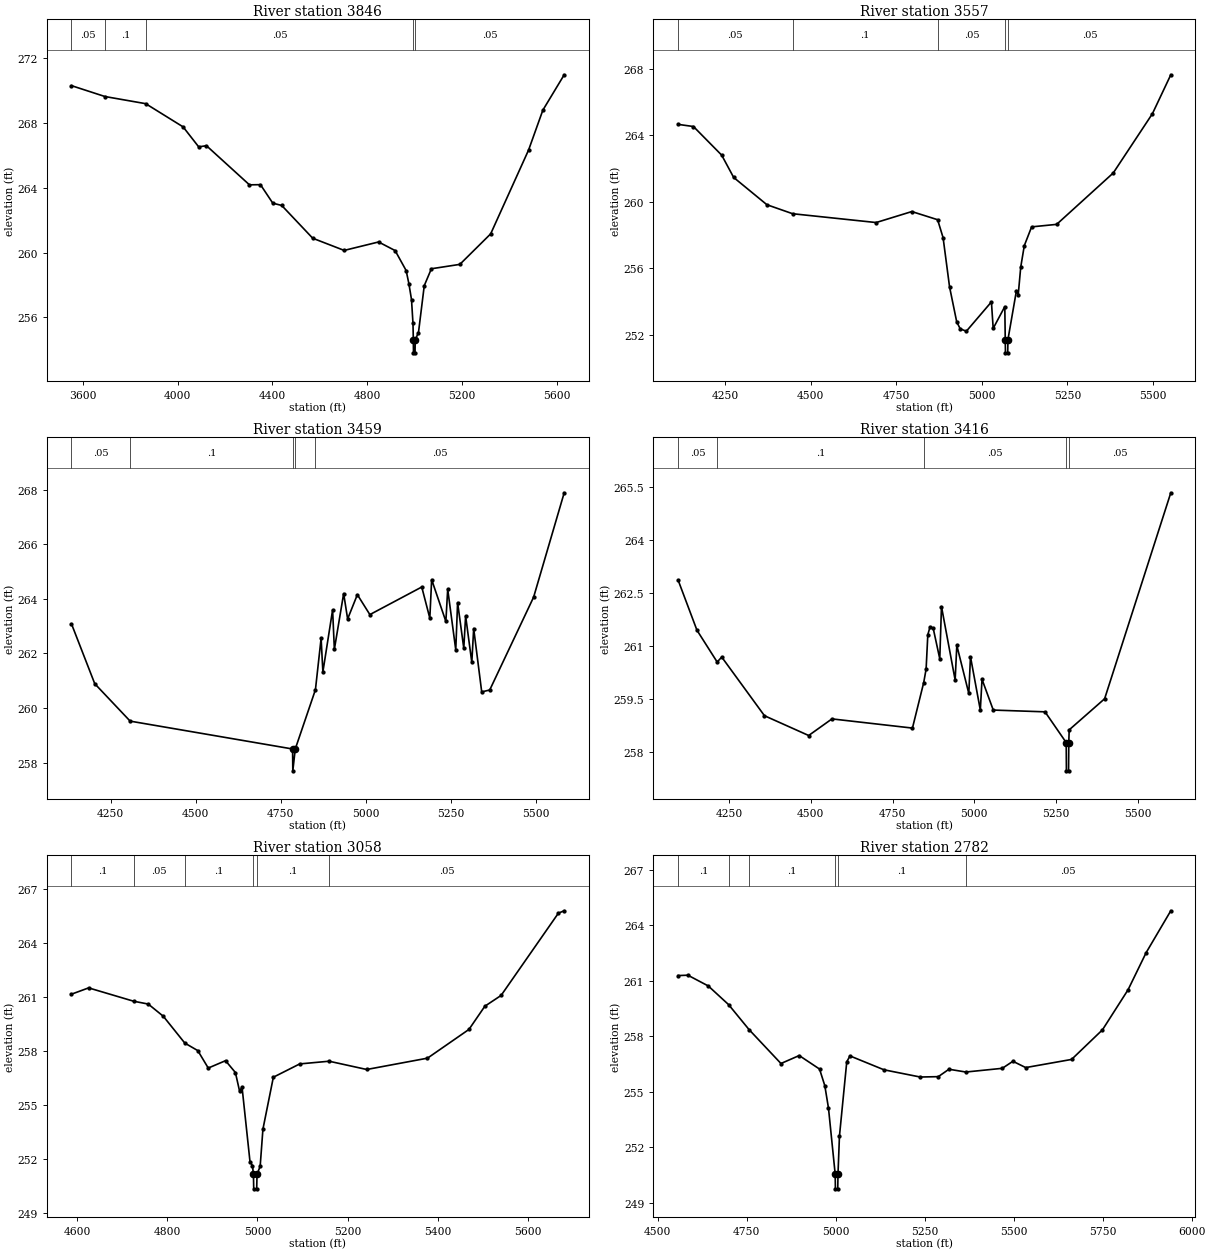
Type RM Length L Ch R = 1,3846,289,289,289
BEGIN DESCRIPTION:
UNT 005 in La Jarita Watershed 7.0
END DESCRIPTION:
XS GIS Cut Line= 3
      2124074.96     13391025.02      2125425.00     13390425.00
      2125425.00     13389824.97
#Sta/Elev= 30
  3552.7  270.28  3693.9  269.61  3865.5  269.17  4023.3  267.74  4089.0  266.51
  4121.8  266.58  4303.0  264.17  4349.5  264.18  4401.5  263.04  4439.1  262.90
  4569.8  260.88  4702.5  260.13  4847.5  260.65  4917.2  260.12  4963.7  258.89
  4975.4  258.07  4986.3  257.10  4992.5  255.64  4994.0  254.62  4994.6  253.82
  5001.2  253.82  5001.9  254.62  5015.7  255.07  5040.1  257.96  5070.1  259.00
  5190.1  259.27  5320.1  261.15  5480.1  266.32  5540.1  268.77  5630.1  270.95
#Mann=5,-1,0
  3552.7    0.05       0  3693.9     0.1       0  3865.5    0.05       0
  4994.0    0.03       0  5001.9    0.05       0
Bank Sta=4994,5001.9
Exp/Cntr=0.3,0.1

Type RM Length L Ch R = 1,3557,98,98,98
BEGIN DESCRIPTION:
Mapping XS 57f9f121
END DESCRIPTION:
XS GIS Cut Line= 3
      2125091.46     13390911.57      2125709.51     13390585.19
      2125508.12     13389873.37
#Sta/Elev= 30
  4113.3  264.65  4158.2  264.52  4240.6  262.80  4275.6  261.46  4372.7  259.82
  4447.8  259.28  4691.6  258.75  4795.8  259.41  4871.1  258.92  4887.1  257.84
  4906.0  254.88  4926.8  252.79  4937.1  252.36  4955.1  252.22  5028.2  253.98
  5033.4  252.39  5067.3  253.70  5068.6  251.72  5069.2  250.92  5075.8  250.92
  5076.5  251.72  5101.3  254.66  5106.5  254.41  5113.8  256.07  5124.2  257.36
  5145.6  258.49  5218.7  258.64  5384.0  261.73  5498.3  265.29  5552.0  267.63
#Mann=5,-1,0
  4113.3    0.05       0  4447.8     0.1       0  4871.1    0.05       0
  5068.6   0.035       0  5076.5    0.05       0
Bank Sta=5068.6,5076.5
Exp/Cntr=0.3,0.1

Type RM Length L Ch R = 1,3459,43,43,43
BEGIN DESCRIPTION:
Mapping XS 2a41d08d
END DESCRIPTION:
XS GIS Cut Line= 4
      2125226.84     13390890.76      2125810.21     13390578.24
      2125754.65     13390383.80      2125525.48     13389845.59
#Sta/Elev= 30
  4134.8  263.08  4203.2  260.89  4307.3  259.52  4785.0  258.50  4785.7  257.70
  4792.9  258.50  4852.2  260.67  4868.9  262.55  4874.1  261.32  4902.7  263.59
  4907.9  262.15  4935.2  264.19  4946.9  263.26  4975.5  264.15  5012.3  263.42
  5164.9  264.43  5188.6  263.29  5194.0  264.70  5235.8  263.17  5241.2  264.35
  5264.9  262.13  5270.3  263.86  5288.5  262.19  5293.9  263.37  5312.1  261.67
  5317.6  262.91  5341.2  260.59  5364.8  260.66  5493.9  264.06  5583.8  267.88
#Mann=5,-1,0
  4134.8    0.05       0  4307.3     0.1       0  4785.0   0.035       0
  4792.9     0.1       0  4852.2    0.05       0
Bank Sta=4785,4792.9
Exp/Cntr=0.3,0.1

Type RM Length L Ch R = 1,3416,358,358,358
BEGIN DESCRIPTION:
Mapping XS 29214764
END DESCRIPTION:
XS GIS Cut Line= 4
      2125265.09     13390925.45      2125851.87     13390602.55
      2125796.32     13390373.38      2125636.60     13389793.54
#Sta/Elev= 30
  4094.2  262.86  4151.9  261.44  4213.7  260.54  4227.7  260.68  4358.4  259.02
  4493.6  258.46  4564.8  258.93  4811.0  258.67  4845.5  259.96  4852.8  260.34
  4858.0  261.31  4864.3  261.52  4874.6  261.49  4894.6  260.63  4899.8  262.11
  4941.6  260.03  4946.7  261.01  4983.4  259.65  4988.5  260.69  5018.6  259.18
  5023.8  260.05  5058.2  259.18  5216.5  259.13  5281.3  258.26  5281.9  257.46
  5288.5  257.46  5289.2  258.26  5290.4  258.62  5398.8  259.50  5601.2  265.33
#Mann=5,-1,0
  4094.2    0.05       0  4213.7     0.1       0  4845.5    0.05       0
  5281.3   0.035       0  5289.2    0.05       0
Bank Sta=5281.3,5289.2
Exp/Cntr=0.3,0.1

Type RM Length L Ch R = 1,3058,276,276,276
BEGIN DESCRIPTION:
Mapping XS 277787ca
END DESCRIPTION:
XS GIS Cut Line= 4
      2126081.68     13390610.21      2126138.11     13390382.33
      2125990.54     13390054.64      2125660.66     13389681.36
#Sta/Elev= 30
  4587.7  261.16  4625.7  261.51  4725.2  260.77  4757.9  260.61  4791.3  259.93
  4838.9  258.44  4867.7  258.02  4890.9  257.05  4929.2  257.46  4951.1  256.80
  4960.3  255.77  4965.8  255.99  4983.4  251.85  4988.9  251.62  4991.1  251.13
  4991.7  250.33  4998.3  250.33  4999.0  251.13  5006.0  251.59  5012.1  253.65
  5035.2  256.54  5093.7  257.28  5158.8  257.43  5242.2  256.97  5376.9  257.60
  5468.9  259.20  5504.1  260.49  5540.1  261.09  5667.2  265.67  5680.0  265.80
#Mann=6,-1,0
  4587.7     0.1       0  4725.2    0.05       0  4838.9     0.1       0
  4991.1    0.07       0  4999.0     0.1       0  5158.8    0.05       0
Bank Sta=4991.1,4999
Exp/Cntr=0.3,0.1

Type RM Length L Ch R = 1,2782,398,398,398
BEGIN DESCRIPTION:
Mapping XS ed34a4ea
END DESCRIPTION:
XS GIS Cut Line= 4
      2126135.94     13390564.62      2126261.81     13390373.65
      2126350.78     13389989.54      2125721.45     13389562.03
#Sta/Elev= 30
  4557.6  261.28  4585.1  261.30  4642.3  260.72  4699.5  259.71  4757.0  258.36
  4846.5  256.53  4897.8  256.96  4954.9  256.23  4969.7  255.33  4980.0  254.12
  4998.8  250.56  4999.4  249.76  5006.0  249.76  5006.7  250.56  5010.8  252.61
  5031.3  256.62  5040.3  256.94  5135.9  256.19  5237.6  255.80  5288.4  255.82
  5318.3  256.22  5365.8  256.07  5468.1  256.27  5498.0  256.65  5533.9  256.31
  5662.7  256.75  5749.5  258.35  5821.3  260.51  5872.2  262.52  5941.4  264.78
#Mann=6,-1,0
  4557.6     0.1       0  4699.5    0.05       0  4757.0     0.1       0
  4998.8    0.07       0  5006.7     0.1       0  5365.8    0.05       0
Bank Sta=4998.8,5006.7
Exp/Cntr=0.3,0.1

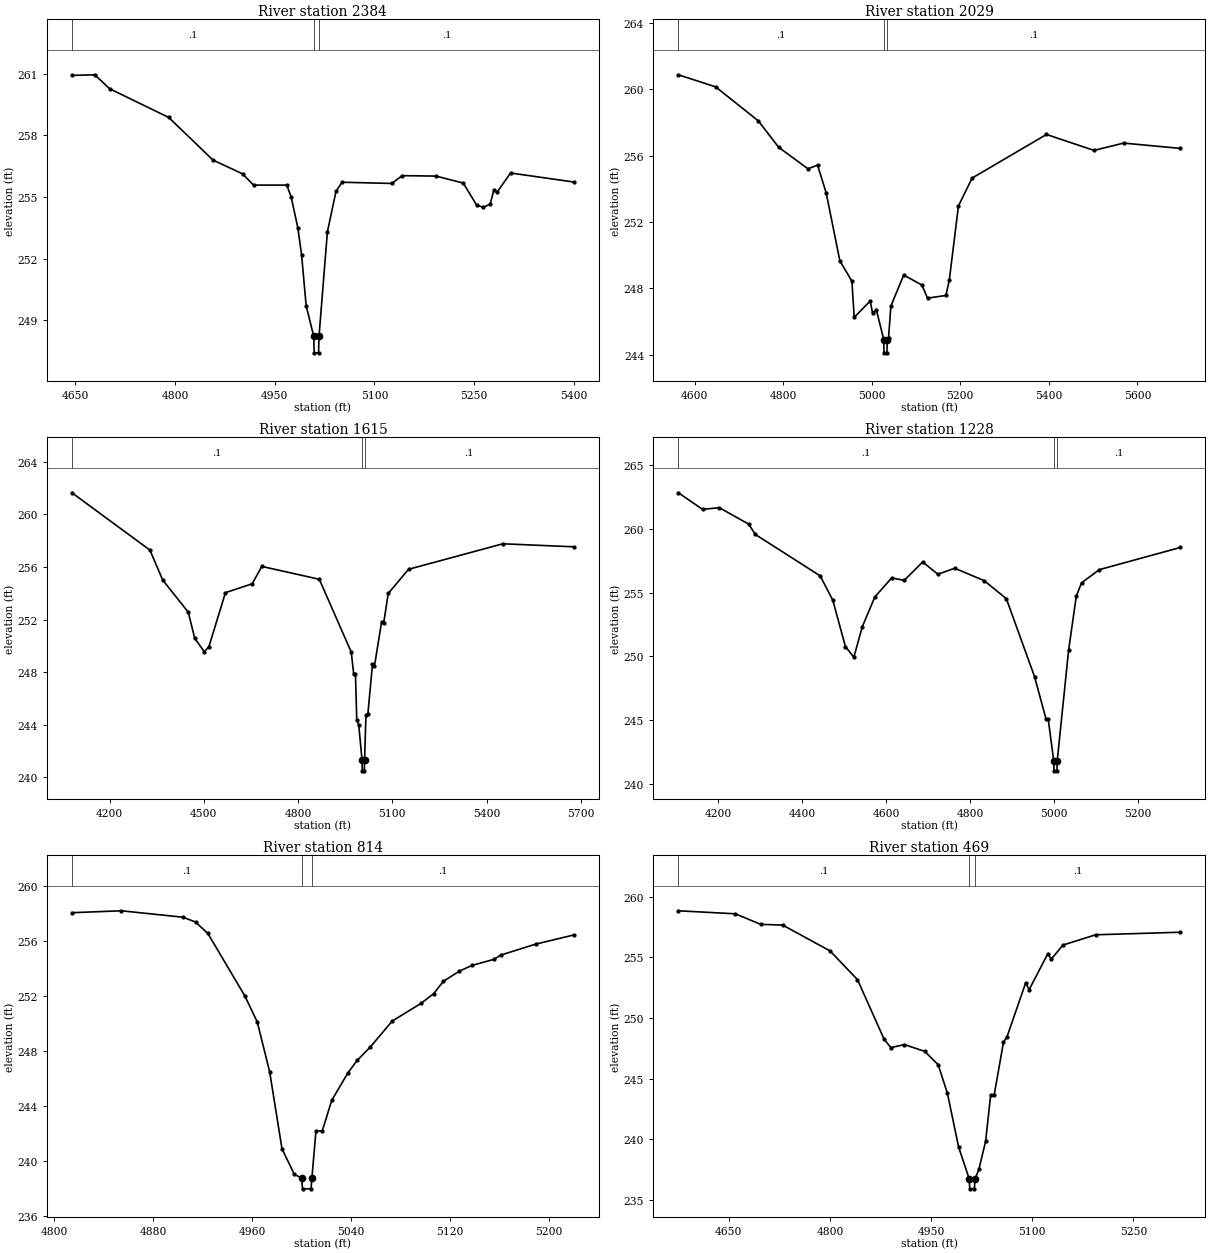
Type RM Length L Ch R = 1,2384,355,355,355
BEGIN DESCRIPTION:
Mapping XS dcadd972
END DESCRIPTION:
XS GIS Cut Line= 3
      2126181.51     13390566.79      2126546.09     13390380.16
      2126613.36     13390041.66
#Sta/Elev= 30
  4645.1  260.93  4679.5  260.96  4701.7  260.28  4790.6  258.88  4857.2  256.80
  4901.6  256.13  4918.2  255.58  4968.2  255.58  4974.8  254.99  4984.8  253.49
  4990.4  252.18  4997.3  249.69  5008.7  248.20  5009.3  247.40  5015.9  247.40
  5016.6  248.20  5029.2  253.30  5042.2  255.28  5051.3  255.72  5126.1  255.66
  5141.5  256.04  5192.5  256.02  5233.5  255.68  5253.7  254.60  5263.8  254.50
  5274.0  254.65  5279.5  255.34  5284.6  255.24  5304.6  256.17  5399.8  255.73
#Mann=3,-1,0
  4645.1     0.1       0  5008.7    0.07       0  5016.6     0.1       0
Bank Sta=5008.7,5016.6
Exp/Cntr=0.3,0.1

Type RM Length L Ch R = 1,2029,414,414,414
BEGIN DESCRIPTION:
Mapping XS 7f3d5b28
END DESCRIPTION:
XS GIS Cut Line= 4
      2126131.59     13390612.36      2126313.89     13390714.36
      2126804.34     13390592.84      2127165.04     13390379.01
#Sta/Elev= 30
  4563.4  260.88  4647.5  260.15  4743.9  258.10  4789.7  256.51  4855.9  255.21
  4877.6  255.43  4897.1  253.76  4928.0  249.66  4955.2  248.43  4960.4  246.25
  4996.6  247.24  5001.8  246.51  5010.4  246.71  5027.1  244.91  5027.7  244.11
  5034.3  244.11  5035.0  244.91  5038.0  245.03  5043.2  246.93  5072.2  248.80
  5113.4  248.20  5126.0  247.41  5167.4  247.57  5175.2  248.50  5195.8  252.97
  5226.7  254.65  5394.6  257.28  5501.9  256.32  5569.0  256.76  5696.9  256.44
#Mann=3,-1,0
  4563.4     0.1       0  5027.1    0.07       0  5035.0     0.1       0
Bank Sta=5027.1,5035
Exp/Cntr=0.3,0.1

Type RM Length L Ch R = 1,1615,387,387,387
BEGIN DESCRIPTION:
UNT 005 in La Jarita Watershed 4.0
END DESCRIPTION:
XS GIS Cut Line= 3
      2125691.03     13391139.72      2126575.00     13390975.00
      2127134.69     13390557.56
#Sta/Elev= 30
  4080.3  261.64  4328.5  257.28  4369.2  255.00  4450.5  252.56  4470.9  250.58
  4501.4  249.55  4516.1  249.93  4568.8  254.04  4654.0  254.72  4684.5  256.04
  4867.6  255.06  4969.3  249.52  4976.9  247.86  4982.6  247.86  4986.8  244.35
  4993.0  243.99  5003.6  241.29  5004.3  240.49  5010.9  240.49  5011.6  241.29
  5016.0  244.74  5022.2  244.84  5036.8  248.59  5043.1  248.46  5066.0  251.84
  5072.3  251.70  5086.9  253.98  5151.5  255.82  5451.7  257.76  5677.7  257.53
#Mann=3,-1,0
  4080.3     0.1       0  5003.6    0.07       0  5011.6     0.1       0
Bank Sta=5003.6,5011.6
Exp/Cntr=0.3,0.1

Type RM Length L Ch R = 1,1228,414,414,414
BEGIN DESCRIPTION:
UNT 005 in La Jarita Watershed 3.0
END DESCRIPTION:
XS GIS Cut Line= 3
      2125647.67     13391280.77      2126525.00     13391325.00
      2126835.23     13391390.88
#Sta/Elev= 30
  4105.4  262.84  4162.8  261.54  4202.9  261.67  4272.9  260.38  4288.3  259.58
  4443.2  256.32  4473.2  254.41  4503.2  250.78  4523.3  249.94  4543.3  252.32
  4573.3  254.67  4613.4  256.16  4643.4  255.97  4687.2  257.41  4723.5  256.45
  4763.6  256.92  4833.7  255.95  4886.6  254.53  4953.8  248.41  4981.3  245.07
  4986.4  245.07  4999.4  241.83  5000.1  241.03  5007.0  241.03  5007.8  241.83
  5035.0  250.52  5053.2  254.73  5065.6  255.77  5107.9  256.81  5301.0  258.55
#Mann=3,-1,0
  4105.4     0.1       0  4999.4    0.07       0  5007.8     0.1       0
Bank Sta=4999.4,5007.8
Exp/Cntr=0.3,0.1

Type RM Length L Ch R = 1,814,345,345,345
BEGIN DESCRIPTION:
UNT 005 in La Jarita Watershed 2.0
END DESCRIPTION:
XS GIS Cut Line= 3
      2126225.00     13391675.00      2126425.00     13391675.00
      2126625.04     13391624.99
#Sta/Elev= 30
  4814.2  258.09  4854.2  258.23  4904.2  257.76  4914.2  257.41  4924.2  256.58
  4954.2  252.02  4964.2  250.13  4974.2  246.51  4984.2  240.90  4994.2  239.04
  5000.0  238.79  5000.8  237.99  5007.7  237.99  5008.4  238.79  5011.7  242.21
  5016.8  242.21  5024.5  244.44  5037.4  246.41  5045.1  247.35  5055.4  248.29
  5073.5  250.21  5096.7  251.49  5107.0  252.20  5114.7  253.09  5127.6  253.83
  5137.9  254.25  5155.9  254.70  5161.1  255.00  5189.4  255.80  5220.4  256.47
#Mann=3,-1,0
  4814.2     0.1       0  5000.0    0.07       0  5008.4     0.1       0
Bank Sta=5000,5008.4
Exp/Cntr=0.3,0.1

Type RM Length L Ch R = 1,469,0,0,0
BEGIN DESCRIPTION:
UNT 005 in La Jarita Watershed 1.0
END DESCRIPTION:
XS GIS Cut Line= 3
      2126160.90     13391959.15      2126625.00     13391925.00
      2126706.04     13391658.50
#Sta/Elev= 30
  4575.5  258.84  4659.8  258.59  4697.5  257.72  4730.0  257.66  4800.2  255.53
  4840.9  253.16  4880.4  248.24  4890.4  247.55  4910.5  247.80  4940.6  247.24
  4960.6  246.13  4974.2  243.78  4990.7  239.37  5006.6  236.70  5007.3  235.90
  5014.2  235.90  5015.0  236.70  5020.8  237.50  5030.8  239.81  5038.3  243.64
  5043.5  243.64  5057.3  248.00  5062.5  248.44  5090.1  252.88  5095.4  252.34
  5123.0  255.30  5128.2  254.85  5145.4  256.01  5194.0  256.86  5319.4  257.07
#Mann=3,-1,0
  4575.5     0.1       0  5006.6    0.07       0  5015.0     0.1       0
Bank Sta=5006.6,5015
Exp/Cntr=0.3,0.1

Chan Stop Cuts=-1