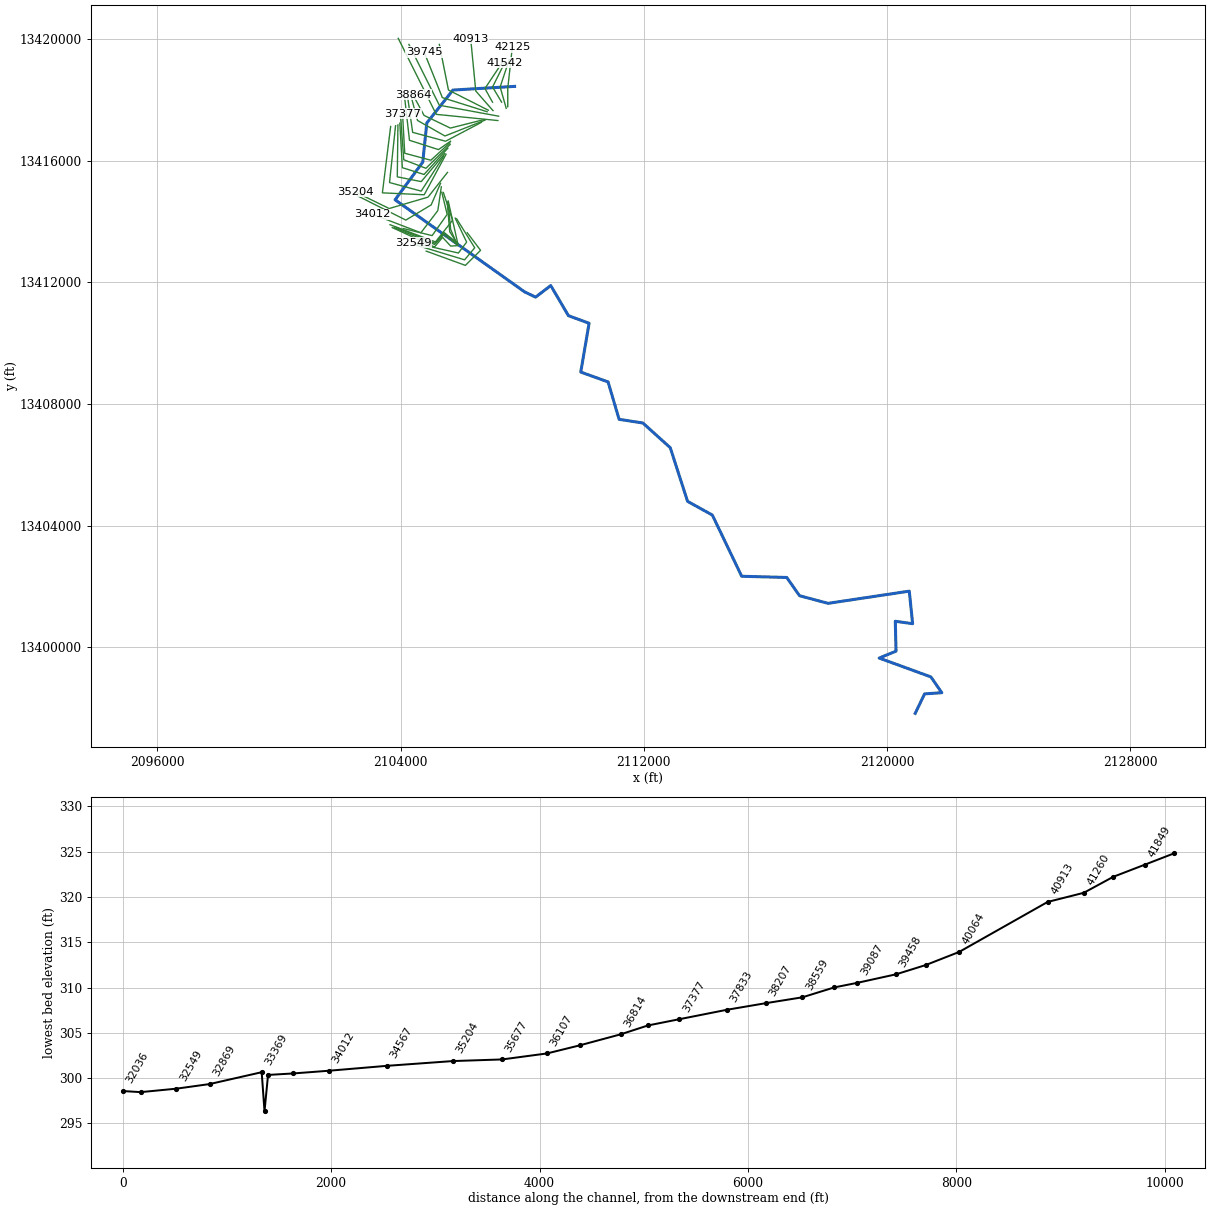
--- UNT 006 in La Jarita Watershed.prj (project) ---

Proj Title=UNT 006 in La Jarita Watershed Base Level Engineering
Current Plan=p01
Default Exp/Contr=0.3,0.1
English Units
Geom File=g01
Flow File=f01
Plan File=p01
Y Axis Title=Elevation
X Axis Title(PF)=Main Channel Distance
X Axis Title(XS)=Station
BEGIN DESCRIPTION:
UNT 006 in La Jarita Watershed
END DESCRIPTION:
DSS Export Rating Curves= 0
DSS Export Rating Curve Sorted= 0
DSS Export Volume Flow Curves= 0
DXF OffsetX= 0
DXF OffsetY= 0
DXF ScaleX= 1
DXF ScaleY= 10

--- UNT 006 in La Jarita Watershed.p01 (plan) ---

Plan Title=Multiple Run
Short Identifier=Multiple
Geom File=g01
Flow File=f01
Subcritical Flow
K Sum by GR= 0
Std Step Tol= 0.01
Critical Tol= 0.01
Num of Std Step Trials= 20
Max Error Tol= 0.3
Flow Tol Ratio= 0.001
Split Flow NTrial= 30
Split Flow Tol= 0.02
Split Flow Ratio= 0.02
Log Output Level= 0
Friction Slope Method= 1
Unsteady Friction Slope Method= 2
Unsteady Bridges Friction Slope Method= 1
Parabolic Critical Depth
Global Vel Dist=  1 , 1 , 1
Global Log Level= 0
CheckData=True
Encroach Param= -1, 0, 0, 0
BEGIN DESCRIPTION:
Multiple Run
END DESCRIPTION:

--- UNT 006 in La Jarita Watershed.f01 (steady flow) ---

Flow Title=Multiple
Program Version=5.05
Number of Profiles= 7
Profile Names=10-year,25-year,50-year,1pct_min,100-year,1pct_plu,500-year
River Rch & RM=UNT 006 in La Ja,Reach-1         ,42125
     107     139     163      96     191     380     264
River Rch & RM=UNT 006 in La Ja,Reach-1         ,40064
     181     242     290     173     345     688     496
River Rch & RM=UNT 006 in La Ja,Reach-1         ,33430
     182     242     290     173     345     688     495
River Rch & RM=UNT 006 in La Ja,Reach-1         ,28575
     299     409     497     301     600    1197     888
River Rch & RM=UNT 006 in La Ja,Reach-1         ,19962
     412     571     701     428     853    1702    1284
River Rch & RM=UNT 006 in La Ja,Reach-1         ,8192
     543     762     944     581    1158    2311    1771
Boundary for River Rch & Prof#=UNT 006 in La Ja,Reach-1         , 1
Up Type= 0
Dn Type= 3
Dn Slope=0.0014
Boundary for River Rch & Prof#=UNT 006 in La Ja,Reach-1         , 2
Up Type= 0
Dn Type= 3
Dn Slope=0.0014
Boundary for River Rch & Prof#=UNT 006 in La Ja,Reach-1         , 3
Up Type= 0
Dn Type= 3
Dn Slope=0.0014
Boundary for River Rch & Prof#=UNT 006 in La Ja,Reach-1         , 4
Up Type= 0
Dn Type= 3
Dn Slope=0.0014
Boundary for River Rch & Prof#=UNT 006 in La Ja,Reach-1         , 5
Up Type= 0
Dn Type= 3
Dn Slope=0.0014
Boundary for River Rch & Prof#=UNT 006 in La Ja,Reach-1         , 6
Up Type= 0
Dn Type= 3
Dn Slope=0.0014
Boundary for River Rch & Prof#=UNT 006 in La Ja,Reach-1         , 7
Up Type= 0
Dn Type= 3
Dn Slope=0.0014
DSS Import GetInterval= 0
DSS Import GetPeak= 0
DSS Import FillOption= 0

--- UNT 006 in La Jarita Watershed.g01 (geometry) ---

Geom Title=Existing Conditions

River Reach=UNT 006 in La Ja,Reach-1
Reach XY= 30
      2107750.80     13418444.54      2105723.49     13418323.83
      2104863.48     13417241.49      2104730.80     13415954.54
      2103820.80     13414714.54      2108080.48     13411686.39
      2108440.80     13411514.54      2108940.80     13411894.54
      2109520.80     13410904.54      2110200.80     13410654.54
      2109926.55     13409049.19      2110824.99     13408725.84
      2111187.94     13407495.48      2111969.19     13407374.39
      2112870.23     13406561.89      2113439.25     13404797.48
      2114254.35     13404346.96      2115219.19     13402334.15
      2116700.80     13402294.54      2117120.80     13401694.54
      2118058.97     13401443.54      2120730.80     13401844.54
      2120840.80     13400774.54      2120270.80     13400854.54
      2120295.26     13399870.45      2119740.80     13399644.54
      2121440.80     13399024.54      2121800.80     13398504.54
      2121234.69     13398466.28      2120925.00     13397825.00

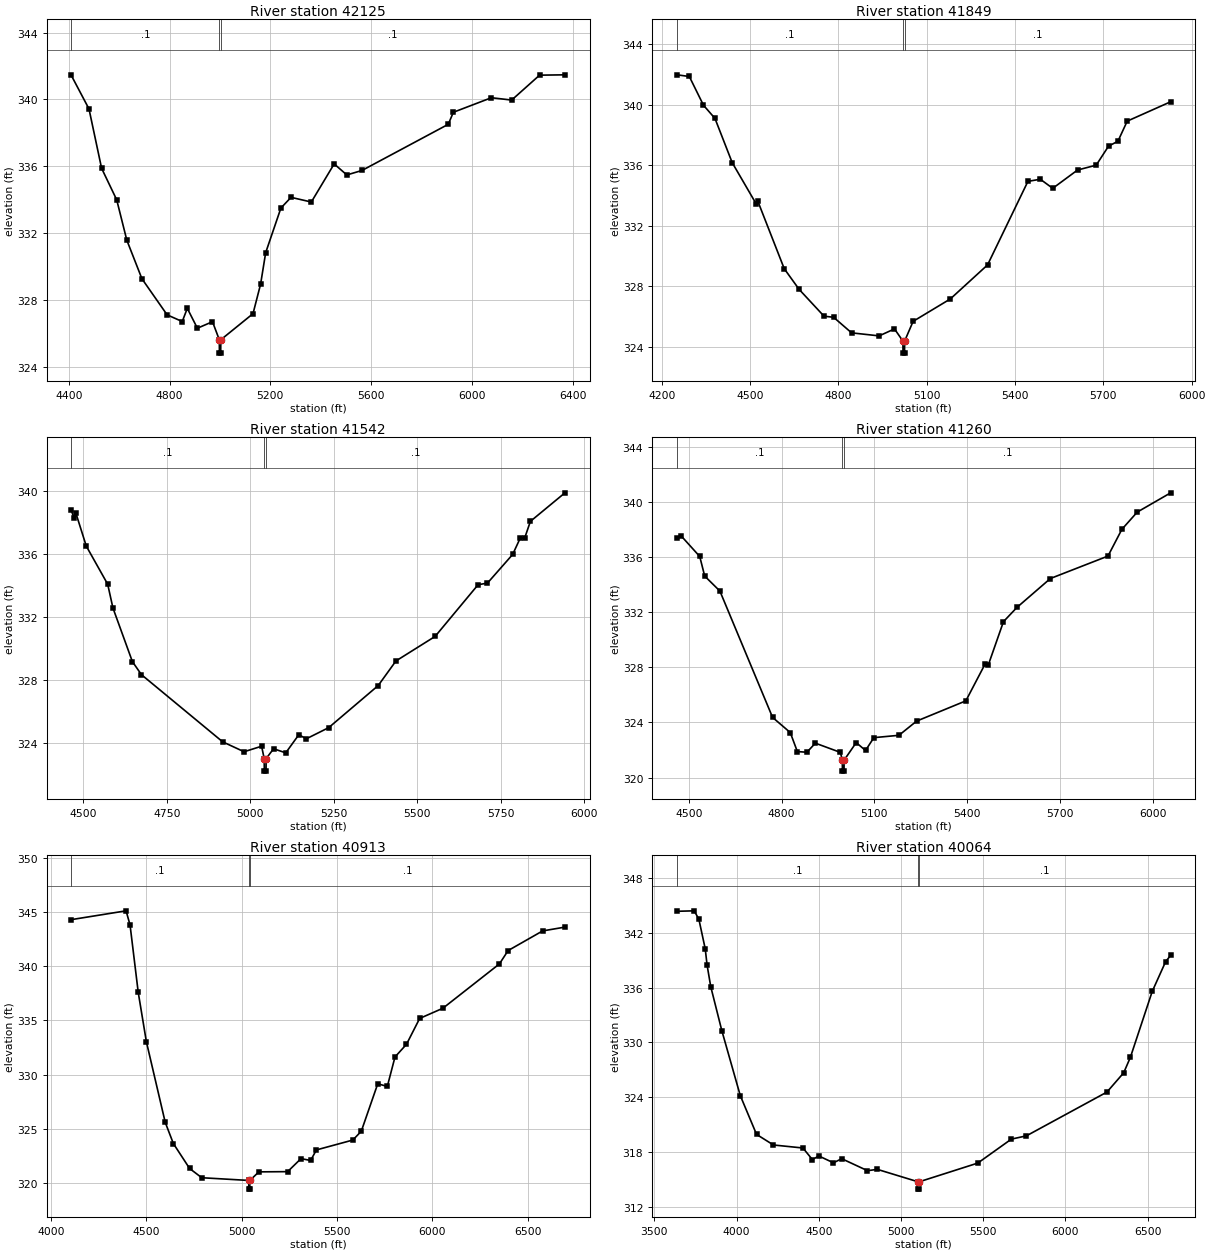
Type RM Length L Ch R = 1,42125,276,276,276
BEGIN DESCRIPTION:
UNT 006 in La Jarita Watershed 44.0
END DESCRIPTION:
XS GIS Cut Line= 3
      2107525.00     13417775.04      2107525.00     13418375.00
      2107675.00     13419725.03
#Sta/Elev= 30
  4410.5  341.43  4480.5  339.43  4530.5  335.88  4590.5  333.99  4630.5  331.58
  4690.5  329.27  4790.5  327.11  4850.5  326.71  4870.5  327.50  4910.5  326.31
  4970.5  326.70  4997.5  325.62  4998.0  324.82  5003.0  324.82  5003.5  325.62
  5131.2  327.18  5161.4  328.95  5181.5  330.83  5241.9  333.50  5282.1  334.14
  5362.6  333.86  5453.2  336.14  5503.5  335.48  5563.8  335.75  5905.9  338.51
  5926.1  339.23  6077.0  340.10  6157.5  339.96  6268.2  341.45  6368.8  341.47
#Mann=3,-1,0
  4410.5     0.1       0  4997.5    0.07       0  5003.5     0.1       0
Bank Sta=4997.5,5003.5
Exp/Cntr=0.3,0.1

Type RM Length L Ch R = 1,41849,307,307,307
BEGIN DESCRIPTION:
UNT 006 in La Jarita Watershed 43.0
END DESCRIPTION:
XS GIS Cut Line= 3
      2107474.99     13417725.04      2107275.00     13418425.00
      2107575.01     13419325.04
#Sta/Elev= 30
  4252.0  341.98  4293.6  341.87  4341.7  339.97  4380.7  339.10  4439.2  336.18
  4521.1  333.44  4526.3  333.63  4616.0  329.17  4666.7  327.80  4751.2  326.03
  4783.7  325.96  4844.8  324.93  4938.4  324.73  4990.5  325.19  5019.1  324.39
  5019.6  323.59  5024.6  323.59  5025.1  324.39  5053.8  325.69  5180.2  327.17
  5306.7  329.42  5443.8  334.94  5485.9  335.08  5528.1  334.48  5612.4  335.69
  5675.7  336.01  5717.8  337.27  5749.5  337.59  5781.1  338.92  5928.7  340.20
#Mann=3,-1,0
  4252.0     0.1       0  5019.1    0.07       0  5025.1     0.1       0
Bank Sta=5019.1,5025.1
Exp/Cntr=0.3,0.1

Type RM Length L Ch R = 1,41542,282,282,282
BEGIN DESCRIPTION:
UNT 006 in La Jarita Watershed 42.0
END DESCRIPTION:
XS GIS Cut Line= 3
      2107325.00     13417925.01      2107025.00     13418425.00
      2107424.99     13419224.99
#Sta/Elev= 30
  4464.1  338.78  4471.9  338.29  4477.7  338.60  4508.8  336.51  4572.9  334.09
  4588.5  332.59  4646.8  329.18  4674.0  328.35  4917.0  324.09  4981.1  323.46
  5033.6  323.81  5041.3  323.03  5041.8  322.23  5046.8  322.23  5047.3  323.03
  5069.5  323.65  5105.9  323.39  5145.0  324.54  5167.4  324.28  5234.5  324.99
  5382.6  327.66  5435.7  329.22  5553.1  330.78  5681.7  334.06  5709.6  334.16
  5785.1  335.98  5807.4  337.00  5821.4  337.04  5838.2  338.08  5941.6  339.89
#Mann=3,-1,0
  4464.1     0.1       0  5041.3    0.07       0  5047.3     0.1       0
Bank Sta=5041.3,5047.3
Exp/Cntr=0.3,0.1

Type RM Length L Ch R = 1,41260,347,347,347
BEGIN DESCRIPTION:
UNT 006 in La Jarita Watershed 41.0
END DESCRIPTION:
XS GIS Cut Line= 3
      2107025.02     13417924.97      2106775.00     13418375.00
      2107375.01     13419275.01
#Sta/Elev= 30
  4461.7  337.42  4475.5  337.53  4535.0  336.05  4551.0  334.63  4600.2  333.54
  4770.6  324.37  4827.8  323.27  4850.7  321.89  4881.6  321.84  4909.0  322.50
  4990.0  321.83  4996.1  321.27  4996.6  320.47  5001.6  320.47  5002.1  321.27
  5041.1  322.54  5071.2  321.97  5098.2  322.90  5179.3  323.07  5236.4  324.10
  5395.7  325.57  5458.8  328.28  5467.8  328.14  5517.4  331.32  5560.9  332.35
  5669.1  334.45  5855.4  336.08  5900.4  338.02  5950.0  339.27  6058.2  340.67
#Mann=3,-1,0
  4461.7     0.1       0  4996.1    0.07       0  5002.1     0.1       0
Bank Sta=4996.1,5002.1
Exp/Cntr=0.3,0.1

Type RM Length L Ch R = 1,40913,849,849,849
BEGIN DESCRIPTION:
Mapping XS 4920b53d
END DESCRIPTION:
XS GIS Cut Line= 3
      2107041.41     13417646.94      2106473.70     13418292.78
      2106306.73     13420011.40
#Sta/Elev= 30
  4108.2  344.28  4395.0  345.09  4415.9  343.78  4458.6  337.59  4501.3  333.04
  4600.0  325.62  4642.7  323.66  4728.0  321.36  4791.6  320.51  5037.7  320.26
  5038.2  319.46  5043.2  319.46  5043.7  320.26  5090.9  321.05  5241.6  321.07
  5311.7  322.27  5362.2  322.10  5392.3  323.07  5583.2  323.98  5627.6  324.79
  5713.8  329.16  5764.0  328.92  5804.2  331.63  5864.5  332.80  5933.5  335.18
  6055.4  336.12  6351.3  340.20  6397.0  341.43  6577.9  343.24  6694.8  343.59
#Mann=3,-1,0
  4108.2     0.1       0  5037.7    0.07       0  5043.7     0.1       0
Bank Sta=5037.7,5043.7
Exp/Cntr=0.3,0.1

Type RM Length L Ch R = 1,40064,319,319,319
BEGIN DESCRIPTION:
UNT 006 in La Jarita Watershed 40.0
END DESCRIPTION:
XS GIS Cut Line= 3
      2106887.73     13417659.98      2105575.00     13418325.00
      2105275.00     13419825.02
#Sta/Elev= 30
  3638.3  344.34  3742.3  344.39  3770.7  343.48  3809.5  340.23  3820.8  338.45
  3843.1  336.09  3910.4  331.28  4022.5  324.18  4121.5  319.93  4224.3  318.77
  4403.6  318.44  4461.2  317.17  4500.1  317.57  4589.2  316.82  4639.4  317.27
  4796.0  315.96  4856.5  316.10  5104.1  314.74  5104.6  313.94  5109.6  313.94
  5110.1  314.74  5466.8  316.79  5670.8  319.41  5762.5  319.77  6252.1  324.56
  6354.0  326.67  6394.8  328.37  6527.4  335.57  6609.0  338.83  6639.6  339.52
#Mann=3,-1,0
  3638.3     0.1       0  5104.1    0.07       0  5110.1     0.1       0
Bank Sta=5104.1,5110.1
Exp/Cntr=0.3,0.1

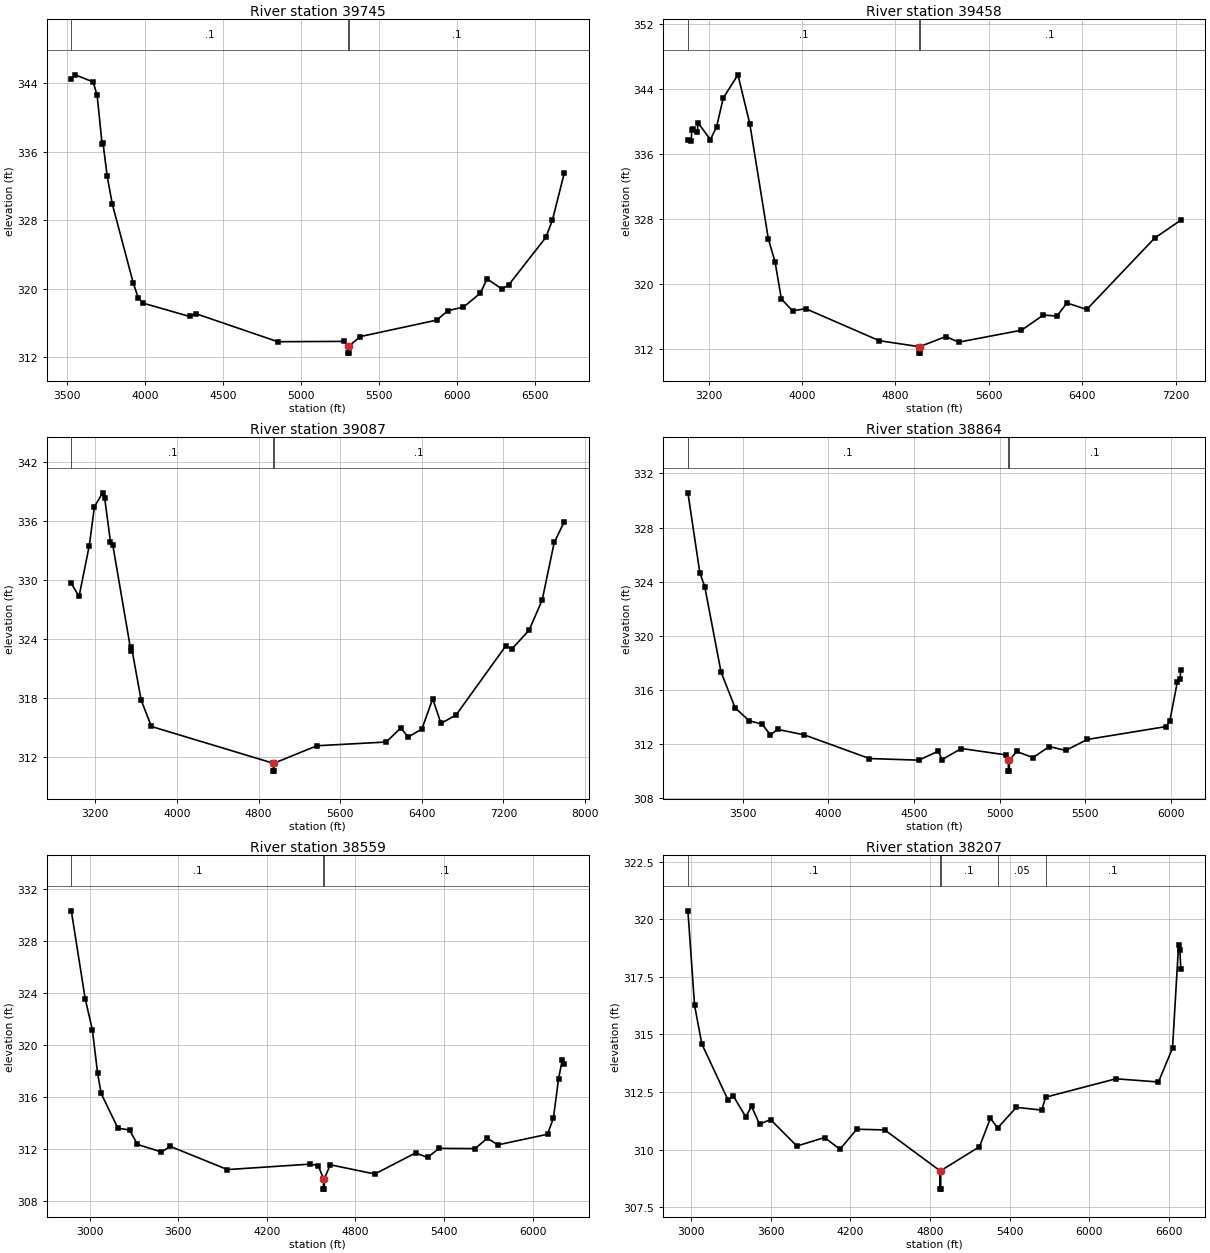
Type RM Length L Ch R = 1,39745,287,287,287
BEGIN DESCRIPTION:
UNT 006 in La Jarita Watershed 39.0
END DESCRIPTION:
XS GIS Cut Line= 3
      2106848.68     13417610.50      2105375.00     13418075.00
      2104775.00     13419575.00
#Sta/Elev= 30
  3529.1  344.51  3553.9  344.94  3669.3  344.11  3694.6  342.56  3727.0  336.82
  3732.2  337.02  3759.3  333.11  3791.7  329.90  3926.4  320.67  3958.7  318.92
  3991.1  318.32  4287.6  316.77  4330.4  317.08  4853.4  313.83  5280.2  313.87
  5301.4  313.30  5301.9  312.50  5307.0  312.50  5307.5  313.30  5382.6  314.43
  5872.6  316.35  5945.3  317.46  6043.6  317.86  6151.3  319.47  6195.7  321.15
  6291.3  319.97  6334.4  320.46  6572.7  326.00  6614.4  328.00  6689.8  333.45
#Mann=3,-1,0
  3529.1     0.1       0  5301.4    0.07       0  5307.5     0.1       0
Bank Sta=5301.4,5307.5
Exp/Cntr=0.3,0.1

Type RM Length L Ch R = 1,39458,371,371,371
BEGIN DESCRIPTION:
UNT 006 in La Jarita Watershed 38.0
END DESCRIPTION:
XS GIS Cut Line= 3
      2107226.32     13417464.65      2105275.00     13417825.00
      2104274.99     13419825.02
#Sta/Elev= 30
  3023.3  337.65  3051.4  337.56  3056.5  338.88  3065.3  339.02  3104.4  338.69
  3109.4  339.81  3215.4  337.74  3268.3  339.27  3326.3  342.86  3451.7  345.70
  3553.4  339.66  3712.3  325.50  3770.3  322.65  3823.3  318.14  3919.5  316.66
  4031.4  316.94  4661.9  313.00  5002.0  312.27  5002.5  311.47  5007.6  311.47
  5008.1  312.27  5231.2  313.50  5343.0  312.82  5879.7  314.29  6066.9  316.15
  6184.3  316.03  6268.2  317.64  6438.7  316.84  7020.1  325.62  7243.7  327.82
#Mann=3,-1,0
  3023.3     0.1       0  5002.0    0.07       0  5008.1     0.1       0
Bank Sta=5002,5008.1
Exp/Cntr=0.3,0.1

Type RM Length L Ch R = 1,39087,223,223,223
BEGIN DESCRIPTION:
UNT 006 in La Jarita Watershed 37.0
END DESCRIPTION:
XS GIS Cut Line= 3
      2107200.29     13417321.42      2105175.00     13417525.00
      2103924.99     13420025.01
#Sta/Elev= 30
  2964.5  329.62  3040.2  328.29  3140.7  333.46  3190.9  337.41  3271.3  338.83
  3291.4  338.31  3348.5  333.85  3371.8  333.48  3549.0  322.74  3554.0  323.16
  3649.2  317.75  3749.4  315.07  4944.3  311.33  4944.8  310.53  4949.9  310.53
  4950.4  311.33  5371.7  313.11  6051.0  313.49  6193.5  314.92  6266.2  314.00
  6400.3  314.81  6506.6  317.88  6587.6  315.38  6735.7  316.24  7222.1  323.25
  7280.8  322.93  7451.3  324.86  7579.9  327.94  7697.3  333.78  7795.1  335.87
#Mann=3,-1,0
  2964.5     0.1       0  4944.3    0.07       0  4950.4     0.1       0
Bank Sta=4944.3,4950.4
Exp/Cntr=0.3,0.1

Type RM Length L Ch R = 1,38864,305,305,305
BEGIN DESCRIPTION:
Mapping XS 61280038
END DESCRIPTION:
XS GIS Cut Line= 4
      2106752.28     13417354.89      2105637.72     13417073.65
      2104773.14     13417490.31      2104409.29     13418166.04
#Sta/Elev= 30
  3180.6  330.57  3250.0  324.68  3279.0  323.64  3373.7  317.35  3456.3  314.69
  3538.8  313.73  3612.7  313.50  3662.5  312.70  3703.8  313.10  3859.1  312.70
  4240.1  310.95  4528.2  310.83  4641.3  311.49  4663.9  310.87  4777.0  311.69
  5036.9  311.22  5050.9  310.82  5051.4  310.02  5056.5  310.02  5057.0  310.82
  5099.1  311.47  5195.2  311.02  5289.5  311.83  5386.3  311.55  5512.0  312.36
  5971.2  313.31  5993.1  313.71  6036.9  316.59  6053.1  316.81  6057.3  317.50
#Mann=3,-1,0
  3180.6     0.1       0  5050.9    0.07       0  5057.0     0.1       0
Bank Sta=5050.9,5057
Exp/Cntr=0.3,0.1

Type RM Length L Ch R = 1,38559,352,352,352
BEGIN DESCRIPTION:
Mapping XS c957f9bc
END DESCRIPTION:
XS GIS Cut Line= 4
      2106778.32     13417334.05      2105460.64     13416813.23
      2104559.60     13417323.65      2104330.44     13418177.80
#Sta/Elev= 30
  2876.5  330.29  2970.3  323.55  3019.0  321.17  3054.1  317.86  3078.5  316.27
  3192.0  313.61  3270.5  313.47  3324.6  312.36  3486.8  311.78  3546.7  312.21
  3933.8  310.43  4495.3  310.85  4548.8  310.73  4583.1  309.73  4583.6  308.93
  4589.0  308.93  4589.5  309.73  4629.6  310.80  4931.1  310.09  5207.8  311.71
  5288.3  311.36  5366.3  312.06  5609.9  312.04  5692.7  312.83  5765.2  312.33
  6100.5  313.14  6140.5  314.39  6175.3  317.40  6200.1  318.82  6213.3  318.55
#Mann=3,-1,0
  2876.5     0.1       0  4583.1    0.07       0  4589.5     0.1       0
Bank Sta=4583.1,4589.5
Exp/Cntr=0.3,0.1

Type RM Length L Ch R = 1,38207,374,374,374
BEGIN DESCRIPTION:
Mapping XS 94a434f3
END DESCRIPTION:
XS GIS Cut Line= 4
      2106658.52     13417261.12      2105481.47     13416641.35
      2104398.14     13416933.02      2104221.27     13418181.50
#Sta/Elev= 30
  2975.2  320.36  3025.3  316.26  3080.1  314.58  3278.4  312.14  3316.8  312.33
  3410.6  311.42  3454.6  311.87  3515.1  311.10  3597.6  311.30  3795.9  310.15
  4004.9  310.52  4120.7  310.01  4247.3  310.88  4458.2  310.85  4873.7  309.08
  4874.2  308.28  4879.6  308.28  4880.1  309.08  5171.7  310.12  5254.6  311.36
  5307.7  310.93  5449.6  311.83  5641.4  311.71  5669.4  312.27  6200.2  313.07
  6520.1  312.93  6626.1  314.40  6671.6  318.86  6681.7  318.67  6688.3  317.85
#Mann=5,-1,0
  2975.2     0.1       0  4873.7    0.07       0  4880.1     0.1       0
  5307.7    0.05       0  5669.4     0.1       0
Bank Sta=4873.7,4880.1
Exp/Cntr=0.3,0.1

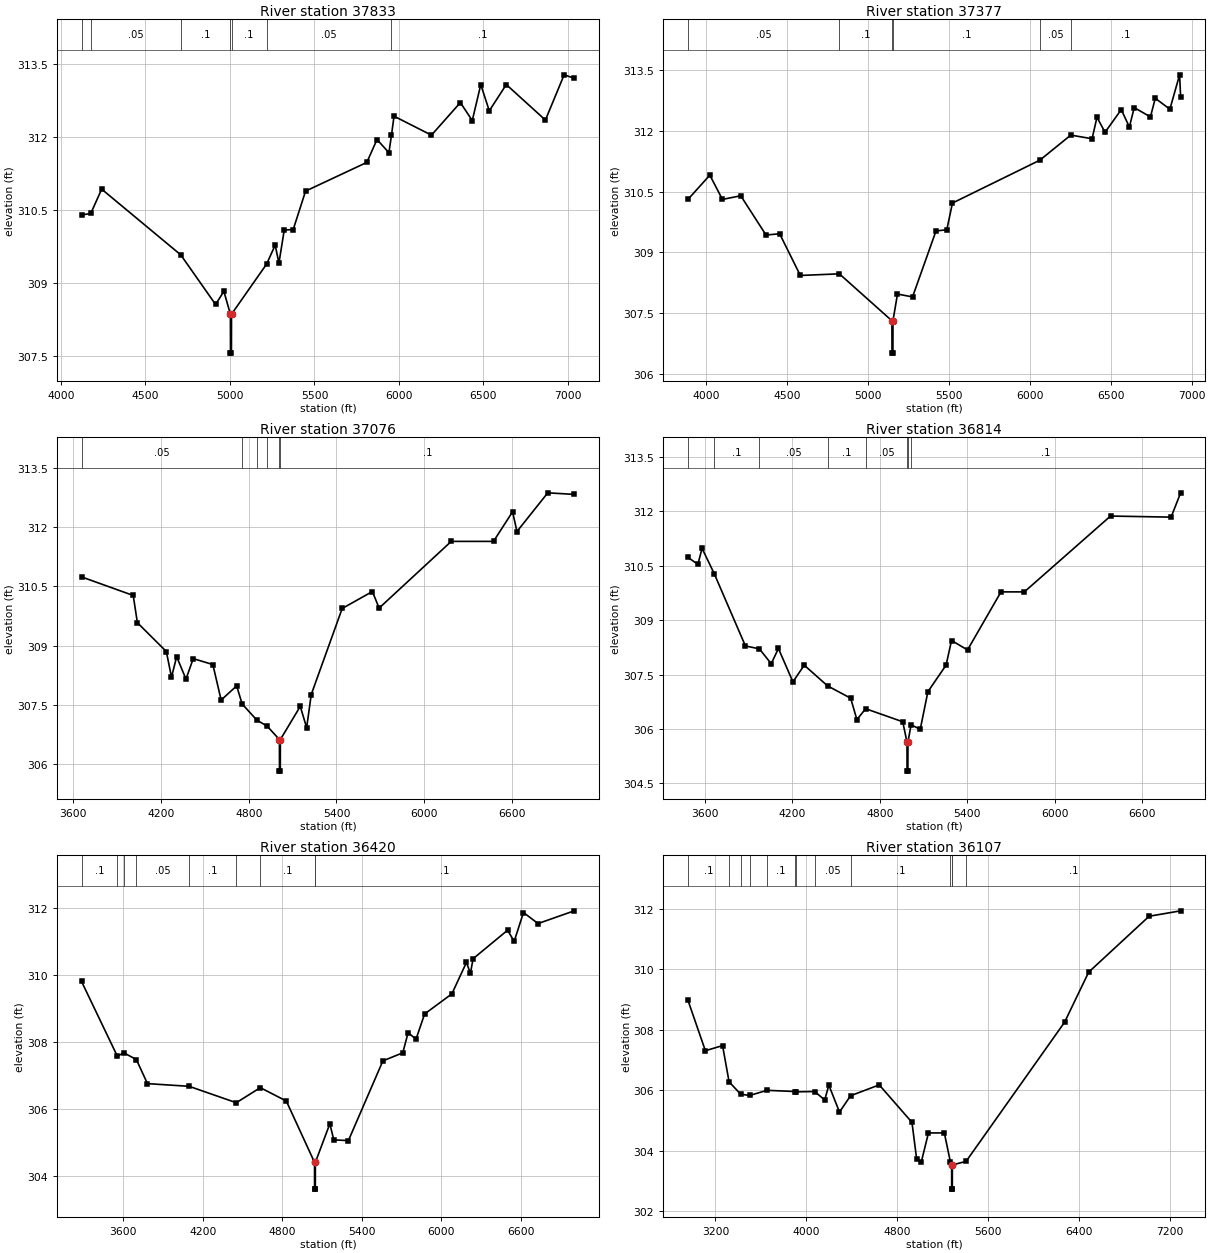
Type RM Length L Ch R = 1,37833,456,456,456
BEGIN DESCRIPTION:
Mapping XS 31e0292b
END DESCRIPTION:
XS GIS Cut Line= 4
      2105642.97     13416641.38      2105247.10     13416365.31
      2104293.97     13416672.60      2104132.51     13418094.50
#Sta/Elev= 30
  4122.0  310.39  4176.4  310.42  4241.1  310.92  4708.9  309.57  4915.0  308.55
  4964.1  308.82  5002.7  308.35  5003.2  307.55  5008.7  307.55  5009.2  308.35
  5216.9  309.38  5267.6  309.77  5289.8  309.40  5321.3  310.08  5374.3  310.09
  5447.4  310.88  5809.8  311.47  5870.1  311.94  5940.6  311.67  5955.7  312.03
  5970.8  312.42  6192.2  312.03  6363.3  312.70  6433.7  312.33  6484.1  313.07
  6534.4  312.53  6635.0  313.07  6866.5  312.34  6977.2  313.27  7037.1  313.20
#Mann=7,-1,0
  4122.0     0.1       0  4176.4    0.05       0  4708.9     0.1       0
  5002.7    0.07       0  5009.2     0.1       0  5216.9    0.05       0
  5955.7     0.1       0
Bank Sta=5002.7,5009.2
Exp/Cntr=0.3,0.1

Type RM Length L Ch R = 1,37377,301,301,301
BEGIN DESCRIPTION:
Mapping XS ca227102
END DESCRIPTION:
XS GIS Cut Line= 4
      2105622.09     13416589.26      2104997.10     13416016.35
      2104137.72     13416245.52      2104064.88     13417551.44
#Sta/Elev= 30
  3886.9  310.31  4022.2  310.91  4100.0  310.31  4213.3  310.40  4369.4  309.43
  4453.8  309.46  4581.5  308.43  4822.8  308.47  5147.6  307.31  5148.1  306.51
  5153.6  306.51  5154.1  307.31  5181.9  307.97  5275.1  307.90  5420.0  309.53
  5486.8  309.56  5521.7  310.22  6062.0  311.28  6253.0  311.90  6384.8  311.81
  6414.9  312.34  6464.9  311.97  6565.1  312.53  6615.2  312.10  6645.2  312.58
  6745.4  312.35  6775.4  312.81  6865.6  312.54  6925.6  313.39  6932.1  312.84
#Mann=6,-1,0
  3886.9    0.05       0  4822.8     0.1       0  5147.6    0.07       0
  5154.1     0.1       0  6062.0    0.05       0  6253.0     0.1       0
Bank Sta=5147.6,5154.1
Exp/Cntr=0.3,0.1

Type RM Length L Ch R = 1,37076,262,262,262
BEGIN DESCRIPTION:
Mapping XS 7860d87f
END DESCRIPTION:
XS GIS Cut Line= 4
      2105632.54     13416537.21      2104835.64     13415750.73
      2104106.47     13416031.98      2103997.10     13417495.53
#Sta/Elev= 30
  3657.1  310.74  4010.5  310.27  4038.8  309.58  4236.8  308.85  4272.1  308.20
  4307.5  308.72  4371.1  308.15  4420.6  308.67  4554.9  308.52  4611.5  307.62
  4717.6  307.98  4755.3  307.52  4856.3  307.11  4926.1  306.96  5010.0  306.62
  5010.5  305.82  5016.0  305.82  5016.5  306.62  5152.6  307.46  5196.2  306.92
  5227.6  307.76  5439.1  309.94  5645.8  310.37  5691.7  309.95  6185.0  311.64
  6473.8  311.64  6604.2  312.39  6634.3  311.89  6844.9  312.87  7025.9  312.83
#Mann=6,-1,0
  3657.1    0.05       0  4755.3     0.1       0  4856.3    0.05       0
  4926.1     0.1       0  5010.0    0.07       0  5016.5     0.1       0
Bank Sta=5010,5016.5
Exp/Cntr=0.3,0.1

Type RM Length L Ch R = 1,36814,394,394,394
BEGIN DESCRIPTION:
Mapping XS bce27fe4
END DESCRIPTION:
XS GIS Cut Line= 4
      2105554.40     13416412.19      2104773.14     13415547.60
      2104059.60     13415771.56      2103976.26     13417235.15
#Sta/Elev= 30
  3484.3  310.73  3552.6  310.54  3581.0  310.98  3664.8  310.28  3878.4  308.29
  3974.3  308.21  4055.5  307.80  4104.8  308.22  4204.2  307.30  4281.9  307.76
  4441.6  307.19  4600.3  306.85  4642.9  306.26  4703.3  306.56  4957.5  306.20
  4986.6  305.64  4987.1  304.84  4992.6  304.84  4993.1  305.64  5014.7  306.12
  5077.4  305.99  5130.0  307.03  5254.5  307.76  5292.1  308.44  5401.7  308.18
  5631.3  309.78  5791.5  309.78  6382.5  311.87  6797.9  311.84  6863.4  312.51
#Mann=8,-1,0
  3484.3    0.05       0  3664.8     0.1       0  3974.3    0.05       0
  4441.6     0.1       0  4703.3    0.05       0  4986.6   0.035       0
  4993.1    0.05       0  5014.7     0.1       0
Bank Sta=4986.6,4993.1
Exp/Cntr=0.3,0.1

Type RM Length L Ch R = 1,36420,313,313,313
BEGIN DESCRIPTION:
Mapping XS b6a83471
END DESCRIPTION:
XS GIS Cut Line= 4
      2105455.45     13416235.13      2104679.39     13415313.23
      2103892.93     13415469.48      2103913.77     13417177.86
#Sta/Elev= 30
  3286.6  309.82  3556.4  307.59  3605.3  307.69  3699.9  307.49  3783.5  306.77
  4097.9  306.69  4453.4  306.20  4634.7  306.65  4830.9  306.25  5043.4  304.42
  5043.9  303.62  5049.4  303.62  5049.9  304.42  5158.8  305.57  5188.9  305.09
  5299.0  305.07  5559.0  307.45  5709.0  307.69  5749.0  308.29  5809.1  308.10
  5873.5  308.85  6079.1  309.45  6189.1  310.39  6219.1  310.06  6239.1  310.50
  6499.1  311.35  6549.1  311.02  6619.1  311.88  6729.1  311.55  7002.0  311.93
#Mann=9,-1,0
  3286.6     0.1       0  3556.4    0.05       0  3605.3     0.1       0
  3699.9    0.05       0  4097.9     0.1       0  4453.4    0.05       0
  4634.7     0.1       0  5043.4    0.07       0  5049.9     0.1       0
Bank Sta=5043.4,5049.9
Exp/Cntr=0.3,0.1

Type RM Length L Ch R = 1,36107,430,430,430
BEGIN DESCRIPTION:
Mapping XS 6e3dfc0c
END DESCRIPTION:
XS GIS Cut Line= 4
      2105424.21     13416157.02      2104679.39     13415000.73
      2103637.72     13415281.98      2103835.55     13417150.86
#Sta/Elev= 30
  2957.8  308.98  3111.1  307.31  3262.3  307.48  3319.7  306.28  3421.9  305.87
  3501.1  305.83  3652.9  306.00  3900.8  305.96  3904.5  305.95  4072.6  305.96
  4160.8  305.68  4197.1  306.17  4290.8  305.28  4388.0  305.82  4640.3  306.18
  4928.2  304.94  4969.6  303.72  5011.0  303.64  5073.2  304.59  5212.9  304.59
  5266.3  303.63  5277.1  303.53  5277.6  302.73  5283.1  302.73  5283.6  303.53
  5404.5  303.65  6270.0  308.25  6482.5  309.91  7014.1  311.76  7291.5  311.94
#Mann=13,-1,0
  2957.8     0.1       0  3319.7    0.05       0  3421.9     0.1       0
  3501.1    0.05       0  3652.9     0.1       0  3900.8    0.05       0
  3904.5     0.1       0  4072.6    0.05       0  4388.0     0.1       0
  5266.3    0.05       0  5277.1    0.07       0  5283.6    0.05       0
  5404.5     0.1       0
Bank Sta=5277.1,5283.6
Exp/Cntr=0.3,0.1

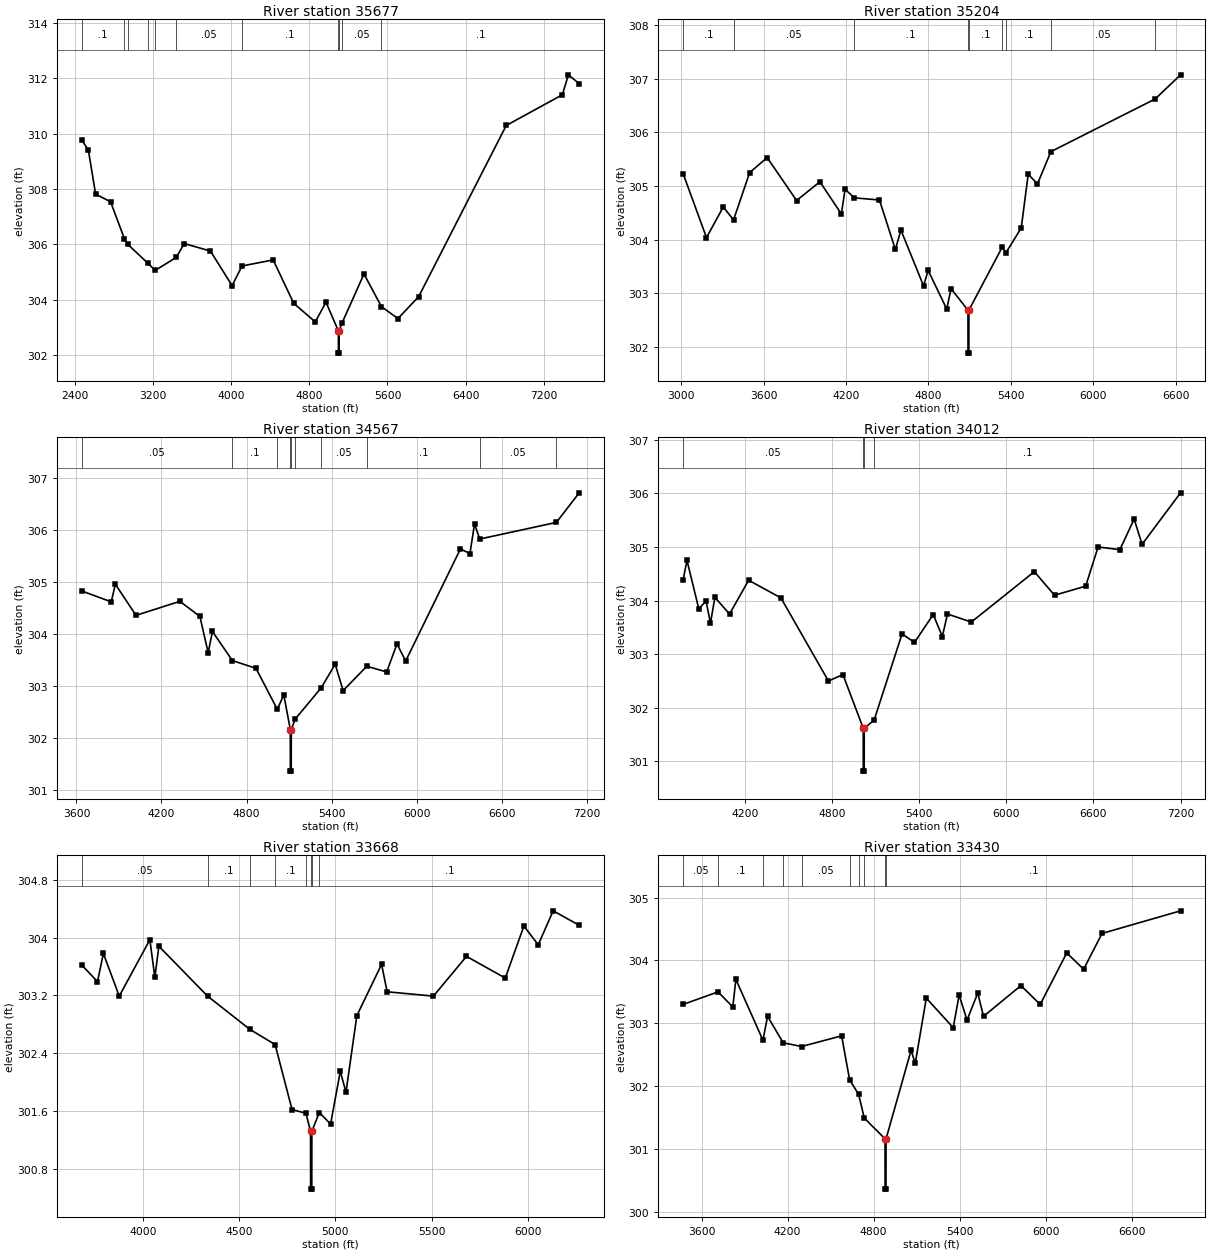
Type RM Length L Ch R = 1,35677,473,473,473
BEGIN DESCRIPTION:
Mapping XS 9ead7796
END DESCRIPTION:
XS GIS Cut Line= 4
      2105497.12     13416214.30      2104778.35     13414880.94
      2103403.35     13414943.44      2103674.18     13417125.72
#Sta/Elev= 30
  2472.1  309.77  2539.5  309.41  2613.4  307.82  2766.7  307.54  2908.0  306.21
  2940.2  306.01  3151.3  305.31  3222.9  305.06  3438.7  305.53  3520.9  306.03
  3788.6  305.76  4010.2  304.51  4111.8  305.22  4430.7  305.44  4640.9  303.87
  4861.1  303.20  4971.2  303.91  5097.9  302.87  5098.4  302.07  5104.3  302.07
  5104.8  302.87  5135.4  303.16  5359.9  304.93  5538.7  303.75  5707.5  303.32
  5919.1  304.11  6815.9  310.30  7390.3  311.41  7451.5  312.13  7562.3  311.81
#Mann=11,-1,0
  2472.1     0.1       0  2908.0    0.05       0  2940.2     0.1       0
  3151.3    0.05       0  3222.9     0.1       0  3438.7    0.05       0
  4111.8     0.1       0  5097.9    0.07       0  5104.8     0.1       0
  5135.4    0.05       0  5538.7     0.1       0
Bank Sta=5097.9,5104.8
Exp/Cntr=0.3,0.1

Type RM Length L Ch R = 1,35204,637,637,637
BEGIN DESCRIPTION:
Mapping XS 69d5d619
END DESCRIPTION:
XS GIS Cut Line= 4
      2105543.98     13415615.32      2104903.35     13414802.81
      2103627.31     13414427.81      2102498.56     13414979.18
#Sta/Elev= 30
  3014.1  305.23  3184.2  304.04  3306.1  304.61  3381.2  304.37  3498.4  305.25
  3625.8  305.53  3840.1  304.73  4009.9  305.08  4166.0  304.48  4193.0  304.94
  4260.7  304.78  4443.1  304.74  4559.1  303.82  4599.5  304.18  4764.6  303.14
  4797.5  303.43  4933.0  302.71  4964.3  303.09  5087.5  302.69  5088.0  301.89
  5093.9  301.89  5094.4  302.69  5338.5  303.87  5362.2  303.75  5475.4  304.22
  5526.0  305.22  5593.6  305.04  5691.0  305.64  6450.0  306.62  6635.0  307.07
#Mann=9,-1,0
  3014.1     0.1       0  3381.2    0.05       0  4260.7     0.1       0
  5087.5    0.07       0  5094.4     0.1       0  5338.5    0.05       0
  5362.2     0.1       0  5691.0    0.05       0  6450.0     0.1       0
Bank Sta=5087.5,5094.4
Exp/Cntr=0.3,0.1

Type RM Length L Ch R = 1,34567,555,555,555
BEGIN DESCRIPTION:
Mapping XS 0d31bc63
END DESCRIPTION:
XS GIS Cut Line= 4
      2105314.79     13415255.90      2105007.52     13414547.60
      2104174.18     13414047.60      2102596.02     13414839.29
#Sta/Elev= 30
  3637.7  304.83  3845.5  304.62  3874.5  304.96  4020.2  304.36  4329.5  304.63
  4471.0  304.34  4529.3  303.64  4559.5  304.05  4699.8  303.49  4866.6  303.34
  5017.3  302.55  5063.0  302.83  5108.9  302.16  5109.4  301.36  5115.4  301.36
  5115.9  302.16  5142.7  302.36  5328.4  302.97  5425.4  303.42  5481.6  302.91
  5648.5  303.38  5788.7  303.27  5861.8  303.81  5922.7  303.48  6309.3  305.64
  6376.4  305.55  6408.6  306.12  6445.3  305.83  6986.1  306.15  7147.2  306.72
#Mann=10,-1,0
  3637.7    0.05       0  4699.8     0.1       0  5017.3    0.05       0
  5108.9    0.07       0  5115.9    0.05       0  5142.7     0.1       0
  5328.4    0.05       0  5648.5     0.1       0  6445.3    0.05       0
  6986.1     0.1       0
Bank Sta=5108.9,5115.9
Exp/Cntr=0.3,0.1

Type RM Length L Ch R = 1,34012,344,344,344
BEGIN DESCRIPTION:
Mapping XS 1721ae3a
END DESCRIPTION:
XS GIS Cut Line= 4
      2105340.85     13415141.34      2105226.27     13414360.10
      2104668.97     13413630.94      2103064.81     13414245.52
#Sta/Elev= 30
  3774.5  304.39  3801.1  304.75  3882.0  303.85  3932.5  303.99  3962.8  303.58
  3993.2  304.06  4094.2  303.75  4225.6  304.38  4448.0  304.05  4775.1  302.50
  4874.9  302.62  5014.7  301.62  5015.2  300.82  5021.2  300.82  5021.7  301.62
  5089.6  301.77  5282.1  303.38  5367.3  303.22  5496.8  303.74  5559.4  303.33
  5594.8  303.75  5759.0  303.60  6192.9  304.54  6332.1  304.10  6546.5  304.27
  6631.9  305.00  6781.9  304.95  6880.2  305.52  6934.9  305.05  7199.7  306.01
#Mann=4,-1,0
  3774.5    0.05       0  5014.7    0.03       0  5021.7    0.05       0
  5089.6     0.1       0
Bank Sta=5014.7,5021.7
Exp/Cntr=0.3,0.1

Type RM Length L Ch R = 1,33668,238,238,238
BEGIN DESCRIPTION:
Mapping XS 4cf73d39
END DESCRIPTION:
XS GIS Cut Line= 4
      2105356.48     13414964.27      2105533.56     13414235.10
      2105038.77     13413537.19      2104085.63     13413771.56
#Sta/Elev= 30
  3680.6  303.62  3762.2  303.39  3793.0  303.78  3875.4  303.19  4034.7  303.97
  4060.6  303.45  4081.6  303.88  4334.9  303.19  4554.8  302.73  4686.2  302.52
  4774.3  301.62  4846.6  301.57  4870.4  301.32  4870.9  300.52  4876.9  300.52
  4877.4  301.32  4916.1  301.58  4974.8  301.42  5025.3  302.15  5054.8  301.86
  5111.4  302.92  5240.1  303.63  5268.9  303.25  5509.7  303.19  5681.7  303.74
  5883.5  303.44  5980.3  304.16  6054.8  303.90  6132.7  304.37  6268.0  304.17
#Mann=8,-1,0
  3680.6    0.05       0  4334.9     0.1       0  4554.8    0.05       0
  4686.2     0.1       0  4846.6    0.05       0  4870.4    0.07       0
  4877.4    0.05       0  4916.1     0.1       0
Bank Sta=4870.4,4877.4
Exp/Cntr=0.3,0.1

Type RM Length L Ch R = 1,33430,34,34,34
BEGIN DESCRIPTION:
Mapping XS d865d501
END DESCRIPTION:
XS GIS Cut Line= 4
      2105408.56     13414953.84      2105710.64     13414042.40
      2105148.14     13413328.85      2103653.32     13413896.57
#Sta/Elev= 30
  3471.8  303.30  3715.0  303.50  3818.2  303.26  3839.3  303.70  4028.1  302.73
  4060.5  303.11  4169.1  302.69  4297.3  302.63  4576.8  302.80  4632.4  302.10
  4694.9  301.87  4735.0  301.49  4879.5  301.16  4880.0  300.36  4886.0  300.36
  4886.5  301.16  5061.0  302.57  5089.9  302.36  5167.2  303.40  5354.7  302.93
  5396.1  303.45  5450.9  303.05  5525.8  303.48  5566.2  303.11  5826.7  303.60
  5961.2  303.30  6146.2  304.12  6263.9  303.86  6392.3  304.43  6939.6  304.79
#Mann=10,-1,0
  3471.8    0.05       0  3715.0     0.1       0  4028.1    0.05       0
  4169.1     0.1       0  4297.3    0.05       0  4632.4     0.1       0
  4694.9    0.05       0  4735.0     0.1       0  4879.5    0.07       0
  4886.5     0.1       0
Bank Sta=4879.5,4886.5
Exp/Cntr=0.3,0.1

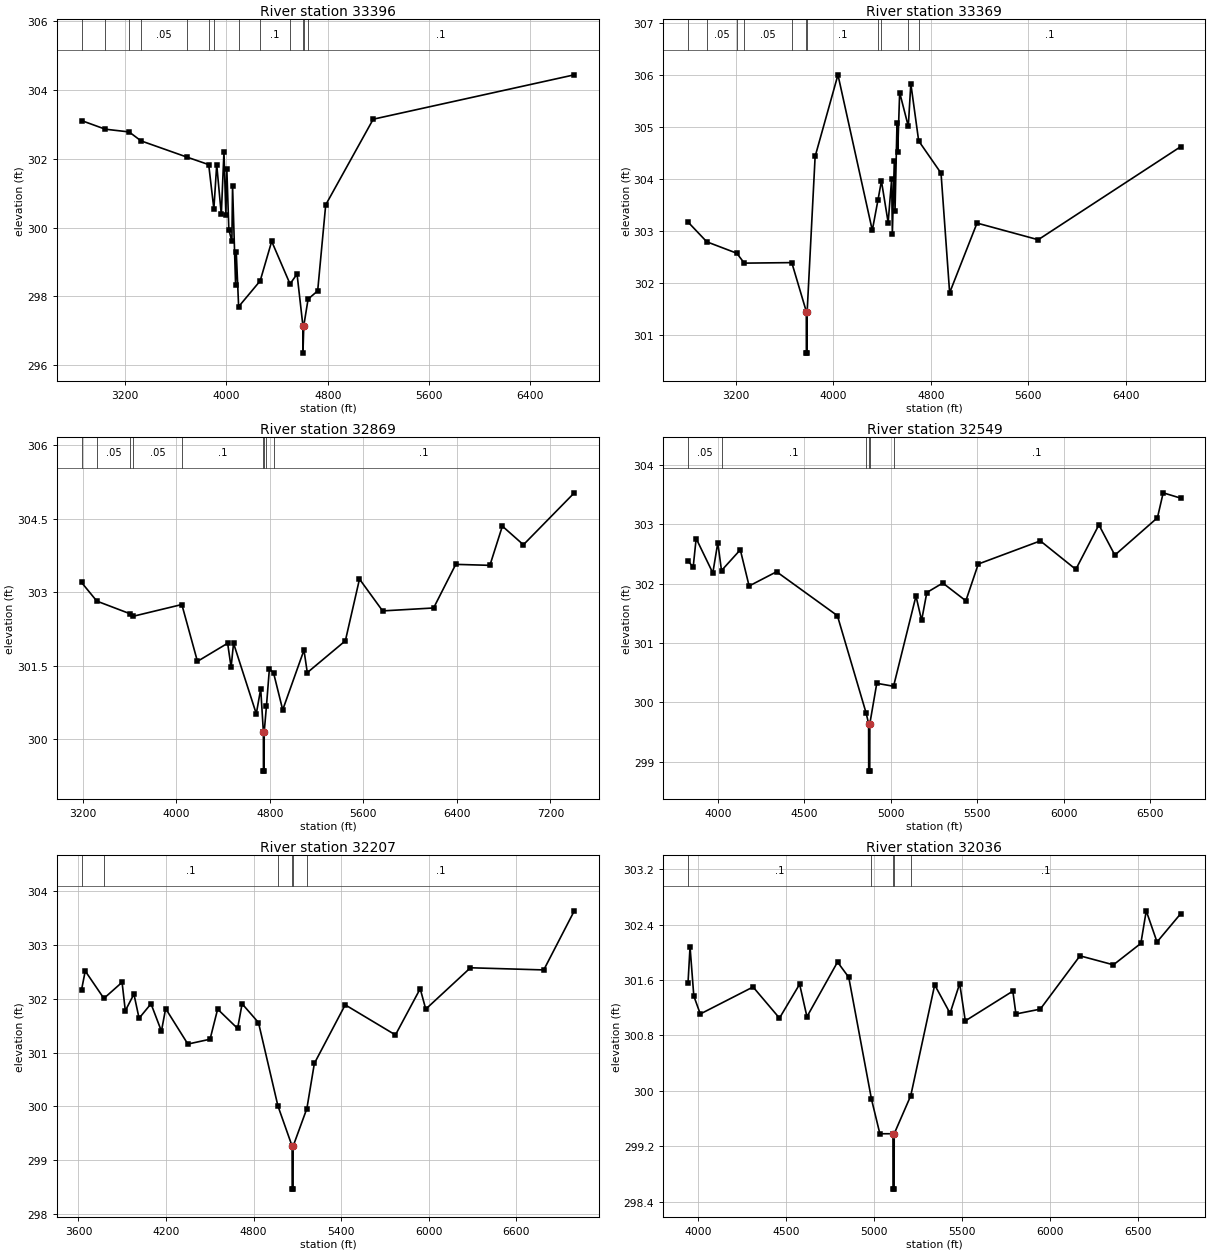
Type RM Length L Ch R = 1,33396,27,27,27
BEGIN DESCRIPTION:
Mapping XS cc32e5ff
END DESCRIPTION:
XS GIS Cut Line= 6
      2105534.43     13414642.21      2105616.89     13413665.66
      2105859.95     13413292.40      2105438.94     13413635.28
      2105130.78     13413288.06      2103863.42     13413804.55
#Sta/Elev= 30
  2854.6  303.11  3041.5  302.86  3230.4  302.78  3324.6  302.52  3686.1  302.05
  3859.3  301.83  3900.2  300.54  3922.7  301.83  3958.9  300.38  3980.0  302.20
  3995.1  300.37  4002.5  301.71  4018.5  299.94  4042.5  299.60  4047.9  301.22
  4071.9  298.33  4077.3  299.28  4095.9  297.70  4266.1  298.45  4357.2  299.60
  4502.1  298.36  4557.5  298.65  4603.7  297.15  4604.2  296.35  4610.8  297.15
  4644.9  297.92  4720.5  298.16  4784.0  300.66  5159.4  303.15  6748.6  304.44
#Mann=13,-1,0
  2854.6     0.1       0  3041.5    0.05       0  3230.4     0.1       0
  3324.6    0.05       0  3686.1     0.1       0  3859.3    0.07       0
  3900.2     0.1       0  4095.9    0.07       0  4266.1     0.1       0
  4502.1    0.07       0  4603.7    0.07       0  4610.8    0.07       0
  4644.9     0.1       0
Bank Sta=4603.7,4610.8
Exp/Cntr=0.3,0.1

Type RM Length L Ch R = 1,33369,500,500,500
BEGIN DESCRIPTION:
Mapping XS b6449aed
END DESCRIPTION:
XS GIS Cut Line= 6
      2105559.61     13414662.15      2105648.14     13413740.31
      2105861.68     13413240.31      2105424.18     13413578.85
      2105122.10     13413245.52      2103794.00     13413797.59
#Sta/Elev= 30
  2806.0  303.18  2960.1  302.80  3206.8  302.58  3268.0  302.39  3658.3  302.40
  3777.5  301.46  3778.0  300.66  3784.0  300.66  3784.6  301.46  3850.0  304.44
  4037.5  306.01  4319.6  303.02  4365.9  303.60  4394.6  303.97  4449.8  303.17
  4478.6  304.01  4484.3  302.95  4500.5  304.36  4506.2  303.39  4522.4  305.08
  4528.1  304.52  4544.3  305.67  4615.3  305.02  4636.0  305.84  4700.5  304.74
  4884.1  304.12  4954.8  301.82  5179.7  303.16  5682.2  302.84  6853.3  304.63
#Mann=11,-1,0
  2806.0     0.1       0  2960.1    0.05       0  3206.8     0.1       0
  3268.0    0.05       0  3658.3     0.1       0  3777.5    0.07       0
  3784.6     0.1       0  4365.9    0.05       0  4394.6     0.1       0
  4615.3    0.07       0  4700.5     0.1       0
Bank Sta=3777.5,3784.6
Exp/Cntr=0.3,0.1

Type RM Length L Ch R = 1,32869,320,320,320
BEGIN DESCRIPTION:
Mapping XS a7c6c210
END DESCRIPTION:
XS GIS Cut Line= 6
      2105570.01     13414667.41      2105898.14     13413209.06
      2105648.14     13413193.44      2105382.52     13413479.90
      2105116.89     13413162.19      2103726.29     13413802.80
#Sta/Elev= 30
  3190.9  303.20  3321.5  302.82  3607.5  302.56  3631.2  302.51  4048.3  302.75
  4181.7  301.59  4439.8  301.96  4469.4  301.47  4490.3  301.96  4684.8  300.52
  4722.6  301.03  4745.4  300.15  4745.9  299.35  4751.9  299.35  4752.5  300.15
  4771.4  300.67  4796.9  301.44  4833.0  301.35  4910.7  300.60  5092.5  301.82
  5120.8  301.36  5446.3  302.01  5567.1  303.27  5764.9  302.62  6200.8  302.68
  6390.0  303.57  6682.0  303.55  6788.6  304.35  6968.5  303.97  7403.7  305.03
#Mann=9,-1,0
  3190.9     0.1       0  3321.5    0.05       0  3607.5     0.1       0
  3631.2    0.05       0  4048.3     0.1       0  4745.4    0.07       0
  4752.5     0.1       0  4771.4    0.05       0  4833.0     0.1       0
Bank Sta=4745.4,4752.5
Exp/Cntr=0.3,0.1

Type RM Length L Ch R = 1,32549,342,342,342
BEGIN DESCRIPTION:
Mapping XS 095186a9
END DESCRIPTION:
XS GIS Cut Line= 4
      2105798.73     13414110.42      2106173.75     13413323.93
      2105902.92     13412964.56      2104413.33     13413303.10
#Sta/Elev= 30
  3827.1  302.38  3857.0  302.28  3874.2  302.76  3970.5  302.18  3999.3  302.69
  4020.7  302.22  4129.4  302.57  4180.3  301.96  4339.2  302.20  4690.7  301.46
  4856.7  299.82  4871.2  299.64  4871.7  298.84  4877.7  298.84  4878.3  299.64
  4918.4  300.32  5015.4  300.27  5145.0  301.79  5177.6  301.38  5207.8  301.85
  5300.1  302.01  5433.4  301.71  5505.2  302.33  5864.1  302.72  6069.2  302.24
  6202.6  302.99  6294.8  302.48  6541.0  303.11  6574.3  303.53  6676.0  303.44
#Mann=6,-1,0
  3827.1    0.05       0  4020.7     0.1       0  4856.7    0.05       0
  4871.2    0.03       0  4878.3    0.05       0  5015.4     0.1       0
Bank Sta=4871.2,4878.3
Exp/Cntr=0.3,0.1

Type RM Length L Ch R = 1,32207,171,171,171
BEGIN DESCRIPTION:
Mapping XS c563d469
END DESCRIPTION:
XS GIS Cut Line= 4
      2105845.61     13414089.59      2106439.37     13413136.43
      2106106.04     13412740.60      2104444.61     13413245.80
#Sta/Elev= 30
  3621.2  302.17  3646.4  302.52  3774.3  302.01  3898.9  302.31  3921.1  301.78
  3980.1  302.09  4015.4  301.64  4097.2  301.91  4168.6  301.40  4197.5  301.82
  4349.7  301.16  4501.9  301.25  4553.8  301.81  4690.7  301.45  4721.4  301.91
  4833.7  301.56  4966.8  300.01  5064.2  299.26  5064.7  298.46  5070.8  298.46
  5071.3  299.26  5165.4  299.96  5216.7  300.80  5428.1  301.89  5772.4  301.33
  5942.0  302.19  5980.1  301.81  6286.3  302.58  6788.8  302.54  6998.2  303.64
#Mann=6,-1,0
  3621.2    0.05       0  3774.3     0.1       0  4966.8    0.05       0
  5064.2    0.03       0  5071.3    0.05       0  5165.4     0.1       0
Bank Sta=5064.2,5071.3
Exp/Cntr=0.3,0.1

Type RM Length L Ch R = 1,32036,247,247,247
BEGIN DESCRIPTION:
Mapping XS fcfc0f15
END DESCRIPTION:
XS GIS Cut Line= 4
      2106194.61     13413631.19      2106632.08     13413053.10
      2106132.08     13412558.31      2104845.62     13413027.06
#Sta/Elev= 30
  3942.8  301.56  3954.3  302.08  3975.6  301.37  4012.5  301.11  4312.1  301.50
  4462.0  301.05  4576.4  301.54  4618.0  301.07  4791.6  301.86  4855.3  301.64
  4984.3  299.88  5032.0  299.38  5106.3  299.38  5106.8  298.58  5112.9  298.58
  5113.4  299.38  5207.4  299.93  5343.2  301.53  5430.6  301.12  5485.2  301.55
  5517.0  301.01  5786.8  301.44  5804.5  301.11  5942.8  301.18  6168.2  301.95
  6357.9  301.82  6513.8  302.13  6544.3  302.60  6605.5  302.15  6740.4  302.56
#Mann=5,-1,0
  3942.8     0.1       0  4984.3    0.05       0  5106.3    0.03       0
  5113.4    0.05       0  5207.4     0.1       0
Bank Sta=5106.3,5113.4
Exp/Cntr=0.3,0.1