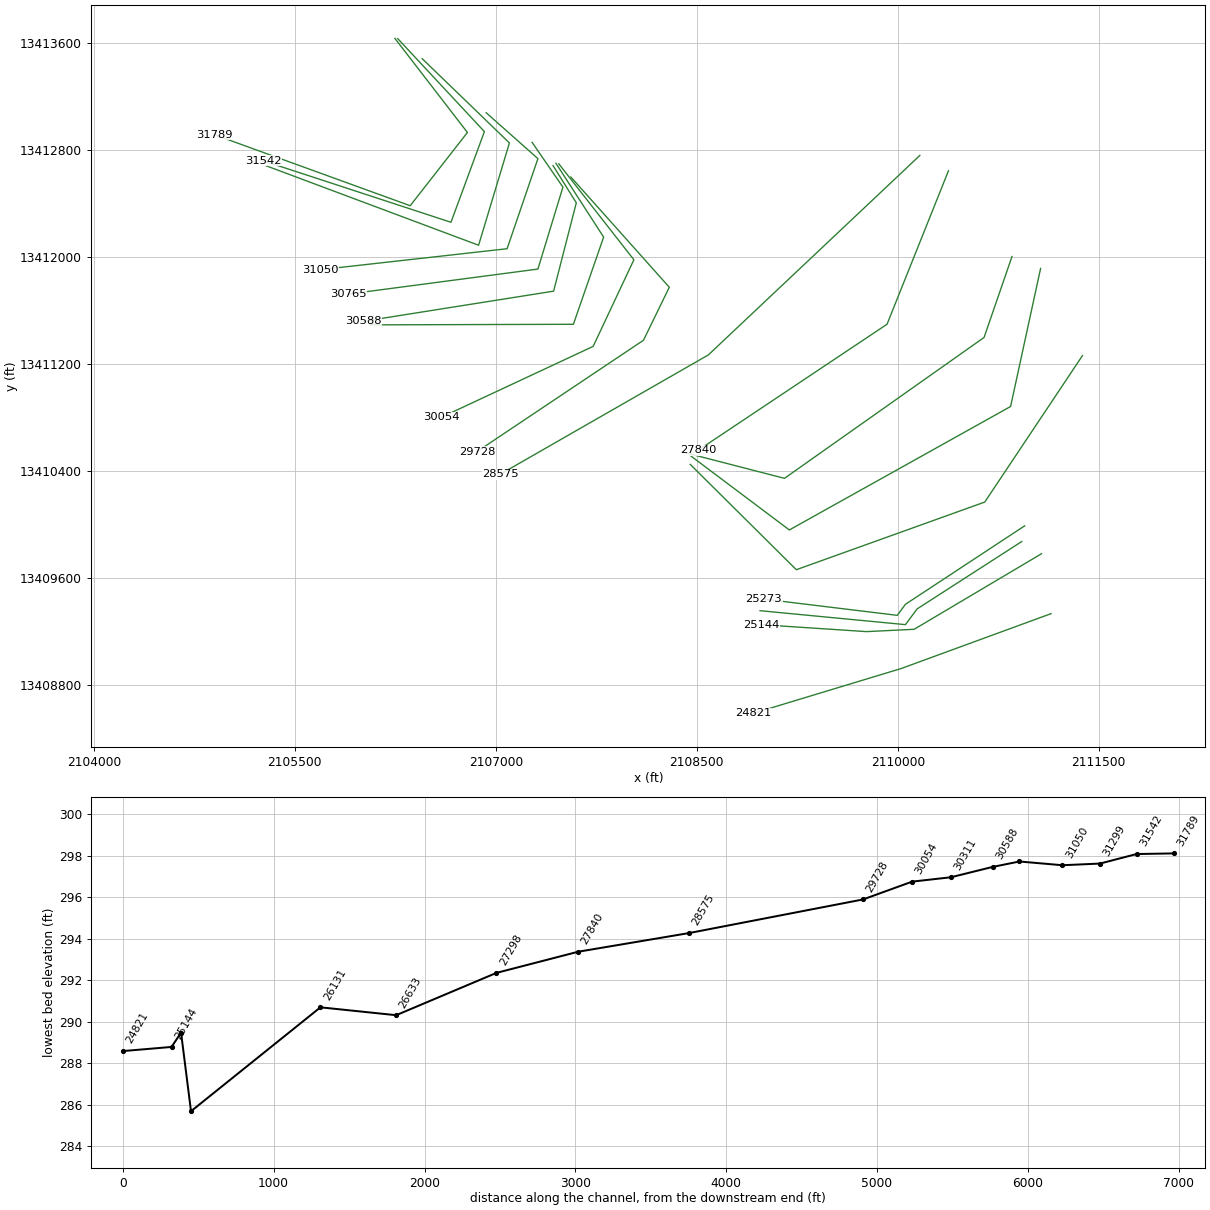
HEC-RAS study UNT 006 in La Jarita Watershed.prj: UNT 006 in La Jarita Watershed Base Level Engineering

--- UNT 006 in La Jarita Watershed.g01 (geometry) --- (continued)

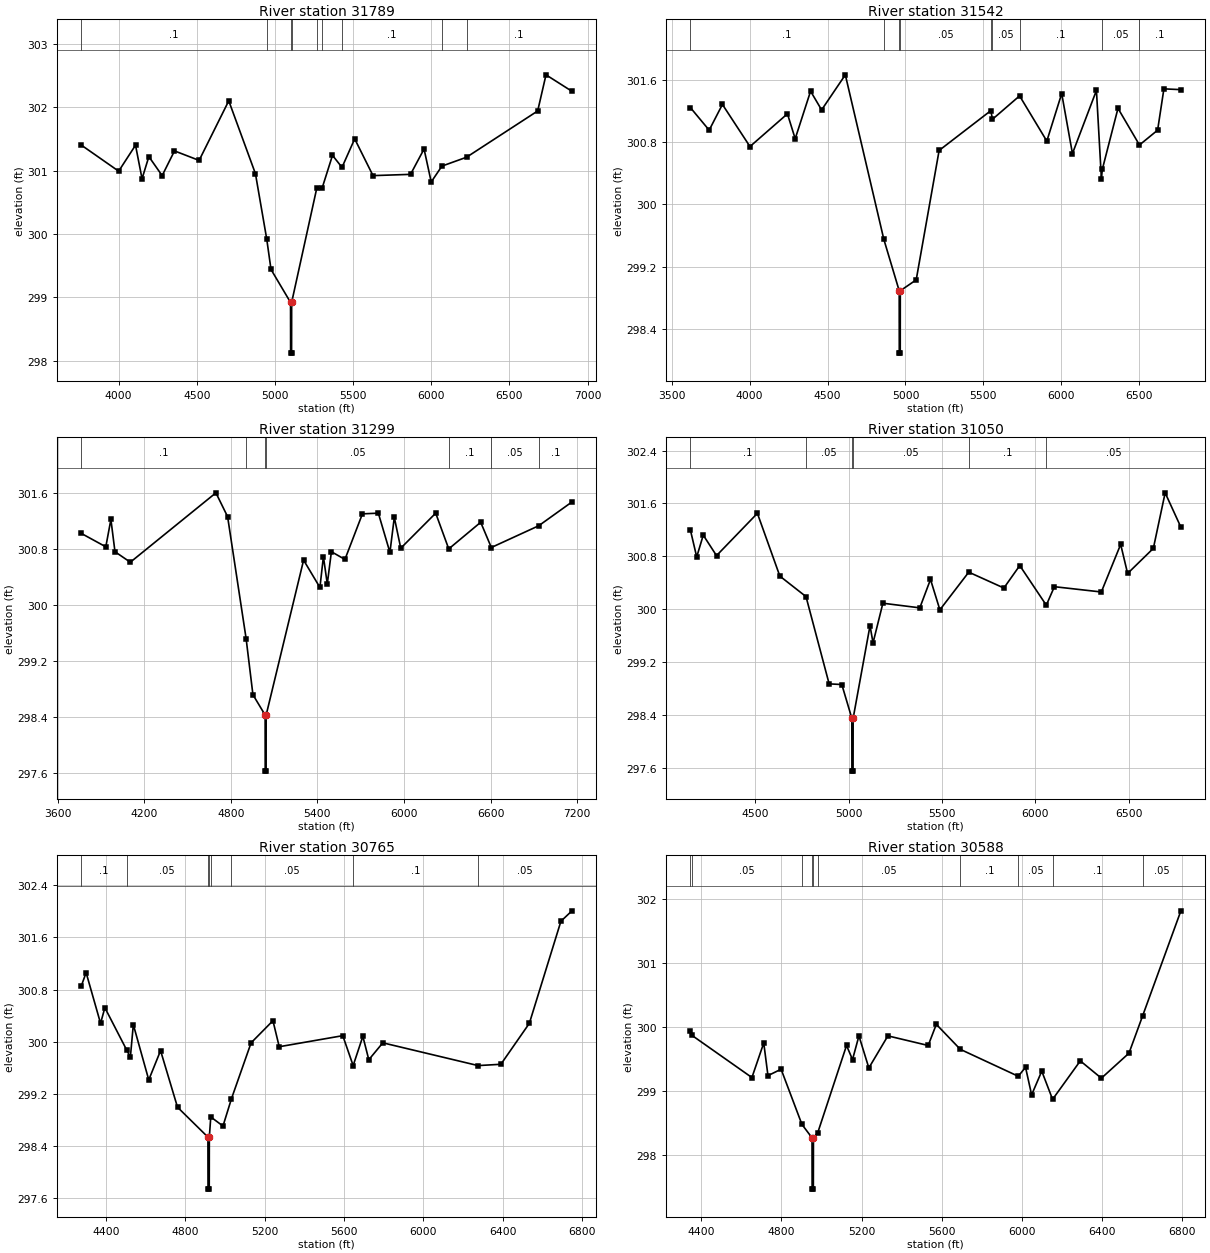
Type RM Length L Ch R = 1,31789,247,247,247
BEGIN DESCRIPTION:
Mapping XS e3c51141
END DESCRIPTION:
XS GIS Cut Line= 4
      2106246.70     13413631.19      2106788.33     13412928.10
      2106361.25     13412381.23      2104898.82     13412912.07
#Sta/Elev= 30
  3762.6  301.40  4000.7  300.99  4108.5  301.40  4150.2  300.87  4193.7  301.22
  4278.8  300.92  4357.7  301.31  4515.2  301.16  4704.8  302.10  4875.5  300.95
  4947.6  299.92  4975.0  299.44  5099.9  298.92  5100.4  298.12  5106.5  298.12
  5107.0  298.92  5267.5  300.72  5301.5  300.72  5368.2  301.24  5429.0  301.05
  5510.2  301.50  5627.3  300.92  5867.3  300.94  5953.8  301.34  5999.6  300.82
  6067.9  301.07  6225.4  301.21  6680.5  301.94  6733.7  302.51  6899.8  302.25
#Mann=9,-1,0
  3762.6     0.1       0  4947.6    0.05       0  5099.9    0.03       0
  5107.0    0.05       0  5267.5     0.1       0  5301.5    0.05       0
  5429.0     0.1       0  6067.9    0.05       0  6225.4     0.1       0
Bank Sta=5099.9,5107
Exp/Cntr=0.3,0.1

Type RM Length L Ch R = 1,31542,243,243,243
BEGIN DESCRIPTION:
Mapping XS 653a609c
END DESCRIPTION:
XS GIS Cut Line= 4
      2106268.37     13413629.05      2106915.07     13412934.61
      2106665.50     13412257.53      2105261.39     13412717.61
#Sta/Elev= 30
  3619.3  301.24  3740.0  300.95  3825.0  301.28  4001.9  300.74  4242.3  301.16
  4292.1  300.84  4390.8  301.45  4461.6  301.21  4613.8  301.66  4860.9  299.55
  4959.6  298.89  4960.1  298.09  4966.2  298.09  4966.7  298.89  5068.7  299.03
  5215.8  300.69  5547.4  301.20  5558.3  301.09  5732.2  301.39  5907.0  300.81
  6002.5  301.42  6071.4  300.65  6225.4  301.46  6257.2  300.33  6263.5  300.45
  6363.7  301.23  6501.5  300.76  6618.0  300.95  6658.4  301.48  6767.4  301.47
#Mann=9,-1,0
  3619.3     0.1       0  4860.9    0.05       0  4959.6    0.03       0
  4966.7    0.05       0  5547.4     0.1       0  5558.3    0.05       0
  5732.2     0.1       0  6263.5    0.05       0  6501.5     0.1       0
Bank Sta=4959.6,4966.7
Exp/Cntr=0.3,0.1

Type RM Length L Ch R = 1,31299,249,249,249
BEGIN DESCRIPTION:
Mapping XS e7097e25
END DESCRIPTION:
XS GIS Cut Line= 4
      2106450.68     13413479.30      2107101.70     13412849.98
      2106871.67     13412086.09      2105284.08     13412680.35
#Sta/Elev= 30
  3765.1  301.02  3933.9  300.83  3969.2  301.22  3997.4  300.76  4103.7  300.61
  4696.7  301.60  4777.7  301.26  4906.0  299.52  4953.2  298.72  5037.7  298.43
  5038.2  297.63  5044.3  297.63  5044.8  298.43  5304.2  300.64  5417.3  300.25
  5441.4  300.69  5468.3  300.30  5496.8  300.76  5590.6  300.65  5711.7  301.30
  5822.1  301.31  5902.3  300.75  5932.6  301.25  5977.3  300.81  6219.4  301.31
  6309.8  300.80  6531.1  301.18  6604.8  300.82  6932.9  301.13  7163.5  301.47
#Mann=7,-1,0
  3765.1     0.1       0  4906.0    0.05       0  5037.7    0.03       0
  5044.8    0.05       0  6309.8     0.1       0  6604.8    0.05       0
  6932.9     0.1       0
Bank Sta=5037.7,5044.8
Exp/Cntr=0.3,0.1

Type RM Length L Ch R = 1,31050,285,285,285
BEGIN DESCRIPTION:
Mapping XS c0a0a6ab
END DESCRIPTION:
XS GIS Cut Line= 4
      2106928.11     13413075.66      2107314.37     13412732.79
      2107084.34     13412060.05      2105691.15     13411903.80
#Sta/Elev= 30
  4151.3  301.20  4185.3  300.79  4220.4  301.12  4291.5  300.81  4510.6  301.45
  4631.0  300.50  4771.2  300.19  4895.2  298.87  4963.1  298.86  5016.8  298.35
  5017.3  297.55  5023.4  297.55  5023.9  298.35  5114.3  299.75  5130.5  299.49
  5183.3  300.09  5381.2  300.02  5438.5  300.45  5488.8  299.99  5643.6  300.56
  5831.9  300.32  5917.0  300.66  6059.3  300.06  6102.6  300.34  6354.2  300.26
  6457.9  300.98  6495.1  300.54  6633.1  300.92  6696.3  301.76  6780.7  301.24
#Mann=6,-1,0
  4151.3     0.1       0  4771.2    0.05       0  5016.8    0.03       0
  5023.9    0.05       0  5643.6     0.1       0  6059.3    0.05       0
Bank Sta=5016.8,5023.9
Exp/Cntr=0.3,0.1

Type RM Length L Ch R = 1,30765,177,177,177
BEGIN DESCRIPTION:
Mapping XS faf3d356
END DESCRIPTION:
XS GIS Cut Line= 4
      2107270.97     13412854.32      2107501.01     13412520.12
      2107314.37     13411908.14      2105899.75     13411721.54
#Sta/Elev= 30
  4277.2  300.86  4300.7  301.06  4373.5  300.28  4395.3  300.52  4505.1  299.87
  4523.8  299.76  4538.7  300.26  4616.5  299.41  4676.0  299.86  4761.4  298.99
  4914.7  298.53  4915.2  297.73  4921.3  297.73  4921.8  298.53  4929.1  298.84
  4990.6  298.70  5033.3  299.12  5132.3  299.98  5242.4  300.32  5274.1  299.92
  5594.4  300.09  5646.7  299.63  5695.6  300.08  5725.6  299.72  5796.2  299.98
  6276.3  299.63  6391.3  299.65  6534.8  300.28  6693.9  301.85  6749.6  302.01
#Mann=8,-1,0
  4277.2     0.1       0  4505.1    0.05       0  4914.7    0.07       0
  4921.8    0.05       0  4929.1     0.1       0  5033.3    0.05       0
  5646.7     0.1       0  6276.3    0.05       0
Bank Sta=4914.7,4921.8
Exp/Cntr=0.3,0.1

Type RM Length L Ch R = 1,30588,277,277,277
BEGIN DESCRIPTION:
Mapping XS 77c8cabd
END DESCRIPTION:
XS GIS Cut Line= 4
      2107427.23     13412680.70      2107600.83     13412402.93
      2107431.56     13411743.21      2106008.98     13411517.67
#Sta/Elev= 30
  4345.1  299.94  4352.1  299.87  4652.4  299.21  4711.5  299.75  4732.5  299.24
  4798.1  299.34  4902.0  298.48  4952.5  298.27  4953.0  297.47  4959.1  297.47
  4959.6  298.27  4981.1  298.35  5124.8  299.71  5154.7  299.49  5186.7  299.86
  5236.2  299.36  5331.3  299.86  5532.5  299.71  5573.0  300.04  5692.9  299.65
  5982.1  299.23  6018.5  299.37  6048.9  298.94  6099.5  299.31  6153.5  298.87
  6291.9  299.47  6397.1  299.20  6534.9  299.59  6602.8  300.17  6794.1  301.81
#Mann=10,-1,0
  4345.1     0.1       0  4352.1    0.05       0  4902.0     0.1       0
  4952.5    0.03       0  4959.6     0.1       0  4981.1    0.05       0
  5692.9     0.1       0  5982.1    0.05       0  6153.5     0.1       0
  6602.8    0.05       0
Bank Sta=4952.5,4959.6
Exp/Cntr=0.3,0.1

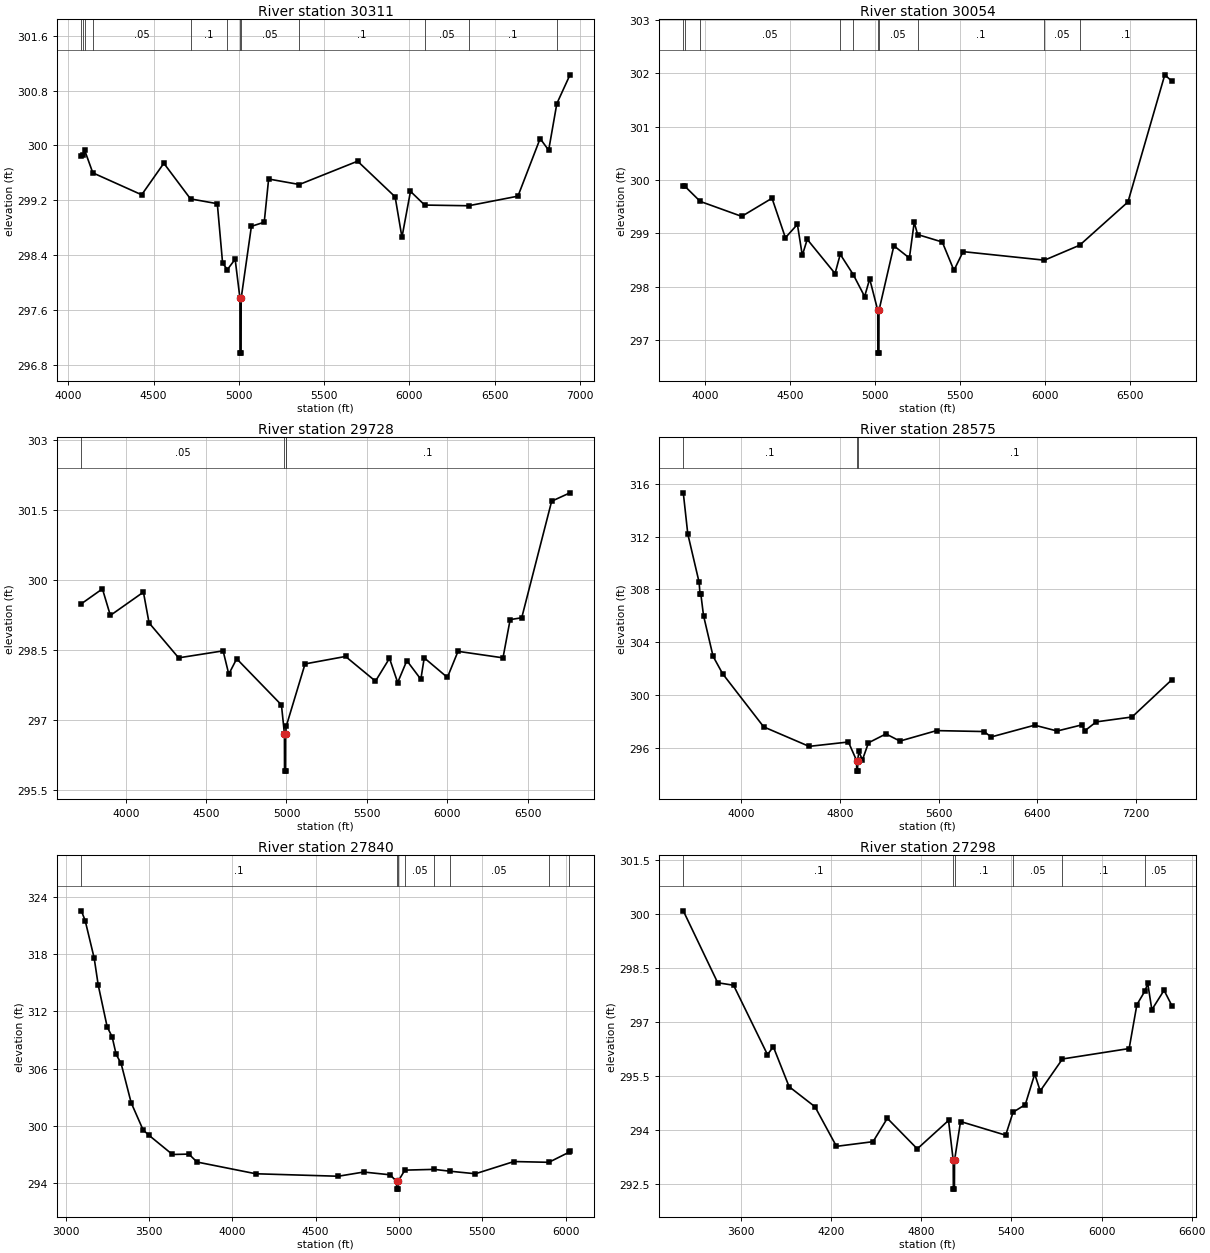
Type RM Length L Ch R = 1,30311,257,257,257
BEGIN DESCRIPTION:
Mapping XS 49010b05
END DESCRIPTION:
XS GIS Cut Line= 4
      2107448.91     13412698.09      2107804.83     13412146.85
      2107579.13     13411495.81      2106060.04     13411491.47
#Sta/Elev= 30
  4076.8  299.85  4086.7  299.86  4096.2  299.93  4144.0  299.60  4430.4  299.28
  4560.3  299.74  4716.7  299.22  4873.8  299.15  4904.9  298.28  4933.1  298.19
  4978.3  298.34  5006.5  297.77  5007.0  296.97  5013.1  296.97  5013.6  297.77
  5073.6  298.82  5148.8  298.88  5174.6  299.51  5354.8  299.43  5696.1  299.77
  5916.1  299.25  5956.1  298.66  6006.1  299.33  6089.4  299.13  6347.0  299.12
  6636.1  299.26  6766.1  300.10  6816.1  299.93  6864.0  300.61  6941.1  301.03
#Mann=12,-1,0
  4076.8     0.1       0  4086.7    0.05       0  4096.2     0.1       0
  4144.0    0.05       0  4716.7     0.1       0  4933.1    0.05       0
  5006.5    0.03       0  5013.6    0.05       0  5354.8     0.1       0
  6089.4    0.05       0  6347.0     0.1       0  6864.0    0.05       0
Bank Sta=5006.5,5013.6
Exp/Cntr=0.3,0.1

Type RM Length L Ch R = 1,30054,326,326,326
BEGIN DESCRIPTION:
Mapping XS 55df7237
END DESCRIPTION:
XS GIS Cut Line= 4
      2107470.60     13412693.76      2108030.52     13411977.58
      2107726.70     13411330.88      2106593.85     13410801.35
#Sta/Elev= 30
  3873.4  299.88  3883.9  299.88  3973.2  299.60  4217.1  299.32  4395.3  299.66
  4474.0  298.92  4544.6  299.17  4573.4  298.59  4602.4  298.89  4766.1  298.25
  4796.6  298.61  4873.2  298.23  4940.0  297.82  4969.7  298.15  5017.3  297.56
  5017.8  296.76  5023.9  296.76  5024.4  297.56  5112.1  298.77  5203.3  298.54
  5231.7  299.21  5251.7  298.98  5396.8  298.84  5465.3  298.31  5519.1  298.66
  5997.8  298.50  6204.7  298.78  6488.9  299.59  6705.5  301.97  6747.5  301.85
#Mann=10,-1,0
  3873.4    0.05       0  3883.9     0.1       0  3973.2    0.05       0
  4796.6     0.1       0  4873.2    0.05       0  5017.3    0.03       0
  5024.4    0.05       0  5251.7     0.1       0  5997.8    0.05       0
  6204.7     0.1       0
Bank Sta=5017.3,5024.4
Exp/Cntr=0.3,0.1

Type RM Length L Ch R = 1,29728,1153,1153,1153
BEGIN DESCRIPTION:
Mapping XS daf15fd4
END DESCRIPTION:
XS GIS Cut Line= 4
      2107560.50     13412595.31      2108294.84     13411772.43
      2108102.13     13411376.60      2106858.71     13410544.18
#Sta/Elev= 30
  3724.2  299.49  3855.3  299.81  3904.6  299.24  4110.3  299.74  4145.4  299.08
  4329.3  298.33  4606.0  298.48  4641.2  297.98  4690.5  298.31  4968.8  297.32
  4987.5  296.70  4988.0  295.90  4994.1  295.90  4994.7  296.70  4998.5  296.86
  5115.7  298.20  5367.6  298.36  5553.8  297.83  5640.9  298.32  5691.9  297.80
  5748.9  298.27  5836.0  297.87  5857.0  298.33  6001.1  297.91  6067.2  298.47
  6347.0  298.33  6391.4  299.15  6463.5  299.19  6649.6  301.69  6763.7  301.87
#Mann=4,-1,0
  3724.2    0.05       0  4987.5    0.07       0  4994.7    0.05       0
  4998.5     0.1       0
Bank Sta=4987.5,4994.7
Exp/Cntr=0.3,0.1

Type RM Length L Ch R = 1,28575,735,735,735
BEGIN DESCRIPTION:
Mapping XS fce7d4ab
END DESCRIPTION:
XS GIS Cut Line= 3
      2110164.61     13412756.78      2108586.51     13411267.22
      2107034.45     13410376.61
#Sta/Elev= 30
  3531.4  315.30  3567.8  312.20  3659.7  308.54  3666.9  307.68  3673.8  307.64
  3695.3  306.03  3772.9  302.95  3850.6  301.63  4183.2  297.62  4550.9  296.15
  4869.3  296.48  4935.7  295.08  4936.5  294.28  4943.7  294.28  4944.5  295.08
  4954.3  295.77  4982.6  295.12  5031.9  296.42  5173.5  297.09  5286.8  296.55
  5583.8  297.34  5968.4  297.27  6026.0  296.86  6378.3  297.75  6561.0  297.31
  6759.5  297.77  6787.0  297.34  6877.4  298.00  7167.9  298.37  7490.9  301.19
#Mann=3,-1,0
  3531.4     0.1       0  4935.7    0.07       0  4944.5     0.1       0
Bank Sta=4935.7,4944.5
Exp/Cntr=0.3,0.1

Type RM Length L Ch R = 1,27840,542,542,542
BEGIN DESCRIPTION:
Mapping XS 2fdc7b55
END DESCRIPTION:
XS GIS Cut Line= 3
      2110378.19     13412642.25      2109919.84     13411496.39
      2108509.18     13410554.21
#Sta/Elev= 30
  3094.7  322.54  3117.7  321.51  3171.6  317.59  3195.8  314.77  3249.6  310.38
  3279.3  309.34  3303.5  307.49  3333.1  306.55  3393.3  302.44  3465.1  299.58
  3501.0  299.01  3641.0  297.01  3739.7  297.05  3788.2  296.22  4140.9  294.99
  4635.3  294.73  4788.0  295.17  4947.2  294.88  4984.9  294.18  4985.7  293.38
  4992.9  293.38  4993.7  294.18  5034.8  295.37  5211.2  295.45  5303.4  295.26
  5457.8  294.99  5689.1  296.27  5898.5  296.19  6017.5  297.23  6025.2  297.40
#Mann=8,-1,0
  3094.7     0.1       0  4984.9    0.07       0  4993.7     0.1       0
  5034.8    0.05       0  5211.2     0.1       0  5303.4    0.05       0
  5898.5     0.1       0  6017.5    0.05       0
Bank Sta=4984.9,4993.7
Exp/Cntr=0.3,0.1

Type RM Length L Ch R = 1,27298,665,665,665
BEGIN DESCRIPTION:
Mapping XS dc312bb5
END DESCRIPTION:
XS GIS Cut Line= 4
      2110852.12     13412001.56      2110643.80     13411397.43
      2109154.22     13410345.35      2108389.26     13410543.09
#Sta/Elev= 30
  3215.9  300.10  3445.0  298.10  3550.7  298.03  3776.4  296.10  3815.2  296.32
  3920.3  295.21  4092.7  294.65  4235.5  293.55  4479.2  293.68  4574.1  294.33
  4773.5  293.48  4981.6  294.27  5012.8  293.16  5013.6  292.36  5020.8  292.36
  5021.6  293.16  5061.6  294.24  5362.0  293.86  5411.3  294.50  5492.5  294.71
  5555.3  295.56  5591.9  295.09  5740.1  295.98  6183.9  296.27  6235.5  297.49
  6289.1  297.87  6307.8  298.08  6335.1  297.35  6416.3  297.89  6468.7  297.46
#Mann=6,-1,0
  3215.9     0.1       0  5012.8    0.07       0  5021.6     0.1       0
  5411.3    0.05       0  5740.1     0.1       0  6289.1    0.05       0
Bank Sta=5012.8,5021.6
Exp/Cntr=0.3,0.1

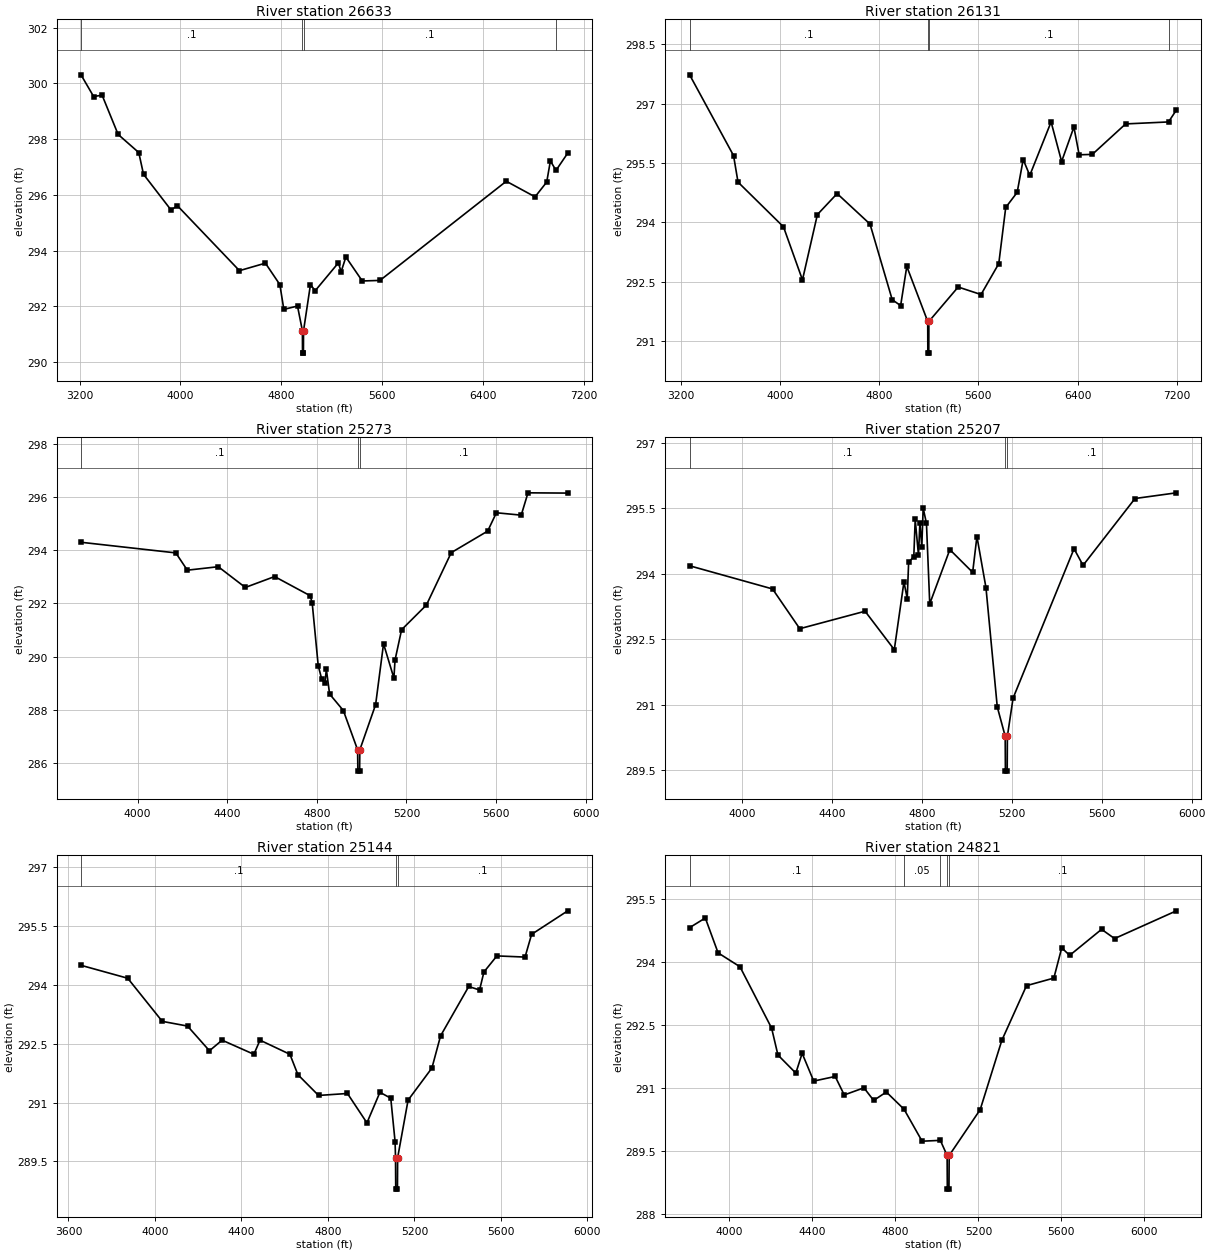
Type RM Length L Ch R = 1,26633,502,502,502
BEGIN DESCRIPTION:
Mapping XS f94cfa06
END DESCRIPTION:
XS GIS Cut Line= 4
      2111065.67     13411913.01      2110841.72     13410881.81
      2109190.68     13409959.93      2108457.63     13410511.01
#Sta/Elev= 30
  3210.7  300.31  3311.0  299.53  3378.1  299.58  3505.4  298.17  3669.2  297.52
  3706.8  296.74  3925.0  295.46  3976.1  295.61  4468.3  293.28  4674.3  293.55
  4789.0  292.78  4820.6  291.89  4929.1  292.01  4968.1  291.12  4968.9  290.32
  4976.1  290.32  4976.9  291.12  5031.9  292.78  5069.6  292.56  5253.6  293.56
  5275.3  293.24  5313.0  293.77  5443.2  292.91  5583.7  292.93  6586.4  296.49
  6814.6  295.93  6907.2  296.46  6936.3  297.22  6980.9  296.88  7074.0  297.50
#Mann=4,-1,0
  3210.7     0.1       0  4968.1    0.07       0  4976.9     0.1       0
  6980.9    0.05       0
Bank Sta=4968.1,4976.9
Exp/Cntr=0.3,0.1

Type RM Length L Ch R = 1,26131,858,858,858
BEGIN DESCRIPTION:
Mapping XS c086f2cc
END DESCRIPTION:
XS GIS Cut Line= 4
      2111378.20     13411262.05      2110649.01     13410168.26
      2109242.76     13409663.06      2108451.11     13410449.49
#Sta/Elev= 30
  3271.8  297.73  3626.0  295.69  3662.0  295.02  4028.6  293.89  4181.7  292.55
  4302.0  294.20  4461.2  294.73  4726.3  293.96  4905.3  292.05  4973.2  291.90
  5022.9  292.89  5191.7  291.50  5192.6  290.70  5200.1  290.70  5201.0  291.50
  5437.2  292.37  5621.5  292.18  5764.5  292.96  5820.7  294.38  5912.9  294.76
  5961.4  295.59  6014.5  295.19  6186.5  296.54  6271.3  295.54  6370.3  296.41
  6412.8  295.71  6518.8  295.72  6787.5  296.49  7133.3  296.54  7196.5  296.84
#Mann=4,-1,0
  3271.8     0.1       0  5191.7    0.07       0  5201.0     0.1       0
  7133.3    0.05       0
Bank Sta=5191.7,5201
Exp/Cntr=0.3,0.1

Type RM Length L Ch R = 1,25273,66,66,66
BEGIN DESCRIPTION:
Mapping XS facd8223
END DESCRIPTION:
XS GIS Cut Line= 4
      2110946.71     13409990.65      2110056.96     13409404.71
      2109996.19     13409322.25      2108998.95     13409443.65
#Sta/Elev= 30
  3747.3  294.30  4170.5  293.90  4221.8  293.25  4360.0  293.38  4480.7  292.60
  4611.4  293.01  4769.9  292.29  4779.0  292.03  4806.0  289.66  4821.4  289.16
  4836.1  289.01  4842.3  289.52  4856.9  288.59  4918.2  287.97  4981.9  286.49
  4982.9  285.69  4990.8  285.69  4991.7  286.49  5062.2  288.19  5097.6  290.48
  5143.8  289.19  5148.9  289.87  5178.2  291.01  5289.0  291.94  5399.8  293.91
  5562.3  294.72  5601.3  295.41  5712.1  295.32  5742.3  296.16  5919.7  296.15
#Mann=3,-1,0
  3747.3     0.1       0  4981.9    0.07       0  4991.7     0.1       0
Bank Sta=4981.9,4991.7
Exp/Cntr=0.3,0.1

Type RM Length L Ch R = 1,25207,63,63,63
BEGIN DESCRIPTION:
Mapping XS ea15b129
END DESCRIPTION:
XS GIS Cut Line= 4
      2110925.00     13409873.46      2110143.76     13409369.99
      2110056.96     13409252.80      2108971.90     13409356.97
#Sta/Elev= 30
  3766.7  294.18  4135.5  293.65  4256.7  292.74  4547.2  293.14  4677.2  292.26
  4720.1  293.81  4734.7  293.43  4741.0  294.26  4764.0  294.39  4770.2  295.24
  4784.8  294.42  4791.1  295.17  4799.5  294.62  4805.7  295.50  4820.3  295.15
  4834.9  293.31  4924.3  294.55  5025.8  294.03  5044.8  294.85  5085.0  293.68
  5135.3  290.95  5170.5  290.28  5171.5  289.48  5179.4  289.48  5180.3  290.28
  5205.6  291.15  5476.8  294.57  5517.0  294.19  5748.1  295.72  5932.0  295.85
#Mann=3,-1,0
  3766.7     0.1       0  5170.5    0.07       0  5180.3     0.1       0
Bank Sta=5170.5,5180.3
Exp/Cntr=0.3,0.1

Type RM Length L Ch R = 1,25144,323,323,323
BEGIN DESCRIPTION:
Mapping XS 4d19aace
END DESCRIPTION:
XS GIS Cut Line= 4
      2111072.54     13409782.30      2110122.06     13409218.08
      2109766.16     13409200.72      2108978.12     13409252.68
#Sta/Elev= 30
  3657.9  294.50  3874.0  294.17  4033.8  293.07  4150.7  292.95  4252.0  292.32
  4310.5  292.59  4457.5  292.23  4485.9  292.59  4624.2  292.23  4661.2  291.71
  4756.7  291.18  4890.4  291.23  4980.5  290.48  5040.6  291.26  5090.7  291.11
  5110.7  290.00  5112.7  289.59  5113.7  288.79  5121.6  288.79  5122.5  289.59
  5170.8  291.06  5281.1  291.88  5321.1  292.70  5451.4  293.96  5501.5  293.87
  5521.6  294.33  5581.7  294.74  5711.8  294.71  5742.1  295.29  5909.3  295.89
#Mann=3,-1,0
  3657.9     0.1       0  5112.7    0.07       0  5122.5     0.1       0
Bank Sta=5112.7,5122.5
Exp/Cntr=0.3,0.1

Type RM Length L Ch R = 1,24821,806,806,806
BEGIN DESCRIPTION:
UNT 006 in La Jarita Watershed 20.0
END DESCRIPTION:
XS GIS Cut Line= 3
      2111143.82     13409334.94      2110025.00     13408925.00
      2108919.97     13408590.18
#Sta/Elev= 30
  3807.9  294.81  3883.5  295.04  3945.1  294.21  4050.5  293.88  4203.1  292.42
  4233.6  291.78  4319.8  291.35  4350.3  291.82  4406.0  291.16  4509.6  291.27
  4553.2  290.83  4648.0  291.00  4695.1  290.70  4756.1  290.90  4841.5  290.49
  4928.5  289.73  5016.4  289.75  5049.1  289.39  5050.1  288.59  5058.0  288.59
  5059.0  289.39  5208.4  290.48  5312.9  292.13  5431.8  293.43  5563.5  293.61
  5601.6  294.33  5639.7  294.15  5793.6  294.77  5856.3  294.55  6154.1  295.21
#Mann=5,-1,0
  3807.9     0.1       0  4841.5    0.05       0  5016.4     0.1       0
  5049.1    0.03       0  5059.0     0.1       0
Bank Sta=5049.1,5059
Exp/Cntr=0.3,0.1