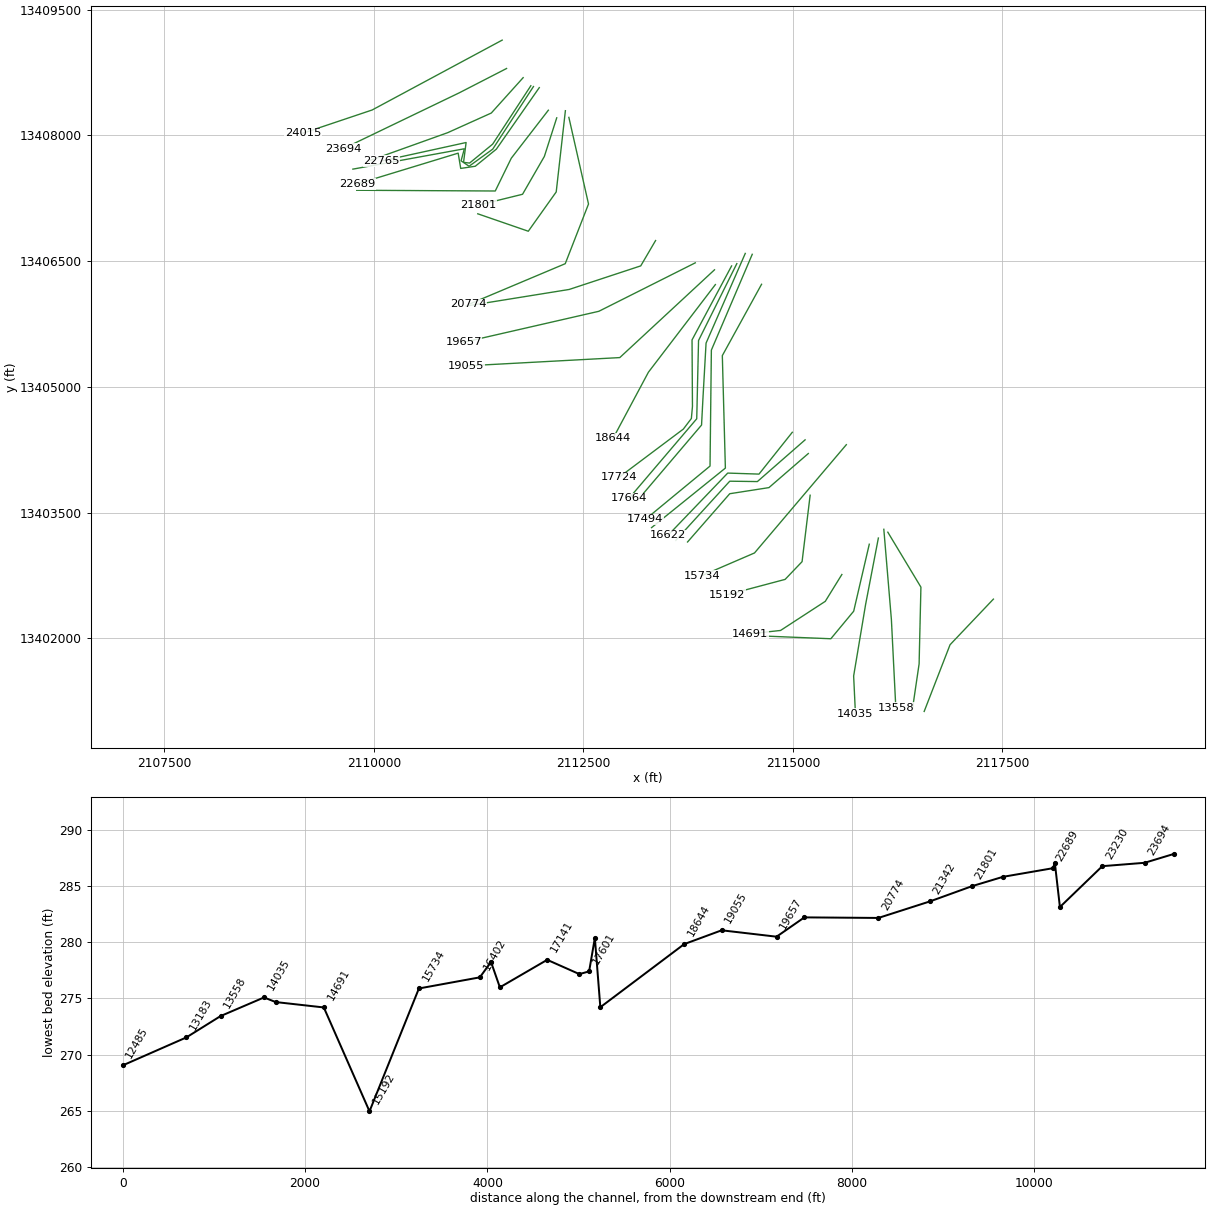
HEC-RAS study UNT 006 in La Jarita Watershed.prj: UNT 006 in La Jarita Watershed Base Level Engineering

--- UNT 006 in La Jarita Watershed.g01 (geometry) --- (continued)

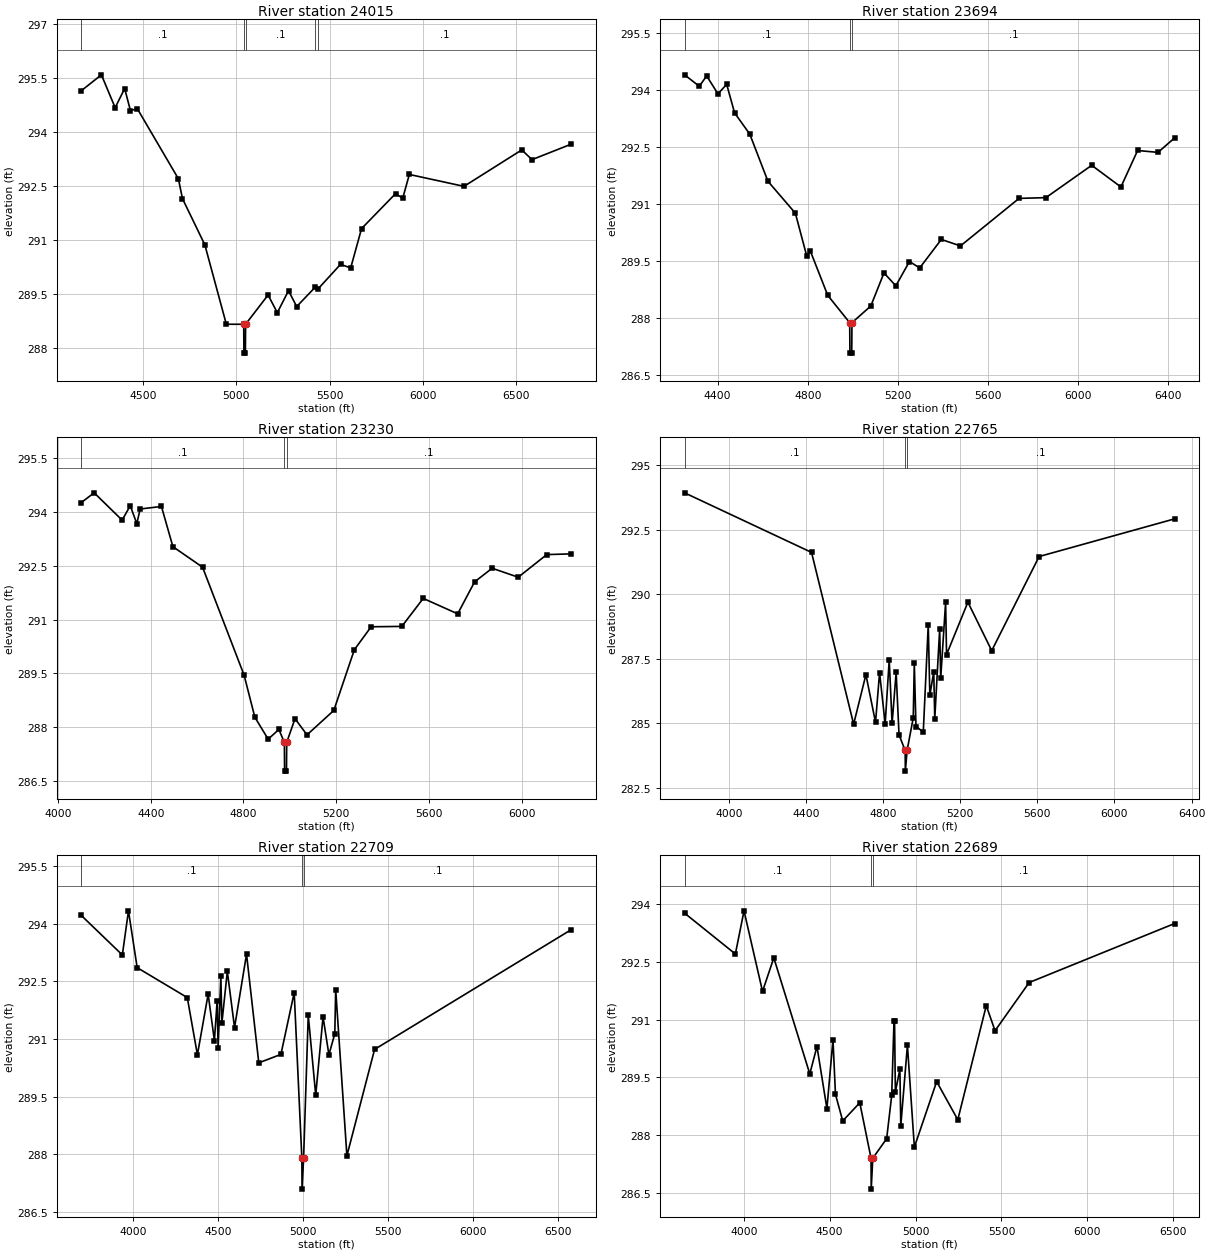
Type RM Length L Ch R = 1,24015,321,321,321
BEGIN DESCRIPTION:
Mapping XS bf767d65
END DESCRIPTION:
XS GIS Cut Line= 3
      2111530.14     13409135.91      2109978.10     13408302.60
      2109155.17     13408026.55
#Sta/Elev= 30
  4167.9  295.14  4275.9  295.58  4349.6  294.67  4400.7  295.20  4431.6  294.59
  4468.8  294.64  4689.0  292.70  4710.9  292.15  4831.0  290.87  4946.3  288.67
  5039.6  288.67  5040.6  287.87  5048.6  287.87  5049.6  288.67  5170.4  289.48
  5219.9  288.99  5280.0  289.60  5323.9  289.16  5423.9  289.70  5436.9  289.64
  5559.3  290.33  5613.7  290.23  5672.0  291.32  5854.8  292.29  5893.0  292.16
  5928.4  292.82  6221.7  292.49  6531.9  293.50  6586.7  293.23  6797.5  293.66
#Mann=5,-1,0
  4167.9     0.1       0  5039.6    0.07       0  5049.6     0.1       0
  5423.9    0.05       0  5436.9     0.1       0
Bank Sta=5039.6,5049.6
Exp/Cntr=0.3,0.1

Type RM Length L Ch R = 1,23694,464,464,464
BEGIN DESCRIPTION:
Mapping XS 1de47f13
END DESCRIPTION:
XS GIS Cut Line= 3
      2111582.28     13408797.40      2111014.56     13408505.72
      2109630.53     13407839.72
#Sta/Elev= 30
  4253.4  294.40  4318.4  294.10  4351.5  294.37  4401.5  293.90  4440.2  294.15
  4475.2  293.40  4542.7  292.84  4623.3  291.60  4745.0  290.76  4795.2  289.64
  4811.8  289.76  4888.6  288.60  4986.1  287.88  4987.1  287.08  4995.1  287.08
  4996.1  287.88  5079.8  288.32  5138.2  289.19  5190.8  288.85  5251.3  289.49
  5296.6  289.32  5392.6  290.07  5477.6  289.90  5737.6  291.15  5856.7  291.17
  6060.0  292.02  6189.6  291.45  6263.6  292.41  6354.1  292.36  6427.6  292.74
#Mann=3,-1,0
  4253.4     0.1       0  4986.1    0.07       0  4996.1     0.1       0
Bank Sta=4986.1,4996.1
Exp/Cntr=0.3,0.1

Type RM Length L Ch R = 1,23230,465,465,465
BEGIN DESCRIPTION:
Mapping XS 67a76ac1
END DESCRIPTION:
XS GIS Cut Line= 4
      2111780.21     13408688.05      2111399.97     13408266.14
      2110879.14     13408031.76      2109962.50     13407703.65
#Sta/Elev= 30
  4100.7  294.26  4156.3  294.53  4276.7  293.77  4311.8  294.17  4340.2  293.67
  4354.4  294.08  4446.3  294.15  4495.7  293.03  4623.5  292.46  4802.8  289.45
  4849.1  288.28  4906.4  287.67  4952.7  287.94  4976.3  287.58  4977.3  286.78
  4985.4  286.78  4986.4  287.58  5022.2  288.24  5073.9  287.79  5189.5  288.47
  5278.0  290.16  5350.4  290.80  5482.8  290.81  5575.1  291.59  5723.6  291.16
  5796.5  292.05  5872.2  292.43  5984.6  292.18  6107.7  292.81  6213.4  292.83
#Mann=3,-1,0
  4100.7     0.1       0  4976.3    0.07       0  4986.4     0.1       0
Bank Sta=4976.3,4986.4
Exp/Cntr=0.3,0.1

Type RM Length L Ch R = 1,22765,56,56,56
BEGIN DESCRIPTION:
Mapping XS 15d17d3e
END DESCRIPTION:
XS GIS Cut Line= 6
      2111871.96     13408591.63      2111416.25     13407895.04
      2111140.64     13407669.35      2111069.03     13407678.03
      2111099.41     13407914.57      2110089.04     13407693.42
#Sta/Elev= 30
  3771.2  293.93  4429.4  291.62  4647.6  284.96  4711.3  286.88  4761.1  285.03
  4782.1  286.96  4811.1  284.97  4832.1  287.45  4847.0  284.99  4868.0  286.97
  4882.9  284.55  4914.7  283.94  4915.7  283.14  4924.8  283.94  4956.7  285.21
  4962.1  287.32  4970.8  284.87  5008.7  284.66  5034.4  288.81  5042.7  286.08
  5062.9  286.99  5068.2  285.17  5093.7  288.65  5099.0  286.74  5124.5  289.69
  5129.3  287.66  5240.0  289.69  5363.5  287.81  5609.2  291.46  6311.4  292.92
#Mann=3,-1,0
  3771.2     0.1       0  4914.7    0.07       0  4924.8     0.1       0
Bank Sta=4914.7,4924.8
Exp/Cntr=0.3,0.1

Type RM Length L Ch R = 1,22709,20,20,20
BEGIN DESCRIPTION:
Mapping XS 4d2c594d
END DESCRIPTION:
XS GIS Cut Line= 6
      2111903.23     13408582.11      2111417.12     13407835.58
      2111135.00     13407631.59      2111039.51     13407696.69
      2111078.57     13407839.92      2109748.09     13407597.23
#Sta/Elev= 30
  3697.7  294.22  3938.9  293.19  3974.9  294.34  4026.0  292.86  4320.5  292.08
  4380.0  290.59  4443.1  292.17  4479.7  290.96  4495.9  291.99  4501.6  290.77
  4517.8  292.65  4523.5  291.41  4555.7  292.76  4598.1  291.30  4668.6  293.21
  4740.6  290.38  4870.6  290.60  4948.7  292.21  4993.7  287.89  4994.7  287.09
  5003.8  287.89  5031.2  291.62  5075.1  289.54  5118.1  291.58  5152.6  290.59
  5187.2  291.14  5192.4  292.29  5258.3  287.96  5420.9  290.73  6576.6  293.85
#Mann=3,-1,0
  3697.7     0.1       0  4993.7    0.07       0  5003.8     0.1       0
Bank Sta=4993.7,5003.8
Exp/Cntr=0.3,0.1

Type RM Length L Ch R = 1,22689,549,549,549
BEGIN DESCRIPTION:
Mapping XS bc9f2a44
END DESCRIPTION:
XS GIS Cut Line= 6
      2111972.69     13408569.12      2111460.52     13407835.58
      2111208.78     13407631.59      2111035.17     13407605.55
      2111004.79     13407787.84      2109795.62     13407419.45
#Sta/Elev= 30
  3655.8  293.76  3951.4  292.70  4001.7  293.82  4109.4  291.73  4175.1  292.60
  4384.4  289.59  4426.2  290.30  4484.1  288.69  4519.4  290.48  4533.8  289.06
  4576.1  288.37  4675.4  288.84  4740.9  287.40  4741.9  286.60  4751.0  287.40
  4831.8  287.91  4861.1  289.03  4874.5  290.95  4877.7  290.95  4882.4  289.12
  4908.7  289.71  4914.0  288.25  4952.6  290.33  4993.0  287.69  5122.8  289.39
  5245.7  288.40  5411.4  291.36  5462.5  290.71  5661.1  291.96  6507.2  293.49
#Mann=3,-1,0
  3655.8     0.1       0  4740.9    0.07       0  4751.0     0.1       0
Bank Sta=4740.9,4751
Exp/Cntr=0.3,0.1

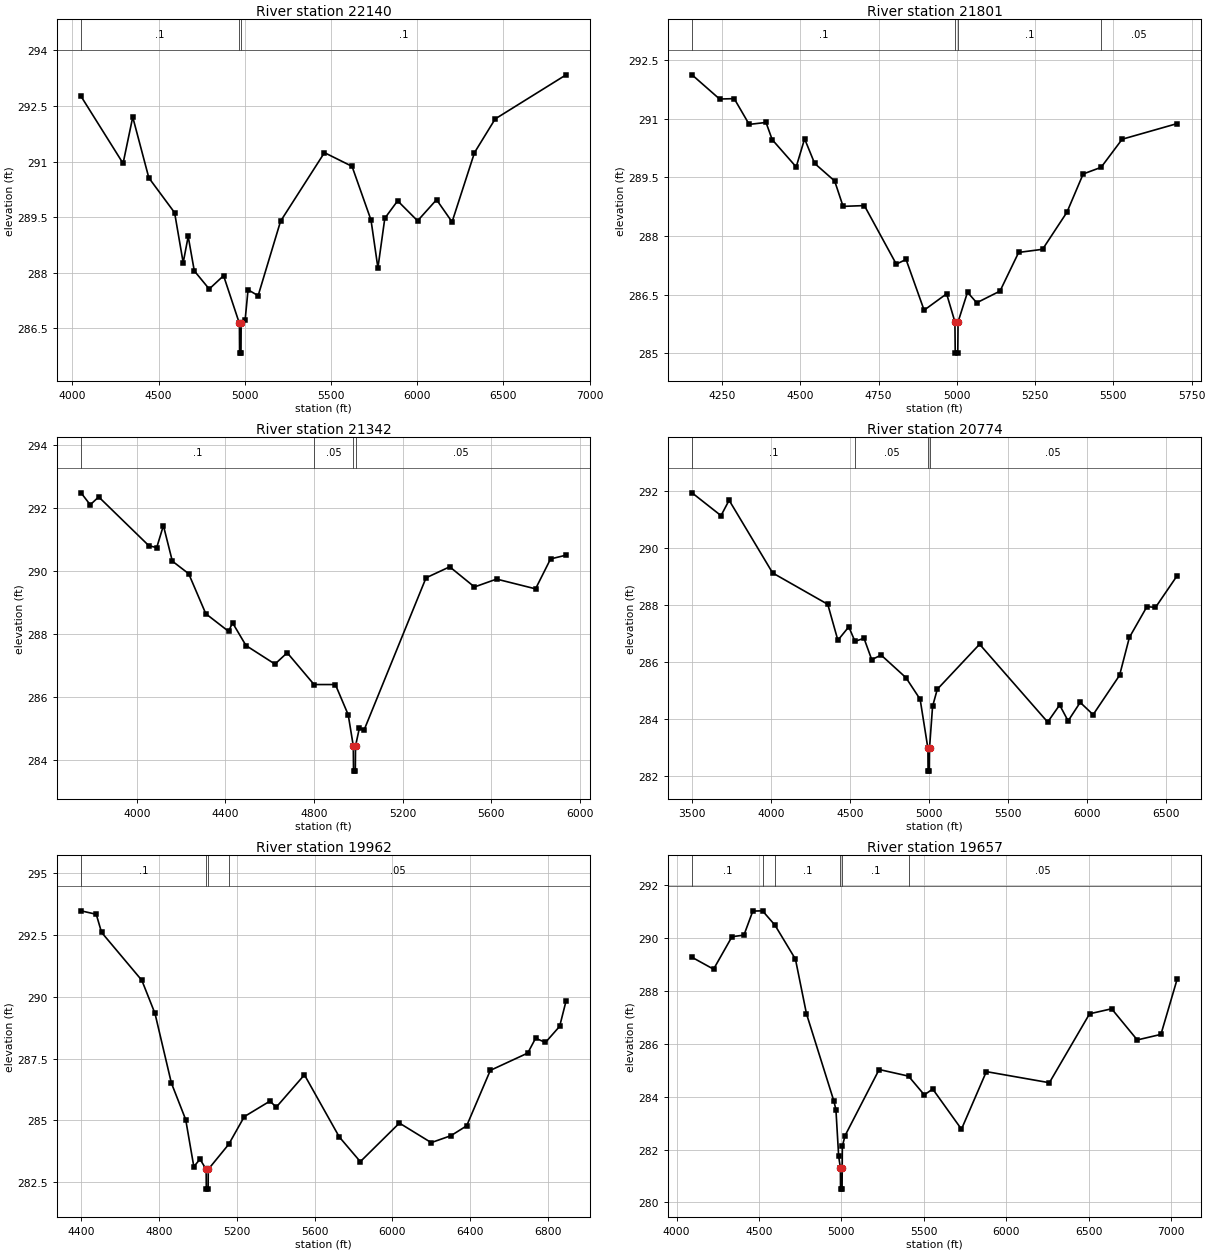
Type RM Length L Ch R = 1,22140,339,339,339
BEGIN DESCRIPTION:
Mapping XS e8c1464e
END DESCRIPTION:
XS GIS Cut Line= 4
      2112081.19     13408300.01      2111638.47     13407727.07
      2111447.50     13407336.45      2109793.88     13407345.13
#Sta/Elev= 30
  4050.5  292.76  4294.2  290.95  4350.3  292.20  4443.6  290.56  4593.0  289.62
  4642.8  288.27  4671.8  288.98  4707.2  288.05  4793.7  287.56  4877.0  287.92
  4968.8  286.63  4969.8  285.83  4977.9  285.83  4978.9  286.63  5001.9  286.72
  5018.9  287.54  5077.4  287.38  5207.4  289.39  5461.9  291.24  5621.9  290.87
  5731.9  289.42  5771.9  288.13  5811.9  289.47  5886.3  289.94  6001.9  289.40
  6111.9  289.97  6201.9  289.37  6331.9  291.24  6451.9  292.15  6863.0  293.34
#Mann=3,-1,0
  4050.5     0.1       0  4968.8    0.07       0  4978.9     0.1       0
Bank Sta=4968.8,4978.9
Exp/Cntr=0.3,0.1

Type RM Length L Ch R = 1,21801,459,459,459
BEGIN DESCRIPTION:
Mapping XS fb860d00
END DESCRIPTION:
XS GIS Cut Line= 4
      2112181.02     13408208.88      2112033.44     13407748.78
      2111773.02     13407297.39      2111243.51     13407167.18
#Sta/Elev= 30
  4153.8  292.13  4241.9  291.51  4288.6  291.52  4336.4  290.86  4390.2  290.91
  4409.9  290.47  4486.6  289.77  4513.5  290.49  4545.6  289.86  4609.5  289.41
  4636.4  288.76  4704.4  288.78  4806.4  287.28  4837.6  287.40  4895.3  286.10
  4967.2  286.52  4993.7  285.80  4994.7  285.00  5002.8  285.00  5003.8  285.80
  5033.9  286.56  5063.4  286.29  5137.8  286.59  5197.3  287.58  5273.7  287.66
  5351.6  288.61  5403.4  289.59  5460.7  289.76  5528.0  290.48  5703.4  290.88
#Mann=4,-1,0
  4153.8     0.1       0  4993.7    0.07       0  5003.8     0.1       0
  5460.7    0.05       0
Bank Sta=4993.7,5003.8
Exp/Cntr=0.3,0.1

Type RM Length L Ch R = 1,21342,568,568,568
BEGIN DESCRIPTION:
Mapping XS 14678552
END DESCRIPTION:
XS GIS Cut Line= 4
      2112284.31     13408294.16      2112174.93     13407325.38
      2111841.59     13406856.63      2111238.74     13407064.51
#Sta/Elev= 30
  3749.0  292.49  3790.4  292.11  3828.7  292.36  4054.9  290.81  4090.3  290.75
  4120.5  291.45  4160.8  290.32  4234.6  289.92  4311.7  288.65  4414.3  288.09
  4432.5  288.36  4492.9  287.64  4623.7  287.05  4678.9  287.41  4800.1  286.40
  4896.2  286.40  4954.1  285.44  4977.0  284.45  4978.0  283.65  4986.1  283.65
  4987.1  284.45  5004.5  285.02  5025.4  284.95  5305.1  289.79  5411.9  290.14
  5523.6  289.50  5623.4  289.75  5799.1  289.44  5866.8  290.39  5936.8  290.51
#Mann=4,-1,0
  3749.0     0.1       0  4800.1    0.05       0  4977.0    0.03       0
  4987.1    0.05       0
Bank Sta=4977,4987.1
Exp/Cntr=0.3,0.1

Type RM Length L Ch R = 1,20774,812,812,812
BEGIN DESCRIPTION:
UNT 006 in La Jarita Watershed 15.0
END DESCRIPTION:
XS GIS Cut Line= 4
      2112325.98     13408214.23      2112560.34     13407181.28
      2112282.57     13406469.48      2111129.04     13405983.78
#Sta/Elev= 30
  3497.6  291.93  3681.4  291.13  3732.7  291.67  4008.7  289.12  4358.2  288.02
  4422.2  286.76  4491.5  287.23  4530.7  286.72  4587.8  286.83  4636.8  286.08
  4696.5  286.24  4853.4  285.45  4943.7  284.69  4993.0  282.97  4994.0  282.17
  5002.1  282.17  5003.1  282.97  5022.6  284.44  5052.4  285.04  5320.6  286.62
  5752.2  283.89  5828.2  284.49  5881.8  283.93  5958.4  284.58  6040.4  284.15
  6208.0  285.53  6270.3  286.86  6381.6  287.94  6435.8  287.91  6572.5  289.02
#Mann=4,-1,0
  3497.6     0.1       0  4530.7    0.05       0  4993.0    0.03       0
  5003.1    0.05       0
Bank Sta=4993,5003.1
Exp/Cntr=0.3,0.1

Type RM Length L Ch R = 1,19962,305,305,305
BEGIN DESCRIPTION:
Mapping XS c68c00b8
END DESCRIPTION:
XS GIS Cut Line= 4
      2113360.68     13406745.49      2113183.61     13406443.44
      2112329.44     13406162.19      2111100.28     13405964.27
#Sta/Elev= 30
  4398.6  293.47  4476.8  293.33  4504.0  292.60  4711.3  290.66  4778.9  289.32
  4863.1  286.51  4936.8  285.03  4978.6  283.13  5010.4  283.43  5042.0  283.02
  5042.8  282.22  5052.1  282.22  5052.9  283.02  5157.9  284.03  5238.1  285.15
  5370.5  285.78  5402.2  285.53  5547.4  286.84  5726.6  284.33  5834.8  283.33
  6035.8  284.89  6199.5  284.10  6300.8  284.38  6381.8  284.78  6503.3  287.02
  6695.8  287.72  6736.3  288.32  6786.9  288.15  6859.9  288.80  6893.0  289.83
#Mann=4,-1,0
  4398.6     0.1       0  5042.0    0.07       0  5052.9     0.1       0
  5157.9    0.05       0
Bank Sta=5042,5052.9
Exp/Cntr=0.3,0.1

Type RM Length L Ch R = 1,19657,602,602,602
BEGIN DESCRIPTION:
Mapping XS 7d7ec603
END DESCRIPTION:
XS GIS Cut Line= 3
      2113834.63     13406479.88      2112683.61     13405901.77
      2111069.55     13405532.10
#Sta/Elev= 30
  4093.2  289.28  4224.0  288.83  4335.7  290.06  4408.3  290.12  4462.1  291.03
  4521.1  291.04  4596.3  290.50  4720.9  289.21  4787.9  287.14  4954.4  283.83
  4966.6  283.51  4983.3  281.74  4993.8  281.30  4994.6  280.50  5003.9  280.50
  5004.7  281.30  5005.6  282.12  5021.6  282.52  5228.9  285.03  5407.1  284.78
  5502.9  284.07  5554.2  284.29  5728.6  282.77  5879.6  284.95  6262.1  284.53
  6506.1  287.14  6640.0  287.33  6795.5  286.15  6939.2  286.36  7037.1  288.44
#Mann=6,-1,0
  4093.2     0.1       0  4521.1    0.05       0  4596.3     0.1       0
  4993.8    0.07       0  5004.7     0.1       0  5407.1    0.05       0
Bank Sta=4993.8,5004.7
Exp/Cntr=0.3,0.1

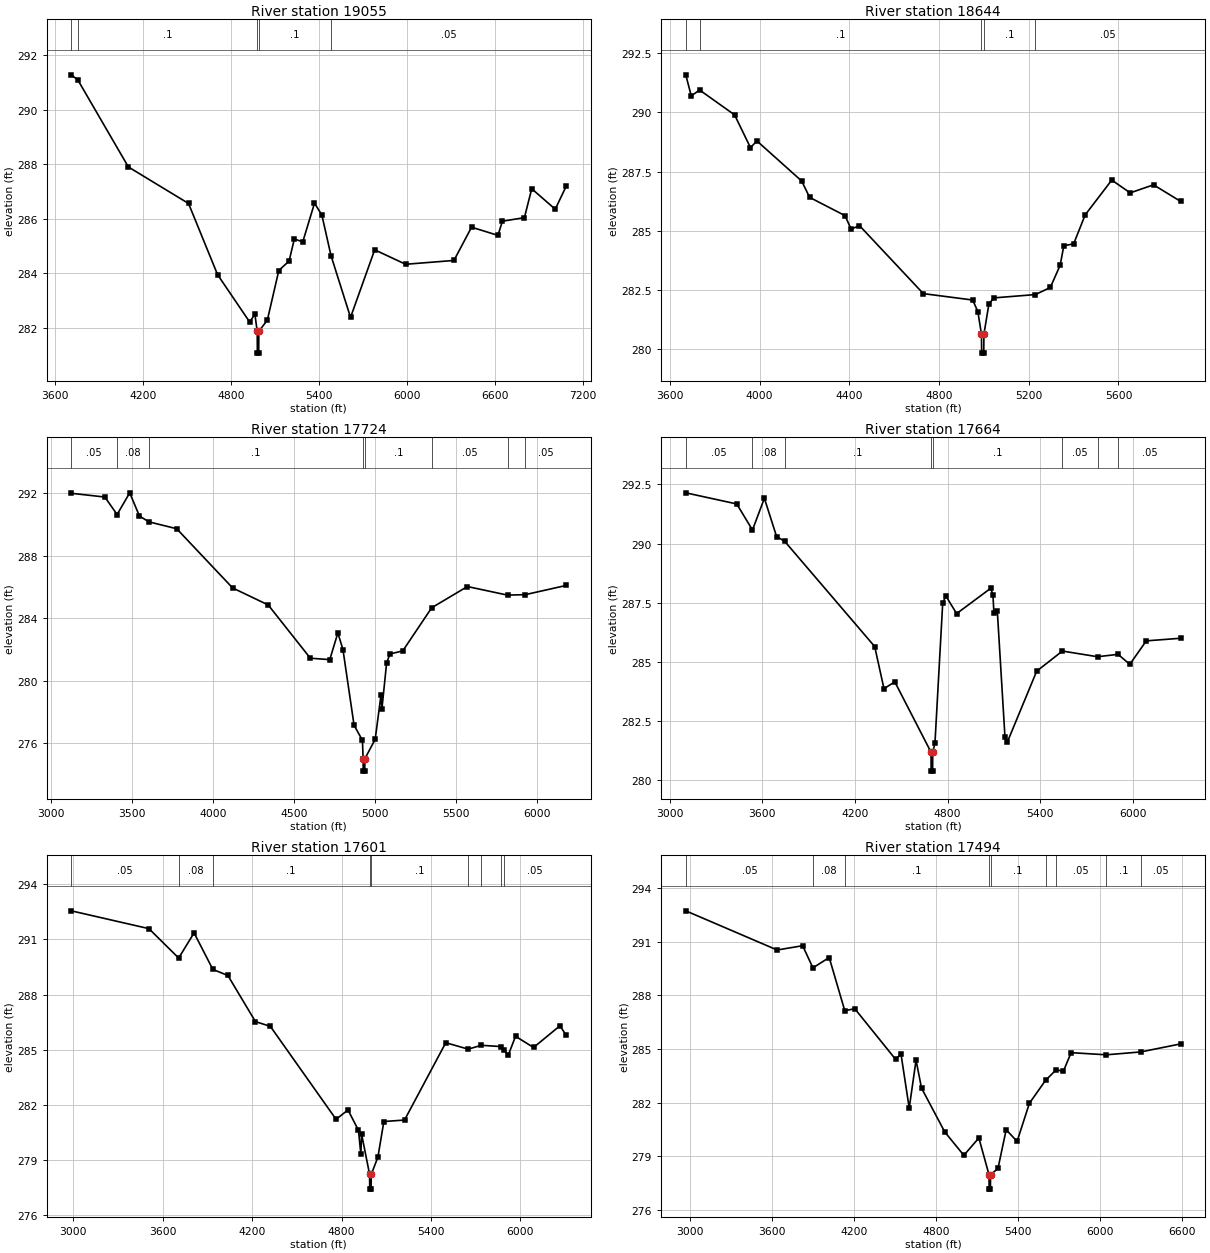
Type RM Length L Ch R = 1,19055,411,411,411
BEGIN DESCRIPTION:
UNT 006 in La Jarita Watershed 14.0
END DESCRIPTION:
XS GIS Cut Line= 3
      2114063.81     13406396.55      2112933.61     13405349.69
      2111100.32     13405250.73
#Sta/Elev= 30
  3708.7  291.28  3753.6  291.09  4098.2  287.90  4508.7  286.56  4706.6  283.95
  4926.0  282.21  4961.2  282.50  4977.3  281.87  4978.1  281.07  4987.4  281.07
  4988.2  281.87  5046.2  282.28  5124.5  284.10  5194.8  284.45  5230.5  285.26
  5287.9  285.15  5368.0  286.57  5418.1  286.14  5480.5  284.65  5613.9  282.38
  5778.6  284.86  5989.8  284.33  6319.4  284.47  6439.6  285.69  6619.8  285.39
  6649.9  285.91  6800.1  286.04  6850.2  287.10  7010.4  286.35  7085.2  287.19
#Mann=5,-1,0
  3708.7    0.08       0  3753.6     0.1       0  4977.3    0.07       0
  4988.2     0.1       0  5480.5    0.05       0
Bank Sta=4977.3,4988.2
Exp/Cntr=0.3,0.1

Type RM Length L Ch R = 1,18644,920,920,920
BEGIN DESCRIPTION:
UNT 006 in La Jarita Watershed 13.0
END DESCRIPTION:
XS GIS Cut Line= 3
      2114074.22     13406220.32      2113275.00     13405175.00
      2112854.96     13404389.39
#Sta/Elev= 30
  3670.7  291.58  3695.2  290.69  3732.3  290.94  3888.4  289.89  3959.1  288.51
  3988.1  288.79  4187.6  287.10  4223.0  286.41  4380.8  285.64  4407.9  285.07
  4445.2  285.22  4729.9  282.35  4950.2  282.08  4973.0  281.59  4989.2  280.64
  4990.0  279.84  4999.3  279.84  5000.1  280.64  5022.3  281.91  5044.2  282.17
  5229.6  282.31  5296.2  282.61  5340.1  283.55  5356.4  284.37  5400.3  284.45
  5451.5  285.67  5570.2  287.14  5652.3  286.60  5756.3  286.94  5877.4  286.24
#Mann=5,-1,0
  3670.7    0.08       0  3732.3     0.1       0  4989.2    0.07       0
  5000.1     0.1       0  5229.6    0.05       0
Bank Sta=4989.2,5000.1
Exp/Cntr=0.3,0.1

Type RM Length L Ch R = 1,17724,60,60,60
BEGIN DESCRIPTION:
Mapping XS 8864fb4c
END DESCRIPTION:
XS GIS Cut Line= 6
      2114267.81     13406442.57      2113795.83     13405560.35
      2113800.80     13404766.35      2113787.78     13404623.12
      2113692.29     13404497.26      2112924.74     13403921.93
#Sta/Elev= 30
  3126.0  292.01  3333.2  291.77  3408.8  290.65  3486.8  292.04  3546.9  290.55
  3605.9  290.18  3776.9  289.74  4122.1  285.95  4341.9  284.86  4601.9  281.45
  4721.9  281.36  4771.9  283.07  4803.4  282.00  4871.9  277.16  4923.7  276.19
  4927.7  275.02  4928.4  274.22  4937.9  274.22  4938.7  275.02  5002.2  276.25
  5038.6  279.12  5043.6  278.18  5072.8  281.14  5093.6  281.72  5172.6  281.92
  5351.2  284.68  5571.5  286.04  5819.4  285.49  5928.8  285.52  6181.6  286.11
#Mann=8,-1,0
  3126.0    0.05       0  3408.8    0.08       0  3605.9     0.1       0
  4927.7    0.07       0  4938.7     0.1       0  5351.2    0.05       0
  5819.4    0.08       0  5928.8    0.05       0
Bank Sta=4927.7,4938.7
Exp/Cntr=0.3,0.1

Type RM Length L Ch R = 1,17664,63,63,63
BEGIN DESCRIPTION:
Mapping XS d2a94903
END DESCRIPTION:
XS GIS Cut Line= 4
      2114330.32     13406470.36      2113873.49     13405553.65
      2113851.83     13404619.86      2113044.52     13403671.92
#Sta/Elev= 30
  3105.1  292.14  3435.1  291.67  3536.9  290.57  3613.9  291.91  3693.2  290.29
  3744.4  290.10  4328.0  285.65  4388.0  283.87  4458.1  284.16  4692.6  281.19
  4693.4  280.39  4702.9  280.39  4703.6  281.19  4718.1  281.58  4768.2  287.48
  4788.2  287.79  4858.2  287.04  5079.0  288.11  5093.3  287.84  5099.8  287.05
  5121.8  287.14  5171.2  281.83  5185.5  281.60  5376.5  284.61  5542.9  285.46
  5770.2  285.22  5903.3  285.32  5979.4  284.90  6085.9  285.89  6308.5  286.00
#Mann=8,-1,0
  3105.1    0.05       0  3536.9    0.08       0  3744.4     0.1       0
  4692.6    0.07       0  4703.6     0.1       0  5542.9    0.05       0
  5770.2    0.08       0  5903.3    0.05       0
Bank Sta=4692.6,4703.6
Exp/Cntr=0.3,0.1

Type RM Length L Ch R = 1,17601,107,107,107
BEGIN DESCRIPTION:
Mapping XS 0936ff5f
END DESCRIPTION:
XS GIS Cut Line= 5
      2114431.02     13406591.92      2113963.17     13405522.35
      2113926.66     13404874.86      2113909.30     13404545.00
      2113149.38     13403651.90
#Sta/Elev= 30
  2987.9  292.56  3508.4  291.59  3708.1  289.99  3811.3  291.36  3937.3  289.37
  4038.1  289.04  4222.8  286.53  4322.9  286.27  4763.6  281.21  4843.7  281.72
  4913.8  280.61  4929.7  279.32  4934.8  280.40  4988.5  278.21  4989.2  277.41
  4998.7  277.41  4999.5  278.21  5044.0  279.15  5084.1  281.09  5222.6  281.17
  5499.3  285.38  5649.9  285.03  5737.3  285.24  5870.4  285.17  5892.3  284.97
  5917.7  284.69  5967.1  285.73  6087.9  285.12  6264.7  286.30  6306.8  285.79
#Mann=9,-1,0
  2987.9    0.05       0  3708.1    0.08       0  3937.3     0.1       0
  4988.5    0.07       0  4999.5     0.1       0  5649.9    0.05       0
  5737.3    0.08       0  5870.4     0.1       0  5892.3    0.05       0
Bank Sta=4988.5,4999.5
Exp/Cntr=0.3,0.1

Type RM Length L Ch R = 1,17494,353,353,353
BEGIN DESCRIPTION:
Mapping XS d608e40b
END DESCRIPTION:
XS GIS Cut Line= 4
      2114514.33     13406581.45      2114026.55     13405439.08
      2114010.51     13404055.97      2113239.85     13403420.69
#Sta/Elev= 30
  2967.0  292.73  3636.0  290.54  3823.0  290.78  3898.1  289.54  4017.3  290.12
  4131.6  287.14  4204.3  287.26  4503.2  284.43  4543.3  284.71  4603.3  281.70
  4653.3  284.38  4693.3  282.82  4863.3  280.37  5003.3  279.06  5113.3  280.03
  5187.8  277.97  5188.5  277.17  5198.0  277.17  5198.8  277.97  5253.3  278.33
  5313.3  280.49  5393.3  279.84  5483.3  281.97  5601.6  283.25  5680.3  283.85
  5731.5  283.75  5788.9  284.80  6046.5  284.68  6298.3  284.84  6591.1  285.29
#Mann=9,-1,0
  2967.0    0.05       0  3898.1    0.08       0  4131.6     0.1       0
  5187.8    0.07       0  5198.8     0.1       0  5601.6    0.08       0
  5680.3    0.05       0  6046.5     0.1       0  6298.3    0.05       0
Bank Sta=5187.8,5198.8
Exp/Cntr=0.3,0.1

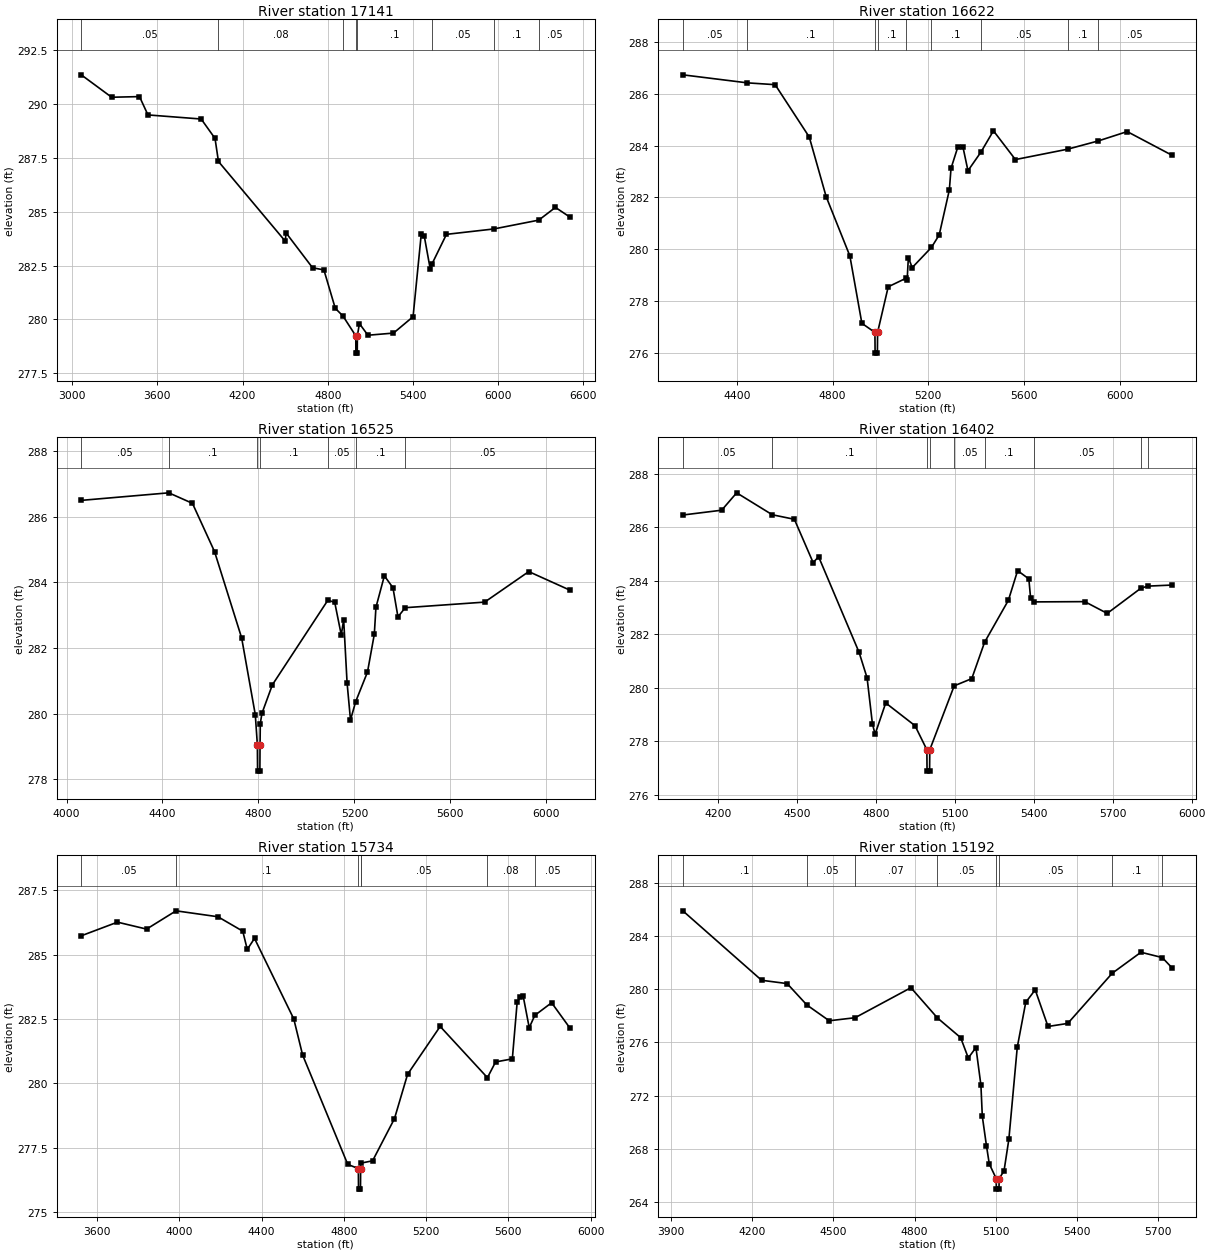
Type RM Length L Ch R = 1,17141,519,519,519
BEGIN DESCRIPTION:
UNT 006 in La Jarita Watershed 11.0
END DESCRIPTION:
XS GIS Cut Line= 4
      2114625.44     13406223.80      2114157.25     13405373.23
      2114193.67     13404031.67      2113312.56     13403321.57
#Sta/Elev= 30
  3063.7  291.35  3277.9  290.31  3474.0  290.34  3533.6  289.49  3908.6  289.30
  4006.1  288.40  4030.2  287.33  4501.2  283.63  4506.2  284.02  4693.1  282.40
  4773.1  282.30  4853.1  280.52  4907.5  280.16  4997.7  279.24  4998.4  278.44
  5008.0  278.44  5008.7  279.24  5023.2  279.81  5083.2  279.27  5263.3  279.37
  5401.2  280.13  5458.7  283.95  5479.5  283.89  5522.7  282.32  5533.2  282.56
  5636.3  283.95  5970.0  284.20  6286.6  284.61  6404.0  285.20  6508.3  284.74
#Mann=8,-1,0
  3063.7    0.05       0  4030.2    0.08       0  4907.5     0.1       0
  4997.7    0.07       0  5008.7     0.1       0  5533.2    0.05       0
  5970.0     0.1       0  6286.6    0.05       0
Bank Sta=4997.7,5008.7
Exp/Cntr=0.3,0.1

Type RM Length L Ch R = 1,16622,97,97,97
BEGIN DESCRIPTION:
Mapping XS 20421448
END DESCRIPTION:
XS GIS Cut Line= 4
      2114992.30     13404458.77      2114594.89     13403960.14
      2114221.63     13403972.29      2113507.88     13403228.69
#Sta/Elev= 30
  4174.8  286.73  4444.3  286.42  4560.2  286.35  4702.7  284.33  4773.2  282.03
  4872.3  279.74  4922.4  277.14  4976.9  276.79  4977.6  275.99  4987.2  275.99
  4988.0  276.79  5032.4  278.55  5106.8  278.88  5111.5  278.83  5116.5  279.68
  5132.5  279.29  5212.9  280.07  5245.2  280.55  5287.7  282.29  5294.6  283.12
  5322.9  283.94  5344.3  283.95  5365.4  283.03  5419.7  283.75  5471.7  284.57
  5563.5  283.46  5781.3  283.86  5909.9  284.18  6030.2  284.54  6216.6  283.63
#Mann=9,-1,0
  4174.8    0.05       0  4444.3     0.1       0  4976.9    0.07       0
  4988.0     0.1       0  5106.8    0.05       0  5212.9     0.1       0
  5419.7    0.05       0  5781.3     0.1       0  5909.9    0.05       0
Bank Sta=4976.9,4988
Exp/Cntr=0.3,0.1

Type RM Length L Ch R = 1,16525,123,123,123
BEGIN DESCRIPTION:
Mapping XS 774ccf1d
END DESCRIPTION:
XS GIS Cut Line= 4
      2115145.06     13404368.47      2114575.62     13403871.08
      2114245.76     13403875.42      2113603.43     13403172.33
#Sta/Elev= 30
  4061.3  286.50  4426.2  286.73  4524.8  286.41  4616.9  284.94  4729.9  282.31
  4786.8  279.97  4795.5  279.05  4796.3  278.25  4805.9  278.25  4806.6  279.05
  4807.7  279.70  4814.5  280.01  4858.0  280.88  5089.5  283.46  5118.0  283.39
  5145.2  282.40  5155.2  282.86  5169.4  280.94  5183.6  279.81  5205.4  280.37
  5254.5  281.27  5282.9  282.42  5289.7  283.24  5324.8  284.20  5360.6  283.84
  5381.5  282.95  5411.8  283.23  5742.9  283.40  5926.7  284.33  6099.6  283.76
#Mann=7,-1,0
  4061.3    0.05       0  4426.2     0.1       0  4795.5    0.07       0
  4806.6     0.1       0  5089.5    0.05       0  5205.4     0.1       0
  5411.8    0.05       0
Bank Sta=4795.5,4806.6
Exp/Cntr=0.3,0.1

Type RM Length L Ch R = 1,16402,668,668,668
BEGIN DESCRIPTION:
Mapping XS 40c89af2
END DESCRIPTION:
XS GIS Cut Line= 4
      2115183.26     13404205.28      2114713.64     13403799.03
      2114245.76     13403726.11      2113742.31     13403150.62
#Sta/Elev= 30
  4065.5  286.46  4213.2  286.64  4270.2  287.29  4405.5  286.47  4489.6  286.30
  4560.9  284.68  4581.7  284.90  4735.7  281.32  4766.0  280.37  4786.3  278.65
  4796.4  278.26  4836.9  279.43  4948.2  278.58  4993.3  277.68  4994.0  276.88
  5003.6  276.88  5004.4  277.68  5097.2  280.07  5164.0  280.34  5212.7  281.70
  5303.2  283.27  5338.3  284.38  5381.0  284.07  5387.7  283.35  5399.3  283.21
  5593.6  283.22  5679.0  282.78  5806.7  283.72  5833.1  283.80  5924.6  283.84
#Mann=9,-1,0
  4065.5    0.05       0  4405.5     0.1       0  4993.3    0.07       0
  5004.4     0.1       0  5097.2    0.05       0  5212.7     0.1       0
  5399.3    0.05       0  5806.7     0.1       0  5833.1    0.05       0
Bank Sta=4993.3,5004.4
Exp/Cntr=0.3,0.1

Type RM Length L Ch R = 1,15734,542,542,542
BEGIN DESCRIPTION:
Mapping XS fd2f4900
END DESCRIPTION:
XS GIS Cut Line= 3
      2115637.07     13404310.77      2114541.16     13403019.55
      2113911.83     13402748.29
#Sta/Elev= 30
  3522.2  285.73  3698.4  286.26  3840.1  285.99  3983.4  286.70  4187.2  286.47
  4308.0  285.91  4329.9  285.20  4365.1  285.63  4556.2  282.50  4599.1  281.10
  4818.8  276.85  4870.3  276.69  4871.1  275.89  4880.7  275.89  4881.4  276.69
  4882.8  276.90  4939.6  276.99  5046.1  278.63  5109.8  280.35  5268.3  282.21
  5498.2  280.22  5538.0  280.83  5619.4  280.95  5642.9  283.15  5658.1  283.35
  5671.9  283.40  5701.6  282.16  5728.8  282.64  5810.5  283.13  5901.1  282.13
#Mann=7,-1,0
  3522.2    0.05       0  3983.4     0.1       0  4870.3    0.03       0
  4881.4     0.1       0  4882.8    0.05       0  5498.2    0.08       0
  5728.8    0.05       0
Bank Sta=4870.3,4881.4
Exp/Cntr=0.3,0.1

Type RM Length L Ch R = 1,15192,501,501,501
BEGIN DESCRIPTION:
Mapping XS a9681255
END DESCRIPTION:
XS GIS Cut Line= 4
      2115205.31     13403708.16      2115109.00     13402915.80
      2114906.69     13402704.46      2114212.23     13402519.99
#Sta/Elev= 30
  3942.7  285.91  4234.2  280.68  4328.7  280.43  4401.6  278.82  4484.4  277.63
  4580.1  277.86  4786.6  280.12  4884.9  277.84  4970.6  276.36  4998.9  274.83
  5027.2  275.61  5045.6  272.79  5050.8  270.43  5066.2  268.21  5076.6  266.85
  5102.1  265.75  5102.8  264.95  5112.4  264.95  5113.2  265.75  5131.1  266.32
  5149.0  268.70  5180.1  275.63  5211.5  279.02  5246.5  279.96  5293.9  277.20
  5367.0  277.43  5531.5  281.21  5637.8  282.79  5716.6  282.39  5752.0  281.63
#Mann=8,-1,0
  3942.7     0.1       0  4401.6    0.05       0  4580.1    0.07       0
  4884.9    0.05       0  5102.1    0.03       0  5113.2    0.05       0
  5531.5     0.1       0  5716.6    0.08       0
Bank Sta=5102.1,5113.2
Exp/Cntr=0.3,0.1

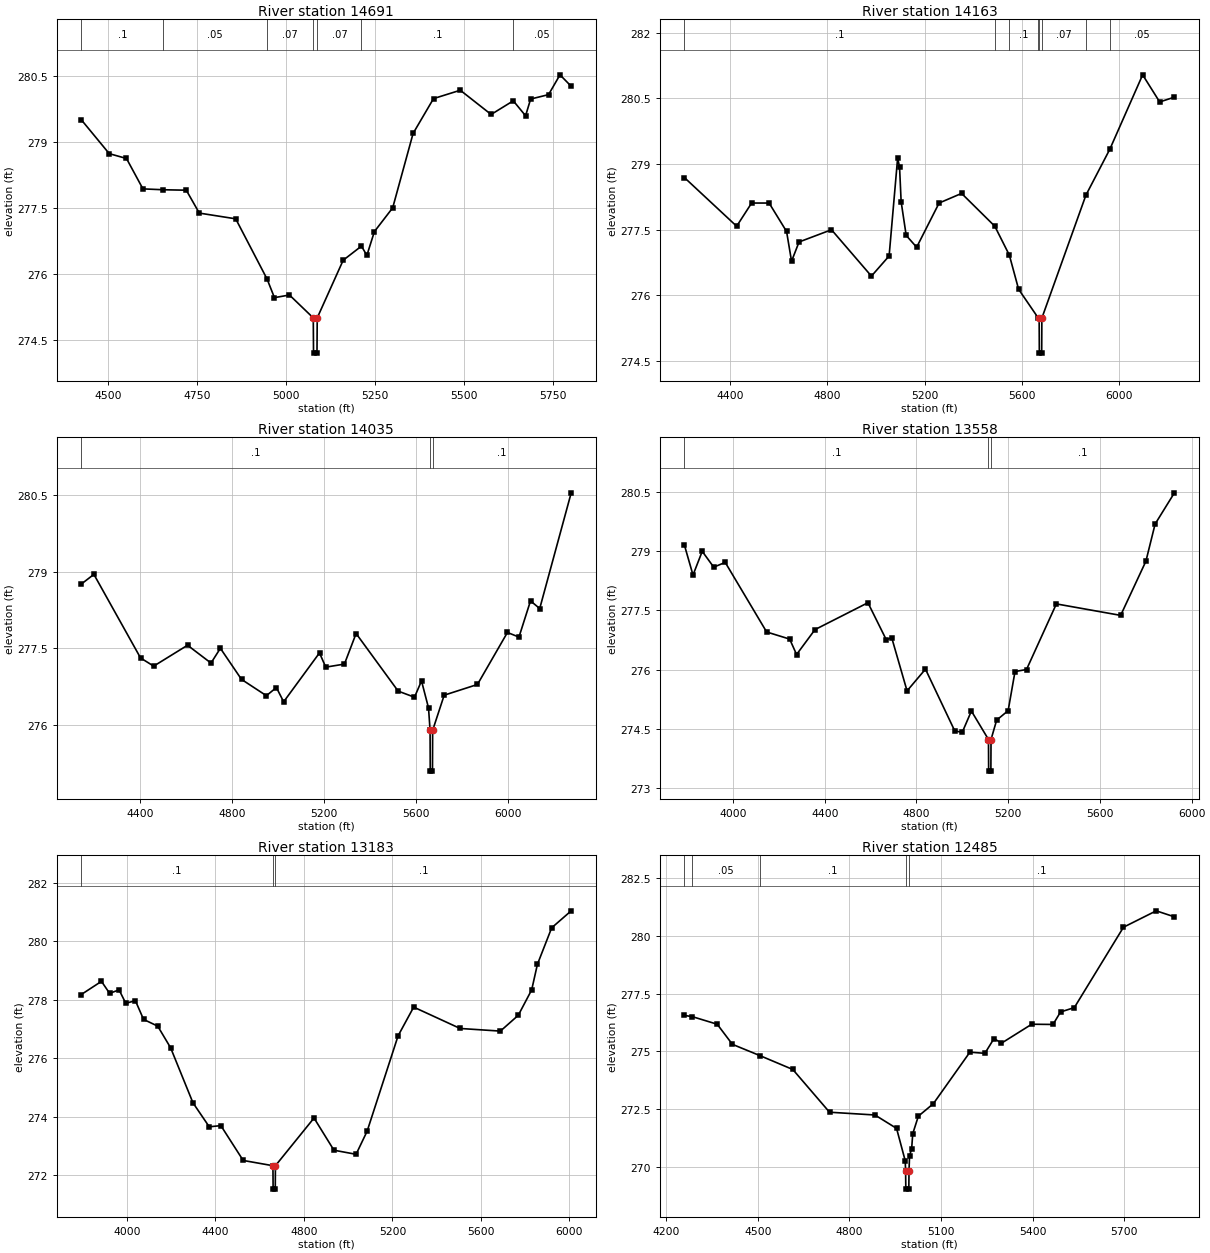
Type RM Length L Ch R = 1,14691,528,528,528
BEGIN DESCRIPTION:
Mapping XS 24442cc5
END DESCRIPTION:
XS GIS Cut Line= 4
      2115583.78     13402762.70      2115385.87     13402442.57
      2114852.01     13402095.35      2114491.73     13402056.28
#Sta/Elev= 30
  4424.8  279.50  4503.3  278.73  4551.7  278.62  4597.9  277.93  4655.2  277.91
  4719.6  277.90  4756.2  277.38  4858.4  277.25  4946.6  275.88  4967.1  275.46
  5009.3  275.52  5076.2  275.00  5076.9  274.20  5086.6  274.20  5087.3  275.00
  5160.2  276.31  5211.4  276.63  5226.7  276.42  5247.8  276.96  5299.2  277.50
  5356.5  279.19  5413.8  279.98  5489.0  280.17  5575.6  279.62  5637.8  279.93
  5672.3  279.59  5686.5  279.97  5736.8  280.07  5768.9  280.52  5800.4  280.26
#Mann=7,-1,0
  4424.8     0.1       0  4655.2    0.05       0  4946.6    0.07       0
  5076.2    0.07       0  5087.3    0.07       0  5211.4     0.1       0
  5637.8    0.05       0
Bank Sta=5076.2,5087.3
Exp/Cntr=0.3,0.1

Type RM Length L Ch R = 1,14163,128,128,128
BEGIN DESCRIPTION:
UNT 006 in La Jarita Watershed 10.0
END DESCRIPTION:
XS GIS Cut Line= 4
      2115911.05     13403124.03      2115725.00     13402325.00
      2115452.36     13401996.55      2114684.46     13402027.64
#Sta/Elev= 30
  4211.8  278.69  4426.4  277.58  4488.0  278.11  4559.9  278.11  4631.8  277.46
  4652.3  276.78  4683.1  277.22  4816.6  277.50  4980.9  276.44  5053.7  276.90
  5088.8  279.14  5096.7  278.93  5103.2  278.14  5124.0  277.37  5167.0  277.10
  5259.4  278.11  5351.9  278.33  5488.6  277.58  5548.4  276.92  5586.5  276.14
  5666.5  275.49  5671.1  275.48  5671.8  274.68  5681.5  274.68  5682.2  275.48
  5863.5  278.29  5961.9  279.34  6096.9  281.04  6167.0  280.42  6227.6  280.53
#Mann=8,-1,0
  4211.8     0.1       0  5488.6    0.05       0  5548.4     0.1       0
  5666.5    0.07       0  5671.1    0.07       0  5682.2    0.07       0
  5863.5     0.1       0  5961.9    0.05       0
Bank Sta=5671.1,5682.2
Exp/Cntr=0.3,0.1

Type RM Length L Ch R = 1,14035,477,477,477
BEGIN DESCRIPTION:
Mapping XS 8235f0a1
END DESCRIPTION:
XS GIS Cut Line= 4
      2116019.54     13403197.76      2115867.64     13402407.85
      2115724.41     13401552.81      2115746.04     13401098.56
#Sta/Elev= 30
  4146.3  278.76  4201.0  278.95  4403.6  277.31  4460.6  277.15  4607.4  277.56
  4709.2  277.21  4749.9  277.50  4841.6  276.89  4949.6  276.57  4993.0  276.73
  5024.5  276.45  5180.1  277.41  5207.1  277.13  5288.2  277.19  5338.9  277.79
  5521.4  276.66  5592.3  276.54  5622.8  276.86  5653.2  276.33  5660.0  275.89
  5660.7  275.09  5670.4  275.09  5671.1  275.89  5721.2  276.58  5865.5  276.79
  5995.6  277.81  6045.7  277.72  6095.8  278.43  6135.8  278.28  6272.4  280.55
#Mann=3,-1,0
  4146.3     0.1       0  5660.0    0.07       0  5671.1     0.1       0
Bank Sta=5660,5671.1
Exp/Cntr=0.3,0.1

Type RM Length L Ch R = 1,13558,375,375,375
BEGIN DESCRIPTION:
UNT 006 in La Jarita Watershed 9.0
END DESCRIPTION:
XS GIS Cut Line= 3
      2116084.65     13403301.99      2116175.00     13402225.00
      2116227.88     13401170.90
#Sta/Elev= 30
  3788.6  279.14  3825.7  278.39  3865.9  278.99  3916.0  278.59  3966.2  278.71
  4146.8  276.95  4247.2  276.77  4277.3  276.38  4357.6  277.01  4588.4  277.69
  4668.7  276.75  4691.9  276.81  4759.0  275.46  4839.3  276.01  4966.8  274.45
  4999.5  274.41  5039.6  274.95  5114.1  274.23  5114.8  273.43  5124.5  273.43
  5125.2  274.23  5149.7  274.72  5199.8  274.96  5229.8  275.95  5279.9  276.00
  5410.1  277.66  5690.4  277.37  5800.5  278.74  5840.6  279.68  5924.8  280.47
#Mann=3,-1,0
  3788.6     0.1       0  5114.1    0.07       0  5125.2     0.1       0
Bank Sta=5114.1,5125.2
Exp/Cntr=0.3,0.1

Type RM Length L Ch R = 1,13183,698,698,698
BEGIN DESCRIPTION:
Mapping XS 1882970e
END DESCRIPTION:
XS GIS Cut Line= 4
      2116132.40     13403267.21      2116527.36     13402611.84
      2116505.66     13401696.04      2116427.79     13401168.29
#Sta/Elev= 30
  3793.5  278.18  3884.7  278.63  3921.6  278.22  3964.3  278.34  3994.6  277.88
  4038.1  277.97  4075.0  277.33  4139.0  277.10  4197.3  276.36  4298.3  274.48
  4372.0  273.66  4424.5  273.70  4525.4  272.51  4659.9  272.33  4660.7  271.53
  4670.4  271.53  4671.1  272.33  4845.6  273.96  4935.6  272.86  5035.7  272.72
  5085.7  273.51  5225.7  276.77  5296.1  277.75  5506.1  277.02  5688.1  276.93
  5768.9  277.47  5829.6  278.34  5855.4  279.21  5920.0  280.46  6008.2  281.04
#Mann=3,-1,0
  3793.5     0.1       0  4659.9    0.07       0  4671.1     0.1       0
Bank Sta=4659.9,4671.1
Exp/Cntr=0.3,0.1

Type RM Length L Ch R = 1,12485,352,352,352
BEGIN DESCRIPTION:
UNT 006 in La Jarita Watershed 8.0
END DESCRIPTION:
XS GIS Cut Line= 3
      2117392.29     13402469.22      2116875.00     13401925.00
      2116566.12     13401129.51
#Sta/Elev= 30
  4260.0  276.56  4285.1  276.51  4367.1  276.18  4416.8  275.31  4507.1  274.82
  4614.7  274.22  4734.9  272.37  4883.6  272.25  4954.4  271.67  4982.7  270.27
  4984.0  269.84  4984.7  269.04  4994.5  269.04  4995.2  269.84  4996.9  270.48
  5003.8  270.79  5007.4  271.44  5025.8  272.20  5074.9  272.74  5194.5  274.97
  5243.6  274.92  5273.5  275.56  5298.0  275.36  5397.0  276.18  5466.7  276.17
  5491.3  276.71  5536.5  276.90  5697.4  280.38  5804.7  281.09  5864.2  280.83
#Mann=5,-1,0
  4260.0     0.1       0  4285.1    0.05       0  4507.1     0.1       0
  4984.0    0.07       0  4995.2     0.1       0
Bank Sta=4984,4995.2
Exp/Cntr=0.3,0.1