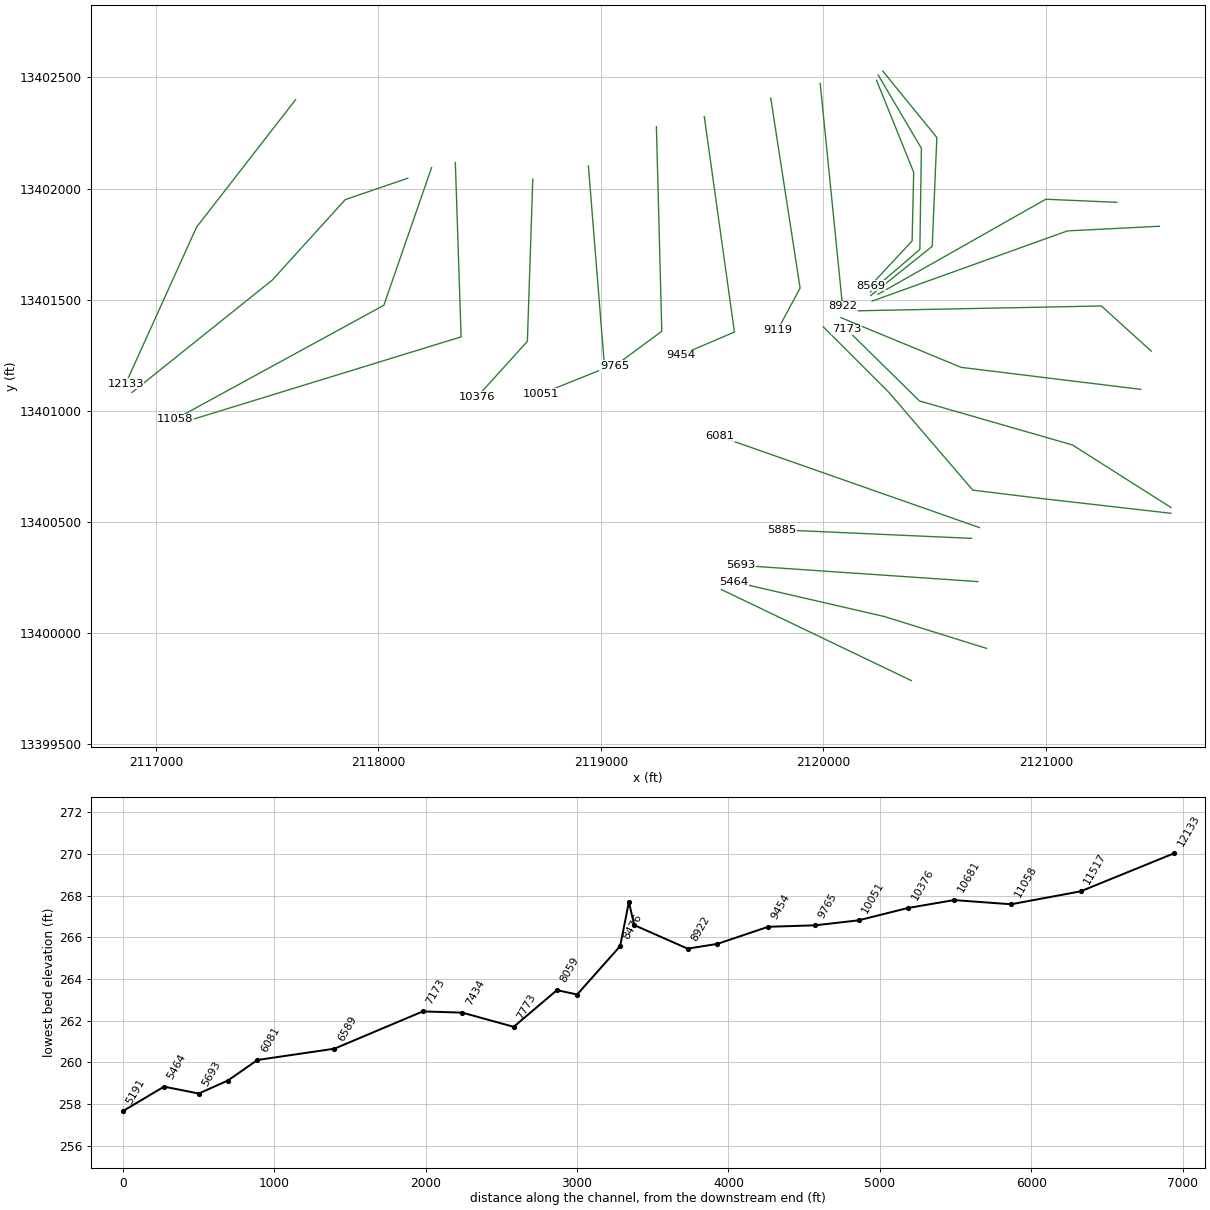
HEC-RAS study UNT 006 in La Jarita Watershed.prj: UNT 006 in La Jarita Watershed Base Level Engineering

--- UNT 006 in La Jarita Watershed.g01 (geometry) --- (continued)

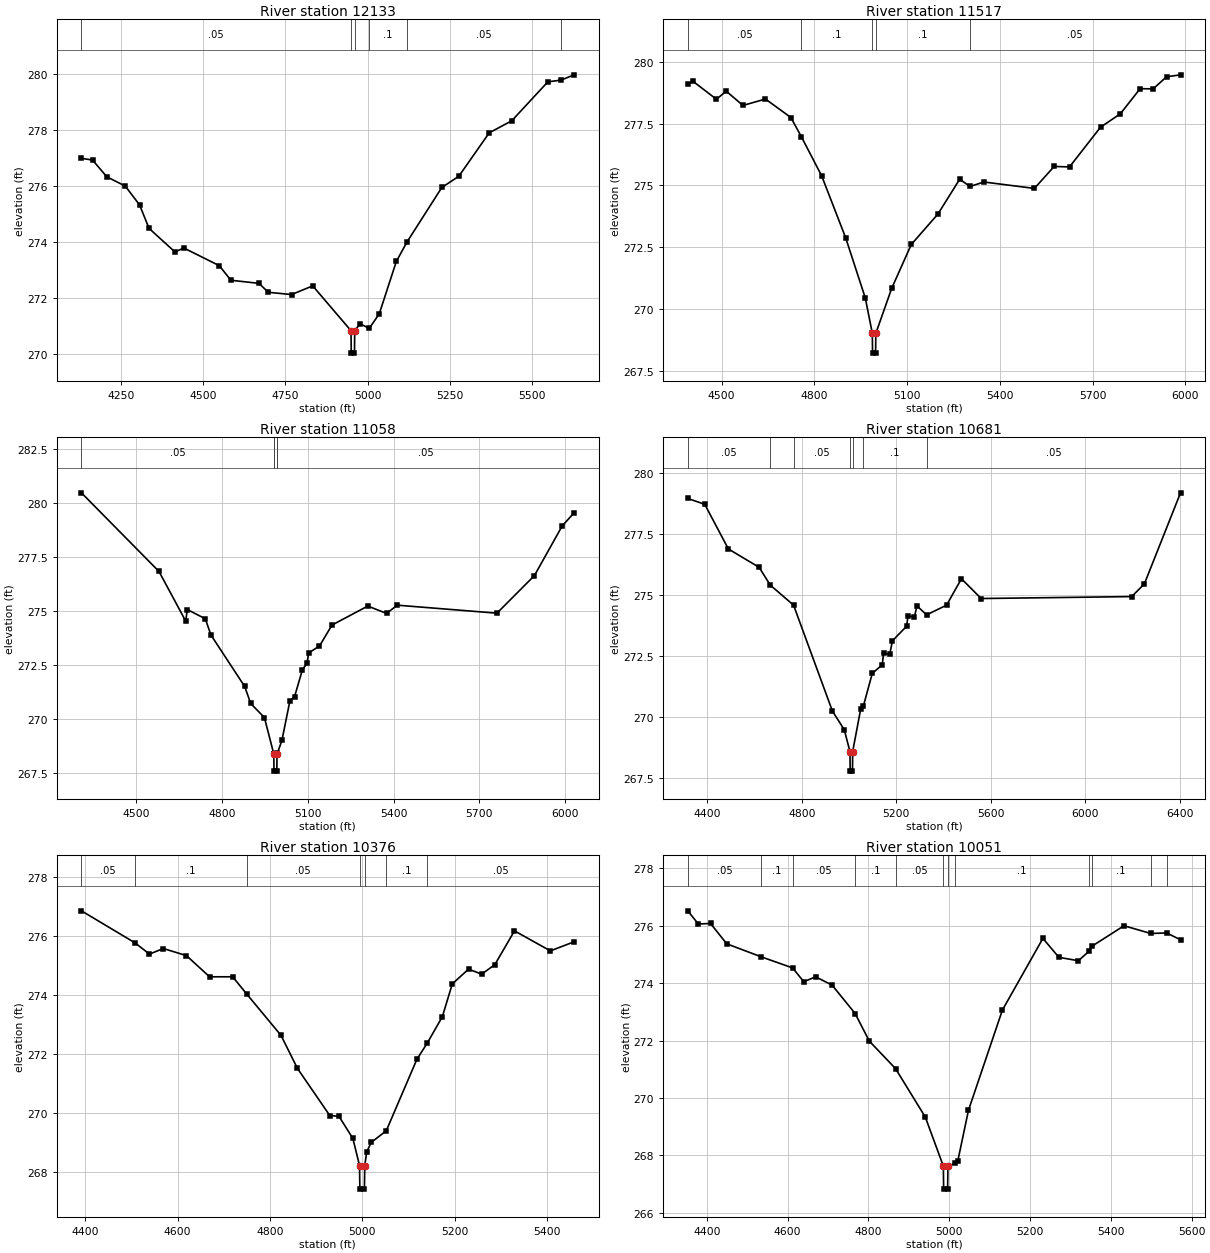
Type RM Length L Ch R = 1,12133,616,616,616
BEGIN DESCRIPTION:
UNT 006 in La Jarita Watershed 7.0
END DESCRIPTION:
XS GIS Cut Line= 3
      2117628.38     13402399.75      2117183.08     13401826.07
      2116864.52     13401122.02
#Sta/Elev= 30
  4129.4  276.98  4163.2  276.92  4206.7  276.32  4262.8  275.99  4306.2  275.32
  4335.2  274.48  4413.9  273.64  4441.1  273.78  4548.8  273.15  4584.1  272.63
  4669.2  272.52  4698.2  272.20  4768.7  272.12  4833.0  272.43  4949.5  270.83
  4950.2  270.03  4960.1  270.03  4960.7  270.83  4977.5  271.08  5004.7  270.91
  5035.4  271.43  5087.3  273.30  5119.0  273.98  5225.7  275.94  5277.4  276.34
  5369.9  277.89  5438.5  278.32  5548.3  279.71  5587.8  279.77  5628.4  279.96
#Mann=6,-1,0
  4129.4    0.05       0  4949.5    0.03       0  4960.7    0.05       0
  5004.7     0.1       0  5119.0    0.05       0  5587.8     0.1       0
Bank Sta=4949.5,4960.7
Exp/Cntr=0.3,0.1

Type RM Length L Ch R = 1,11517,459,459,459
BEGIN DESCRIPTION:
Mapping XS 65979ebe
END DESCRIPTION:
XS GIS Cut Line= 4
      2118132.73     13402046.47      2117851.49     13401950.12
      2117523.37     13401588.14      2116893.12     13401082.91
#Sta/Elev= 30
  4390.9  279.09  4407.6  279.22  4483.6  278.49  4515.3  278.82  4569.3  278.24
  4642.2  278.50  4724.5  277.75  4758.4  276.97  4823.9  275.39  4901.6  272.88
  4965.1  270.44  4987.8  269.01  4988.5  268.21  4998.4  268.21  4999.1  269.01
  5050.3  270.83  5113.8  272.61  5199.8  273.84  5270.2  275.25  5303.9  274.96
  5348.7  275.14  5511.9  274.88  5575.9  275.77  5625.5  275.75  5725.8  277.36
  5789.8  277.90  5853.9  278.92  5896.0  278.91  5939.2  279.40  5984.5  279.48
#Mann=5,-1,0
  4390.9    0.05       0  4758.4     0.1       0  4987.8    0.07       0
  4999.1     0.1       0  5303.9    0.05       0
Bank Sta=4987.8,4999.1
Exp/Cntr=0.3,0.1

Type RM Length L Ch R = 1,11058,377,377,377
BEGIN DESCRIPTION:
UNT 006 in La Jarita Watershed 6.0
END DESCRIPTION:
XS GIS Cut Line= 3
      2118239.51     13402094.21      2118025.00     13401475.00
      2117088.34     13400963.15
#Sta/Elev= 30
  4308.9  280.47  4580.1  276.83  4673.6  274.53  4678.9  275.07  4742.0  274.64
  4761.7  273.89  4879.6  271.51  4900.7  270.72  4948.6  270.07  4981.3  268.39
  4981.4  268.39  4982.1  267.59  4992.0  267.59  4992.7  268.39  4993.9  268.42
  5009.8  269.01  5037.7  270.84  5053.9  271.03  5081.4  272.28  5097.5  272.58
  5103.2  273.06  5141.2  273.38  5184.8  274.35  5310.0  275.23  5375.5  274.89
  5413.5  275.27  5761.6  274.90  5892.6  276.64  5989.8  278.94  6031.6  279.55
#Mann=5,-1,0
  4308.9    0.05       0  4981.3     0.1       0  4981.4    0.03       0
  4992.7     0.1       0  4993.9    0.05       0
Bank Sta=4981.4,4992.7
Exp/Cntr=0.3,0.1

Type RM Length L Ch R = 1,10681,305,305,305
BEGIN DESCRIPTION:
Mapping XS d261f633
END DESCRIPTION:
XS GIS Cut Line= 3
      2118346.28     13402116.76      2118372.32     13401332.93
      2117128.76     13400950.50
#Sta/Elev= 30
  4317.4  278.96  4389.2  278.72  4489.3  276.89  4619.3  276.14  4666.5  275.41
  4765.1  274.59  4929.5  270.25  4979.5  269.49  5003.9  268.59  5004.6  267.79
  5014.5  267.79  5015.2  268.59  5049.6  270.35  5061.0  270.47  5098.1  271.79
  5140.6  272.15  5145.8  272.61  5172.1  272.58  5183.7  273.13  5243.9  273.73
  5249.1  274.14  5276.6  274.11  5287.2  274.56  5328.1  274.19  5412.7  274.59
  5475.5  275.67  5559.2  274.86  6196.2  274.94  6249.7  275.46  6402.7  279.19
#Mann=7,-1,0
  4317.4    0.05       0  4666.5     0.1       0  4765.1    0.05       0
  5003.9   0.033       0  5015.2    0.05       0  5061.0     0.1       0
  5328.1    0.05       0
Bank Sta=5003.9,5015.2
Exp/Cntr=0.3,0.1

Type RM Length L Ch R = 1,10376,325,325,325
BEGIN DESCRIPTION:
Mapping XS 29172e1c
END DESCRIPTION:
XS GIS Cut Line= 3
      2118694.37     13402042.10      2118670.07     13401312.97
      2118444.40     13401063.00
#Sta/Elev= 30
  4392.1  276.86  4508.3  275.77  4539.3  275.39  4569.3  275.58  4619.3  275.34
  4669.4  274.62  4719.4  274.62  4749.5  274.04  4824.0  272.63  4859.5  271.51
  4929.5  269.91  4949.5  269.88  4979.5  269.13  4993.9  268.21  4994.6  267.41
  5004.5  267.41  5005.2  268.21  5009.5  268.68  5019.5  269.00  5051.7  269.39
  5118.1  271.82  5140.1  272.36  5173.0  273.26  5194.7  274.38  5229.8  274.88
  5258.2  274.71  5286.6  275.03  5329.2  276.18  5406.9  275.50  5458.4  275.81
#Mann=7,-1,0
  4392.1    0.05       0  4508.3     0.1       0  4749.5    0.05       0
  4993.9   0.033       0  5005.2    0.05       0  5051.7     0.1       0
  5140.1    0.05       0
Bank Sta=4993.9,5005.2
Exp/Cntr=0.3,0.1

Type RM Length L Ch R = 1,10051,286,286,286
BEGIN DESCRIPTION:
Mapping XS 0792c044
END DESCRIPTION:
XS GIS Cut Line= 3
      2118944.37     13402101.16      2119017.29     13401191.44
      2118732.52     13401076.84
#Sta/Elev= 30
  4352.9  276.52  4379.1  276.06  4409.2  276.08  4449.4  275.37  4534.0  274.92
  4612.4  274.53  4640.0  274.05  4669.4  274.22  4710.2  273.93  4767.2  272.94
  4802.2  271.98  4867.2  271.02  4940.9  269.33  4985.5  267.62  4986.2  266.82
  4996.1  266.82  4996.8  267.62  5014.5  267.72  5021.2  267.80  5047.7  269.57
  5131.6  273.06  5231.9  275.56  5271.4  274.90  5319.7  274.78  5346.8  275.12
  5352.6  275.28  5432.6  276.00  5499.0  275.73  5538.2  275.75  5572.5  275.51
#Mann=12,-1,0
  4352.9    0.05       0  4534.0     0.1       0  4612.4    0.05       0
  4767.2     0.1       0  4867.2    0.05       0  4985.5    0.03       0
  4996.8    0.05       0  5014.5     0.1       0  5346.8    0.05       0
  5352.6     0.1       0  5499.0    0.05       0  5538.2     0.1       0
Bank Sta=4985.5,4996.8
Exp/Cntr=0.3,0.1

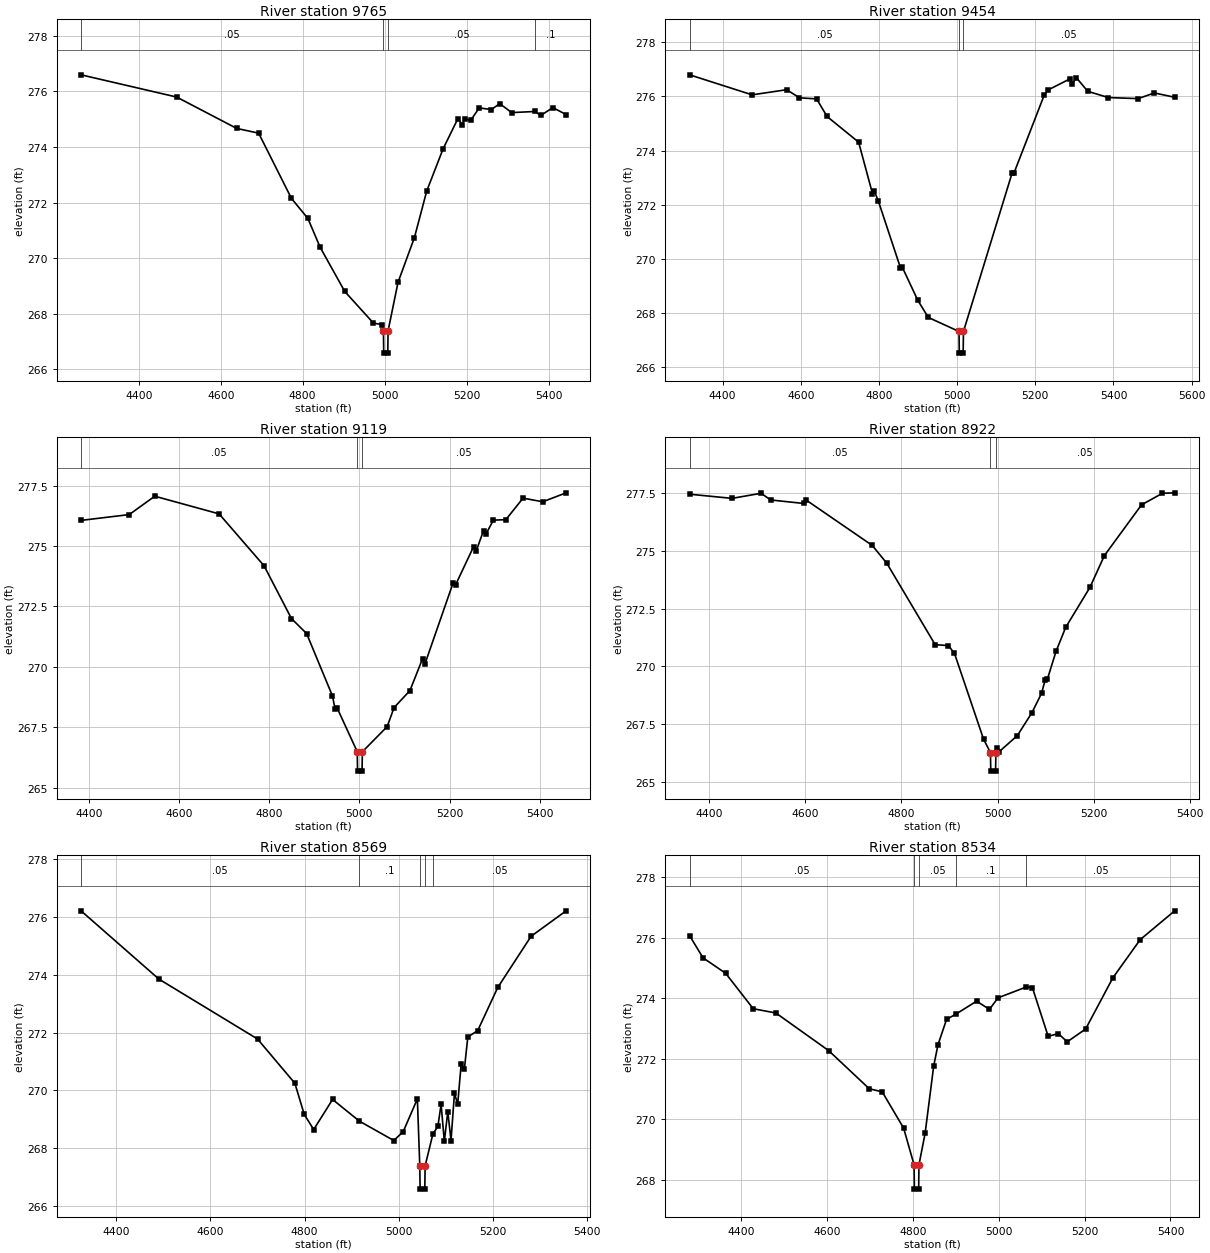
Type RM Length L Ch R = 1,9765,311,311,311
BEGIN DESCRIPTION:
Mapping XS f4254a7b
END DESCRIPTION:
XS GIS Cut Line= 3
      2119249.93     13402278.26      2119274.23     13401358.11
      2119062.41     13401201.85
#Sta/Elev= 30
  4259.2  276.60  4492.5  275.80  4639.1  274.67  4692.6  274.50  4772.6  272.15
  4812.7  271.43  4842.7  270.39  4902.7  268.80  4972.7  267.66  4992.7  267.61
  4997.1  267.38  4997.8  266.58  5007.7  266.58  5008.4  267.38  5032.7  269.13
  5072.7  270.74  5102.8  272.42  5142.8  273.94  5178.7  275.02  5189.1  274.81
  5195.4  275.01  5210.0  274.96  5230.8  275.41  5260.1  275.35  5281.0  275.56
  5310.2  275.24  5366.2  275.28  5381.2  275.14  5410.5  275.42  5442.9  275.17
#Mann=4,-1,0
  4259.2    0.05       0  4997.1    0.03       0  5008.4    0.05       0
  5366.2     0.1       0
Bank Sta=4997.1,5008.4
Exp/Cntr=0.3,0.1

Type RM Length L Ch R = 1,9454,335,335,335
BEGIN DESCRIPTION:
Mapping XS ea9b030c
END DESCRIPTION:
XS GIS Cut Line= 3
      2119465.21     13402323.34      2119600.62     13401354.64
      2119358.82     13401251.01
#Sta/Elev= 30
  4315.4  276.80  4475.3  276.06  4563.9  276.25  4596.4  275.95  4640.4  275.91
  4667.1  275.26  4747.9  274.31  4783.3  272.41  4788.4  272.49  4798.4  272.13
  4854.8  269.67  4859.8  269.68  4899.4  268.46  4926.2  267.83  5004.8  267.31
  5005.4  266.51  5015.4  266.51  5016.1  267.31  5140.6  273.17  5145.7  273.18
  5222.5  276.04  5232.6  276.24  5288.6  276.65  5293.5  276.46  5305.2  276.69
  5334.2  276.19  5386.8  275.96  5462.9  275.92  5504.6  276.13  5556.6  275.97
#Mann=3,-1,0
  4315.4    0.05       0  5004.8    0.03       0  5016.1    0.05       0
Bank Sta=5004.8,5016.1
Exp/Cntr=0.3,0.1

Type RM Length L Ch R = 1,9119,197,197,197
BEGIN DESCRIPTION:
Mapping XS 6e5ca436
END DESCRIPTION:
XS GIS Cut Line= 3
      2119763.81     13402406.76      2119895.76     13401552.55
      2119795.05     13401365.02
#Sta/Elev= 30
  4381.8  276.06  4488.8  276.30  4545.5  277.06  4688.3  276.33  4788.3  274.18
  4849.0  272.00  4882.7  271.38  4940.1  268.80  4945.8  268.27  4950.8  268.29
  4995.2  266.49  4995.8  265.69  5005.8  265.69  5006.5  266.49  5061.5  267.53
  5077.0  268.32  5112.1  269.02  5140.2  270.34  5145.2  270.11  5208.3  273.49
  5213.4  273.39  5253.7  274.98  5259.4  274.80  5275.6  275.64  5281.3  275.51
  5297.5  276.07  5325.1  276.09  5363.3  276.98  5407.1  276.83  5459.0  277.20
#Mann=3,-1,0
  4381.8    0.05       0  4995.2    0.03       0  5006.5    0.05       0
Bank Sta=4995.2,5006.5
Exp/Cntr=0.3,0.1

Type RM Length L Ch R = 1,8922,353,353,353
BEGIN DESCRIPTION:
Mapping XS 37557d17
END DESCRIPTION:
XS GIS Cut Line= 2
      2119986.04     13402472.72      2120086.69     13401469.66
#Sta/Elev= 30
  4360.1  277.46  4448.3  277.28  4508.6  277.50  4528.7  277.21  4597.0  277.06
  4602.1  277.21  4739.7  275.24  4769.9  274.47  4870.4  270.94  4898.0  270.90
  4910.6  270.56  4970.9  266.85  4985.3  266.26  4986.0  265.46  4996.0  265.46
  4996.6  266.26  4998.4  266.45  5003.4  266.30  5041.2  267.00  5071.4  267.99
  5091.5  268.83  5098.7  269.39  5103.7  269.45  5121.6  270.65  5141.7  271.69
  5192.0  273.42  5222.1  274.80  5299.3  277.00  5342.7  277.50  5368.2  277.52
#Mann=3,-1,0
  4360.1    0.05       0  4985.3    0.03       0  4996.6    0.05       0
Bank Sta=4985.3,4996.6
Exp/Cntr=0.3,0.1

Type RM Length L Ch R = 1,8569,35,35,35
BEGIN DESCRIPTION:
Mapping XS 15c3dc20
END DESCRIPTION:
XS GIS Cut Line= 4
      2120239.51     13402486.58      2120406.18     13402073.39
      2120399.23     13401764.36      2120211.74     13401562.98
#Sta/Elev= 30
  4325.3  276.21  4490.6  273.85  4699.9  271.78  4779.2  270.25  4799.2  269.17
  4819.2  268.65  4859.3  269.69  4916.2  268.94  4989.3  268.27  5009.3  268.58
  5039.3  269.71  5044.4  267.39  5045.1  266.59  5055.1  266.59  5055.7  267.39
  5072.0  268.48  5082.9  268.77  5089.7  269.52  5096.5  268.24  5103.9  269.27
  5110.7  268.27  5118.0  269.90  5124.9  269.53  5132.2  270.90  5139.0  270.73
  5146.4  271.85  5167.4  272.07  5209.9  273.56  5280.7  275.33  5355.1  276.21
#Mann=5,-1,0
  4325.3    0.05       0  4916.2     0.1       0  5044.4    0.07       0
  5055.7     0.1       0  5072.0    0.05       0
Bank Sta=5044.4,5055.7
Exp/Cntr=0.3,0.1

Type RM Length L Ch R = 1,8534,58,58,58
BEGIN DESCRIPTION:
Mapping XS 3fd5c249
END DESCRIPTION:
XS GIS Cut Line= 4
      2120246.45     13402510.90      2120440.90     13402181.02
      2120433.96     13401726.16      2120211.76     13401535.22
#Sta/Elev= 30
  4279.1  276.06  4310.4  275.33  4363.1  274.82  4427.5  273.65  4480.2  273.51
  4603.2  272.27  4698.0  271.01  4728.1  270.91  4778.1  269.71  4802.4  268.50
  4803.1  267.70  4813.1  267.70  4813.7  268.50  4828.1  269.54  4848.1  271.76
  4858.1  272.46  4878.1  273.30  4899.6  273.47  4948.1  273.90  4978.1  273.63
  4998.1  274.01  5064.4  274.37  5078.1  274.35  5115.0  272.74  5138.5  272.83
  5159.4  272.56  5202.2  272.98  5265.8  274.67  5329.5  275.93  5409.9  276.88
#Mann=5,-1,0
  4279.1    0.05       0  4802.4    0.07       0  4813.7    0.05       0
  4899.6     0.1       0  5064.4    0.05       0
Bank Sta=4802.4,4813.7
Exp/Cntr=0.3,0.1

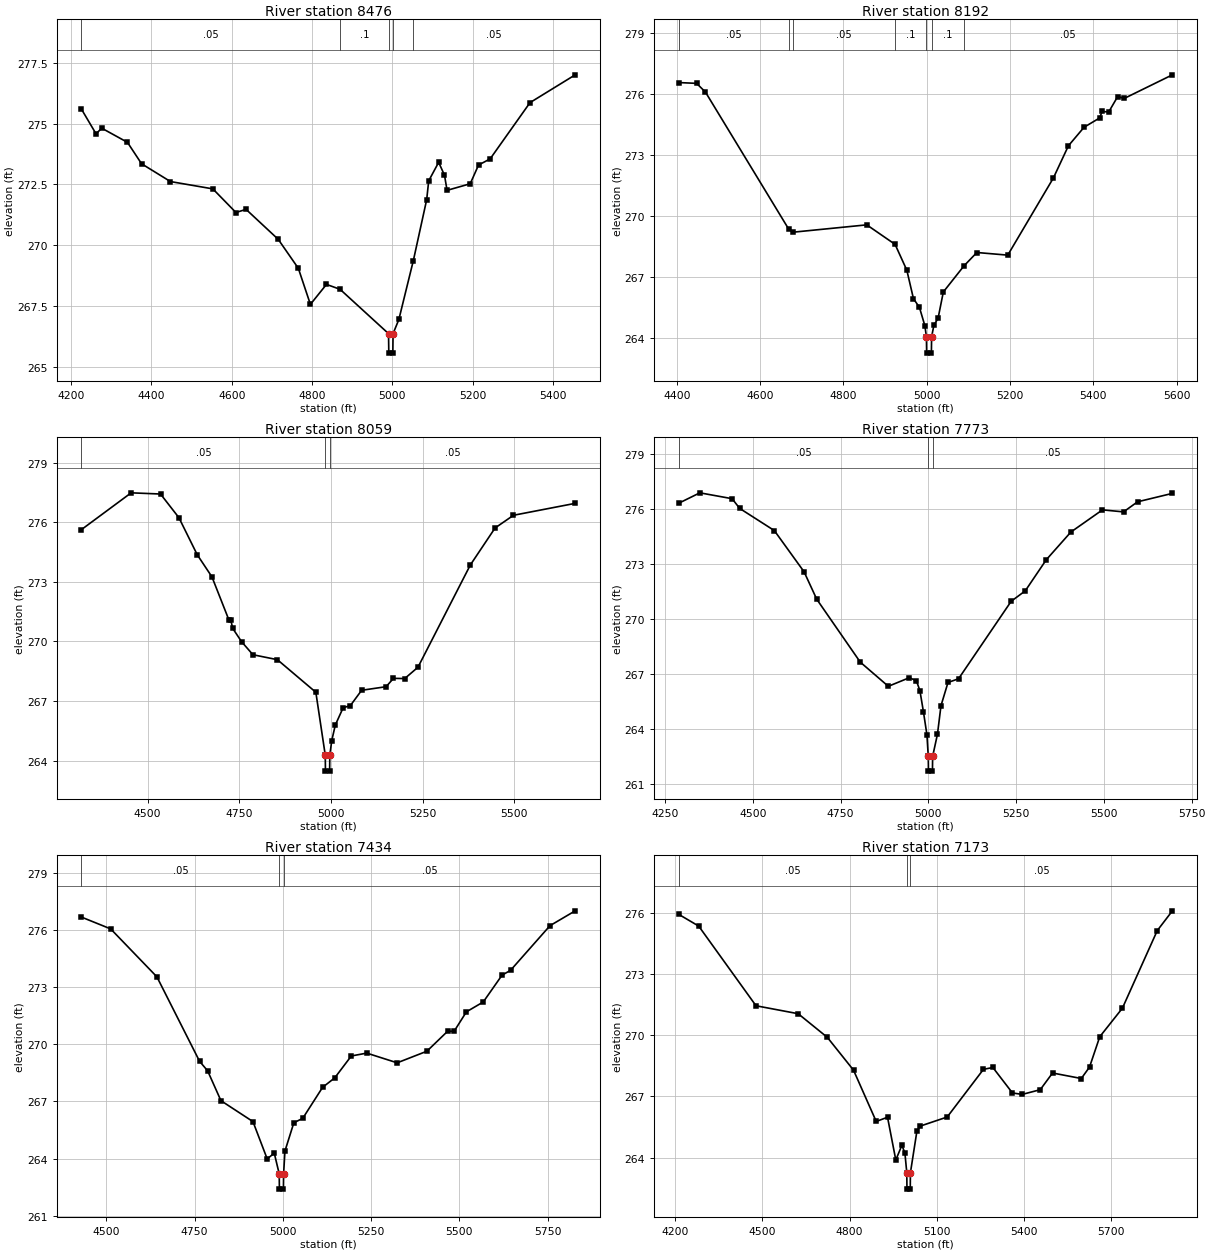
Type RM Length L Ch R = 1,8476,284,284,284
BEGIN DESCRIPTION:
Mapping XS 70092964
END DESCRIPTION:
XS GIS Cut Line= 4
      2120267.32     13402528.21      2120510.34     13402229.64
      2120489.51     13401740.05      2120213.09     13401518.92
#Sta/Elev= 30
  4226.1  275.59  4262.3  274.58  4276.6  274.81  4340.5  274.23  4375.7  273.35
  4447.6  272.62  4553.1  272.32  4610.6  271.35  4635.7  271.48  4715.8  270.25
  4765.9  269.06  4795.9  267.58  4835.9  268.40  4869.7  268.20  4990.4  266.38
  4991.1  265.58  5001.1  265.58  5001.7  266.38  5016.1  266.96  5052.2  269.38
  5085.4  271.88  5090.4  272.65  5115.2  273.41  5129.7  272.88  5136.1  272.26
  5193.7  272.53  5214.5  273.30  5243.3  273.55  5342.6  275.86  5455.1  277.00
#Mann=5,-1,0
  4226.1    0.05       0  4869.7     0.1       0  4990.4    0.07       0
  5001.7     0.1       0  5052.2    0.05       0
Bank Sta=4990.4,5001.7
Exp/Cntr=0.3,0.1

Type RM Length L Ch R = 1,8192,133,133,133
BEGIN DESCRIPTION:
Mapping XS d1e9bf87
END DESCRIPTION:
XS GIS Cut Line= 3
      2121319.35     13401937.97      2120999.93     13401951.86
      2120246.47     13401524.78
#Sta/Elev= 30
  4404.1  276.57  4447.2  276.53  4468.5  276.10  4668.7  269.35  4679.5  269.21
  4855.9  269.57  4923.9  268.61  4952.1  267.34  4968.0  265.94  4982.4  265.51
  4995.4  264.61  4999.2  264.06  4999.7  263.26  5011.1  263.26  5011.6  264.06
  5017.1  264.63  5027.2  264.98  5039.8  266.27  5089.3  267.55  5120.3  268.21
  5194.5  268.08  5304.2  271.88  5340.2  273.46  5377.7  274.37  5415.3  274.83
  5421.0  275.15  5436.9  275.12  5458.5  275.88  5474.4  275.79  5589.9  276.95
#Mann=7,-1,0
  4404.1    0.05       0  4668.7     0.1       0  4679.5    0.05       0
  4923.9     0.1       0  4999.2    0.07       0  5011.6     0.1       0
  5089.3    0.05       0
Bank Sta=4999.2,5011.6
Exp/Cntr=0.3,0.1

Type RM Length L Ch R = 1,8059,286,286,286
BEGIN DESCRIPTION:
Mapping XS 6013566f
END DESCRIPTION:
XS GIS Cut Line= 3
      2121510.36     13401830.33      2121097.15     13401809.50
      2120219.34     13401493.76
#Sta/Elev= 30
  4319.5  275.63  4455.0  277.48  4535.1  277.42  4585.2  276.23  4635.3  274.36
  4675.3  273.25  4721.8  271.07  4726.8  271.08  4731.8  270.66  4756.4  269.98
  4787.1  269.33  4853.8  269.08  4958.7  267.44  4984.4  264.27  4984.9  263.47
  4996.3  263.47  4996.8  264.27  5002.1  265.01  5011.8  265.79  5033.1  266.66
  5052.9  266.77  5083.6  267.54  5150.3  267.72  5170.4  268.14  5201.1  268.13
  5237.2  268.70  5380.1  273.85  5447.5  275.71  5497.7  276.35  5666.1  276.95
#Mann=3,-1,0
  4319.5    0.05       0  4984.4    0.03       0  4996.8    0.05       0
Bank Sta=4984.4,4996.8
Exp/Cntr=0.3,0.1

Type RM Length L Ch R = 1,7773,339,339,339
BEGIN DESCRIPTION:
UNT 006 in La Jarita Watershed 5.0
END DESCRIPTION:
XS GIS Cut Line= 3
      2121473.91     13401268.67      2121249.93     13401471.82
      2120145.83     13401450.00
#Sta/Elev= 30
  4288.4  276.33  4348.8  276.90  4440.7  276.58  4462.3  276.05  4561.0  274.84
  4645.7  272.59  4681.9  271.09  4805.8  267.66  4885.8  266.34  4945.8  266.81
  4965.8  266.64  4975.8  266.10  4985.8  264.95  4995.8  263.69  4999.6  262.51
  5000.1  261.71  5011.5  261.71  5012.0  262.51  5025.8  263.73  5035.8  265.28
  5055.8  266.55  5085.8  266.75  5235.8  270.98  5275.9  271.55  5335.9  273.25
  5405.9  274.76  5495.9  275.97  5555.9  275.86  5595.9  276.41  5695.1  276.87
#Mann=3,-1,0
  4288.4    0.05       0  4999.6    0.03       0  5012.0    0.05       0
Bank Sta=4999.6,5012
Exp/Cntr=0.3,0.1

Type RM Length L Ch R = 1,7434,261,261,261
BEGIN DESCRIPTION:
Mapping XS d0667e96
END DESCRIPTION:
XS GIS Cut Line= 3
      2121427.06     13401096.82      2120619.72     13401195.78
      2120079.00     13401419.35
#Sta/Elev= 30
  4429.5  276.69  4512.2  276.07  4643.1  273.55  4764.0  269.11  4786.8  268.61
  4824.5  267.04  4915.2  265.94  4955.5  263.98  4975.6  264.28  4989.6  263.19
  4990.1  262.39  5001.5  262.39  5002.0  263.19  5005.8  264.39  5031.0  265.88
  5056.2  266.11  5112.4  267.74  5146.9  268.24  5193.8  269.39  5237.6  269.54
  5323.7  269.03  5407.9  269.64  5466.6  270.69  5485.1  270.69  5519.8  271.71
  5567.6  272.23  5620.8  273.64  5644.7  273.89  5756.6  276.24  5828.0  277.02
#Mann=3,-1,0
  4429.5    0.05       0  4989.6    0.03       0  5002.0    0.05       0
Bank Sta=4989.6,5002
Exp/Cntr=0.3,0.1

Type RM Length L Ch R = 1,7173,584,584,584
BEGIN DESCRIPTION:
Mapping XS 91b36e83
END DESCRIPTION:
XS GIS Cut Line= 4
      2121562.41     13400565.58      2121119.72     13400846.82
      2120432.22     13401044.74      2120104.07     13401367.68
#Sta/Elev= 30
  4211.6  275.94  4280.7  275.36  4478.0  271.45  4623.2  271.06  4723.6  269.90
  4813.8  268.29  4892.0  265.77  4930.9  265.98  4959.4  263.88  4980.3  264.60
  4990.7  264.23  4997.3  263.25  4997.8  262.45  5009.2  262.45  5009.7  263.25
  5031.9  265.28  5042.8  265.54  5136.4  265.99  5261.3  268.33  5293.7  268.42
  5361.1  267.17  5394.8  267.10  5456.8  267.33  5499.2  268.15  5598.2  267.88
  5626.5  268.44  5661.8  269.93  5739.7  271.33  5859.8  275.14  5911.9  276.11
#Mann=3,-1,0
  4211.6    0.05       0  4997.3    0.03       0  5009.7    0.05       0
Bank Sta=4997.3,5009.7
Exp/Cntr=0.3,0.1

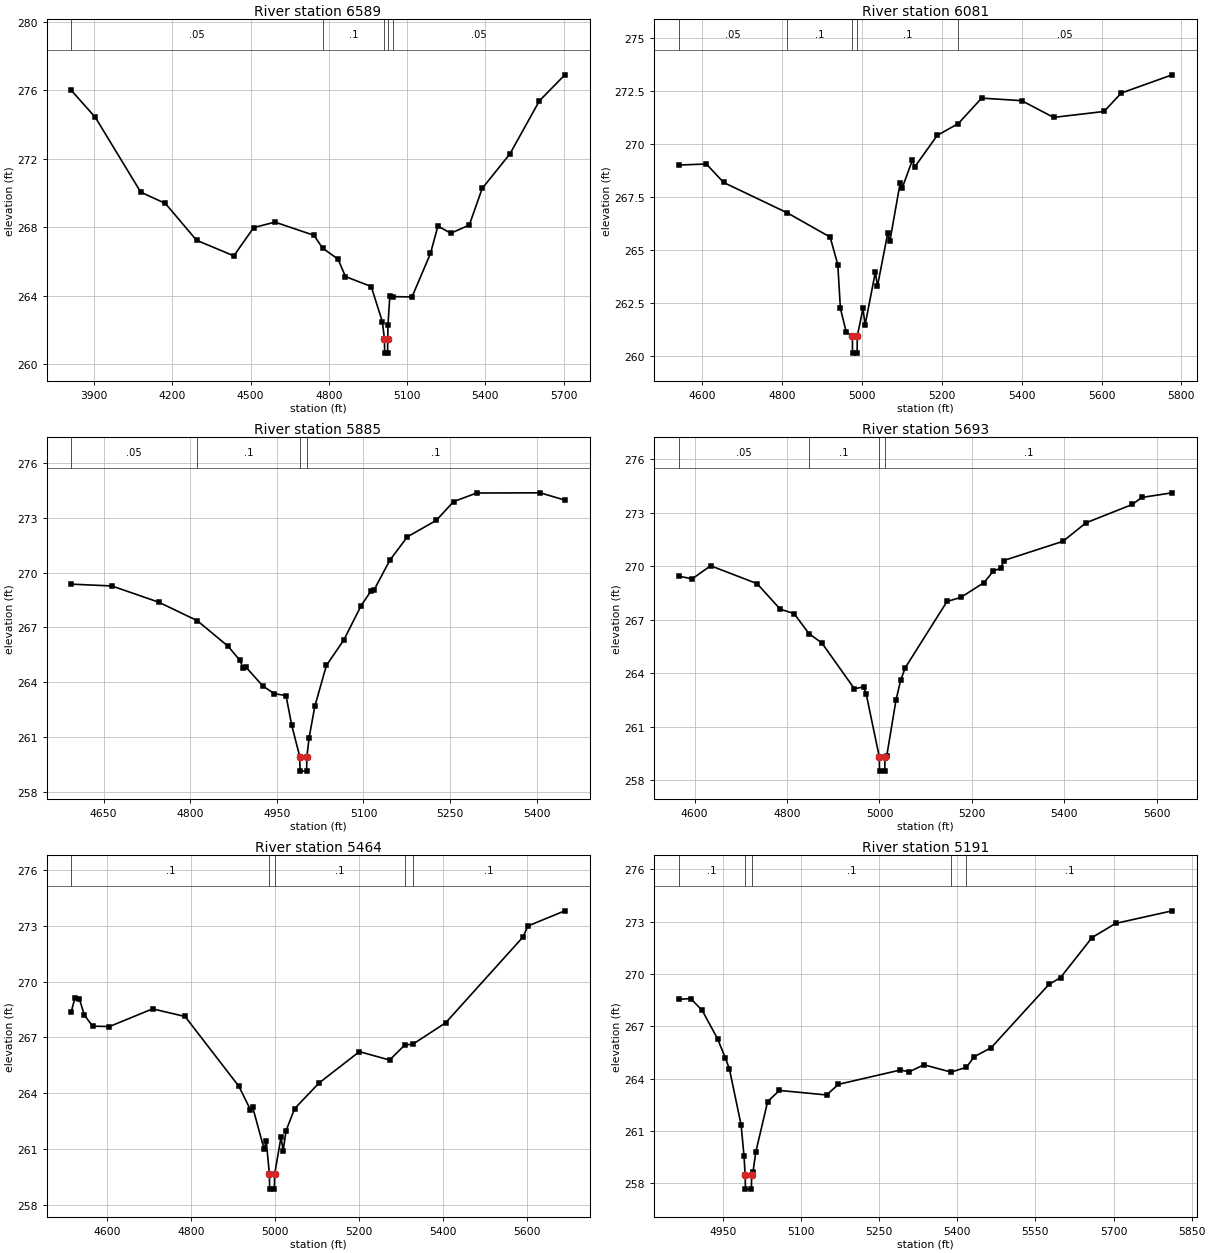
Type RM Length L Ch R = 1,6589,508,508,508
BEGIN DESCRIPTION:
Mapping XS 94a720b1
END DESCRIPTION:
XS GIS Cut Line= 5
      2121562.46     13400539.53      2120968.68     13400607.24
      2120671.80     13400643.70      2120296.80     13401081.20
      2119999.93     13401378.07
#Sta/Elev= 30
  3812.4  276.01  3905.1  274.42  4079.0  270.06  4173.4  269.40  4293.0  267.25
  4435.8  266.34  4512.1  267.99  4593.4  268.31  4743.2  267.54  4776.2  266.79
  4835.4  266.15  4863.9  265.13  4962.7  264.55  5005.5  262.49  5013.6  261.46
  5014.1  260.66  5025.5  260.66  5026.0  261.46  5026.9  262.28  5034.1  264.02
  5046.5  263.96  5119.1  263.94  5189.9  266.48  5218.5  268.08  5267.8  267.66
  5338.8  268.14  5388.3  270.28  5494.4  272.29  5607.5  275.39  5705.2  276.91
#Mann=5,-1,0
  3812.4    0.05       0  4776.2     0.1       0  5013.6    0.07       0
  5026.0     0.1       0  5046.5    0.05       0
Bank Sta=5013.6,5026
Exp/Cntr=0.3,0.1

Type RM Length L Ch R = 1,6081,196,196,196
BEGIN DESCRIPTION:
Mapping XS 78c73fcb
END DESCRIPTION:
XS GIS Cut Line= 2
      2120701.33     13400475.29      2119534.69     13400885.00
#Sta/Elev= 30
  4540.5  269.00  4610.3  269.05  4653.2  268.18  4813.2  266.74  4920.2  265.60
  4939.4  264.30  4945.9  262.24  4960.6  261.11  4975.9  260.92  4976.4  260.12
  4987.8  260.12  4988.3  260.92  5002.5  262.23  5007.8  261.45  5033.5  263.94
  5038.8  263.28  5064.5  265.78  5069.8  265.40  5095.5  268.14  5100.8  267.92
  5126.5  269.24  5131.8  268.90  5188.5  270.40  5241.4  270.96  5299.7  272.16
  5400.1  272.04  5479.9  271.25  5606.4  271.53  5649.5  272.40  5777.0  273.26
#Mann=5,-1,0
  4540.5    0.05       0  4813.2     0.1       0  4975.9    0.07       0
  4988.3     0.1       0  5241.4    0.05       0
Bank Sta=4975.9,4988.3
Exp/Cntr=0.3,0.1

Type RM Length L Ch R = 1,5885,192,192,192
BEGIN DESCRIPTION:
Mapping XS 841e363e
END DESCRIPTION:
XS GIS Cut Line= 2
      2120666.59     13400426.68      2119812.45     13400464.88
#Sta/Elev= 30
  4593.8  269.37  4664.2  269.27  4745.5  268.38  4812.1  267.37  4865.7  265.96
  4885.7  265.21  4891.3  264.80  4896.3  264.83  4925.7  263.79  4945.7  263.37
  4965.8  263.27  4975.8  261.63  4989.6  259.93  4990.1  259.13  5001.5  259.13
  5002.0  259.93  5005.8  260.96  5015.8  262.69  5035.8  264.92  5065.9  266.31
  5095.9  268.19  5113.3  269.01  5118.3  269.05  5145.9  270.69  5176.0  271.96
  5226.0  272.86  5256.1  273.89  5296.1  274.36  5406.2  274.37  5448.8  273.97
#Mann=4,-1,0
  4593.8    0.05       0  4812.1     0.1       0  4989.6    0.07       0
  5002.0     0.1       0
Bank Sta=4989.6,5002
Exp/Cntr=0.3,0.1

Type RM Length L Ch R = 1,5693,229,229,229
BEGIN DESCRIPTION:
Mapping XS a6bb7638
END DESCRIPTION:
XS GIS Cut Line= 2
      2120694.39     13400232.24      2119629.17     13400305.10
#Sta/Elev= 30
  4565.4  269.44  4594.9  269.29  4634.9  270.02  4735.2  269.02  4785.3  267.59
  4815.4  267.34  4847.4  266.22  4875.5  265.69  4945.7  263.13  4965.7  263.23
  4971.5  262.81  4999.6  259.31  5000.1  258.51  5011.5  258.51  5012.0  259.31
  5015.8  259.37  5035.9  262.51  5045.9  263.61  5055.9  264.31  5146.1  268.02
  5176.2  268.25  5226.3  269.08  5246.4  269.73  5263.3  269.89  5268.3  270.31
  5396.7  271.39  5446.8  272.43  5547.1  273.46  5567.1  273.85  5633.1  274.11
#Mann=4,-1,0
  4565.4    0.05       0  4847.4     0.1       0  4999.6    0.07       0
  5012.0     0.1       0
Bank Sta=4999.6,5012
Exp/Cntr=0.3,0.1

Type RM Length L Ch R = 1,5464,273,273,273
BEGIN DESCRIPTION:
UNT 006 in La Jarita Watershed 2.0
END DESCRIPTION:
XS GIS Cut Line= 3
      2120733.47     13399931.88      2120275.00     13400075.00
      2119598.66     13400231.06
#Sta/Elev= 30
  4515.4  268.38  4524.3  269.11  4534.7  269.07  4546.6  268.20  4566.2  267.60
  4606.3  267.58  4709.0  268.53  4786.2  268.12  4914.5  264.36  4941.7  263.11
  4946.9  263.26  4974.2  261.00  4979.4  261.42  4986.9  259.64  4987.4  258.84
  4998.8  258.84  4999.3  259.64  5014.5  261.63  5019.6  260.91  5026.5  261.98
  5047.0  263.17  5105.2  264.55  5201.0  266.23  5272.8  265.78  5308.7  266.58
  5328.7  266.64  5406.2  267.78  5590.9  272.41  5601.2  272.98  5689.8  273.80
#Mann=5,-1,0
  4515.4     0.1       0  4986.9    0.07       0  4999.3     0.1       0
  5308.7    0.05       0  5328.7     0.1       0
Bank Sta=4986.9,4999.3
Exp/Cntr=0.3,0.1

Type RM Length L Ch R = 1,5191,372,372,372
BEGIN DESCRIPTION:
Mapping XS 5ca1ac4e
END DESCRIPTION:
XS GIS Cut Line= 2
      2120395.95     13399786.91      2119541.73     13400196.65
#Sta/Elev= 30
  4865.2  268.54  4888.4  268.59  4910.6  267.91  4940.0  266.29  4955.0  265.18
  4962.7  264.57  4985.3  261.34  4990.9  259.54  4993.1  258.46  4993.6  257.66
  5005.0  257.66  5005.5  258.46  5008.0  258.62  5013.5  259.79  5036.2  262.68
  5058.8  263.32  5149.4  263.06  5172.1  263.67  5290.9  264.49  5308.0  264.39
  5336.2  264.79  5388.4  264.37  5417.8  264.65  5432.4  265.25  5465.2  265.77
  5576.1  269.40  5598.3  269.79  5658.9  272.09  5704.2  272.90  5812.6  273.62
#Mann=5,-1,0
  4865.2     0.1       0  4993.1    0.07       0  5005.5     0.1       0
  5388.4    0.05       0  5417.8     0.1       0
Bank Sta=4993.1,5005.5
Exp/Cntr=0.3,0.1