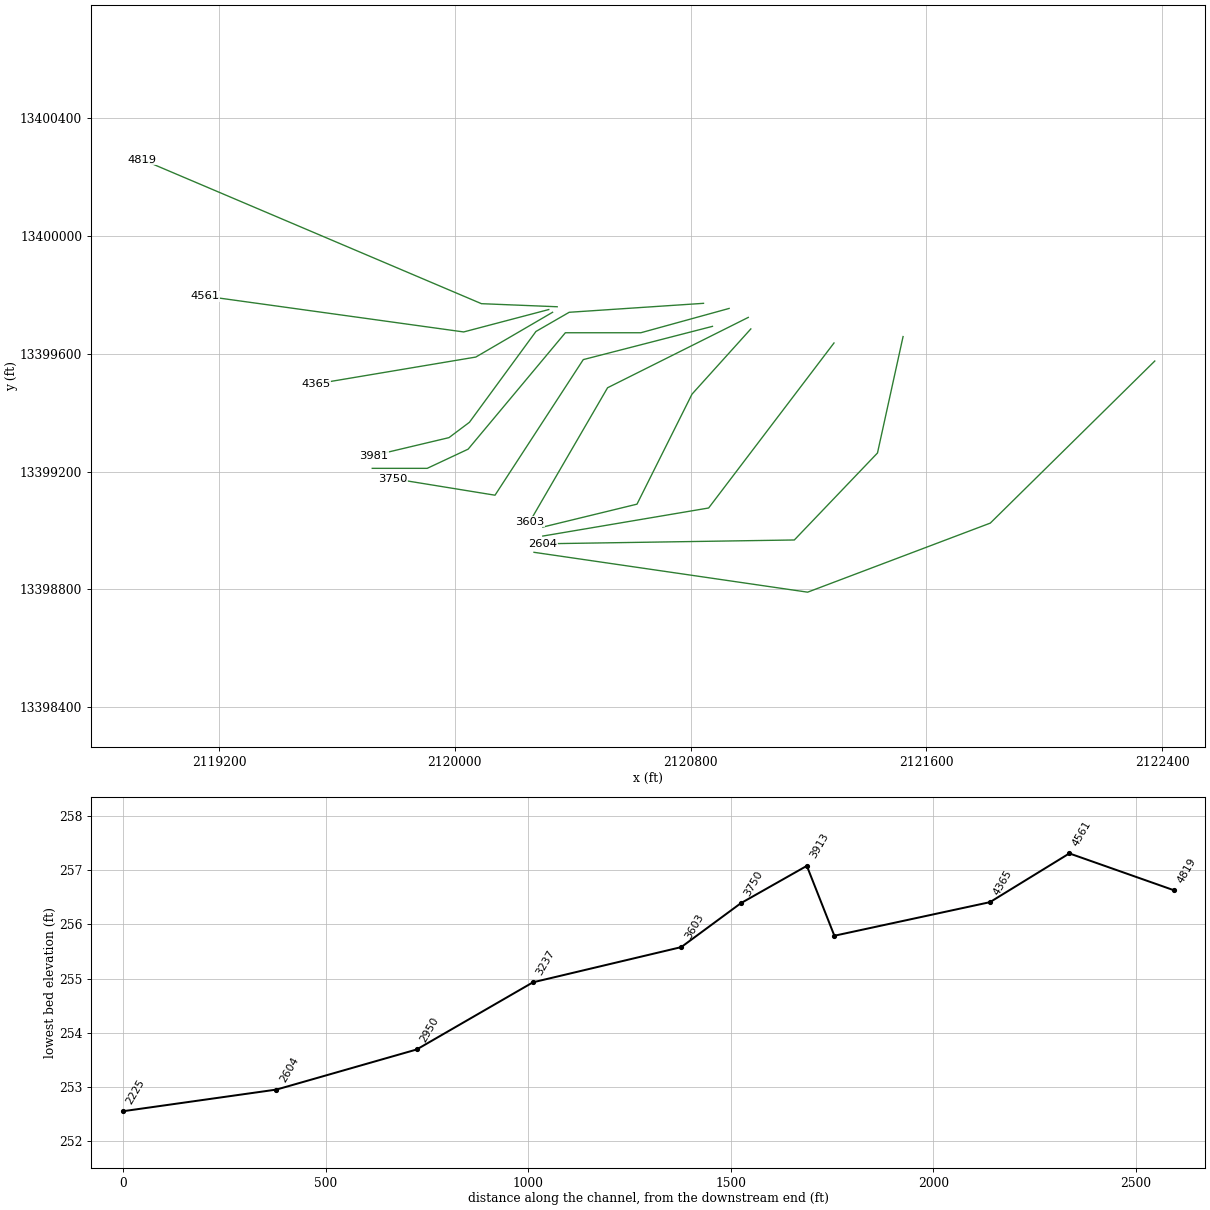
HEC-RAS study UNT 006 in La Jarita Watershed.prj: UNT 006 in La Jarita Watershed Base Level Engineering

--- UNT 006 in La Jarita Watershed.g01 (geometry) --- (continued)

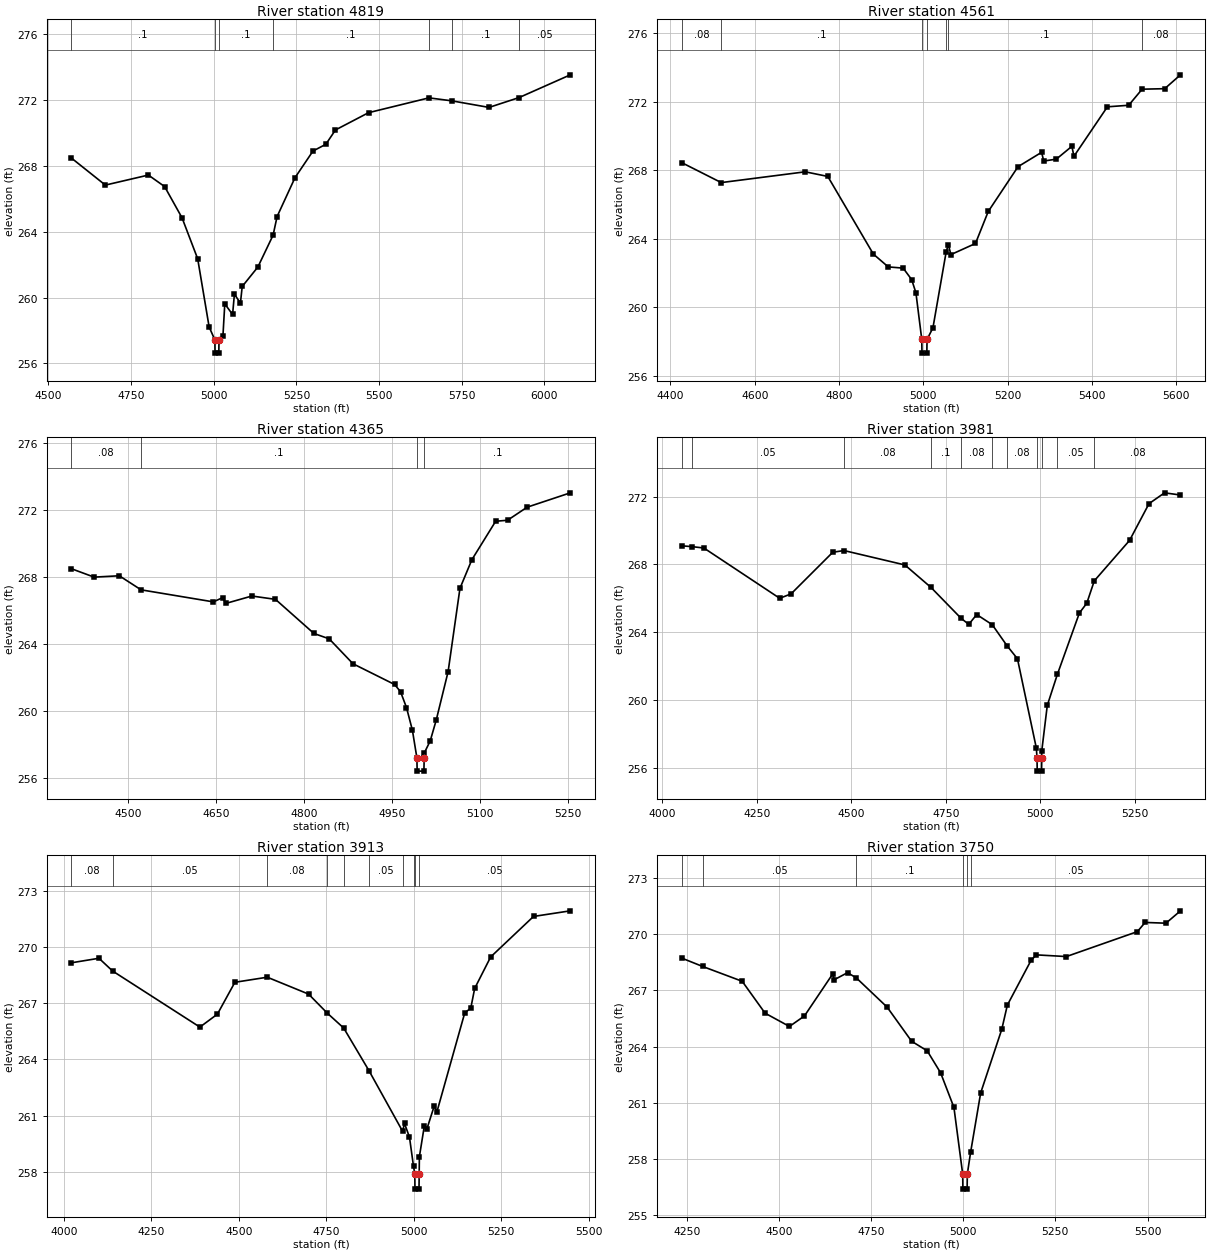
Type RM Length L Ch R = 1,4819,258,258,258
BEGIN DESCRIPTION:
Mapping XS 7810679d
END DESCRIPTION:
XS GIS Cut Line= 3
      2120347.32     13399759.15      2120090.35     13399769.57
      2118938.78     13400258.63
#Sta/Elev= 30
  4570.0  268.48  4672.4  266.84  4802.5  267.45  4851.6  266.75  4904.3  264.85
  4951.6  262.36  4986.2  258.22  5003.6  257.43  5004.1  256.63  5015.5  256.63
  5016.0  257.43  5028.0  257.70  5033.5  259.62  5057.1  258.98  5062.6  260.21
  5080.8  259.67  5086.2  260.68  5133.5  261.86  5179.6  263.80  5191.7  264.93
  5245.8  267.29  5300.2  268.91  5339.1  269.32  5368.1  270.19  5468.2  271.24
  5650.9  272.14  5719.7  271.96  5832.5  271.56  5923.6  272.16  6078.3  273.54
#Mann=7,-1,0
  4570.0     0.1       0  5003.6    0.07       0  5016.0     0.1       0
  5179.6     0.1       0  5650.9    0.08       0  5719.7     0.1       0
  5923.6    0.05       0
Bank Sta=5003.6,5016
Exp/Cntr=0.3,0.1

Type RM Length L Ch R = 1,4561,196,196,196
BEGIN DESCRIPTION:
Mapping XS afb2f107
END DESCRIPTION:
XS GIS Cut Line= 3
      2120318.63     13399749.59      2120030.02     13399673.65
      2119153.24     13399795.18
#Sta/Elev= 30
  4426.6  268.45  4520.6  267.28  4719.9  267.91  4773.4  267.64  4881.5  263.10
  4916.9  262.35  4952.2  262.28  4972.4  261.61  4982.5  260.84  4996.4  258.11
  4996.9  257.31  5008.4  257.31  5008.9  258.11  5022.9  258.79  5054.2  263.22
  5059.4  263.66  5065.5  263.07  5123.8  263.72  5154.1  265.59  5224.8  268.21
  5280.7  269.05  5285.8  268.54  5315.6  268.65  5352.5  269.40  5357.5  268.82
  5436.8  271.71  5487.3  271.80  5519.2  272.74  5572.8  272.77  5610.2  273.58
#Mann=7,-1,0
  4426.6    0.08       0  4520.6     0.1       0  4996.4    0.07       0
  5008.9     0.1       0  5054.2    0.05       0  5059.4     0.1       0
  5519.2    0.08       0
Bank Sta=4996.4,5008.9
Exp/Cntr=0.3,0.1

Type RM Length L Ch R = 1,4365,384,384,384
BEGIN DESCRIPTION:
Mapping XS 7b405392
END DESCRIPTION:
XS GIS Cut Line= 3
      2120331.67     13399740.38      2120071.25     13399588.47
      2119529.33     13399497.43
#Sta/Elev= 30
  4402.9  268.51  4441.5  268.01  4484.5  268.09  4521.6  267.25  4644.9  266.53
  4660.6  266.78  4666.4  266.44  4710.7  266.88  4750.9  266.68  4816.5  264.64
  4842.5  264.32  4883.1  262.83  4954.1  261.59  4964.2  261.16  4974.4  260.21
  4984.5  258.85  4992.1  257.21  4992.6  256.41  5004.1  256.41  5004.6  257.21
  5004.8  257.50  5014.9  258.22  5025.1  259.46  5045.4  262.36  5065.6  267.34
  5085.9  269.05  5126.5  271.35  5146.8  271.41  5180.1  272.19  5253.9  273.05
#Mann=4,-1,0
  4402.9    0.08       0  4521.6     0.1       0  4992.1    0.07       0
  5004.6     0.1       0
Bank Sta=4992.1,5004.6
Exp/Cntr=0.3,0.1

Type RM Length L Ch R = 1,3981,68,68,68
BEGIN DESCRIPTION:
Mapping XS 84994904
END DESCRIPTION:
XS GIS Cut Line= 6
      2120843.78     13399770.76      2120388.09     13399740.38
      2120275.25     13399675.27      2120049.55     13399367.11
      2119980.11     13399315.03      2119724.02     13399254.26
#Sta/Elev= 30
  4051.6  269.10  4079.5  269.05  4110.5  268.97  4311.0  266.00  4341.0  266.26
  4451.3  268.72  4481.0  268.82  4641.9  267.97  4711.1  266.64  4790.5  264.82
  4810.9  264.46  4831.9  265.04  4873.0  264.44  4912.3  263.19  4939.6  262.43
  4989.5  257.16  4991.4  256.59  4991.9  255.79  5003.4  255.79  5003.9  256.59
  5004.0  257.00  5018.5  259.67  5045.1  261.50  5103.4  265.13  5123.0  265.71
  5142.8  267.03  5236.1  269.42  5287.5  271.59  5328.6  272.23  5370.7  272.10
#Mann=11,-1,0
  4051.6    0.08       0  4079.5    0.05       0  4481.0    0.08       0
  4711.1     0.1       0  4790.5    0.08       0  4873.0     0.1       0
  4912.3    0.08       0  4991.4    0.07       0  5003.9    0.08       0
  5045.1    0.05       0  5142.8    0.08       0
Bank Sta=4991.4,5003.9
Exp/Cntr=0.3,0.1

Type RM Length L Ch R = 1,3913,163,163,163
BEGIN DESCRIPTION:
Mapping XS c6178624
END DESCRIPTION:
XS GIS Cut Line= 6
      2120930.67     13399753.41      2120631.15     13399670.93
      2120375.07     13399670.93      2120045.21     13399275.97
      2119906.32     13399210.86      2119719.83     13399210.86
#Sta/Elev= 30
  4022.1  269.15  4100.6  269.39  4139.6  268.71  4388.9  265.72  4438.9  266.41
  4488.9  268.11  4581.4  268.38  4699.3  267.48  4752.5  266.47  4799.7  265.67
  4871.8  263.40  4967.8  260.17  4973.4  260.58  4987.6  259.85  4999.1  258.30
  5002.8  257.88  5003.3  257.08  5014.8  257.08  5015.3  257.88  5015.9  258.81
  5030.1  260.46  5037.4  260.29  5058.4  261.52  5065.8  261.19  5145.5  266.48
  5162.7  266.73  5173.8  267.78  5219.5  269.46  5341.9  271.62  5447.1  271.92
#Mann=10,-1,0
  4022.1    0.08       0  4139.6    0.05       0  4581.4    0.08       0
  4752.5    0.05       0  4799.7    0.08       0  4871.8    0.05       0
  4967.8    0.08       0  4999.1    0.05       0  5002.8   0.035       0
  5015.3    0.05       0
Bank Sta=5002.8,5015.3
Exp/Cntr=0.3,0.1

Type RM Length L Ch R = 1,3750,147,147,147
BEGIN DESCRIPTION:
Mapping XS 4d878ac5
END DESCRIPTION:
XS GIS Cut Line= 4
      2120874.16     13399692.62      2120435.84     13399579.79
      2120136.36     13399119.72      2119789.58     13399176.07
#Sta/Elev= 30
  4236.4  268.72  4293.6  268.27  4400.7  267.48  4462.7  265.78  4528.8  265.07
  4569.5  265.63  4645.7  267.86  4650.9  267.57  4686.4  267.94  4710.3  267.66
  4793.8  266.10  4860.2  264.28  4902.4  263.77  4938.7  262.60  4974.9  260.75
  4998.7  257.19  4999.2  256.39  5010.7  256.39  5011.2  257.19  5020.1  258.35
  5047.4  261.52  5104.7  264.92  5119.8  266.21  5183.9  268.59  5198.2  268.89
  5279.9  268.80  5472.4  270.13  5493.4  270.62  5549.9  270.58  5589.3  271.24
#Mann=6,-1,0
  4236.4    0.08       0  4293.6    0.05       0  4710.3     0.1       0
  4998.7    0.07       0  5011.2     0.1       0  5020.1    0.05       0
Bank Sta=4998.7,5011.2
Exp/Cntr=0.3,0.1

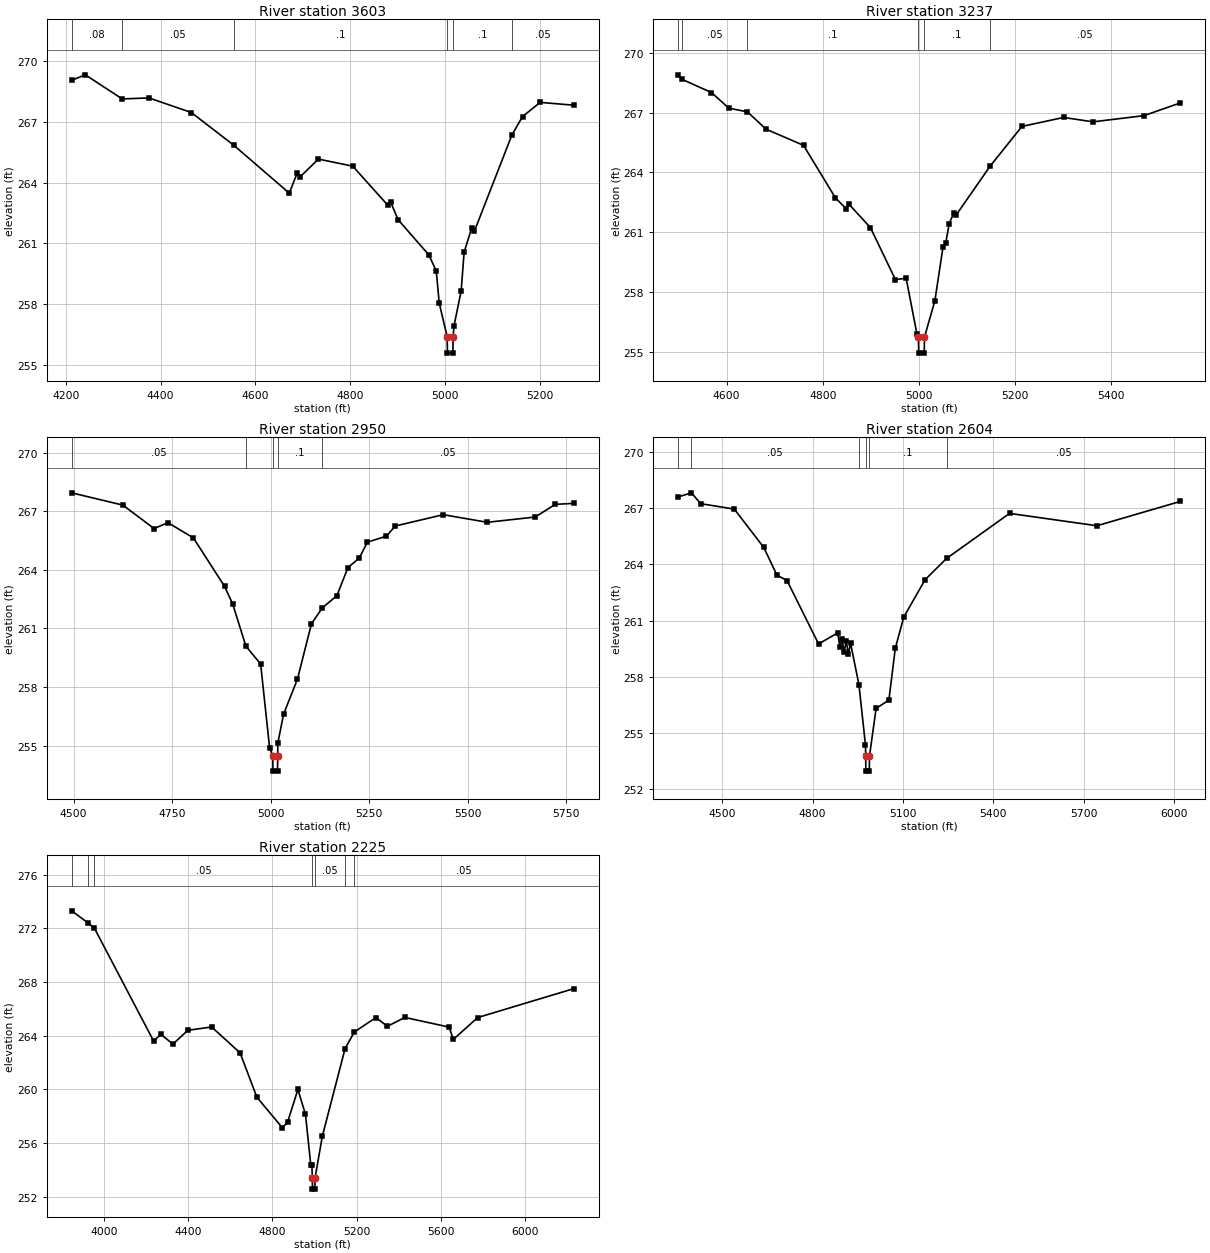
Type RM Length L Ch R = 1,3603,366,366,366
BEGIN DESCRIPTION:
Mapping XS 5cd83c16
END DESCRIPTION:
XS GIS Cut Line= 3
      2120995.70     13399723.00      2120518.30     13399484.30
      2120253.95     13399029.26
#Sta/Elev= 30
  4212.1  269.05  4241.0  269.32  4318.9  268.13  4375.2  268.18  4464.6  267.46
  4554.0  265.85  4671.4  263.48  4688.2  264.47  4693.8  264.27  4732.9  265.16
  4805.4  264.81  4879.9  262.87  4885.7  263.02  4901.4  262.16  4966.0  260.43
  4981.7  259.64  4987.9  258.06  5004.8  256.38  5005.3  255.58  5016.8  255.58
  5017.3  256.38  5019.0  256.91  5034.2  258.64  5040.5  260.56  5056.2  261.74
  5062.0  261.59  5141.4  266.35  5163.8  267.26  5201.1  267.96  5272.1  267.82
#Mann=6,-1,0
  4212.1    0.08       0  4318.9    0.05       0  4554.0     0.1       0
  5004.8    0.07       0  5017.3     0.1       0  5141.4    0.05       0
Bank Sta=5004.8,5017.3
Exp/Cntr=0.3,0.1

Type RM Length L Ch R = 1,3237,287,287,287
BEGIN DESCRIPTION:
Mapping XS 14f346f6
END DESCRIPTION:
XS GIS Cut Line= 4
      2121004.38     13399683.92      2120804.76     13399462.60
      2120618.13     13399089.34      2120298.52     13399011.59
#Sta/Elev= 30
  4499.2  268.90  4506.8  268.68  4568.6  268.01  4604.5  267.23  4643.4  267.04
  4682.2  266.17  4760.0  265.36  4826.4  262.72  4848.7  262.18  4854.3  262.41
  4899.1  261.23  4951.1  258.62  4973.4  258.69  4995.8  255.89  4999.0  255.73
  4999.5  254.93  5011.0  254.93  5011.5  255.73  5033.2  257.57  5050.0  260.25
  5055.6  260.44  5062.9  261.43  5072.3  261.96  5077.9  261.88  5147.8  264.31
  5214.2  266.31  5300.8  266.76  5361.9  266.54  5467.8  266.85  5543.5  267.49
#Mann=6,-1,0
  4499.2    0.08       0  4506.8    0.05       0  4643.4     0.1       0
  4999.0    0.07       0  5011.5     0.1       0  5147.8    0.05       0
Bank Sta=4999,5011.5
Exp/Cntr=0.3,0.1

Type RM Length L Ch R = 1,2950,346,346,346
BEGIN DESCRIPTION:
Mapping XS 20e3f410
END DESCRIPTION:
XS GIS Cut Line= 3
      2121286.56     13399636.25      2120861.18     13399076.31
      2120298.47     13398981.09
#Sta/Elev= 30
  4495.1  267.95  4625.1  267.32  4704.1  266.12  4739.5  266.42  4803.9  265.64
  4882.9  263.16  4903.7  262.25  4937.2  260.09  4974.5  259.18  4997.3  254.87
  5005.3  254.49  5005.8  253.69  5017.3  253.69  5017.8  254.49  5018.1  255.12
  5032.7  256.61  5068.0  258.41  5103.4  261.24  5131.2  262.06  5167.9  262.68
  5196.0  264.12  5224.8  264.61  5245.1  265.42  5293.4  265.73  5316.1  266.25
  5437.8  266.83  5549.4  266.44  5671.1  266.71  5721.8  267.36  5769.0  267.41
#Mann=5,-1,0
  4495.1    0.05       0  4937.2     0.1       0  5005.3    0.07       0
  5017.8     0.1       0  5131.2    0.05       0
Bank Sta=5005.3,5017.8
Exp/Cntr=0.3,0.1

Type RM Length L Ch R = 1,2604,379,379,379
BEGIN DESCRIPTION:
Mapping XS 63a30200
END DESCRIPTION:
XS GIS Cut Line= 4
      2121520.91     13399657.93      2121434.10     13399262.95
      2121151.98     13398967.81      2120298.48     13398954.81
#Sta/Elev= 30
  4353.9  267.61  4398.2  267.83  4428.6  267.25  4540.3  266.96  4638.1  264.91
  4681.8  263.43  4715.3  263.14  4819.9  259.75  4883.5  260.34  4890.7  259.59
  4897.6  260.01  4904.8  259.32  4911.8  259.90  4919.0  259.20  4925.9  259.80
  4953.9  257.57  4975.6  254.34  4976.3  253.75  4976.8  252.95  4988.3  252.95
  4988.8  253.75  5010.8  256.30  5053.3  256.75  5074.4  259.51  5102.7  261.19
  5173.6  263.19  5245.3  264.33  5453.6  266.73  5743.6  266.07  6020.2  267.37
#Mann=6,-1,0
  4353.9    0.08       0  4398.2    0.05       0  4953.9     0.1       0
  4976.3    0.07       0  4988.8     0.1       0  5245.3    0.05       0
Bank Sta=4976.3,4988.8
Exp/Cntr=0.3,0.1

Type RM Length L Ch R = 1,2225,0,0,0
BEGIN DESCRIPTION:
UNT 006 in La Jarita Watershed 1.0
END DESCRIPTION:
XS GIS Cut Line= 4
      2122374.98     13399574.98      2121816.91     13399025.10
      2121197.12     13398790.72      2120268.71     13398925.96
#Sta/Elev= 30
  3846.5  273.30  3922.6  272.42  3954.4  272.01  4235.4  263.60  4270.7  264.09
  4327.3  263.36  4398.0  264.39  4511.2  264.64  4646.2  262.71  4726.0  259.40
  4846.7  257.13  4871.6  257.54  4920.7  259.98  4956.7  258.12  4981.6  254.38
  4986.9  254.37  4989.3  253.35  4989.8  252.55  5001.3  252.55  5001.8  253.35
  5036.6  256.49  5144.6  263.02  5188.8  264.27  5291.1  265.34  5345.3  264.69
  5428.7  265.35  5638.9  264.63  5658.5  263.71  5774.0  265.34  6230.8  267.50
#Mann=7,-1,0
  3846.5    0.05       0  3922.6    0.08       0  3954.4    0.05       0
  4989.3   0.035       0  5001.8    0.05       0  5144.6     0.1       0
  5188.8    0.05       0
Bank Sta=4989.3,5001.8
Exp/Cntr=0.3,0.1

Chan Stop Cuts=-1