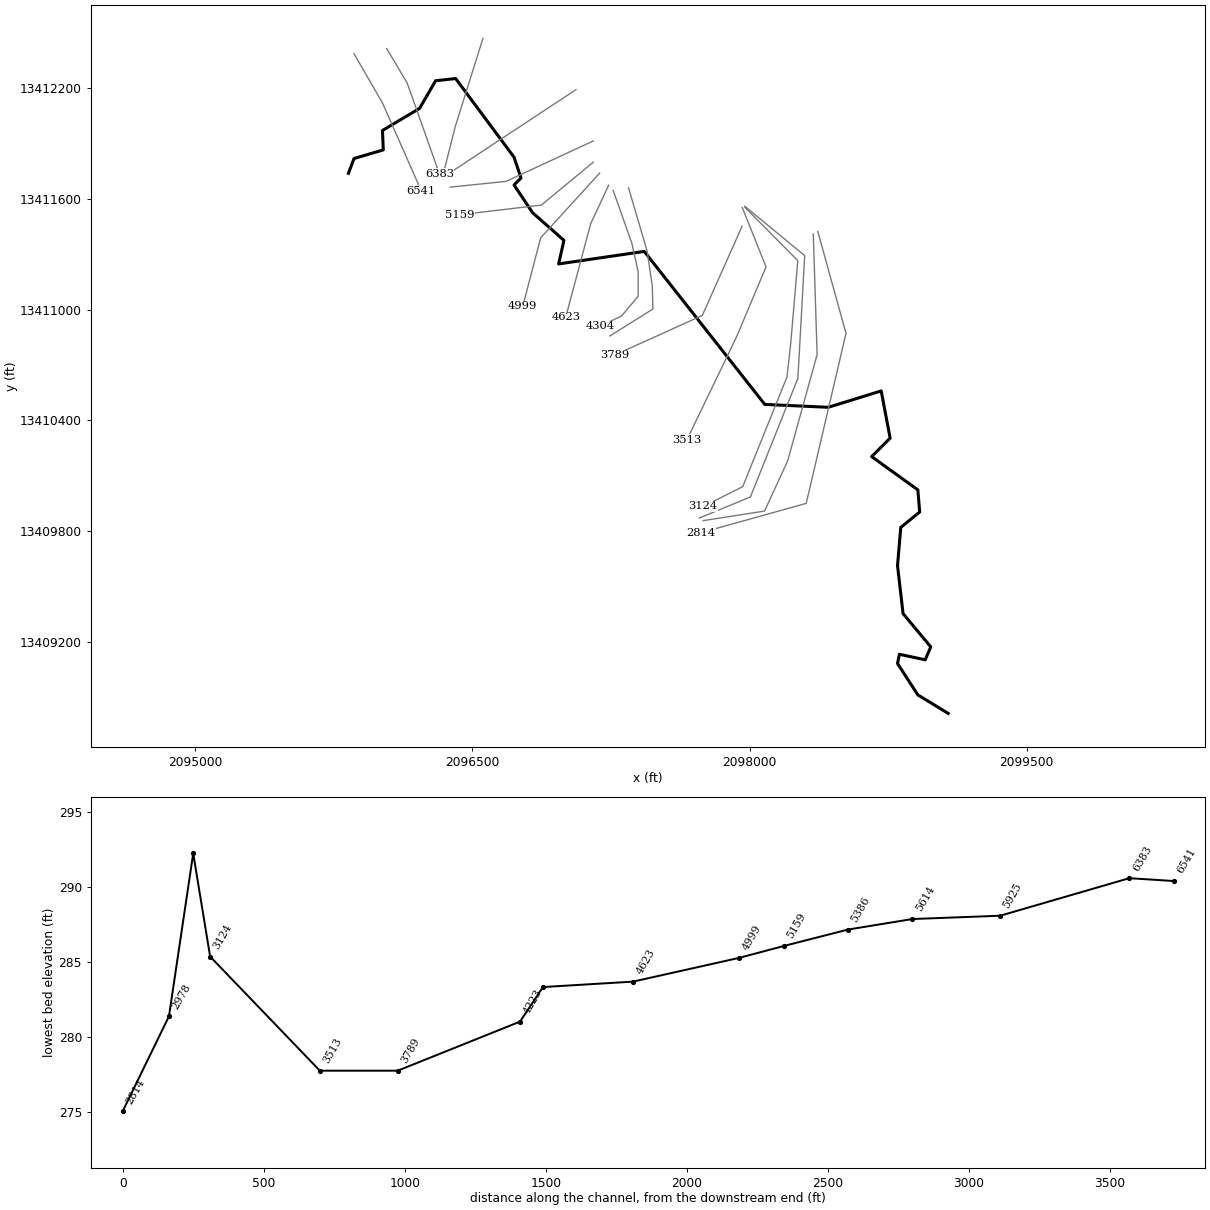
--- UNT 007 in La Jarita Watershed.prj (project) ---

Proj Title=UNT 007 in La Jarita Watershed Base Level Engineering
Current Plan=p01
Default Exp/Contr=0.3,0.1
English Units
Geom File=g01
Flow File=f01
Plan File=p01
BEGIN DESCRIPTION:
UNT 007 in La Jarita Watershed
END DESCRIPTION:

--- UNT 007 in La Jarita Watershed.p01 (plan) ---

Plan Title=Multiple Run
Short Identifier=Multiple
Geom File=g01
Flow File=f01
Subcritical Flow
K Sum by GR= 0
Std Step Tol= 0.01
Critical Tol= 0.01
Num of Std Step Trials= 20
Max Error Tol= 0.3
Flow Tol Ratio= 0.001
Split Flow NTrial= 30
Split Flow Tol= 0.02
Split Flow Ratio= 0.02
Log Output Level= 0
Friction Slope Method= 1
Unsteady Friction Slope Method= 2
Unsteady Bridges Friction Slope Method= 1
Parabolic Critical Depth
Global Vel Dist=  1 , 1 , 1
Global Log Level= 0
CheckData=True
Encroach Param= -1, 0, 0, 0
BEGIN DESCRIPTION:
Multiple Run
END DESCRIPTION:

--- UNT 007 in La Jarita Watershed.f01 (steady flow) ---

Flow Title=Multiple
Number of Profiles=7
Profile Names=10-year,25-year,50-year,1pct_min,100-year,1pct_plu,500-year
River Rch & RM= UNT 007 in La Ja,Reach-1,6541
     184     253     310     190     378     755     572
River Rch & RM= UNT 007 in La Ja,Reach-1,5614
     268     375     464     287     572    1141     881
Boundary for River Rch & Prof#=UNT 007 in La Ja,Reach-1,1
Up Type=0
Dn Type=3
Dn Slope=0.005
Boundary for River Rch & Prof#=UNT 007 in La Ja,Reach-1,2
Up Type=0
Dn Type=3
Dn Slope=0.005
Boundary for River Rch & Prof#=UNT 007 in La Ja,Reach-1,3
Up Type=0
Dn Type=3
Dn Slope=0.005
Boundary for River Rch & Prof#=UNT 007 in La Ja,Reach-1,4
Up Type=0
Dn Type=3
Dn Slope=0.005
Boundary for River Rch & Prof#=UNT 007 in La Ja,Reach-1,5
Up Type=0
Dn Type=3
Dn Slope=0.005
Boundary for River Rch & Prof#=UNT 007 in La Ja,Reach-1,6
Up Type=0
Dn Type=3
Dn Slope=0.005
Boundary for River Rch & Prof#=UNT 007 in La Ja,Reach-1,7
Up Type=0
Dn Type=3
Dn Slope=0.005

--- UNT 007 in La Jarita Watershed.g01 (geometry) ---

Geom Title=Existing Conditions

River Reach=UNT 007 in La Ja,Reach-1
Reach XY= 30
      2095828.31     13411737.84      2095858.69     13411818.13
      2096017.11     13411864.79      2096012.77     13411970.04
      2096213.51     13412089.40      2096300.31     13412239.14
      2096408.82     13412251.08      2096725.00     13411825.00
      2096762.51     13411712.51      2096725.00     13411675.00
      2096825.00     13411525.00      2096995.01     13411375.13
      2096966.36     13411247.52      2097429.90     13411315.23
      2098082.25     13410487.10      2098426.00     13410471.48
      2098712.45     13410560.02      2098760.80     13410304.54
      2098660.80     13410204.54      2098910.80     13410024.54
      2098920.80     13409904.54      2098818.36     13409821.09
      2098800.80     13409614.54      2098830.80     13409354.54
      2098980.80     13409174.54      2098950.80     13409104.54
      2098810.80     13409134.54      2098800.80     13409084.54
      2098910.80     13408914.54      2099075.00     13408814.54

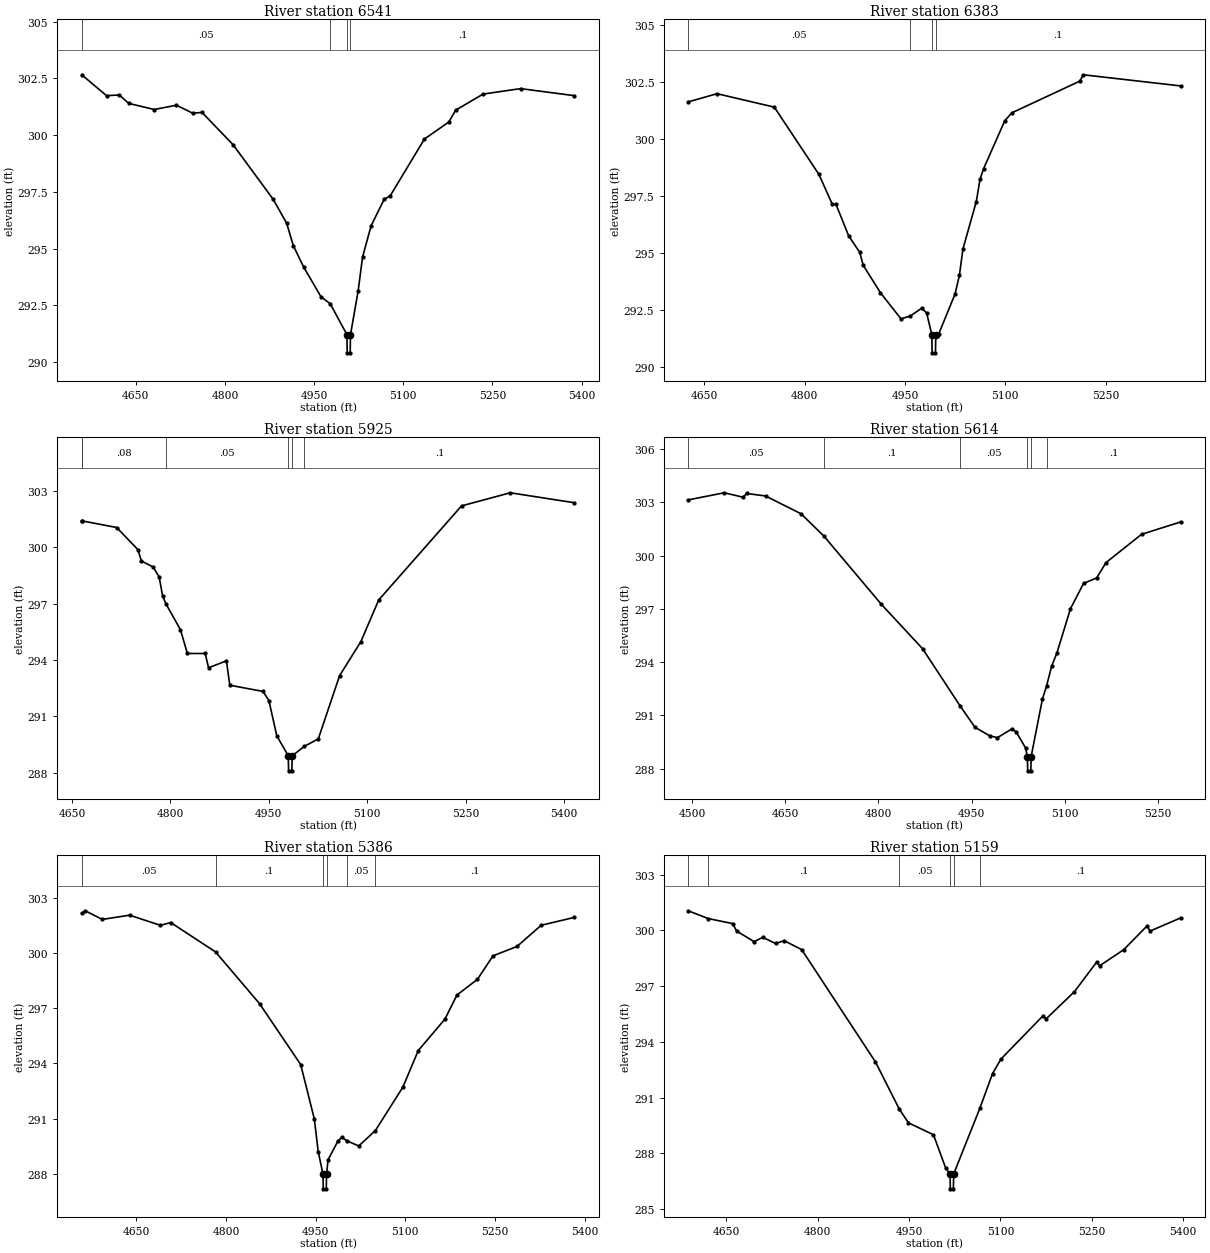
Type RM Length L Ch R = 1,6541,158,158,158
BEGIN DESCRIPTION:
UNT 007 in La Jarita Watershed 1.0
END DESCRIPTION:
XS GIS Cut Line= 3
      2095858.71     13412385.37      2096011.47     13412121.52
      2096223.28     13411642.33
#Sta/Elev= 30
  4559.1  302.66  4600.8  301.74  4622.3  301.77  4638.1  301.40  4681.1  301.13
  4718.4  301.32  4745.7  300.97  4761.5  301.00  4813.7  299.58  4880.8  297.19
  4903.9  296.12  4915.1  295.13  4932.9  294.17  4961.7  292.88  4977.3  292.57
  5005.3  291.21  5005.8  290.41  5010.8  290.41  5011.3  291.21  5024.2  293.14
  5031.6  294.63  5046.0  296.01  5067.9  297.17  5078.2  297.33  5135.7  299.83
  5176.8  300.58  5188.2  301.10  5234.4  301.81  5297.5  302.05  5387.9  301.74
#Mann=4,-1,0
  4559.1    0.05       0  4977.3     0.1       0  5005.3    0.07       0
  5011.3     0.1       0
Bank Sta=5005.3,5011.3
Exp/Cntr=0.3,0.1

Type RM Length L Ch R = 1,6383,458,458,458
BEGIN DESCRIPTION:
UNT 007 in La Jarita Watershed 2.0
END DESCRIPTION:
XS GIS Cut Line= 3
      2096035.75     13412413.22      2096146.89     13412225.69
      2096320.25     13411736.80
#Sta/Elev= 30
  4625.7  301.61  4668.8  301.97  4754.5  301.38  4821.2  298.43  4841.2  297.12
  4846.7  297.12  4865.6  295.74  4882.2  295.01  4887.5  294.44  4913.1  293.24
  4944.0  292.09  4958.1  292.22  4974.9  292.56  4982.3  292.35  4990.0  291.40
  4990.5  290.60  4995.5  290.60  4996.0  291.40  5000.4  291.43  5024.8  293.18
  5031.3  294.00  5036.6  295.16  5056.6  297.24  5062.2  298.22  5067.5  298.68
  5099.1  300.78  5109.7  301.13  5211.3  302.52  5216.6  302.80  5362.4  302.31
#Mann=4,-1,0
  4625.7    0.05       0  4958.1     0.1       0  4990.0    0.07       0
  4996.0     0.1       0
Bank Sta=4990,4996
Exp/Cntr=0.3,0.1

Type RM Length L Ch R = 1,5925,311,311,311
BEGIN DESCRIPTION:
UNT 007 in La Jarita Watershed 3.0
END DESCRIPTION:
XS GIS Cut Line= 3
      2096556.61     13412468.73      2096407.30     13411993.05
      2096345.24     13411748.26
#Sta/Elev= 30
  4664.8  301.41  4665.7  301.41  4718.1  301.06  4750.5  299.88  4755.7  299.28
  4773.5  298.96  4782.9  298.43  4788.1  297.41  4793.7  296.96  4815.3  295.62
  4825.9  294.35  4853.0  294.35  4858.2  293.59  4885.4  293.96  4890.6  292.66
  4941.2  292.33  4950.2  291.84  4962.2  289.97  4979.7  288.90  4980.2  288.10
  4985.2  288.10  4985.7  288.90  5004.4  289.41  5025.5  289.80  5058.0  293.17
  5090.4  294.98  5117.6  297.20  5243.9  302.21  5318.2  302.91  5415.9  302.38
#Mann=6,-1,0
  4664.8    0.05       0  4665.7    0.08       0  4793.7    0.05       0
  4979.7    0.03       0  4985.7    0.05       0  5004.4     0.1       0
Bank Sta=4979.7,4985.7
Exp/Cntr=0.3,0.1

Type RM Length L Ch R = 1,5614,228,228,228
BEGIN DESCRIPTION:
UNT 007 in La Jarita Watershed 4.0
END DESCRIPTION:
XS GIS Cut Line= 2
      2097060.06     13412190.95      2096398.45     13411754.50
#Sta/Elev= 30
  4494.0  303.14  4552.1  303.54  4582.2  303.29  4588.2  303.50  4618.4  303.36
  4675.5  302.36  4712.1  301.11  4805.0  297.25  4871.3  294.75  4931.6  291.53
  4955.5  290.33  4979.3  289.85  4991.6  289.75  5015.2  290.25  5021.8  290.07
  5036.8  289.17  5039.8  288.68  5040.3  287.88  5045.3  287.88  5045.8  288.68
  5063.9  291.91  5070.7  292.67  5079.0  293.80  5087.1  294.50  5109.1  297.01
  5130.2  298.44  5151.2  298.74  5166.3  299.61  5223.5  301.20  5286.6  301.90
#Mann=6,-1,0
  4494.0    0.05       0  4712.1     0.1       0  4931.6    0.05       0
  5039.8    0.03       0  5045.8    0.05       0  5070.7     0.1       0
Bank Sta=5039.8,5045.8
Exp/Cntr=0.3,0.1

Type RM Length L Ch R = 1,5386,227,227,227
BEGIN DESCRIPTION:
UNT 007 in La Jarita Watershed 5.0
END DESCRIPTION:
XS GIS Cut Line= 3
      2097153.82     13411913.18      2096681.61     13411694.44
      2096379.74     13411663.21
#Sta/Elev= 30
  4558.7  302.16  4564.6  302.30  4593.0  301.83  4638.9  302.06  4690.2  301.51
  4707.6  301.66  4782.6  300.06  4856.1  297.25  4924.9  293.94  4947.8  290.97
  4954.2  289.21  4962.2  287.98  4962.7  287.18  4967.7  287.18  4968.2  287.98
  4970.7  288.76  4987.2  289.78  4993.6  289.98  5001.8  289.80  5022.0  289.51
  5049.9  290.35  5095.8  292.71  5121.6  294.70  5166.2  296.41  5186.3  297.72
  5220.5  298.57  5246.6  299.85  5286.8  300.36  5327.0  301.51  5382.6  301.94
#Mann=6,-1,0
  4558.7    0.05       0  4782.6     0.1       0  4962.2    0.07       0
  4968.2     0.1       0  5001.8    0.05       0  5049.9     0.1       0
Bank Sta=4962.2,4968.2
Exp/Cntr=0.3,0.1

Type RM Length L Ch R = 1,5159,160,160,160
BEGIN DESCRIPTION:
UNT 007 in La Jarita Watershed 6.0
END DESCRIPTION:
XS GIS Cut Line= 3
      2097153.82     13411798.60      2096872.58     13411565.96
      2096431.63     13411513.88
#Sta/Elev= 30
  4587.1  301.05  4620.2  300.63  4660.1  300.36  4666.6  299.96  4695.3  299.39
  4709.6  299.62  4730.5  299.29  4744.8  299.44  4773.5  298.96  4894.6  292.92
  4933.8  290.38  4948.9  289.64  4989.9  289.00  5010.1  287.20  5017.1  286.89
  5017.6  286.09  5022.6  286.09  5023.1  286.89  5066.3  290.44  5086.9  292.29
  5100.7  293.07  5169.8  295.40  5174.8  295.23  5221.5  296.70  5257.7  298.28
  5262.8  298.09  5302.1  298.95  5340.6  300.23  5345.7  299.96  5396.1  300.67
#Mann=6,-1,0
  4587.1    0.05       0  4620.2     0.1       0  4933.8    0.05       0
  5017.1    0.03       0  5023.1    0.05       0  5066.3     0.1       0
Bank Sta=5017.1,5023.1
Exp/Cntr=0.3,0.1

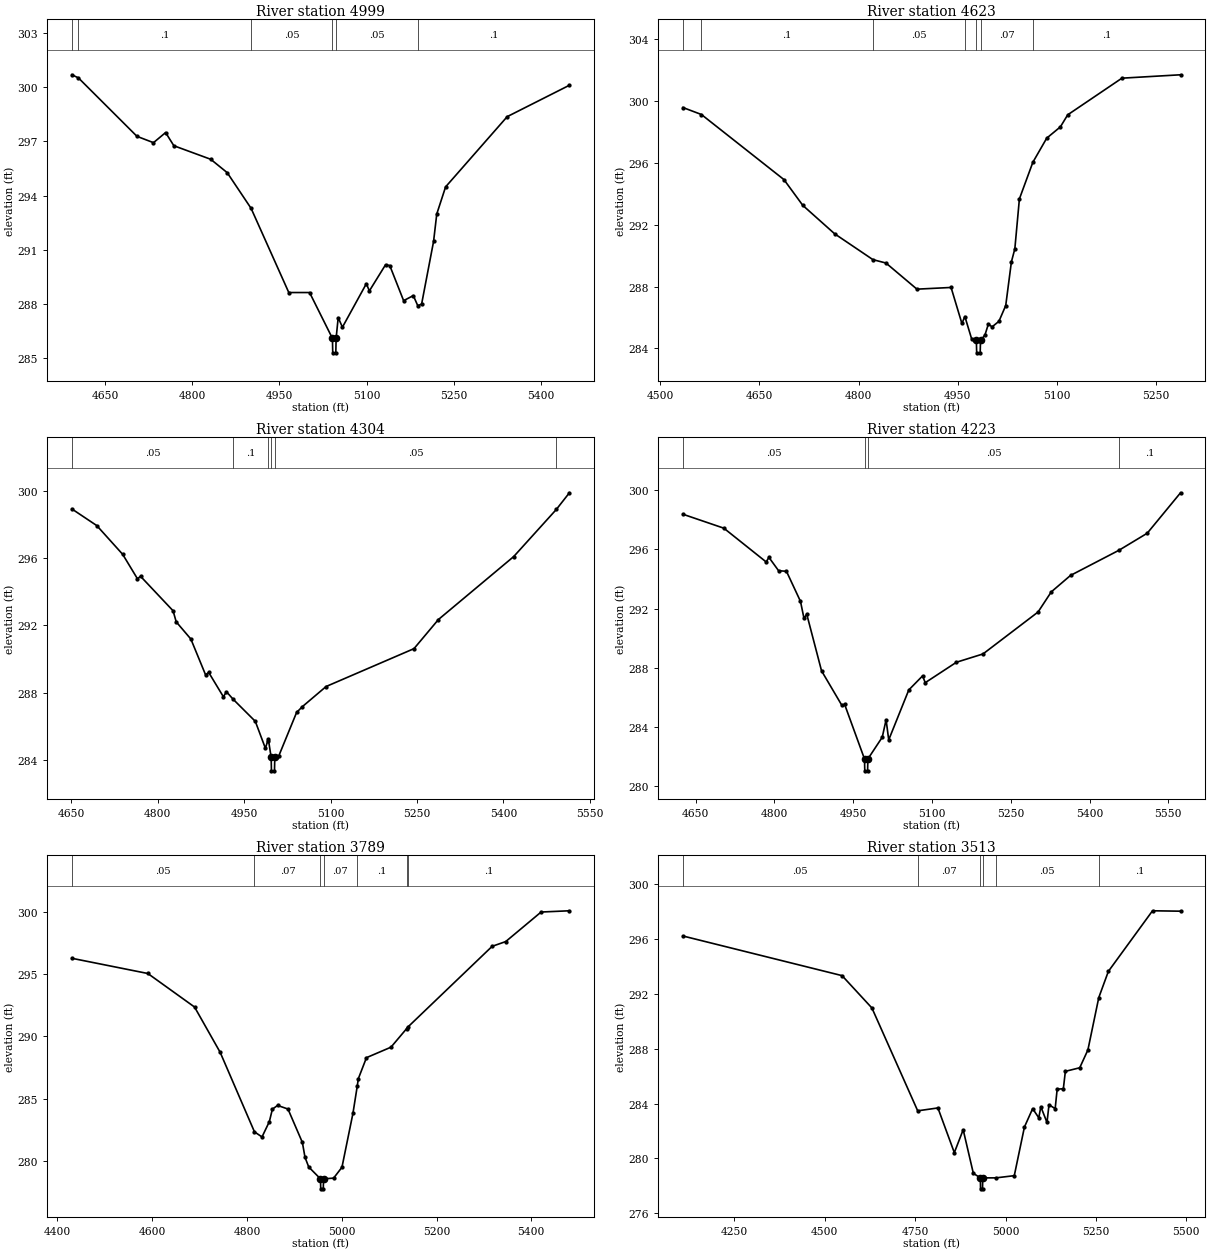
Type RM Length L Ch R = 1,4999,376,376,376
BEGIN DESCRIPTION:
UNT 007 in La Jarita Watershed 7.0
END DESCRIPTION:
XS GIS Cut Line= 3
      2097188.58     13411739.60      2096869.11     13411388.88
      2096772.23     13411018.66
#Sta/Elev= 30
  4592.4  300.69  4603.6  300.52  4704.6  297.28  4733.0  296.93  4753.9  297.49
  4768.1  296.76  4831.6  296.01  4860.0  295.27  4901.2  293.29  4966.1  288.63
  5001.9  288.63  5041.3  286.09  5041.8  285.29  5047.1  285.29  5047.6  286.09
  5051.2  287.24  5058.5  286.71  5099.7  289.12  5104.9  288.72  5132.8  290.17
  5140.1  290.12  5163.9  288.18  5180.6  288.46  5188.3  287.90  5194.9  287.99
  5215.5  291.46  5221.0  292.98  5236.2  294.48  5342.3  298.37  5449.5  300.11
#Mann=6,-1,0
  4592.4    0.05       0  4603.6     0.1       0  4901.2    0.05       0
  5041.3    0.03       0  5047.6    0.05       0  5188.3     0.1       0
Bank Sta=5041.3,5047.6
Exp/Cntr=0.3,0.1

Type RM Length L Ch R = 1,4623,319,319,319
BEGIN DESCRIPTION:
UNT 007 in La Jarita Watershed 8.0
END DESCRIPTION:
XS GIS Cut Line= 3
      2097237.15     13411673.58      2097139.94     13411465.27
      2097004.76     13410959.19
#Sta/Elev= 30
  4534.1  299.58  4562.0  299.13  4687.0  294.92  4715.6  293.25  4763.9  291.41
  4821.8  289.74  4841.6  289.52  4888.5  287.83  4940.2  287.94  4956.6  285.61
  4961.1  286.06  4971.3  284.62  4978.5  284.51  4979.0  283.71  4984.3  283.71
  4984.8  284.51  4991.5  284.86  4996.7  285.57  5002.3  285.39  5012.7  285.75
  5023.0  286.77  5031.6  289.60  5036.8  290.44  5043.7  293.67  5064.1  296.04
  5085.1  297.60  5105.8  298.33  5116.9  299.11  5199.0  301.48  5287.8  301.70
#Mann=7,-1,0
  4534.1    0.05       0  4562.0     0.1       0  4821.8    0.05       0
  4961.1    0.07       0  4978.5    0.07       0  4984.8    0.07       0
  5064.1     0.1       0
Bank Sta=4978.5,4984.8
Exp/Cntr=0.3,0.1

Type RM Length L Ch R = 1,4304,81,81,81
BEGIN DESCRIPTION:
UNT 007 in La Jarita Watershed 9.0
END DESCRIPTION:
XS GIS Cut Line= 6
      2097261.48     13411645.79      2097362.16     13411361.10
      2097396.89     13411204.85      2097396.89     13411072.91
      2097306.61     13410965.27      2097189.58     13410910.20
#Sta/Elev= 30
  4650.7  298.91  4694.0  297.92  4739.0  296.21  4764.6  294.76  4769.9  294.91
  4826.4  292.86  4831.9  292.20  4857.3  291.18  4882.9  289.05  4888.2  289.20
  4913.8  287.75  4919.1  288.05  4930.8  287.60  4969.2  286.29  4986.7  284.69
  4990.5  285.10  4991.8  285.24  4996.7  284.15  4997.2  283.35  5002.5  283.35
  5003.0  284.15  5010.1  284.25  5040.9  286.82  5051.1  287.17  5092.1  288.36
  5244.7  290.61  5287.1  292.34  5417.8  296.08  5491.8  298.88  5514.5  299.87
#Mann=6,-1,0
  4650.7    0.05       0  4930.8     0.1       0  4990.5    0.05       0
  4996.7    0.04       0  5003.0    0.05       0  5491.8     0.1       0
Bank Sta=4996.7,5003
Exp/Cntr=0.3,0.1

Type RM Length L Ch R = 1,4223,434,434,434
BEGIN DESCRIPTION:
UNT 007 in La Jarita Watershed 10.0
END DESCRIPTION:
XS GIS Cut Line= 5
      2097344.81     13411659.70      2097445.50     13411315.96
      2097473.27     13411128.46      2097476.75     13411003.46
      2097244.14     13410857.65
#Sta/Elev= 30
  4625.9  298.37  4703.7  297.43  4784.3  295.15  4789.5  295.46  4807.9  294.56
  4822.9  294.52  4849.6  292.49  4856.3  291.34  4861.5  291.63  4889.7  287.80
  4928.4  285.47  4933.6  285.54  4971.5  281.85  4972.0  281.05  4977.4  281.05
  4977.9  281.85  5005.3  283.32  5012.6  284.50  5017.6  283.14  5055.8  286.51
  5082.1  287.46  5087.1  287.00  5146.5  288.38  5197.1  288.94  5301.9  291.77
  5327.1  293.13  5363.7  294.24  5456.0  295.94  5509.8  297.09  5573.2  299.82
#Mann=4,-1,0
  4625.9    0.05       0  4971.5    0.04       0  4977.9    0.05       0
  5456.0     0.1       0
Bank Sta=4971.5,4977.9
Exp/Cntr=0.3,0.1

Type RM Length L Ch R = 1,3789,276,276,276
BEGIN DESCRIPTION:
UNT 007 in La Jarita Watershed 11.0
END DESCRIPTION:
XS GIS Cut Line= 3
      2097959.40     13411451.41      2097744.11     13410968.74
      2097269.18     13410753.81
#Sta/Elev= 30
  4430.6  296.27  4590.9  295.05  4689.5  292.36  4743.5  288.73  4815.9  282.35
  4831.8  281.94  4847.3  283.17  4853.7  284.17  4864.7  284.47  4886.6  284.18
  4917.0  281.50  4922.5  280.31  4930.4  279.53  4955.2  278.58  4955.7  277.78
  4961.1  277.78  4961.6  278.58  4982.9  278.64  5000.5  279.51  5023.7  283.84
  5032.7  286.00  5035.0  286.61  5052.2  288.30  5103.9  289.14  5137.0  290.63
  5139.4  290.75  5317.4  297.23  5346.0  297.61  5420.7  299.98  5480.4  300.08
#Mann=7,-1,0
  4430.6    0.05       0  4815.9    0.07       0  4955.2    0.07       0
  4961.6    0.07       0  5032.7     0.1       0  5137.0    0.05       0
  5139.4     0.1       0
Bank Sta=4955.2,4961.6
Exp/Cntr=0.3,0.1

Type RM Length L Ch R = 1,3513,389,389,389
BEGIN DESCRIPTION:
UNT 007 in La Jarita Watershed 12.0
END DESCRIPTION:
XS GIS Cut Line= 4
      2097960.34     13411552.72      2098089.04     13411231.84
      2097931.61     13410857.63      2097660.78     13410295.14
#Sta/Elev= 30
  4107.9  296.22  4547.8  293.33  4630.4  290.97  4757.0  283.47  4812.9  283.68
  4858.3  280.42  4882.8  282.09  4910.9  278.91  4930.3  278.58  4930.8  277.78
  4936.3  277.78  4936.8  278.58  4973.3  278.58  5024.1  278.74  5052.2  282.29
  5074.9  283.63  5091.9  282.96  5097.5  283.77  5114.6  282.62  5120.1  283.91
  5137.2  283.63  5142.7  285.05  5159.8  285.08  5165.4  286.35  5205.1  286.61
  5227.7  287.91  5257.8  291.73  5284.3  293.64  5406.4  298.06  5483.9  298.03
#Mann=6,-1,0
  4107.9    0.05       0  4757.0    0.07       0  4930.3   0.033       0
  4936.8    0.07       0  4973.3    0.05       0  5257.8     0.1       0
Bank Sta=4930.3,4936.8
Exp/Cntr=0.3,0.1

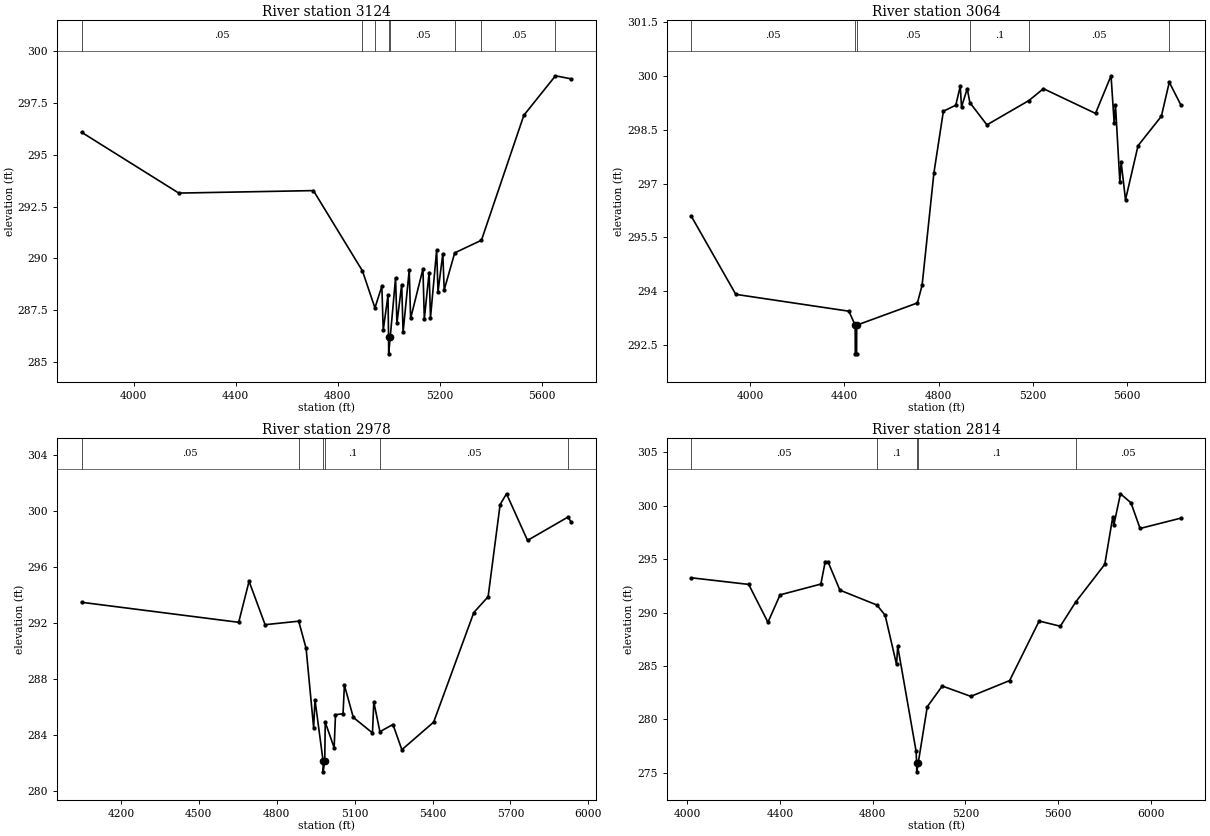
Type RM Length L Ch R = 1,3124,60,60,60
BEGIN DESCRIPTION:
UNT 007 in La Jarita Watershed 13.0
END DESCRIPTION:
XS GIS Cut Line= 6
      2097975.06     13411553.65      2098260.88     13411265.49
      2098223.27     13410822.91      2098202.44     13410635.41
      2097962.86     13410041.66      2097748.79     13409934.62
#Sta/Elev= 30
  3795.9  296.09  4176.7  293.15  4704.2  293.27  4896.2  289.39  4945.2  287.60
  4972.3  288.65  4977.7  286.52  4996.4  288.21  4998.6  286.18  4999.1  285.38
  5005.1  286.18  5026.0  289.05  5031.4  286.86  5050.1  288.73  5055.5  286.42
  5079.6  289.43  5085.0  287.09  5133.3  289.48  5138.7  287.06  5157.5  289.31
  5162.9  287.13  5187.0  290.39  5192.4  288.38  5211.2  290.22  5216.6  288.47
  5257.7  290.26  5362.5  290.87  5528.6  296.91  5652.5  298.82  5714.2  298.67
#Mann=8,-1,0
  3795.9    0.05       0  4896.2     0.1       0  4945.2    0.05       0
  4998.6   0.033       0  5005.1    0.05       0  5257.7     0.1       0
  5362.5    0.05       0  5652.5     0.1       0
Bank Sta=4998.6,5005.1
Exp/Cntr=0.3,0.1

Type RM Length L Ch R = 1,3064,86,86,86
BEGIN DESCRIPTION:
UNT 007 in La Jarita Watershed 14.0
END DESCRIPTION:
XS GIS Cut Line= 5
      2097974.19     13411559.72      2098298.35     13411292.37
      2098261.47     13410628.46      2098004.52     13409986.10
      2097728.36     13409872.18
#Sta/Elev= 30
  3751.5  296.09  3940.1  293.91  4419.4  293.44  4446.2  293.05  4446.7  292.25
  4452.2  292.25  4452.7  293.05  4709.9  293.67  4729.9  294.16  4780.0  297.30
  4820.1  299.02  4872.8  299.19  4891.6  299.72  4897.0  299.14  4921.2  299.65
  4932.5  299.26  5004.7  298.64  5182.9  299.32  5244.3  299.65  5465.1  298.96
  5530.9  300.01  5544.3  298.68  5549.7  299.20  5568.2  297.05  5573.7  297.60
  5592.2  296.55  5645.4  298.06  5744.3  298.88  5777.8  299.83  5827.2  299.19
#Mann=6,-1,0
  3751.5    0.05       0  4446.2    0.07       0  4452.7    0.05       0
  4932.5     0.1       0  5182.9    0.05       0  5777.8     0.1       0
Bank Sta=4446.2,4452.7
Exp/Cntr=0.3,0.1

Type RM Length L Ch R = 1,2978,164,164,164
BEGIN DESCRIPTION:
UNT 007 in La Jarita Watershed 15.0
END DESCRIPTION:
XS GIS Cut Line= 5
      2098344.80     13411409.67      2098365.64     13410756.94
      2098205.91     13410180.55      2098080.91     13409909.71
      2097748.81     13409857.82
#Sta/Elev= 30
  4048.5  293.51  4653.5  292.08  4693.5  295.01  4755.2  291.91  4884.7  292.16
  4913.1  290.22  4942.2  284.54  4947.4  286.54  4978.4  282.20  4978.9  281.40
  4984.9  282.20  4986.9  284.94  5021.2  283.12  5026.3  285.48  5055.4  285.55
  5060.6  287.59  5094.9  285.29  5168.7  284.18  5173.9  286.39  5197.3  284.27
  5247.6  284.78  5281.9  282.98  5404.3  284.95  5559.1  292.78  5614.1  293.91
  5660.3  300.49  5684.9  301.26  5765.9  297.93  5921.9  299.60  5934.1  299.23
#Mann=6,-1,0
  4048.5    0.05       0  4884.7     0.1       0  4978.4    0.07       0
  4984.9     0.1       0  5197.3    0.05       0  5921.9     0.1       0
Bank Sta=4978.4,4984.9
Exp/Cntr=0.3,0.1

Type RM Length L Ch R = 1,2814,0,0,0
BEGIN DESCRIPTION:
UNT 007 in La Jarita Watershed 16.0
END DESCRIPTION:
XS GIS Cut Line= 4
      2098369.10     13411423.64      2098521.89     13410871.52
      2098306.61     13409951.38      2097733.71     13409791.66
#Sta/Elev= 30
  4017.7  293.26  4265.3  292.64  4348.3  289.09  4400.7  291.66  4576.6  292.67
  4595.5  294.77  4607.5  294.76  4658.9  292.10  4818.3  290.71  4854.0  289.75
  4903.2  285.14  4908.3  286.83  4987.5  277.02  4990.0  275.88  4990.5  275.08
  4996.5  275.88  5035.8  281.18  5100.5  283.12  5223.7  282.15  5391.1  283.63
  5518.6  289.21  5609.9  288.72  5676.2  290.99  5801.7  294.52  5835.8  298.91
  5841.0  298.23  5869.4  301.13  5914.6  300.29  5954.0  297.88  6130.3  298.85
#Mann=5,-1,0
  4017.7    0.05       0  4818.3     0.1       0  4990.0    0.07       0
  4996.5     0.1       0  5676.2    0.05       0
Bank Sta=4990,4996.5
Exp/Cntr=0.3,0.1

Chan Stop Cuts=-1