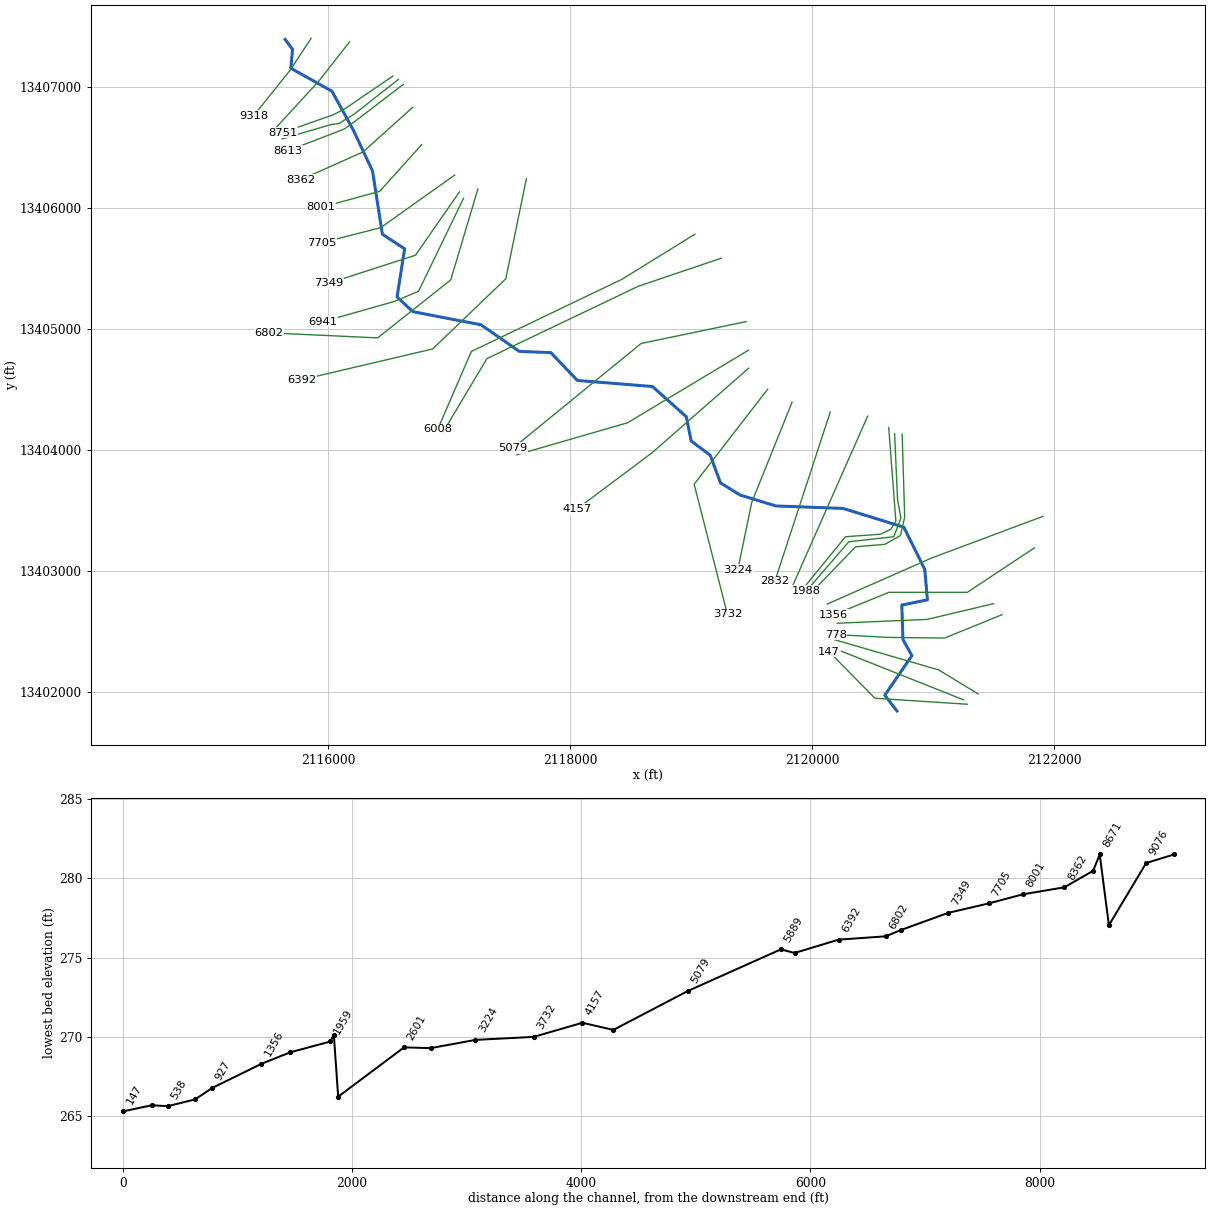
--- UNT 008 in La Jarita Watershed.prj (project) ---

Proj Title=UNT 008 in La Jarita Watershed Base Level Engineering
Current Plan=p01
Default Exp/Contr=0.3,0.1
English Units
Geom File=g01
Flow File=f01
Plan File=p01
Y Axis Title=Elevation
X Axis Title(PF)=Main Channel Distance
X Axis Title(XS)=Station
BEGIN DESCRIPTION:
UNT 008 in La Jarita Watershed
END DESCRIPTION:
DSS Export Rating Curves= 0
DSS Export Rating Curve Sorted= 0
DSS Export Volume Flow Curves= 0
DXF OffsetX= 0
DXF OffsetY= 0
DXF ScaleX= 1
DXF ScaleY= 10

--- UNT 008 in La Jarita Watershed.p01 (plan) ---

Plan Title=Multiple Run
Short Identifier=Multiple
Geom File=g01
Flow File=f01
Subcritical Flow
K Sum by GR= 0
Std Step Tol= 0.01
Critical Tol= 0.01
Num of Std Step Trials= 20
Max Error Tol= 0.3
Flow Tol Ratio= 0.001
Split Flow NTrial= 30
Split Flow Tol= 0.02
Split Flow Ratio= 0.02
Log Output Level= 0
Friction Slope Method= 1
Unsteady Friction Slope Method= 2
Unsteady Bridges Friction Slope Method= 1
Parabolic Critical Depth
Global Vel Dist=  1 , 1 , 1
Global Log Level= 0
CheckData=True
Encroach Param= -1, 0, 0, 0
BEGIN DESCRIPTION:
Multiple Run
END DESCRIPTION:

--- UNT 008 in La Jarita Watershed.f01 (steady flow) ---

Flow Title=Multiple
Program Version=5.05
Number of Profiles= 7
Profile Names=10-year,25-year,50-year,1pct_min,100-year,1pct_plu,500-year
River Rch & RM=UNT 008 in La Ja,Reach-1         ,9318
     121     160     190     113     226     451     324
River Rch & RM=UNT 008 in La Ja,Reach-1         ,6008
     172     232     280     169     337     673     496
River Rch & RM=UNT 008 in La Ja,Reach-1         ,5079
     189     255     309     186     371     741     545
River Rch & RM=UNT 008 in La Ja,Reach-1         ,1356
     224     306     372     226     450     898     669
Boundary for River Rch & Prof#=UNT 008 in La Ja,Reach-1         , 1
Up Type= 0
Dn Type= 3
Dn Slope=0.005
Boundary for River Rch & Prof#=UNT 008 in La Ja,Reach-1         , 2
Up Type= 0
Dn Type= 3
Dn Slope=0.005
Boundary for River Rch & Prof#=UNT 008 in La Ja,Reach-1         , 3
Up Type= 0
Dn Type= 3
Dn Slope=0.005
Boundary for River Rch & Prof#=UNT 008 in La Ja,Reach-1         , 4
Up Type= 0
Dn Type= 3
Dn Slope=0.005
Boundary for River Rch & Prof#=UNT 008 in La Ja,Reach-1         , 5
Up Type= 0
Dn Type= 3
Dn Slope=0.005
Boundary for River Rch & Prof#=UNT 008 in La Ja,Reach-1         , 6
Up Type= 0
Dn Type= 3
Dn Slope=0.005
Boundary for River Rch & Prof#=UNT 008 in La Ja,Reach-1         , 7
Up Type= 0
Dn Type= 3
Dn Slope=0.005
DSS Import GetInterval= 0
DSS Import GetPeak= 0
DSS Import FillOption= 0

--- UNT 008 in La Jarita Watershed.g01 (geometry) ---

Geom Title=Existing Conditions
Program Version=5.05

River Reach=UNT 008 in La Ja,Reach-1
Reach XY= 30
        2115646.     13407391.97       2115707.4     13407309.15
      2115692.75     13407153.37      2116032.46     13406964.37
      2116210.86     13406639.77      2116367.92     13406304.71
      2116449.38     13405782.47      2116633.09     13405662.07
       2116570.8     13405264.54       2116701.5     13405142.77
      2117264.65     13405034.26       2117580.8     13404814.54
       2117840.8     13404804.54       2118060.8     13404574.54
       2118680.8     13404524.54       2118960.8     13404274.54
       2119000.8     13404074.54      2119158.06     13403957.27
      2119243.38     13403727.93      2119405.06      13403628.1
       2119700.2     13403538.04      2120256.84     13403517.42
      2120758.14     13403362.26       2120930.8     13403014.54
       2120952.8     13402762.32      2120741.21     13402718.92
       2120750.8     13402433.55      2120824.76     13402301.17
       2120600.8     13401974.54       2120700.8     13401844.54

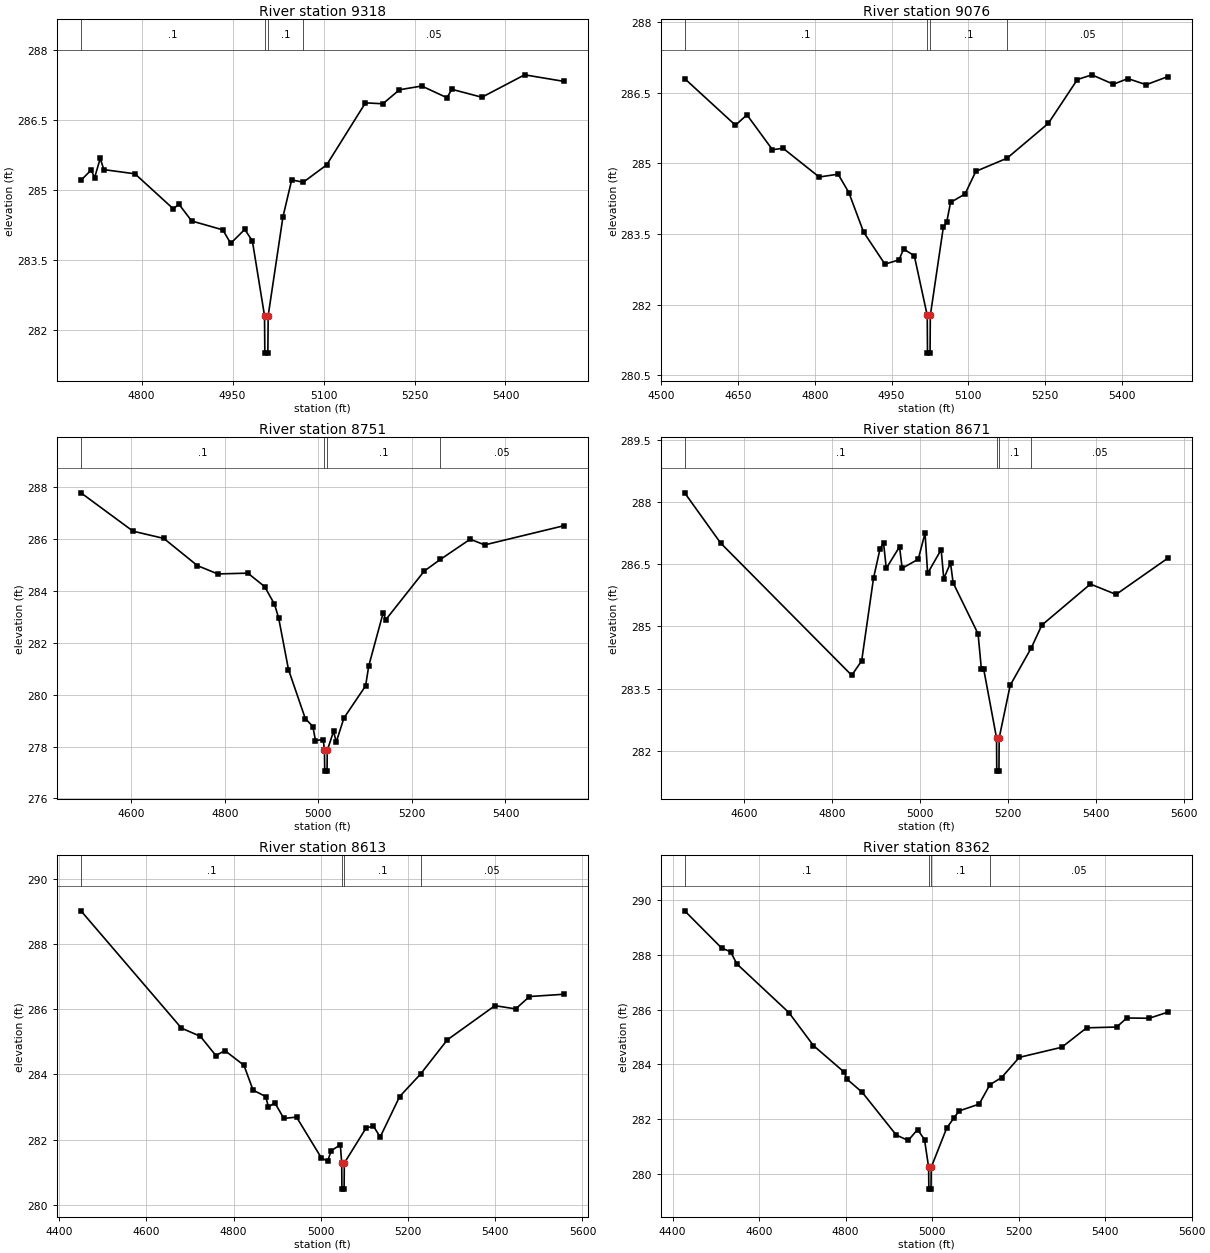
Type RM Length L Ch R = 1 ,9318    ,242,242,242
BEGIN DESCRIPTION:
Mapping XS fdbff936
END DESCRIPTION:
XS GIS Cut Line= 3
       2115860.6     13407401.69       2115690.6     13407141.46
      2115386.69     13406763.03
#Sta/Elev= 30
    4700  285.21  4716.7  285.43  4722.6  285.27  4731.8  285.68  4737.8  285.44
  4789.1  285.35  4852.3   284.6  4861.5   284.7  4882.6  284.34  4933.9  284.15
  4946.9  283.86  4970.1  284.16  4982.7  283.91  5002.7  282.31  5003.2  281.51
  5008.2  281.51  5008.7  282.31  5033.1  284.43  5047.5  285.22  5066.6  285.17
  5105.1  285.54  5169.1  286.87  5197.9  286.85  5225.1  287.15  5261.9  287.23
  5303.5  286.98  5311.5  287.16  5361.1  286.99  5431.5  287.47  5496.2  287.33
#Mann= 4 ,-1 , 0
    4700      .1       0  5002.7     .07       0  5008.7      .1       0
  5066.6     .05       0
Bank Sta=5002.7,5008.7
XS Rating Curve= 0 ,0
Exp/Cntr=0.3,0.1

Type RM Length L Ch R = 1 ,9076    ,325,325,325
BEGIN DESCRIPTION:
Mapping XS e7b3b90c
END DESCRIPTION:
XS GIS Cut Line= 3
      2116178.27     13407371.74      2115920.02       13407042.
      2115564.27      13406656.5
#Sta/Elev= 30
  4545.9   286.8  4645.1  285.81  4667.6  286.03  4717.4  285.29  4738.2  285.32
  4808.7  284.71  4845.7  284.77  4866.6  284.38  4895.5  283.54  4937.1  282.86
  4964.7  282.95  4973.5  283.18  4994.5  283.04  5019.8  281.77  5020.3  280.97
  5025.3  280.97  5025.8  281.77  5051.2  283.64    5058  283.76  5065.3  284.17
  5093.7  284.35  5114.7  284.83  5175.8  285.11  5256.4  285.85  5313.1  286.78
  5341.5  286.88  5383.5  286.68  5411.8   286.8  5447.5  286.67  5489.3  286.84
#Mann= 4 ,-1 , 0
  4545.9      .1       0  5019.8     .07       0  5025.8      .1       0
  5175.8     .05       0
Bank Sta=5019.8,5025.8
XS Rating Curve= 0 ,0
Exp/Cntr=0.3,0.1

Type RM Length L Ch R = 1 ,8751    ,80,80,80
BEGIN DESCRIPTION:
Mapping XS 61e0156a
END DESCRIPTION:
XS GIS Cut Line= 4
      2116536.72     13407089.43      2116137.72     13406817.91
      2116043.25     13406769.09      2115625.42      13406622.1
#Sta/Elev= 30
  4492.8  287.79  4604.1  286.31  4669.9  286.03  4741.7  284.98  4785.2  284.66
  4849.5  284.69  4885.4  284.17  4906.4  283.49  4915.3  282.96  4936.3  280.97
  4972.2  279.08  4988.4  278.77    4994  278.23  5010.5  278.27  5013.2  277.85
  5013.7  277.05  5018.7  277.05  5019.2  277.85  5032.7  278.59  5038.3  278.17
  5054.8   279.1  5101.1  280.34  5107.8  281.11  5138.8  283.17  5144.1  282.89
  5226.4  284.77  5260.9  285.22  5324.6     286  5355.5  285.78  5524.7  286.52
#Mann= 4 ,-1 , 0
  4492.8      .1       0  5013.2     .07       0  5019.2      .1       0
  5260.9     .05       0
Bank Sta=5013.2,5019.2
XS Rating Curve= 0 ,0
Exp/Cntr=0.3,0.1

Type RM Length L Ch R = 1 ,8671    ,58,58,58
BEGIN DESCRIPTION:
Mapping XS ae852fff
END DESCRIPTION:
XS GIS Cut Line= 5
       2116582.6      13407061.9      2116214.24     13406773.23
      2116089.34      13406696.6      2116028.29     13406689.44
      2115622.56     13406570.17
#Sta/Elev= 30
  4464.4  288.22  4546.2  287.01  4844.6  283.82  4867.2  284.17  4894.3  286.17
  4908.8  286.86  4916.9  287.02  4923.2   286.4  4953.4  286.92  4959.3   286.4
    4996  286.62  5011.4  287.25  5017.3  286.28  5048.1  286.85    5054  286.15
  5069.4  286.53  5075.3  286.05  5132.1  284.82  5139.5  283.98  5144.7  283.98
  5174.1  282.31  5174.6  281.51  5179.6  281.51  5180.1  282.31  5205.2  283.58
  5253.1  284.48  5277.2  285.03  5387.7  286.02  5446.1  285.77  5563.3  286.64
#Mann= 4 ,-1 , 0
  4464.4      .1       0  5174.1     .07       0  5180.1      .1       0
  5253.1     .05       0
Bank Sta=5174.1,5180.1
XS Rating Curve= 0 ,0
Exp/Cntr=0.3,0.1

Type RM Length L Ch R = 1 ,8613    ,251,251,251
BEGIN DESCRIPTION:
Mapping XS 537cd1ff
END DESCRIPTION:
XS GIS Cut Line= 4
       2116622.5     13407020.56      2116226.68     13406717.91
      2116135.32     13406651.79      2115671.87     13406473.49
#Sta/Elev= 30
  4449.7  289.02  4680.3  285.42  4723.5  285.17  4759.2  284.58    4780  284.73
  4823.6  284.28  4844.4  283.52  4873.5  283.32  4879.8     283  4894.3  283.13
  4915.1  282.65  4944.2  282.69  5000.6  281.45  5015.3  281.33  5023.8  281.66
  5044.7  281.84  5047.8  281.28  5048.3  280.48  5053.3  280.48  5053.8  281.28
  5103.9  282.36  5120.7  282.41  5136.1  282.08  5180.7  283.32  5228.6  284.01
    5290  285.06  5399.3  286.11  5446.8  286.01  5478.5  286.39  5557.3  286.46
#Mann= 4 ,-1 , 0
  4449.7      .1       0  5047.8     .07       0  5053.8      .1       0
  5228.6     .05       0
Bank Sta=5047.8,5053.8
XS Rating Curve= 0 ,0
Exp/Cntr=0.3,0.1

Type RM Length L Ch R = 1 ,8362    ,361,361,361
BEGIN DESCRIPTION:
Mapping XS 036b407c
END DESCRIPTION:
XS GIS Cut Line= 3
      2116699.59     13406830.53      2116288.76     13406462.06
       2115773.6     13406231.65
#Sta/Elev= 30
  4428.1  289.62  4513.5  288.26  4534.4  288.12  4548.6  287.68  4668.9   285.9
  4725.8  284.69  4796.8  283.72  4803.5  283.46  4838.6  282.98  4917.1  281.42
  4944.8  281.22  4966.5  281.62  4982.5  281.25    4992  280.24  4992.5  279.44
  4997.5  279.44    4998  280.24  5033.7  281.67  5049.8  282.03  5062.4   282.3
  5108.8  282.55  5133.6  283.26  5160.6  283.52  5201.6  284.26  5299.9  284.63
  5357.2  285.34  5426.8  285.37    5450   285.7  5501.9  285.69  5544.3  285.91
#Mann= 4 ,-1 , 0
  4428.1      .1       0    4992     .07       0    4998      .1       0
  5133.6     .05       0
Bank Sta=4992,4998
XS Rating Curve= 0 ,0
Exp/Cntr=0.3,0.1

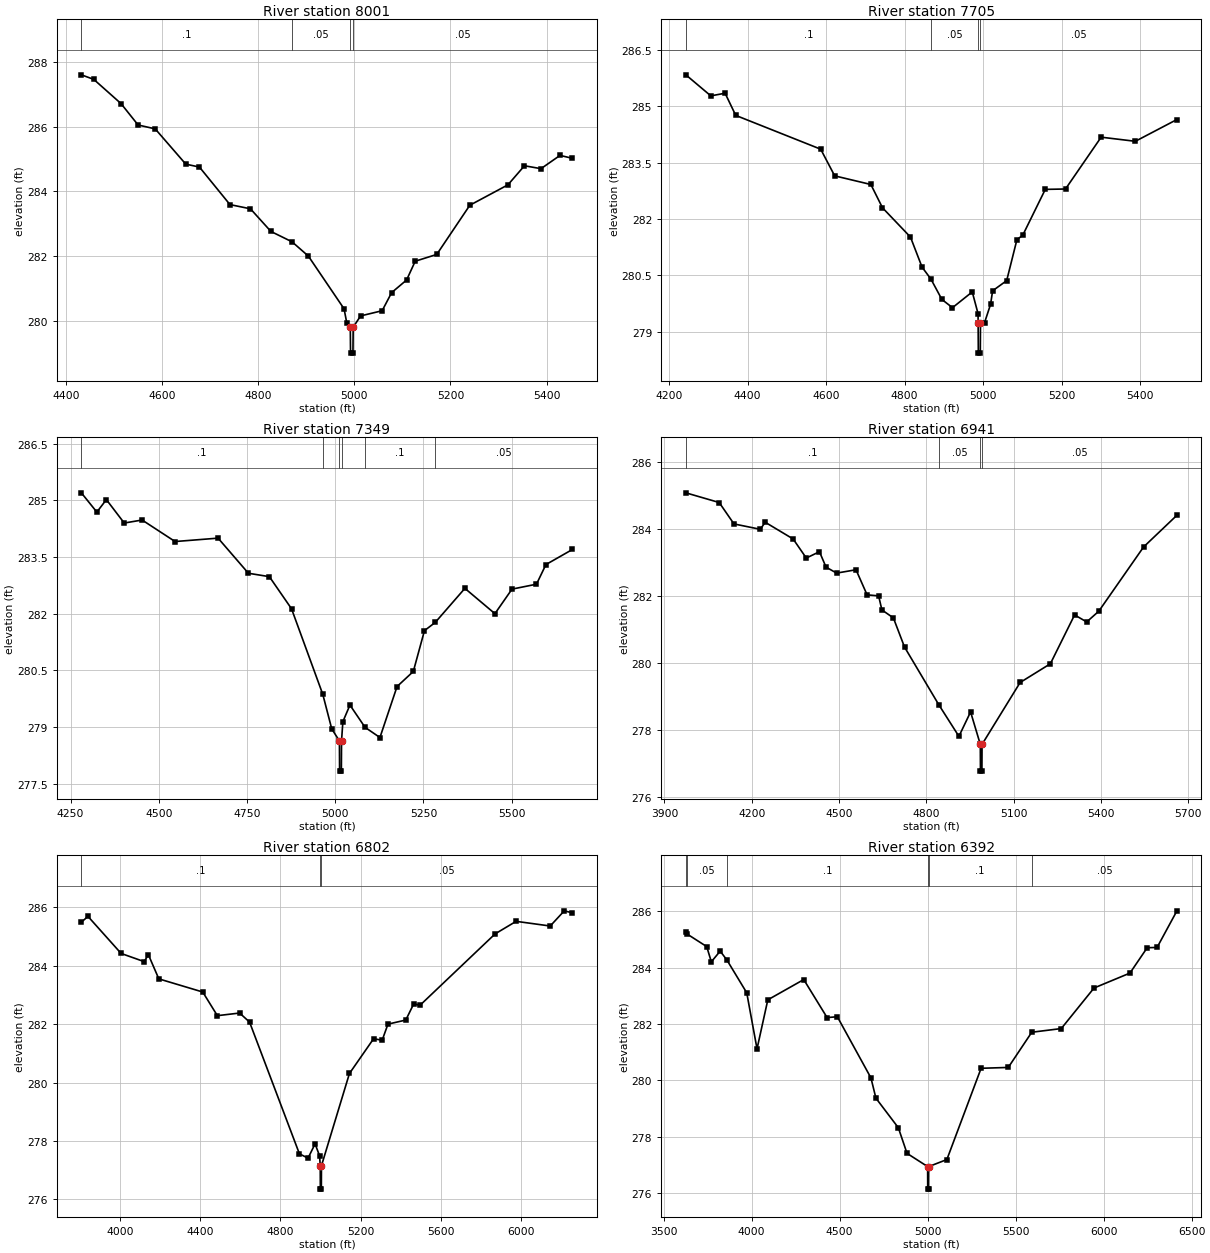
Type RM Length L Ch R = 1 ,8001    ,296,296,296
BEGIN DESCRIPTION:
Mapping XS 784affe9
END DESCRIPTION:
XS GIS Cut Line= 3
      2116774.05     13406522.78      2116427.46     13406137.31
      2115942.44      13406003.9
#Sta/Elev= 30
  4432.4   287.6  4458.2  287.46    4515  286.71  4550.4  286.05    4586  285.93
  4649.6  284.84    4678  284.75  4741.5  283.59  4784.1  283.46  4826.7  282.76
  4870.6  282.44  4904.5     282  4978.8  280.37  4984.4  279.94  4991.8   279.8
  4992.3     279  4997.3     279  4997.8   279.8  5013.2  280.15    5058  280.31
  5077.8  280.87  5108.9  281.26  5126.8  281.84  5171.6  282.05  5240.4  283.57
  5319.6   284.2    5354  284.79  5388.4   284.7    5428  285.11  5453.8  285.02
#Mann= 4 ,-1 , 0
  4432.4      .1       0  4870.6     .05       0  4991.8     .03       0
  4997.8     .05       0
Bank Sta=4991.8,4997.8
XS Rating Curve= 0 ,0
Exp/Cntr=0.3,0.1

Type RM Length L Ch R = 1 ,7705    ,356,356,356
BEGIN DESCRIPTION:
Mapping XS 64ef1c07
END DESCRIPTION:
XS GIS Cut Line= 3
      2117046.87     13406271.26      2116434.76     13405836.26
      2115949.85     13405713.28
#Sta/Elev= 30
  4242.7  285.84  4306.3  285.28  4342.7  285.35  4369.8  284.76  4586.3  283.86
  4621.9  283.15  4714.1  282.92  4743.7   282.3    4815  281.52  4844.5  280.72
  4867.2   280.4    4895  279.86    4922  279.64  4972.4  280.06  4987.2  279.48
  4987.4  279.23  4987.9  278.43  4992.9  278.43  4993.4  279.23  5003.7  279.24
  5019.1  279.73  5024.3  280.09  5060.1  280.36  5086.2  281.45  5101.1  281.57
  5158.5  282.79    5210   282.8  5300.8  284.18  5387.9  284.07  5493.9  284.65
#Mann= 4 ,-1 , 0
  4242.7      .1       0  4867.2     .05       0  4987.4     .03       0
  4993.4     .05       0
Bank Sta=4987.4,4993.4
XS Rating Curve= 0 ,0
Exp/Cntr=0.3,0.1

Type RM Length L Ch R = 1 ,7349    ,408,408,408
BEGIN DESCRIPTION:
Mapping XS 2d6857c9
END DESCRIPTION:
XS GIS Cut Line= 3
      2117087.13     13406133.03      2116722.72       13405609.
      2116005.97     13405377.78
#Sta/Elev= 30
  4280.7   285.2  4324.6  284.69  4351.6  285.02  4402.2   284.4  4452.9  284.48
  4546.3  283.91  4668.1     284    4754  283.07  4813.4  282.98  4876.2  282.13
  4964.9  279.86  4990.1  278.95  5011.9  278.63  5012.4  277.83  5017.4  277.83
  5017.9  278.63  5021.7  279.14  5041.7  279.58  5084.5  278.99  5126.7  278.72
  5175.2  280.07  5221.3  280.47  5252.8  281.55  5283.6  281.77  5367.4  282.67
  5452.5     282  5500.9  282.65  5570.2  282.78    5597   283.3  5672.1   283.7
#Mann= 6 ,-1 , 0
  4280.7      .1       0  4964.9     .05       0  5011.9     .03       0
  5017.9     .05       0  5084.5      .1       0  5283.6     .05       0
Bank Sta=5011.9,5017.9
XS Rating Curve= 0 ,0
Exp/Cntr=0.3,0.1

Type RM Length L Ch R = 1 ,6941    ,139,139,139
BEGIN DESCRIPTION:
Mapping XS ec64c17d
END DESCRIPTION:
XS GIS Cut Line= 4
      2117120.89     13406081.18      2116748.33     13405311.48
      2116550.15     13405227.65      2115956.69     13405059.59
#Sta/Elev= 30
  3973.6  285.08  4088.2  284.79  4138.9  284.15  4229.3  283.99  4246.3   284.2
  4342.2   283.7  4387.4  283.13  4432.6  283.32  4455.1  282.86  4491.5  282.68
  4558.2  282.78  4596.2  282.03  4635.8     282  4647.1  281.58  4686.6  281.34
  4724.8  280.47  4842.2  278.75  4911.7   277.8  4951.8  278.53  4985.2  277.56
  4985.7  276.76  4990.7  276.76  4991.2  277.56    5122  279.41  5225.9  279.97
  5309.1  281.43  5350.7  281.22  5392.2  281.54    5546  283.46  5660.7  284.41
#Mann= 4 ,-1 , 0
  3973.6      .1       0  4842.2     .05       0  4985.2     .03       0
  4991.2     .05       0
Bank Sta=4985.2,4991.2
XS Rating Curve= 0 ,0
Exp/Cntr=0.3,0.1

Type RM Length L Ch R = 1 ,6802    ,410,410,410
BEGIN DESCRIPTION:
UNT 008 in La Jarita Watershed 4.0
END DESCRIPTION:
XS GIS Cut Line= 4
       2117238.3     13406155.44      2117014.34     13405405.42
      2116410.17     13404926.25       2115514.3     13404967.92
#Sta/Elev= 30
  3806.7  285.49  3839.7  285.69  4005.3  284.42  4120.4  284.14  4141.1  284.38
  4193.3  283.55  4412.5   283.1  4485.5  282.29  4596.6  282.38  4646.2  282.07
  4894.9  277.56  4937.9  277.41  4973.1   277.9  4995.6  277.49  4998.9  277.15
  4999.4  276.35  5004.4  276.35  5004.9  277.15  5144.6  280.31  5265.1   281.5
    5308  281.45  5336.8     282  5425.8  282.14  5465.8   282.7  5495.9  282.64
  5871.5  285.09  5976.4  285.52  6146.6  285.36  6216.7  285.88  6257.4  285.81
#Mann= 3 ,-1 , 0
  3806.7      .1       0  4998.9     .03       0  5004.9     .05       0
Bank Sta=4998.9,5004.9
XS Rating Curve= 0 ,0
Exp/Cntr=0.3,0.1

Type RM Length L Ch R = 1 ,6392    ,384,384,384
BEGIN DESCRIPTION:
Mapping XS fb4e0817
END DESCRIPTION:
XS GIS Cut Line= 4
      2117639.33     13406241.13       2117469.2     13405414.79
      2116865.03     13404834.93      2115785.16     13404581.46
#Sta/Elev= 30
  3626.1  285.27  3632.4   285.2  3744.7  284.75  3770.9  284.21  3821.2  284.59
  3859.8  284.27  3972.1  283.11  4030.5  281.12  4091.8  282.86    4296  283.58
  4428.7  282.23  4486.8  282.26  4677.7  280.09    4706  279.37  4833.4  278.32
  4882.8  277.41  4999.9  276.94  5000.4  276.14  5005.4  276.14  5005.9  276.94
  5109.2  277.19  5303.7  280.43  5458.1  280.46  5591.6  281.71  5759.2  281.84
  5945.3  283.28  6149.5  283.81  6247.4  284.71  6303.6  284.72  6416.4  286.02
#Mann= 6 ,-1 , 0
  3626.1      .1       0  3632.4     .05       0  3859.8      .1       0
  4999.9     .07       0  5005.9      .1       0  5591.6     .05       0
Bank Sta=4999.9,5005.9
XS Rating Curve= 0 ,0
Exp/Cntr=0.3,0.1

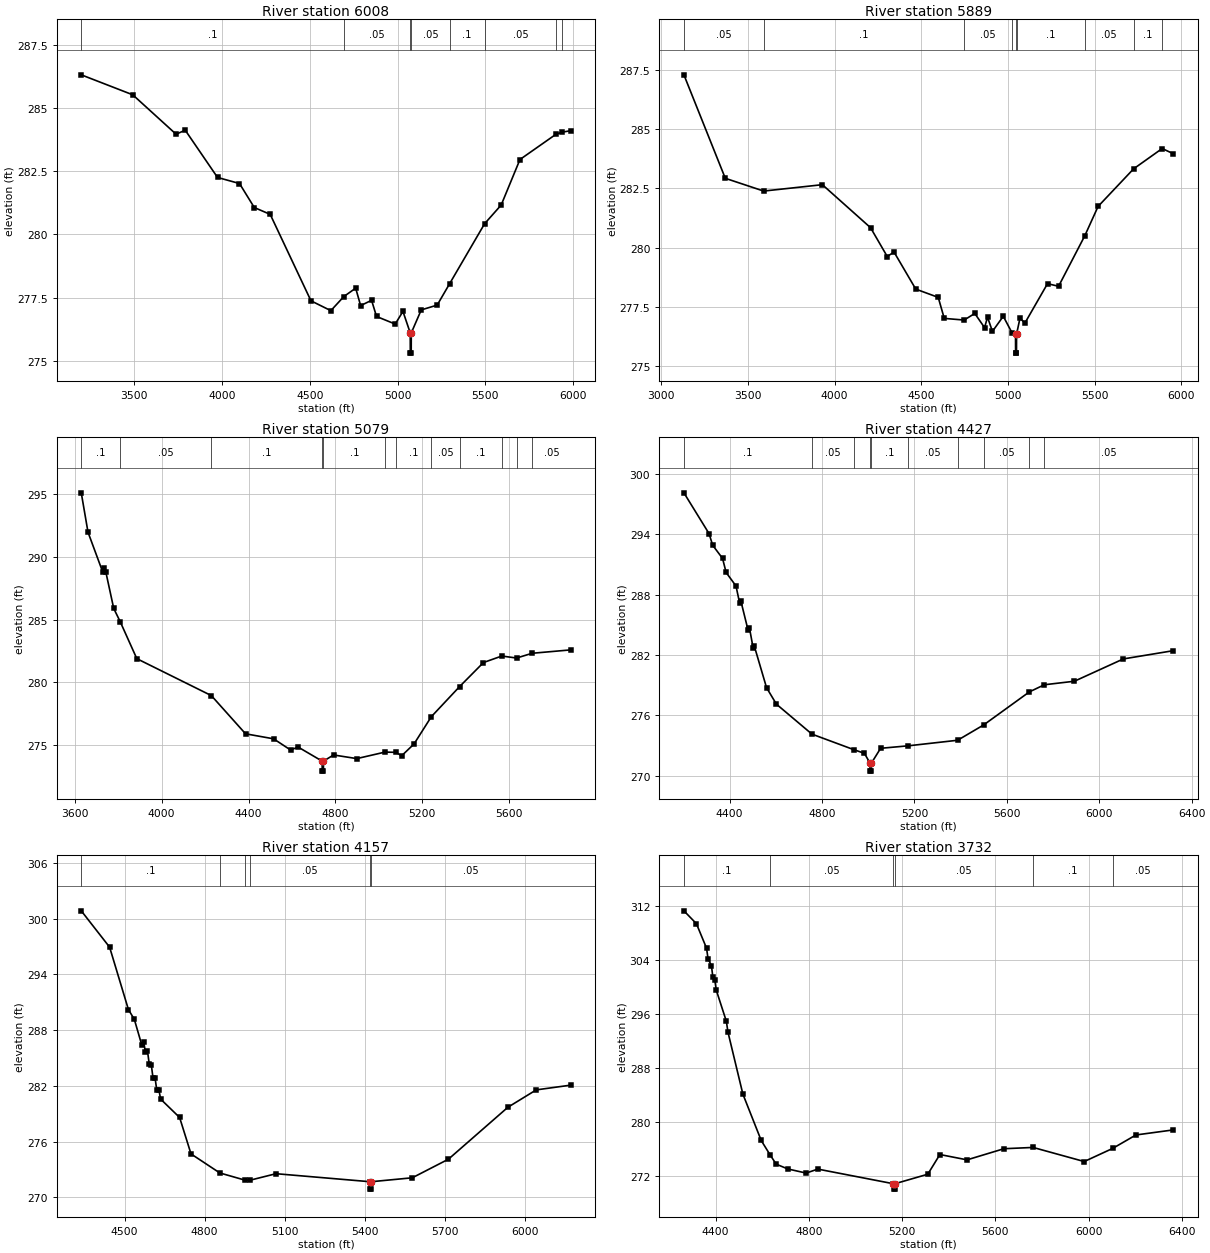
Type RM Length L Ch R = 1 ,6008    ,119,119,119
BEGIN DESCRIPTION:
Mapping XS c2769eac
END DESCRIPTION:
XS GIS Cut Line= 4
      2119031.72     13405782.86        2118431.     13405411.32
      2117184.48      13404814.1      2116906.69     13404171.72
#Sta/Elev= 30
  3197.3  286.31  3490.6  285.52  3737.6  283.96  3789.6  284.12  3973.7  282.25
  4098.8  282.01  4183.2  281.06  4273.8  280.79    4506  277.37  4619.3  276.98
  4693.6  277.54  4760.8  277.87    4789  277.18  4851.4  277.39  4879.6  276.75
  4985.9  276.45  5030.2  276.95  5071.6   276.1  5072.1   275.3  5077.1   275.3
  5077.6   276.1  5134.4  277.01  5225.1   277.2  5295.5  278.04  5495.4  280.42
  5589.9  281.16  5696.8  282.96  5902.3  283.96  5936.3  284.04  5985.7   284.1
#Mann= 8 ,-1 , 0
  3197.3      .1       0  4693.6     .05       0  5071.6     .03       0
  5077.6     .05       0  5295.5      .1       0  5495.4     .05       0
  5902.3      .1       0  5936.3     .05       0
Bank Sta=5071.6,5077.6
XS Rating Curve= 0 ,0
Exp/Cntr=0.3,0.1

Type RM Length L Ch R = 1 ,5889    ,810,810,810
BEGIN DESCRIPTION:
Mapping XS e8f31169
END DESCRIPTION:
XS GIS Cut Line= 4
      2119250.42     13405584.92      2118562.95     13405352.29
      2117312.95     13404755.07      2116949.19     13404145.34
#Sta/Elev= 30
  3131.9  287.31  3370.4  282.93  3591.7  282.39    3930  282.66  4207.7  280.84
    4304  279.62    4343  279.81  4468.3  278.24  4597.9  277.89  4632.6     277
  4747.5  276.93  4808.5  277.21  4864.9  276.61  4882.1  277.05  4910.3  276.45
  4972.8  277.09  5024.7  276.37  5043.4  276.33  5043.9  275.53  5048.9  275.53
  5049.4  276.33  5069.1  277.01  5097.3   276.8  5227.8  278.47  5291.6  278.36
  5442.9   280.5  5519.4  281.74    5724  283.33  5888.8  284.19    5953  283.97
#Mann= 9 ,-1 , 0
  3131.9     .05       0  3591.7      .1       0  4747.5     .05       0
  5024.7      .1       0  5043.4     .03       0  5049.4      .1       0
  5442.9     .05       0    5724      .1       0  5888.8     .05       0
Bank Sta=5043.4,5049.4
XS Rating Curve= 0 ,0
Exp/Cntr=0.3,0.1

Type RM Length L Ch R = 1 ,5079    ,652,652,652
BEGIN DESCRIPTION:
Mapping XS 1f1f1004
END DESCRIPTION:
XS GIS Cut Line= 3
      2119455.35     13405060.63      2118587.25     13404880.07
      2117529.08     13404016.19
#Sta/Elev= 30
  3630.2  295.13  3661.2  291.99  3729.6  288.78  3734.7  289.15  3742.9  288.84
  3779.6   285.9  3809.5  284.84  3885.9  281.89    4229  278.94  4386.4  275.89
  4515.5  275.49  4593.4   274.6  4628.6  274.83  4738.9  273.71  4739.4  272.91
  4744.7  272.91  4745.2  273.71  4791.6   274.2  4898.5  273.91  5028.4  274.43
  5079.5  274.41  5104.6  274.13    5162  275.08  5241.7  277.26  5371.7  279.66
  5481.5  281.58  5565.9   282.1  5633.8  281.94  5705.8  282.32  5882.9  282.59
#Mann= 12 ,-1 , 0
  3630.2      .1       0  3809.5     .05       0    4229      .1       0
  4738.9     .07       0  4745.2      .1       0  5028.4     .05       0
  5079.5      .1       0  5241.7     .05       0  5371.7      .1       0
  5565.9     .05       0  5633.8      .1       0  5705.8     .05       0
Bank Sta=4738.9,4745.2
XS Rating Curve= 0 ,0
Exp/Cntr=0.3,0.1

Type RM Length L Ch R = 1 ,4427    ,270,270,270
BEGIN DESCRIPTION:
UNT 008 in La Jarita Watershed 3.0
END DESCRIPTION:
XS GIS Cut Line= 3
      2119475.03     13404825.02        2118475.       13404225.
      2117560.16     13403960.62
#Sta/Elev= 30
  4202.1  298.13    4311  294.07  4326.5  292.92  4369.3  291.61  4384.8  290.21
  4427.6  288.86  4443.1  287.18    4449  287.34  4480.1  284.44  4485.9  284.68
  4501.5  282.74  4507.3  282.85  4559.8  278.75  4602.5  277.11  4756.3  274.13
    4937  272.59  4983.5  272.22  5007.5  271.25    5008  270.45  5013.3  270.45
  5013.8  271.25  5053.5  272.72  5174.1  272.97  5386.8  273.52  5499.4  275.04
  5697.4  278.33  5762.2  279.04  5892.3  279.39  6104.4  281.61  6320.6  282.43
#Mann= 10 ,-1 , 0
  4202.1      .1       0  4756.3     .05       0    4937      .1       0
  5007.5     .07       0  5013.8      .1       0  5174.1     .05       0
  5386.8      .1       0  5499.4     .05       0  5697.4      .1       0
  5762.2     .05       0
Bank Sta=5007.5,5013.8
XS Rating Curve= 0 ,0
Exp/Cntr=0.3,0.1

Type RM Length L Ch R = 1 ,4157    ,425,425,425
BEGIN DESCRIPTION:
UNT 008 in La Jarita Watershed 2.0
END DESCRIPTION:
XS GIS Cut Line= 3
      2119475.02     13404675.02        2118675.       13403975.
      2118056.66     13403512.68
#Sta/Elev= 30
  4337.6  300.85  4443.9  296.94  4514.6  290.21  4536.5  289.18    4564  286.46
  4571.6  286.76  4578.2  285.64  4585.8  285.79  4592.5  284.36  4600.1  284.29
  4606.7  282.87  4614.3  282.88  4620.9  281.52  4628.5   281.6  4635.2  280.59
  4706.4  278.61  4749.1  274.69  4857.2  272.64  4952.3  271.86  4970.4  271.86
    5068  272.56  5419.3   271.7  5419.8   270.9  5425.2   270.9  5425.7   271.7
  5578.8  272.12  5714.3  274.12  5937.3  279.71  6043.6  281.58  6172.7  282.09
#Mann= 6 ,-1 , 0
  4337.6      .1       0  4857.2     .05       0  4952.3      .1       0
  4970.4     .05       0  5419.3     .03       0  5425.7     .05       0
Bank Sta=5419.3,5425.7
XS Rating Curve= 0 ,0
Exp/Cntr=0.3,0.1

Type RM Length L Ch R = 1 ,3732    ,508,508,508
BEGIN DESCRIPTION:
Mapping XS 500daae4
END DESCRIPTION:
XS GIS Cut Line= 3
      2119633.07     13404502.27      2119025.45     13403717.57
      2119299.76     13402644.63
#Sta/Elev= 30
  4263.8  311.27  4317.5  309.36    4361  305.72  4367.3  304.17  4381.8  303.15
  4388.1  301.43  4396.3  301.01  4402.6  299.52  4446.1  294.87  4452.4  293.35
  4516.7  284.11  4595.5  277.22  4634.1  275.06  4659.8  273.71  4709.6     273
  4788.4  272.39  4838.1  272.98  5162.7  270.81  5163.2  270.01  5168.6  270.01
  5169.1  270.81  5310.2  272.22  5362.1  275.14  5478.7  274.35  5636.8     276
    5762  276.19  5981.4   274.1  6103.2  276.04  6203.3  278.04  6363.7  278.79
#Mann= 6 ,-1 , 0
  4263.8      .1       0  4634.1     .05       0  5162.7     .03       0
  5169.1     .05       0    5762      .1       0  6103.2     .05       0
Bank Sta=5162.7,5169.1
XS Rating Curve= 0 ,0
Exp/Cntr=0.3,0.1

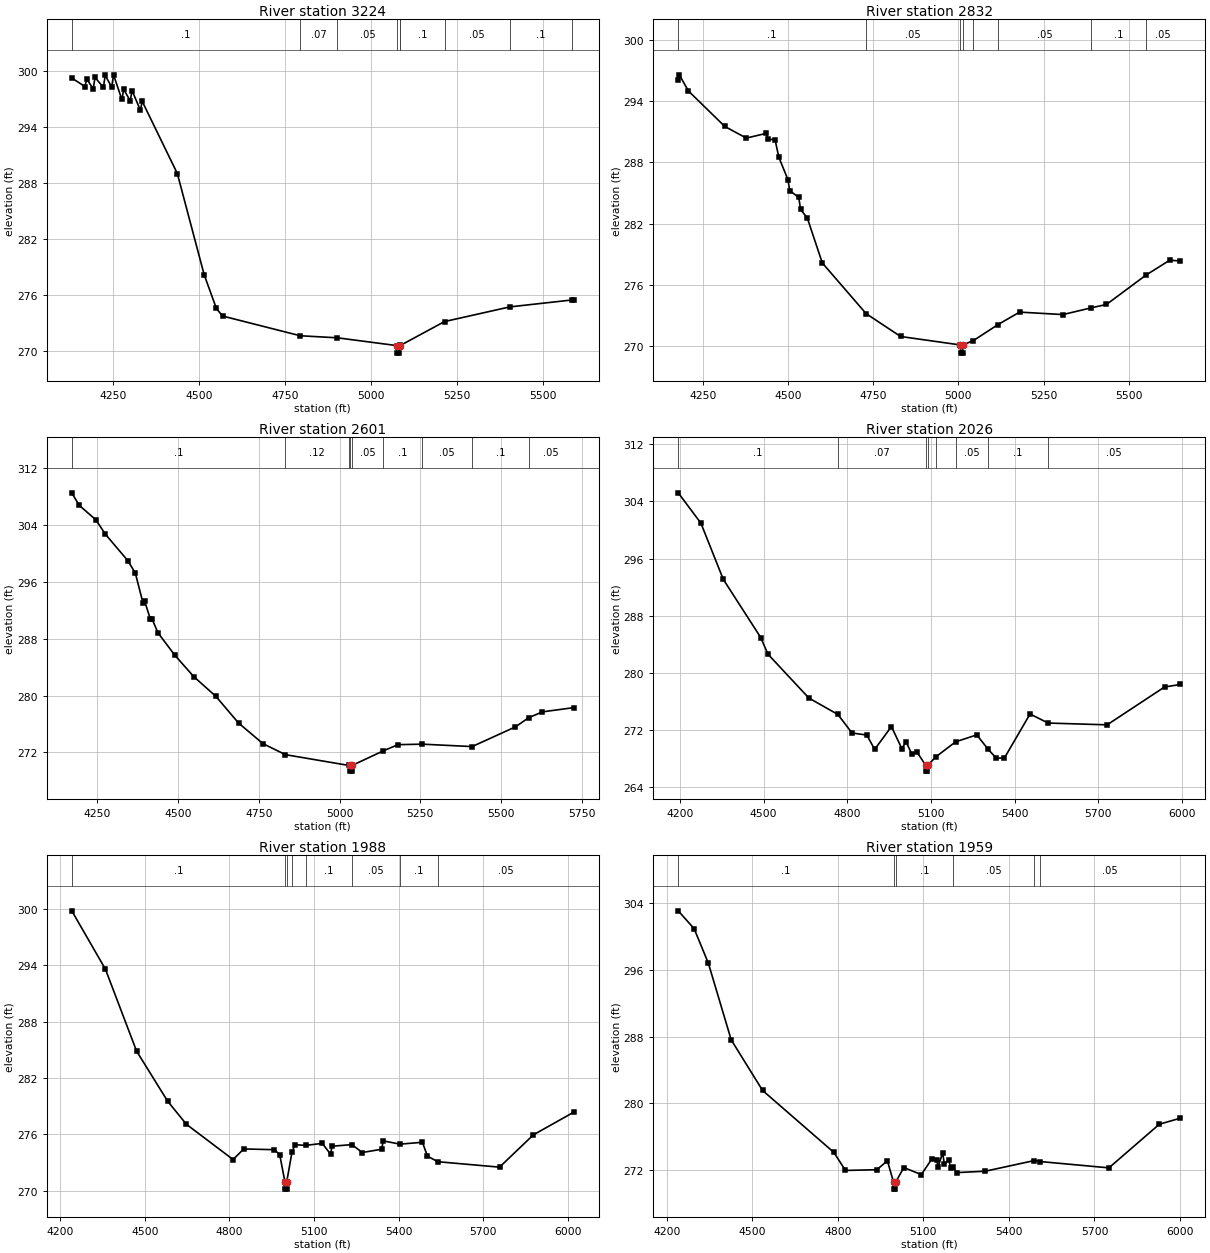
Type RM Length L Ch R = 1 ,3224    ,392,392,392
BEGIN DESCRIPTION:
Mapping XS cfa8bf95
END DESCRIPTION:
XS GIS Cut Line= 3
      2119834.48     13404394.67      2119501.14     13403567.21
      2119386.56     13403012.71
#Sta/Elev= 30
  4131.2  299.28  4169.3  298.37  4174.7  299.16  4193.4  298.13  4198.8  299.34
    4223  298.28  4228.4  299.56  4247.1  298.31  4252.5  299.62  4276.7  296.98
  4282.1  298.07  4300.9  296.83  4306.3  297.94  4330.4  295.84  4335.8  296.78
  4437.8  289.05  4515.7  278.22  4551.3   274.6  4569.4  273.79  4794.9  271.68
  4902.6  271.46  5076.7  270.62  5077.2  269.82  5082.8  269.82  5083.3  270.62
  5085.4  270.64  5213.9   273.2  5403.4  274.77  5583.7  275.51  5589.5  275.56
#Mann= 9 ,-1 , 0
  4131.2      .1       0  4794.9     .07       0  4902.6     .05       0
  5076.7    .033       0  5083.3     .05       0  5085.4      .1       0
  5213.9     .05       0  5403.4      .1       0  5583.7     .05       0
Bank Sta=5076.7,5083.3
XS Rating Curve= 0 ,0
Exp/Cntr=0.3,0.1

Type RM Length L Ch R = 1 ,2832    ,231,231,231
BEGIN DESCRIPTION:
Mapping XS 3044eca8
END DESCRIPTION:
XS GIS Cut Line= 2
      2120150.44     13404314.76      2119692.12     13402915.51
#Sta/Elev= 30
  4178.4  296.05  4181.6  296.58  4208.2     295  4314.9  291.52  4378.1  290.38
  4436.4  290.84  4441.6  290.27  4462.3  290.22  4473.5  288.49  4500.1  286.31
  4505.3  285.23  4531.9  284.56  4537.2  283.38    4557  282.54  4600.9  278.14
  4729.4  273.17  4830.6  270.93  5006.1   270.1  5006.6   269.3  5012.2   269.3
  5012.7   270.1  5044.1  270.53  5116.2   272.1  5179.4  273.32  5306.8  273.08
  5389.4  273.74  5434.2  274.07  5550.2  276.95  5619.8  278.41  5650.8  278.33
#Mann= 8 ,-1 , 0
  4178.4      .1       0  4729.4     .05       0  5006.1    .033       0
  5012.7     .05       0  5044.1      .1       0  5116.2     .05       0
  5389.4      .1       0  5550.2     .05       0
Bank Sta=5006.1,5012.7
XS Rating Curve= 0 ,0
Exp/Cntr=0.3,0.1

Type RM Length L Ch R = 1 ,2601    ,575,575,575
BEGIN DESCRIPTION:
Mapping XS ebb8d268
END DESCRIPTION:
XS GIS Cut Line= 2
      2120459.46     13404280.04      2119831.03     13402859.98
#Sta/Elev= 30
  4171.8  308.57  4194.5  306.82  4246.5  304.76  4275.7  302.74  4345.1  299.02
  4368.4  297.26  4391.7  293.11  4397.2  293.31    4415  290.74  4420.5  290.76
  4438.3  288.85  4490.3   285.7  4549.1  282.67  4617.7  279.88  4687.6  276.13
  4762.9  273.23  4832.6  271.67  5028.9  270.15  5032.2  270.15  5032.7  269.35
  5038.3  269.35  5038.8  270.15    5135   272.2  5180.8  273.08  5255.9  273.15
  5410.2  272.81  5544.2  275.59  5584.8  276.87  5627.3   277.7  5724.7   278.3
#Mann= 9 ,-1 , 0
  4171.8      .1       0  4832.6     .12       0  5028.9     .05       0
  5032.2     .07       0  5038.8     .05       0    5135      .1       0
  5255.9     .05       0  5410.2      .1       0  5584.8     .05       0
Bank Sta=5032.2,5038.8
XS Rating Curve= 0 ,0
Exp/Cntr=0.3,0.1

Type RM Length L Ch R = 1 ,2026    ,38,38,38
BEGIN DESCRIPTION:
Mapping XS a428d283
END DESCRIPTION:
XS GIS Cut Line= 6
      2120633.09     13404186.27      2120692.12     13403412.01
      2120650.45     13403346.04      2120563.64     13403304.37
      2120275.45     13403283.54      2119921.47     13402849.74
#Sta/Elev= 30
  4193.9   305.2  4275.3  300.95  4355.4  293.09    4490  284.93  4515.7  282.61
  4662.5  276.47  4766.6  274.17  4817.2  271.58  4870.3  271.29  4898.4  269.28
  4958.5  272.48  4995.8   269.4  5011.1  270.34  5032.3  268.57  5049.5  268.96
  5081.6  267.04  5082.1  266.24  5087.7  266.24  5088.2  267.04  5117.7  268.23
  5188.6  270.34  5264.5  271.31  5304.5  269.35  5334.8  268.04  5364.1   268.1
  5455.8  274.24  5520.6  272.97  5732.2  272.72  5938.2  278.02  5994.7  278.37
#Mann= 8 ,-1 , 0
  4193.9      .1       0  4766.6     .07       0  5081.6     .07       0
  5088.2     .07       0  5117.7      .1       0  5188.6     .05       0
  5304.5      .1       0  5520.6     .05       0
Bank Sta=5081.6,5088.2
XS Rating Curve= 0 ,0
Exp/Cntr=0.3,0.1

Type RM Length L Ch R = 1 ,1988    ,29,29,29
BEGIN DESCRIPTION:
Mapping XS 2367a5ff
END DESCRIPTION:
XS GIS Cut Line= 6
       2120681.7     13404134.23        2120706.     13403592.57
      2120733.78     13403436.32      2120674.75     13403283.54
      2120303.23     13403241.87      2119952.53     13402835.62
#Sta/Elev= 30
  4241.6   299.8  4360.9  293.58  4471.1  284.87  4581.2  279.53    4648  277.06
  4813.3  273.31    4851  274.44  4959.2  274.36  4978.4  273.84  4996.8  270.96
  4997.3  270.16    5003  270.16  5003.5  270.96  5021.8  274.07  5032.3  274.89
  5070.3  274.82  5129.4  275.03  5158.7  273.88  5163.9  274.73  5234.4   274.9
    5271  274.06    5340  274.41  5345.1   275.3  5404.8  274.95  5484.1  275.15
  5502.1  273.67  5538.7  273.08  5757.4   272.5  5877.3  275.94  6020.8  278.36
#Mann= 8 ,-1 , 0
  4241.6      .1       0  4996.8     .07       0  5003.5      .1       0
  5021.8     .07       0  5070.3      .1       0  5234.4     .05       0
  5404.8      .1       0  5538.7     .05       0
Bank Sta=4996.8,5003.5
XS Rating Curve= 0 ,0
Exp/Cntr=0.3,0.1

Type RM Length L Ch R = 1 ,1959    ,350,350,350
BEGIN DESCRIPTION:
Mapping XS 6ceb7a9c
END DESCRIPTION:
XS GIS Cut Line= 6
       2120744.2     13404130.74      2120765.03     13403446.74
      2120730.31     13403293.96      2120601.84     13403221.04
      2120358.78     13403200.21      2119994.21     13402821.74
#Sta/Elev= 30
  4240.1   303.1  4295.8  300.96  4345.8  296.81  4425.8  287.63  4535.8  281.56
  4786.1  274.12  4826.6  271.96  4936.8  272.05  4973.7  273.12  4995.5  270.52
    4996  269.72  5001.7  269.72  5002.2  270.52  5031.2  272.31  5092.6  271.46
  5130.1  273.37    5146  273.25  5151.7  272.41  5167.6  274.09  5173.4  272.71
  5189.2  273.25    5195  272.24  5204.3  272.39  5216.6   271.7  5317.2  271.87
  5489.3  273.15  5508.8  273.03  5750.6  272.27  5927.3   277.5    6001  278.23
#Mann= 6 ,-1 , 0
  4240.1      .1       0  4995.5     .07       0  5002.2      .1       0
  5204.3     .05       0  5489.3      .1       0  5508.8     .05       0
Bank Sta=4995.5,5002.2
XS Rating Curve= 0 ,0
Exp/Cntr=0.3,0.1

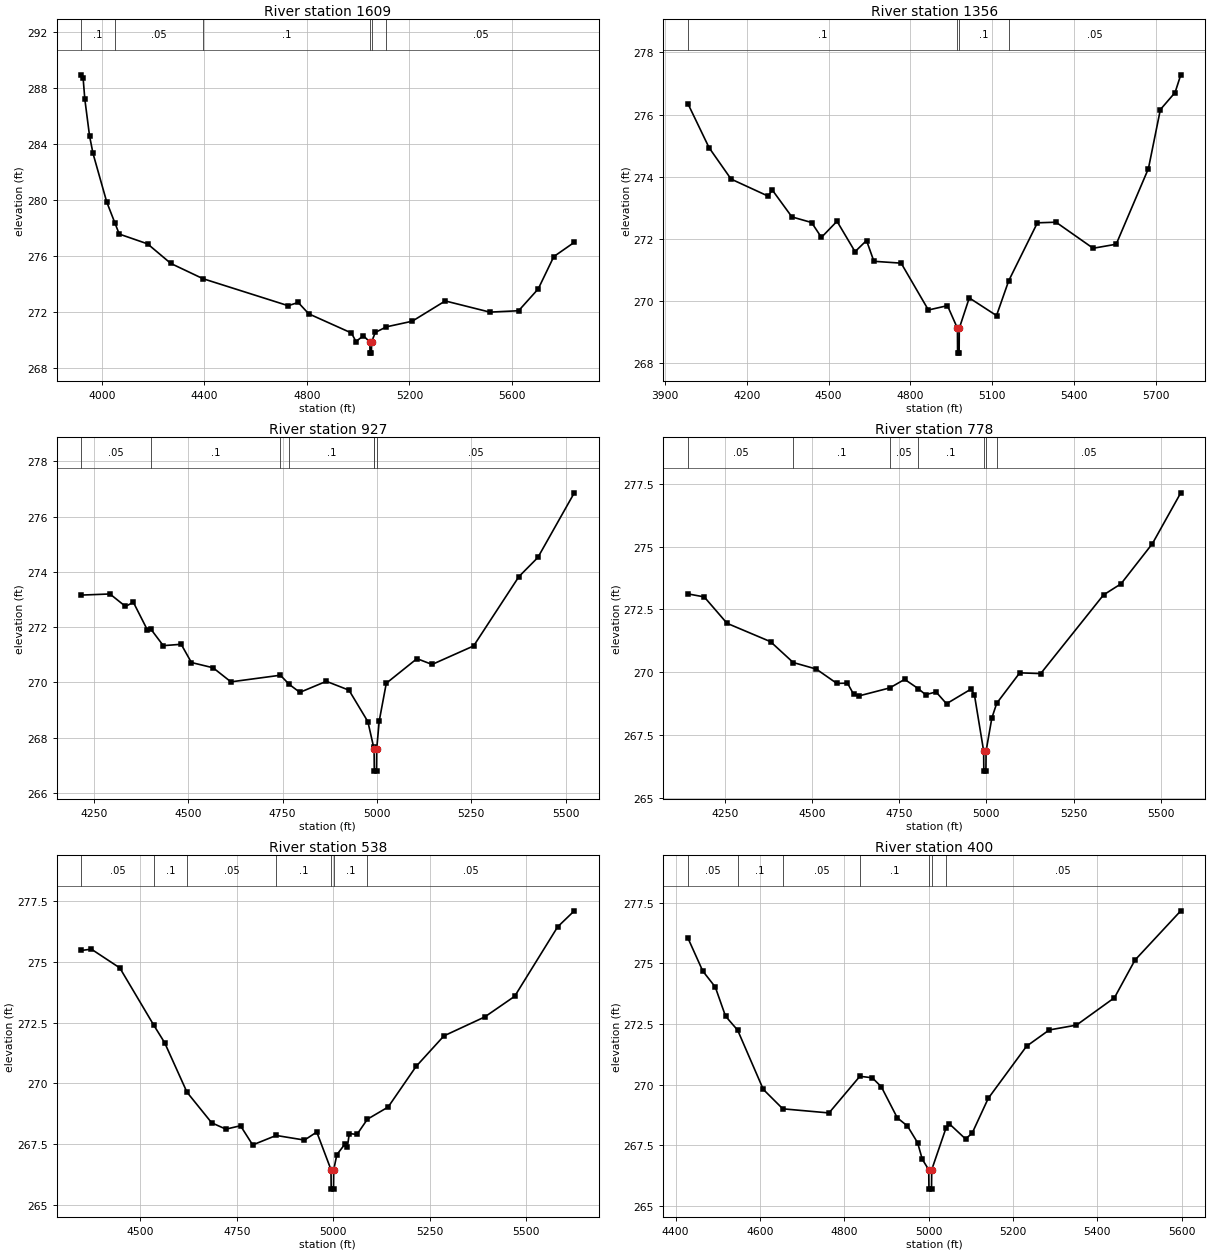
Type RM Length L Ch R = 1 ,1609    ,253,253,253
BEGIN DESCRIPTION:
Mapping XS 2c41f7d4
END DESCRIPTION:
XS GIS Cut Line= 3
      2121907.37     13403451.94      2120988.12     13403108.19
      2120126.17       13402728.
#Sta/Elev= 30
  3920.1  288.93  3926.8  288.67  3933.3  287.19  3951.8  284.56  3965.3  283.31
  4018.7  279.85  4050.1  278.37  4067.6  277.55  4178.1  276.85  4268.9  275.45
  4394.4  274.36  4726.9  272.43  4766.1  272.66  4807.1  271.85  4973.7  270.48
  4991.5  269.87  5020.3  270.28  5045.7  269.84  5046.2  269.04  5051.9  269.04
  5052.4  269.84    5067  270.52  5110.6  270.92    5211  271.32  5339.9  272.77
    5514  271.97  5626.3  272.07  5702.8  273.63  5763.6  275.94  5843.6  276.96
#Mann= 6 ,-1 , 0
  3920.1      .1       0  4050.1     .05       0  4394.4      .1       0
  5045.7     .07       0  5052.4      .1       0  5110.6     .05       0
Bank Sta=5045.7,5052.4
XS Rating Curve= 0 ,0
Exp/Cntr=0.3,0.1

Type RM Length L Ch R = 1 ,1356    ,429,429,429
BEGIN DESCRIPTION:
Mapping XS 2c2219e8
END DESCRIPTION:
XS GIS Cut Line= 4
      2121837.07     13403191.52      2121282.39     13402824.34
      2120633.96     13402824.34      2120175.66     13402636.86
#Sta/Elev= 30
  3983.4  276.35  4061.2  274.93  4141.8  273.92  4277.9  273.37  4292.9  273.57
  4365.1   272.7  4437.3  272.52  4473.4  272.04  4530.6  272.56  4596.8  271.58
  4638.9  271.94    4666  271.27    4766  271.21    4866   269.7    4936  269.84
  4972.6  269.11  4973.1  268.31  4978.8  268.31  4979.3  269.11    5016  270.09
    5116  269.52  5160.6  270.64    5266  272.51  5334.3  272.53  5470.6  271.69
  5555.2  271.82  5673.5  274.26  5717.3  276.16  5771.3  276.71  5792.2  277.28
#Mann= 4 ,-1 , 0
  3983.4      .1       0  4972.6     .07       0  4979.3      .1       0
  5160.6     .05       0
Bank Sta=4972.6,4979.3
XS Rating Curve= 0 ,0
Exp/Cntr=0.3,0.1

Type RM Length L Ch R = 1 ,927     ,149,149,149
BEGIN DESCRIPTION:
Mapping XS ae951e3a
END DESCRIPTION:
XS GIS Cut Line= 3
      2121498.58      13402730.6      2120949.06     13402600.38
      2120208.46      13402569.2
#Sta/Elev= 30
  4217.1  273.16  4292.7   273.2  4333.8  272.75  4354.7   272.9  4391.8   271.9
  4400.4  271.94    4434  271.33  4481.4  271.38  4508.5  270.72  4565.9  270.53
  4613.2  270.02  4744.2  270.26  4767.6  269.93  4795.9  269.64    4866  270.04
    4926  269.72  4976.1  268.58  4991.5  267.65  4992.6  267.59  4993.1  266.79
    4999  266.79  4999.5  267.59  5006.1   268.6  5024.9  269.97  5106.2  270.86
  5146.2  270.65  5256.3  271.32  5376.4  273.83  5426.5  274.52  5523.1  276.86
#Mann= 7 ,-1 , 0
  4217.1     .05       0  4400.4      .1       0  4744.2     .05       0
  4767.6      .1       0  4991.5     .05       0  4992.6     .03       0
  4999.5     .05       0
Bank Sta=4992.6,4999.5
XS Rating Curve= 0 ,0
Exp/Cntr=0.3,0.1

Type RM Length L Ch R = 1 ,778     ,240,240,240
BEGIN DESCRIPTION:
Mapping XS 3ad40324
END DESCRIPTION:
XS GIS Cut Line= 4
      2121568.89     13402639.46      2121094.89     13402446.74
      2120631.35     13402451.94      2120193.83     13402475.38
#Sta/Elev= 30
  4144.2  273.12    4191     273  4256.4  271.95  4381.1  271.22  4446.2  270.39
  4512.3  270.13  4571.2  269.56  4601.8  269.57  4619.3  269.13  4634.2  269.06
  4723.1  269.38  4765.8  269.72  4804.9  269.35  4825.8  269.11  4855.8  269.22
  4885.8  268.75  4955.8  269.33  4965.8  269.11  4992.3  266.87  4992.8  266.07
  4998.8  266.07  4999.3  266.87  5015.8  268.18  5029.8  268.77  5095.8  269.98
  5155.9  269.95  5336.1  273.08  5386.2  273.52  5476.3  275.12  5557.6  277.14
#Mann= 7 ,-1 , 0
  4144.2     .05       0  4446.2      .1       0  4723.1     .05       0
  4804.9      .1       0  4992.3     .07       0  4999.3      .1       0
  5029.8     .05       0
Bank Sta=4992.3,4999.3
XS Rating Curve= 0 ,0
Exp/Cntr=0.3,0.1

Type RM Length L Ch R = 1 ,538     ,138,138,138
BEGIN DESCRIPTION:
Mapping XS 0826a094
END DESCRIPTION:
XS GIS Cut Line= 3
      2121370.91     13401985.81      2121045.41     13402183.71
      2120183.47      13402433.7
#Sta/Elev= 30
  4347.1  275.47    4373  275.52  4446.6  274.75  4534.8  272.39  4562.9  271.67
  4620.9  269.63    4685  268.37  4721.8  268.11  4759.7  268.25  4791.3  267.46
  4852.2  267.85  4925.6  267.66  4957.5  267.99  4994.4  266.44  4994.9  265.64
    5001  265.64  5001.5  266.44  5009.6  267.06  5030.4  267.49  5036.7  267.36
  5041.9  267.93  5061.7  267.89  5088.9  268.52  5142.6  269.02    5215  270.69
  5287.3  271.95  5393.2  272.73  5470.8  273.58  5582.3  276.44  5625.5   277.1
#Mann= 7 ,-1 , 0
  4347.1     .05       0  4534.8      .1       0  4620.9     .05       0
  4852.2      .1       0  4994.4     .07       0  5001.5      .1       0
  5088.9     .05       0
Bank Sta=4994.4,5001.5
XS Rating Curve= 0 ,0
Exp/Cntr=0.3,0.1

Type RM Length L Ch R = 1 ,400     ,253,253,253
BEGIN DESCRIPTION:
Mapping XS 9c94010b
END DESCRIPTION:
XS GIS Cut Line= 2
      2121251.12     13401936.33       2120165.2     13402368.61
#Sta/Elev= 30
  4429.2  276.05  4464.4  274.69  4494.1  274.03  4518.4  272.83  4547.2  272.25
    4608  269.81  4654.2  269.01  4763.8  268.84    4837  270.35  4866.3  270.29
  4887.8  269.92  4925.7  268.64  4949.9   268.3    4974  267.61    4985  266.93
  5000.3   266.5  5000.8   265.7  5006.9   265.7  5007.4   266.5  5040.9   268.2
  5049.3  268.39  5087.5  267.77  5103.1     268  5141.4  269.44  5232.3  271.59
  5286.1  272.26  5350.7  272.46  5440.8  273.59  5489.4  275.14    5598  277.17
#Mann= 7 ,-1 , 0
  4429.2     .05       0  4547.2      .1       0  4654.2     .05       0
    4837      .1       0  5000.3     .07       0  5007.4      .1       0
  5040.9     .05       0
Bank Sta=5000.3,5007.4
XS Rating Curve= 0 ,0
Exp/Cntr=0.3,0.1

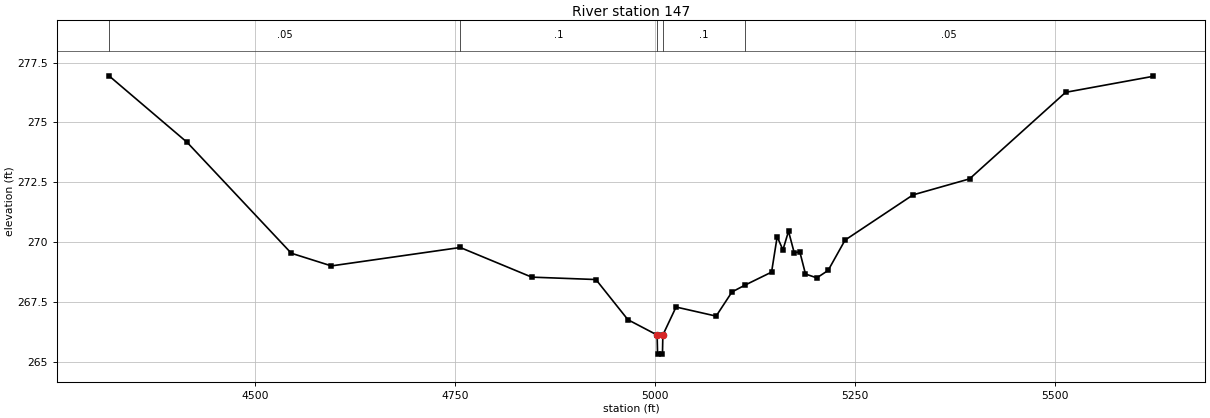
Type RM Length L Ch R = 1 ,147     ,0,0,0
BEGIN DESCRIPTION:
UNT 008 in La Jarita Watershed 1.0
END DESCRIPTION:
XS GIS Cut Line= 3
      2121282.38     13401899.86      2120519.37     13401949.34
      2120139.59     13402334.33
#Sta/Elev= 30
  4317.5  276.95  4415.1  274.17  4545.4  269.53  4595.5     269  4756.6  269.77
    4846  268.53  4926.2  268.43  4966.2  266.75  5002.7  266.11  5003.3  265.31
  5009.4  265.31  5009.9  266.11  5026.4  267.28  5076.5   266.9  5096.3  267.91
  5112.2  268.19  5145.8  268.74  5152.8  270.22    5160  269.67    5167  270.45
  5174.1  269.55  5181.1  269.59  5188.2  268.66  5202.4   268.5  5216.5  268.81
  5237.7  270.08  5322.6  271.97  5393.3  272.64  5513.4  276.26  5622.9  276.93
#Mann= 5 ,-1 , 0
  4317.5     .05       0  4756.6      .1       0  5002.7     .07       0
  5009.9      .1       0  5112.2     .05       0
Bank Sta=5002.7,5009.9
XS Rating Curve= 0 ,0
Exp/Cntr=0.3,0.1
LCMann Table=0

Chan Stop Cuts=-1
Use User Specified Reach Order=0
Composite Channel Slope=5