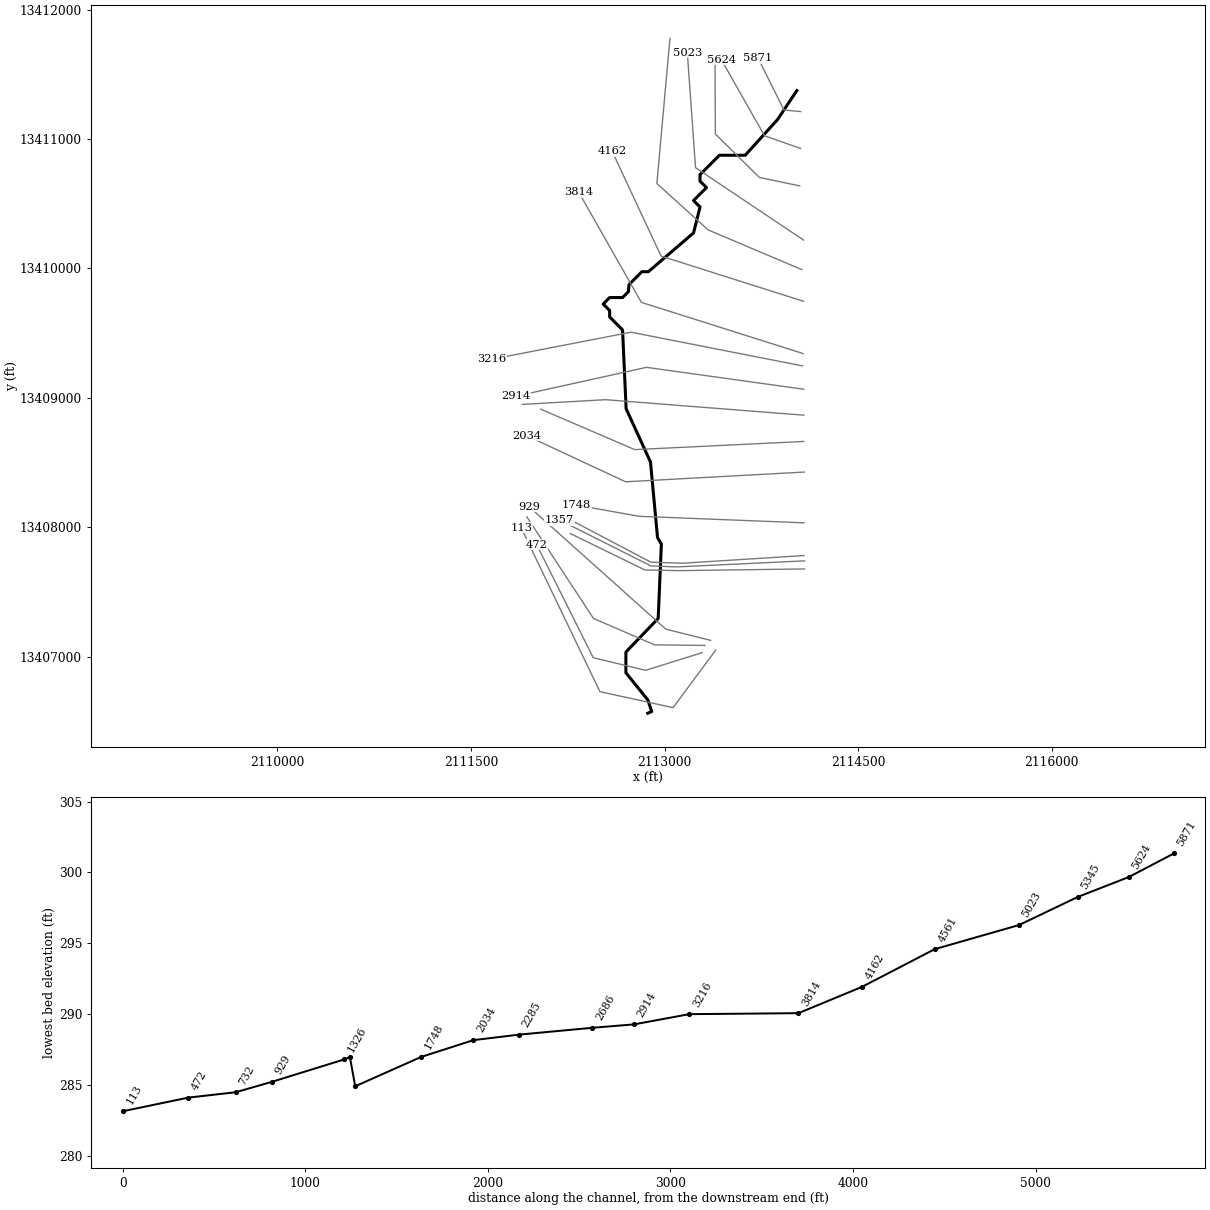
--- UNT 011 in La Jarita Watershed.prj (project) ---

Proj Title=UNT 011 in La Jarita Watershed Base Level Engineering
Current Plan=p01
Default Exp/Contr=0.3,0.1
English Units
Geom File=g01
Flow File=f01
Plan File=p01
BEGIN DESCRIPTION:
UNT 011 in La Jarita Watershed
END DESCRIPTION:

--- UNT 011 in La Jarita Watershed.p01 (plan) ---

Plan Title=Multiple Run
Short Identifier=Multiple
Geom File=g01
Flow File=f01
Subcritical Flow
K Sum by GR= 0
Std Step Tol= 0.01
Critical Tol= 0.01
Num of Std Step Trials= 20
Max Error Tol= 0.3
Flow Tol Ratio= 0.001
Split Flow NTrial= 30
Split Flow Tol= 0.02
Split Flow Ratio= 0.02
Log Output Level= 0
Friction Slope Method= 1
Unsteady Friction Slope Method= 2
Unsteady Bridges Friction Slope Method= 1
Parabolic Critical Depth
Global Vel Dist=  1 , 1 , 1
Global Log Level= 0
CheckData=True
Encroach Param= -1, 0, 0, 0
BEGIN DESCRIPTION:
Multiple Run
END DESCRIPTION:

--- UNT 011 in La Jarita Watershed.f01 (steady flow) ---

Flow Title=Multiple
Number of Profiles=7
Profile Names=10-year,25-year,50-year,1pct_min,100-year,1pct_plu,500-year
River Rch & RM= UNT 011 in La Ja,Reach-1,5871
     127     168     200     119     237     473     338
River Rch & RM= UNT 011 in La Ja,Reach-1,3216
     164     219     263     157     314     627     455
River Rch & RM= UNT 011 in La Ja,Reach-1,113
     412     571     701     428     853    1702    1284
Boundary for River Rch & Prof#=UNT 011 in La Ja,Reach-1,1
Up Type=0
Dn Type=3
Dn Slope=0.005
Boundary for River Rch & Prof#=UNT 011 in La Ja,Reach-1,2
Up Type=0
Dn Type=3
Dn Slope=0.005
Boundary for River Rch & Prof#=UNT 011 in La Ja,Reach-1,3
Up Type=0
Dn Type=3
Dn Slope=0.005
Boundary for River Rch & Prof#=UNT 011 in La Ja,Reach-1,4
Up Type=0
Dn Type=3
Dn Slope=0.005
Boundary for River Rch & Prof#=UNT 011 in La Ja,Reach-1,5
Up Type=0
Dn Type=3
Dn Slope=0.005
Boundary for River Rch & Prof#=UNT 011 in La Ja,Reach-1,6
Up Type=0
Dn Type=3
Dn Slope=0.005
Boundary for River Rch & Prof#=UNT 011 in La Ja,Reach-1,7
Up Type=0
Dn Type=3
Dn Slope=0.005

--- UNT 011 in La Jarita Watershed.g01 (geometry) ---

Geom Title=Existing Conditions

River Reach=UNT 011 in La Ja,Reach-1
Reach XY= 30
      2114025.00     13411375.00      2113875.00     13411150.65
      2113625.00     13410875.00      2113425.00     13410875.00
      2113275.00     13410725.00      2113275.00     13410675.00
      2113325.00     13410625.00      2113225.00     13410525.00
      2113275.00     13410475.00      2113225.00     13410275.00
      2112875.00     13409975.00      2112825.00     13409975.00
      2112725.00     13409875.00      2112720.26     13409820.26
      2112675.00     13409775.00      2112575.00     13409775.00
      2112525.00     13409725.00      2112575.00     13409675.00
      2112575.00     13409625.00      2112675.00     13409525.00
      2112702.58     13408915.72      2112891.39     13408503.39
      2112945.76     13407919.96      2112975.70     13407869.18
      2112950.80     13407294.54      2112700.80     13407034.54
      2112700.80     13406874.54      2112870.80     13406664.54
      2112900.80     13406574.54      2112870.23     13406561.89

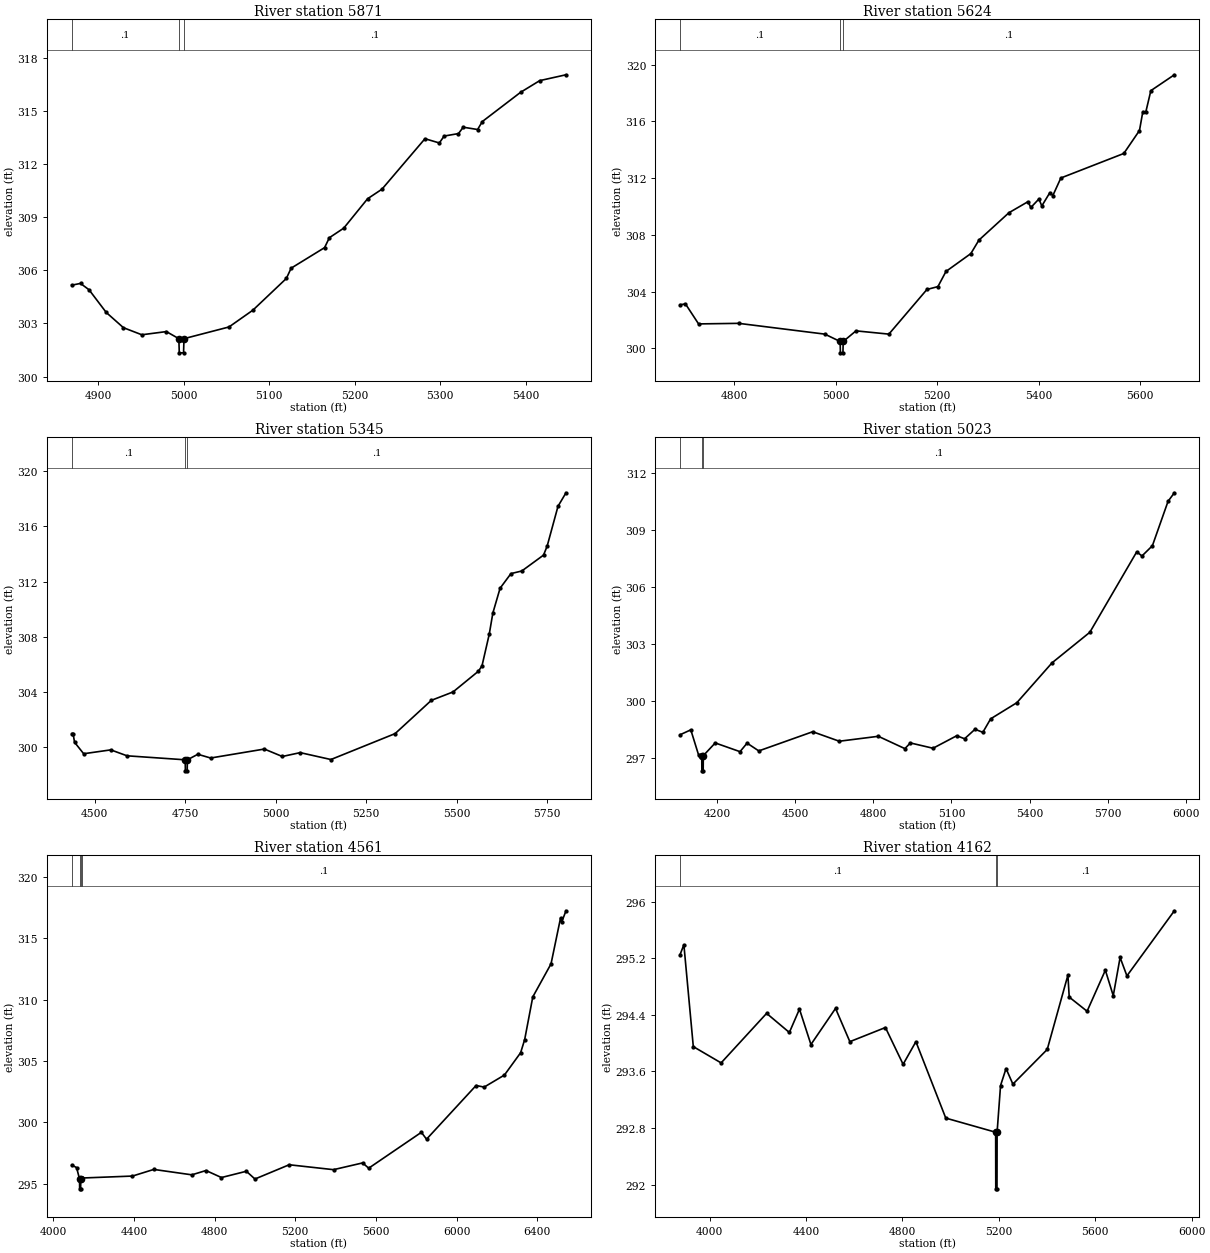
Type RM Length L Ch R = 1,5871,247,247,247
BEGIN DESCRIPTION:
UNT 011 in La Jarita Watershed 3.0
END DESCRIPTION:
XS GIS Cut Line= 3
      2114055.23     13411212.54      2113925.00     13411225.00
      2113725.02     13411624.97
#Sta/Elev= 30
  4868.9  305.16  4879.2  305.26  4889.2  304.90  4909.3  303.62  4929.4  302.76
  4950.9  302.36  4979.6  302.54  4994.2  302.14  4994.7  301.34  4999.7  301.34
  5000.2  302.14  5052.8  302.80  5080.8  303.75  5119.9  305.54  5125.5  306.12
  5164.6  307.28  5170.2  307.84  5187.0  308.38  5214.9  310.04  5231.7  310.58
  5282.0  313.43  5298.8  313.19  5304.4  313.58  5321.2  313.72  5326.7  314.08
  5343.5  313.95  5349.1  314.40  5393.8  316.05  5416.2  316.71  5446.9  317.04
#Mann=3,-1,0
  4868.9     0.1       0  4994.2    0.07       0  5000.2     0.1       0
Bank Sta=4994.2,5000.2
Exp/Cntr=0.3,0.1

Type RM Length L Ch R = 1,5624,279,279,279
BEGIN DESCRIPTION:
UNT 011 in La Jarita Watershed 2.0
END DESCRIPTION:
XS GIS Cut Line= 3
      2114053.97     13410927.81      2113775.00     13411025.00
      2113439.71     13411614.73
#Sta/Elev= 30
  4693.7  303.07  4704.4  303.13  4730.2  301.72  4809.1  301.76  4978.9  301.00
  5009.1  300.48  5009.6  299.68  5014.6  299.68  5015.1  300.48  5040.3  301.23
  5105.1  301.00  5180.1  304.15  5201.7  304.35  5217.6  305.42  5266.6  306.68
  5282.5  307.63  5341.6  309.56  5379.1  310.34  5384.8  309.93  5400.7  310.53
  5406.4  310.04  5422.3  310.98  5428.1  310.77  5443.9  312.01  5567.9  313.74
  5598.8  315.36  5605.4  316.69  5611.1  316.64  5621.2  318.17  5667.5  319.29
#Mann=3,-1,0
  4693.7     0.1       0  5009.1    0.07       0  5015.1     0.1       0
Bank Sta=5009.1,5015.1
Exp/Cntr=0.3,0.1

Type RM Length L Ch R = 1,5345,322,322,322
BEGIN DESCRIPTION:
Mapping XS 63aef6f6
END DESCRIPTION:
XS GIS Cut Line= 4
      2114047.40     13410638.33      2113734.95     13410703.42
      2113393.80     13411039.36      2113391.20     13411607.11
#Sta/Elev= 30
  4436.3  300.98  4440.1  300.98  4444.2  300.35  4469.4  299.52  4544.3  299.80
  4589.2  299.37  4749.9  299.08  4750.4  298.28  4755.4  298.28  4755.9  299.08
  4784.8  299.48  4820.2  299.21  4968.6  299.86  5018.2  299.32  5067.6  299.60
  5152.5  299.10  5329.9  300.98  5429.9  303.39  5489.9  304.00  5559.9  305.50
  5569.9  305.89  5589.9  308.18  5599.9  309.72  5619.9  311.52  5649.9  312.58
  5679.9  312.77  5739.9  313.92  5749.9  314.57  5779.9  317.46  5802.0  318.44
#Mann=3,-1,0
  4436.3     0.1       0  4749.9    0.07       0  4755.9     0.1       0
Bank Sta=4749.9,4755.9
Exp/Cntr=0.3,0.1

Type RM Length L Ch R = 1,5023,462,462,462
BEGIN DESCRIPTION:
Mapping XS fbfadc2e
END DESCRIPTION:
XS GIS Cut Line= 3
      2114077.40     13410219.04      2113240.16     13410778.94
      2113176.49     13411669.16
#Sta/Elev= 30
  4056.8  298.20  4098.1  298.46  4128.2  297.13  4140.2  297.10  4140.7  296.30
  4145.7  296.30  4146.2  297.10  4192.0  297.77  4287.3  297.31  4314.4  297.76
  4359.4  297.35  4566.6  298.36  4668.7  297.86  4818.8  298.12  4920.9  297.47
  4941.9  297.77  5029.0  297.49  5120.2  298.15  5150.3  297.99  5190.4  298.49
  5220.5  298.33  5250.5  299.04  5351.2  299.89  5486.4  301.99  5631.7  303.60
  5812.0  307.84  5832.0  307.62  5872.1  308.16  5932.3  310.50  5956.5  310.95
#Mann=3,-1,0
  4056.8     0.1       0  4140.2    0.07       0  4146.2     0.1       0
Bank Sta=4140.2,4146.2
Exp/Cntr=0.3,0.1

Type RM Length L Ch R = 1,4561,399,399,399
BEGIN DESCRIPTION:
Mapping XS 6db22b4d
END DESCRIPTION:
XS GIS Cut Line= 4
      2114063.59     13409991.11      2113339.11     13410297.17
      2112940.68     13410656.54      2113042.24     13411778.92
#Sta/Elev= 30
  4092.1  296.54  4116.3  296.33  4131.0  295.40  4131.5  294.60  4136.5  294.60
  4137.0  295.40  4141.9  295.48  4393.4  295.64  4499.0  296.18  4687.6  295.74
  4757.8  296.09  4834.3  295.52  4957.8  296.03  5000.4  295.40  5170.1  296.56
  5389.8  296.16  5534.1  296.71  5564.2  296.28  5825.3  299.20  5850.9  298.64
  6096.4  303.01  6136.5  302.88  6236.9  303.86  6317.3  305.68  6337.3  306.75
  6377.5  310.22  6467.9  312.91  6515.2  316.65  6520.2  316.29  6542.1  317.23
#Mann=4,-1,0
  4092.1    0.08       0  4131.0    0.07       0  4137.0    0.08       0
  4141.9     0.1       0
Bank Sta=4131,4137
Exp/Cntr=0.3,0.1

Type RM Length L Ch R = 1,4162,348,348,348
BEGIN DESCRIPTION:
Mapping XS 290d61b7
END DESCRIPTION:
XS GIS Cut Line= 3
      2114077.43     13409745.94      2112973.36     13410095.56
      2112594.76     13410904.33
#Sta/Elev= 30
  3877.1  295.25  3893.0  295.39  3932.1  293.95  4047.5  293.72  4236.3  294.42
  4330.7  294.15  4372.6  294.48  4420.2  293.98  4522.3  294.49  4581.7  294.02
  4729.3  294.22  4802.7  293.70  4855.8  294.02  4979.7  292.94  5186.7  292.74
  5187.2  291.94  5192.2  291.94  5192.7  292.74  5207.0  293.40  5229.8  293.64
  5258.2  293.42  5400.7  293.91  5486.5  294.96  5492.0  294.65  5566.1  294.45
  5641.9  295.03  5674.7  294.67  5703.1  295.21  5731.4  294.95  5928.2  295.87
#Mann=3,-1,0
  3877.1     0.1       0  5186.7    0.07       0  5192.7     0.1       0
Bank Sta=5186.7,5192.7
Exp/Cntr=0.3,0.1

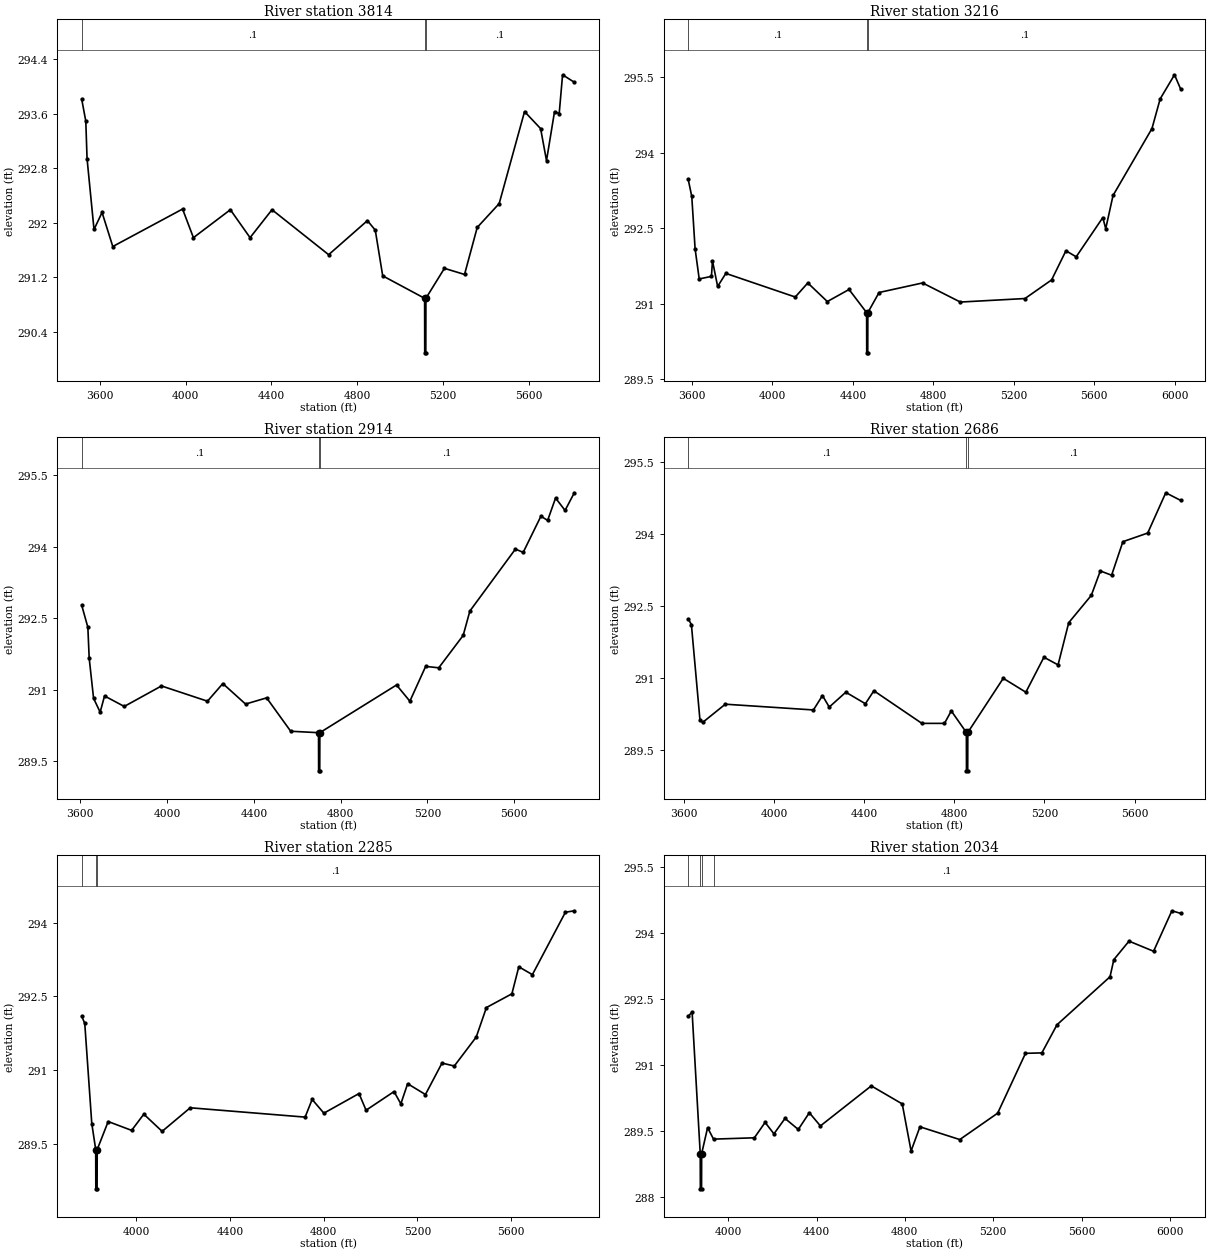
Type RM Length L Ch R = 1,3814,598,598,598
BEGIN DESCRIPTION:
Mapping XS 8b93573f
END DESCRIPTION:
XS GIS Cut Line= 3
      2114073.02     13409342.32      2112820.58     13409737.76
      2112334.87     13410590.90
#Sta/Elev= 30
  3515.9  293.81  3534.8  293.49  3540.7  292.94  3573.1  291.90  3610.6  292.15
  3660.6  291.65  3985.7  292.20  4036.3  291.78  4208.4  292.19  4300.2  291.78
  4402.4  292.19  4666.4  291.53  4847.0  292.03  4883.6  291.89  4918.2  291.22
  5113.5  290.89  5114.0  290.09  5119.0  290.09  5119.5  290.89  5205.8  291.33
  5299.5  291.24  5358.6  291.93  5460.9  292.28  5579.1  293.63  5654.0  293.38
  5681.4  292.91  5718.8  293.63  5740.5  293.60  5756.3  294.17  5811.0  294.06
#Mann=3,-1,0
  3515.9     0.1       0  5113.5    0.07       0  5119.5     0.1       0
Bank Sta=5113.5,5119.5
Exp/Cntr=0.3,0.1

Type RM Length L Ch R = 1,3216,302,302,302
BEGIN DESCRIPTION:
Mapping XS cb330bac
END DESCRIPTION:
XS GIS Cut Line= 3
      2114068.68     13409246.83      2112740.59     13409507.24
      2111664.25     13409298.92
#Sta/Elev= 30
  3580.8  293.47  3598.6  293.13  3615.1  292.09  3635.5  291.49  3696.4  291.54
  3701.5  291.85  3727.2  291.34  3768.0  291.60  4113.2  291.13  4175.6  291.41
  4272.7  291.04  4380.7  291.28  4468.1  290.82  4468.6  290.02  4473.7  290.02
  4474.2  290.82  4530.0  291.22  4746.3  291.41  4934.2  291.03  5255.6  291.10
  5388.0  291.47  5459.3  292.05  5510.3  291.93  5642.7  292.71  5657.2  292.49
  5693.6  293.15  5887.1  294.48  5927.9  295.07  5999.2  295.55  6030.5  295.26
#Mann=3,-1,0
  3580.8     0.1       0  4468.1    0.07       0  4474.2     0.1       0
Bank Sta=4468.1,4474.2
Exp/Cntr=0.3,0.1

Type RM Length L Ch R = 1,2914,228,228,228
BEGIN DESCRIPTION:
Mapping XS aa12d485
END DESCRIPTION:
XS GIS Cut Line= 3
      2114079.09     13409066.27      2112860.38     13409235.54
      2111844.79     13409011.59
#Sta/Elev= 30
  3606.7  292.77  3634.9  292.31  3641.1  291.66  3661.3  290.82  3691.6  290.53
  3711.8  290.87  3802.7  290.65  3974.3  291.08  4186.3  290.76  4257.0  291.13
  4361.8  290.70  4458.9  290.83  4569.9  290.13  4698.1  290.10  4698.6  289.30
  4703.7  289.30  4704.2  290.10  5057.7  291.10  5119.1  290.76  5191.9  291.49
  5252.2  291.46  5364.9  292.14  5395.6  292.65  5605.7  293.95  5641.4  293.88
  5723.3  294.64  5754.0  294.55  5790.7  295.02  5834.4  294.76  5877.1  295.13
#Mann=3,-1,0
  3606.7     0.1       0  4698.1    0.07       0  4704.2     0.1       0
Bank Sta=4698.1,4704.2
Exp/Cntr=0.3,0.1

Type RM Length L Ch R = 1,2686,401,401,401
BEGIN DESCRIPTION:
Mapping XS 34f50da3
END DESCRIPTION:
XS GIS Cut Line= 3
      2114079.15     13408865.74      2112542.67     13408985.54
      2111898.44     13408949.17
#Sta/Elev= 30
  3619.0  292.23  3633.2  292.11  3671.0  290.13  3683.3  290.07  3783.6  290.45
  4174.8  290.33  4215.0  290.63  4245.0  290.39  4318.6  290.70  4405.5  290.46
  4443.1  290.73  4656.3  290.05  4756.6  290.05  4786.7  290.31  4853.7  289.86
  4854.2  289.06  4859.6  289.06  4860.1  289.86  5017.4  290.99  5117.7  290.70
  5197.9  291.43  5260.7  291.27  5308.0  292.15  5408.2  292.72  5448.3  293.23
  5498.3  293.14  5548.4  293.84  5658.6  294.02  5738.7  294.86  5805.4  294.70
#Mann=3,-1,0
  3619.0     0.1       0  4853.7    0.07       0  4860.1     0.1       0
Bank Sta=4853.7,4860.1
Exp/Cntr=0.3,0.1

Type RM Length L Ch R = 1,2285,251,251,251
BEGIN DESCRIPTION:
Mapping XS 0579420b
END DESCRIPTION:
XS GIS Cut Line= 3
      2114077.85     13408662.62      2112769.50     13408599.53
      2112040.03     13408912.64
#Sta/Elev= 30
  3766.4  292.09  3779.3  291.95  3809.3  289.91  3826.1  289.38  3826.6  288.58
  3832.0  288.58  3832.5  289.38  3879.4  289.95  3979.5  289.77  4031.5  290.10
  4109.7  289.75  4229.8  290.23  4720.4  290.04  4750.4  290.40  4800.5  290.12
  4950.6  290.52  4980.7  290.18  5100.2  290.56  5129.2  290.31  5158.2  290.72
  5234.3  290.50  5305.0  291.14  5357.5  291.08  5451.2  291.67  5494.7  292.27
  5603.5  292.55  5633.0  293.10  5691.0  292.94  5832.0  294.21  5870.1  294.24
#Mann=3,-1,0
  3766.4     0.1       0  3826.1    0.07       0  3832.5     0.1       0
Bank Sta=3826.1,3832.5
Exp/Cntr=0.3,0.1

Type RM Length L Ch R = 1,2034,286,286,286
BEGIN DESCRIPTION:
Mapping XS 0029e77c
END DESCRIPTION:
XS GIS Cut Line= 3
      2114082.64     13408426.08      2112698.75     13408350.83
      2111933.25     13408706.91
#Sta/Elev= 30
  3819.0  292.11  3836.7  292.21  3873.5  288.99  3874.0  288.19  3879.4  288.19
  3879.9  288.99  3906.8  289.58  3933.7  289.32  4118.6  289.35  4167.2  289.70
  4207.2  289.44  4257.3  289.79  4317.4  289.54  4367.4  289.92  4417.5  289.62
  4647.9  290.53  4788.1  290.12  4828.1  289.05  4868.2  289.60  5048.5  289.31
  5220.1  289.91  5346.1  291.27  5420.2  291.28  5488.9  291.92  5728.8  293.01
  5746.1  293.40  5814.8  293.82  5926.0  293.59  6008.9  294.51  6049.2  294.45
#Mann=4,-1,0
  3819.0    0.08       0  3873.5    0.07       0  3879.9    0.08       0
  3933.7     0.1       0
Bank Sta=3873.5,3879.9
Exp/Cntr=0.3,0.1

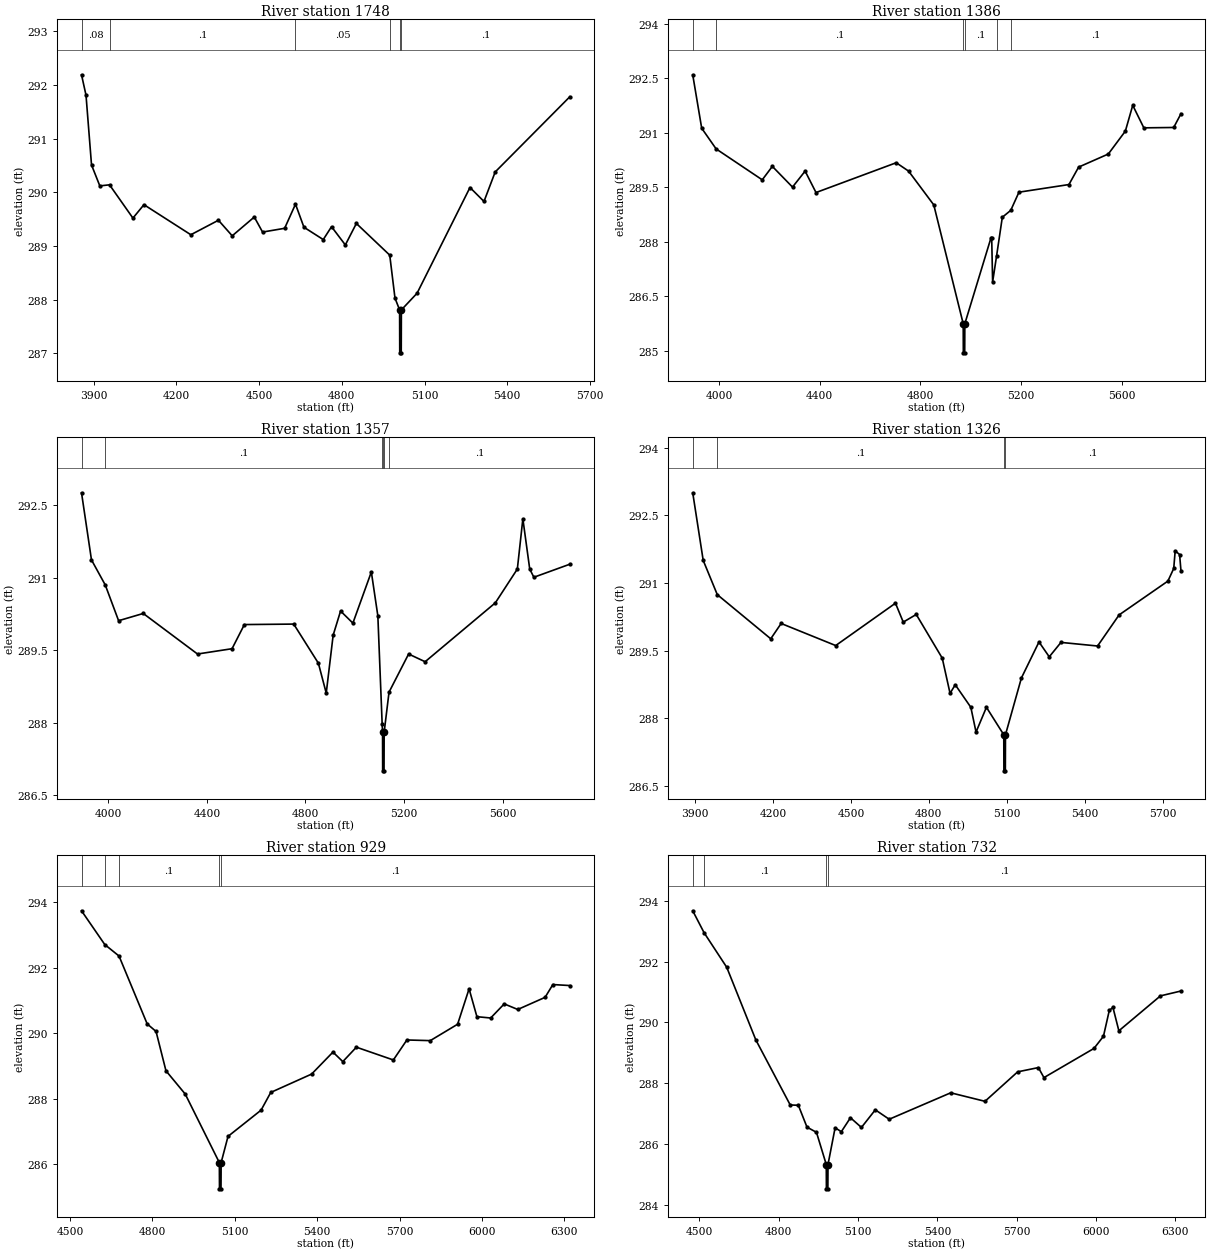
Type RM Length L Ch R = 1,1748,362,362,362
BEGIN DESCRIPTION:
Mapping XS b2cf0650
END DESCRIPTION:
XS GIS Cut Line= 3
      2114081.31     13408033.58      2112803.22     13408084.12
      2112318.57     13408170.66
#Sta/Elev= 30
  3855.5  292.19  3871.8  291.81  3891.8  290.51  3921.9  290.12  3957.1  290.14
  4042.0  289.52  4082.0  289.77  4252.1  289.21  4352.2  289.48  4402.2  289.19
  4482.3  289.54  4512.3  289.26  4592.4  289.33  4631.8  289.78  4662.4  289.35
  4732.5  289.12  4762.5  289.36  4812.6  289.02  4852.6  289.42  4973.7  288.83
  4992.7  288.03  5009.5  287.81  5010.0  287.01  5015.4  287.01  5015.9  287.81
  5072.8  288.12  5264.8  290.09  5315.6  289.83  5356.3  290.38  5626.9  291.78
#Mann=6,-1,0
  3855.5    0.08       0  3957.1     0.1       0  4631.8    0.05       0
  4973.7     0.1       0  5009.5    0.07       0  5015.9     0.1       0
Bank Sta=5009.5,5015.9
Exp/Cntr=0.3,0.1

Type RM Length L Ch R = 1,1386,29,29,29
BEGIN DESCRIPTION:
Mapping XS 2957b5cf
END DESCRIPTION:
XS GIS Cut Line= 4
      2114080.55     13407780.81      2113142.59     13407721.43
      2112895.20     13407729.24      2112229.29     13408078.53
#Sta/Elev= 30
  3895.6  292.59  3931.2  291.12  3988.6  290.55  4171.7  289.70  4211.8  290.07
  4291.9  289.50  4342.0  289.94  4385.2  289.35  4703.8  290.17  4752.9  289.94
  4853.0  289.01  4969.9  285.74  4970.4  284.94  4975.8  284.94  4976.3  285.74
  5080.5  288.11  5083.0  288.11  5086.7  286.89  5102.3  287.60  5125.2  288.67
  5158.7  288.86  5191.3  289.36  5389.8  289.57  5428.3  290.05  5546.2  290.41
  5613.9  291.04  5643.2  291.75  5687.3  291.13  5805.9  291.14  5834.9  291.52
#Mann=6,-1,0
  3895.6    0.08       0  3988.6     0.1       0  4969.9    0.07       0
  4976.3     0.1       0  5102.3    0.05       0  5158.7     0.1       0
Bank Sta=4969.9,4976.3
Exp/Cntr=0.3,0.1

Type RM Length L Ch R = 1,1357,31,31,31
BEGIN DESCRIPTION:
Mapping XS 1adeed89
END DESCRIPTION:
XS GIS Cut Line= 4
      2114085.31     13407739.66      2113093.11     13407692.79
      2112895.20     13407700.60      2112188.42     13408054.71
#Sta/Elev= 30
  3890.9  292.76  3931.3  291.37  3987.3  290.85  4041.4  290.11  4141.5  290.26
  4361.7  289.42  4501.9  289.53  4551.9  290.03  4752.2  290.04  4852.3  289.23
  4884.2  288.61  4912.3  289.81  4942.4  290.31  4992.4  290.06  5067.3  291.12
  5093.7  290.21  5111.2  287.97  5112.8  287.80  5113.3  287.00  5118.8  287.00
  5119.3  287.80  5139.1  288.63  5218.6  289.42  5285.6  289.26  5570.6  290.48
  5659.9  291.18  5682.3  292.22  5710.2  291.18  5727.0  291.01  5872.8  291.28
#Mann=6,-1,0
  3890.9    0.08       0  3987.3     0.1       0  5111.2    0.05       0
  5112.8    0.07       0  5119.3    0.05       0  5139.1     0.1       0
Bank Sta=5112.8,5119.3
Exp/Cntr=0.3,0.1

Type RM Length L Ch R = 1,1326,397,397,397
BEGIN DESCRIPTION:
Mapping XS 04c0488b
END DESCRIPTION:
XS GIS Cut Line= 4
      2114085.27     13407677.16      2113119.16     13407664.14
      2112848.32     13407669.35      2112270.82     13407950.30
#Sta/Elev= 30
  3891.3  293.00  3931.6  291.50  3985.8  290.74  4191.6  289.76  4231.6  290.10
  4441.6  289.61  4671.6  290.55  4701.6  290.13  4751.6  290.30  4851.7  289.33
  4881.7  288.55  4901.7  288.74  4961.7  288.24  4981.7  287.69  5021.7  288.24
  5088.5  287.63  5089.0  286.83  5094.5  286.83  5095.0  287.63  5156.3  288.89
  5224.0  289.69  5263.5  289.36  5308.6  289.68  5449.5  289.60  5532.4  290.29
  5720.1  291.04  5742.6  291.32  5748.2  291.71  5765.2  291.63  5770.6  291.26
#Mann=4,-1,0
  3891.3    0.08       0  3985.8     0.1       0  5088.5    0.07       0
  5095.0     0.1       0
Bank Sta=5088.5,5095
Exp/Cntr=0.3,0.1

Type RM Length L Ch R = 1,929,197,197,197
BEGIN DESCRIPTION:
Mapping XS dbf8b160
END DESCRIPTION:
XS GIS Cut Line= 3
      2113356.98     13407125.08      2113009.78     13407211.88
      2111950.77     13408158.04
#Sta/Elev= 30
  4541.8  293.73  4626.5  292.70  4678.4  292.35  4780.9  290.28  4813.2  290.05
  4849.3  288.85  4919.5  288.14  5043.7  286.05  5044.2  285.25  5049.7  285.25
  5050.2  286.05  5075.3  286.85  5195.7  287.65  5230.9  288.19  5379.7  288.75
  5457.4  289.42  5493.3  289.13  5542.7  289.57  5677.3  289.18  5726.6  289.79
  5811.8  289.77  5911.3  290.27  5953.1  291.35  5981.6  290.50  6031.7  290.46
  6081.0  290.89  6130.4  290.72  6229.8  291.09  6258.2  291.48  6319.8  291.45
#Mann=5,-1,0
  4541.8     0.1       0  4626.5    0.05       0  4678.4     0.1       0
  5043.7    0.07       0  5050.2     0.1       0
Bank Sta=5043.7,5050.2
Exp/Cntr=0.3,0.1

Type RM Length L Ch R = 1,732,260,260,260
BEGIN DESCRIPTION:
Mapping XS d67b22e0
END DESCRIPTION:
XS GIS Cut Line= 4
      2113313.56     13407086.02      2112922.98     13407090.36
      2112449.88     13407294.35      2111933.38     13408079.96
#Sta/Elev= 30
  4475.2  293.67  4518.0  292.95  4603.8  291.81  4713.8  289.42  4843.8  287.28
  4874.5  287.27  4907.2  286.55  4943.0  286.38  4980.1  285.32  4980.6  284.52
  4986.1  284.52  4986.6  285.32  5013.5  286.53  5037.0  286.40  5071.5  286.86
  5113.0  286.54  5165.5  287.12  5218.0  286.81  5450.6  287.68  5580.1  287.40
  5703.7  288.37  5782.0  288.51  5803.0  288.18  5992.1  289.14  6028.0  289.54
  6050.1  290.39  6063.9  290.49  6086.3  289.72  6243.5  290.87  6321.2  291.03
#Mann=4,-1,0
  4475.2    0.05       0  4518.0     0.1       0  4980.1    0.07       0
  4986.6     0.1       0
Bank Sta=4980.1,4986.6
Exp/Cntr=0.3,0.1

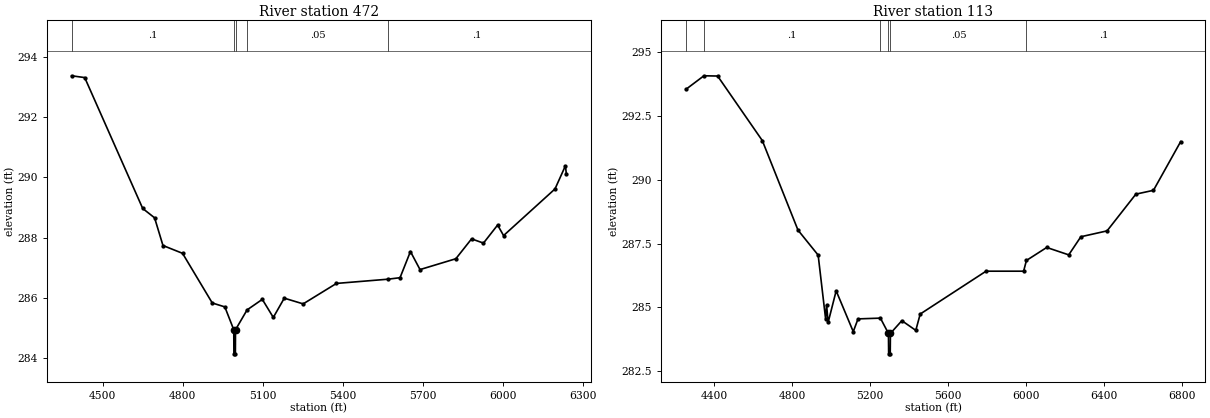
Type RM Length L Ch R = 1,472,359,359,359
BEGIN DESCRIPTION:
Mapping XS c5cab481
END DESCRIPTION:
XS GIS Cut Line= 4
      2113292.01     13407030.18      2112853.61     13406893.45
      2112447.79     13406991.11      2112009.70     13407865.13
#Sta/Elev= 30
  4383.6  293.38  4432.8  293.32  4650.2  288.97  4694.7  288.66  4726.1  287.74
  4799.5  287.48  4910.9  285.83  4958.0  285.70  4991.5  284.94  4992.0  284.14
  4997.5  284.14  4998.0  284.94  5041.4  285.60  5098.5  285.95  5139.7  285.35
  5180.8  285.99  5251.6  285.80  5376.4  286.48  5569.1  286.62  5614.7  286.67
  5653.7  287.54  5689.6  286.94  5823.9  287.30  5882.8  287.96  5927.5  287.82
  5980.5  288.42  6002.8  288.07  6195.6  289.62  6234.7  290.39  6237.9  290.13
#Mann=5,-1,0
  4383.6     0.1       0  4991.5    0.07       0  4998.0     0.1       0
  5041.4    0.05       0  5569.1     0.1       0
Bank Sta=4991.5,4998
Exp/Cntr=0.3,0.1

Type RM Length L Ch R = 1,113,0,0,0
BEGIN DESCRIPTION:
Mapping XS 3a9de95c
END DESCRIPTION:
XS GIS Cut Line= 4
      2113396.95     13407050.44      2113066.28     13406604.82
      2112499.88     13406728.52      2111889.22     13407995.70
#Sta/Elev= 30
  4254.2  293.55  4346.4  294.08  4416.8  294.07  4646.3  291.54  4829.6  288.03
  4933.2  287.05  4971.5  284.55  4976.6  285.09  4984.4  284.41  5025.7  285.65
  5113.5  284.05  5138.0  284.55  5253.0  284.58  5294.3  283.98  5295.3  283.18
  5303.4  283.18  5304.4  283.98  5363.1  284.48  5434.8  284.10  5457.4  284.74
  5795.7  286.42  5988.7  286.42  6003.0  286.84  6107.3  287.35  6220.4  287.06
  6282.7  287.77  6417.3  288.00  6565.3  289.44  6655.7  289.59  6795.5  291.50
#Mann=6,-1,0
  4254.2    0.05       0  4346.4     0.1       0  5253.0    0.05       0
  5294.3    0.07       0  5304.4    0.05       0  6003.0     0.1       0
Bank Sta=5294.3,5304.4
Exp/Cntr=0.3,0.1

Chan Stop Cuts=-1