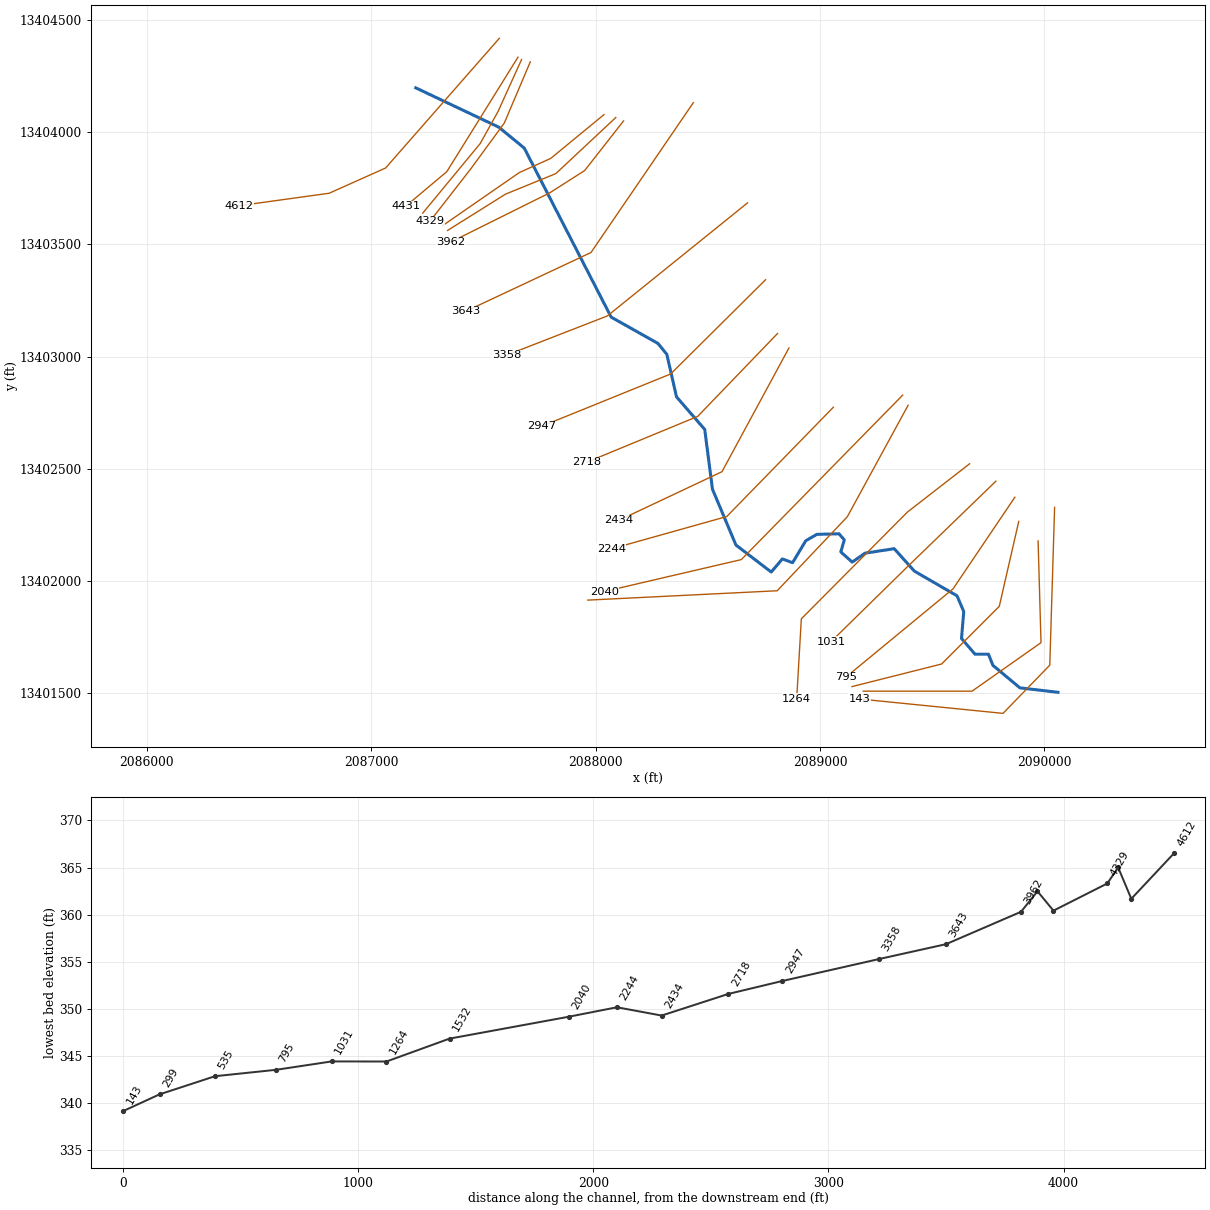
--- UNT 012 in La Jarita Watershed.prj (project) ---

Proj Title=UNT 012 in La Jarita Watershed Base Level Engineering
Current Plan=p01
Default Exp/Contr=0.3,0.1
English Units
Geom File=g01
Flow File=f01
Plan File=p01
Y Axis Title=Elevation
X Axis Title(PF)=Main Channel Distance
X Axis Title(XS)=Station
BEGIN DESCRIPTION:
UNT 012 in La Jarita Watershed
END DESCRIPTION:
DSS Export Rating Curves= 0
DSS Export Rating Curve Sorted= 0
DSS Export Volume Flow Curves= 0
DXF OffsetX= 0
DXF OffsetY= 0
DXF ScaleX= 1
DXF ScaleY= 10

--- UNT 012 in La Jarita Watershed.p01 (plan) ---

Plan Title=Multiple Run
Short Identifier=Multiple
Geom File=g01
Flow File=f01
Subcritical Flow
K Sum by GR= 0
Std Step Tol= 0.01
Critical Tol= 0.01
Num of Std Step Trials= 20
Max Error Tol= 0.3
Flow Tol Ratio= 0.001
Split Flow NTrial= 30
Split Flow Tol= 0.02
Split Flow Ratio= 0.02
Log Output Level= 0
Friction Slope Method= 1
Unsteady Friction Slope Method= 2
Unsteady Bridges Friction Slope Method= 1
Parabolic Critical Depth
Global Vel Dist=  1 , 1 , 1
Global Log Level= 0
CheckData=True
Encroach Param= -1, 0, 0, 0
BEGIN DESCRIPTION:
Multiple Run
END DESCRIPTION:

--- UNT 012 in La Jarita Watershed.f01 (steady flow) ---

Flow Title=Multiple
Program Version=5.05
Number of Profiles= 7
Profile Names=10-year,25-year,50-year,1pct_min,100-year,1pct_plu,500-year
River Rch & RM=UNT 012 in La Ja,Reach-1         ,4612
     112     148     177     106     211     421     304
River Rch & RM=UNT 012 in La Ja,Reach-1         ,1264
     189     259     316     193     384     767     577
River Rch & RM=UNT 012 in La Ja,Reach-1         ,143
     386     548     685     426     849    1695    1329
Boundary for River Rch & Prof#=UNT 012 in La Ja,Reach-1         , 1
Up Type= 0
Dn Type= 3
Dn Slope=0.005
Boundary for River Rch & Prof#=UNT 012 in La Ja,Reach-1         , 2
Up Type= 0
Dn Type= 3
Dn Slope=0.005
Boundary for River Rch & Prof#=UNT 012 in La Ja,Reach-1         , 3
Up Type= 0
Dn Type= 3
Dn Slope=0.005
Boundary for River Rch & Prof#=UNT 012 in La Ja,Reach-1         , 4
Up Type= 0
Dn Type= 3
Dn Slope=0.005
Boundary for River Rch & Prof#=UNT 012 in La Ja,Reach-1         , 5
Up Type= 0
Dn Type= 3
Dn Slope=0.005
Boundary for River Rch & Prof#=UNT 012 in La Ja,Reach-1         , 6
Up Type= 0
Dn Type= 3
Dn Slope=0.005
Boundary for River Rch & Prof#=UNT 012 in La Ja,Reach-1         , 7
Up Type= 0
Dn Type= 3
Dn Slope=0.005
DSS Import GetInterval= 0
DSS Import GetPeak= 0
DSS Import FillOption= 0

--- UNT 012 in La Jarita Watershed.g01 (geometry) ---

Geom Title=Existing Conditions
Program Version=5.05

River Reach=UNT 012 in La Ja,Reach-1
Reach XY= 30
      2087199.09     13404197.96      2087569.18     13404022.64
      2087682.48     13403929.56      2088069.69     13403176.38
      2088277.74     13403059.38       2088317.6     13403011.06
      2088360.96     13402820.86      2088486.64     13402675.92
      2088521.09     13402409.56      2088625.73     13402160.73
      2088783.01     13402040.42      2088832.49     13402099.01
      2088878.06     13402082.08      2088936.65     13402179.74
      2088986.13     13402208.38      2089085.09     13402210.99
      2089108.53     13402183.64       2089092.9     13402130.26
      2089143.68     13402084.69       2089200.8     13402124.54
       2089330.8     13402144.54       2089420.8     13402044.54
       2089610.8     13401934.54       2089640.8     13401864.54
       2089630.8     13401744.54       2089690.8     13401674.54
       2089750.8     13401674.54       2089770.8     13401624.54
       2089890.8     13401524.54       2090060.8     13401504.54

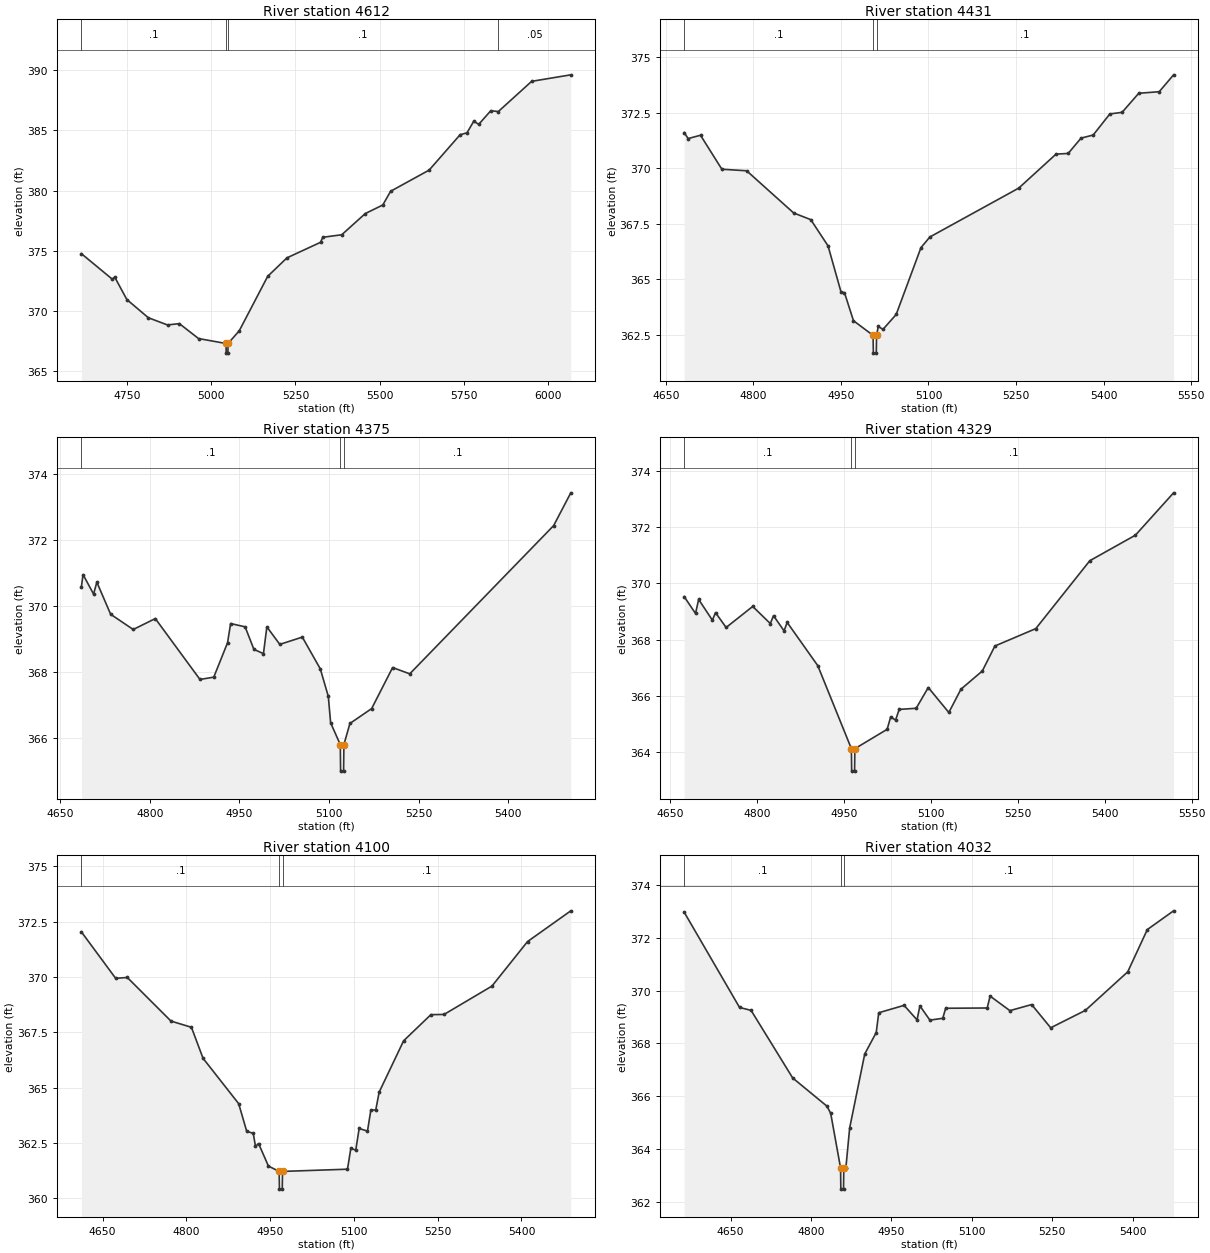
Type RM Length L Ch R = 1 ,4612    ,181,181,181
BEGIN DESCRIPTION:
Mapping XS c5a7f40d
END DESCRIPTION:
XS GIS Cut Line= 4
      2087571.32     13404418.56      2087064.63     13403840.71
      2086813.02      13403728.3      2086410.08     13403672.51
#Sta/Elev= 30
  4615.5  374.76  4707.6  372.63  4714.2  372.82  4750.3  370.95  4813.9  369.44
  4870.8  368.84  4905.9  368.95  4962.9  367.71  5044.3   367.3  5044.8   366.5
  5049.8   366.5  5050.3   367.3  5083.4  368.35  5167.9  372.88  5224.8  374.41
  5324.4   375.7  5331.1  376.12  5387.4  376.33  5457.1  378.09    5509   378.8
  5532.2  379.94  5646.5   381.7  5738.4  384.64  5758.6  384.79  5778.8  385.76
  5793.5   385.5  5829.2  386.63  5851.5  386.56  5950.4  389.07  6066.4  389.61
#Mann= 4 ,-1 , 0
  4615.5      .1       0  5044.3     .07       0  5050.3      .1       0
  5851.5     .05       0
Bank Sta=5044.3,5050.3
XS Rating Curve= 0 ,0
Exp/Cntr=0.3,0.1

Type RM Length L Ch R = 1 ,4431    ,56,56,56
BEGIN DESCRIPTION:
Mapping XS cd842c11
END DESCRIPTION:
XS GIS Cut Line= 3
      2087654.41     13404334.45      2087337.63     13403824.71
      2087154.91     13403671.04
#Sta/Elev= 30
  4681.2  371.61    4688  371.34  4709.2  371.49  4745.8  369.96  4788.3  369.89
  4868.9  367.99  4898.2  367.69  4927.8  366.51  4950.1  364.43    4956   364.4
  4971.4  363.14    5005  362.48  5005.5  361.68  5010.5  361.68    5011  362.48
  5013.9  362.88    5022  362.75  5044.6  363.42  5087.1  366.43  5102.4  366.91
  5254.7  369.11  5318.6  370.64  5339.4  370.67  5361.5  371.36  5382.3   371.5
  5410.9  372.45  5431.8  372.52  5460.4  373.38  5495.5  373.45  5520.1  374.21
#Mann= 3 ,-1 , 0
  4681.2      .1       0    5005     .07       0    5011      .1       0
Bank Sta=5005,5011
XS Rating Curve= 0 ,0
Exp/Cntr=0.3,0.1

Type RM Length L Ch R = 1 ,4375    ,46,46,46
BEGIN DESCRIPTION:
Mapping XS 531afb48
END DESCRIPTION:
XS GIS Cut Line= 4
      2087670.45     13404324.07      2087565.84     13404092.77
      2087486.12     13403949.77      2087230.16     13403639.77
#Sta/Elev= 30
  4685.3  370.58  4688.1  370.95  4705.7  370.36  4711.2  370.72  4734.3  369.75
  4772.1  369.29  4809.1  369.62  4883.9  367.78    4907  367.85  4930.1  368.89
  4935.2  369.47  4959.5  369.37  4974.2  368.69  4990.2  368.56  4995.9  369.37
  5017.6  368.84  5055.3  369.06  5085.4   368.1  5098.8  367.27  5102.7  366.47
  5118.9  365.81  5119.4  365.01  5124.4  365.01  5124.9  365.81    5135  366.45
  5171.4   366.9  5206.5  368.14  5235.2  367.95  5476.2  372.43  5504.9  373.42
#Mann= 3 ,-1 , 0
  4685.3      .1       0  5118.9     .07       0  5124.9      .1       0
Bank Sta=5118.9,5124.9
XS Rating Curve= 0 ,0
Exp/Cntr=0.3,0.1

Type RM Length L Ch R = 1 ,4329    ,229,229,229
BEGIN DESCRIPTION:
Mapping XS 20902060
END DESCRIPTION:
XS GIS Cut Line= 4
      2087709.45     13404313.87      2087593.49     13404040.95
      2087442.96     13403835.43      2087262.75     13403603.87
#Sta/Elev= 30
  4674.1  369.53  4693.7  368.93  4699.1  369.43  4722.8  368.69  4728.2  368.96
  4746.5  368.43  4792.4  369.18  4822.8  368.57  4828.3  368.85  4846.5  368.31
  4851.9  368.61  4904.7  367.07  4962.7  364.11  4963.2  363.31  4968.2  363.31
  4968.7  364.11  5024.4   364.8  5030.5  365.24    5039  365.13  5045.2  365.51
  5074.5  365.55  5095.4  366.29  5130.9   365.4  5151.8  366.23  5188.7  366.88
  5210.4  367.77    5281  368.39  5374.2  370.81  5452.9  371.72  5518.8  373.23
#Mann= 3 ,-1 , 0
  4674.1      .1       0  4962.7     .07       0  4968.7      .1       0
Bank Sta=4962.7,4968.7
XS Rating Curve= 0 ,0
Exp/Cntr=0.3,0.1

Type RM Length L Ch R = 1 ,4100    ,68,68,68
BEGIN DESCRIPTION:
Mapping XS 9a57b843
END DESCRIPTION:
XS GIS Cut Line= 4
      2088037.75     13404078.72      2087800.13     13403883.28
      2087660.61     13403820.55      2087318.91     13403584.05
#Sta/Elev= 30
  4612.1  372.04  4673.5  369.94  4694.3  369.98  4772.5  368.01  4809.1  367.73
  4829.9  366.33  4893.7  364.28  4908.1  363.03  4919.8  362.94  4923.8  362.35
  4929.3  362.48    4947  361.46  4966.2  361.22  4966.7  360.42  4971.7  360.42
  4972.2  361.22  5088.5  361.32  5094.5  362.26  5103.3  362.18  5109.4  363.16
  5124.3  363.04  5130.4     364  5139.1  363.99  5145.2   364.8    5189  367.12
  5237.8   368.3  5261.4  368.31  5347.1  369.59  5410.8   371.6  5488.3  372.99
#Mann= 3 ,-1 , 0
  4612.1      .1       0  4966.2     .07       0  4972.2      .1       0
Bank Sta=4966.2,4972.2
XS Rating Curve= 0 ,0
Exp/Cntr=0.3,0.1

Type RM Length L Ch R = 1 ,4032    ,70,70,70
BEGIN DESCRIPTION:
Mapping XS 3ec96446
END DESCRIPTION:
XS GIS Cut Line= 4
      2088090.42     13404065.87      2087823.25     13403815.87
      2087599.07     13403724.32      2087340.77     13403562.59
#Sta/Elev= 30
  4563.4  372.97  4666.7  369.36  4688.2  369.25  4765.8  366.69  4829.8  365.62
  4836.7  365.35  4855.1  363.28  4855.6  362.48  4860.6  362.48  4861.1  363.28
    4865  363.29  4872.1   364.8  4900.2   367.6  4921.6  368.41  4926.3  369.16
  4973.6  369.44  4997.7  368.89  5003.1  369.42  5021.7  368.88  5045.7  368.95
  5051.1  369.33  5128.6  369.34    5134  369.79  5170.9  369.24  5211.5  369.47
    5247  368.59  5311.7  369.25  5390.7  370.71  5427.2  372.31  5476.2  373.02
#Mann= 3 ,-1 , 0
  4563.4      .1       0  4855.1     .07       0  4861.1      .1       0
Bank Sta=4855.1,4861.1
XS Rating Curve= 0 ,0
Exp/Cntr=0.3,0.1

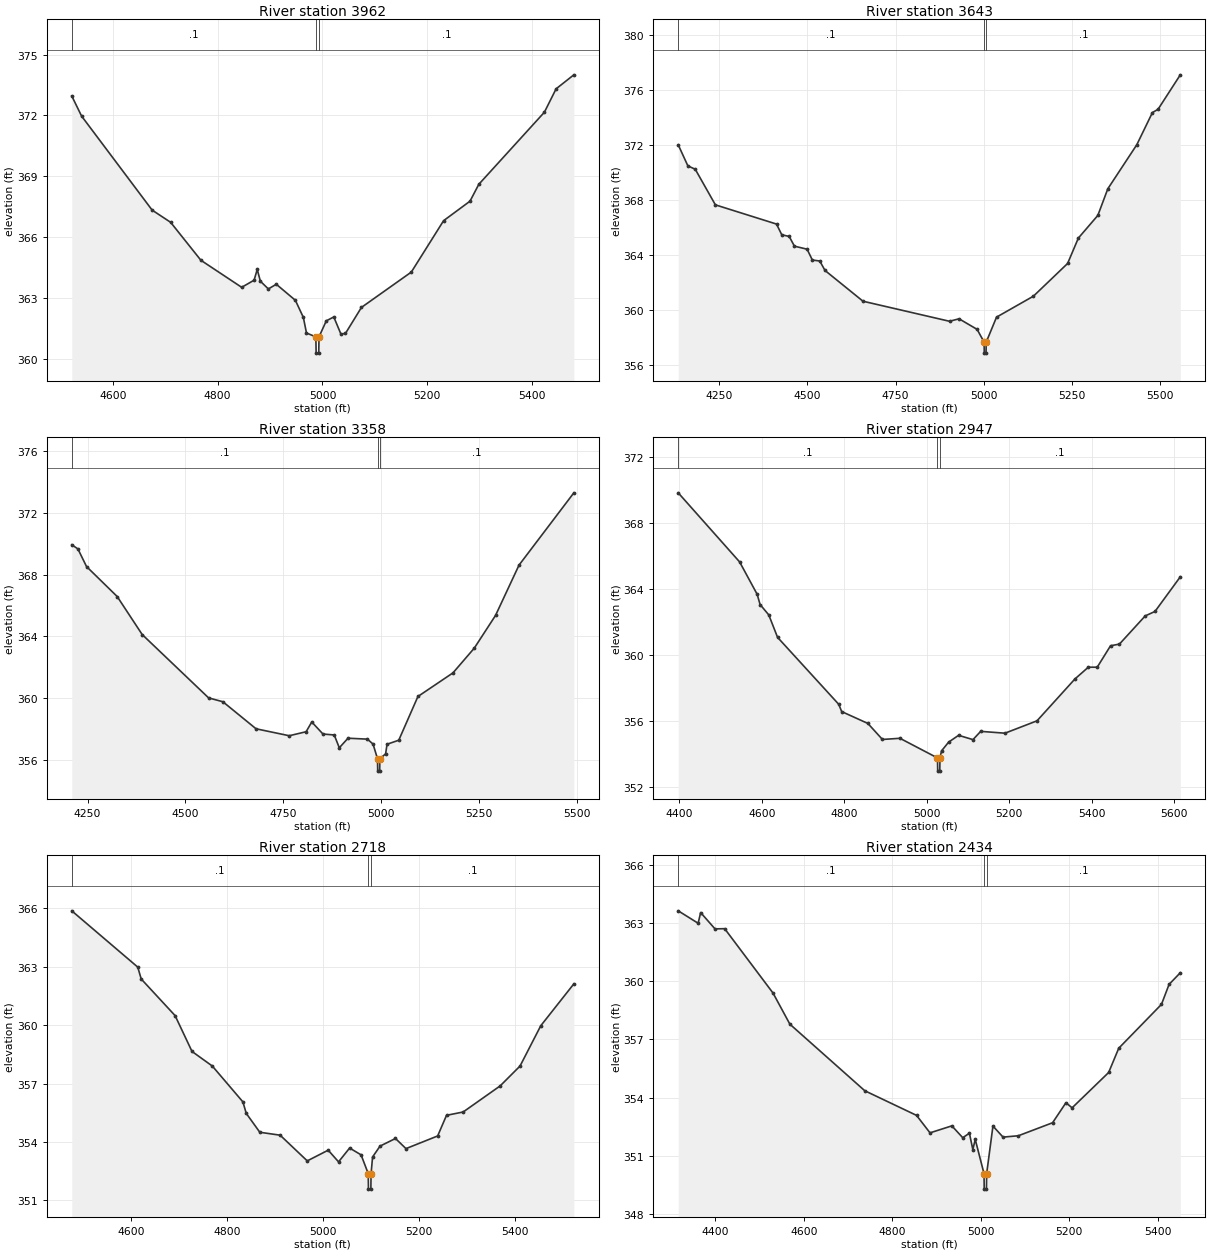
Type RM Length L Ch R = 1 ,3962    ,319,319,319
BEGIN DESCRIPTION:
Mapping XS 61939d2e
END DESCRIPTION:
XS GIS Cut Line= 4
      2088124.87     13404050.45      2087951.48     13403829.26
      2087796.04     13403730.14      2087354.68     13403510.73
#Sta/Elev= 30
  4521.5  372.96  4540.2  371.97  4674.9  367.34  4710.2  366.74    4768  364.87
  4845.8  363.54  4869.5  363.89  4875.5  364.42  4881.5  363.84  4896.7  363.46
  4911.9  363.69  4948.3   362.9  4963.5  362.06  4969.5  361.29  4987.4   361.1
  4987.9   360.3  4992.9   360.3  4993.4   361.1  5007.3  361.89  5021.6  362.08
  5035.2  361.24  5043.9  361.27  5074.4  362.55  5169.6  364.29  5231.2  366.82
  5281.6  367.78  5298.4  368.61  5423.6  372.16  5445.9  373.31  5479.8     374
#Mann= 3 ,-1 , 0
  4521.5      .1       0  4987.4     .07       0  4993.4      .1       0
Bank Sta=4987.4,4993.4
XS Rating Curve= 0 ,0
Exp/Cntr=0.3,0.1

Type RM Length L Ch R = 1 ,3643    ,285,285,285
BEGIN DESCRIPTION:
Mapping XS 71cfa663
END DESCRIPTION:
XS GIS Cut Line= 3
      2088435.85     13404131.93      2087979.86     13403464.28
      2087423.36     13403202.98
#Sta/Elev= 30
    4134  372.03  4161.3   370.5  4182.3  370.25  4239.3  367.66  4412.6  366.26
  4427.5  365.48  4448.5  365.36  4463.4  364.65  4499.3  364.43  4514.2  363.64
  4535.2  363.57  4550.1  362.88  4657.8  360.64    4903  359.18  4930.1  359.36
  4981.3  358.59  5001.1  357.66  5001.6  356.86  5006.6  356.86  5007.1  357.66
  5036.3  359.48    5141  361.01  5237.8  363.39  5268.3  365.24  5323.5  366.89
  5351.8  368.83    5434  372.04  5478.2  374.38  5494.2  374.62  5557.3  377.13
#Mann= 3 ,-1 , 0
    4134      .1       0  5001.1     .07       0  5007.1      .1       0
Bank Sta=5001.1,5007.1
XS Rating Curve= 0 ,0
Exp/Cntr=0.3,0.1

Type RM Length L Ch R = 1 ,3358    ,411,411,411
BEGIN DESCRIPTION:
Mapping XS 0ff72a1b
END DESCRIPTION:
XS GIS Cut Line= 3
      2088677.26     13403685.35       2088052.8     13403181.58
      2087604.37     13403007.11
#Sta/Elev= 30
  4209.5  369.93  4225.2  369.66  4247.2  368.52  4325.6  366.58  4389.5  364.12
  4559.3  360.02  4595.8  359.77  4680.6  358.02  4765.4  357.57  4808.6  357.83
    4823  358.46  4851.7  357.68  4880.5  357.62  4893.4  356.79  4915.7  357.41
  4965.3  357.35  4979.7  357.03  4991.1  356.08  4991.6  355.28  4996.6  355.28
  4997.1  356.08  5011.8   356.4  5015.5  357.02  5045.4  357.28  5094.4  360.11
  5184.1  361.64  5238.5  363.24  5292.9  365.36  5352.8  368.61    5493  373.29
#Mann= 3 ,-1 , 0
  4209.5      .1       0  4991.1     .07       0  4997.1      .1       0
Bank Sta=4991.1,4997.1
XS Rating Curve= 0 ,0
Exp/Cntr=0.3,0.1

Type RM Length L Ch R = 1 ,2947    ,229,229,229
BEGIN DESCRIPTION:
Mapping XS 64961c3b
END DESCRIPTION:
XS GIS Cut Line= 3
      2088757.77     13403343.01       2088334.6     13402922.93
      2087758.14     13402689.24
#Sta/Elev= 30
  4397.2  369.82  4546.2  365.63  4588.7  363.67  4595.8  363.05  4616.9  362.42
  4638.2  361.06  4786.7     357  4793.8  356.56  4857.4  355.84  4892.7  354.87
  4935.2  354.94  5026.3  353.75  5026.8  352.95  5031.8  352.95  5032.3  353.75
  5036.2  354.18  5053.4  354.71  5077.5  355.12  5112.4  354.86  5131.1  355.36
  5190.1  355.25  5267.8     356  5359.9  358.54  5392.3  359.25  5413.9  359.25
  5446.2  360.55  5467.8  360.65  5530.4  362.36  5554.1  362.63  5615.5  364.73
#Mann= 3 ,-1 , 0
  4397.2      .1       0  5026.3     .07       0  5032.3      .1       0
Bank Sta=5026.3,5032.3
XS Rating Curve= 0 ,0
Exp/Cntr=0.3,0.1

Type RM Length L Ch R = 1 ,2718    ,284,284,284
BEGIN DESCRIPTION:
Mapping XS 6c4ab35b
END DESCRIPTION:
XS GIS Cut Line= 3
      2088811.25     13403103.57      2088455.08     13402733.85
       2087961.2     13402529.92
#Sta/Elev= 30
  4475.4  365.87  4613.1  362.98  4620.3  362.37    4691  360.49  4726.3  358.65
  4768.7   357.9  4832.5  356.06  4839.5  355.47  4867.8   354.5  4910.2  354.35
  4966.8  353.03  5010.5  353.58  5032.1  352.98  5055.2  353.69  5079.1  353.34
    5094  352.38  5094.5  351.58  5099.5  351.58    5100  352.38  5103.1  353.23
  5118.7  353.79  5150.9  354.18  5172.8  353.66  5238.9  354.31  5257.4  355.37
  5292.1  355.54  5369.3  356.88  5410.8   357.9  5454.1  359.97  5523.1  362.12
#Mann= 3 ,-1 , 0
  4475.4      .1       0    5094     .07       0    5100      .1       0
Bank Sta=5094,5100
XS Rating Curve= 0 ,0
Exp/Cntr=0.3,0.1

Type RM Length L Ch R = 1 ,2434    ,190,190,190
BEGIN DESCRIPTION:
Mapping XS 1d3ec86b
END DESCRIPTION:
XS GIS Cut Line= 3
      2088861.84     13403038.85      2088563.52     13402487.62
       2088103.8     13402270.73
#Sta/Elev= 30
  4315.9  363.62  4360.9  362.98  4366.6  363.53    4399  362.69  4420.9   362.7
  4530.3  359.38  4568.3  357.78  4737.6  354.35  4854.7  353.08  4885.1  352.18
  4934.5  352.54  4959.1  351.93  4974.2  352.16  4981.9  351.32  4987.4  351.84
  5007.2  350.08  5007.7  349.28  5012.7  349.28  5013.2  350.08  5027.4  352.53
  5050.2  351.96  5084.8  352.03  5162.2   352.7  5192.4  353.73  5206.4  353.47
    5289  355.29  5311.8  356.54  5408.4   358.8  5425.6  359.83    5451  360.43
#Mann= 3 ,-1 , 0
  4315.9      .1       0  5007.2     .07       0  5013.2      .1       0
Bank Sta=5007.2,5013.2
XS Rating Curve= 0 ,0
Exp/Cntr=0.3,0.1

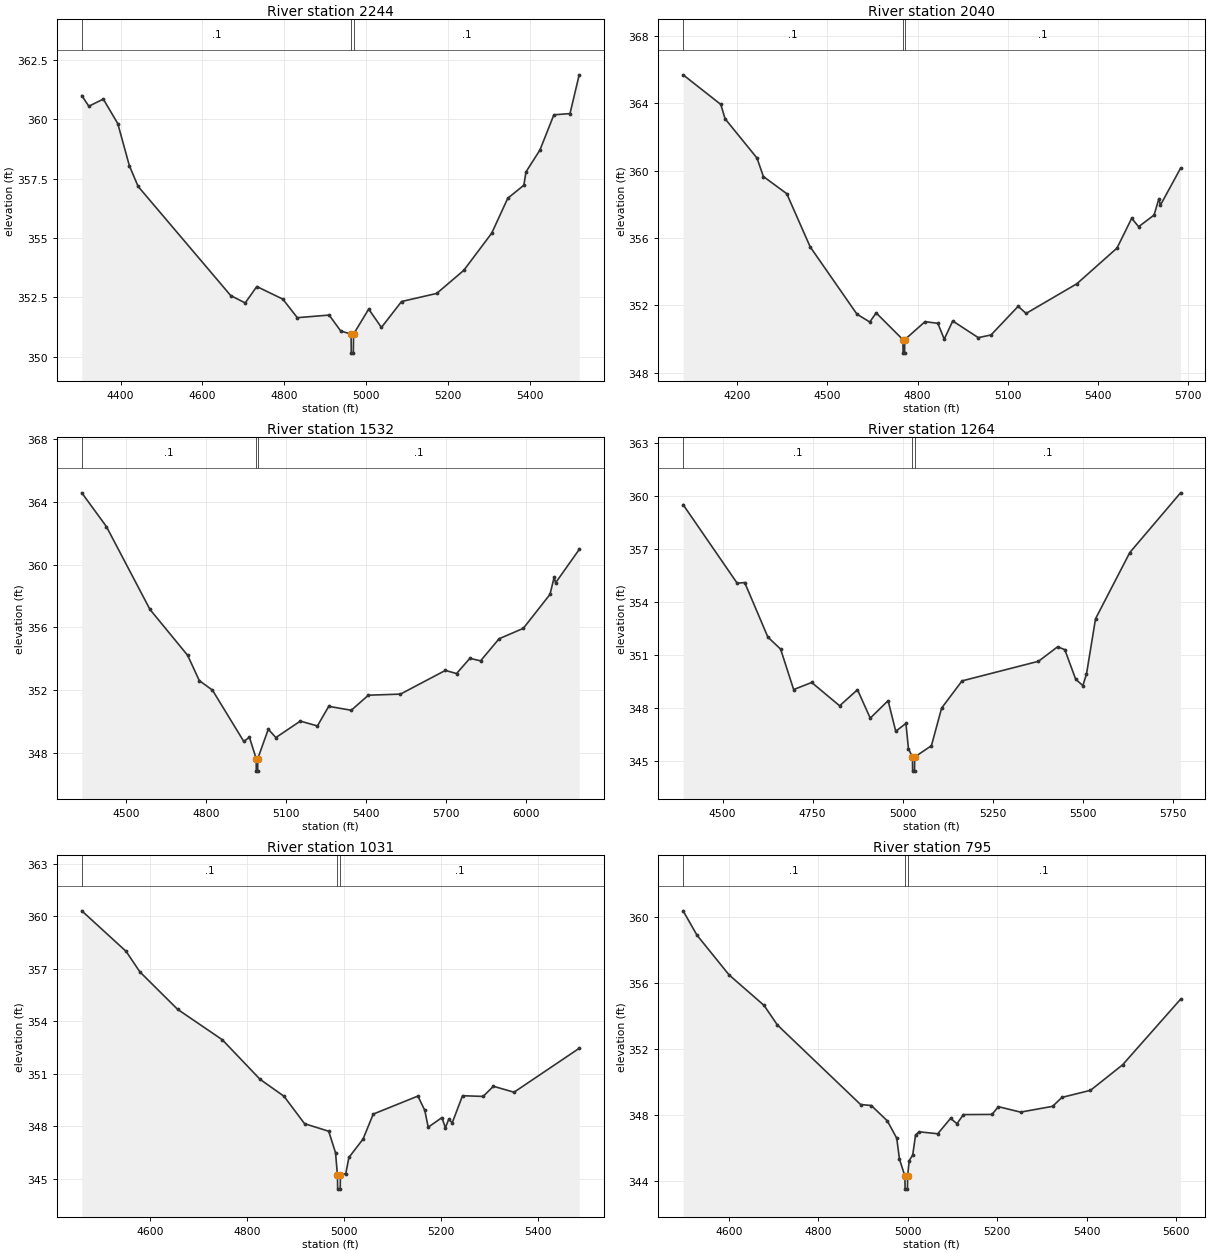
Type RM Length L Ch R = 1 ,2244    ,204,204,204
BEGIN DESCRIPTION:
Mapping XS 17273a11
END DESCRIPTION:
XS GIS Cut Line= 3
      2089059.66     13402774.71      2088584.78     13402287.84
      2088069.95     13402143.47
#Sta/Elev= 30
  4305.2  360.99  4322.4  360.54  4357.8  360.84  4393.1  359.81  4421.4  358.04
  4442.7  357.17  4668.9  352.58  4704.3  352.27  4732.6  352.96  4796.2  352.43
  4831.6  351.65  4909.3  351.76  4937.6  351.09  4962.9  350.96  4963.4  350.16
  4968.4  350.16  4968.9  350.96  5005.9  352.01    5037  351.24  5086.1  352.33
    5172  352.67  5238.1  353.64  5306.2   355.2  5345.5  356.67  5384.8  357.22
  5390.1  357.78  5424.1   358.7  5458.2  360.18  5497.5  360.23    5520  361.86
#Mann= 3 ,-1 , 0
  4305.2      .1       0  4962.9     .07       0  4968.9      .1       0
Bank Sta=4962.9,4968.9
XS Rating Curve= 0 ,0
Exp/Cntr=0.3,0.1

Type RM Length L Ch R = 1 ,2040    ,508,508,508
BEGIN DESCRIPTION:
UNT 012 in La Jarita Watershed 2.0
END DESCRIPTION:
XS GIS Cut Line= 3
      2089368.51     13402828.61      2088649.76     13402095.97
      2088039.34     13401953.77
#Sta/Elev= 30
    4021  365.69  4146.3  363.93  4160.4  363.08  4266.4  360.75  4287.7  359.65
  4365.4  358.63  4443.3  355.47  4598.9  351.47  4641.3  351.01  4662.5  351.55
  4751.5  349.96    4752  349.16    4757  349.16  4757.5  349.96    4825  351.03
  4867.5  350.93  4888.8  349.99    4917  351.07  5001.9  350.08  5044.3  350.24
  5134.4  351.94  5160.9  351.52  5329.5  353.28  5462.9   355.4  5511.8  357.17
  5534.8  356.67  5586.1  357.36  5602.1  358.33  5607.2  357.95  5674.1  360.14
#Mann= 3 ,-1 , 0
    4021      .1       0  4751.5     .07       0  4757.5      .1       0
Bank Sta=4751.5,4757.5
XS Rating Curve= 0 ,0
Exp/Cntr=0.3,0.1

Type RM Length L Ch R = 1 ,1532    ,268,268,268
BEGIN DESCRIPTION:
Mapping XS 6f06bb31
END DESCRIPTION:
XS GIS Cut Line= 4
      2089392.82     13402783.48      2089121.98     13402286.94
      2088809.48     13401957.08      2087965.69     13401915.41
#Sta/Elev= 30
  4335.3  364.57  4427.6  362.42  4590.8  357.14  4732.2  354.21  4775.9   352.6
  4825.3  351.99  4942.7  348.72  4963.7  348.99  4989.1  347.63  4989.6  346.83
  4994.6  346.83  4995.1  347.63  5034.5   349.5  5062.9  348.97  5154.7  350.02
  5218.6  349.71  5261.1  350.96  5345.6  350.71  5409.8  351.67    5530  351.74
  5698.4  353.25  5740.2  353.05  5790.3  354.02  5830.3  353.86  5899.9  355.27
  5990.5  355.93  6090.7   358.1  6106.4  359.21  6111.4  358.83  6200.1  360.96
#Mann= 3 ,-1 , 0
  4335.3      .1       0  4989.1     .07       0  4995.1      .1       0
Bank Sta=4989.1,4995.1
XS Rating Curve= 0 ,0
Exp/Cntr=0.3,0.1

Type RM Length L Ch R = 1 ,1264    ,233,233,233
BEGIN DESCRIPTION:
Mapping XS 7cc66170
END DESCRIPTION:
XS GIS Cut Line= 4
      2089667.15     13402523.08       2089389.6     13402307.53
      2088917.12     13401832.08      2088896.29     13401474.49
#Sta/Elev= 30
  4390.6  359.49  4540.6  355.04  4561.4  355.08  4625.7  351.99    4661  351.31
  4697.2  349.02  4747.3  349.42  4824.8   348.1  4874.3  349.01  4909.7   347.4
  4959.2  348.39  4980.4  346.66  5008.7   347.1  5015.7  345.66  5026.8   345.2
  5027.3   344.4  5032.5   344.4    5033   345.2  5079.4  345.84  5107.7  347.97
  5164.3  349.51  5376.4  350.62  5429.4  351.44  5449.4  351.28  5479.5  349.61
  5499.5  349.24  5509.6   349.9  5534.7  353.03  5629.8  356.78  5770.5  360.16
#Mann= 3 ,-1 , 0
  4390.6      .1       0  5026.8     .07       0    5033      .1       0
Bank Sta=5026.8,5033
XS Rating Curve= 0 ,0
Exp/Cntr=0.3,0.1

Type RM Length L Ch R = 1 ,1031    ,236,236,236
BEGIN DESCRIPTION:
Mapping XS 781e135f
END DESCRIPTION:
XS GIS Cut Line= 3
      2089783.93     13402445.26       2089386.8     13402061.15
       2089049.6     13401730.44
#Sta/Elev= 30
  4459.8  360.32  4551.2     358  4579.5  356.83  4657.2  354.69  4749.3  352.95
    4827  350.69  4876.4  349.72  4918.8  348.15  4968.5  347.72  4982.6  346.49
  4986.5  345.21    4987  344.41  4992.2  344.41  4992.7  345.21  5003.7   345.3
  5010.1  346.22  5039.2  347.27  5060.3   348.7  5152.3  349.73  5166.5  348.91
  5173.5  347.95  5201.8   348.5  5208.9  347.92  5215.9  348.41    5223   348.2
  5244.2  349.75  5286.6  349.71  5307.9  350.29  5350.3  349.95  5484.6  352.46
#Mann= 3 ,-1 , 0
  4459.8      .1       0  4986.5     .07       0  4992.7      .1       0
Bank Sta=4986.5,4992.7
XS Rating Curve= 0 ,0
Exp/Cntr=0.3,0.1

Type RM Length L Ch R = 1 ,795     ,260,260,260
BEGIN DESCRIPTION:
UNT 012 in La Jarita Watershed 3.0
END DESCRIPTION:
XS GIS Cut Line= 3
      2089868.53     13402373.78      2089593.07      13401965.6
      2089115.01     13401571.64
#Sta/Elev= 30
  4498.1  360.36    4529  358.89  4600.9  356.48  4678.9  354.64  4708.9  353.45
  4894.8  348.64  4918.7  348.58  4954.6  347.65  4975.6   346.6  4981.7  345.33
  4993.8  344.32  4994.3  343.52  4999.5  343.52    5000  344.32  5003.4  345.24
  5011.3  345.59  5017.7   346.8  5025.6  346.99  5067.2  346.87  5095.9   347.8
  5110.3  347.48  5124.6  348.03  5188.5  348.04  5202.8  348.51  5252.3  348.18
    5324  348.53  5344.8  349.07  5408.7   349.5  5480.4  351.04    5610  355.01
#Mann= 3 ,-1 , 0
  4498.1      .1       0  4993.8     .07       0    5000      .1       0
Bank Sta=4993.8,5000
XS Rating Curve= 0 ,0
Exp/Cntr=0.3,0.1

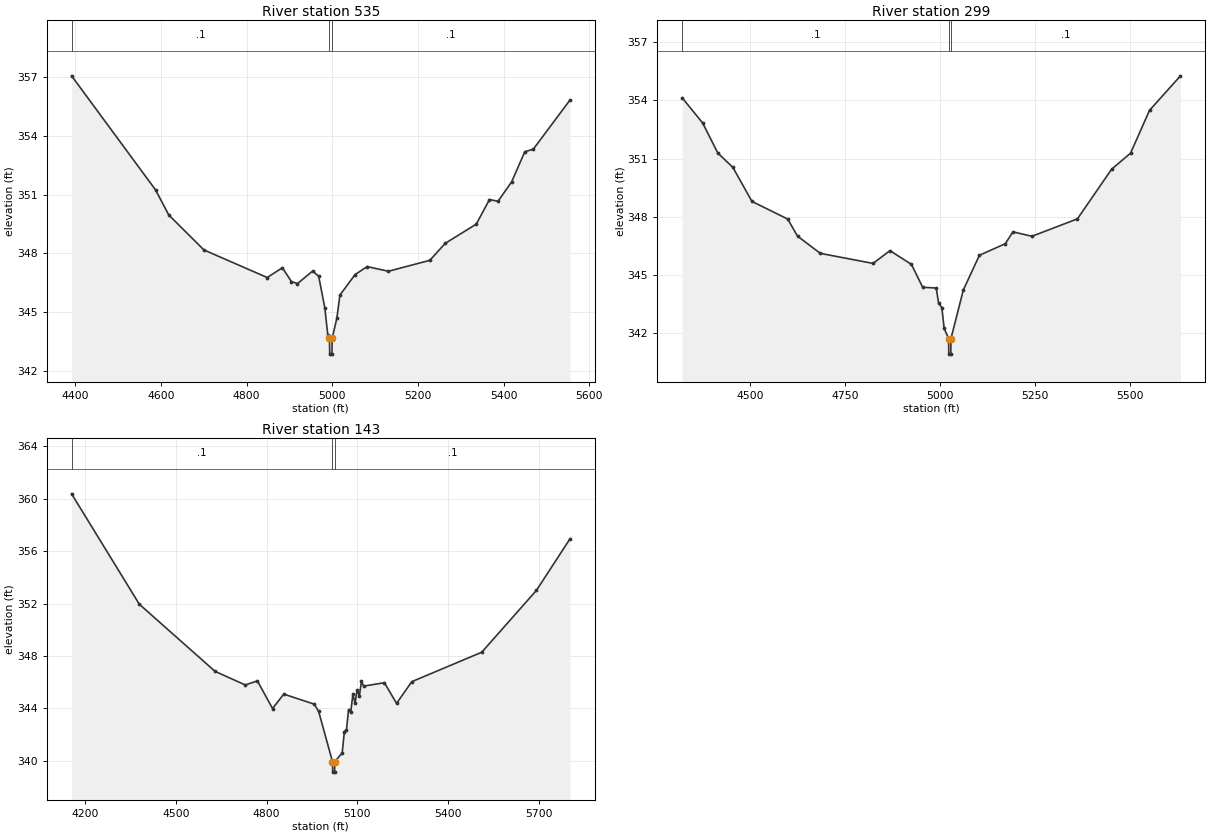
Type RM Length L Ch R = 1 ,535     ,236,236,236
BEGIN DESCRIPTION:
Mapping XS 693d99b1
END DESCRIPTION:
XS GIS Cut Line= 4
      2089885.88     13402266.14      2089799.07     13401887.64
      2089542.12     13401630.69      2089142.83       13401530.
#Sta/Elev= 30
  4391.5  357.08  4587.6  351.24  4618.4  349.96  4700.5  348.17  4848.2  346.76
  4883.6  347.26  4904.8  346.55  4918.9  346.45  4954.3  347.09  4968.4  346.82
  4982.6  345.22  4989.6  343.83  4993.6  343.64  4994.1  342.84  4999.3  342.84
  4999.8  343.64  5010.8  344.68  5017.9  345.86  5053.3  346.91  5081.6  347.32
  5131.1  347.08  5227.9  347.64  5263.8  348.51  5336.2  349.49  5367.1  350.75
    5387  350.66  5418.7  351.65  5449.6   353.2  5469.2  353.32    5555  355.84
#Mann= 3 ,-1 , 0
  4391.5      .1       0  4993.6     .07       0  4999.8      .1       0
Bank Sta=4993.6,4999.8
XS Rating Curve= 0 ,0
Exp/Cntr=0.3,0.1

Type RM Length L Ch R = 1 ,299     ,156,156,156
BEGIN DESCRIPTION:
Mapping XS d355e97d
END DESCRIPTION:
XS GIS Cut Line= 4
      2089972.03     13402178.97      2089985.05     13401725.85
      2089677.76      13401509.7      2089193.36      13401509.7
#Sta/Elev= 30
  4320.2  354.14  4374.2  352.84  4414.2  351.29  4454.2  350.54  4504.2  348.79
  4598.5  347.88  4624.3     347  4684.3  346.11  4823.5  345.59  4867.9  346.25
  4924.6  345.54  4954.2  344.36  4989.9  344.32    4996  343.56  5004.7   343.3
  5010.8  342.24  5022.5  341.71    5023  340.91  5028.2  340.91  5028.7  341.71
  5061.3  344.22  5103.7  346.01    5172  346.61    5192  347.22    5242  346.99
    5362  347.89    5452  350.45    5502  351.28    5552  353.49  5633.6  355.27
#Mann= 3 ,-1 , 0
  4320.2      .1       0  5022.5     .07       0  5028.7      .1       0
Bank Sta=5022.5,5028.7
XS Rating Curve= 0 ,0
Exp/Cntr=0.3,0.1

Type RM Length L Ch R = 1 ,143     ,0,0,0
BEGIN DESCRIPTION:
UNT 012 in La Jarita Watershed 1.0
END DESCRIPTION:
XS GIS Cut Line= 4
      2090045.59      13402328.6      2090024.11     13401625.59
      2089815.78     13401410.74        2089175.       13401475.
#Sta/Elev= 30
  4155.9  360.38  4379.6  351.95  4629.7  346.82  4729.8  345.78  4769.8  346.09
  4819.8  343.98    4857  345.08  4957.9  344.31  4972.1  343.76  5017.9  339.92
  5018.5  339.12  5024.9  339.12  5025.5  339.92    5050  340.59    5057  342.19
  5064.1  342.37  5071.1   343.9  5078.3  343.71  5085.3  345.09  5092.4  344.38
  5099.4  345.41  5106.6  344.93  5113.6  346.05  5120.7  345.69  5189.4  345.95
  5229.6  344.37  5279.9  346.03    5511  348.28  5691.9  353.01  5802.5  356.94
#Mann= 3 ,-1 , 0
  4155.9      .1       0  5017.9     .07       0  5025.5      .1       0
Bank Sta=5017.9,5025.5
XS Rating Curve= 0 ,0
Exp/Cntr=0.3,0.1
LCMann Table=0

Chan Stop Cuts=-1
Use User Specified Reach Order=0
Composite Channel Slope=5