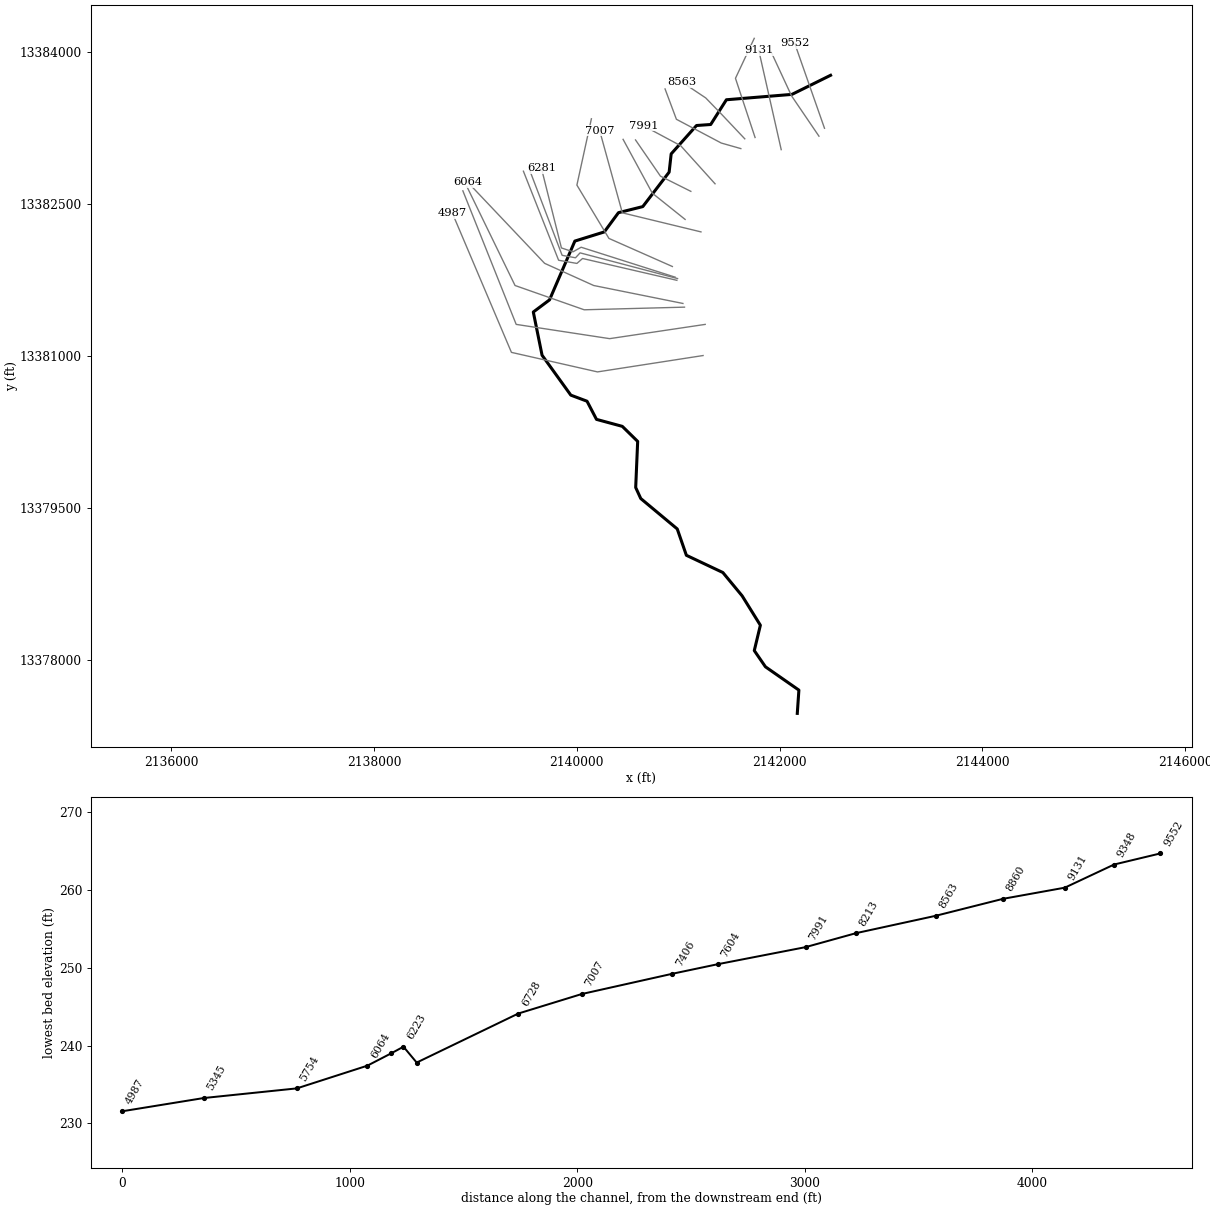
--- UNT 013 in La Jarita Watershed.prj (project) ---

Proj Title=UNT 013 in La Jarita Watershed Base Level Engineering
Current Plan=p01
Default Exp/Contr=0.3,0.1
English Units
Geom File=g01
Flow File=f01
Plan File=p01
BEGIN DESCRIPTION:
UNT 013 in La Jarita Watershed
END DESCRIPTION:

--- UNT 013 in La Jarita Watershed.p01 (plan) ---

Plan Title=Multiple Run
Short Identifier=Multiple
Geom File=g01
Flow File=f01
Subcritical Flow
K Sum by GR= 0
Std Step Tol= 0.01
Critical Tol= 0.01
Num of Std Step Trials= 20
Max Error Tol= 0.3
Flow Tol Ratio= 0.001
Split Flow NTrial= 30
Split Flow Tol= 0.02
Split Flow Ratio= 0.02
Log Output Level= 0
Friction Slope Method= 1
Unsteady Friction Slope Method= 2
Unsteady Bridges Friction Slope Method= 1
Parabolic Critical Depth
Global Vel Dist=  1 , 1 , 1
Global Log Level= 0
CheckData=True
Encroach Param= -1, 0, 0, 0
BEGIN DESCRIPTION:
Multiple Run
END DESCRIPTION:

--- UNT 013 in La Jarita Watershed.f01 (steady flow) ---

Flow Title=Multiple
Number of Profiles=7
Profile Names=10-year,25-year,50-year,1pct_min,100-year,1pct_plu,500-year
River Rch & RM= UNT 013 in La Ja,Reach-1,9552
     142     190     228     137     273     544     396
River Rch & RM= UNT 013 in La Ja,Reach-1,8563
     197     269     327     199     397     792     593
Boundary for River Rch & Prof#=UNT 013 in La Ja,Reach-1,1
Up Type=0
Dn Type=3
Dn Slope=0.005
Boundary for River Rch & Prof#=UNT 013 in La Ja,Reach-1,2
Up Type=0
Dn Type=3
Dn Slope=0.005
Boundary for River Rch & Prof#=UNT 013 in La Ja,Reach-1,3
Up Type=0
Dn Type=3
Dn Slope=0.005
Boundary for River Rch & Prof#=UNT 013 in La Ja,Reach-1,4
Up Type=0
Dn Type=3
Dn Slope=0.005
Boundary for River Rch & Prof#=UNT 013 in La Ja,Reach-1,5
Up Type=0
Dn Type=3
Dn Slope=0.005
Boundary for River Rch & Prof#=UNT 013 in La Ja,Reach-1,6
Up Type=0
Dn Type=3
Dn Slope=0.005
Boundary for River Rch & Prof#=UNT 013 in La Ja,Reach-1,7
Up Type=0
Dn Type=3
Dn Slope=0.005

--- UNT 013 in La Jarita Watershed.g01 (geometry) ---

Geom Title=Existing Conditions

River Reach=UNT 013 in La Ja,Reach-1
Reach XY= 30
      2142503.37     13383769.93      2142122.30     13383581.57
      2141475.59     13383528.62      2141320.80     13383284.54
      2141180.80     13383274.54      2140930.80     13382994.54
      2140910.80     13382814.54      2140650.80     13382474.54
      2140410.80     13382414.54      2140270.80     13382224.54
      2139980.80     13382134.54      2139730.80     13381554.54
      2139570.80     13381434.54      2139657.14     13381008.20
      2139940.80     13380614.54      2140100.80     13380554.54
      2140194.06     13380375.47      2140448.77     13380306.57
      2140600.31     13380158.11      2140580.80     13379703.25
      2140630.80     13379594.54      2140990.80     13379294.54
      2141080.80     13379034.54      2141440.80     13378864.54
      2141630.80     13378634.54      2141810.80     13378344.54
      2141750.80     13378094.54      2141860.80     13377934.54
      2142190.80     13377704.54      2142175.00     13377475.00

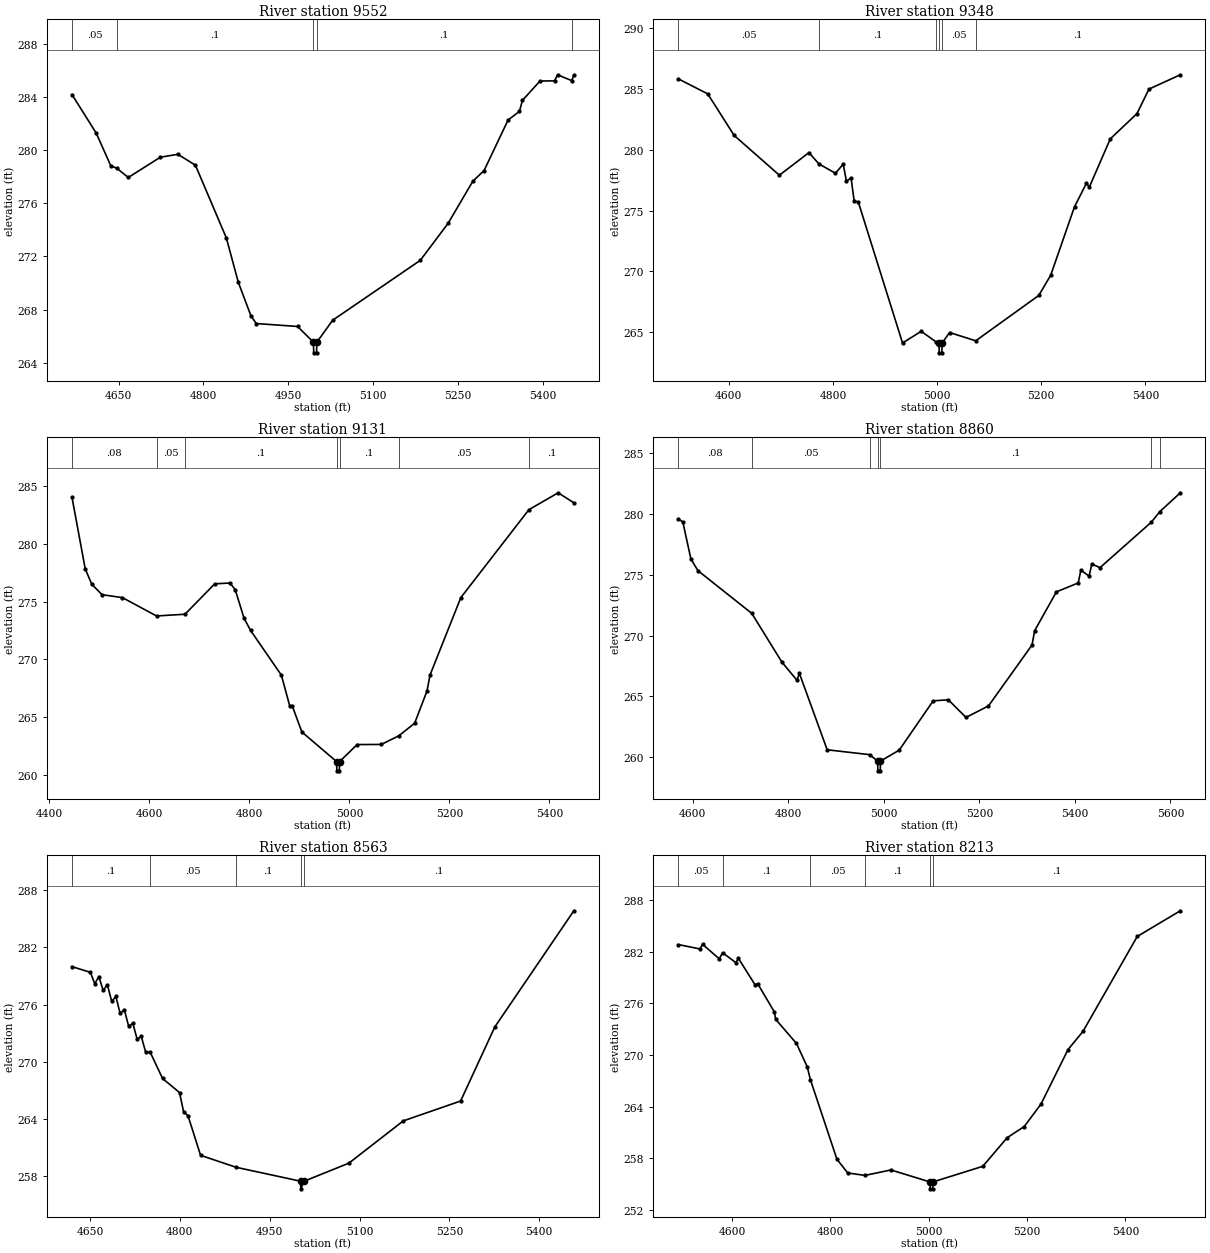
Type RM Length L Ch R = 1,9552,204,204,204
BEGIN DESCRIPTION:
Mapping XS 9e675c69
END DESCRIPTION:
XS GIS Cut Line= 2
      2142443.47     13383247.38      2142149.59     13384084.81
#Sta/Elev= 30
  4567.6  284.22  4610.5  281.31  4636.2  278.85  4647.1  278.65  4667.2  277.96
  4723.9  279.49  4754.9  279.71  4785.9  278.89  4840.6  273.40  4861.8  270.05
  4884.2  267.51  4893.6  266.94  4966.6  266.72  4994.6  265.53  4995.1  264.73
  5000.1  264.73  5000.6  265.53  5028.6  267.19  5183.6  271.71  5232.7  274.50
  5276.5  277.68  5296.3  278.48  5338.7  282.29  5358.9  282.95  5364.2  283.78
  5395.2  285.24  5420.9  285.25  5426.2  285.71  5451.3  285.27  5455.1  285.68
#Mann=5,-1,0
  4567.6    0.05       0  4647.1     0.1       0  4994.6    0.07       0
  5000.6     0.1       0  5451.3    0.05       0
Bank Sta=4994.6,5000.6
Exp/Cntr=0.3,0.1

Type RM Length L Ch R = 1,9348,217,217,217
BEGIN DESCRIPTION:
UNT 013 in La Jarita Watershed 16.0
END DESCRIPTION:
XS GIS Cut Line= 3
      2142388.77     13383169.26      2142117.95     13383567.68
      2141914.83     13384005.18
#Sta/Elev= 30
  4503.1  285.83  4559.4  284.60  4610.2  281.18  4697.0  277.91  4753.9  279.77
  4772.9  278.84  4804.8  278.07  4819.7  278.82  4825.8  277.42  4834.7  277.68
  4840.7  275.79  4848.6  275.71  4933.6  264.11  4969.5  265.07  4998.6  264.18
  5003.6  264.10  5004.1  263.30  5009.1  263.30  5009.6  264.10  5024.0  264.97
  5074.2  264.29  5195.3  268.02  5218.2  269.68  5264.0  275.32  5286.9  277.25
  5292.4  276.93  5332.7  280.90  5384.0  282.98  5406.9  284.99  5467.2  286.17
#Mann=6,-1,0
  4503.1    0.05       0  4772.9     0.1       0  4998.6    0.05       0
  5003.6   0.035       0  5009.6    0.05       0  5074.2     0.1       0
Bank Sta=5003.6,5009.6
Exp/Cntr=0.3,0.1

Type RM Length L Ch R = 1,9131,271,271,271
BEGIN DESCRIPTION:
Mapping XS ba184b16
END DESCRIPTION:
XS GIS Cut Line= 2
      2142016.39     13383036.46      2141795.05     13384015.55
#Sta/Elev= 30
  4445.0  284.07  4471.5  277.86  4484.5  276.52  4505.0  275.61  4546.0  275.35
  4614.2  273.76  4671.1  273.91  4730.6  276.55  4761.3  276.62  4771.6  276.03
  4789.2  273.56  4802.3  272.50  4863.9  268.62  4880.7  265.93  4885.8  265.93
  4904.9  263.69  4974.3  261.12  4974.8  260.32  4979.8  260.32  4980.3  261.12
  5015.3  262.60  5063.6  262.61  5098.4  263.35  5130.4  264.45  5155.1  267.25
  5161.2  268.64  5222.7  275.35  5358.8  282.98  5417.5  284.45  5448.8  283.58
#Mann=7,-1,0
  4445.0    0.08       0  4614.2    0.05       0  4671.1     0.1       0
  4974.3    0.07       0  4980.3     0.1       0  5098.4    0.05       0
  5358.8     0.1       0
Bank Sta=4974.3,4980.3
Exp/Cntr=0.3,0.1

Type RM Length L Ch R = 1,8860,297,297,297
BEGIN DESCRIPTION:
Mapping XS aec54dde
END DESCRIPTION:
XS GIS Cut Line= 3
      2141758.59     13383156.19      2141565.14     13383740.19
      2141750.37     13384134.55
#Sta/Elev= 30
  4569.9  279.60  4579.2  279.33  4596.1  276.29  4610.8  275.34  4723.5  271.83
  4786.3  267.84  4818.0  266.34  4823.3  266.89  4881.4  260.62  4970.3  260.22
  4987.0  259.69  4987.5  258.89  4992.5  258.89  4993.0  259.69  5032.2  260.59
  5103.3  264.64  5135.0  264.73  5172.0  263.28  5219.0  264.22  5310.3  269.23
  5315.8  270.41  5361.4  273.60  5407.0  274.33  5412.6  275.38  5429.9  274.89
  5435.4  275.88  5452.7  275.59  5560.0  279.32  5577.9  280.19  5620.8  281.74
#Mann=7,-1,0
  4569.9    0.08       0  4723.5    0.05       0  4970.3     0.1       0
  4987.0    0.07       0  4993.0     0.1       0  5560.0    0.05       0
  5577.9     0.1       0
Bank Sta=4987,4993
Exp/Cntr=0.3,0.1

Type RM Length L Ch R = 1,8563,350,350,350
BEGIN DESCRIPTION:
Mapping XS bf25661d
END DESCRIPTION:
XS GIS Cut Line= 4
      2141656.98     13383143.23      2141433.06     13383380.18
      2141271.60     13383546.84      2141038.60     13383702.18
#Sta/Elev= 30
  4619.8  279.98  4650.6  279.38  4657.9  278.18  4664.7  278.94  4672.0  277.48
  4678.9  278.09  4686.2  276.33  4693.1  276.85  4700.3  275.07  4707.2  275.48
  4714.5  273.73  4721.4  274.04  4728.7  272.37  4735.5  272.69  4742.8  271.04
  4750.5  271.01  4771.1  268.26  4799.4  266.79  4806.3  264.76  4813.6  264.36
  4834.6  260.21  4893.8  258.96  5001.5  257.50  5002.0  256.70  5007.5  257.50
  5082.2  259.39  5173.1  263.82  5268.8  265.90  5325.9  273.66  5457.9  285.83
#Mann=5,-1,0
  4619.8     0.1       0  4750.5    0.05       0  4893.8     0.1       0
  5001.5    0.07       0  5007.5     0.1       0
Bank Sta=5001.5,5007.5
Exp/Cntr=0.3,0.1

Type RM Length L Ch R = 1,8213,222,222,222
BEGIN DESCRIPTION:
Mapping XS 205e99a0
END DESCRIPTION:
XS GIS Cut Line= 4
      2141617.99     13383046.83      2141425.25     13383101.53
      2140982.54     13383335.91      2140870.56     13383635.38
#Sta/Elev= 30
  4490.8  282.81  4534.7  282.30  4539.9  282.84  4573.8  281.16  4580.8  281.86
  4607.7  280.71  4612.9  281.21  4646.8  278.13  4652.0  278.28  4685.9  275.00
  4688.7  274.13  4730.8  271.35  4752.8  268.64  4759.2  267.15  4813.2  257.91
  4835.2  256.31  4870.3  256.03  4923.2  256.66  5002.5  255.27  5003.0  254.47
  5008.0  254.47  5008.5  255.27  5109.9  257.08  5159.5  260.40  5194.3  261.70
  5228.2  264.29  5283.4  270.63  5313.7  272.73  5424.2  283.75  5511.8  286.73
#Mann=6,-1,0
  4490.8    0.05       0  4580.8     0.1       0  4759.2    0.05       0
  4870.3     0.1       0  5002.5    0.07       0  5008.5     0.1       0
Bank Sta=5002.5,5008.5
Exp/Cntr=0.3,0.1

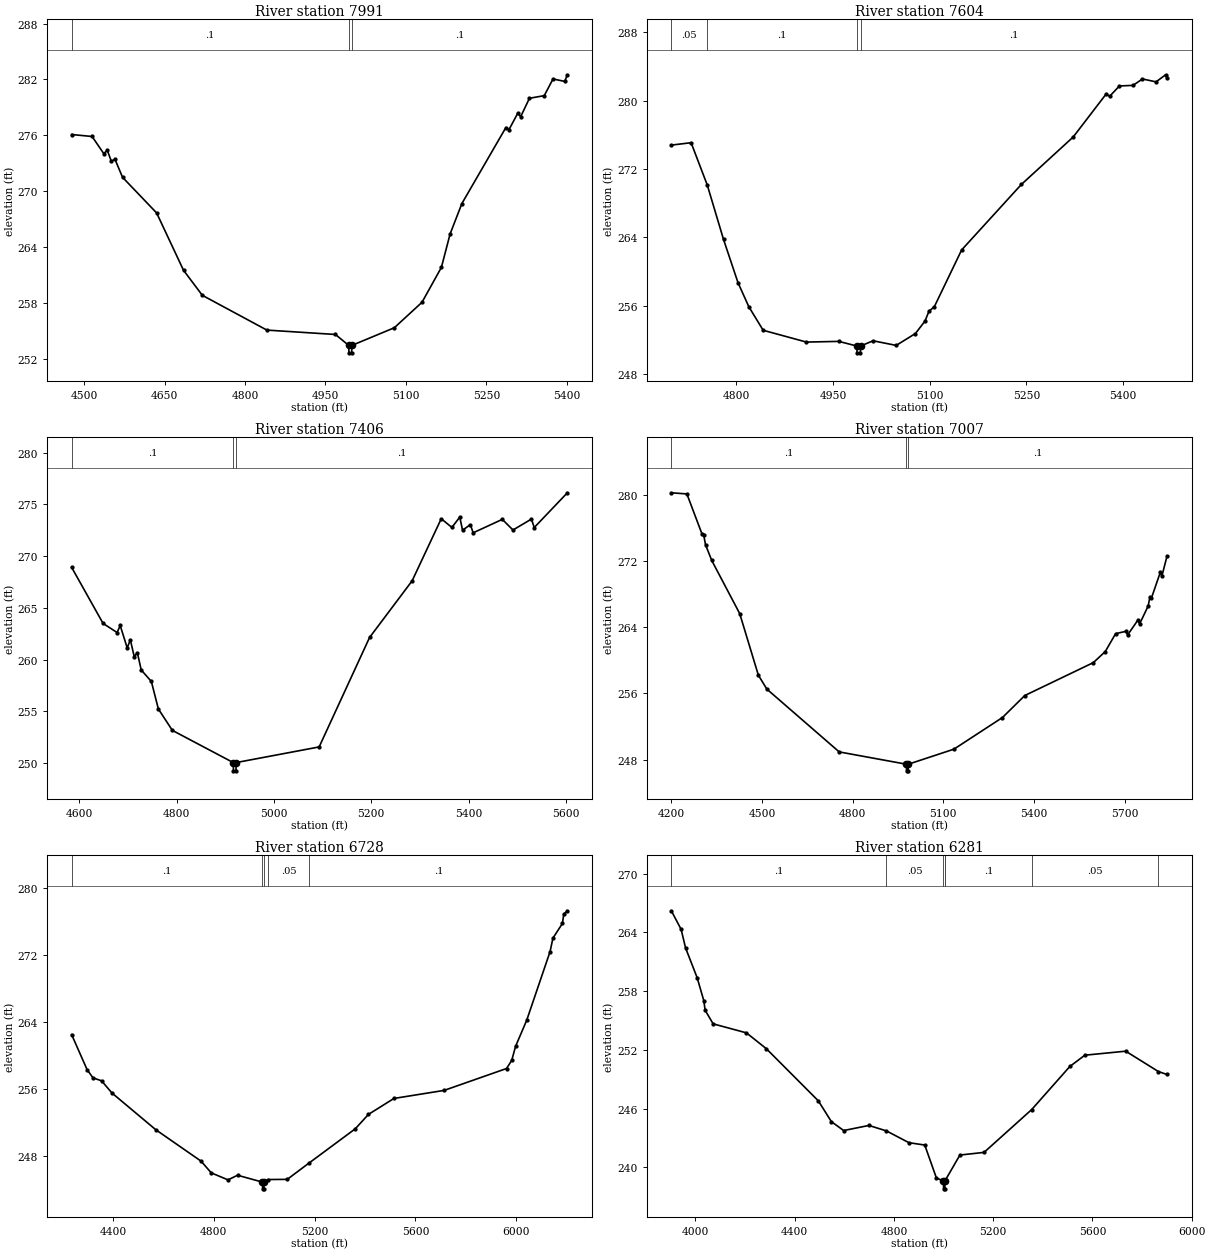
Type RM Length L Ch R = 1,7991,387,387,387
BEGIN DESCRIPTION:
UNT 013 in La Jarita Watershed 15.0
END DESCRIPTION:
XS GIS Cut Line= 3
      2141363.63     13382699.60      2141025.00     13383075.00
      2140656.13     13383272.55
#Sta/Elev= 30
  4476.9  276.09  4515.0  275.88  4536.7  274.05  4543.4  274.39  4550.9  273.22
  4557.6  273.44  4571.8  271.50  4635.3  267.68  4685.4  261.53  4720.5  258.84
  4840.8  255.11  4968.6  254.64  4993.3  253.47  4993.8  252.67  4998.8  252.67
  4999.3  253.47  5078.3  255.36  5129.9  258.09  5166.1  261.84  5182.3  265.42
  5204.3  268.69  5286.3  276.84  5292.0  276.61  5308.3  278.36  5313.9  278.01
  5330.2  279.98  5357.8  280.26  5374.1  282.05  5396.0  281.79  5400.9  282.50
#Mann=3,-1,0
  4476.9     0.1       0  4993.3    0.07       0  4999.3     0.1       0
Bank Sta=4993.3,4999.3
Exp/Cntr=0.3,0.1

Type RM Length L Ch R = 1,7604,198,198,198
BEGIN DESCRIPTION:
UNT 013 in La Jarita Watershed 14.0
END DESCRIPTION:
XS GIS Cut Line= 3
      2141124.97     13382625.01      2140825.00     13382775.00
      2140579.01     13383132.21
#Sta/Elev= 30
  4699.1  274.78  4729.8  275.06  4754.9  270.10  4780.1  263.74  4802.5  258.69
  4819.3  255.87  4841.6  253.11  4908.7  251.73  4959.0  251.81  4986.8  251.27
  4987.3  250.47  4992.3  250.47  4992.8  251.27  5012.1  251.88  5048.0  251.34
  5077.8  252.73  5092.7  254.19  5098.7  255.32  5107.3  255.89  5149.5  262.51
  5242.1  270.17  5322.6  275.73  5373.3  280.72  5379.4  280.51  5394.3  281.70
  5415.3  281.77  5430.1  282.52  5451.1  282.18  5466.0  283.01  5468.2  282.60
#Mann=4,-1,0
  4699.1    0.05       0  4754.9     0.1       0  4986.8    0.07       0
  4992.8     0.1       0
Bank Sta=4986.8,4992.8
Exp/Cntr=0.3,0.1

Type RM Length L Ch R = 1,7406,399,399,399
BEGIN DESCRIPTION:
UNT 013 in La Jarita Watershed 13.0
END DESCRIPTION:
XS GIS Cut Line= 3
      2141068.44     13382348.08      2140744.69     13382607.06
      2140456.49     13383137.99
#Sta/Elev= 30
  4584.4  268.92  4649.0  263.50  4677.8  262.62  4684.2  263.30  4698.6  261.13
  4705.0  261.92  4713.0  260.29  4719.4  260.68  4727.4  259.00  4748.2  257.89
  4762.6  255.23  4791.4  253.16  4916.5  250.05  4917.0  249.25  4922.1  249.25
  4922.6  250.05  5093.0  251.56  5196.6  262.14  5284.1  267.62  5343.9  273.62
  5365.8  272.78  5382.0  273.78  5387.7  272.51  5403.8  273.05  5409.5  272.26
  5469.4  273.56  5491.3  272.53  5529.3  273.59  5535.0  272.77  5603.1  276.13
#Mann=3,-1,0
  4584.4     0.1       0  4916.5    0.07       0  4922.6     0.1       0
Bank Sta=4916.5,4922.6
Exp/Cntr=0.3,0.1

Type RM Length L Ch R = 1,7007,279,279,279
BEGIN DESCRIPTION:
UNT 013 in La Jarita Watershed 12.0
END DESCRIPTION:
XS GIS Cut Line= 3
      2141225.01     13382225.00      2140449.12     13382413.05
      2140224.99     13383225.03
#Sta/Elev= 30
  4200.1  280.28  4251.6  280.14  4302.1  275.25  4307.2  275.19  4313.3  274.00
  4333.9  272.09  4426.5  265.66  4488.2  258.21  4516.2  256.53  4755.7  248.93
  4978.2  247.44  4978.7  246.64  4983.8  246.64  4984.3  247.44  5135.3  249.26
  5296.0  253.09  5369.9  255.75  5596.7  259.73  5636.3  261.07  5670.6  263.24
  5705.0  263.52  5710.2  263.07  5744.5  264.89  5749.7  264.39  5778.5  266.60
  5784.1  267.70  5789.2  267.55  5818.4  270.65  5823.6  270.19  5840.8  272.63
#Mann=3,-1,0
  4200.1     0.1       0  4978.2    0.07       0  4984.3     0.1       0
Bank Sta=4978.2,4984.3
Exp/Cntr=0.3,0.1

Type RM Length L Ch R = 1,6728,447,447,447
BEGIN DESCRIPTION:
UNT 013 in La Jarita Watershed 11.0
END DESCRIPTION:
XS GIS Cut Line= 4
      2140942.63     13381883.64      2140316.91     13382160.53
      2140000.77     13382686.60      2140143.77     13383340.95
#Sta/Elev= 30
  4235.5  262.52  4296.9  258.34  4320.1  257.37  4354.4  257.01  4395.5  255.56
  4569.5  251.18  4748.9  247.44  4790.0  246.03  4856.2  245.20  4894.1  245.75
  4993.1  244.93  4993.6  244.13  4998.7  244.13  4999.2  244.93  5016.2  245.24
  5091.3  245.26  5178.9  247.23  5361.4  251.29  5413.8  253.01  5514.9  254.91
  5714.1  255.87  5961.8  258.48  5982.3  259.44  5997.9  261.14  6041.8  264.23
  6134.7  272.43  6146.0  274.03  6183.7  275.78  6188.9  276.88  6203.3  277.29
#Mann=5,-1,0
  4235.5     0.1       0  4993.1    0.07       0  4999.2     0.1       0
  5016.2    0.05       0  5178.9     0.1       0
Bank Sta=4993.1,4999.2
Exp/Cntr=0.3,0.1

Type RM Length L Ch R = 1,6281,58,58,58
BEGIN DESCRIPTION:
Mapping XS c430050a
END DESCRIPTION:
XS GIS Cut Line= 5
      2140969.69     13381778.58      2140042.61     13382073.72
      2139962.74     13382028.58      2139848.16     13382066.78
      2139650.25     13382854.96
#Sta/Elev= 30
  3902.7  266.20  3942.3  264.30  3960.1  262.41  4006.8  259.37  4033.6  257.03
  4039.0  256.05  4071.2  254.66  4205.4  253.74  4285.4  252.13  4495.3  246.80
  4547.8  244.68  4597.3  243.77  4699.2  244.29  4770.0  243.73  4860.4  242.53
  4924.2  242.29  4971.1  238.93  4999.6  238.62  5000.1  237.82  5005.2  237.82
  5005.7  238.62  5005.8  238.64  5065.9  241.27  5163.2  241.54  5355.2  245.91
  5509.0  250.31  5569.5  251.46  5734.1  251.87  5865.9  249.79  5900.8  249.49
#Mann=7,-1,0
  3902.7     0.1       0  4770.0    0.05       0  4999.6   0.035       0
  5005.7    0.05       0  5005.8     0.1       0  5355.2    0.05       0
  5865.9     0.1       0
Bank Sta=4999.6,5005.7
Exp/Cntr=0.3,0.1

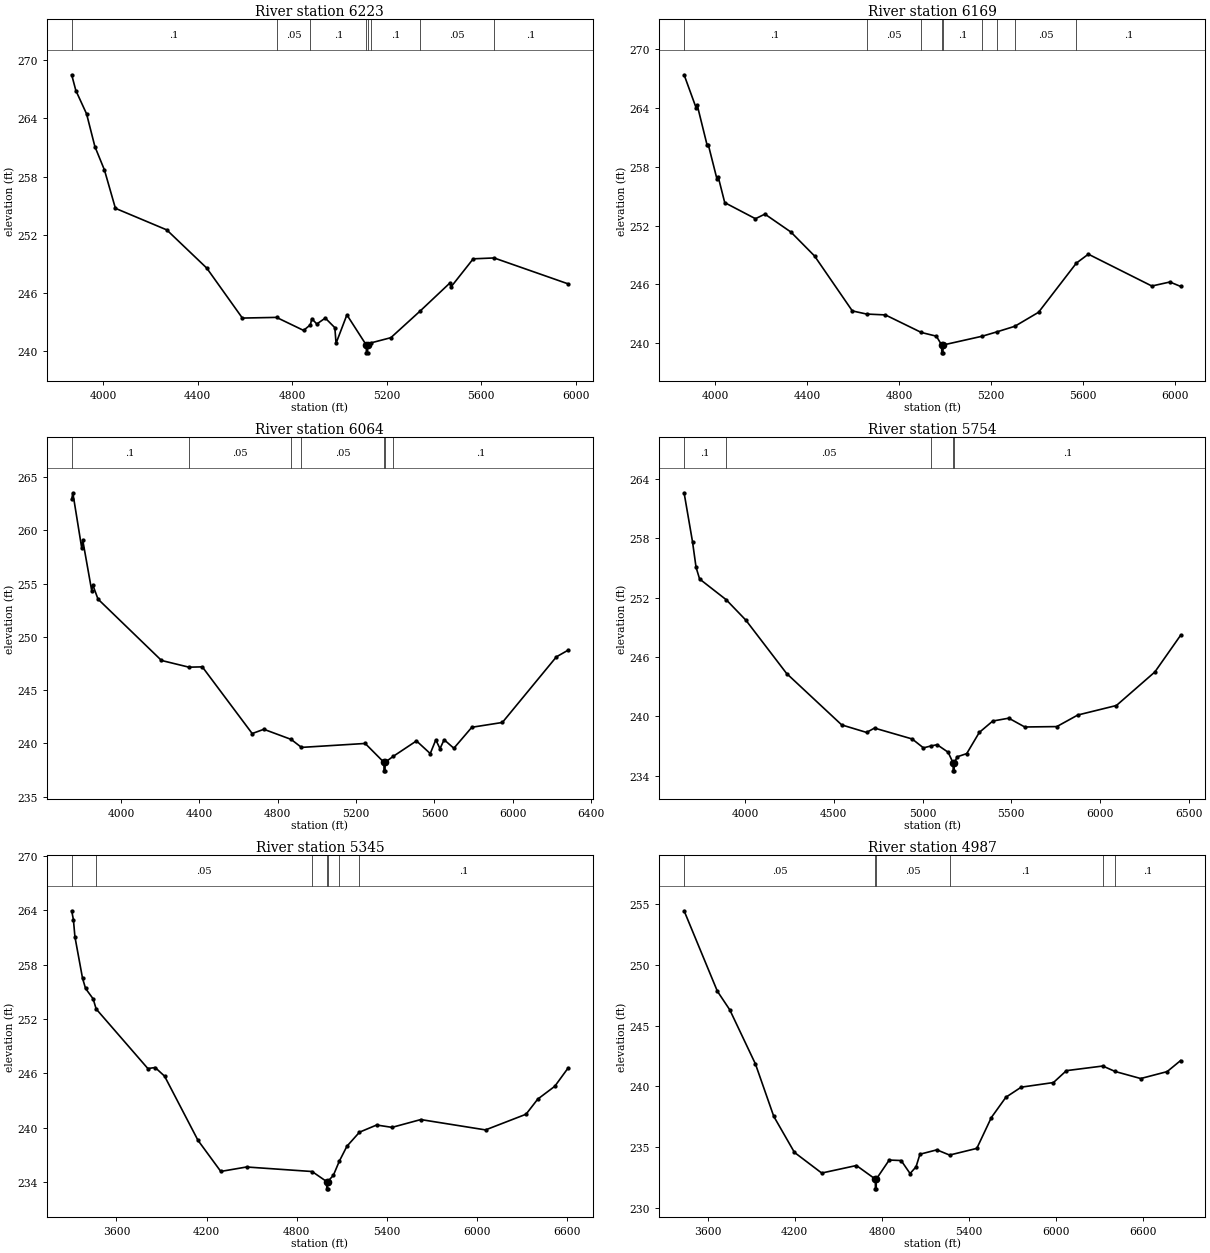
Type RM Length L Ch R = 1,6223,54,54,54
BEGIN DESCRIPTION:
Mapping XS d583915a
END DESCRIPTION:
XS GIS Cut Line= 5
      2140993.99     13381764.70      2140032.19     13382018.17
      2139987.05     13381969.56      2139855.11     13381993.86
      2139532.41     13382840.50
#Sta/Elev= 30
  3866.3  268.49  3883.9  266.87  3929.4  264.46  3964.5  261.10  4004.9  258.69
  4051.4  254.74  4268.6  252.52  4437.8  248.59  4588.7  243.44  4733.2  243.51
  4847.7  242.17  4876.6  242.75  4882.3  243.38  4903.8  242.83  4939.5  243.44
  4980.0  242.45  4985.1  240.84  5031.0  243.77  5113.1  240.66  5113.6  239.86
  5118.7  239.86  5119.2  240.66  5132.2  240.88  5217.0  241.42  5342.1  244.19
  5466.4  247.04  5471.8  246.65  5565.6  249.54  5653.9  249.63  5967.5  246.96
#Mann=8,-1,0
  3866.3     0.1       0  4733.2    0.05       0  4876.6     0.1       0
  5113.1    0.07       0  5119.2     0.1       0  5132.2     0.1       0
  5342.1    0.05       0  5653.9     0.1       0
Bank Sta=5113.1,5119.2
Exp/Cntr=0.3,0.1

Type RM Length L Ch R = 1,6169,105,105,105
BEGIN DESCRIPTION:
Mapping XS 57d9e0c7
END DESCRIPTION:
XS GIS Cut Line= 5
      2140987.03     13381747.34      2140056.49     13381962.61
      2140000.94     13381914.00      2139820.38     13381945.25
      2139473.15     13382823.74
#Sta/Elev= 30
  3865.6  267.39  3917.8  264.02  3923.0  264.26  3965.7  260.20  3970.8  260.25
  4008.4  256.75  4013.5  257.00  4042.2  254.34  4175.6  252.70  4216.7  253.17
  4329.6  251.34  4432.2  248.90  4596.4  243.29  4658.1  242.97  4740.1  242.88
  4896.1  241.09  4961.5  240.71  4984.5  239.81  4985.0  239.01  4990.1  239.01
  4990.6  239.81  5161.2  240.71  5225.7  241.16  5302.3  241.72  5405.4  243.15
  5569.7  248.17  5621.7  249.08  5897.5  245.83  5976.0  246.24  6022.4  245.79
#Mann=9,-1,0
  3865.6     0.1       0  4658.1    0.05       0  4896.1     0.1       0
  4984.5    0.07       0  4990.6     0.1       0  5161.2    0.05       0
  5225.7     0.1       0  5302.3    0.05       0  5569.7     0.1       0
Bank Sta=4984.5,4990.6
Exp/Cntr=0.3,0.1

Type RM Length L Ch R = 1,6064,310,310,310
BEGIN DESCRIPTION:
Mapping XS 29ec886d
END DESCRIPTION:
XS GIS Cut Line= 4
      2141046.79     13381519.06      2140166.57     13381696.15
      2139682.19     13381914.90      2138921.77     13382716.99
#Sta/Elev= 30
  3747.9  262.89  3753.7  263.52  3799.5  258.30  3804.6  259.05  3850.3  254.32
  3855.4  254.88  3882.3  253.54  4206.3  247.78  4346.5  247.15  4414.8  247.18
  4669.4  240.92  4728.9  241.32  4868.3  240.37  4920.9  239.62  5246.2  239.99
  5341.9  238.22  5342.4  237.42  5347.5  237.42  5348.0  238.22  5388.6  238.77
  5508.0  240.23  5578.4  239.04  5606.7  240.33  5628.1  239.50  5649.2  240.34
  5698.9  239.54  5790.7  241.51  5946.5  241.96  6222.3  248.12  6282.5  248.75
#Mann=7,-1,0
  3747.9     0.1       0  4346.5    0.05       0  4868.3     0.1       0
  4920.9    0.05       0  5341.9    0.03       0  5348.0    0.05       0
  5388.6     0.1       0
Bank Sta=5341.9,5348
Exp/Cntr=0.3,0.1

Type RM Length L Ch R = 1,5754,409,409,409
BEGIN DESCRIPTION:
Mapping XS 279238d6
END DESCRIPTION:
XS GIS Cut Line= 4
      2141062.40     13381482.61      2140072.82     13381456.57
      2139390.52     13381696.15      2138916.57     13382670.10
#Sta/Elev= 30
  3657.1  262.59  3704.5  257.65  3724.5  255.06  3744.5  253.88  3894.0  251.79
  4004.6  249.73  4234.7  244.33  4544.8  239.14  4684.7  238.38  4729.5  238.82
  4941.5  237.72  5005.1  236.82  5046.6  237.01  5082.2  237.14  5144.2  236.38
  5172.2  235.30  5172.7  234.50  5177.8  234.50  5178.3  235.30  5195.6  235.92
  5248.8  236.24  5319.6  238.38  5395.4  239.53  5485.6  239.82  5575.8  238.93
  5756.2  238.97  5874.5  240.14  6091.8  241.10  6308.5  244.49  6453.3  248.19
#Mann=5,-1,0
  3657.1     0.1       0  3894.0    0.05       0  5046.6     0.1       0
  5172.2    0.03       0  5178.3     0.1       0
Bank Sta=5172.2,5178.3
Exp/Cntr=0.3,0.1

Type RM Length L Ch R = 1,5345,358,358,358
BEGIN DESCRIPTION:
Mapping XS 67c6d342
END DESCRIPTION:
XS GIS Cut Line= 4
      2141266.39     13381312.47      2140323.68     13381171.84
      2139401.81     13381312.47      2138875.81     13382630.08
#Sta/Elev= 30
  3302.4  263.93  3313.9  262.95  3324.1  261.05  3374.6  256.49  3394.8  255.36
  3445.4  254.21  3465.3  253.10  3809.3  246.53  3858.1  246.64  3920.6  245.69
  4143.0  238.61  4294.7  235.18  4466.6  235.67  4902.4  235.17  4999.7  234.06
  5000.2  233.26  5005.3  233.26  5005.8  234.06  5043.7  234.74  5083.6  236.31
  5134.3  237.96  5217.9  239.51  5332.0  240.30  5434.4  240.04  5625.7  240.90
  6056.8  239.76  6326.3  241.49  6404.4  243.16  6517.6  244.57  6606.8  246.60
#Mann=7,-1,0
  3302.4     0.1       0  3465.3    0.05       0  4902.4     0.1       0
  4999.7    0.07       0  5005.8     0.1       0  5083.6    0.05       0
  5217.9     0.1       0
Bank Sta=4999.7,5005.8
Exp/Cntr=0.3,0.1

Type RM Length L Ch R = 1,4987,0,0,0
BEGIN DESCRIPTION:
UNT 013 in La Jarita Watershed 10.0
END DESCRIPTION:
XS GIS Cut Line= 4
      2141245.58     13381005.18      2140203.89     13380843.72
      2139354.93     13381036.43      2138771.91     13382410.69
#Sta/Elev= 30
  3438.1  254.45  3667.1  247.83  3752.4  246.30  3929.2  241.84  4055.2  237.53
  4197.6  234.56  4385.4  232.86  4624.4  233.48  4754.5  232.36  4755.0  231.56
  4760.4  231.56  4760.9  232.36  4850.0  233.93  4932.2  233.89  4993.6  232.82
  5034.6  233.37  5061.5  234.41  5178.1  234.77  5265.5  234.34  5452.9  234.89
  5553.0  237.43  5653.1  239.10  5758.6  239.93  5980.4  240.31  6069.7  241.29
  6319.9  241.67  6405.2  241.22  6581.1  240.64  6763.0  241.21  6855.6  242.12
#Mann=6,-1,0
  3438.1    0.05       0  4754.5    0.03       0  4760.9    0.05       0
  5265.5     0.1       0  6319.9    0.05       0  6405.2     0.1       0
Bank Sta=4754.5,4760.9
Exp/Cntr=0.3,0.1

Chan Stop Cuts=-1