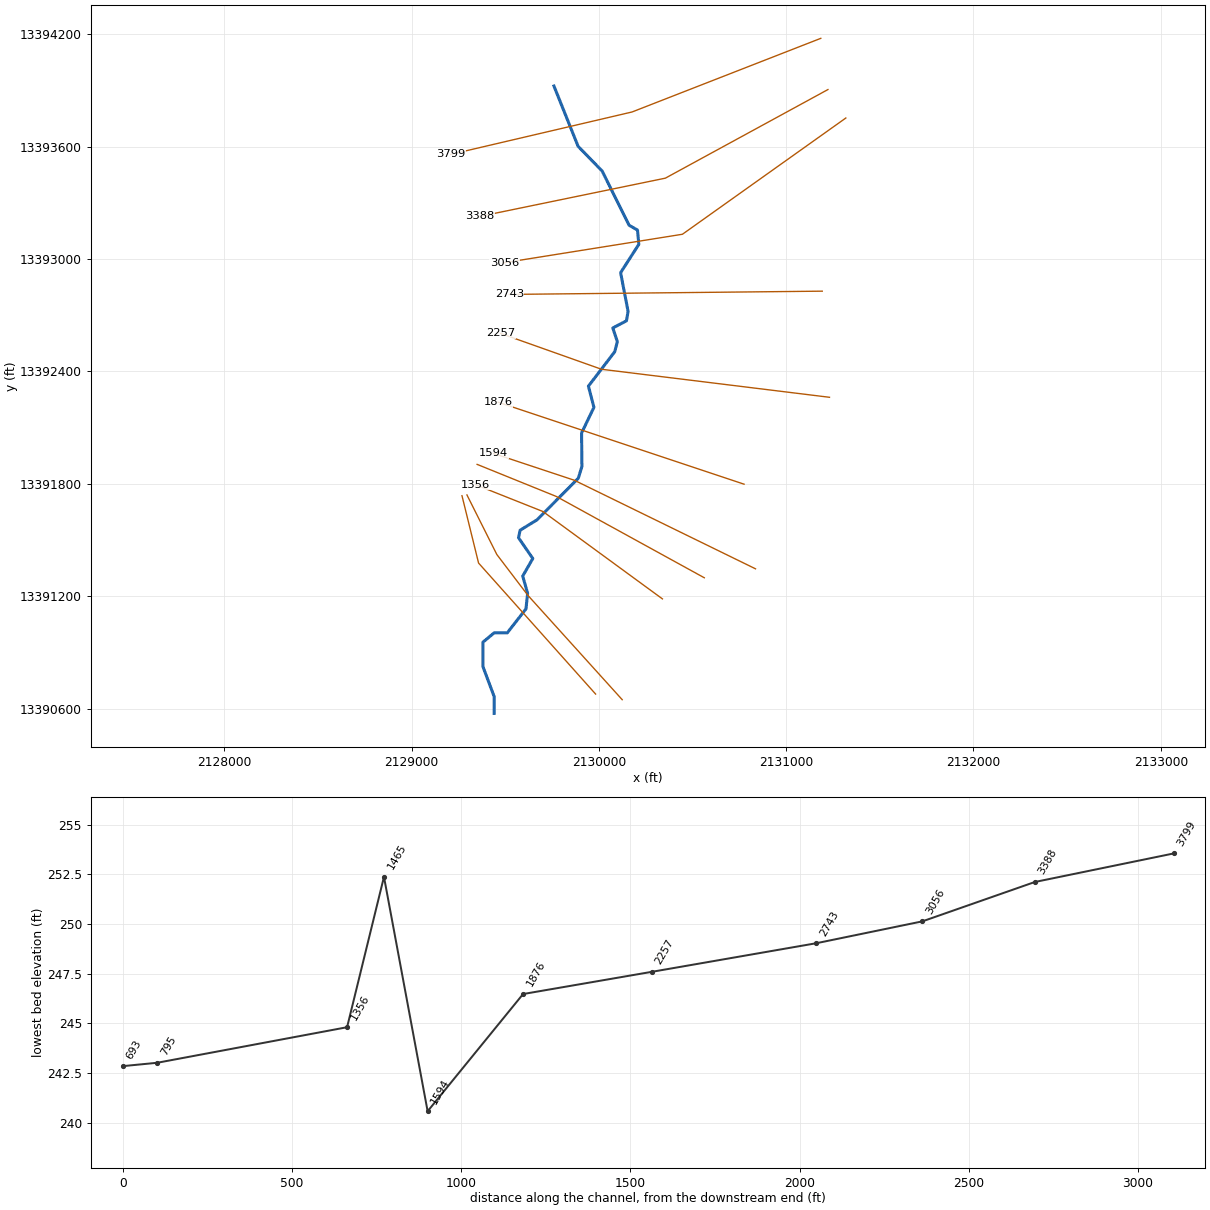
--- UNT 017 in La Jarita Watershed.prj (project) ---

Proj Title=UNT 017 in La Jarita Watershed Base Level Engineering
Current Plan=p01
Default Exp/Contr=0.3,0.1
English Units
Geom File=g01
Flow File=f01
Plan File=p01
BEGIN DESCRIPTION:
UNT 017 in La Jarita Watershed
END DESCRIPTION:

--- UNT 017 in La Jarita Watershed.p01 (plan) ---

Plan Title=Multiple Run
Short Identifier=Multiple
Geom File=g01
Flow File=f01
Subcritical Flow
K Sum by GR= 0
Std Step Tol= 0.01
Critical Tol= 0.01
Num of Std Step Trials= 20
Max Error Tol= 0.3
Flow Tol Ratio= 0.001
Split Flow NTrial= 30
Split Flow Tol= 0.02
Split Flow Ratio= 0.02
Log Output Level= 0
Friction Slope Method= 1
Unsteady Friction Slope Method= 2
Unsteady Bridges Friction Slope Method= 1
Parabolic Critical Depth
Global Vel Dist=  1 , 1 , 1
Global Log Level= 0
CheckData=True
Encroach Param= -1, 0, 0, 0
BEGIN DESCRIPTION:
Multiple Run
END DESCRIPTION:

--- UNT 017 in La Jarita Watershed.f01 (steady flow) ---

Flow Title=Multiple
Number of Profiles=7
Profile Names=10-year,25-year,50-year,1pct_min,100-year,1pct_plu,500-year
River Rch & RM= UNT 017 in La Ja,Reach-1,3799
     167     228     278     169     338     674     505
River Rch & RM= UNT 017 in La Ja,Reach-1,3056
     195     268     328     200     399     796     601
Boundary for River Rch & Prof#=UNT 017 in La Ja,Reach-1,1
Up Type=0
Dn Type=3
Dn Slope=0.005
Boundary for River Rch & Prof#=UNT 017 in La Ja,Reach-1,2
Up Type=0
Dn Type=3
Dn Slope=0.005
Boundary for River Rch & Prof#=UNT 017 in La Ja,Reach-1,3
Up Type=0
Dn Type=3
Dn Slope=0.005
Boundary for River Rch & Prof#=UNT 017 in La Ja,Reach-1,4
Up Type=0
Dn Type=3
Dn Slope=0.005
Boundary for River Rch & Prof#=UNT 017 in La Ja,Reach-1,5
Up Type=0
Dn Type=3
Dn Slope=0.005
Boundary for River Rch & Prof#=UNT 017 in La Ja,Reach-1,6
Up Type=0
Dn Type=3
Dn Slope=0.005
Boundary for River Rch & Prof#=UNT 017 in La Ja,Reach-1,7
Up Type=0
Dn Type=3
Dn Slope=0.005

--- UNT 017 in La Jarita Watershed.g01 (geometry) ---

Geom Title=Existing Conditions

River Reach=UNT 017 in La Ja,Reach-1
Reach XY= 30
      2129760.07     13393924.00      2129889.19     13393601.73
      2130017.23     13393470.44      2130161.04     13393180.84
      2130206.18     13393154.80      2130213.13     13393078.41
      2130115.91     13392927.36      2130155.84     13392720.77
      2130147.16     13392670.42      2130074.24     13392632.23
      2130098.55     13392559.31      2130084.66     13392505.49
      2129944.03     13392321.46      2129973.55     13392208.61
      2129907.57     13392071.46      2129909.31     13391892.64
      2129890.21     13391830.14      2129669.73     13391607.92
      2129579.45     13391552.36      2129570.77     13391512.43
      2129647.16     13391401.32      2129593.34     13391307.57
      2129619.38     13391215.56      2129610.70     13391132.23
      2129510.80     13391004.54      2129440.80     13391004.54
      2129380.80     13390954.54      2129380.80     13390824.54
      2129440.80     13390664.54      2129440.80     13390574.54

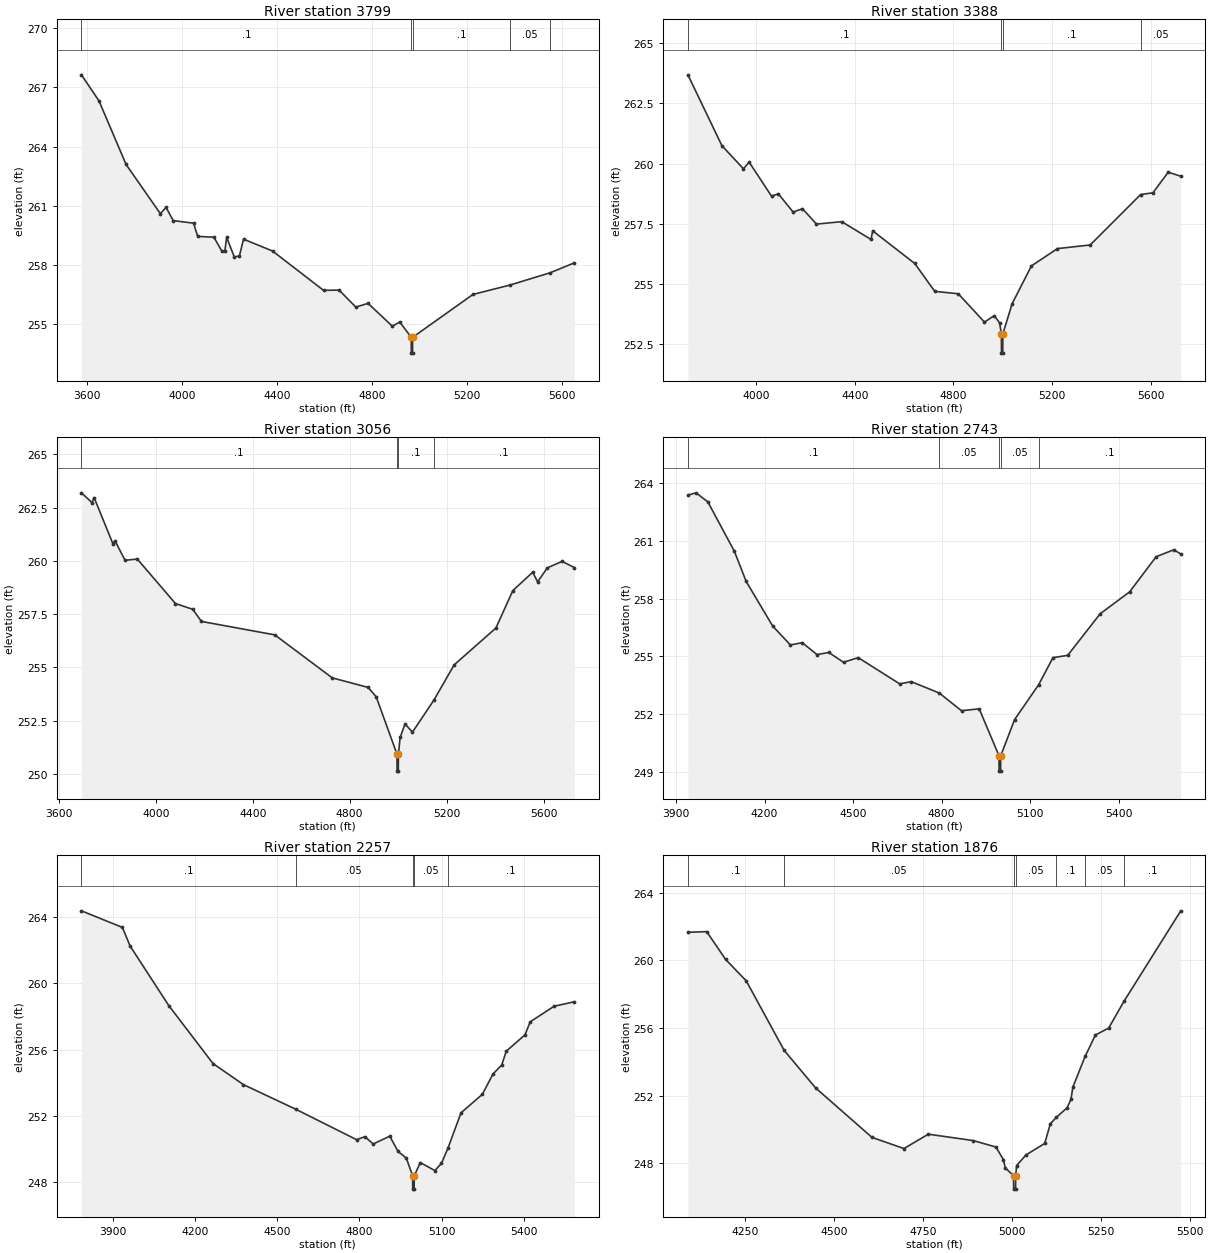
Type RM Length L Ch R = 1,3799,411,411,411
BEGIN DESCRIPTION:
UNT 017 in La Jarita Watershed 2.0
END DESCRIPTION:
XS GIS Cut Line= 3
      2131184.77     13394178.56      2130176.95     13393785.33
      2129209.08     13393558.97
#Sta/Elev= 30
  3575.9  267.64  3649.9  266.32  3764.0  263.10  3908.4  260.61  3932.4  260.93
  3962.3  260.26  4048.0  260.13  4065.6  259.46  4133.8  259.42  4166.0  258.74
  4179.7  258.70  4187.5  259.41  4219.7  258.42  4241.2  258.47  4258.5  259.32
  4380.7  258.72  4595.4  256.73  4661.3  256.74  4731.6  255.88  4783.0  256.07
  4885.7  254.91  4916.5  255.13  4964.8  254.35  4965.3  253.55  4970.3  253.55
  4970.8  254.35  5224.6  256.52  5381.7  257.00  5550.4  257.62  5651.7  258.12
#Mann=5,-1,0
  3575.9     0.1       0  4964.8    0.07       0  4970.8     0.1       0
  5381.7    0.05       0  5550.4     0.1       0
Bank Sta=4964.8,4970.8
Exp/Cntr=0.3,0.1

Type RM Length L Ch R = 1,3388,332,332,332
BEGIN DESCRIPTION:
Mapping XS 84742b77
END DESCRIPTION:
XS GIS Cut Line= 3
      2131222.93     13393905.11      2130354.91     13393432.03
      2129365.29     13393228.03
#Sta/Elev= 30
  3722.9  263.69  3860.9  260.74  3948.3  259.78  3971.1  260.06  4062.2  258.64
  4089.7  258.74  4149.6  257.98  4187.5  258.12  4244.4  257.48  4346.9  257.58
  4465.7  256.84  4472.2  257.20  4643.0  255.84  4724.1  254.68  4819.6  254.58
  4925.8  253.40  4965.4  253.67  4987.1  253.37  4994.3  252.91  4994.8  252.11
  4999.8  252.11  5000.3  252.91  5038.1  254.17  5116.2  255.74  5221.9  256.46
  5354.6  256.61  5559.1  258.71  5608.9  258.78  5671.1  259.64  5721.9  259.47
#Mann=4,-1,0
  3722.9     0.1       0  4994.3    0.07       0  5000.3     0.1       0
  5559.1    0.05       0
Bank Sta=4994.3,5000.3
Exp/Cntr=0.3,0.1

Type RM Length L Ch R = 1,3056,313,313,313
BEGIN DESCRIPTION:
Mapping XS efc2e777
END DESCRIPTION:
XS GIS Cut Line= 3
      2131318.42     13393753.19      2130446.05     13393132.55
      2129495.53     13392980.64
#Sta/Elev= 30
  3693.5  263.20  3737.1  262.74  3745.7  262.98  3823.2  260.81  3831.8  260.95
  3873.6  260.03  3924.0  260.09  4081.4  258.00  4152.7  257.73  4188.6  257.16
  4490.9  256.53  4728.2  254.51  4876.6  254.06  4909.5  253.62  4995.1  250.93
  4995.6  250.13  5000.6  250.13  5001.1  250.93  5008.2  251.71  5028.5  252.35
  5058.9  251.96  5146.7  253.45  5231.0  255.12  5403.2  256.85  5473.2  258.61
  5555.1  259.47  5575.3  259.02  5615.8  259.68  5676.6  259.98  5726.7  259.69
#Mann=4,-1,0
  3693.5     0.1       0  4995.1    0.03       0  5001.1     0.1       0
  5146.7     0.1       0
Bank Sta=4995.1,5001.1
Exp/Cntr=0.3,0.1

Type RM Length L Ch R = 1,2743,486,486,486
BEGIN DESCRIPTION:
Mapping XS da370870
END DESCRIPTION:
XS GIS Cut Line= 2
      2131192.61     13392828.73      2129521.60     13392811.37
#Sta/Elev= 30
  3939.9  263.38  3967.5  263.50  4007.5  263.03  4097.5  260.46  4137.5  258.89
  4227.5  256.57  4287.5  255.59  4327.5  255.71  4377.5  255.09  4417.5  255.20
  4467.5  254.69  4517.5  254.93  4657.6  253.57  4697.6  253.68  4792.3  253.09
  4867.6  252.17  4927.6  252.27  4994.6  249.83  4995.1  249.03  5000.1  249.03
  5000.6  249.83  5047.6  251.71  5129.4  253.53  5177.6  254.93  5227.6  255.05
  5337.6  257.21  5437.6  258.35  5527.6  260.18  5587.6  260.54  5611.0  260.32
#Mann=5,-1,0
  3939.9     0.1       0  4792.3    0.05       0  4994.6    0.03       0
  5000.6    0.05       0  5129.4     0.1       0
Bank Sta=4994.6,5000.6
Exp/Cntr=0.3,0.1

Type RM Length L Ch R = 1,2257,381,381,381
BEGIN DESCRIPTION:
Mapping XS ffbc77ef
END DESCRIPTION:
XS GIS Cut Line= 3
      2131231.21     13392262.09      2130013.77     13392411.83
      2129475.57     13392602.81
#Sta/Elev= 30
  3786.1  264.36  3935.6  263.36  3963.6  262.24  4104.7  258.65  4265.9  255.16
  4376.7  253.89  4567.1  252.41  4789.8  250.57  4820.0  250.75  4850.3  250.31
  4910.7  250.78  4941.0  249.86  4971.2  249.46  4994.0  248.39  4994.5  247.59
  4999.6  247.59  5000.1  248.39  5022.0  249.19  5075.1  248.71  5099.3  249.14
  5123.2  250.07  5170.6  252.19  5248.3  253.30  5287.3  254.53  5319.1  255.07
  5335.6  255.90  5404.0  256.89  5422.9  257.67  5510.1  258.61  5583.8  258.88
#Mann=5,-1,0
  3786.1     0.1       0  4567.1    0.05       0  4994.0    0.03       0
  5000.1    0.05       0  5123.2     0.1       0
Bank Sta=4994,5000.1
Exp/Cntr=0.3,0.1

Type RM Length L Ch R = 1,1876,282,282,282
BEGIN DESCRIPTION:
Mapping XS 62b563f1
END DESCRIPTION:
XS GIS Cut Line= 2
      2130775.07     13391798.19      2129462.57     13392235.69
#Sta/Elev= 30
  4090.6  261.66  4143.4  261.70  4196.3  260.06  4254.3  258.79  4360.7  254.68
  4449.3  252.45  4607.4  249.53  4697.0  248.87  4765.5  249.72  4892.0  249.34
  4955.2  248.96  4976.1  248.22  4981.6  247.72  5004.6  247.27  5005.1  246.47
  5010.3  246.47  5010.8  247.27  5013.2  247.86  5039.4  248.49  5092.1  249.17
  5108.1  250.34  5124.7  250.71  5155.3  251.29  5165.9  251.79  5171.3  252.51
  5205.8  254.33  5234.6  255.59  5271.5  255.99  5315.0  257.59  5474.1  262.93
#Mann=7,-1,0
  4090.6     0.1       0  4360.7    0.05       0  5004.6    0.03       0
  5010.8    0.05       0  5124.7     0.1       0  5205.8    0.05       0
  5315.0     0.1       0
Bank Sta=5004.6,5010.8
Exp/Cntr=0.3,0.1

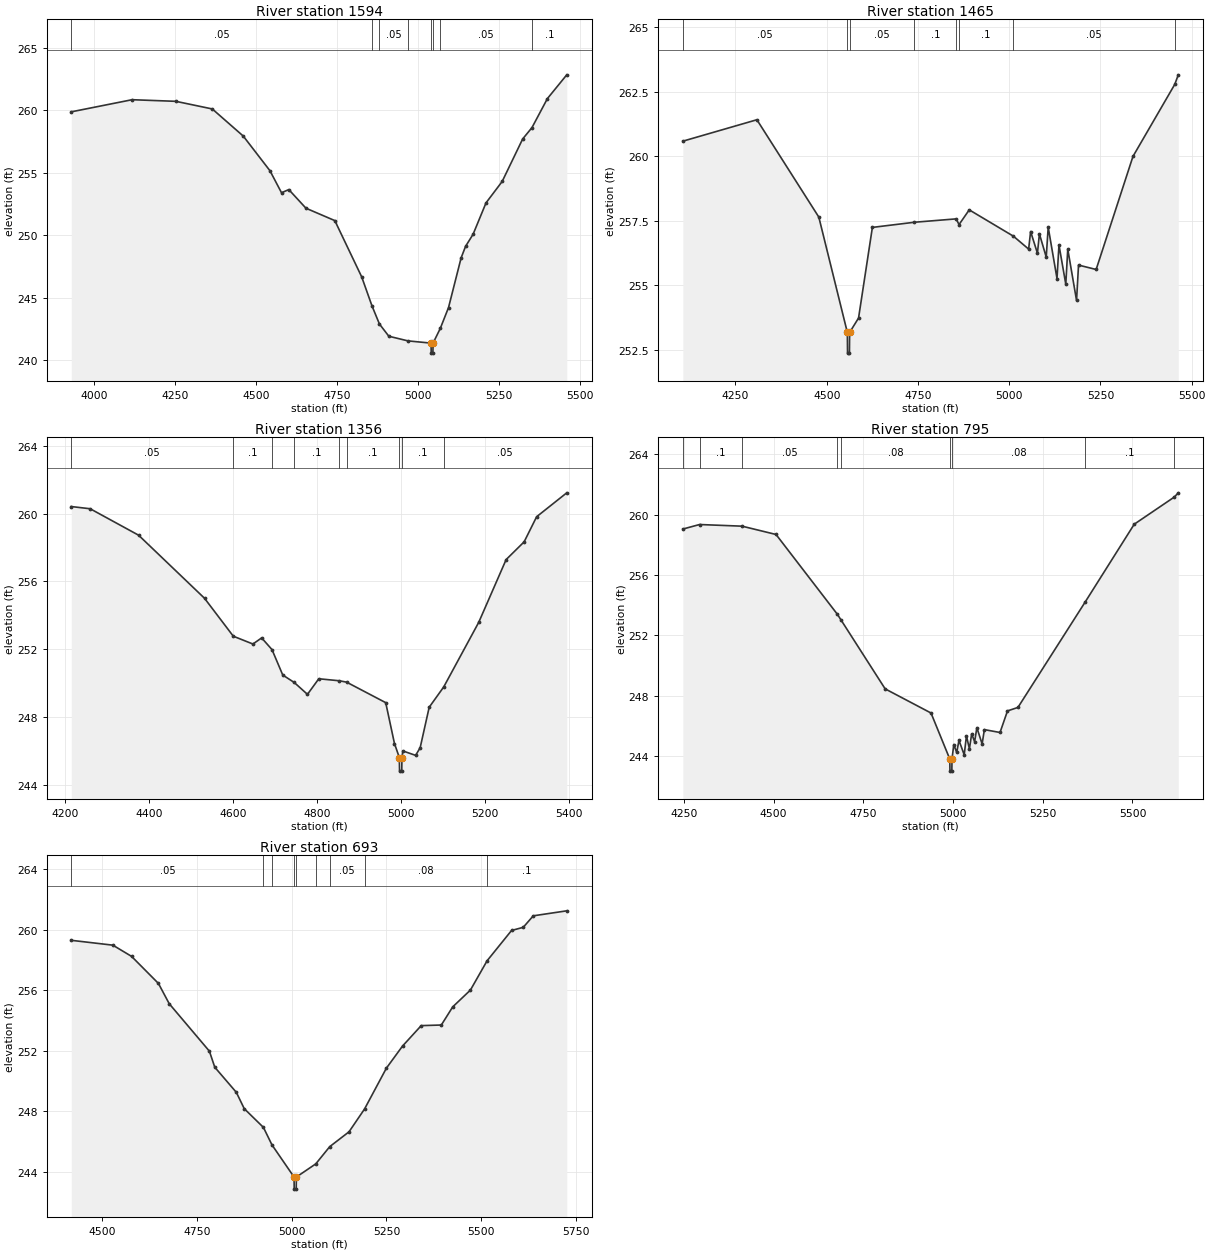
Type RM Length L Ch R = 1,1594,129,129,129
BEGIN DESCRIPTION:
Mapping XS 859b069a
END DESCRIPTION:
XS GIS Cut Line= 3
      2130836.29     13391346.28      2129868.37     13391819.39
      2129438.27     13391962.03
#Sta/Elev= 30
  3928.7  259.87  4116.6  260.84  4251.7  260.71  4364.2  260.10  4459.9  257.93
  4542.3  255.16  4578.0  253.40  4600.6  253.65  4653.6  252.16  4742.7  251.17
  4825.7  246.67  4857.5  244.35  4880.5  242.90  4909.6  241.92  4968.5  241.55
  5040.0  241.37  5040.5  240.57  5045.7  240.57  5046.2  241.37  5068.4  242.54
  5093.9  244.21  5132.9  248.19  5146.6  249.11  5169.9  250.08  5209.8  252.59
  5259.7  254.30  5323.0  257.70  5351.8  258.61  5399.4  260.93  5459.2  262.83
#Mann=8,-1,0
  3928.7    0.05       0  4857.5     0.1       0  4880.5    0.05       0
  4968.5     0.1       0  5040.0    0.07       0  5046.2     0.1       0
  5068.4    0.05       0  5351.8     0.1       0
Bank Sta=5040,5046.2
Exp/Cntr=0.3,0.1

Type RM Length L Ch R = 1,1465,109,109,109
BEGIN DESCRIPTION:
Mapping XS 2210841d
END DESCRIPTION:
XS GIS Cut Line= 3
      2130562.80     13391298.56      2129772.88     13391732.58
      2129349.88     13391903.95
#Sta/Elev= 30
  4105.8  260.58  4308.7  261.41  4478.4  257.64  4556.6  253.17  4557.1  252.37
  4562.3  252.37  4562.8  253.17  4587.3  253.73  4625.2  257.24  4740.6  257.44
  4854.6  257.57  4862.7  257.35  4890.6  257.92  5011.6  256.90  5053.4  256.40
  5058.8  257.08  5077.5  256.24  5082.9  256.99  5101.6  256.09  5107.0  257.25
  5131.1  255.26  5136.5  256.56  5155.2  255.04  5160.6  256.40  5184.7  254.41
  5190.1  255.78  5238.4  255.61  5339.3  259.99  5453.8  262.78  5463.5  263.15
#Mann=8,-1,0
  4105.8    0.05       0  4556.6    0.07       0  4562.8    0.05       0
  4740.6     0.1       0  4854.6    0.05       0  4862.7     0.1       0
  5011.6    0.05       0  5453.8     0.1       0
Bank Sta=4556.6,4562.8
Exp/Cntr=0.3,0.1

Type RM Length L Ch R = 1,1356,561,561,561
BEGIN DESCRIPTION:
Mapping XS 040572fd
END DESCRIPTION:
XS GIS Cut Line= 3
      2130339.30     13391185.70      2129701.27     13391652.29
      2129341.03     13391795.51
#Sta/Elev= 30
  4215.9  260.41  4260.8  260.28  4375.9  258.72  4532.6  255.00  4601.1  252.76
  4647.7  252.30  4668.5  252.66  4693.1  251.97  4718.7  250.47  4746.0  250.03
  4777.4  249.33  4804.4  250.25  4853.5  250.13  4870.5  250.05  4963.5  248.84
  4984.3  246.43  4995.9  245.60  4996.4  244.80  5001.6  244.80  5002.1  245.60
  5004.4  245.99  5034.6  245.73  5045.4  246.18  5066.9  248.57  5101.5  249.77
  5184.7  253.58  5249.8  257.28  5292.7  258.33  5322.4  259.81  5394.0  261.22
#Mann=9,-1,0
  4215.9    0.05       0  4601.1     0.1       0  4693.1    0.05       0
  4746.0     0.1       0  4853.5    0.05       0  4870.5     0.1       0
  4995.9    0.07       0  5002.1     0.1       0  5101.5    0.05       0
Bank Sta=4995.9,5002.1
Exp/Cntr=0.3,0.1

Type RM Length L Ch R = 1,795,102,102,102
BEGIN DESCRIPTION:
Mapping XS 8661a2df
END DESCRIPTION:
XS GIS Cut Line= 4
      2130124.42     13390647.65      2129621.84     13391203.61
      2129455.01     13391422.88      2129295.53     13391740.85
#Sta/Elev= 30
  4247.0  259.05  4293.6  259.35  4412.1  259.24  4506.7  258.69  4677.7  253.40
  4688.5  253.00  4810.8  248.46  4938.6  246.86  4990.9  243.81  4991.4  243.01
  4996.6  243.01  4997.1  243.81  5002.0  244.77  5010.2  244.25  5016.5  245.05
  5031.1  244.09  5037.3  245.35  5045.6  244.49  5051.9  245.48  5060.1  244.96
  5066.4  245.89  5081.0  244.81  5087.3  245.76  5130.9  245.57  5151.7  247.00
  5180.8  247.23  5368.6  254.23  5504.9  259.37  5616.6  261.17  5627.7  261.45
#Mann=9,-1,0
  4247.0    0.05       0  4293.6     0.1       0  4412.1    0.05       0
  4677.7     0.1       0  4688.5    0.08       0  4990.9    0.07       0
  4997.1    0.08       0  5368.6     0.1       0  5616.6    0.05       0
Bank Sta=4990.9,4997.1
Exp/Cntr=0.3,0.1

Type RM Length L Ch R = 1,693,0,0,0
BEGIN DESCRIPTION:
UNT 017 in La Jarita Watershed 1.0
END DESCRIPTION:
XS GIS Cut Line= 3
      2129982.50     13390677.59      2129357.58     13391377.17
      2129269.03     13391736.58
#Sta/Elev= 30
  4417.8  259.29  4527.5  258.97  4576.8  258.23  4647.8  256.44  4676.3  255.10
  4782.4  251.96  4796.6  250.90  4853.5  249.24  4874.4  248.16  4925.1  246.92
  4947.5  245.77  5005.9  243.64  5006.4  242.84  5011.6  242.84  5012.1  243.64
  5063.3  244.51  5100.2  245.65  5151.1  246.63  5192.1  248.14  5249.8  250.84
  5292.4  252.30  5341.7  253.65  5394.8  253.69  5424.9  254.89  5471.6  256.00
  5515.7  257.94  5580.2  259.94  5611.1  260.15  5637.6  260.91  5726.0  261.24
#Mann=9,-1,0
  4417.8    0.05       0  4925.1    0.08       0  4947.5    0.05       0
  5005.9   0.035       0  5012.1    0.05       0  5063.3    0.08       0
  5100.2    0.05       0  5192.1    0.08       0  5515.7     0.1       0
Bank Sta=5005.9,5012.1
Exp/Cntr=0.3,0.1

Chan Stop Cuts=-1