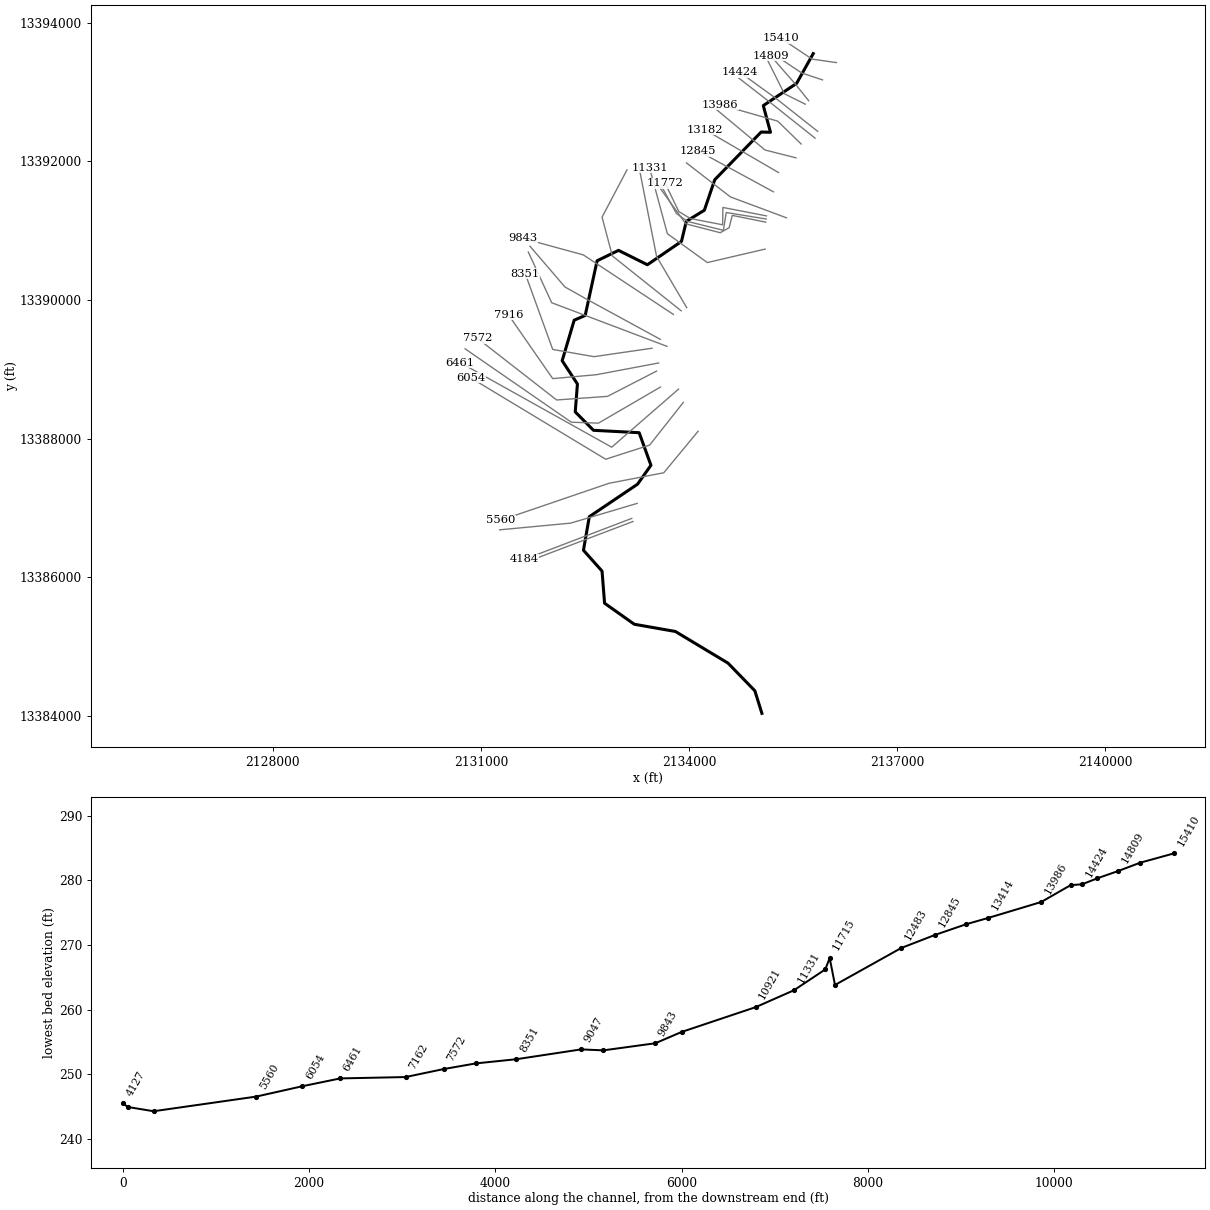
--- UNT 018 in La Jarita Watershed.prj (project) ---

Proj Title=UNT 018 in La Jarita Watershed Base Level Engineering
Current Plan=p01
Default Exp/Contr=0.3,0.1
English Units
Geom File=g01
Flow File=f01
Plan File=p01
BEGIN DESCRIPTION:
UNT 018 in La Jarita Watershed
END DESCRIPTION:

--- UNT 018 in La Jarita Watershed.p01 (plan) ---

Plan Title=Multiple Run
Short Identifier=Multiple
Geom File=g01
Flow File=f01
Subcritical Flow
K Sum by GR= 0
Std Step Tol= 0.01
Critical Tol= 0.01
Num of Std Step Trials= 20
Max Error Tol= 0.3
Flow Tol Ratio= 0.001
Split Flow NTrial= 30
Split Flow Tol= 0.02
Split Flow Ratio= 0.02
Log Output Level= 0
Friction Slope Method= 1
Unsteady Friction Slope Method= 2
Unsteady Bridges Friction Slope Method= 1
Parabolic Critical Depth
Global Vel Dist=  1 , 1 , 1
Global Log Level= 0
CheckData=True
Encroach Param= -1, 0, 0, 0
BEGIN DESCRIPTION:
Multiple Run
END DESCRIPTION:

--- UNT 018 in La Jarita Watershed.f01 (steady flow) ---

Flow Title=Multiple
Number of Profiles=7
Profile Names=10-year,25-year,50-year,1pct_min,100-year,1pct_plu,500-year
River Rch & RM= UNT 018 in La Ja,Reach-1,15410
     139     186     222     133     266     530     385
River Rch & RM= UNT 018 in La Ja,Reach-1,13182
     177     240     290     175     349     696     513
River Rch & RM= UNT 018 in La Ja,Reach-1,6461
     227     311     379     230     459     917     686
River Rch & RM= UNT 018 in La Ja,Reach-1,1625
     230     315     384     233     465     928     694
Boundary for River Rch & Prof#=UNT 018 in La Ja,Reach-1,1
Up Type=0
Dn Type=3
Dn Slope=0.005
Boundary for River Rch & Prof#=UNT 018 in La Ja,Reach-1,2
Up Type=0
Dn Type=3
Dn Slope=0.005
Boundary for River Rch & Prof#=UNT 018 in La Ja,Reach-1,3
Up Type=0
Dn Type=3
Dn Slope=0.005
Boundary for River Rch & Prof#=UNT 018 in La Ja,Reach-1,4
Up Type=0
Dn Type=3
Dn Slope=0.005
Boundary for River Rch & Prof#=UNT 018 in La Ja,Reach-1,5
Up Type=0
Dn Type=3
Dn Slope=0.005
Boundary for River Rch & Prof#=UNT 018 in La Ja,Reach-1,6
Up Type=0
Dn Type=3
Dn Slope=0.005
Boundary for River Rch & Prof#=UNT 018 in La Ja,Reach-1,7
Up Type=0
Dn Type=3
Dn Slope=0.005

--- UNT 018 in La Jarita Watershed.g01 (geometry) ---

Geom Title=Existing Conditions

River Reach=UNT 018 in La Ja,Reach-1
Reach XY= 30
      2135790.80     13393554.54      2135550.80     13393124.54
      2135070.80     13392804.54      2135174.32     13392419.43
      2135039.77     13392422.90      2134370.80     13391734.54
      2134220.80     13391294.54      2133960.80     13391134.54
      2133890.80     13390844.54      2133399.15     13390507.97
      2132983.35     13390715.44      2132674.32     13390565.26
      2132502.73     13389776.81      2132343.88     13389707.80
      2132170.70     13389123.17      2132390.76     13388787.23
      2132359.12     13388384.76      2132622.14     13388119.13
      2133280.80     13388084.54      2133450.80     13387614.54
      2133257.47     13387341.44      2132562.15     13386872.69
      2132477.52     13386388.32      2132745.75     13386087.54
      2132782.21     13385623.99      2133210.59     13385320.61
      2133803.04     13385216.44      2134562.15     13384759.41
      2134948.87     13384360.97      2135050.80     13384034.54

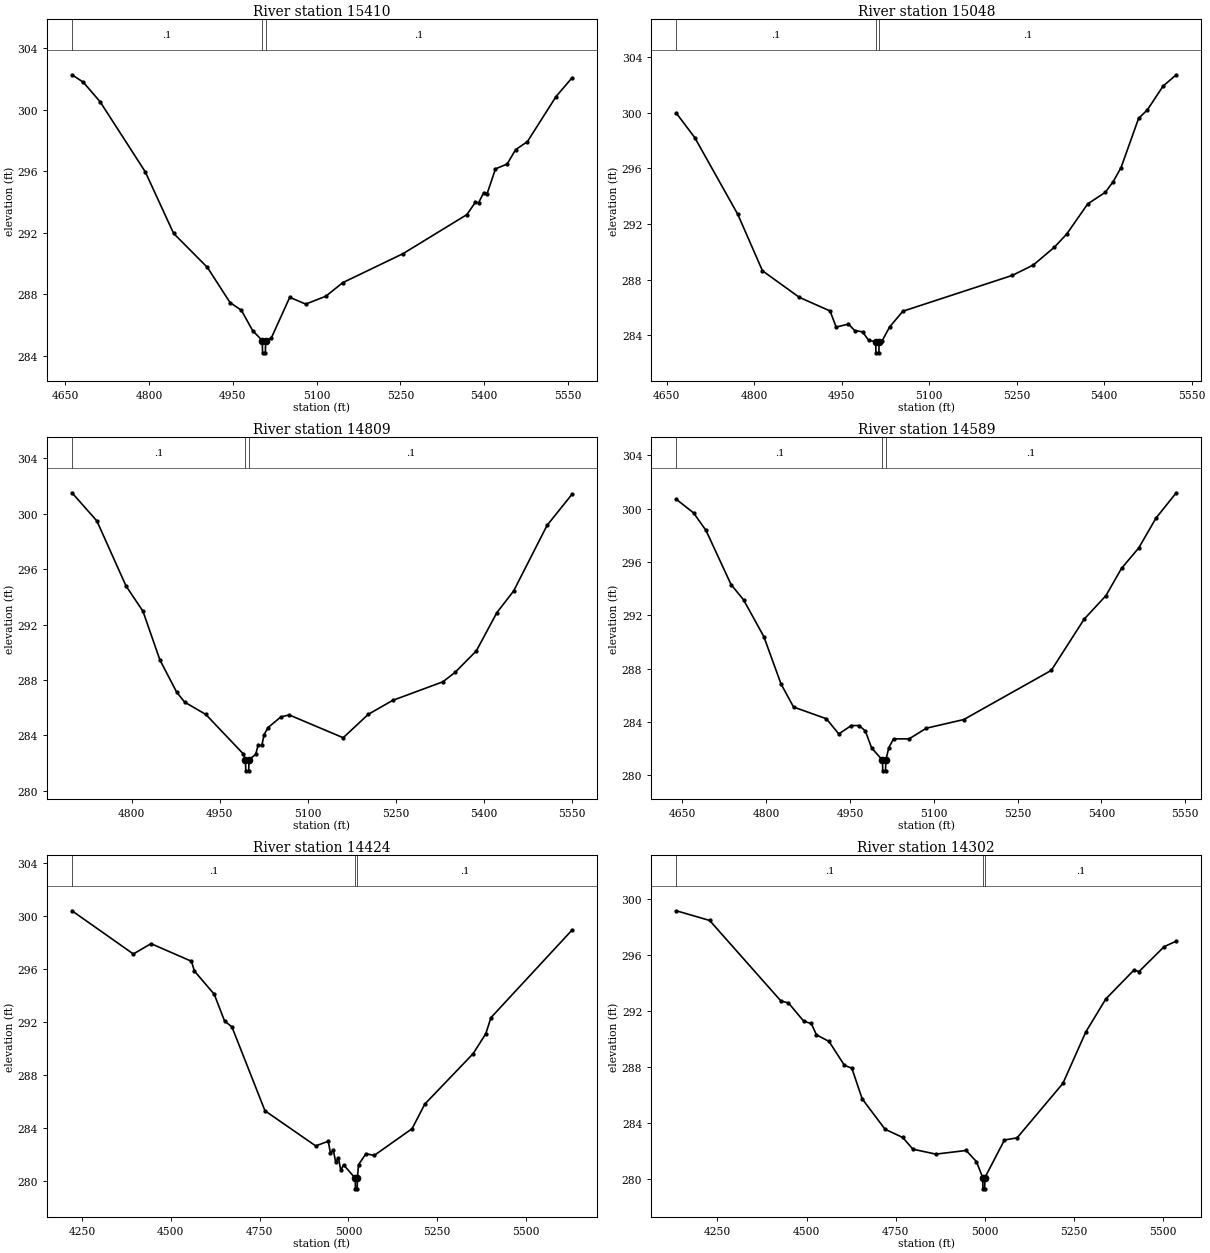
Type RM Length L Ch R = 1,15410,362,362,362
BEGIN DESCRIPTION:
UNT 018 in La Jarita Watershed 19.0
END DESCRIPTION:
XS GIS Cut Line= 3
      2136125.01     13393425.00      2135775.00     13393475.00
      2135324.99     13393775.00
#Sta/Elev= 30
  4662.4  302.26  4682.6  301.78  4712.9  300.50  4793.7  295.94  4844.2  291.95
  4904.8  289.73  4945.2  287.45  4965.5  286.95  4985.7  285.62  5002.9  284.98
  5003.4  284.18  5008.4  284.18  5008.9  284.98  5019.0  285.14  5052.0  287.79
  5080.6  287.35  5116.6  287.86  5146.7  288.74  5254.8  290.63  5369.0  293.17
  5384.0  293.96  5390.0  293.94  5399.0  294.59  5405.1  294.52  5420.1  296.14
  5441.1  296.46  5456.1  297.39  5477.2  297.91  5528.2  300.83  5556.8  302.05
#Mann=3,-1,0
  4662.4     0.1       0  5002.9    0.07       0  5008.9     0.1       0
Bank Sta=5002.9,5008.9
Exp/Cntr=0.3,0.1

Type RM Length L Ch R = 1,15048,239,239,239
BEGIN DESCRIPTION:
UNT 018 in La Jarita Watershed 18.0
END DESCRIPTION:
XS GIS Cut Line= 3
      2135924.98     13393175.01      2135625.00     13393275.00
      2135175.03     13393574.98
#Sta/Elev= 30
  4666.6  299.97  4698.2  298.21  4772.0  292.69  4814.2  288.64  4877.4  286.73
  4930.1  285.75  4940.6  284.59  4961.7  284.81  4972.3  284.34  4985.8  284.25
  4996.3  283.64  5008.3  283.54  5008.8  282.74  5013.8  282.74  5014.3  283.54
  5018.9  283.57  5032.4  284.61  5054.9  285.73  5242.7  288.31  5278.8  289.06
  5314.8  290.34  5335.8  291.28  5371.9  293.45  5402.0  294.28  5415.5  295.05
  5429.0  296.06  5459.0  299.59  5474.1  300.21  5501.1  301.92  5523.6  302.73
#Mann=3,-1,0
  4666.6     0.1       0  5008.3    0.07       0  5014.3     0.1       0
Bank Sta=5008.3,5014.3
Exp/Cntr=0.3,0.1

Type RM Length L Ch R = 1,14809,220,220,220
BEGIN DESCRIPTION:
UNT 018 in La Jarita Watershed 17.0
END DESCRIPTION:
XS GIS Cut Line= 3
      2135725.02     13392874.98      2135525.00     13393125.00
      2135174.99     13393525.01
#Sta/Elev= 30
  4698.5  301.52  4740.9  299.49  4790.6  294.79  4819.4  292.97  4848.2  289.46
  4877.0  287.11  4890.6  286.40  4926.6  285.51  4990.7  282.65  4994.1  282.24
  4994.6  281.44  4999.6  281.44  5000.1  282.24  5011.5  282.63  5015.5  283.27
  5022.0  283.27  5025.8  284.05  5032.4  284.56  5054.3  285.33  5068.5  285.48
  5160.6  283.83  5203.3  285.52  5245.0  286.53  5330.5  287.87  5351.4  288.56
  5387.4  290.10  5422.5  292.87  5451.0  294.43  5508.0  299.17  5550.2  301.40
#Mann=3,-1,0
  4698.5     0.1       0  4994.1    0.07       0  5000.1     0.1       0
Bank Sta=4994.1,5000.1
Exp/Cntr=0.3,0.1

Type RM Length L Ch R = 1,14589,165,165,165
BEGIN DESCRIPTION:
UNT 018 in La Jarita Watershed 16.0
END DESCRIPTION:
XS GIS Cut Line= 3
      2135675.04     13392824.98      2135375.00     13392975.00
      2135124.99     13393475.03
#Sta/Elev= 30
  4639.4  300.71  4670.2  299.69  4692.5  298.37  4737.3  294.31  4759.6  293.17
  4796.0  290.40  4826.7  286.85  4849.1  285.12  4907.8  284.24  4930.1  283.10
  4952.5  283.73  4966.5  283.73  4977.6  283.32  4988.8  282.05  5008.2  281.13
  5008.7  280.33  5013.7  280.33  5014.2  281.13  5019.6  282.07  5028.0  282.73
  5055.9  282.73  5086.7  283.53  5153.7  284.18  5310.3  287.87  5369.0  291.71
  5408.1  293.48  5436.0  295.53  5466.8  297.06  5497.5  299.29  5533.9  301.20
#Mann=3,-1,0
  4639.4     0.1       0  5008.2    0.07       0  5014.2     0.1       0
Bank Sta=5008.2,5014.2
Exp/Cntr=0.3,0.1

Type RM Length L Ch R = 1,14424,122,122,122
BEGIN DESCRIPTION:
UNT 018 in La Jarita Watershed 15.0
END DESCRIPTION:
XS GIS Cut Line= 3
      2135855.25     13392432.72      2135250.71     13392910.26
      2134735.53     13393283.36
#Sta/Elev= 30
  4222.3  300.38  4395.0  297.12  4444.7  297.90  4558.5  296.57  4566.6  295.84
  4622.6  294.08  4651.5  292.07  4672.3  291.62  4765.3  285.29  4908.0  282.64
  4943.3  282.99  4949.6  282.10  4957.7  282.30  4964.1  281.45  4972.1  281.74
  4978.5  280.81  4986.6  281.21  5019.3  280.20  5019.8  279.40  5024.8  279.40
  5025.3  280.20  5028.5  281.22  5049.4  282.05  5072.6  281.92  5179.3  283.94
  5214.9  285.79  5351.0  289.60  5386.5  291.10  5401.2  292.32  5628.8  298.91
#Mann=3,-1,0
  4222.3     0.1       0  5019.3    0.07       0  5025.3     0.1       0
Bank Sta=5019.3,5025.3
Exp/Cntr=0.3,0.1

Type RM Length L Ch R = 1,14302,316,316,316
BEGIN DESCRIPTION:
UNT 018 in La Jarita Watershed 14.0
END DESCRIPTION:
XS GIS Cut Line= 3
      2135817.10     13392335.18      2135166.23     13392852.95
      2134716.22     13393202.96
#Sta/Elev= 30
  4134.8  299.13  4228.1  298.44  4428.3  292.68  4449.1  292.55  4492.4  291.23
  4513.2  291.08  4527.6  290.27  4562.9  289.80  4606.1  288.09  4626.9  287.89
  4655.8  285.70  4719.9  283.53  4769.5  282.94  4798.3  282.10  4862.4  281.75
  4947.3  282.01  4976.2  281.22  4994.0  280.07  4994.5  279.27  4999.5  279.27
  5000.0  280.07  5054.9  282.76  5090.2  282.91  5218.7  286.80  5282.9  290.47
  5339.0  292.83  5417.8  294.89  5432.3  294.79  5502.8  296.57  5536.6  296.96
#Mann=3,-1,0
  4134.8     0.1       0  4994.0    0.07       0  5000.0     0.1       0
Bank Sta=4994,5000
Exp/Cntr=0.3,0.1

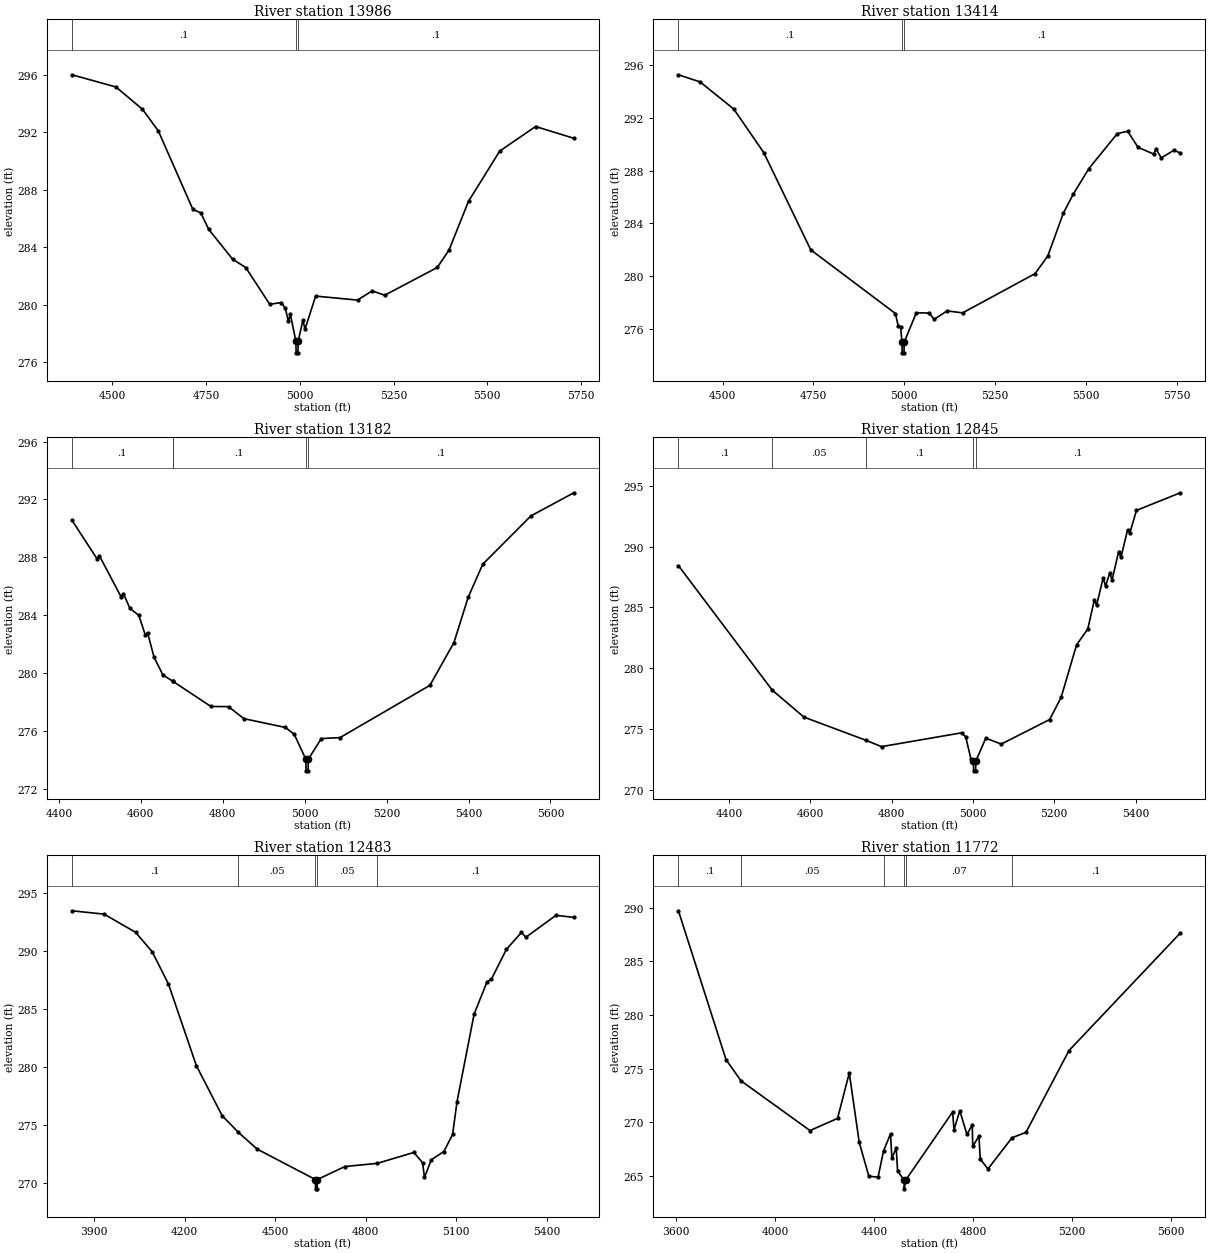
Type RM Length L Ch R = 1,13986,572,572,572
BEGIN DESCRIPTION:
Mapping XS b3caeca1
END DESCRIPTION:
XS GIS Cut Line= 3
      2135616.58     13392250.39      2135278.02     13392580.26
      2134444.73     13392818.97
#Sta/Elev= 30
  4391.8  296.01  4509.3  295.16  4580.0  293.61  4622.4  292.10  4714.5  286.64
  4735.6  286.40  4756.9  285.25  4820.5  283.18  4855.8  282.59  4919.6  280.04
  4950.9  280.16  4961.3  279.75  4969.5  278.86  4974.7  279.34  4989.5  277.46
  4990.0  276.66  4995.0  276.66  4995.5  277.46  5008.4  278.96  5013.6  278.29
  5042.2  280.61  5153.9  280.33  5192.8  280.97  5226.6  280.67  5366.8  282.60
  5398.1  283.81  5450.2  287.21  5533.4  290.70  5629.2  292.41  5731.3  291.59
#Mann=3,-1,0
  4391.8     0.1       0  4989.5    0.07       0  4995.5     0.1       0
Bank Sta=4989.5,4995.5
Exp/Cntr=0.3,0.1

Type RM Length L Ch R = 1,13414,232,232,232
BEGIN DESCRIPTION:
Mapping XS 0d38f901
END DESCRIPTION:
XS GIS Cut Line= 3
      2135542.74     13392050.76      2135095.73     13392163.60
      2134389.12     13392753.16
#Sta/Elev= 30
  4378.6  295.26  4438.2  294.72  4531.0  292.66  4613.5  289.36  4742.8  281.99
  4975.9  277.16  4983.7  276.19  4990.2  276.11  4993.9  274.98  4994.4  274.18
  4999.4  274.18  4999.9  274.98  5033.2  277.21  5068.3  277.20  5082.6  276.72
  5117.8  277.36  5160.7  277.21  5359.9  280.18  5395.0  281.51  5438.0  284.77
  5465.7  286.23  5508.3  288.15  5586.4  290.80  5615.0  290.98  5643.6  289.76
  5686.6  289.25  5693.1  289.64  5707.4  288.96  5742.5  289.54  5759.9  289.33
#Mann=3,-1,0
  4378.6     0.1       0  4993.9    0.07       0  4999.9     0.1       0
Bank Sta=4993.9,4999.9
Exp/Cntr=0.3,0.1

Type RM Length L Ch R = 1,13182,337,337,337
BEGIN DESCRIPTION:
Mapping XS bc762a34
END DESCRIPTION:
XS GIS Cut Line= 2
      2135291.07     13391838.06      2134232.06     13392454.37
#Sta/Elev= 30
  4431.9  290.56  4493.2  287.89  4499.0  288.10  4551.9  285.26  4557.7  285.48
  4573.5  284.46  4595.0  283.99  4610.7  282.65  4616.5  282.78  4632.2  281.10
  4653.7  279.87  4677.8  279.43  4677.9  279.43  4771.2  277.68  4814.2  277.67
  4851.5  276.84  4953.2  276.23  4974.7  275.75  5002.9  274.03  5003.4  273.23
  5008.4  273.23  5008.9  274.03  5040.6  275.46  5086.5  275.53  5305.7  279.14
  5364.5  282.10  5399.3  285.24  5434.8  287.52  5552.3  290.86  5657.2  292.46
#Mann=5,-1,0
  4431.9     0.1       0  4677.8    0.05       0  4677.9     0.1       0
  5002.9    0.07       0  5008.9     0.1       0
Bank Sta=5002.9,5008.9
Exp/Cntr=0.3,0.1

Type RM Length L Ch R = 1,12845,362,362,362
BEGIN DESCRIPTION:
Mapping XS 04509515
END DESCRIPTION:
XS GIS Cut Line= 2
      2135217.22     13391560.32      2134132.71     13392150.29
#Sta/Elev= 30
  4275.5  288.44  4506.2  278.20  4584.2  275.98  4736.3  274.08  4775.1  273.55
  4972.4  274.69  4982.2  274.36  4995.2  272.51  5001.1  272.36  5001.6  271.56
  5006.6  271.56  5007.1  272.36  5031.6  274.25  5069.6  273.76  5188.7  275.78
  5216.9  277.60  5254.9  281.92  5282.4  283.22  5298.6  285.61  5304.2  285.18
  5320.4  287.44  5326.1  286.75  5336.6  287.84  5342.2  287.24  5358.4  289.60
  5364.1  289.12  5380.3  291.37  5385.9  291.11  5402.1  292.98  5510.1  294.43
#Mann=5,-1,0
  4275.5     0.1       0  4506.2    0.05       0  4736.3     0.1       0
  5001.1    0.07       0  5007.1     0.1       0
Bank Sta=5001.1,5007.1
Exp/Cntr=0.3,0.1

Type RM Length L Ch R = 1,12483,711,711,711
BEGIN DESCRIPTION:
Mapping XS bd9795d8
END DESCRIPTION:
XS GIS Cut Line= 3
      2135404.74     13391185.31      2134595.73     13391487.38
      2133963.76     13391976.99
#Sta/Elev= 30
  3826.6  293.46  3933.1  293.17  4037.3  291.61  4092.6  289.93  4146.5  287.15
  4238.8  280.14  4324.3  275.83  4378.0  274.40  4440.2  272.96  4633.3  270.34
  4633.8  269.54  4638.9  269.54  4639.4  270.34  4731.2  271.46  4837.9  271.73
  4959.4  272.67  4988.4  271.79  4994.7  270.52  5017.3  272.04  5059.0  272.75
  5087.9  274.22  5102.4  277.03  5159.1  284.57  5202.0  287.35  5216.5  287.58
  5266.3  290.15  5316.1  291.60  5330.6  291.18  5430.2  293.07  5489.6  292.89
#Mann=5,-1,0
  3826.6     0.1       0  4378.0    0.05       0  4633.3    0.07       0
  4639.4    0.05       0  4837.9     0.1       0
Bank Sta=4633.3,4639.4
Exp/Cntr=0.3,0.1

Type RM Length L Ch R = 1,11772,57,57,57
BEGIN DESCRIPTION:
Mapping XS 5849466f
END DESCRIPTION:
XS GIS Cut Line= 6
      2135116.59     13391213.07      2134488.09     13391334.60
      2134484.62     13391084.60      2134019.34     13391174.88
      2133852.68     13391275.58      2133654.77     13391685.29
#Sta/Elev= 30
  3610.2  289.72  3802.5  275.85  3863.0  273.88  4141.5  269.25  4252.7  270.38
  4300.1  274.61  4340.2  268.16  4379.0  265.00  4416.2  264.90  4438.5  267.36
  4466.6  268.94  4472.1  266.68  4489.6  267.63  4495.1  265.49  4521.5  264.62
  4522.0  263.82  4527.6  264.62  4717.4  270.98  4722.9  269.32  4746.3  271.09
  4775.2  268.89  4796.5  269.77  4798.7  267.78  4823.6  268.73  4828.9  266.59
  4859.8  265.67  4957.2  268.58  5013.4  269.08  5187.2  276.70  5636.7  287.65
#Mann=6,-1,0
  3610.2     0.1       0  3863.0    0.05       0  4438.5    0.07       0
  4521.5    0.07       0  4527.6    0.07       0  4957.2     0.1       0
Bank Sta=4521.5,4527.6
Exp/Cntr=0.3,0.1

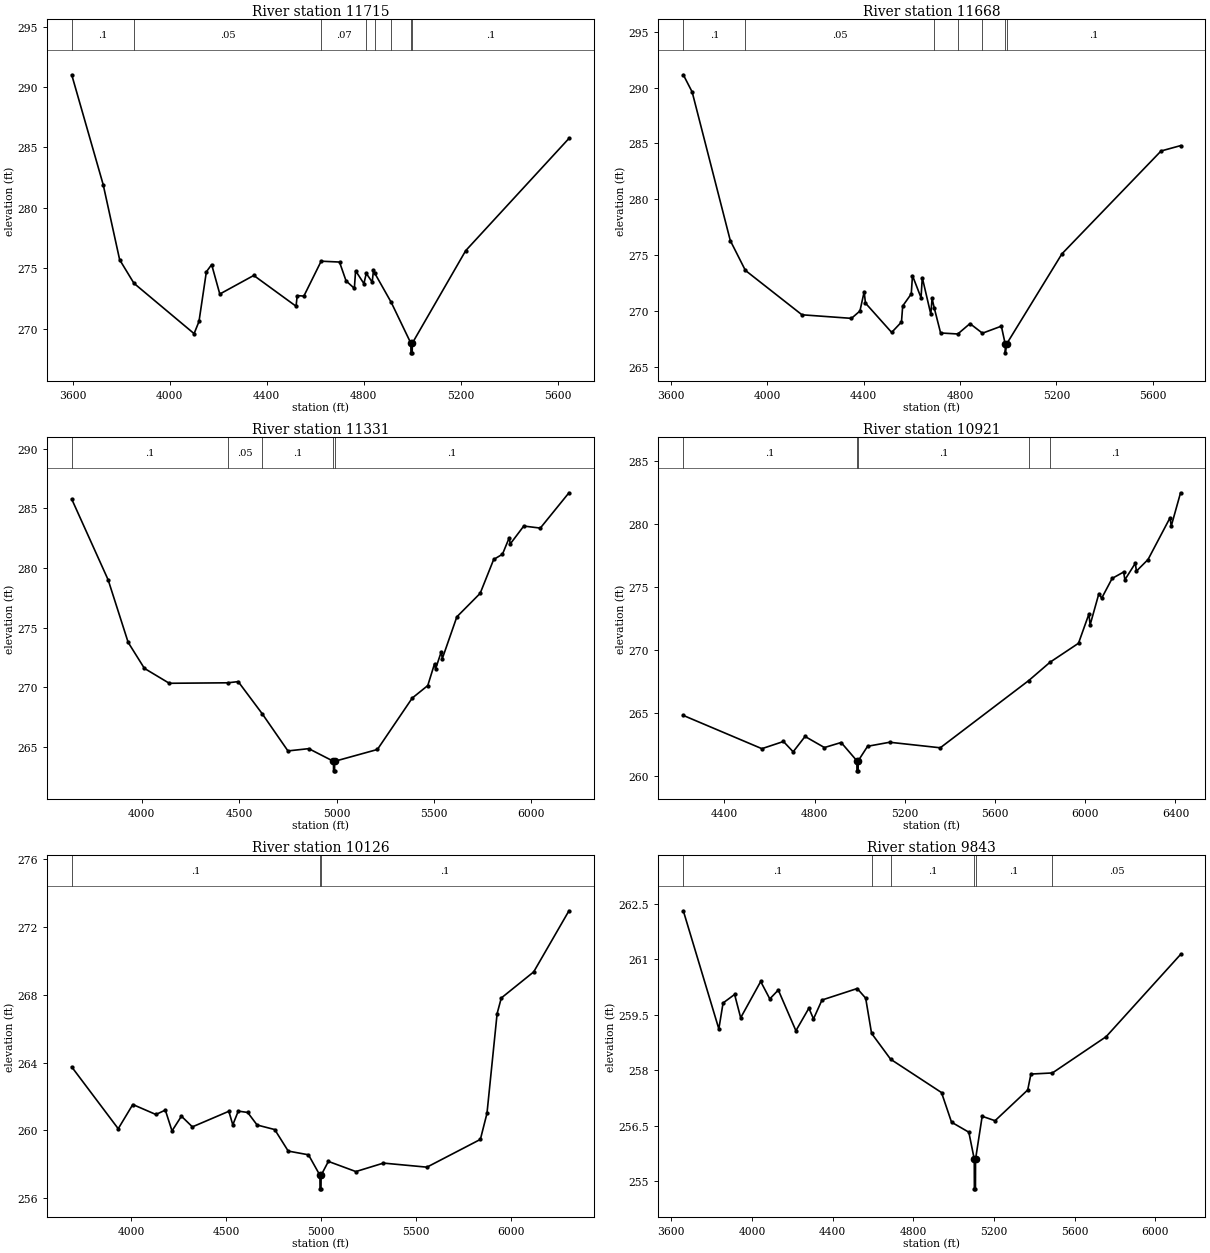
Type RM Length L Ch R = 1,11715,47,47,47
BEGIN DESCRIPTION:
Mapping XS fa27e6cb
END DESCRIPTION:
XS GIS Cut Line= 6
      2135113.12     13391167.93      2134536.70     13391261.69
      2134495.04     13391004.74      2133977.68     13391133.22
      2133817.95     13391247.80      2133595.73     13391654.06
#Sta/Elev= 30
  3595.9  291.02  3725.7  281.92  3793.6  275.70  3852.6  273.75  4100.6  269.58
  4120.8  270.59  4151.2  274.70  4173.0  275.30  4206.6  272.86  4346.7  274.40
  4521.1  271.85  4525.9  272.73  4553.3  272.69  4624.6  275.58  4700.3  275.51
  4727.3  273.95  4761.5  273.33  4766.7  274.79  4800.9  273.72  4810.7  274.57
  4835.1  273.85  4840.3  274.81  4846.1  274.57  4913.6  272.17  4994.5  268.79
  4995.0  267.99  5000.1  267.99  5000.6  268.79  5220.6  276.45  5646.6  285.75
#Mann=8,-1,0
  3595.9     0.1       0  3852.6    0.05       0  4624.6    0.07       0
  4810.7    0.05       0  4846.1    0.07       0  4913.6     0.1       0
  4994.5    0.07       0  5000.6     0.1       0
Bank Sta=4994.5,5000.6
Exp/Cntr=0.3,0.1

Type RM Length L Ch R = 1,11668,337,337,337
BEGIN DESCRIPTION:
Mapping XS 756e3b23
END DESCRIPTION:
XS GIS Cut Line= 6
      2135106.19     13391122.79      2134623.51     13391220.02
      2134578.37     13391042.94      2134449.90     13390970.02
      2133953.37     13391098.49      2133540.59     13391670.67
#Sta/Elev= 30
  3651.6  291.15  3688.3  289.61  3846.6  276.29  3909.1  273.62  4143.9  269.64
  4349.4  269.32  4384.5  269.98  4402.2  271.71  4407.4  270.69  4516.2  268.06
  4556.9  268.99  4562.0  270.43  4597.5  271.51  4602.6  273.15  4638.1  271.17
  4643.3  272.97  4678.7  269.69  4683.9  271.10  4692.5  270.29  4719.3  268.01
  4790.6  267.92  4841.2  268.85  4892.9  267.99  4971.4  268.62  4987.3  267.03
  4987.8  266.23  4993.4  267.03  5222.7  275.10  5634.1  284.32  5715.0  284.80
#Mann=7,-1,0
  3651.6     0.1       0  3909.1    0.05       0  4692.5    0.07       0
  4790.6    0.05       0  4892.9     0.1       0  4987.3    0.07       0
  4993.4     0.1       0
Bank Sta=4987.3,4993.4
Exp/Cntr=0.3,0.1

Type RM Length L Ch R = 1,11331,410,410,410
BEGIN DESCRIPTION:
Mapping XS 0d72722d
END DESCRIPTION:
XS GIS Cut Line= 4
      2135097.14     13390733.91      2134263.79     13390539.47
      2133687.40     13390956.13      2133430.46     13391907.49
#Sta/Elev= 30
  3640.6  285.78  3827.6  279.01  3930.3  273.77  4013.7  271.59  4141.4  270.34
  4441.6  270.38  4495.2  270.48  4618.7  267.78  4750.5  264.67  4857.3  264.86
  4984.2  263.80  4984.7  263.00  4989.8  263.00  4990.3  263.80  5209.6  264.79
  5388.5  269.10  5468.3  270.15  5503.0  271.98  5508.2  271.54  5537.7  272.99
  5542.9  272.41  5617.5  275.91  5737.2  277.88  5806.6  280.72  5851.7  281.16
  5886.4  282.54  5891.6  282.02  5961.0  283.52  6046.0  283.35  6193.0  286.31
#Mann=5,-1,0
  3640.6     0.1       0  4441.6    0.05       0  4618.7     0.1       0
  4984.2    0.07       0  4990.3     0.1       0
Bank Sta=4984.2,4990.3
Exp/Cntr=0.3,0.1

Type RM Length L Ch R = 1,10921,795,795,795
BEGIN DESCRIPTION:
Mapping XS c8ec5968
END DESCRIPTION:
XS GIS Cut Line= 3
      2133966.32     13389889.13      2133532.28     13390626.99
      2133271.95     13391950.37
#Sta/Elev= 30
  4217.7  264.79  4566.1  262.15  4661.8  262.72  4704.8  261.90  4757.5  263.12
  4843.4  262.24  4917.6  262.64  4987.2  261.19  4987.7  260.39  4992.8  260.39
  4993.3  261.19  5034.8  262.34  5132.6  262.66  5357.1  262.22  5749.4  267.56
  5844.2  269.02  5970.0  270.52  6016.3  272.85  6021.4  271.97  6060.3  274.46
  6072.8  274.10  6119.1  275.67  6170.4  276.18  6175.5  275.56  6221.8  276.87
  6226.9  276.25  6278.3  277.17  6376.0  280.49  6381.1  279.82  6422.5  282.47
#Mann=5,-1,0
  4217.7     0.1       0  4987.2    0.07       0  4993.3     0.1       0
  5749.4    0.05       0  5844.2     0.1       0
Bank Sta=4987.2,4993.3
Exp/Cntr=0.3,0.1

Type RM Length L Ch R = 1,10126,283,283,283
BEGIN DESCRIPTION:
Mapping XS 1a446f42
END DESCRIPTION:
XS GIS Cut Line= 4
      2133886.56     13389843.26      2132894.34     13390634.95
      2132745.91     13391194.85      2133105.26     13391877.10
#Sta/Elev= 30
  3687.4  263.75  3932.4  260.10  4009.2  261.53  4130.9  260.94  4180.6  261.20
  4215.8  259.97  4265.4  260.84  4323.1  260.21  4515.2  261.13  4536.0  260.33
  4564.9  261.14  4614.5  261.06  4664.1  260.32  4757.0  260.05  4828.0  258.78
  4934.8  258.56  4995.1  257.35  4995.6  256.55  5000.7  256.55  5001.2  257.35
  5039.6  258.17  5184.4  257.57  5329.7  258.07  5558.8  257.83  5840.4  259.47
  5875.2  261.01  5928.6  266.90  5950.6  267.82  6121.2  269.36  6307.1  272.97
#Mann=3,-1,0
  3687.4     0.1       0  4995.1    0.07       0  5001.2     0.1       0
Bank Sta=4995.1,5001.2
Exp/Cntr=0.3,0.1

Type RM Length L Ch R = 1,9843,558,558,558
BEGIN DESCRIPTION:
Mapping XS 3d1b7164
END DESCRIPTION:
XS GIS Cut Line= 3
      2133774.54     13389791.21      2132475.07     13390650.58
      2131599.05     13390889.73
#Sta/Elev= 30
  3659.5  262.31  3835.7  259.12  3856.7  259.82  3913.9  260.05  3944.0  259.42
  4043.3  260.40  4088.5  259.93  4130.6  260.17  4217.9  259.07  4282.4  259.68
  4305.1  259.39  4347.3  259.90  4521.8  260.21  4563.9  259.95  4593.1  259.00
  4687.7  258.30  4940.1  257.40  4989.7  256.60  5075.5  256.33  5102.5  255.60
  5103.0  254.80  5108.3  254.80  5108.8  255.60  5141.7  256.76  5205.5  256.64
  5367.5  257.47  5383.4  257.90  5490.0  257.93  5756.5  258.91  6125.5  261.13
#Mann=6,-1,0
  3659.5     0.1       0  4593.1    0.05       0  4687.7     0.1       0
  5102.5    0.07       0  5108.8     0.1       0  5490.0    0.05       0
Bank Sta=5102.5,5108.8
Exp/Cntr=0.3,0.1

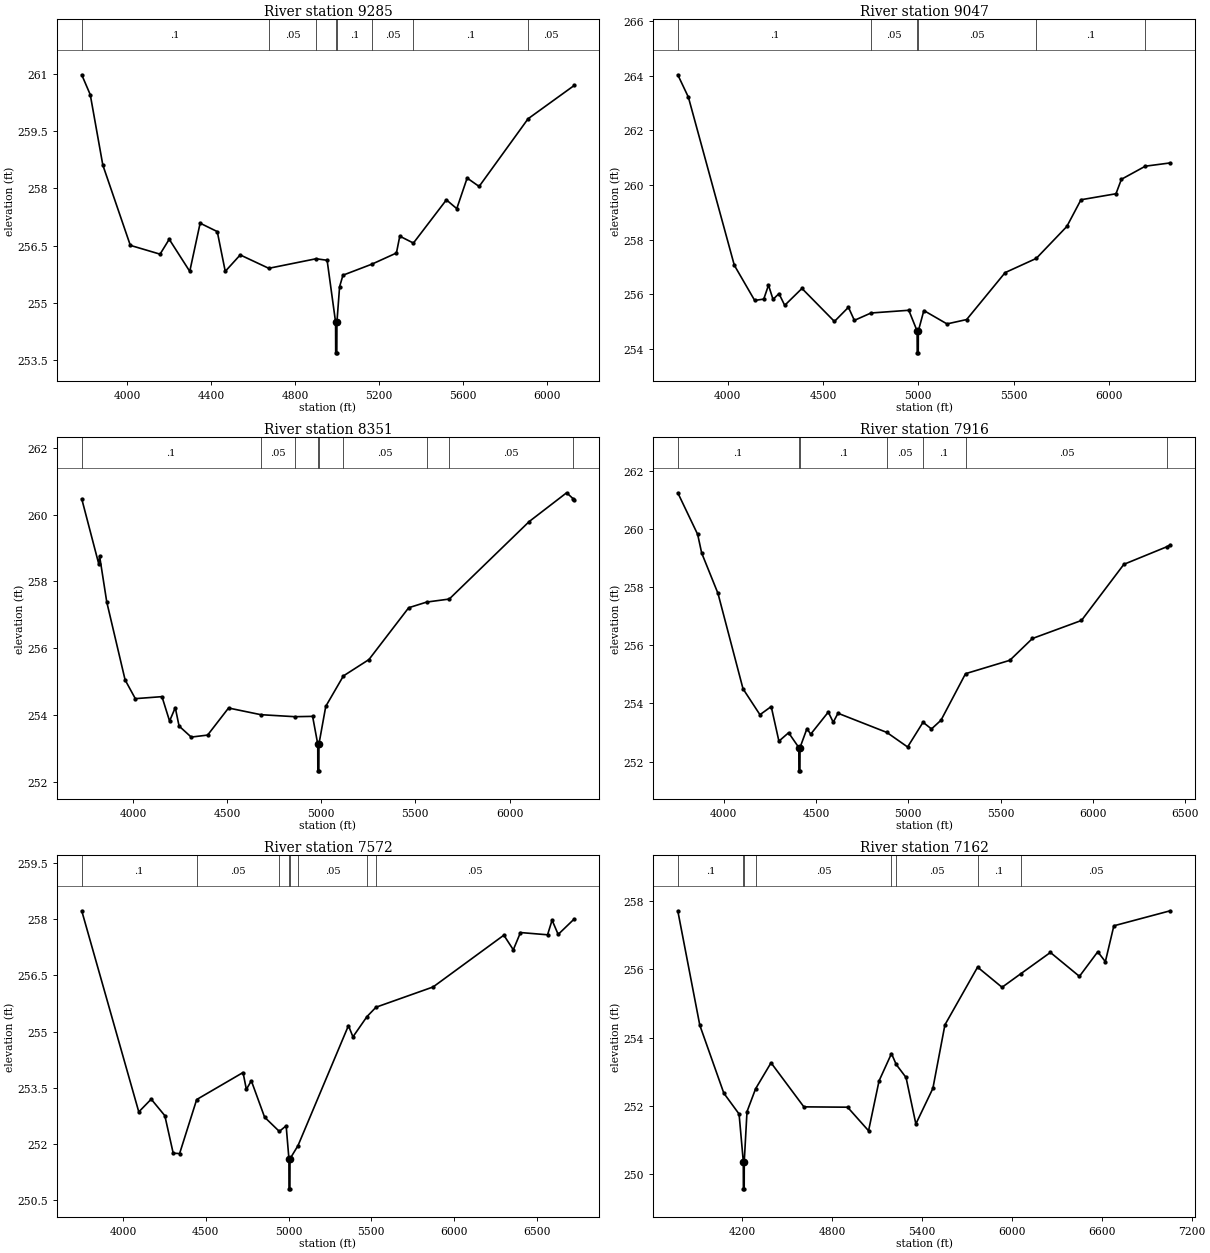
Type RM Length L Ch R = 1,9285,238,238,238
BEGIN DESCRIPTION:
Mapping XS 3f1e0f74
END DESCRIPTION:
XS GIS Cut Line= 4
      2133586.85     13389431.17      2132555.59     13389993.68
      2132211.84     13390186.38      2131706.64     13390774.91
#Sta/Elev= 30
  3783.6  260.97  3824.2  260.45  3884.0  258.61  4015.0  256.51  4156.5  256.28
  4200.1  256.67  4297.9  255.83  4347.3  257.09  4428.9  256.87  4466.9  255.83
  4538.1  256.26  4674.1  255.91  4899.4  256.16  4951.9  256.12  4992.2  254.50
  4992.7  253.70  4998.0  253.70  4998.5  254.50  5011.3  255.43  5027.3  255.73
  5165.7  256.02  5281.8  256.31  5297.8  256.75  5362.7  256.57  5519.7  257.70
  5569.1  257.47  5618.5  258.27  5675.5  258.05  5908.6  259.82  6128.0  260.69
#Mann=8,-1,0
  3783.6     0.1       0  4674.1    0.05       0  4899.4     0.1       0
  4992.2    0.07       0  4998.5     0.1       0  5165.7    0.05       0
  5362.7     0.1       0  5908.6    0.05       0
Bank Sta=4992.2,4998.5
Exp/Cntr=0.3,0.1

Type RM Length L Ch R = 1,9047,696,696,696
BEGIN DESCRIPTION:
Mapping XS 657b0457
END DESCRIPTION:
XS GIS Cut Line= 3
      2133682.35     13389330.47      2132019.99     13389959.82
      2131682.23     13390691.64
#Sta/Elev= 30
  3738.7  264.04  3794.3  263.22  4035.3  257.06  4142.2  255.77  4189.8  255.82
  4214.6  256.33  4238.4  255.81  4269.6  256.02  4299.7  255.59  4390.2  256.21
  4560.5  255.00  4634.0  255.52  4665.1  255.04  4752.4  255.31  4950.7  255.41
  4994.4  254.65  4994.9  253.85  5000.2  253.85  5000.7  254.65  5029.7  255.40
  5151.1  254.91  5254.2  255.07  5456.1  256.79  5619.3  257.31  5779.7  258.48
  5854.0  259.46  6037.6  259.68  6066.1  260.21  6191.6  260.69  6322.2  260.81
#Mann=6,-1,0
  3738.7     0.1       0  4752.4    0.05       0  4994.4    0.03       0
  5000.7    0.05       0  5619.3     0.1       0  6191.6    0.05       0
Bank Sta=4994.4,5000.7
Exp/Cntr=0.3,0.1

Type RM Length L Ch R = 1,8351,435,435,435
BEGIN DESCRIPTION:
Mapping XS 5b579413
END DESCRIPTION:
XS GIS Cut Line= 4
      2133466.64     13389303.29      2132628.94     13389181.75
      2132034.32     13389285.92      2131637.65     13390381.26
#Sta/Elev= 30
  3728.2  260.47  3818.2  258.53  3823.3  258.75  3861.2  257.38  3958.6  255.05
  4012.8  254.49  4154.3  254.55  4194.7  253.82  4225.0  254.22  4245.2  253.67
  4309.6  253.34  4396.8  253.40  4507.9  254.21  4679.5  254.01  4860.3  253.95
  4954.3  253.96  4981.6  253.13  4982.1  252.33  4987.4  252.33  4987.9  253.13
  5024.2  254.26  5117.8  255.17  5253.5  255.66  5464.5  257.21  5560.3  257.38
  5679.9  257.47  6104.7  259.79  6303.2  260.65  6338.4  260.47  6343.3  260.44
#Mann=9,-1,0
  3728.2     0.1       0  4679.5    0.05       0  4860.3     0.1       0
  4981.6    0.07       0  4987.9     0.1       0  5117.8    0.05       0
  5560.3     0.1       0  5679.9    0.05       0  6338.4     0.1       0
Bank Sta=4981.6,4987.9
Exp/Cntr=0.3,0.1

Type RM Length L Ch R = 1,7916,344,344,344
BEGIN DESCRIPTION:
Mapping XS ffd755a8
END DESCRIPTION:
XS GIS Cut Line= 4
      2133562.09     13389090.61      2132663.66     13388921.34
      2132034.32     13388864.91      2131396.30     13389785.06
#Sta/Elev= 30
  3752.0  261.24  3859.6  259.81  3881.3  259.17  3969.6  257.78  4105.2  254.50
  4196.8  253.61  4257.8  253.89  4299.5  252.70  4351.9  252.99  4407.3  252.48
  4407.8  251.68  4413.2  251.68  4413.7  252.48  4451.2  253.13  4471.5  252.94
  4566.8  253.70  4593.6  253.35  4619.3  253.66  4883.9  253.00  4996.2  252.50
  5079.7  253.35  5125.4  253.12  5176.9  253.42  5309.7  255.02  5549.5  255.48
  5671.8  256.23  5937.3  256.85  6166.9  258.78  6401.7  259.39  6417.8  259.45
#Mann=7,-1,0
  3752.0     0.1       0  4407.3   0.035       0  4413.7     0.1       0
  4883.9    0.05       0  5079.7     0.1       0  5309.7    0.05       0
  6401.7     0.1       0
Bank Sta=4407.3,4413.7
Exp/Cntr=0.3,0.1

Type RM Length L Ch R = 1,7572,410,410,410
BEGIN DESCRIPTION:
Mapping XS f11c16cc
END DESCRIPTION:
XS GIS Cut Line= 4
      2133531.74     13388973.43      2132824.25     13388608.84
      2132090.74     13388556.75      2130949.61     13389446.23
#Sta/Elev= 30
  3749.5  258.22  4094.6  252.86  4169.7  253.20  4252.1  252.76  4302.7  251.76
  4341.4  251.75  4444.8  253.19  4725.1  253.91  4745.2  253.46  4775.2  253.69
  4855.4  252.72  4944.5  252.34  4985.8  252.49  5002.6  251.61  5003.1  250.81
  5008.5  250.81  5009.0  251.61  5057.3  251.96  5362.6  255.16  5389.7  254.86
  5474.6  255.40  5529.2  255.65  5874.6  256.19  6302.4  257.57  6359.5  257.18
  6402.9  257.64  6566.7  257.58  6594.0  257.97  6630.9  257.59  6727.6  258.00
#Mann=8,-1,0
  3749.5     0.1       0  4444.8    0.05       0  4944.5     0.1       0
  5002.6    0.07       0  5009.0     0.1       0  5057.3    0.05       0
  5474.6     0.1       0  5529.2    0.05       0
Bank Sta=5002.6,5009
Exp/Cntr=0.3,0.1

Type RM Length L Ch R = 1,7162,701,701,701
BEGIN DESCRIPTION:
Mapping XS ed8977d2
END DESCRIPTION:
XS GIS Cut Line= 4
      2133588.14     13388743.39      2132694.04     13388222.55
      2132303.41     13388235.57      2130771.28     13389294.61
#Sta/Elev= 30
  3768.3  257.71  3915.3  254.36  4075.8  252.37  4177.6  251.76  4205.8  250.37
  4206.3  249.57  4211.7  249.57  4212.2  250.37  4230.5  251.83  4287.9  252.50
  4391.0  253.26  4610.2  251.97  4902.1  251.96  5042.2  251.27  5112.2  252.73
  5195.2  253.53  5226.9  253.21  5292.4  252.83  5358.0  251.47  5471.6  252.51
  5552.0  254.37  5770.1  256.06  5933.5  255.47  6059.6  255.87  6256.3  256.49
  6450.2  255.79  6572.6  256.51  6623.3  256.22  6680.0  257.27  7056.4  257.71
#Mann=8,-1,0
  3768.3     0.1       0  4205.8    0.03       0  4212.2     0.1       0
  4287.9    0.05       0  5195.2     0.1       0  5226.9    0.05       0
  5770.1     0.1       0  6059.6    0.05       0
Bank Sta=4205.8,4212.2
Exp/Cntr=0.3,0.1

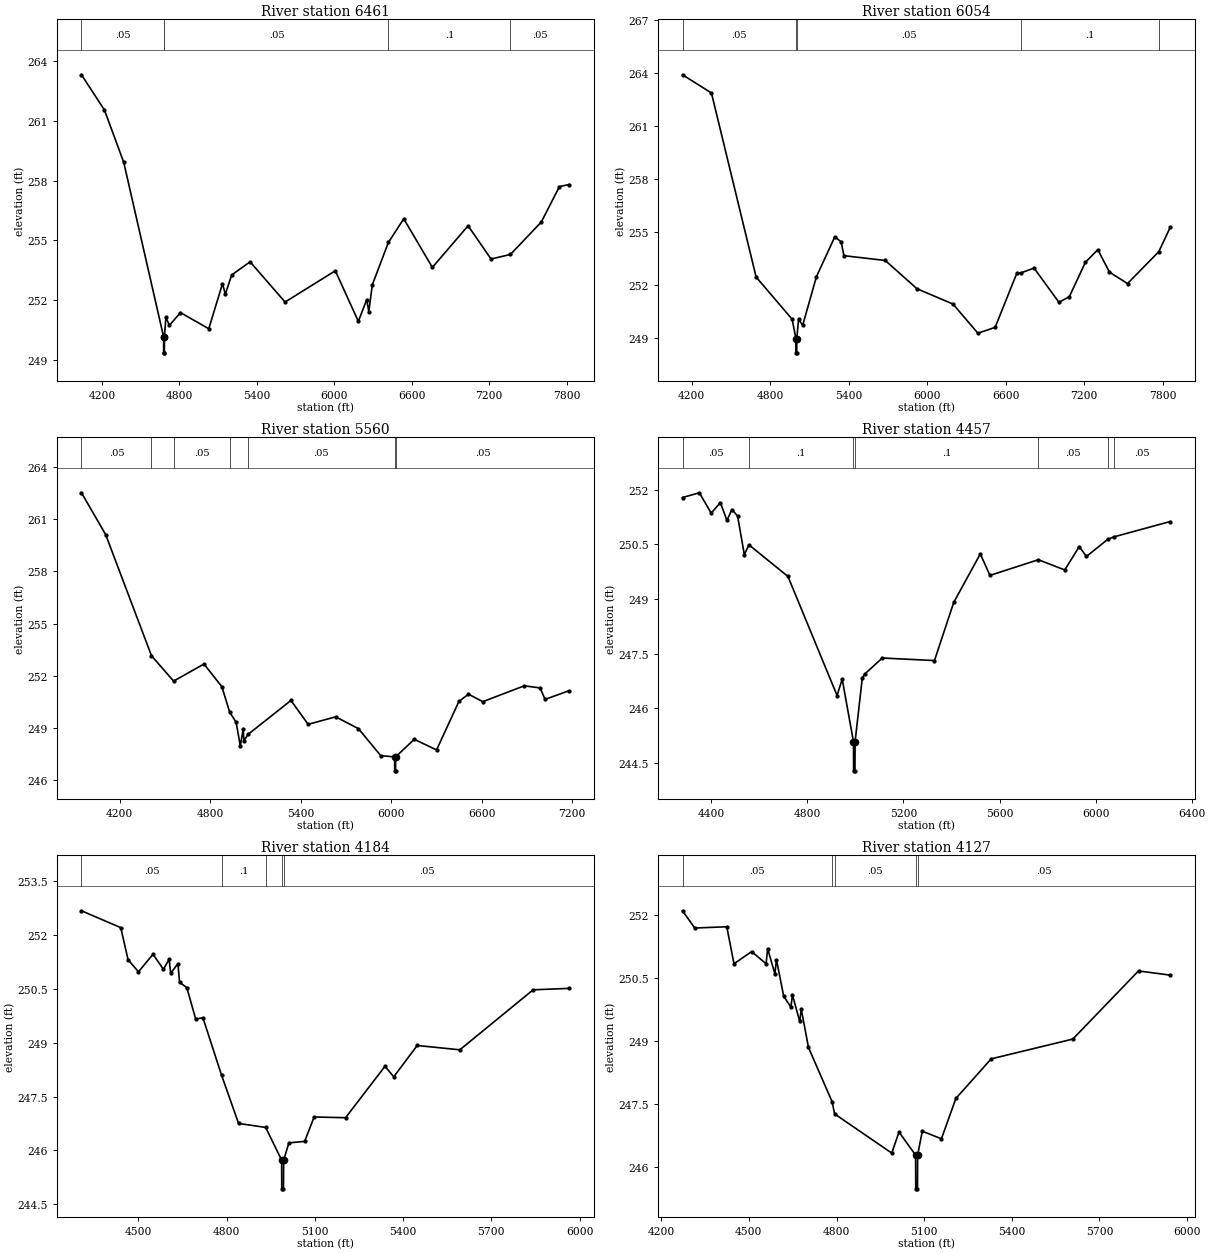
Type RM Length L Ch R = 1,6461,407,407,407
BEGIN DESCRIPTION:
Mapping XS 21559610
END DESCRIPTION:
XS GIS Cut Line= 3
      2133848.56     13388713.01      2132885.01     13387875.33
      2130701.85     13389094.95
#Sta/Elev= 30
  4042.1  263.32  4220.0  261.55  4369.1  258.93  4678.3  250.16  4678.8  249.36
  4684.2  249.36  4684.7  250.16  4695.8  251.14  4723.3  250.74  4808.8  251.38
  5028.1  250.57  5134.4  252.83  5156.3  252.31  5205.7  253.27  5348.2  253.93
  5619.0  251.91  6008.5  253.48  6186.7  250.94  6251.8  252.03  6267.8  251.43
  6295.2  252.78  6419.3  254.90  6538.5  256.09  6760.1  253.65  7037.1  255.74
  7214.7  254.07  7365.1  254.30  7604.2  255.93  7744.7  257.71  7819.6  257.81
#Mann=5,-1,0
  4042.1    0.05       0  4678.3    0.03       0  4684.7    0.05       0
  6419.3     0.1       0  7365.1    0.05       0
Bank Sta=4678.3,4684.7
Exp/Cntr=0.3,0.1

Type RM Length L Ch R = 1,6054,494,494,494
BEGIN DESCRIPTION:
Mapping XS fe6f9c22
END DESCRIPTION:
XS GIS Cut Line= 4
      2133918.00     13388522.04      2133431.89     13387905.71
      2132798.21     13387701.72      2130849.68     13388877.78
#Sta/Elev= 30
  4130.7  263.89  4351.7  262.86  4693.2  252.44  4968.6  250.05  4997.3  248.95
  4997.8  248.15  5003.4  248.15  5003.9  248.95  5017.4  250.05  5049.0  249.71
  5154.0  252.46  5294.6  254.72  5343.1  254.43  5364.1  253.65  5679.6  253.38
  5922.2  251.78  6197.8  250.91  6388.0  249.26  6519.5  249.59  6685.0  252.65
  6719.0  252.68  6817.0  252.95  7007.2  251.01  7086.8  251.33  7209.1  253.27
  7304.2  253.99  7393.4  252.72  7531.2  252.07  7770.6  253.88  7857.3  255.25
#Mann=5,-1,0
  4130.7    0.05       0  4997.3   0.035       0  5003.9    0.05       0
  6719.0     0.1       0  7770.6    0.05       0
Bank Sta=4997.3,5003.9
Exp/Cntr=0.3,0.1

Type RM Length L Ch R = 1,5560,1103,1103,1103
BEGIN DESCRIPTION:
Mapping XS cacdb4d4
END DESCRIPTION:
XS GIS Cut Line= 4
      2134130.64     13388105.33      2133635.88     13387506.41
      2132845.95     13387354.50      2131283.48     13386820.66
#Sta/Elev= 30
  3947.8  262.51  4108.1  260.11  4411.6  253.16  4558.4  251.70  4759.9  252.68
  4878.3  251.38  4930.0  249.92  4972.7  249.34  5000.5  247.98  5019.6  248.93
  5024.6  248.27  5051.5  248.64  5336.3  250.59  5450.3  249.22  5633.1  249.65
  5783.7  248.97  5931.6  247.42  6023.4  247.35  6023.9  246.55  6029.6  246.55
  6030.1  247.35  6153.5  248.36  6301.5  247.75  6449.4  250.53  6512.8  250.95
  6607.9  250.52  6882.7  251.43  6988.4  251.31  7020.1  250.65  7180.2  251.15
#Mann=7,-1,0
  3947.8    0.05       0  4411.6     0.1       0  4558.4    0.05       0
  4930.0     0.1       0  5051.5    0.05       0  6023.4    0.07       0
  6030.1    0.05       0
Bank Sta=6023.4,6030.1
Exp/Cntr=0.3,0.1

Type RM Length L Ch R = 1,4457,273,273,273
BEGIN DESCRIPTION:
Mapping XS 4adfd6cd
END DESCRIPTION:
XS GIS Cut Line= 3
      2133252.24     13387064.58      2132293.87     13386779.84
      2131268.02     13386682.81
#Sta/Elev= 30
  4280.1  251.79  4350.2  251.92  4399.4  251.36  4437.8  251.65  4465.0  251.16
  4485.9  251.46  4509.4  251.28  4537.4  250.22  4556.6  250.49  4719.1  249.62
  4923.5  246.35  4944.9  246.80  4991.8  245.08  4992.3  244.28  4998.0  244.28
  4998.5  245.08  5028.3  246.82  5038.8  246.94  5111.8  247.38  5329.0  247.31
  5409.3  248.91  5519.8  250.24  5560.0  249.65  5761.4  250.08  5871.4  249.80
  5931.6  250.44  5961.8  250.17  6050.2  250.64  6076.9  250.71  6310.3  251.13
#Mann=7,-1,0
  4280.1    0.05       0  4556.6     0.1       0  4991.8    0.07       0
  4998.5     0.1       0  5761.4    0.05       0  6050.2     0.1       0
  6076.9    0.05       0
Bank Sta=4991.8,4998.5
Exp/Cntr=0.3,0.1

Type RM Length L Ch R = 1,4184,57,57,57
BEGIN DESCRIPTION:
Mapping XS bf6934aa
END DESCRIPTION:
XS GIS Cut Line= 2
      2133174.09     13386847.91      2131624.63     13386256.77
#Sta/Elev= 30
  4306.2  252.67  4439.8  252.20  4464.5  251.31  4500.0  250.97  4549.4  251.46
  4584.9  251.04  4604.2  251.32  4609.6  250.93  4634.3  251.20  4639.7  250.68
  4664.4  250.53  4694.5  249.66  4719.2  249.69  4782.7  248.09  4840.4  246.75
  4932.5  246.64  4986.8  245.73  4987.3  244.93  4993.2  244.93  4993.7  245.73
  5011.6  246.21  5065.1  246.25  5097.3  246.93  5204.3  246.91  5338.2  248.34
  5368.3  248.05  5447.8  248.92  5592.9  248.80  5842.2  250.47  5964.6  250.51
#Mann=5,-1,0
  4306.2    0.05       0  4782.7     0.1       0  4932.5    0.05       0
  4986.8    0.03       0  4993.7    0.05       0
Bank Sta=4986.8,4993.7
Exp/Cntr=0.3,0.1

Type RM Length L Ch R = 1,4127,715,715,715
BEGIN DESCRIPTION:
Mapping XS 3d8b6e92
END DESCRIPTION:
XS GIS Cut Line= 2
      2133192.28     13386803.62      2131632.55     13386209.93
#Sta/Elev= 30
  4273.0  252.09  4314.8  251.68  4424.5  251.71  4449.2  250.83  4509.5  251.12
  4559.0  250.83  4564.3  251.19  4589.1  250.59  4594.4  250.93  4619.2  250.06
  4643.9  249.80  4649.3  250.09  4674.0  249.46  4679.4  249.75  4704.1  248.84
  4784.9  247.55  4793.6  247.26  4989.1  246.33  5013.9  246.83  5070.7  246.28
  5071.2  245.48  5077.1  245.48  5077.6  246.28  5093.5  246.85  5159.1  246.67
  5208.6  247.63  5329.4  248.57  5608.7  249.04  5833.5  250.66  5941.9  250.56
#Mann=5,-1,0
  4273.0    0.05       0  4784.9     0.1       0  4793.6    0.05       0
  5070.7    0.03       0  5077.6    0.05       0
Bank Sta=5070.7,5077.6
Exp/Cntr=0.3,0.1