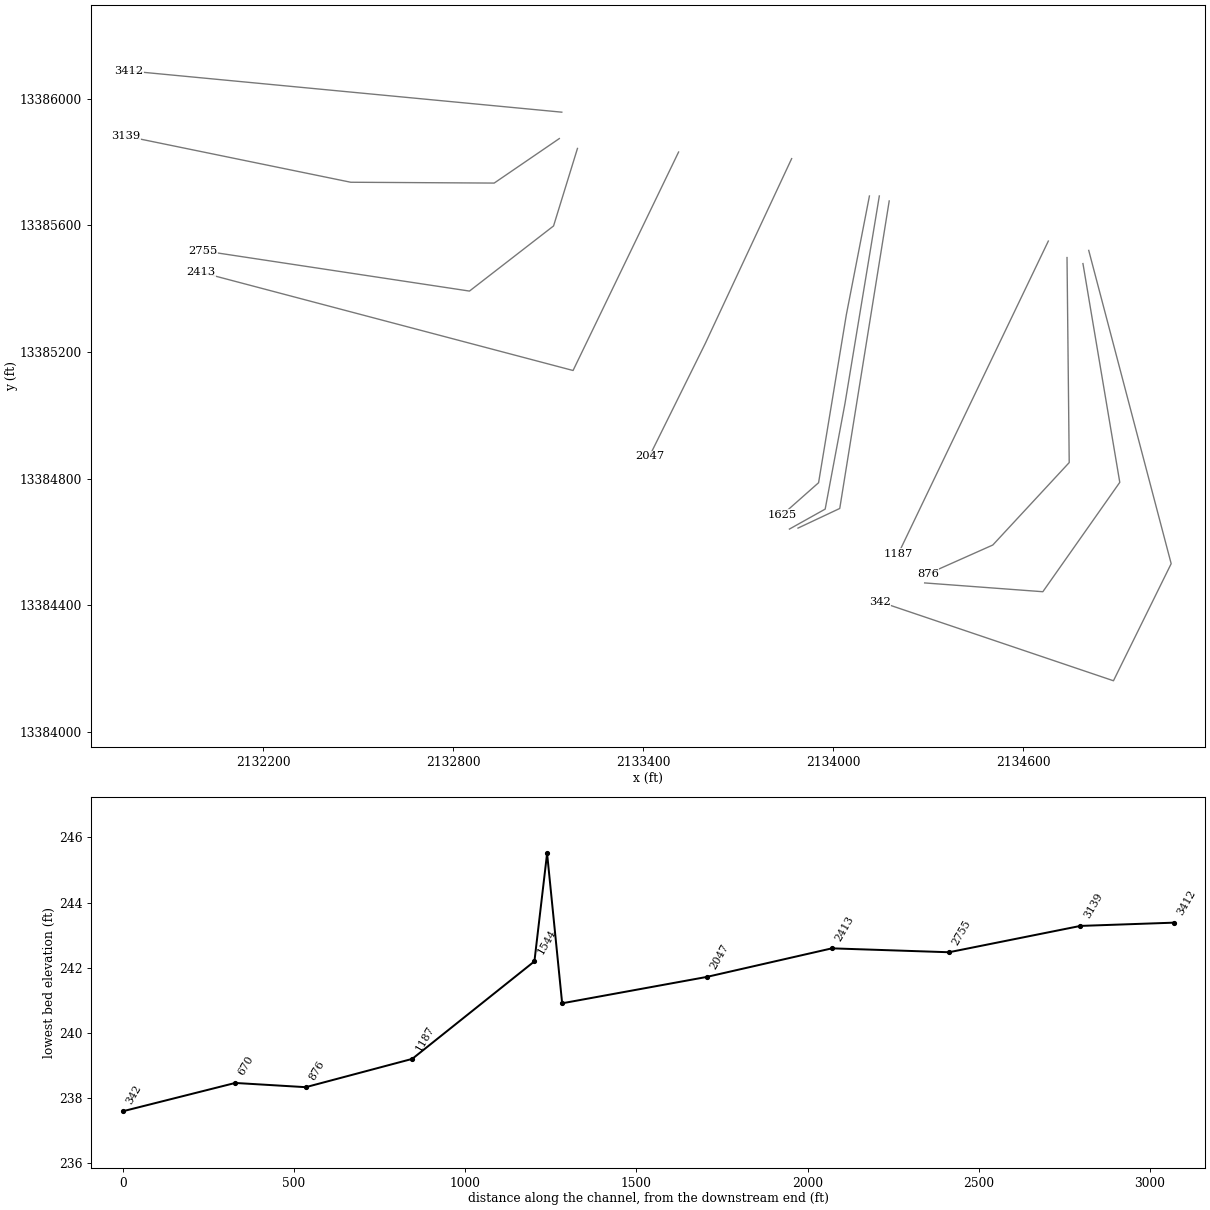
HEC-RAS study UNT 018 in La Jarita Watershed.prj: UNT 018 in La Jarita Watershed Base Level Engineering

--- UNT 018 in La Jarita Watershed.g01 (geometry) --- (continued)

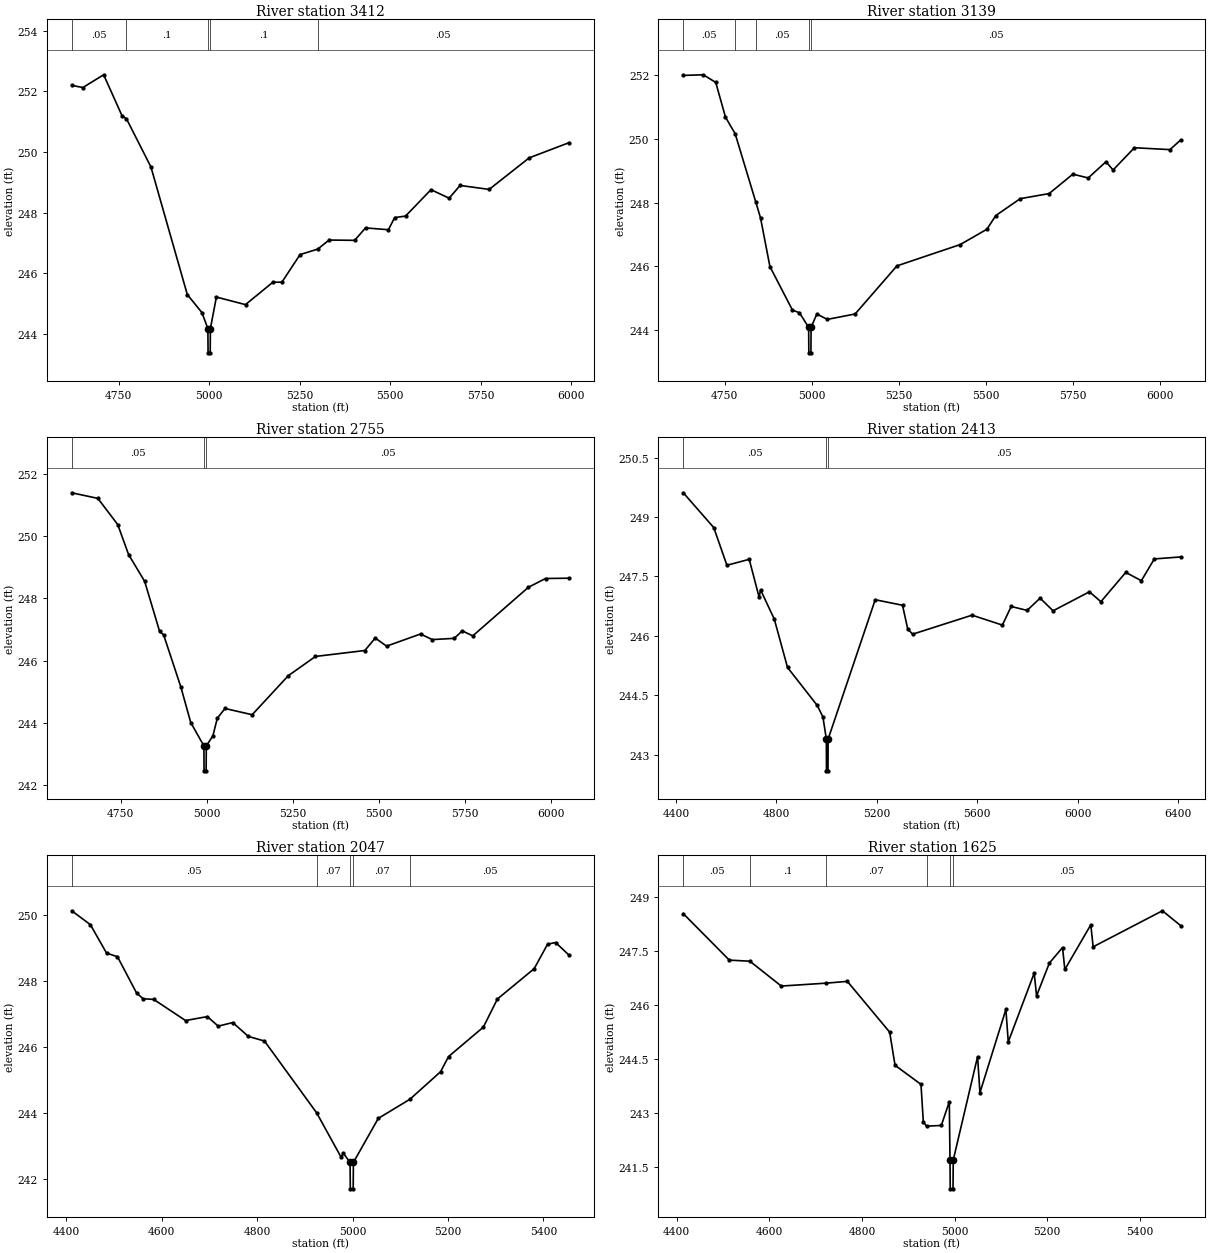
Type RM Length L Ch R = 1,3412,273,273,273
BEGIN DESCRIPTION:
Mapping XS de002a3d
END DESCRIPTION:
XS GIS Cut Line= 2
      2133142.83     13385957.27      2131775.62     13386087.49
#Sta/Elev= 30
  4620.0  252.20  4650.9  252.13  4708.2  252.55  4758.9  251.20  4771.2  251.10
  4838.8  249.51  4939.3  245.30  4979.5  244.71  4996.1  244.18  4996.6  243.38
  5002.5  243.38  5003.0  244.18  5019.6  245.22  5100.0  244.97  5175.7  245.71
  5200.4  245.71  5250.7  246.62  5299.2  246.80  5331.0  247.10  5401.4  247.09
  5431.5  247.50  5494.7  247.44  5511.9  247.84  5542.0  247.89  5612.3  248.76
  5662.5  248.48  5692.7  248.90  5773.0  248.77  5883.5  249.81  5993.4  250.31
#Mann=5,-1,0
  4620.0    0.05       0  4771.2     0.1       0  4996.1    0.07       0
  5003.0     0.1       0  5299.2    0.05       0
Bank Sta=4996.1,5003
Exp/Cntr=0.3,0.1

Type RM Length L Ch R = 1,3139,384,384,384
BEGIN DESCRIPTION:
Mapping XS bc977181
END DESCRIPTION:
XS GIS Cut Line= 4
      2133135.00     13385873.93      2132929.28     13385733.32
      2132476.16     13385735.92      2131765.18     13385881.76
#Sta/Elev= 30
  4631.4  251.99  4688.7  252.01  4724.6  251.77  4752.5  250.68  4780.3  250.16
  4839.7  248.01  4853.3  247.51  4880.1  245.99  4944.9  244.62  4964.9  244.54
  4991.4  244.08  4991.9  243.28  4997.9  243.28  4998.4  244.08  5014.9  244.50
  5044.9  244.33  5124.9  244.50  5244.9  246.01  5426.8  246.68  5503.3  247.16
  5528.9  247.59  5599.0  248.12  5682.0  248.28  5750.2  248.89  5794.3  248.77
  5845.3  249.28  5865.7  249.02  5927.0  249.72  6029.1  249.66  6059.5  249.96
#Mann=5,-1,0
  4631.4    0.05       0  4780.3     0.1       0  4839.7    0.05       0
  4991.4    0.03       0  4998.4    0.05       0
Bank Sta=4991.4,4998.4
Exp/Cntr=0.3,0.1

Type RM Length L Ch R = 1,2755,342,342,342
BEGIN DESCRIPTION:
Mapping XS 4265b696
END DESCRIPTION:
XS GIS Cut Line= 4
      2133192.32     13385842.73      2133116.78     13385597.90
      2132851.16     13385392.17      2132008.73     13385519.58
#Sta/Elev= 30
  4607.9  251.39  4683.8  251.21  4741.6  250.37  4773.0  249.41  4819.7  248.55
  4863.0  246.95  4874.9  246.83  4924.6  245.17  4953.6  244.02  4991.8  243.27
  4992.3  242.47  4998.3  242.47  4998.8  243.27  5017.9  243.59  5030.8  244.16
  5053.2  244.47  5132.0  244.27  5236.7  245.52  5315.9  246.14  5459.2  246.33
  5489.5  246.73  5522.4  246.47  5621.0  246.86  5655.0  246.68  5718.8  246.72
  5742.3  246.96  5772.7  246.80  5934.5  248.36  5984.0  248.64  6052.1  248.65
#Mann=3,-1,0
  4607.9    0.05       0  4991.8    0.03       0  4998.8    0.05       0
Bank Sta=4991.8,4998.8
Exp/Cntr=0.3,0.1

Type RM Length L Ch R = 1,2413,366,366,366
BEGIN DESCRIPTION:
UNT 018 in La Jarita Watershed 3.0
END DESCRIPTION:
XS GIS Cut Line= 3
      2133511.76     13385831.43      2133178.41     13385141.30
      2132003.92     13385451.20
#Sta/Elev= 30
  4429.3  249.61  4550.7  248.73  4603.0  247.78  4691.9  247.93  4731.5  246.97
  4737.0  247.16  4791.8  246.42  4844.5  245.20  4963.0  244.24  4985.6  243.95
  4999.2  243.39  4999.7  242.59  5005.7  242.59  5006.2  243.39  5193.9  246.91
  5302.7  246.77  5323.4  246.17  5343.1  246.04  5579.7  246.52  5700.5  246.27
  5735.6  246.74  5799.1  246.64  5850.8  246.95  5902.5  246.63  6047.3  247.11
  6093.0  246.86  6192.1  247.60  6254.2  247.39  6305.9  247.94  6410.4  247.99
#Mann=3,-1,0
  4429.3    0.05       0  4999.2    0.03       0  5006.2    0.05       0
Bank Sta=4999.2,5006.2
Exp/Cntr=0.3,0.1

Type RM Length L Ch R = 1,2047,422,422,422
BEGIN DESCRIPTION:
UNT 018 in La Jarita Watershed 2.0
END DESCRIPTION:
XS GIS Cut Line= 3
      2133868.86     13385810.55      2133596.30     13385227.24
      2133419.71     13384870.61
#Sta/Elev= 30
  4411.6  250.12  4450.7  249.70  4484.6  248.84  4507.5  248.73  4547.6  247.63
  4561.2  247.46  4583.3  247.44  4650.1  246.80  4695.8  246.92  4718.6  246.63
  4748.9  246.74  4781.7  246.32  4815.5  246.18  4924.7  244.01  4975.5  242.68
  4981.0  242.78  4994.8  242.51  4995.3  241.71  5001.3  241.71  5001.8  242.51
  5053.9  243.84  5120.2  244.42  5184.3  245.25  5201.1  245.71  5274.0  246.60
  5303.4  247.45  5380.6  248.37  5408.6  249.11  5425.4  249.16  5453.4  248.78
#Mann=5,-1,0
  4411.6    0.05       0  4924.7    0.07       0  4994.8    0.07       0
  5001.8    0.07       0  5120.2    0.05       0
Bank Sta=4994.8,5001.8
Exp/Cntr=0.3,0.1

Type RM Length L Ch R = 1,1625,44,44,44
BEGIN DESCRIPTION:
Mapping XS 961003b1
END DESCRIPTION:
XS GIS Cut Line= 4
      2134114.52     13385692.48      2134041.61     13385317.52
      2133953.92     13384786.83      2133839.23     13384685.36
#Sta/Elev= 30
  4414.6  248.54  4513.9  247.25  4558.3  247.22  4626.0  246.53  4722.1  246.61
  4768.6  246.66  4859.9  245.25  4871.5  244.33  4927.5  243.80  4932.5  242.76
  4939.4  242.64  4971.4  242.66  4988.6  243.32  4990.1  241.70  4990.6  240.90
  4996.6  240.90  4997.1  241.70  5049.6  244.57  5054.7  243.57  5110.7  245.88
  5115.8  244.98  5171.8  246.89  5176.9  246.26  5204.6  247.17  5232.9  247.60
  5237.9  246.99  5293.9  248.23  5299.0  247.62  5448.5  248.62  5487.6  248.21
#Mann=6,-1,0
  4414.6    0.05       0  4558.3     0.1       0  4722.1    0.07       0
  4939.4    0.05       0  4990.1    0.03       0  4997.1    0.05       0
Bank Sta=4990.1,4997.1
Exp/Cntr=0.3,0.1

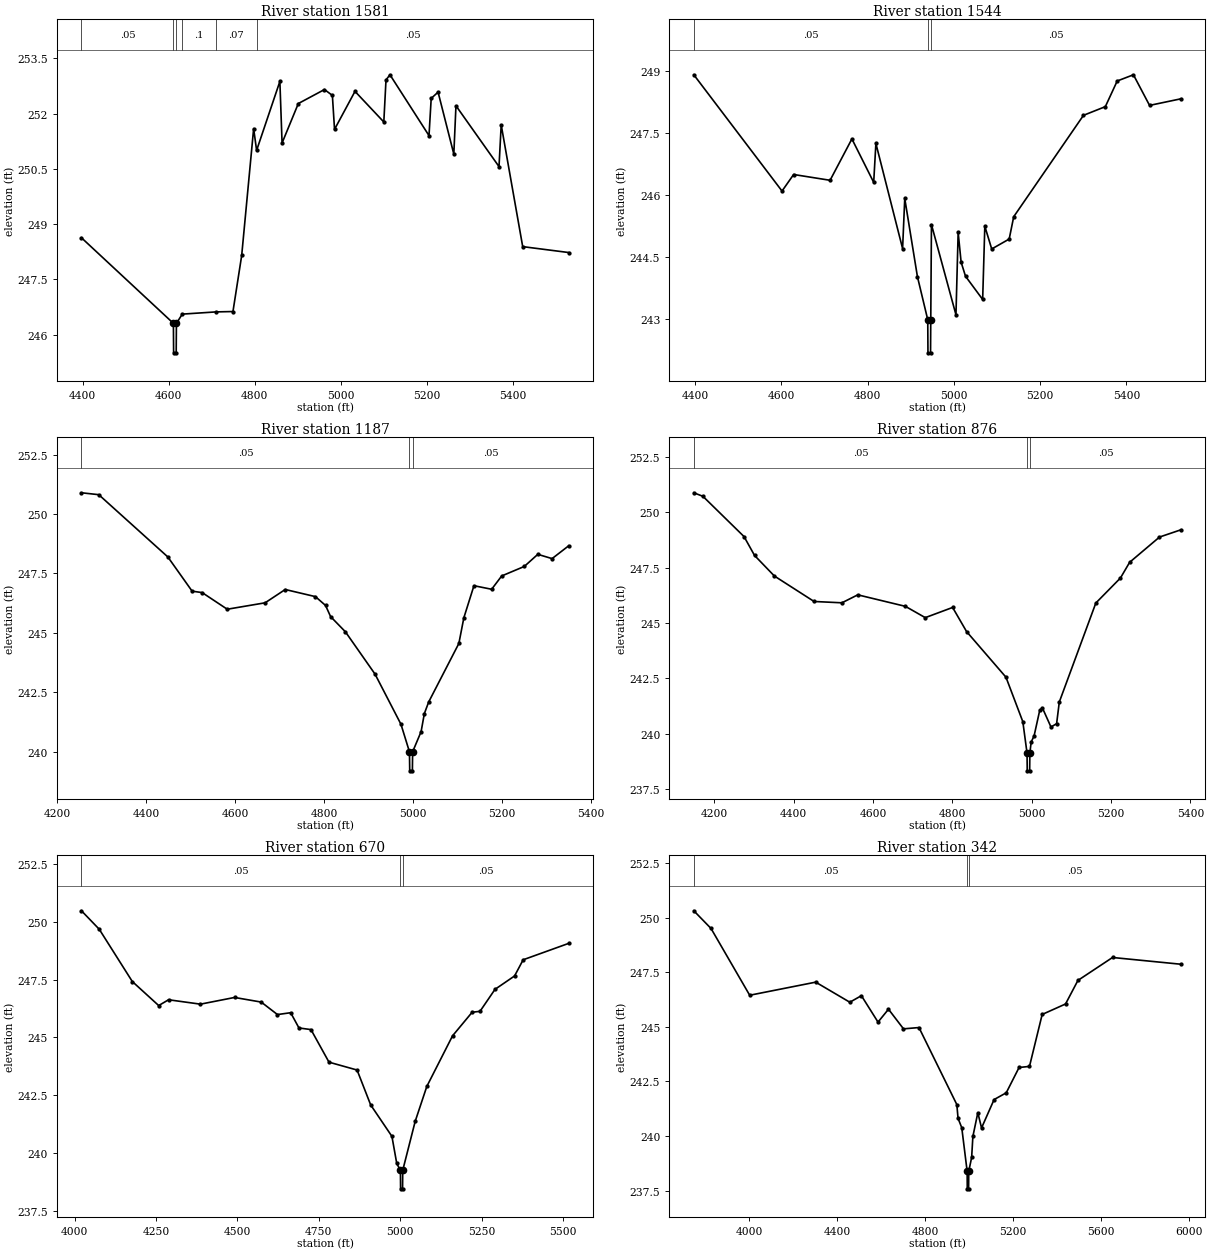
Type RM Length L Ch R = 1,1581,37,37,37
BEGIN DESCRIPTION:
Mapping XS 1b0a89ef
END DESCRIPTION:
XS GIS Cut Line= 4
      2134145.78     13385692.56      2134037.25     13385036.83
      2133974.75     13384703.49      2133861.88     13384640.41
#Sta/Elev= 30
  4397.3  248.63  4611.1  246.31  4611.6  245.51  4617.6  245.51  4618.1  246.31
  4631.8  246.56  4710.1  246.62  4749.6  246.63  4769.9  248.15  4797.7  251.59
  4804.6  251.00  4858.7  252.87  4863.8  251.20  4901.6  252.27  4962.4  252.65
  4980.8  252.49  4985.8  251.57  5033.4  252.60  5100.4  251.77  5105.5  252.91
  5114.7  253.05  5205.5  251.40  5210.6  252.41  5226.6  252.58  5263.2  250.90
  5268.2  252.21  5368.3  250.56  5373.4  251.69  5423.4  248.39  5530.4  248.23
#Mann=6,-1,0
  4397.3    0.05       0  4611.1    0.03       0  4618.1    0.05       0
  4631.8     0.1       0  4710.1    0.07       0  4804.6    0.05       0
Bank Sta=4611.1,4618.1
Exp/Cntr=0.3,0.1

Type RM Length L Ch R = 1,1544,357,357,357
BEGIN DESCRIPTION:
Mapping XS 1a3fc689
END DESCRIPTION:
XS GIS Cut Line= 3
      2134177.02     13385676.86      2134020.78     13384705.54
      2133888.95     13384643.50
#Sta/Elev= 30
  4397.0  248.91  4601.5  246.10  4628.4  246.50  4712.9  246.36  4763.5  247.36
  4814.0  246.31  4819.1  247.25  4881.0  244.71  4886.0  245.92  4915.4  244.03
  4939.3  242.99  4939.8  242.19  4945.8  242.19  4946.3  242.99  4947.9  245.29
  5004.7  243.11  5009.8  245.10  5016.7  244.38  5026.9  244.04  5066.6  243.48
  5071.6  245.25  5087.6  244.70  5128.1  244.94  5138.6  245.48  5300.3  247.93
  5351.0  248.14  5378.5  248.76  5416.1  248.91  5453.5  248.17  5526.5  248.33
#Mann=3,-1,0
  4397.0    0.05       0  4939.3    0.03       0  4946.3    0.05       0
Bank Sta=4939.3,4946.3
Exp/Cntr=0.3,0.1

Type RM Length L Ch R = 1,1187,311,311,311
BEGIN DESCRIPTION:
Mapping XS 2c4bb339
END DESCRIPTION:
XS GIS Cut Line= 2
      2134679.61     13385550.11      2134205.68     13384562.32
#Sta/Elev= 30
  4254.0  250.89  4292.9  250.81  4448.2  248.19  4502.8  246.75  4525.4  246.69
  4581.8  245.99  4666.9  246.26  4712.2  246.82  4780.1  246.52  4802.8  246.15
  4814.2  245.68  4847.5  245.04  4914.1  243.26  4972.4  241.15  4991.5  239.99
  4992.1  239.19  4998.1  239.19  4998.6  239.99  5017.7  240.84  5025.0  241.60
  5034.8  242.09  5102.6  244.55  5113.8  245.63  5136.5  246.98  5176.3  246.83
  5198.9  247.39  5249.7  247.79  5280.1  248.30  5312.2  248.12  5349.6  248.66
#Mann=3,-1,0
  4254.0    0.05       0  4991.5    0.03       0  4998.6    0.05       0
Bank Sta=4991.5,4998.6
Exp/Cntr=0.3,0.1

Type RM Length L Ch R = 1,876,206,206,206
BEGIN DESCRIPTION:
Mapping XS f3492f6d
END DESCRIPTION:
XS GIS Cut Line= 4
      2134738.66     13385498.03      2134745.60     13384850.50
      2134504.28     13384590.09      2134298.84     13384498.59
#Sta/Elev= 30
  4148.8  250.88  4171.8  250.72  4275.4  248.90  4301.8  248.05  4351.8  247.12
  4451.8  245.97  4521.9  245.91  4561.9  246.27  4681.9  245.75  4731.9  245.24
  4800.8  245.70  4836.0  244.61  4935.2  242.55  4977.7  240.54  4988.3  239.12
  4988.8  238.32  4994.9  238.32  4995.4  239.12  4998.7  239.62  5006.1  239.90
  5020.2  241.05  5027.1  241.16  5048.6  240.30  5062.8  240.45  5069.6  241.43
  5161.6  245.90  5223.6  247.03  5246.8  247.74  5322.0  248.88  5376.3  249.21
#Mann=3,-1,0
  4148.8    0.05       0  4988.3    0.03       0  4995.4    0.05       0
Bank Sta=4988.3,4995.4
Exp/Cntr=0.3,0.1

Type RM Length L Ch R = 1,670,328,328,328
BEGIN DESCRIPTION:
Mapping XS de9673fc
END DESCRIPTION:
XS GIS Cut Line= 4
      2134789.00     13385478.98      2134905.32     13384788.00
      2134662.27     13384442.52      2134289.02     13384470.30
#Sta/Elev= 30
  4020.6  250.48  4075.3  249.68  4176.8  247.42  4257.9  246.38  4288.3  246.63
  4386.3  246.44  4491.1  246.73  4573.0  246.53  4622.9  245.99  4663.5  246.07
  4689.0  245.41  4725.9  245.34  4781.3  243.93  4867.6  243.59  4909.4  242.08
  4974.7  240.72  4989.5  239.55  5000.8  239.25  5001.3  238.45  5007.4  238.45
  5007.9  239.25  5046.2  241.37  5081.9  242.88  5161.0  245.07  5221.2  246.09
  5245.4  246.13  5291.4  247.08  5351.6  247.66  5378.0  248.36  5518.0  249.07
#Mann=3,-1,0
  4020.6    0.05       0  5000.8    0.03       0  5007.9    0.05       0
Bank Sta=5000.8,5007.9
Exp/Cntr=0.3,0.1

Type RM Length L Ch R = 1,342,0,0,0
BEGIN DESCRIPTION:
UNT 018 in La Jarita Watershed 1.0
END DESCRIPTION:
XS GIS Cut Line= 4
      2134807.24     13385520.62      2135067.65     13384531.06
      2134885.36     13384161.27      2134147.69     13384410.62
#Sta/Elev= 30
  3748.1  250.32  3826.3  249.51  4002.1  246.45  4302.0  247.05  4457.1  246.13
  4509.7  246.43  4585.2  245.22  4632.8  245.81  4701.0  244.91  4771.3  244.97
  4943.4  241.44  4948.9  240.81  4965.8  240.38  4990.3  238.38  4990.8  237.58
  4996.9  237.58  4997.5  238.38  5010.7  239.02  5016.3  239.98  5038.8  241.07
  5055.7  240.37  5112.6  241.67  5167.9  241.98  5226.2  243.14  5273.5  243.19
  5331.2  245.57  5437.4  246.05  5493.7  247.13  5650.9  248.18  5962.3  247.87
#Mann=3,-1,0
  3748.1    0.05       0  4990.3    0.03       0  4997.5    0.05       0
Bank Sta=4990.3,4997.5
Exp/Cntr=0.3,0.1

Chan Stop Cuts=-1