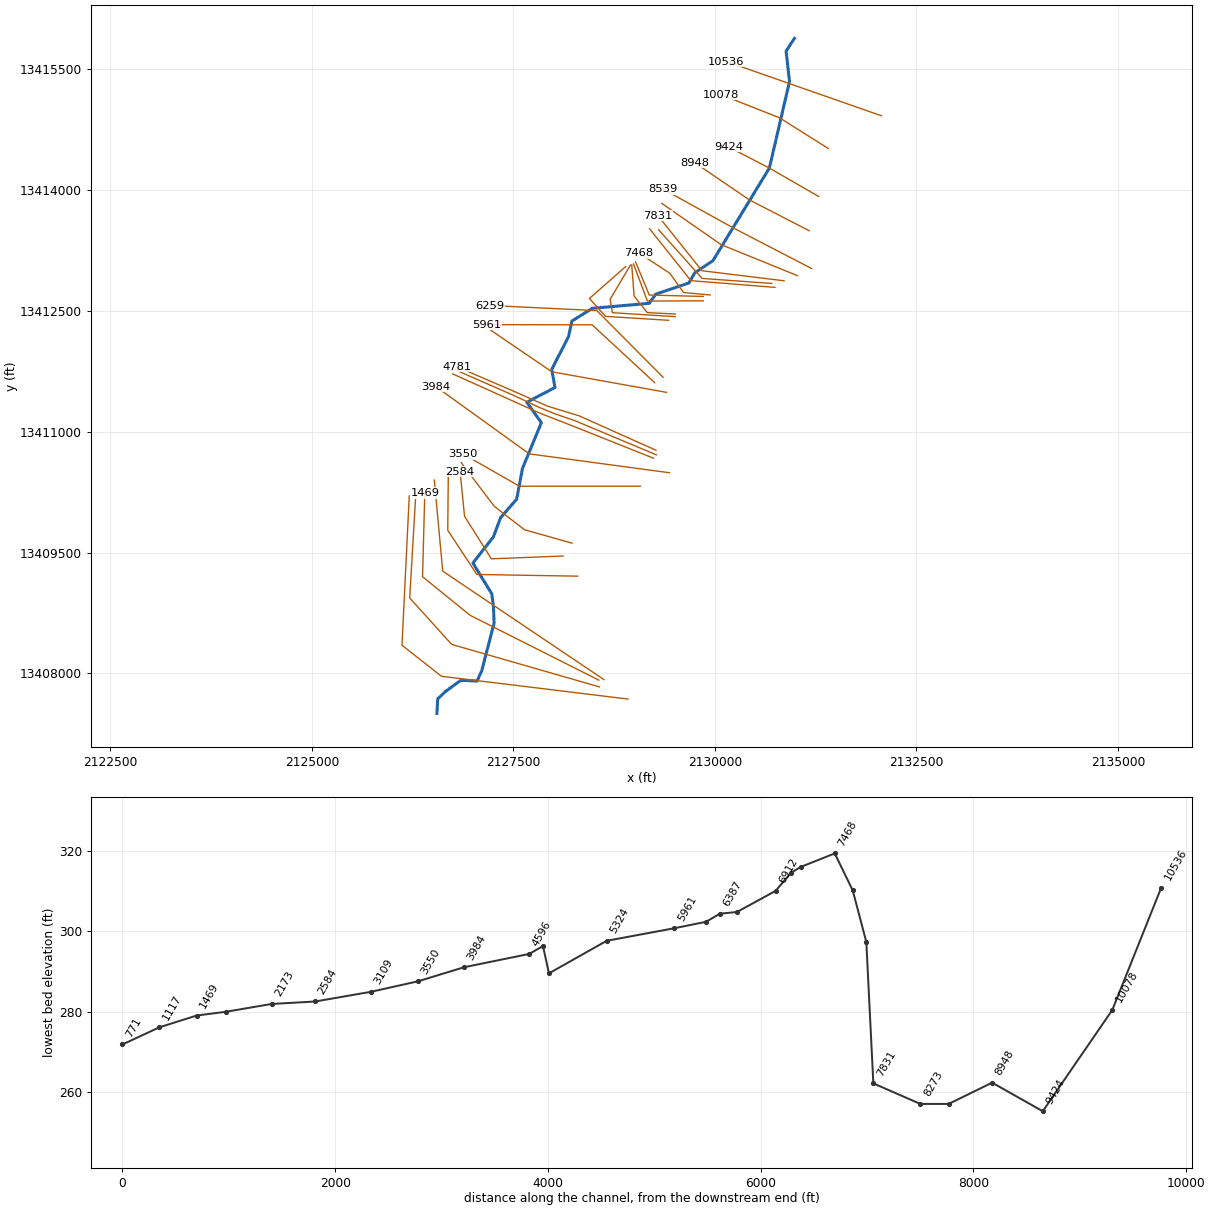
--- UNT 021 in La Jarita Watershed.prj (project) ---

Proj Title=UNT 021 in La Jarita Watershed Base Level Engineering
Current Plan=p01
Default Exp/Contr=0.3,0.1
English Units
Geom File=g01
Flow File=f01
Plan File=p01
BEGIN DESCRIPTION:
UNT 021 in La Jarita Watershed
END DESCRIPTION:

--- UNT 021 in La Jarita Watershed.p01 (plan) ---

Plan Title=Multiple Run
Short Identifier=Multiple
Geom File=g01
Flow File=f01
Subcritical Flow
K Sum by GR= 0
Std Step Tol= 0.01
Critical Tol= 0.01
Num of Std Step Trials= 20
Max Error Tol= 0.3
Flow Tol Ratio= 0.001
Split Flow NTrial= 30
Split Flow Tol= 0.02
Split Flow Ratio= 0.02
Log Output Level= 0
Friction Slope Method= 1
Unsteady Friction Slope Method= 2
Unsteady Bridges Friction Slope Method= 1
Parabolic Critical Depth
Global Vel Dist=  1 , 1 , 1
Global Log Level= 0
CheckData=True
Encroach Param= -1, 0, 0, 0
BEGIN DESCRIPTION:
Multiple Run
END DESCRIPTION:

--- UNT 021 in La Jarita Watershed.f01 (steady flow) ---

Flow Title=Multiple
Number of Profiles=7
Profile Names=10-year,25-year,50-year,1pct_min,100-year,1pct_plu,500-year
River Rch & RM= UNT 021 in La Ja,Reach-1,10536
     147     196     236     141     282     562     410
River Rch & RM= UNT 021 in La Ja,Reach-1,6259
     180     244     296     179     357     712     527
River Rch & RM= UNT 021 in La Ja,Reach-1,3109
     252     349     428     262     523    1043     792
Boundary for River Rch & Prof#=UNT 021 in La Ja,Reach-1,1
Up Type=0
Dn Type=3
Dn Slope=0.005
Boundary for River Rch & Prof#=UNT 021 in La Ja,Reach-1,2
Up Type=0
Dn Type=3
Dn Slope=0.005
Boundary for River Rch & Prof#=UNT 021 in La Ja,Reach-1,3
Up Type=0
Dn Type=3
Dn Slope=0.005
Boundary for River Rch & Prof#=UNT 021 in La Ja,Reach-1,4
Up Type=0
Dn Type=3
Dn Slope=0.005
Boundary for River Rch & Prof#=UNT 021 in La Ja,Reach-1,5
Up Type=0
Dn Type=3
Dn Slope=0.005
Boundary for River Rch & Prof#=UNT 021 in La Ja,Reach-1,6
Up Type=0
Dn Type=3
Dn Slope=0.005
Boundary for River Rch & Prof#=UNT 021 in La Ja,Reach-1,7
Up Type=0
Dn Type=3
Dn Slope=0.005

--- UNT 021 in La Jarita Watershed.g01 (geometry) ---

Geom Title=Existing Conditions

River Reach=UNT 021 in La Ja,Reach-1
Reach XY= 30
      2130985.70     13415885.70      2130882.73     13415727.57
      2130925.00     13415350.00      2130675.00     13414275.00
      2129974.80     13413124.80      2129750.00     13412975.00
      2129676.50     13412848.55      2129264.61     13412708.63
      2129184.75     13412595.79      2128477.96     13412533.59
      2128225.00     13412375.00      2128183.93     13412183.20
      2127975.00     13411775.00      2128015.68     13411550.85
      2127664.98     13411366.82      2127846.65     13411114.54
      2127612.27     13410545.97      2127539.82     13410163.56
      2127340.80     13409934.54      2127250.80     13409694.54
      2126996.98     13409371.58      2127231.36     13408988.76
      2127252.19     13408835.12      2127260.00     13408624.18
      2127106.36     13408033.03      2127049.07     13407905.43
      2126848.55     13407915.85      2126655.84     13407775.22
      2126560.80     13407684.54      2126550.80     13407504.54

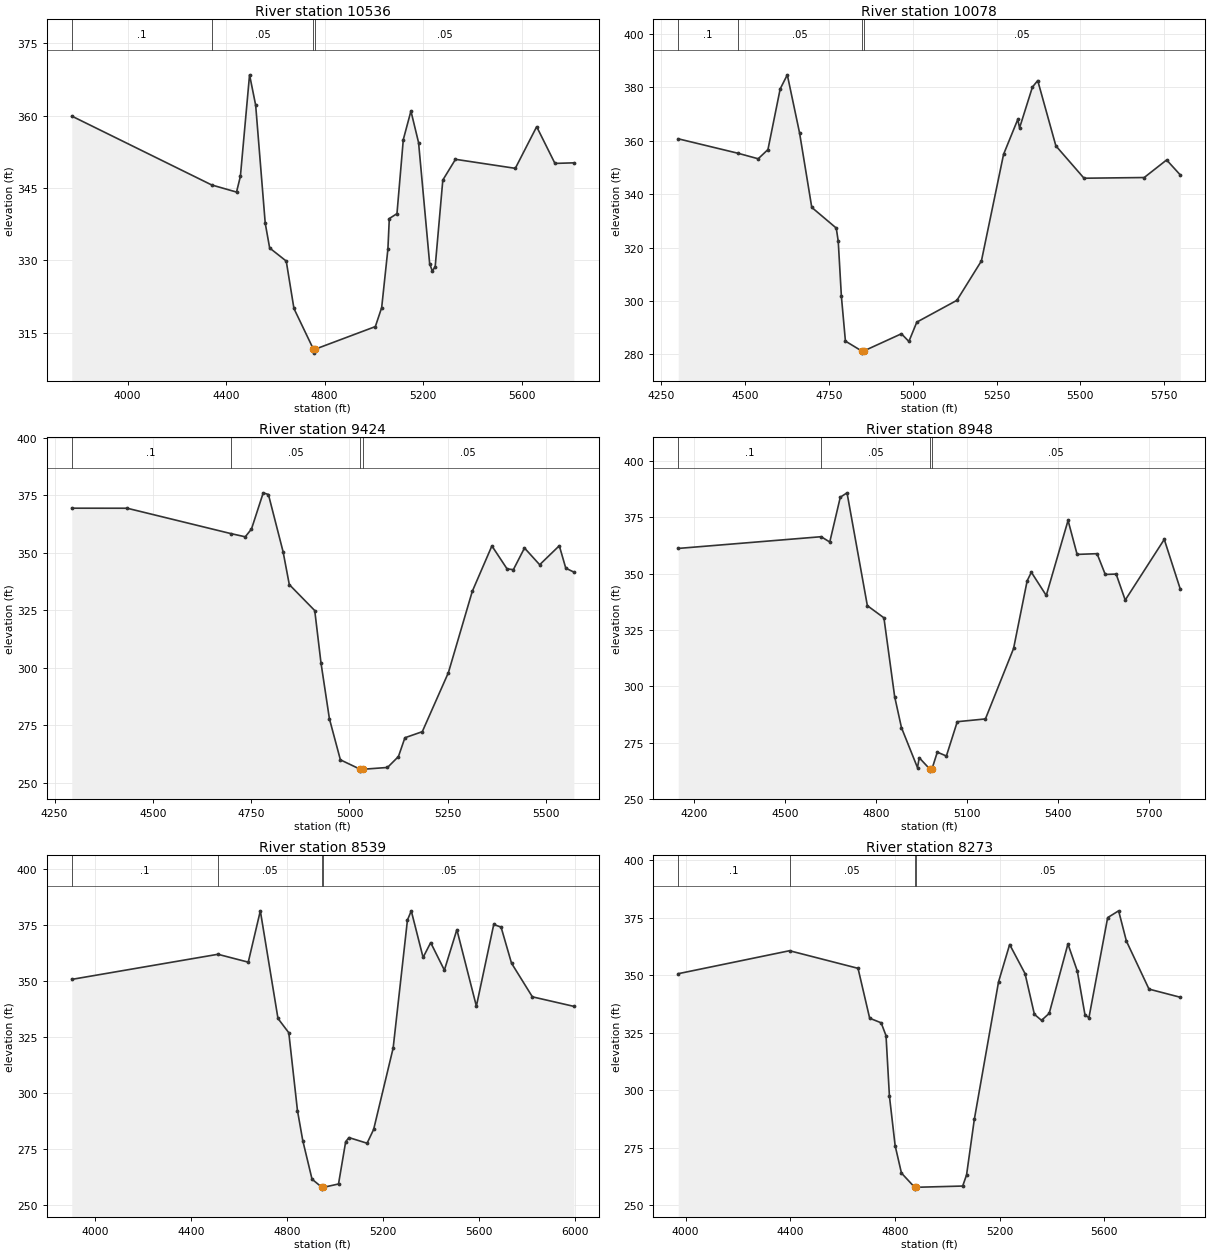
Type RM Length L Ch R = 1,10536,458,458,458
BEGIN DESCRIPTION:
Mapping XS 4aed504f
END DESCRIPTION:
XS GIS Cut Line= 2
      2132066.18     13414923.82      2130142.61     13415597.42
#Sta/Elev= 30
  3773.7  359.92  4341.9  345.64  4442.5  344.17  4458.2  347.43  4495.4  368.47
  4520.2  362.18  4559.0  337.72  4577.0  332.58  4644.3  329.87  4675.6  320.04
  4754.8  311.59  4755.3  310.79  4760.8  311.59  5006.0  316.29  5031.7  320.22
  5057.0  332.36  5062.7  338.68  5093.8  339.70  5119.5  355.05  5150.5  360.96
  5181.5  354.42  5226.5  329.33  5237.1  327.83  5248.9  328.68  5279.9  346.66
  5331.3  350.96  5574.2  349.09  5660.9  357.72  5735.1  350.11  5811.8  350.23
#Mann=4,-1,0
  3773.7     0.1       0  4341.9    0.05       0  4754.8    0.03       0
  4760.8    0.05       0
Bank Sta=4754.8,4760.8
Exp/Cntr=0.3,0.1

Type RM Length L Ch R = 1,10078,654,654,654
BEGIN DESCRIPTION:
UNT 021 in La Jarita Watershed 23.0
END DESCRIPTION:
XS GIS Cut Line= 3
      2131406.60     13414517.70      2130800.00     13414900.00
      2130074.94     13415186.14
#Sta/Elev= 30
  4301.3  360.76  4479.3  355.35  4539.6  353.28  4568.7  356.73  4605.2  379.48
  4626.4  384.74  4662.8  363.06  4699.3  335.06  4772.3  327.31  4778.2  322.38
  4787.6  301.72  4799.6  284.95  4848.2  281.24  4848.7  280.44  4854.2  281.24
  4966.5  287.69  4988.8  284.81  5012.4  292.06  5131.9  300.23  5205.0  315.00
  5271.0  354.95  5313.3  368.02  5318.7  364.86  5357.0  380.15  5372.8  382.59
  5426.9  358.12  5510.8  345.99  5690.2  346.25  5757.0  352.84  5797.8  347.21
#Mann=4,-1,0
  4301.3     0.1       0  4479.3    0.05       0  4848.2    0.03       0
  4854.2    0.05       0
Bank Sta=4848.2,4854.2
Exp/Cntr=0.3,0.1

Type RM Length L Ch R = 1,9424,476,476,476
BEGIN DESCRIPTION:
UNT 021 in La Jarita Watershed 20.0
END DESCRIPTION:
XS GIS Cut Line= 3
      2131286.78     13413922.24      2130675.00     13414275.00
      2130168.51     13414537.77
#Sta/Elev= 30
  4293.8  369.32  4434.8  369.30  4697.6  358.33  4735.0  356.90  4750.8  360.28
  4780.7  375.99  4793.9  375.26  4831.2  350.41  4847.0  336.16  4911.7  324.88
  4927.5  302.26  4949.0  277.92  4976.9  260.10  5027.4  255.99  5027.9  255.19
  5033.4  255.99  5096.7  256.78  5124.5  261.51  5141.0  269.68  5185.2  272.31
  5251.6  297.96  5312.3  333.22  5362.2  352.95  5400.8  342.97  5416.8  342.64
  5445.1  352.05  5483.7  344.78  5533.6  353.02  5550.1  343.28  5570.6  341.59
#Mann=4,-1,0
  4293.8     0.1       0  4697.6    0.05       0  5027.4    0.03       0
  5033.4    0.05       0
Bank Sta=5027.4,5033.4
Exp/Cntr=0.3,0.1

Type RM Length L Ch R = 1,8948,409,409,409
BEGIN DESCRIPTION:
UNT 021 in La Jarita Watershed 18.0
END DESCRIPTION:
XS GIS Cut Line= 3
      2131168.77     13413496.87      2130425.00     13413881.32
      2129749.29     13414341.90
#Sta/Elev= 30
  4149.0  361.16  4620.0  366.36  4648.5  364.01  4683.2  383.89  4705.4  385.84
  4772.4  335.75  4827.0  330.36  4862.4  295.37  4884.9  281.58  4937.7  263.85
  4943.3  268.27  4979.0  263.11  4979.5  262.31  4985.0  263.11  5003.0  270.73
  5032.9  269.02  5068.8  284.25  5161.6  285.48  5254.4  316.76  5299.2  346.81
  5313.0  350.59  5362.1  340.28  5434.0  373.60  5463.8  358.51  5529.6  358.83
  5556.6  349.61  5592.5  349.78  5622.4  338.23  5751.1  365.18  5804.0  343.07
#Mann=4,-1,0
  4149.0     0.1       0  4620.0    0.05       0  4979.0    0.03       0
  4985.0    0.05       0
Bank Sta=4979,4985
Exp/Cntr=0.3,0.1

Type RM Length L Ch R = 1,8539,266,266,266
BEGIN DESCRIPTION:
UNT 021 in La Jarita Watershed 16.0
END DESCRIPTION:
XS GIS Cut Line= 3
      2131198.24     13413028.14      2130225.00     13413533.02
      2129352.78     13414015.97
#Sta/Elev= 30
  3903.6  350.69  4513.0  361.90  4639.5  358.38  4689.8  381.31  4763.4  333.23
  4808.5  326.85  4844.7  292.04  4866.8  278.66  4905.4  261.45  4946.7  257.81
  4947.2  257.01  4952.7  257.81  5015.8  259.31  5045.7  278.21  5059.3  280.03
  5134.9  277.51  5162.3  283.69  5243.6  320.02  5303.2  377.21  5319.2  381.28
  5368.4  360.48  5400.1  367.11  5457.2  354.82  5509.3  372.90  5590.6  338.74
  5663.0  375.21  5693.6  374.03  5737.1  357.93  5824.1  342.90  5997.0  338.64
#Mann=4,-1,0
  3903.6     0.1       0  4513.0    0.05       0  4946.7    0.03       0
  4952.7    0.05       0
Bank Sta=4946.7,4952.7
Exp/Cntr=0.3,0.1

Type RM Length L Ch R = 1,8273,442,442,442
BEGIN DESCRIPTION:
UNT 021 in La Jarita Watershed 15.0
END DESCRIPTION:
XS GIS Cut Line= 3
      2131022.88     13412939.60      2130075.00     13413325.00
      2129339.45     13413836.76
#Sta/Elev= 30
  3971.8  350.64  4397.2  360.62  4659.1  352.97  4703.6  331.29  4747.5  329.29
  4766.1  323.71  4779.1  297.46  4801.0  275.87  4825.1  263.99  4875.6  257.81
  4876.1  257.01  4881.6  257.81  5059.2  258.35  5074.0  263.19  5103.7  287.36
  5196.2  347.07  5238.7  363.32  5297.5  350.69  5333.3  332.98  5360.5  330.36
  5390.0  333.41  5461.5  363.56  5497.3  351.79  5527.0  332.56  5541.9  331.57
  5613.4  375.01  5655.3  377.96  5685.0  364.82  5771.4  343.94  5891.1  340.39
#Mann=4,-1,0
  3971.8     0.1       0  4397.2    0.05       0  4875.6    0.03       0
  4881.6    0.05       0
Bank Sta=4875.6,4881.6
Exp/Cntr=0.3,0.1

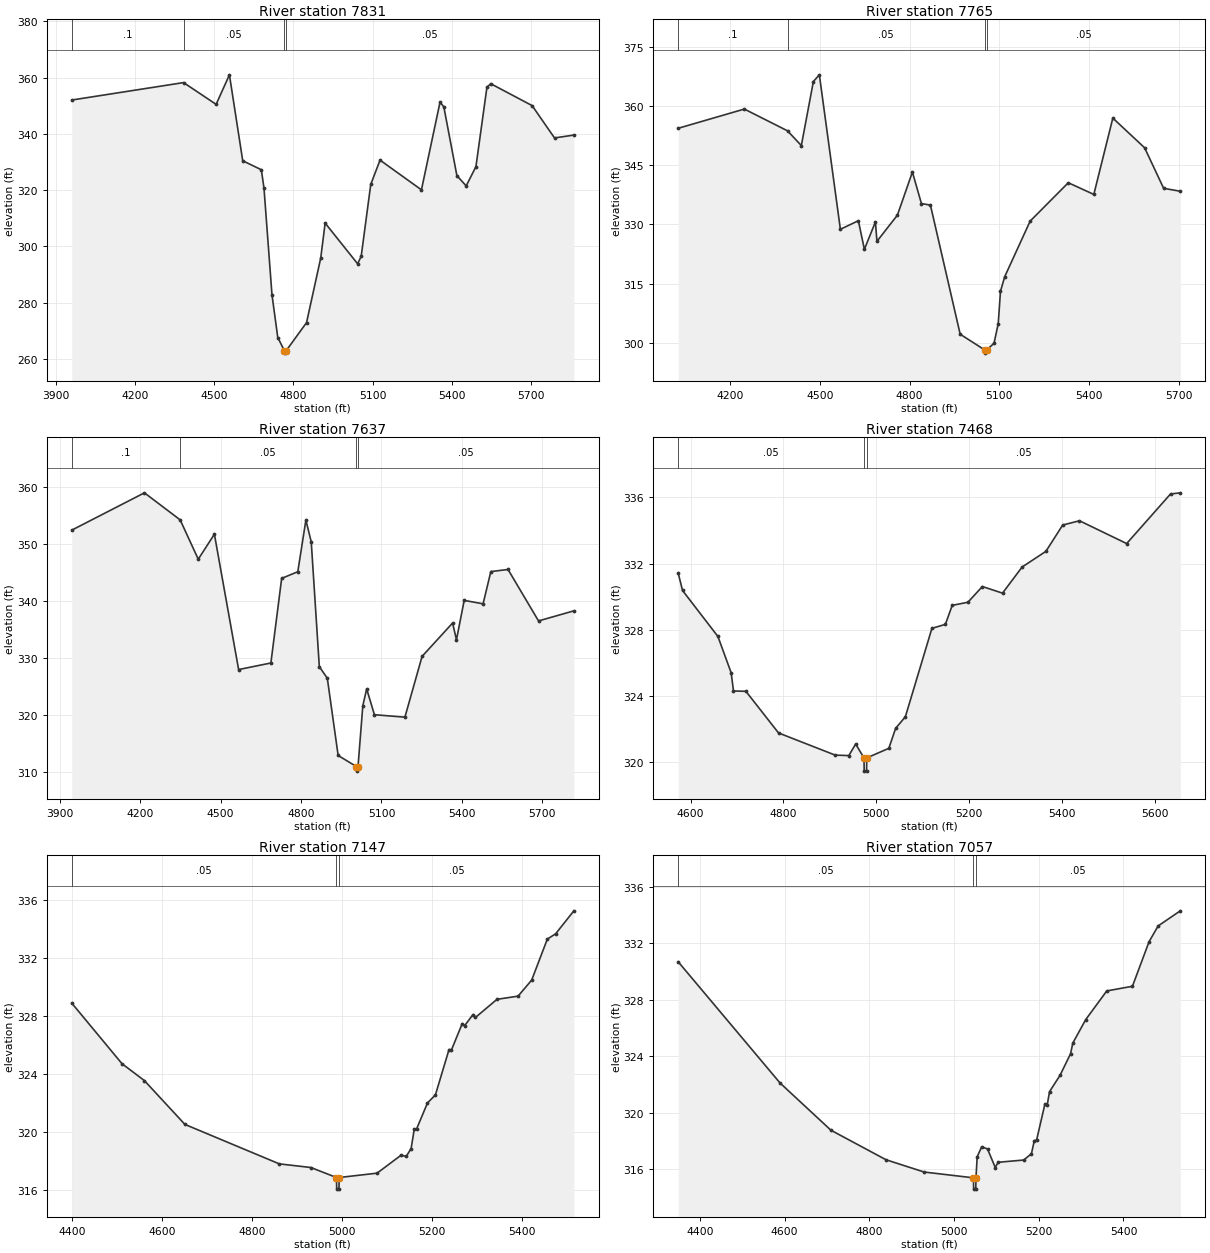
Type RM Length L Ch R = 1,7831,66,66,66
BEGIN DESCRIPTION:
UNT 021 in La Jarita Watershed 14.0
END DESCRIPTION:
XS GIS Cut Line= 3
      2130857.96     13412875.36      2129838.87     13413000.36
      2129291.99     13413684.40
#Sta/Elev= 30
  3960.3  352.02  4383.9  358.21  4507.3  350.48  4557.7  360.97  4608.1  330.45
  4678.6  327.26  4688.7  320.70  4718.9  282.89  4740.9  267.68  4766.3  262.93
  4766.8  262.13  4772.3  262.93  4849.9  272.96  4903.6  295.87  4920.4  308.31
  5043.5  293.86  5057.0  296.51  5093.2  322.03  5128.4  330.68  5285.3  320.12
  5355.7  351.25  5370.1  349.60  5419.7  325.14  5454.9  321.53  5491.8  328.36
  5533.4  356.53  5547.8  357.82  5704.7  350.04  5789.5  338.56  5862.8  339.57
#Mann=4,-1,0
  3960.3     0.1       0  4383.9    0.05       0  4766.3    0.03       0
  4772.3    0.05       0
Bank Sta=4766.3,4772.3
Exp/Cntr=0.3,0.1

Type RM Length L Ch R = 1,7765,128,128,128
BEGIN DESCRIPTION:
UNT 021 in La Jarita Watershed 13.0
END DESCRIPTION:
XS GIS Cut Line= 3
      2130705.18     13412842.37      2129840.61     13412904.87
      2129300.68     13413509.04
#Sta/Elev= 30
  4027.3  354.39  4248.1  359.26  4392.4  353.74  4438.5  350.00  4478.7  366.24
  4498.7  367.94  4568.9  328.78  4629.0  330.95  4649.1  323.70  4686.0  330.65
  4691.0  325.72  4759.4  332.37  4809.5  343.29  4839.6  335.30  4869.7  334.91
  4969.1  302.17  5051.3  298.18  5051.8  297.38  5057.3  298.18  5082.1  299.87
  5096.2  304.85  5103.7  313.06  5117.9  316.77  5202.8  330.85  5330.2  340.58
  5415.5  337.62  5479.0  356.97  5585.2  349.44  5648.7  339.17  5704.4  338.42
#Mann=4,-1,0
  4027.3     0.1       0  4392.4    0.05       0  5051.3    0.03       0
  5057.3    0.05       0
Bank Sta=5051.3,5057.3
Exp/Cntr=0.3,0.1

Type RM Length L Ch R = 1,7637,169,169,169
BEGIN DESCRIPTION:
Mapping XS 3aca6cde
END DESCRIPTION:
XS GIS Cut Line= 3
      2130745.09     13412793.76      2129701.72     13412877.10
      2129187.85     13413522.90
#Sta/Elev= 30
  3945.3  352.39  4216.2  358.92  4349.4  354.19  4416.9  347.31  4477.1  351.68
  4567.4  328.00  4687.7  329.15  4727.9  343.95  4788.1  345.12  4818.2  354.15
  4838.2  350.34  4868.3  328.51  4898.1  326.48  4938.5  312.97  5006.6  311.03
  5007.1  310.23  5012.6  311.03  5030.5  321.69  5044.9  324.61  5073.7  320.10
  5187.4  319.67  5251.5  330.31  5365.2  336.14  5379.6  333.21  5408.5  340.10
  5478.9  339.50  5507.8  345.14  5571.9  345.51  5685.6  336.51  5817.3  338.27
#Mann=4,-1,0
  3945.3     0.1       0  4349.4    0.05       0  5006.6    0.03       0
  5012.6    0.05       0
Bank Sta=5006.6,5012.6
Exp/Cntr=0.3,0.1

Type RM Length L Ch R = 1,7468,321,321,321
BEGIN DESCRIPTION:
Mapping XS 03d0c12b
END DESCRIPTION:
XS GIS Cut Line= 4
      2129940.05     13412699.23      2129610.21     13412729.61
      2129440.94     13412968.32      2129058.44     13413219.00
#Sta/Elev= 30
  4573.5  331.41  4582.8  330.37  4658.9  327.59  4687.5  325.39  4692.5  324.29
  4719.2  324.27  4789.5  321.75  4911.4  320.41  4940.8  320.38  4955.6  321.08
  4973.5  320.24  4974.0  319.44  4979.0  319.44  4979.5  320.24  5027.0  320.82
  5041.7  322.03  5062.6  322.73  5119.8  328.08  5148.8  328.32  5163.5  329.47
  5197.4  329.66  5228.4  330.61  5271.8  330.21  5314.0  331.79  5365.3  332.74
  5401.4  334.33  5437.6  334.59  5539.2  333.21  5633.6  336.21  5654.7  336.28
#Mann=3,-1,0
  4573.5    0.05       0  4973.5    0.03       0  4979.5    0.05       0
Bank Sta=4973.5,4979.5
Exp/Cntr=0.3,0.1

Type RM Length L Ch R = 1,7147,90,90,90
BEGIN DESCRIPTION:
Mapping XS c4597eea
END DESCRIPTION:
XS GIS Cut Line= 3
      2129856.47     13412681.05      2129184.86     13412698.41
      2129015.57     13413109.69
#Sta/Elev= 30
  4399.4  328.87  4510.9  324.70  4560.9  323.53  4651.0  320.51  4861.0  317.79
  4931.1  317.54  4988.1  316.85  4988.6  316.05  4993.6  316.05  4994.1  316.85
  5078.4  317.15  5131.8  318.39  5143.2  318.30  5154.1  318.85  5161.1  320.18
  5166.6  320.22  5190.5  321.99  5208.1  322.54  5238.4  325.67  5243.8  325.64
  5267.8  327.46  5273.2  327.32  5291.7  328.08  5297.1  327.88  5345.0  329.13
  5392.0  329.35  5422.3  330.46  5457.0  333.28  5475.6  333.65  5516.0  335.23
#Mann=3,-1,0
  4399.4    0.05       0  4988.1   0.035       0  4994.1    0.05       0
Bank Sta=4988.1,4994.1
Exp/Cntr=0.3,0.1

Type RM Length L Ch R = 1,7057,145,145,145
BEGIN DESCRIPTION:
Mapping XS 07e8287b
END DESCRIPTION:
XS GIS Cut Line= 3
      2129855.43     13412626.80      2129162.07     13412623.54
      2128989.77     13413084.10
#Sta/Elev= 30
  4349.1  330.70  4589.5  322.12  4709.5  318.78  4839.5  316.69  4929.5  315.82
  5045.9  315.41  5046.4  314.61  5051.4  314.61  5051.9  315.41  5054.7  316.90
  5065.4  317.61  5079.2  317.45  5097.4  316.14  5104.1  316.51  5164.7  316.67
  5182.8  317.12  5189.6  318.04  5195.0  318.09  5214.6  320.63  5219.9  320.54
  5225.5  321.51  5250.2  322.66  5275.1  324.19  5280.5  324.95  5310.9  326.61
  5360.6  328.64  5421.2  328.97  5460.4  332.12  5481.8  333.24  5534.2  334.31
#Mann=3,-1,0
  4349.1    0.05       0  5045.9   0.035       0  5051.9    0.05       0
Bank Sta=5045.9,5051.9
Exp/Cntr=0.3,0.1

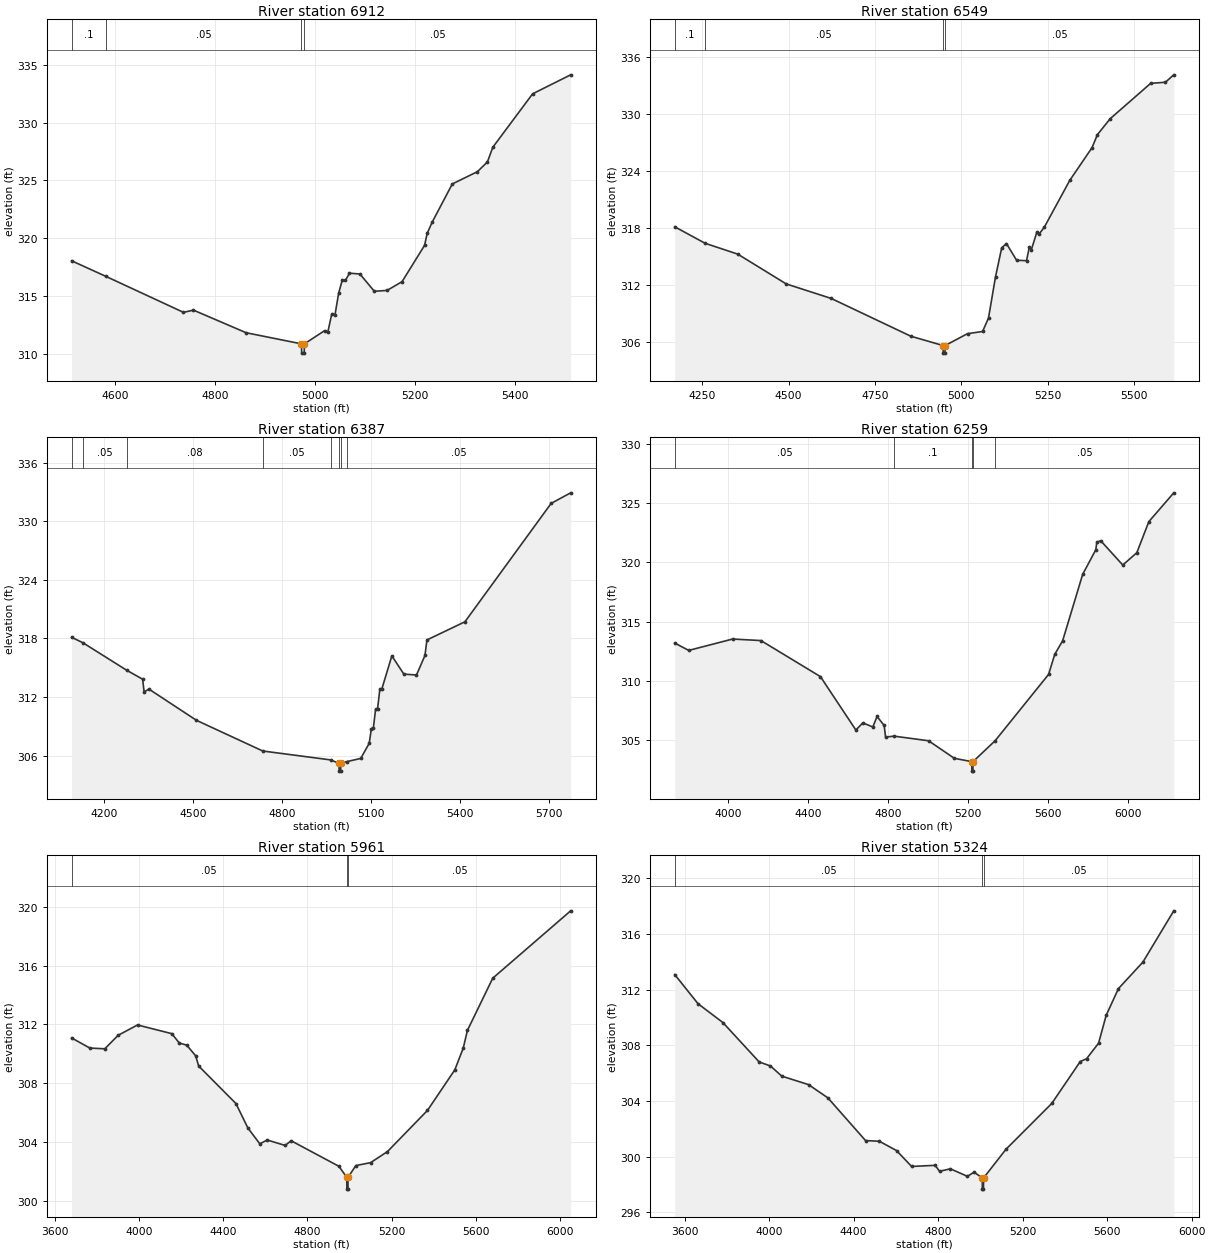
Type RM Length L Ch R = 1,6912,363,363,363
BEGIN DESCRIPTION:
Mapping XS 806089e0
END DESCRIPTION:
XS GIS Cut Line= 4
      2129508.23     13412462.95      2129159.90     13412480.31
      2128997.14     13412685.39      2128967.91     13413070.80
#Sta/Elev= 30
  4513.3  318.07  4582.0  316.72  4736.8  313.62  4756.8  313.81  4862.0  311.86
  4972.5  310.90  4973.0  310.10  4978.0  310.10  4978.5  310.90  5018.8  312.04
  5025.2  311.91  5033.2  313.50  5039.6  313.41  5046.8  315.26  5054.1  316.41
  5060.4  316.38  5068.5  317.00  5089.3  316.93  5118.1  315.44  5143.5  315.51
  5173.6  316.27  5218.5  319.40  5223.8  320.44  5233.8  321.41  5273.9  324.70
  5324.1  325.76  5344.1  326.60  5354.9  327.87  5434.4  332.48  5510.4  334.12
#Mann=4,-1,0
  4513.3     0.1       0  4582.0    0.05       0  4972.5   0.035       0
  4978.5    0.05       0
Bank Sta=4972.5,4978.5
Exp/Cntr=0.3,0.1

Type RM Length L Ch R = 1,6549,162,162,162
BEGIN DESCRIPTION:
Mapping XS 15947ff7
END DESCRIPTION:
XS GIS Cut Line= 4
      2129507.09     13412430.40      2128728.05     13412479.23
      2128699.83     13412646.33      2128951.85     13413071.40
#Sta/Elev= 30
  4170.4  318.15  4258.5  316.41  4352.8  315.27  4493.1  312.13  4623.4  310.60
  4853.8  306.62  4947.0  305.64  4947.5  304.84  4952.5  304.84  4953.0  305.64
  5017.7  306.89  5061.3  307.12  5078.5  308.54  5098.8  312.89  5116.7  315.94
  5130.5  316.38  5159.8  314.62  5188.6  314.58  5196.8  316.05  5202.6  315.75
  5218.3  317.57  5224.1  317.35  5239.7  318.09  5313.8  323.05  5378.1  326.49
  5393.7  327.86  5430.7  329.54  5547.7  333.26  5590.5  333.38  5614.6  334.16
#Mann=4,-1,0
  4170.4     0.1       0  4258.5    0.05       0  4947.0    0.03       0
  4953.0    0.05       0
Bank Sta=4947,4953
Exp/Cntr=0.3,0.1

Type RM Length L Ch R = 1,6387,128,128,128
BEGIN DESCRIPTION:
Mapping XS 0a286210
END DESCRIPTION:
XS GIS Cut Line= 4
      2129424.77     13412384.85      2128642.43     13412433.68
      2128442.78     13412656.12      2128891.85     13413051.08
#Sta/Elev= 30
  4091.0  318.11  4129.2  317.55  4276.3  314.74  4330.2  313.82  4335.2  312.51
  4351.3  312.81  4511.6  309.61  4734.8  306.47  4963.2  305.56  4991.6  305.21
  4992.1  304.41  4997.1  304.41  4997.6  305.21  5017.3  305.38  5064.8  305.71
  5093.2  307.25  5100.7  308.74  5107.4  308.85  5114.9  310.75  5121.6  310.82
  5129.1  312.78  5135.8  312.81  5169.6  316.21  5210.0  314.34  5252.6  314.25
  5281.1  316.25  5287.8  317.84  5415.8  319.70  5706.2  331.82  5771.8  332.90
#Mann=8,-1,0
  4091.0     0.1       0  4129.2    0.05       0  4276.3    0.08       0
  4734.8    0.05       0  4963.2     0.1       0  4991.6    0.07       0
  4997.6     0.1       0  5017.3    0.05       0
Bank Sta=4991.6,4997.6
Exp/Cntr=0.3,0.1

Type RM Length L Ch R = 1,6259,298,298,298
BEGIN DESCRIPTION:
UNT 021 in La Jarita Watershed 10.0
END DESCRIPTION:
XS GIS Cut Line= 3
      2129356.66     13411677.86      2128534.38     13412505.38
      2127210.77     13412568.52
#Sta/Elev= 30
  3735.5  313.20  3805.4  312.58  4024.6  313.54  4166.0  313.41  4463.0  310.37
  4639.8  305.87  4675.1  306.47  4724.6  306.12  4745.8  307.01  4781.2  306.25
  4788.3  305.27  4830.5  305.35  5002.9  304.96  5131.7  303.48  5218.8  303.20
  5219.3  302.40  5224.3  302.40  5224.8  303.20  5335.1  304.96  5602.3  310.56
  5633.0  312.25  5672.3  313.39  5772.5  319.00  5838.0  321.07  5843.0  321.70
  5862.6  321.83  5972.7  319.78  6042.8  320.82  6102.8  323.44  6227.2  325.87
#Mann=5,-1,0
  3735.5    0.05       0  4830.5     0.1       0  5218.8    0.07       0
  5224.8     0.1       0  5335.1    0.05       0
Bank Sta=5218.8,5224.8
Exp/Cntr=0.3,0.1

Type RM Length L Ch R = 1,5961,637,637,637
BEGIN DESCRIPTION:
UNT 021 in La Jarita Watershed 9.0
END DESCRIPTION:
XS GIS Cut Line= 3
      2129252.49     13411610.16      2128476.42     13412328.94
      2127165.21     13412330.65
#Sta/Elev= 30
  3681.0  311.08  3767.6  310.39  3838.5  310.34  3902.0  311.26  3993.8  311.96
  4156.6  311.37  4192.3  310.73  4227.4  310.59  4270.0  309.86  4284.1  309.17
  4461.0  306.62  4517.7  304.96  4574.4  303.88  4609.6  304.14  4694.6  303.77
  4723.0  304.09  4950.2  302.35  4987.2  301.60  4987.7  300.80  4992.8  300.80
  4993.3  301.60  5030.2  302.40  5100.2  302.60  5180.2  303.35  5370.2  306.15
  5500.2  308.91  5540.2  310.39  5560.2  311.60  5680.2  315.14  6050.0  319.72
#Mann=3,-1,0
  3681.0    0.05       0  4987.2   0.035       0  4993.3    0.05       0
Bank Sta=4987.2,4993.3
Exp/Cntr=0.3,0.1

Type RM Length L Ch R = 1,5324,543,543,543
BEGIN DESCRIPTION:
UNT 021 in La Jarita Watershed 8.0
END DESCRIPTION:
XS GIS Cut Line= 3
      2129398.28     13411490.40      2127976.42     13411745.60
      2127218.66     13412262.05
#Sta/Elev= 30
  3553.7  313.08  3664.2  310.98  3781.8  309.63  3953.3  306.80  4006.7  306.51
  4060.4  305.78  4186.9  305.17  4278.4  304.22  4456.7  301.15  4522.2  301.10
  4603.5  300.43  4674.6  299.29  4786.4  299.37  4806.7  298.94  4858.0  299.12
  4938.8  298.58  4970.4  298.88  5009.1  298.46  5009.6  297.66  5014.7  297.66
  5015.2  298.46  5121.0  300.52  5338.1  303.82  5472.9  306.83  5502.7  307.03
  5559.6  308.15  5595.5  310.15  5653.5  312.07  5769.0  313.97  5915.3  317.66
#Mann=3,-1,0
  3553.7    0.05       0  5009.1    0.03       0  5015.2    0.05       0
Bank Sta=5009.1,5015.2
Exp/Cntr=0.3,0.1

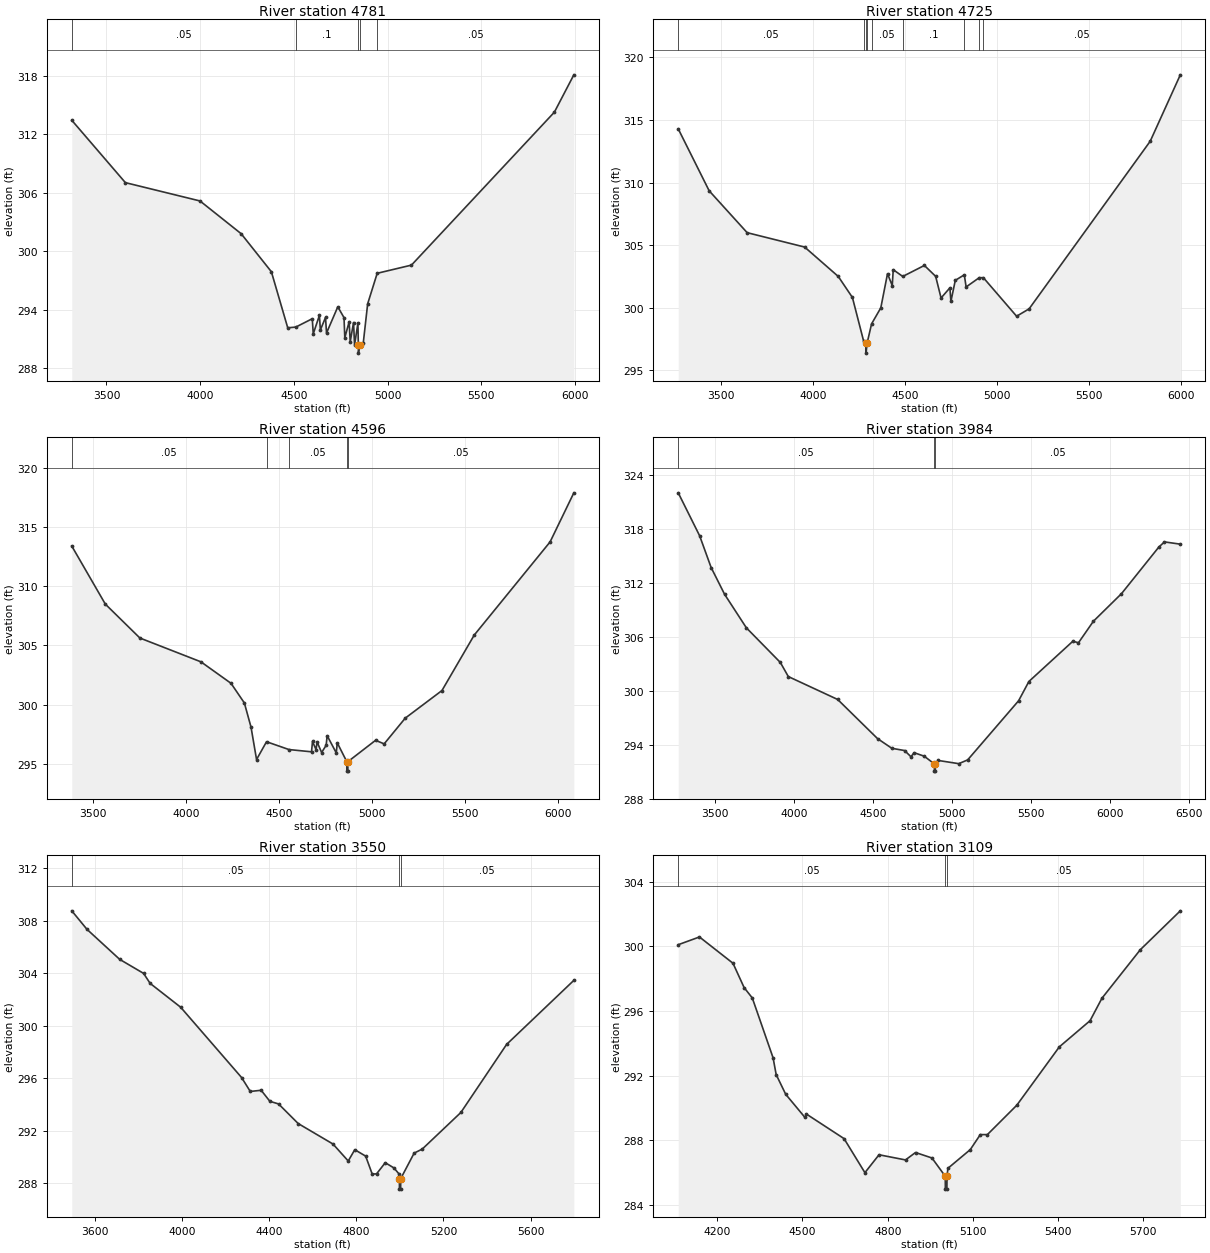
Type RM Length L Ch R = 1,4781,56,56,56
BEGIN DESCRIPTION:
Mapping XS d3847a82
END DESCRIPTION:
XS GIS Cut Line= 5
      2129268.06     13410771.65      2128314.96     13411198.73
      2127924.34     13411318.52      2127523.30     13411495.60
      2126799.63     13411807.98
#Sta/Elev= 30
  3314.8  313.44  3600.9  307.04  3999.3  305.16  4218.9  301.80  4380.1  297.90
  4467.4  292.15  4510.2  292.22  4598.4  293.08  4603.6  291.53  4636.4  293.42
  4641.6  291.93  4669.1  293.21  4674.4  291.61  4734.6  294.30  4767.8  293.19
  4772.0  291.13  4795.3  292.78  4800.8  290.71  4818.6  292.69  4824.1  290.40
  4841.9  292.62  4844.3  290.35  4844.8  289.55  4850.5  290.35  4870.7  290.62
  4894.0  294.61  4944.9  297.74  5127.8  298.58  5890.5  314.27  5994.4  318.10
#Mann=5,-1,0
  3314.8    0.05       0  4510.2     0.1       0  4844.3    0.03       0
  4850.5     0.1       0  4944.9    0.05       0
Bank Sta=4844.3,4850.5
Exp/Cntr=0.3,0.1

Type RM Length L Ch R = 1,4725,129,129,129
BEGIN DESCRIPTION:
Mapping XS b25fe2ac
END DESCRIPTION:
XS GIS Cut Line= 6
      2129273.29     13410714.36      2128268.09     13411136.23
      2128012.88     13411224.77      2127809.75     13411308.10
      2127523.30     13411443.52      2126762.92     13411776.83
#Sta/Elev= 30
  3267.5  314.29  3435.4  309.34  3641.8  305.99  3954.1  304.84  4136.7  302.49
  4213.5  300.81  4274.8  297.30  4287.1  297.16  4287.6  296.36  4293.3  297.16
  4317.6  298.70  4367.7  299.98  4404.1  302.71  4429.9  301.76  4435.2  303.03
  4486.9  302.49  4604.4  303.37  4665.6  302.50  4695.0  300.77  4743.0  301.58
  4748.4  300.49  4772.3  302.18  4821.2  302.62  4831.1  301.65  4902.2  302.39
  4924.9  302.39  5105.3  299.31  5173.2  299.90  5830.9  313.30  5994.4  318.61
#Mann=9,-1,0
  3267.5    0.05       0  4274.8     0.1       0  4287.1    0.03       0
  4293.3     0.1       0  4317.6    0.05       0  4486.9     0.1       0
  4821.2    0.05       0  4902.2     0.1       0  4924.9    0.05       0
Bank Sta=4287.1,4293.3
Exp/Cntr=0.3,0.1

Type RM Length L Ch R = 1,4596,612,612,612
BEGIN DESCRIPTION:
Mapping XS 76d7168d
END DESCRIPTION:
XS GIS Cut Line= 4
      2129236.86     13410672.68      2128273.30     13411058.10
      2127820.17     13411235.19      2126748.60     13411718.95
#Sta/Elev= 30
  3386.1  313.38  3566.6  308.48  3752.4  305.62  4080.9  303.61  4242.4  301.80
  4314.3  300.14  4350.1  298.10  4379.8  295.37  4433.4  296.87  4554.1  296.21
  4675.4  296.02  4680.7  296.89  4699.8  296.21  4705.2  296.86  4729.7  295.96
  4754.1  296.57  4759.5  297.38  4808.5  295.93  4813.8  296.78  4865.0  295.19
  4865.5  294.39  4870.7  294.39  4871.2  295.19  5019.8  296.99  5066.0  296.69
  5179.4  298.86  5376.9  301.19  5550.5  305.87  5958.4  313.73  6086.1  317.87
#Mann=5,-1,0
  3386.1    0.05       0  4433.4     0.1       0  4554.1    0.05       0
  4865.0    0.03       0  4871.2    0.05       0
Bank Sta=4865,4871.2
Exp/Cntr=0.3,0.1

Type RM Length L Ch R = 1,3984,434,434,434
BEGIN DESCRIPTION:
Mapping XS fcbaeb23
END DESCRIPTION:
XS GIS Cut Line= 3
      2129436.05     13410492.12      2127696.51     13410726.49
      2126540.27     13411559.81
#Sta/Elev= 30
  3264.6  322.04  3400.2  317.26  3473.0  313.73  3558.3  310.75  3696.3  307.02
  3911.4  303.17  3961.9  301.60  4274.7  299.05  4527.0  294.70  4617.8  293.62
  4698.5  293.37  4738.8  292.68  4759.0  293.13  4823.0  292.74  4887.1  291.88
  4887.6  291.08  4892.9  291.08  4893.4  291.88  4910.4  292.27  5041.6  291.91
  5098.1  292.33  5420.8  298.91  5485.8  301.05  5764.4  305.53  5800.0  305.36
  5894.4  307.75  6072.4  310.82  6309.2  316.01  6344.8  316.58  6445.1  316.33
#Mann=3,-1,0
  3264.6    0.05       0  4887.1   0.035       0  4893.4    0.05       0
Bank Sta=4887.1,4893.4
Exp/Cntr=0.3,0.1

Type RM Length L Ch R = 1,3550,441,441,441
BEGIN DESCRIPTION:
UNT 021 in La Jarita Watershed 3.0
END DESCRIPTION:
XS GIS Cut Line= 3
      2129075.04     13410325.00      2127575.00     13410325.00
      2126874.97     13410725.02
#Sta/Elev= 30
  3492.5  308.74  3562.5  307.33  3712.5  305.05  3822.5  303.98  3852.5  303.22
  3992.5  301.41  4272.5  296.06  4312.5  295.00  4362.5  295.09  4402.5  294.25
  4442.5  294.05  4532.5  292.56  4692.5  291.00  4762.5  289.71  4792.5  290.57
  4842.5  290.08  4872.5  288.72  4892.5  288.73  4932.5  289.58  4972.5  289.18
  4995.4  288.73  4997.3  288.37  4997.8  287.57  5003.1  287.57  5003.6  288.37
  5065.2  290.31  5102.7  290.62  5279.8  293.40  5490.0  298.58  5798.8  303.45
#Mann=3,-1,0
  3492.5    0.05       0  4997.3   0.035       0  5003.6    0.05       0
Bank Sta=4997.3,5003.6
Exp/Cntr=0.3,0.1

Type RM Length L Ch R = 1,3109,525,525,525
BEGIN DESCRIPTION:
Mapping XS 7000cf4c
END DESCRIPTION:
XS GIS Cut Line= 4
      2128226.86     13409618.00      2127636.58     13409784.66
      2127261.58     13410076.33      2126851.86     13410617.99
#Sta/Elev= 30
  4062.6  300.11  4137.3  300.59  4255.4  298.96  4294.6  297.45  4323.3  296.81
  4396.5  293.10  4407.4  292.06  4440.9  290.84  4508.9  289.40  4514.1  289.61
  4646.4  288.09  4719.8  285.98  4769.5  287.09  4862.7  286.77  4898.0  287.23
  4955.9  286.89  5002.6  285.76  5003.1  284.96  5008.4  284.96  5008.9  285.76
  5012.0  286.25  5090.8  287.41  5126.1  288.34  5151.0  288.34  5254.5  290.16
  5404.4  293.78  5512.5  295.40  5554.2  296.79  5689.4  299.80  5830.2  302.21
#Mann=3,-1,0
  4062.6    0.05       0  5002.6   0.035       0  5008.9    0.05       0
Bank Sta=5002.6,5008.9
Exp/Cntr=0.3,0.1

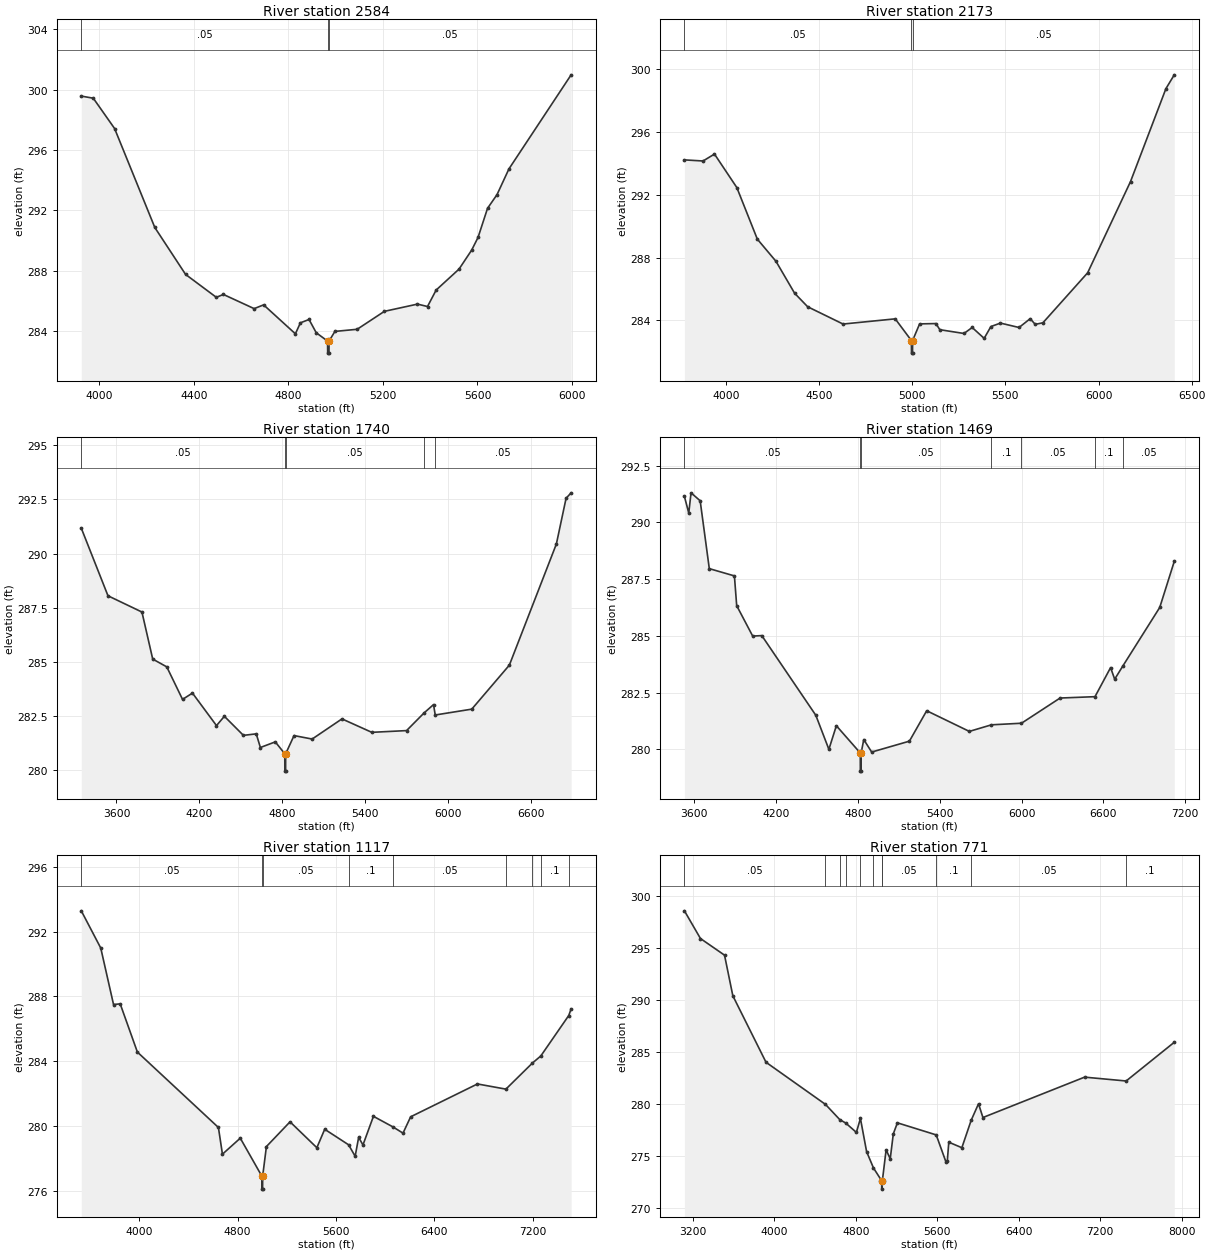
Type RM Length L Ch R = 1,2584,411,411,411
BEGIN DESCRIPTION:
Mapping XS 2cb5d0cc
END DESCRIPTION:
XS GIS Cut Line= 4
      2128115.75     13409458.28      2127226.85     13409423.55
      2126893.52     13409951.33      2126837.97     13410506.86
#Sta/Elev= 30
  3924.1  299.58  3974.9  299.44  4065.0  297.43  4235.1  290.87  4365.2  287.76
  4495.3  286.24  4525.3  286.43  4655.4  285.49  4695.4  285.74  4829.8  283.82
  4851.0  284.55  4887.5  284.77  4918.0  283.89  4965.9  283.34  4966.4  282.54
  4971.8  282.54  4972.3  283.34  4996.9  283.98  5091.0  284.12  5206.3  285.31
  5346.3  285.79  5388.7  285.63  5425.1  286.72  5522.0  288.11  5575.5  289.37
  5602.4  290.21  5642.6  292.14  5682.8  293.05  5733.0  294.75  5996.2  300.99
#Mann=3,-1,0
  3924.1    0.05       0  4965.9   0.035       0  4972.3    0.05       0
Bank Sta=4965.9,4972.3
Exp/Cntr=0.3,0.1

Type RM Length L Ch R = 1,2173,433,433,433
BEGIN DESCRIPTION:
Mapping XS 86e5e896
END DESCRIPTION:
XS GIS Cut Line= 4
      2128296.29     13409208.28      2127046.30     13409229.11
      2126685.19     13409777.72      2126692.13     13410499.93
#Sta/Elev= 30
  3777.5  294.21  3877.4  294.14  3938.8  294.58  4058.8  292.45  4168.8  289.17
  4268.9  287.76  4368.9  285.73  4438.9  284.87  4628.9  283.77  4909.0  284.10
  4995.8  282.72  4996.3  281.92  5001.7  281.92  5002.2  282.72  5039.9  283.78
  5127.3  283.80  5148.4  283.41  5277.9  283.17  5322.0  283.55  5386.3  282.86
  5422.4  283.61  5473.7  283.83  5573.5  283.55  5633.3  284.11  5660.4  283.75
  5701.7  283.85  5941.8  287.03  6171.8  292.83  6361.8  298.74  6406.7  299.62
#Mann=3,-1,0
  3777.5    0.05       0  4995.8   0.035       0  5002.2    0.05       0
Bank Sta=4995.8,5002.2
Exp/Cntr=0.3,0.1

Type RM Length L Ch R = 1,1740,271,271,271
BEGIN DESCRIPTION:
Mapping XS f3c30868
END DESCRIPTION:
XS GIS Cut Line= 3
      2128622.67     13407923.56      2126622.69     13409270.78
      2126518.64     13410401.39
#Sta/Elev= 30
  3345.5  291.17  3538.8  288.05  3784.7  287.30  3862.7  285.13  3964.6  284.77
  4078.6  283.27  4150.6  283.56  4324.5  282.06  4381.5  282.49  4519.4  281.61
  4612.3  281.68  4642.3  281.05  4750.3  281.31  4819.0  280.76  4819.5  279.96
  4824.9  279.96  4825.4  280.76  4886.0  281.60  5017.1  281.44  5233.0  282.37
  5449.0  281.75  5700.8  281.83  5828.3  282.65  5896.0  283.03  5908.3  282.55
  6172.9  282.82  6445.0  284.85  6785.5  290.44  6855.8  292.55  6892.3  292.80
#Mann=5,-1,0
  3345.5    0.05       0  4819.0   0.035       0  4825.4    0.05       0
  5828.3     0.1       0  5908.3    0.05       0
Bank Sta=4819,4825.4
Exp/Cntr=0.3,0.1

Type RM Length L Ch R = 1,1469,352,352,352
BEGIN DESCRIPTION:
Mapping XS 9accd7f1
END DESCRIPTION:
XS GIS Cut Line= 4
      2128560.20     13407916.60      2126962.97     13408722.16
      2126372.69     13409201.33      2126400.43     13410241.50
#Sta/Elev= 30
  3529.2  291.14  3561.0  290.41  3577.7  291.30  3644.6  290.95  3711.5  287.96
  3895.5  287.64  3912.2  286.33  4029.4  284.99  4096.3  285.01  4492.1  281.50
  4587.8  280.00  4642.6  281.04  4817.9  279.84  4818.4  279.04  4823.8  279.04
  4824.3  279.84  4843.4  280.43  4901.4  279.88  5177.9  280.36  5304.6  281.70
  5617.1  280.79  5779.2  281.08  5999.3  281.15  6282.1  282.26  6537.9  282.32
  6652.2  283.60  6682.2  283.09  6742.9  283.68  7012.4  286.25  7118.9  288.28
#Mann=7,-1,0
  3529.2    0.05       0  4817.9   0.035       0  4824.3    0.05       0
  5779.2     0.1       0  5999.3    0.05       0  6537.9     0.1       0
  6742.9    0.05       0
Bank Sta=4817.9,4824.3
Exp/Cntr=0.3,0.1

Type RM Length L Ch R = 1,1117,346,346,346
BEGIN DESCRIPTION:
Mapping XS 0e81c3df
END DESCRIPTION:
XS GIS Cut Line= 4
      2128567.18     13407833.26      2126733.80     13408361.05
      2126212.97     13408937.44      2126289.35     13410236.02
#Sta/Elev= 30
  3528.5  293.29  3686.9  290.99  3790.9  287.50  3845.1  287.54  3985.0  284.56
  4644.2  279.90  4677.0  278.25  4822.2  279.24  4997.8  276.89  4998.3  276.09
  5003.7  276.09  5004.2  276.89  5034.7  278.72  5227.0  280.25  5445.2  278.65
  5509.0  279.79  5703.4  278.83  5756.8  278.12  5785.2  279.29  5820.3  278.82
  5905.5  280.59  6065.6  279.93  6146.1  279.55  6208.2  280.56  6751.7  282.59
  6983.3  282.27  7198.8  283.88  7267.3  284.32  7494.6  286.82  7514.0  287.23
#Mann=9,-1,0
  3528.5    0.05       0  4997.8   0.035       0  5004.2    0.05       0
  5703.4     0.1       0  6065.6    0.05       0  6983.3     0.1       0
  7198.8    0.05       0  7267.3     0.1       0  7494.6    0.05       0
Bank Sta=4997.8,5004.2
Exp/Cntr=0.3,0.1

Type RM Length L Ch R = 1,771,0,0,0
BEGIN DESCRIPTION:
UNT 021 in La Jarita Watershed 2.0
END DESCRIPTION:
XS GIS Cut Line= 4
      2128921.28     13407682.24      2126607.06     13407965.22
      2126117.48     13408350.64      2126207.76     13410204.79
#Sta/Elev= 30
  3116.3  298.57  3273.7  295.91  3510.2  294.31  3591.7  290.41  3917.6  284.02
  4501.8  279.97  4642.0  278.51  4700.5  278.18  4805.1  277.28  4844.9  278.62
  4905.6  275.43  4973.2  273.86  5053.7  272.63  5054.2  271.83  5060.2  272.63
  5097.2  275.61  5137.5  274.74  5167.8  277.14  5208.0  278.20  5589.2  277.04
  5683.8  274.47  5698.3  274.55  5712.7  276.34  5841.0  275.81  5932.8  278.45
  6004.6  280.03  6047.9  278.71  7046.4  282.59  7454.5  282.22  7927.2  285.94
#Mann=11,-1,0
  3116.3    0.05       0  4501.8    0.08       0  4642.0    0.05       0
  4700.5    0.08       0  4844.9     0.1       0  4973.2    0.05       0
  5053.7   0.035       0  5060.2    0.05       0  5589.2     0.1       0
  5932.8    0.05       0  7454.5     0.1       0
Bank Sta=5053.7,5060.2
Exp/Cntr=0.3,0.1

Chan Stop Cuts=-1