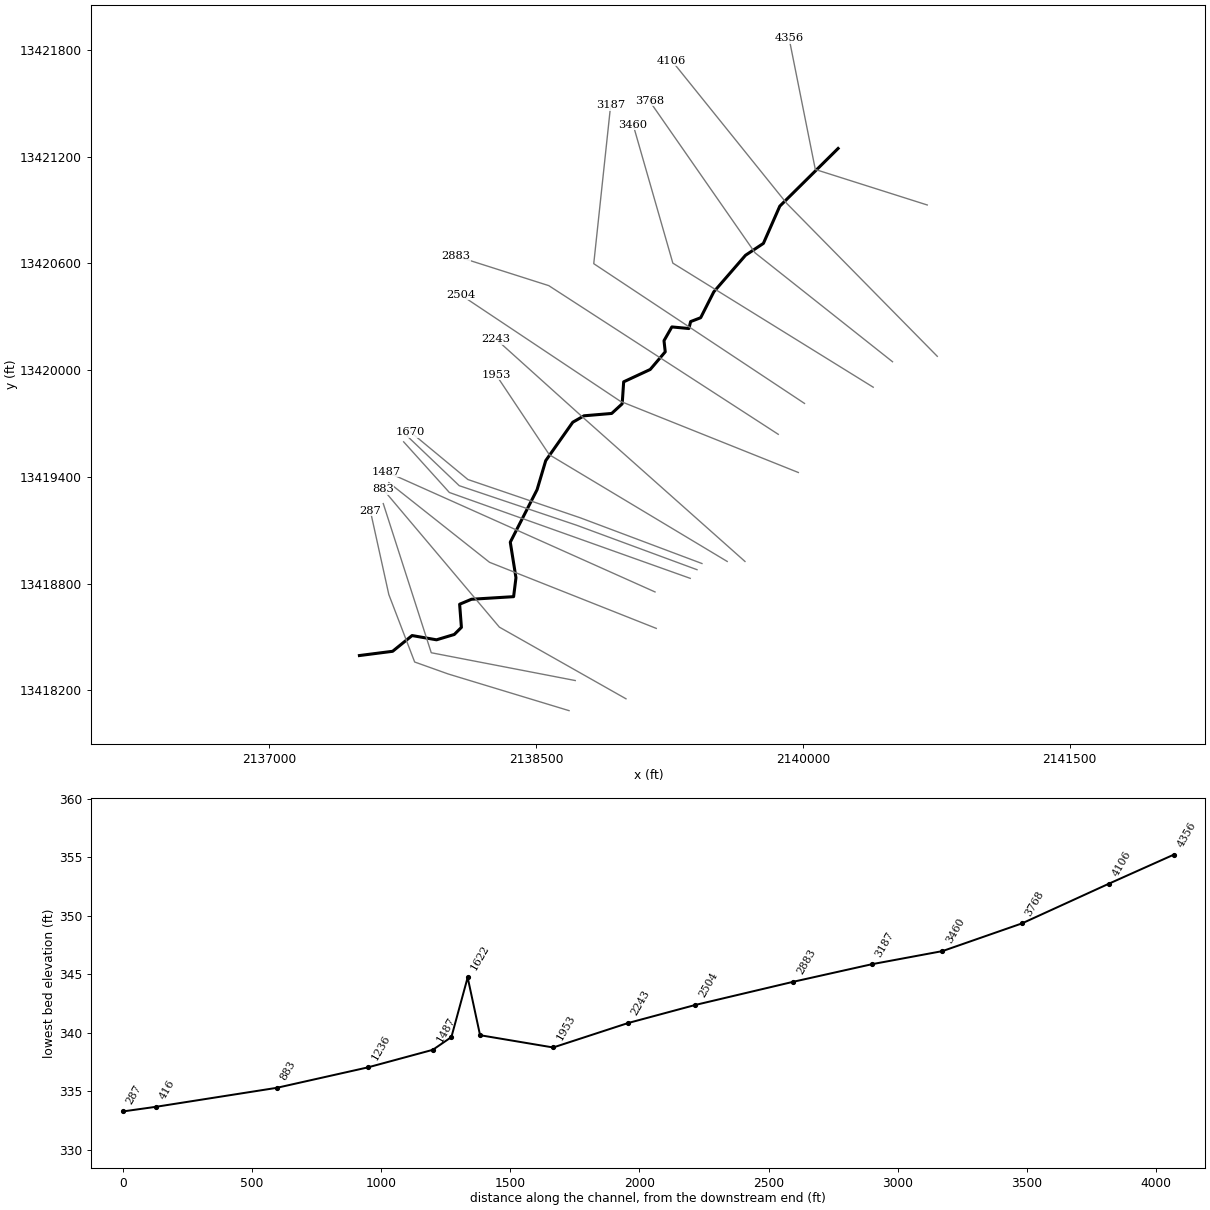
--- UNT 022 in La Jarita Watershed.prj (project) ---

Proj Title=UNT 022 in La Jarita Watershed Base Level Engineering
Current Plan=p01
Default Exp/Contr=0.3,0.1
English Units
Geom File=g01
Flow File=f01
Plan File=p01
Y Axis Title=Elevation
X Axis Title(PF)=Main Channel Distance
X Axis Title(XS)=Station
BEGIN DESCRIPTION:
UNT 022 in La Jarita Watershed
END DESCRIPTION:
DSS Export Rating Curves= 0
DSS Export Rating Curve Sorted= 0
DSS Export Volume Flow Curves= 0
DXF OffsetX= 0
DXF OffsetY= 0
DXF ScaleX= 1
DXF ScaleY= 10

--- UNT 022 in La Jarita Watershed.p01 (plan) ---

Plan Title=Multiple Run
Short Identifier=Multiple
Geom File=g01
Flow File=f01
Subcritical Flow
K Sum by GR= 0
Std Step Tol= 0.01
Critical Tol= 0.01
Num of Std Step Trials= 20
Max Error Tol= 0.3
Flow Tol Ratio= 0.001
Split Flow NTrial= 30
Split Flow Tol= 0.02
Split Flow Ratio= 0.02
Log Output Level= 0
Friction Slope Method= 1
Unsteady Friction Slope Method= 2
Unsteady Bridges Friction Slope Method= 1
Parabolic Critical Depth
Global Vel Dist=  1 , 1 , 1
Global Log Level= 0
CheckData=True
Encroach Param= -1, 0, 0, 0
BEGIN DESCRIPTION:
Multiple Run
END DESCRIPTION:

--- UNT 022 in La Jarita Watershed.f01 (steady flow) ---

Flow Title=Multiple
Program Version=5.05
Number of Profiles= 7
Profile Names=10-year,25-year,50-year,1pct_min,100-year,1pct_plu,500-year
River Rch & RM=UNT 022 in La Ja,Reach-1         ,4356
     135     181     218     131     262     522     382
Boundary for River Rch & Prof#=UNT 022 in La Ja,Reach-1         , 1
Up Type= 0
Dn Type= 3
Dn Slope=0.005
Boundary for River Rch & Prof#=UNT 022 in La Ja,Reach-1         , 2
Up Type= 0
Dn Type= 3
Dn Slope=0.005
Boundary for River Rch & Prof#=UNT 022 in La Ja,Reach-1         , 3
Up Type= 0
Dn Type= 3
Dn Slope=0.005
Boundary for River Rch & Prof#=UNT 022 in La Ja,Reach-1         , 4
Up Type= 0
Dn Type= 3
Dn Slope=0.005
Boundary for River Rch & Prof#=UNT 022 in La Ja,Reach-1         , 5
Up Type= 0
Dn Type= 3
Dn Slope=0.005
Boundary for River Rch & Prof#=UNT 022 in La Ja,Reach-1         , 6
Up Type= 0
Dn Type= 3
Dn Slope=0.005
Boundary for River Rch & Prof#=UNT 022 in La Ja,Reach-1         , 7
Up Type= 0
Dn Type= 3
Dn Slope=0.005
DSS Import GetInterval= 0
DSS Import GetPeak= 0
DSS Import FillOption= 0

--- UNT 022 in La Jarita Watershed.g01 (geometry) ---

Geom Title=Existing Conditions
Program Version=5.05

River Reach=UNT 022 in La Ja,Reach-1
Reach XY= 30
       2140198.5     13421246.39      2139870.81     13420922.18
      2139778.57     13420712.76      2139677.97     13420646.01
      2139499.71      13420440.4      2139425.93     13420295.01
       2139369.5      13420273.3      2139359.74     13420234.24
      2139263.96     13420243.27      2139219.76     13420165.88
      2139226.69     13420103.35      2139142.34     13420004.13
      2138993.03     13419934.69       2138984.7     13419811.08
      2138925.67     13419756.91      2138770.12     13419743.72
      2138706.92     13419707.61      2138554.84     13419491.63
      2138506.23     13419328.44      2138355.53      13419033.3
      2138387.48      13418833.3      2138374.28     13418727.05
      2138137.48     13418712.47       2138070.8     13418684.54
       2138080.8     13418554.54       2138040.8     13418514.54
       2137940.8     13418484.54      2137803.48     13418508.47
      2137694.11     13418419.93      2137507.38     13418396.05

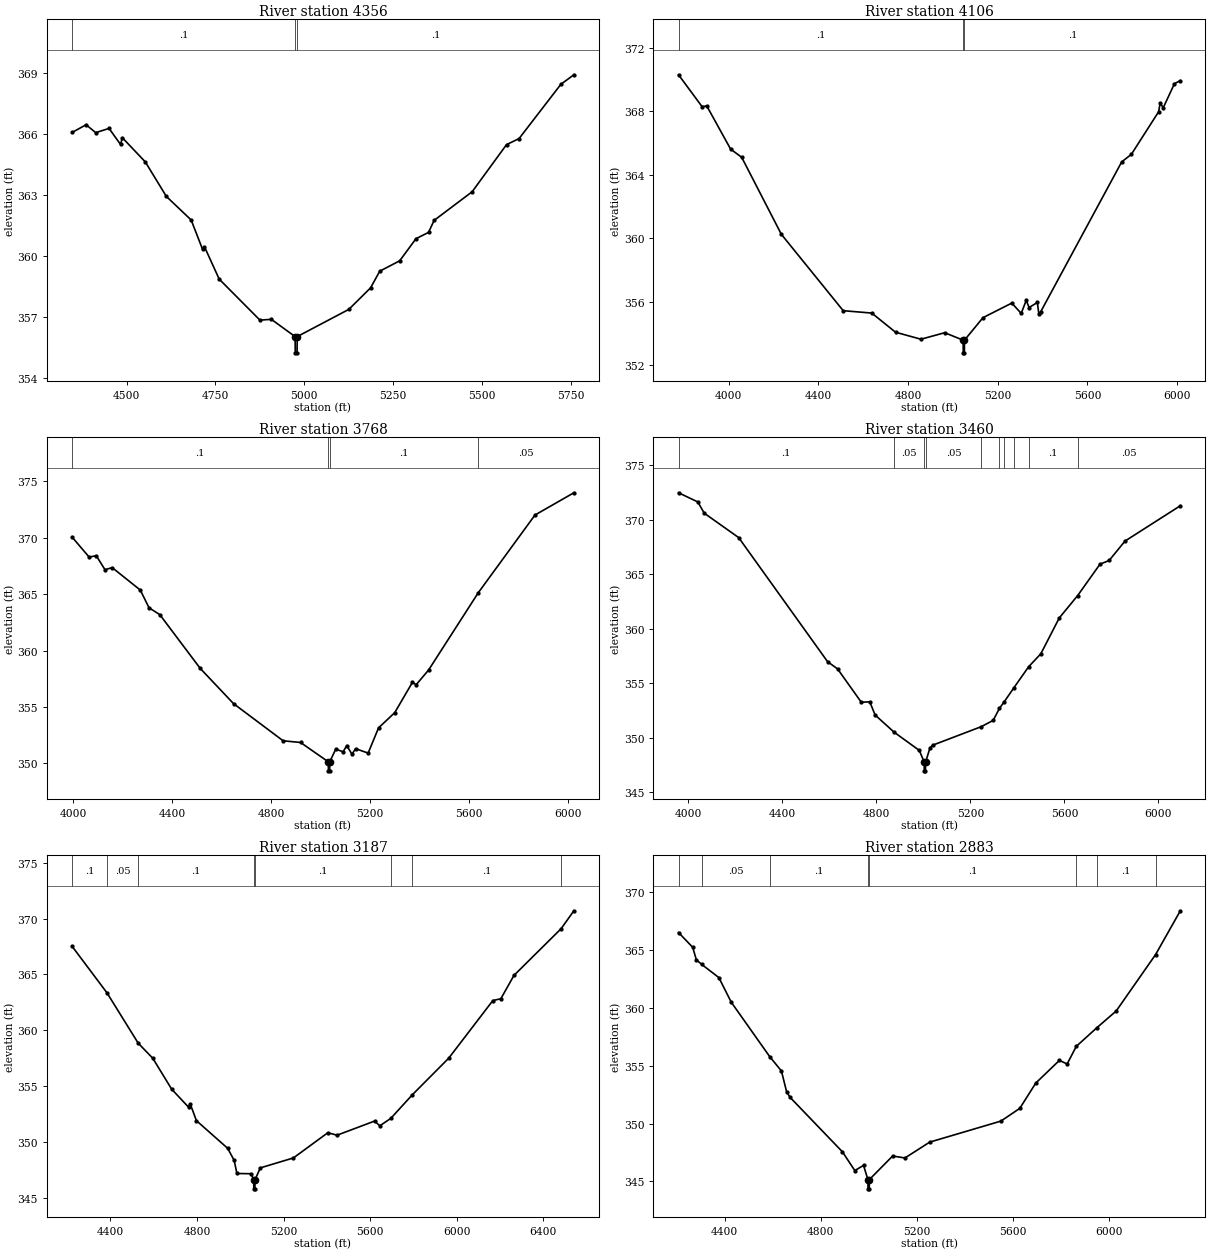
Type RM Length L Ch R = 1 ,4356    ,250,250,250
BEGIN DESCRIPTION:
UNT 022 in La Jarita Watershed 10.0
END DESCRIPTION:
XS GIS Cut Line= 3
      2140699.78     13420928.69      2140070.46     13421128.34
      2139922.89      13421866.2
#Sta/Elev= 30
  4346.7  366.08  4386.3  366.46  4413.3  366.07  4450.8  366.28  4483.1  365.49
  4488.3  365.82  4552.9  364.63  4612.2  362.93    4682  361.77  4714.2  360.32
  4719.5  360.45  4760.9  358.86  4875.6  356.84  4907.7  356.88  4974.6  356.03
  4975.1  355.23  4980.1  355.23  4980.6  356.03  5125.9  357.37  5187.1  358.43
  5212.9  359.25    5269  359.76  5314.9  360.85  5350.3  361.16  5365.9  361.75
    5473  363.16  5569.8  365.48  5605.2  365.78  5722.8  368.45  5759.4  368.92
#Mann= 3 ,-1 , 0
  4346.7      .1       0  4974.6     .07       0  4980.6      .1       0
Bank Sta=4974.6,4980.6
XS Rating Curve= 0 ,0
Exp/Cntr=0.3,0.1

Type RM Length L Ch R = 1 ,4106    ,338,338,338
BEGIN DESCRIPTION:
Mapping XS 47315c76
END DESCRIPTION:
XS GIS Cut Line= 3
       2140756.2     13420078.01      2139909.87     13420937.37
      2139263.31     13421740.14
#Sta/Elev= 30
  3777.1  370.31  3881.9   368.3  3903.1  368.34  4009.2  365.62  4058.7   365.1
  4235.5  360.24  4511.2  355.42  4638.5  355.27  4744.6  354.06  4857.7  353.62
  4963.8  354.03  5045.8  353.56  5046.3  352.76  5051.3  352.76  5051.8  353.56
  5134.3  354.98  5262.7   355.9  5304.7  355.25  5326.9  356.07    5340  355.62
  5376.7  355.94  5383.1  355.23  5391.1  355.34  5752.6  364.81  5795.8  365.29
  5917.4  367.98  5923.8   368.5  5938.2  368.24  5987.8  369.75    6014  369.94
#Mann= 3 ,-1 , 0
  3777.1      .1       0  5045.8     .07       0  5051.8      .1       0
Bank Sta=5045.8,5051.8
XS Rating Curve= 0 ,0
Exp/Cntr=0.3,0.1

Type RM Length L Ch R = 1 ,3768    ,308,308,308
BEGIN DESCRIPTION:
Mapping XS 67bd3cab
END DESCRIPTION:
XS GIS Cut Line= 3
      2140504.48     13420047.61      2139731.92     13420659.59
      2139137.27     13421514.66
#Sta/Elev= 30
  3995.9  370.04  4064.8  368.27  4093.6  368.39  4128.9  367.15  4157.8  367.34
  4271.5  365.35  4306.8  363.78  4350.1  363.18  4513.5  358.42  4648.1   355.3
  4848.5  352.01  4918.9  351.86    5031  350.15  5031.5  349.35  5036.5  349.35
    5037  350.15  5061.2  351.28  5090.8  351.03  5105.6  351.59  5126.6  350.82
  5141.4  351.31    5192  350.92  5233.9  353.15  5299.4   354.5    5371  357.19
  5385.8  356.97  5436.4  358.28  5636.4   365.1  5865.9  371.99    6023  373.96
#Mann= 4 ,-1 , 0
  3995.9      .1       0    5031     .07       0    5037      .1       0
  5636.4     .05       0
Bank Sta=5031,5037
XS Rating Curve= 0 ,0
Exp/Cntr=0.3,0.1

Type RM Length L Ch R = 1 ,3460    ,273,273,273
BEGIN DESCRIPTION:
Mapping XS 82be4f36
END DESCRIPTION:
XS GIS Cut Line= 3
      2140395.97     13419904.39      2139269.42     13420601.91
      2139046.17       13421380.
#Sta/Elev= 30
  3958.4  372.48  4040.5  371.64  4067.7  370.61  4214.2  368.37  4592.4  356.99
  4634.9  356.33  4735.8  353.27  4771.9  353.31  4794.6   352.1  4875.1  350.53
  4982.8  348.85  5003.3  347.78  5003.8  346.98  5008.8  346.98  5009.3  347.78
  5028.4  349.11  5041.6  349.35  5246.1  351.03    5297  351.61  5323.7  352.72
  5343.4   353.3    5384  354.57  5447.8  356.53  5499.4  357.71  5577.9     361
  5656.1  363.05  5751.1  365.93  5790.1  366.27  5857.5  368.05  6092.9  371.29
#Mann= 10 ,-1 , 0
  3958.4      .1       0  4875.1     .05       0  5003.3     .04       0
  5009.3     .05       0  5246.1      .1       0  5323.7     .05       0
  5343.4      .1       0    5384     .05       0  5447.8      .1       0
  5656.1     .05       0
Bank Sta=5003.3,5009.3
XS Rating Curve= 0 ,0
Exp/Cntr=0.3,0.1

Type RM Length L Ch R = 1 ,3187    ,304,304,304
BEGIN DESCRIPTION:
Mapping XS 5b7890c1
END DESCRIPTION:
XS GIS Cut Line= 3
      2140009.71     13419813.22       2138824.8     13420598.82
      2138919.99     13421490.17
#Sta/Elev= 30
  4222.7  367.52  4383.7  363.37  4528.5  358.86  4595.6  357.52  4682.8  354.76
    4761  353.15  4768.3  353.46  4797.1  351.95  4941.5  349.48  4971.6   348.4
  4984.2  347.23  5049.8  347.21  5061.8  346.66  5062.3  345.86  5067.3  345.86
  5067.8  346.66  5092.2  347.73  5245.3  348.62  5404.2  350.87  5446.8  350.65
  5620.1  351.91  5644.4  351.49    5695  352.15  5794.6  354.26  5962.4  357.52
  6166.4  362.67  6203.7  362.84  6264.1  364.92  6481.9  369.09  6540.8  370.69
#Mann= 8 ,-1 , 0
  4222.7      .1       0  4383.7     .05       0  4528.5      .1       0
  5061.8     .07       0  5067.8      .1       0    5695     .05       0
  5794.6      .1       0  6481.9     .05       0
Bank Sta=5061.8,5067.8
XS Rating Curve= 0 ,0
Exp/Cntr=0.3,0.1

Type RM Length L Ch R = 1 ,2883    ,379,379,379
BEGIN DESCRIPTION:
Mapping XS df26c524
END DESCRIPTION:
XS GIS Cut Line= 3
      2139862.09     13419639.65      2138571.84     13420475.42
      2138048.99     13420641.88
#Sta/Elev= 30
  4208.9  366.53  4267.8  365.25    4283  364.17  4304.7  363.78  4376.6  362.63
  4428.1   360.5  4588.1  355.79  4636.5  354.56  4658.2  352.76  4672.7  352.27
  4890.3  347.56  4941.7  345.94    4978  346.39  4996.1  345.16  4996.6  344.36
  5001.6  344.36  5002.1  345.16    5099   347.2  5150.1  347.03    5253   348.4
  5549.1  350.22  5627.5  351.32  5694.1  353.51  5792.2  355.47  5824.4  355.16
  5862.3  356.68  5948.2   358.3  6028.2  359.74    6192  364.62  6294.9  368.41
#Mann= 8 ,-1 , 0
  4208.9      .1       0  4304.7     .05       0  4588.1      .1       0
  4996.1     .07       0  5002.1      .1       0  5862.3     .05       0
  5948.2      .1       0    6192     .05       0
Bank Sta=4996.1,5002.1
XS Rating Curve= 0 ,0
Exp/Cntr=0.3,0.1

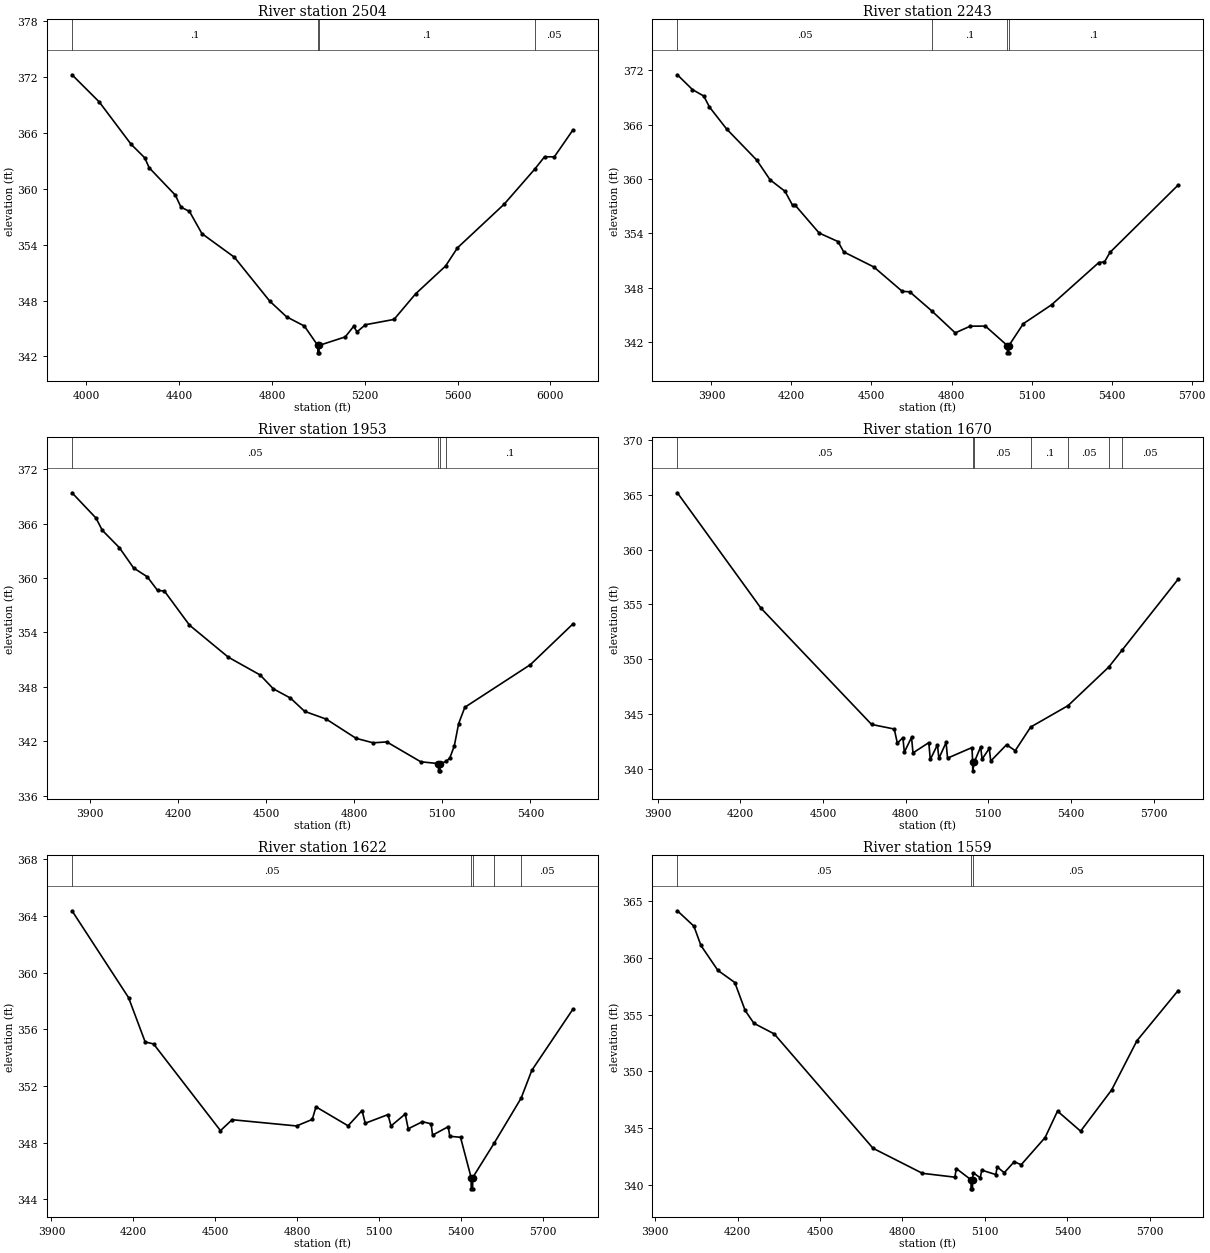
Type RM Length L Ch R = 1 ,2504    ,261,261,261
BEGIN DESCRIPTION:
UNT 022 in La Jarita Watershed 9.0
END DESCRIPTION:
XS GIS Cut Line= 3
      2139974.98     13419425.01        2138975.       13419825.
      2138074.98     13420425.01
#Sta/Elev= 30
  3938.1  372.26  4055.2  369.35  4192.5   364.8  4251.8  363.33  4270.6  362.27
  4383.7  359.32  4407.9  358.03  4444.3  357.58  4498.1  355.19  4638.2  352.65
  4790.3  347.94    4863  346.25  4939.7  345.26  4997.3  343.18  4997.8  342.38
  5002.8  342.38  5003.3  343.18  5115.8  344.09  5151.8  345.22  5166.8  344.64
  5202.9   345.4  5326.1  345.97  5419.2  348.72  5548.4  351.71  5599.5  353.66
  5800.8  358.35  5933.1  362.13  5975.1  363.45  6017.2  363.44  6096.8  366.31
#Mann= 4 ,-1 , 0
  3938.1      .1       0  4997.3     .07       0  5003.3      .1       0
  5933.1     .05       0
Bank Sta=4997.3,5003.3
XS Rating Curve= 0 ,0
Exp/Cntr=0.3,0.1

Type RM Length L Ch R = 1 ,2243    ,290,290,290
BEGIN DESCRIPTION:
UNT 022 in La Jarita Watershed 8.0
END DESCRIPTION:
XS GIS Cut Line= 3
      2139675.01     13418924.99        2138775.       13419725.
      2138274.97     13420175.03
#Sta/Elev= 30
  3772.5  371.49    3829  369.86  3871.6  369.14  3892.9  367.93  3956.9  365.52
  4069.8  362.09    4120  359.91    4176  358.64  4204.4  357.09    4212  357.18
  4303.9  354.04  4374.6   353.1  4395.9  351.96  4508.8   350.3  4615.4  347.61
  4643.4  347.56  4725.4  345.47    4814  343.03  4870.1  343.77  4926.9  343.78
  5009.2  341.63  5009.7  340.83  5014.7  340.83  5015.2  341.63    5069  344.04
  5175.1  346.13  5352.3  350.79  5373.2  350.85  5394.1  351.91  5649.4  359.33
#Mann= 4 ,-1 , 0
  3772.5     .05       0  4725.4      .1       0  5009.2     .07       0
  5015.2      .1       0
Bank Sta=5009.2,5015.2
XS Rating Curve= 0 ,0
Exp/Cntr=0.3,0.1

Type RM Length L Ch R = 1 ,1953    ,283,283,283
BEGIN DESCRIPTION:
UNT 022 in La Jarita Watershed 7.0
END DESCRIPTION:
XS GIS Cut Line= 3
      2139575.02     13418924.99        2138575.       13419525.
      2138275.02     13419974.96
#Sta/Elev= 30
  3837.7  369.41  3919.4  366.62  3940.7  365.28    3999  363.36  4047.6  361.12
  4094.3  360.14  4129.3  358.64  4152.6  358.57  4238.1  354.81  4370.3  351.28
  4479.1  349.31  4523.8  347.79  4582.1  346.77  4630.7   345.3  4704.6  344.44
  4805.7  342.33    4864  341.83  4910.6  341.93  5026.4  339.74  5086.5  339.54
    5087  338.74    5092  338.74  5092.5  339.54  5113.4  339.78  5125.6  340.17
  5140.6  341.46  5155.6  343.95  5176.7  345.75  5400.5  350.46  5544.7  354.93
#Mann= 4 ,-1 , 0
  3837.7     .05       0  5086.5    .033       0  5092.5     .05       0
  5113.4      .1       0
Bank Sta=5086.5,5092.5
XS Rating Curve= 0 ,0
Exp/Cntr=0.3,0.1

Type RM Length L Ch R = 1 ,1670    ,48,48,48
BEGIN DESCRIPTION:
Mapping XS b73a3e6f
END DESCRIPTION:
XS GIS Cut Line= 4
      2139433.14     13418913.36      2138749.15     13419170.28
      2138117.21     13419385.56      2137794.28     13419652.93
#Sta/Elev= 30
  3971.4   365.2  4274.3  354.67  4676.3  344.03  4758.6  343.61  4769.8  342.32
  4789.9  342.82  4795.2   341.5  4821.3  342.85  4826.6  341.43    4884  342.37
  4889.3  340.83  4915.3  342.16  4920.6  340.93  4946.7  342.38    4952  340.95
  5040.8  341.92    5043  340.59  5043.5  339.79    5049  340.59  5072.1  341.98
  5077.4  340.86  5103.5  341.84  5108.7  340.68  5166.2  342.18  5197.5  341.63
  5253.6  343.79  5389.4  345.75  5537.3  349.28  5585.5  350.82  5788.9   357.3
#Mann= 7 ,-1 , 0
  3971.4     .05       0    5043    .033       0    5049     .05       0
  5253.6      .1       0  5389.4     .05       0  5537.3      .1       0
  5585.5     .05       0
Bank Sta=5043,5049
XS Rating Curve= 0 ,0
Exp/Cntr=0.3,0.1

Type RM Length L Ch R = 1 ,1622    ,63,63,63
BEGIN DESCRIPTION:
Mapping XS 744d5860
END DESCRIPTION:
XS GIS Cut Line= 4
      2139405.42     13418878.61      2138728.32     13419128.62
       2138068.6     13419350.84      2137766.54     13419639.01
#Sta/Elev= 30
  3975.3  364.36  4182.5  358.23  4243.4   355.1  4274.2  354.96  4519.4  348.84
    4562  349.61  4798.1  349.17  4855.8  349.63  4869.4  350.52  4987.1  349.18
  5038.3  350.26    5050  349.36  5133.2  349.97  5144.5  349.17  5196.5  350.01
  5207.5  348.97  5259.8  349.47  5291.4  349.32  5296.7  348.52  5354.4  349.12
  5359.7  348.44  5399.2  348.37    5438  345.53  5438.5  344.73  5443.5  344.73
    5444  345.53  5522.4  347.95  5621.3  351.13  5660.6   353.1  5810.7   357.4
#Mann= 5 ,-1 , 0
  3975.3     .05       0    5438     .03       0    5444     .05       0
  5522.4      .1       0  5621.3     .05       0
Bank Sta=5438,5444
XS Rating Curve= 0 ,0
Exp/Cntr=0.3,0.1

Type RM Length L Ch R = 1 ,1559    ,72,72,72
BEGIN DESCRIPTION:
Mapping XS 84d73373
END DESCRIPTION:
XS GIS Cut Line= 3
      2139367.23       13418830.      2138013.04     13419312.65
      2137756.06      13419597.4
#Sta/Elev= 30
  3981.3  364.17  4041.5  362.81    4067  361.11  4128.6  358.91  4190.2  357.84
  4227.8  355.37  4259.7  354.24  4333.7   353.3  4692.9  343.21  4872.5     341
  4990.5  340.66  4995.8  341.42  5049.1  340.43  5049.6  339.63  5054.6  339.63
  5055.1  340.43  5057.4  341.05  5082.9   340.6  5088.2  341.28  5139.3  340.89
  5144.6  341.56  5170.1  341.05  5206.2  342.02  5231.7  341.76  5318.8  344.16
  5363.8  346.49  5447.8  344.72  5560.7  348.36  5652.6   352.7  5802.5  357.13
#Mann= 3 ,-1 , 0
  3981.3     .05       0  5049.1     .03       0  5055.1     .05       0
Bank Sta=5049.1,5055.1
XS Rating Curve= 0 ,0
Exp/Cntr=0.3,0.1

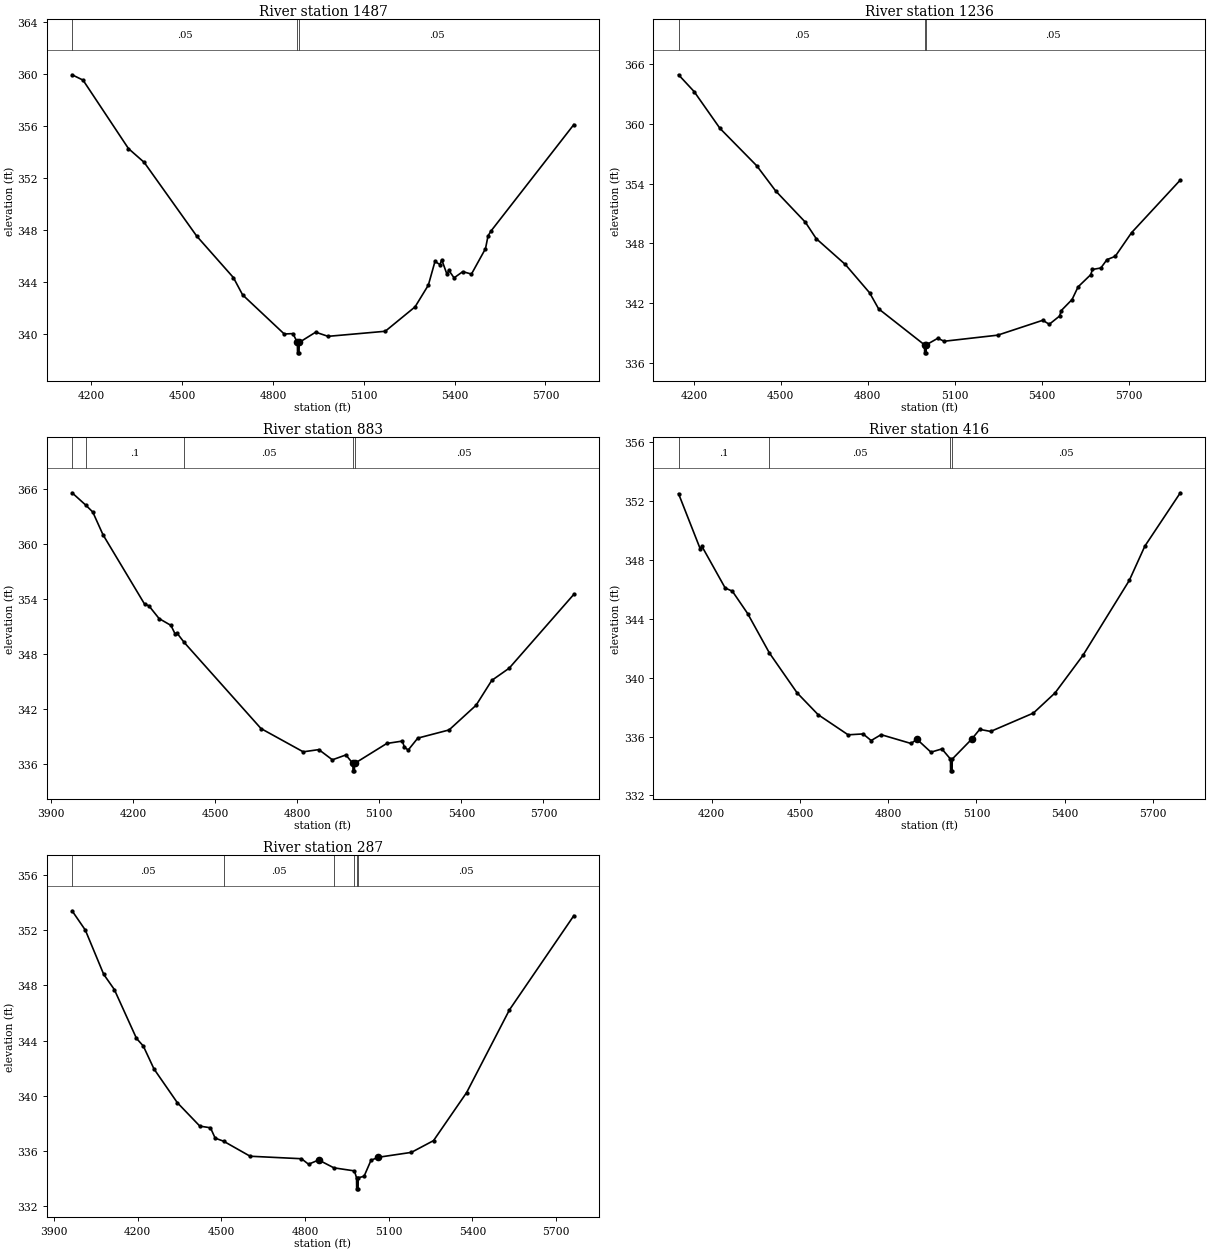
Type RM Length L Ch R = 1 ,1487    ,251,251,251
BEGIN DESCRIPTION:
Mapping XS cbd4ea42
END DESCRIPTION:
XS GIS Cut Line= 2
      2139169.33      13418753.6      2137656.18     13419430.35
#Sta/Elev= 30
  4136.2  359.94  4172.4  359.53  4322.5  354.26  4374.4   353.2  4547.8  347.53
  4669.2  344.33  4699.6     343  4837.1  339.99  4865.8  340.02  4880.5  339.34
    4881  338.54    4886  338.54  4886.5  339.34  4940.9  340.13  4981.8  339.81
  5170.7   340.2  5269.3  342.08  5313.1  343.75    5335  345.57  5351.7  345.33
  5357.2  345.71  5374.9  344.57  5380.4   344.9  5398.1  344.31  5426.8  344.79
  5455.5   344.6  5501.9  346.56  5510.3  347.54  5519.6   347.9  5793.8  356.11
#Mann= 3 ,-1 , 0
  4136.2     .05       0  4880.5     .03       0  4886.5     .05       0
Bank Sta=4880.5,4886.5
XS Rating Curve= 0 ,0
Exp/Cntr=0.3,0.1

Type RM Length L Ch R = 1 ,1236    ,353,353,353
BEGIN DESCRIPTION:
Mapping XS eb8b5ee7
END DESCRIPTION:
XS GIS Cut Line= 3
      2139176.27     13418548.74      2138238.74     13418920.28
       2137672.8     13419368.17
#Sta/Elev= 30
  4147.2  364.89  4200.9  363.21  4290.1  359.52  4417.1  355.77    4482  353.26
  4584.6  350.12  4621.9  348.48  4722.3  345.89  4806.1  343.05    4837  341.45
  4995.3  337.84  4995.8  337.04  5000.8  337.04  5001.3  337.84  5041.2   338.5
  5062.9   338.2  5247.6  338.81    5403   340.3  5425.5   339.9  5460.8  340.72
  5467.1  341.28  5504.1  342.38  5524.9  343.65  5568.2  344.86  5574.5  345.39
  5603.4  345.54  5624.2  346.37  5653.1  346.71  5709.1  349.07  5877.4  354.35
#Mann= 3 ,-1 , 0
  4147.2     .05       0  4995.3    .035       0  5001.3     .05       0
Bank Sta=4995.3,5001.3
XS Rating Curve= 0 ,0
Exp/Cntr=0.3,0.1

Type RM Length L Ch R = 1 ,883     ,467,467,467
BEGIN DESCRIPTION:
Mapping XS 2b754050
END DESCRIPTION:
XS GIS Cut Line= 3
      2139006.07     13418152.94      2138294.29      13418555.7
      2137638.99     13419332.35
#Sta/Elev= 30
  3977.3  365.55  4026.5  364.23  4052.9  363.46  4090.4  360.98  4242.8  353.41
  4257.8  353.26  4295.4  351.86  4338.6  351.12  4354.5  350.15  4360.3   350.3
  4387.2  349.26  4667.9  339.89  4822.1  337.36  4879.3   337.6  4928.7  336.49
  4978.1  337.02  5003.7  336.09  5004.2  335.29  5009.2  335.29  5009.7  336.09
  5127.6  338.27  5184.8  338.53  5191.4  337.89  5205.7  337.55  5240.8  338.85
  5355.2  339.74    5454  342.43  5511.2  345.13  5574.9  346.46  5811.3   354.5
#Mann= 5 ,-1 , 0
  3977.3     .05       0  4026.5      .1       0  4387.2     .05       0
  5003.7    .035       0  5009.7     .05       0
Bank Sta=5003.7,5009.7
XS Rating Curve= 0 ,0
Exp/Cntr=0.3,0.1

Type RM Length L Ch R = 1 ,416     ,129,129,129
BEGIN DESCRIPTION:
Mapping XS 9b80096b
END DESCRIPTION:
XS GIS Cut Line= 3
      2138720.74     13418255.59      2137911.27     13418411.84
      2137641.53     13419250.09
#Sta/Elev= 30
  4087.7  352.52  4161.7  348.75  4166.8  348.95  4246.3   346.1  4270.5  345.89
  4322.4  344.37  4396.6  341.68  4490.7  338.97    4562  337.49  4663.9  336.12
  4714.8  336.18  4742.2  335.73  4775.9  336.13  4877.8  335.53  4897.7  335.82
  4945.3  334.94  4982.6  335.16  5011.7  334.47  5012.2  333.67  5017.2  333.67
  5017.7  334.47  5084.1  335.83    5111  336.49  5148.3  336.35  5293.6   337.6
  5367.1  338.97  5461.7  341.52  5619.3  346.62  5672.1  348.95  5792.7  352.58
#Mann= 4 ,-1 , 0
  4087.7      .1       0  4396.6     .05       0  5011.7     .03       0
  5017.7     .05       0
Bank Sta=4897.7,5084.1
XS Rating Curve= 0 ,0
Exp/Cntr=0.3,0.1

Type RM Length L Ch R = 1 ,287     ,0,0,0
BEGIN DESCRIPTION:
Mapping XS ba2d2a87
END DESCRIPTION:
XS GIS Cut Line= 5
      2138686.01     13418086.32      2138006.61     13418292.41
      2137817.95     13418359.76      2137672.74     13418738.79
      2137568.69     13419210.47
#Sta/Elev= 30
  3964.8   353.4  4012.4     352  4078.2   348.8  4116.3   347.7  4195.8  344.16
  4220.2  343.61  4258.5  341.95  4342.1  339.51  4422.9  337.81    4461  337.69
  4477.9  336.94  4507.9  336.72  4603.3  335.63  4787.3  335.45  4812.8  335.05
  4848.9  335.36  4903.6  334.79  4977.1  334.57  4984.8  334.07  4985.3  333.27
  4990.3  333.27  4990.8  334.07  5011.8  334.18  5036.5  335.33  5061.2  335.55
  5181.4  335.91  5260.8  336.76  5379.5  340.24  5533.1  346.23    5764  353.05
#Mann= 6 ,-1 , 0
  3964.8     .05       0  4507.9     .05       0  4903.6     .05       0
  4977.1     .05       0  4984.8     .03       0  4990.8     .05       0
Bank Sta=4848.9,5061.2
XS Rating Curve= 0 ,0
Exp/Cntr=0.3,0.1
LCMann Table=0

Chan Stop Cuts=-1
Use User Specified Reach Order=0
Composite Channel Slope=5