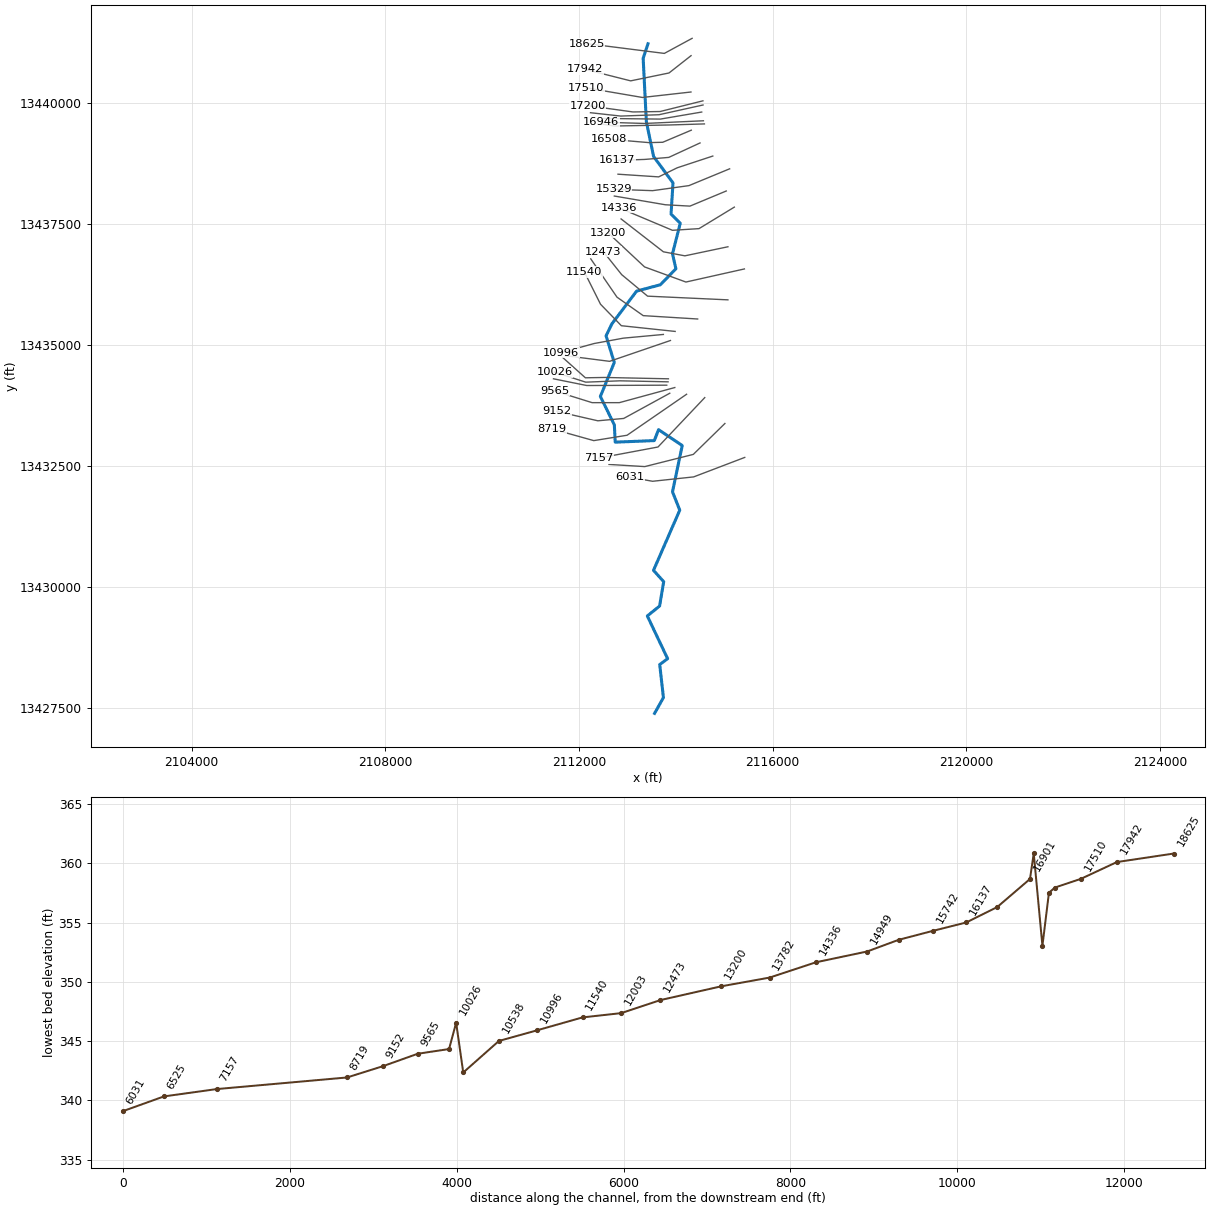
--- UNT 023 in La Jarita Watershed.prj (project) ---

Proj Title=UNT 023 in La Jarita Watershed Base Level Engineering
Current Plan=p01
Default Exp/Contr=0.3,0.1
English Units
Geom File=g01
Flow File=f01
Plan File=p01
BEGIN DESCRIPTION:
UNT 023 in La Jarita Watershed
END DESCRIPTION:

--- UNT 023 in La Jarita Watershed.p01 (plan) ---

Plan Title=Multiple Run
Short Identifier=Multiple
Geom File=g01
Flow File=f01
Subcritical Flow
K Sum by GR= 0
Std Step Tol= 0.01
Critical Tol= 0.01
Num of Std Step Trials= 20
Max Error Tol= 0.3
Flow Tol Ratio= 0.001
Split Flow NTrial= 30
Split Flow Tol= 0.02
Split Flow Ratio= 0.02
Log Output Level= 0
Friction Slope Method= 1
Unsteady Friction Slope Method= 2
Unsteady Bridges Friction Slope Method= 1
Parabolic Critical Depth
Global Vel Dist=  1 , 1 , 1
Global Log Level= 0
CheckData=True
Encroach Param= -1, 0, 0, 0
BEGIN DESCRIPTION:
Multiple Run
END DESCRIPTION:

--- UNT 023 in La Jarita Watershed.f01 (steady flow) ---

Flow Title=Multiple
Number of Profiles=7
Profile Names=10-year,25-year,50-year,1pct_min,100-year,1pct_plu,500-year
River Rch & RM= UNT 023 in La Ja,Reach-1,18625
      69      88     102      59     118     235     161
River Rch & RM= UNT 023 in La Ja,Reach-1,16137
     180     243     293     177     352     703     516
River Rch & RM= UNT 023 in La Ja,Reach-1,12473
     244     334     407     247     493     984     736
River Rch & RM= UNT 023 in La Ja,Reach-1,10996
     283     388     474     288     575    1148     860
River Rch & RM= UNT 023 in La Ja,Reach-1,5541
     296     406     496     301     601    1199     896
Boundary for River Rch & Prof#=UNT 023 in La Ja,Reach-1,1
Up Type=0
Dn Type=3
Dn Slope=0.005
Boundary for River Rch & Prof#=UNT 023 in La Ja,Reach-1,2
Up Type=0
Dn Type=3
Dn Slope=0.005
Boundary for River Rch & Prof#=UNT 023 in La Ja,Reach-1,3
Up Type=0
Dn Type=3
Dn Slope=0.005
Boundary for River Rch & Prof#=UNT 023 in La Ja,Reach-1,4
Up Type=0
Dn Type=3
Dn Slope=0.005
Boundary for River Rch & Prof#=UNT 023 in La Ja,Reach-1,5
Up Type=0
Dn Type=3
Dn Slope=0.005
Boundary for River Rch & Prof#=UNT 023 in La Ja,Reach-1,6
Up Type=0
Dn Type=3
Dn Slope=0.005
Boundary for River Rch & Prof#=UNT 023 in La Ja,Reach-1,7
Up Type=0
Dn Type=3
Dn Slope=0.005

--- UNT 023 in La Jarita Watershed.g01 (geometry) ---

Geom Title=Existing Conditions

River Reach=UNT 023 in La Ja,Reach-1
Reach XY= 30
      2113425.00     13441224.93      2113325.00     13440924.93
      2113390.80     13439614.47      2113540.80     13438894.47
      2113941.21     13438349.48      2113900.80     13437704.47
      2114090.80     13437514.47      2113930.80     13436884.47
      2114000.80     13436574.47      2113680.80     13436244.47
      2113190.14     13436113.27      2112678.85     13435436.19
      2112558.66     13435187.49      2112728.33     13434636.78
      2112440.64     13433934.96      2112729.71     13433348.15
      2112747.07     13432990.51      2113555.23     13433023.06
      2113642.47     13433249.63      2114132.05     13432920.20
      2113930.80     13431964.54      2114080.80     13431584.54
      2113538.30     13430340.77      2113749.24     13430106.40
      2113664.60     13429603.79      2113410.70     13429398.06
      2113829.97     13428515.69      2113666.77     13428392.42
      2113743.25     13427712.39      2113560.80     13427384.54

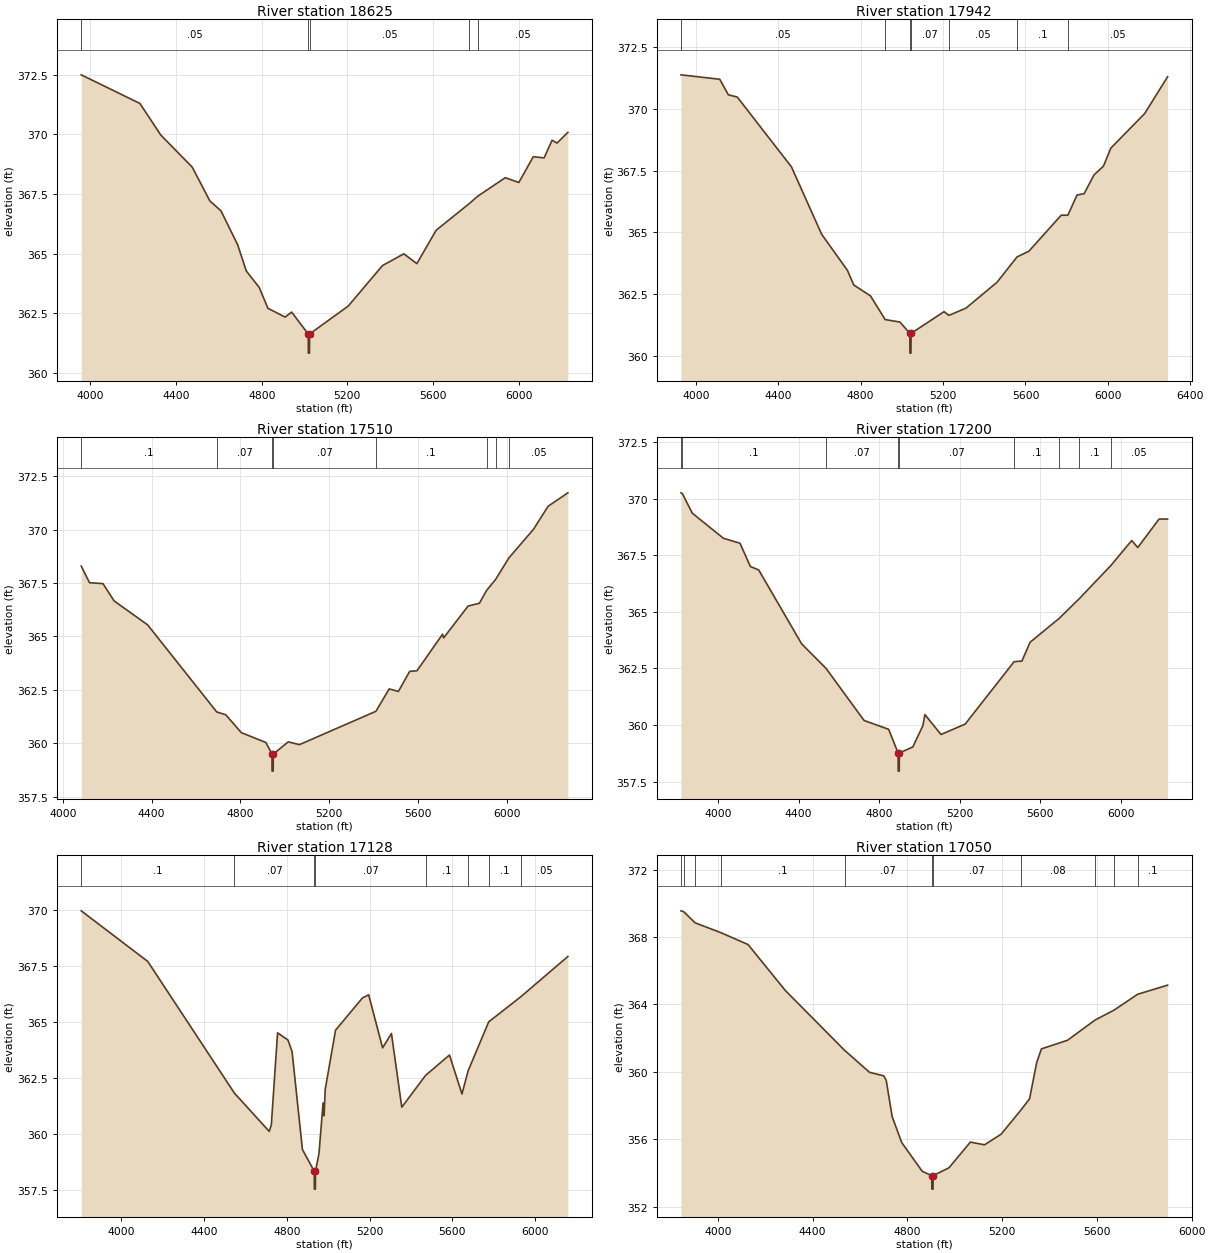
Type RM Length L Ch R = 1,18625,683,683,683
BEGIN DESCRIPTION:
UNT 023 in La Jarita Watershed 22.0
END DESCRIPTION:
XS GIS Cut Line= 3
      2114335.87     13441337.48      2113762.25     13441025.93
      2112154.90     13441228.97
#Sta/Elev= 30
  3957.0  372.49  4231.1  371.29  4328.3  369.97  4475.6  368.62  4557.4  367.21
  4609.8  366.79  4687.6  365.37  4728.0  364.27  4788.4  363.58  4828.7  362.71
  4909.4  362.34  4939.6  362.55  5017.3  361.63  5017.8  360.83  5022.8  360.83
  5023.3  361.63  5203.8  362.80  5364.2  364.50  5463.8  364.99  5524.6  364.58
  5614.9  365.98  5770.2  367.10  5808.3  367.40  5937.5  368.18  6000.9  367.98
  6068.5  369.06  6118.9  369.01  6156.3  369.75  6179.4  369.63  6229.9  370.08
#Mann=5,-1,0
  3957.0    0.05       0  5017.3    0.03       0  5023.3    0.05       0
  5770.2    0.08       0  5808.3    0.05       0
Bank Sta=5017.3,5023.3
Exp/Cntr=0.3,0.1

Type RM Length L Ch R = 1,17942,432,432,432
BEGIN DESCRIPTION:
Mapping XS 8424cb53
END DESCRIPTION:
XS GIS Cut Line= 4
      2114314.19     13440979.42      2113858.43     13440621.33
      2113066.33     13440458.57      2112122.30     13440697.29
#Sta/Elev= 30
  3927.9  371.39  4116.2  371.21  4157.9  370.58  4201.2  370.49  4464.2  367.66
  4610.7  364.93  4735.6  363.47  4766.9  362.87  4847.9  362.43  4919.0  361.47
  4990.8  361.37  5038.9  360.91  5039.4  360.11  5044.4  360.11  5044.9  360.91
  5204.9  361.79  5228.5  361.64  5310.7  361.93  5461.9  362.98  5559.3  364.01
  5616.7  364.24  5773.6  365.70  5806.0  365.70  5850.5  366.52  5884.8  366.57
  5932.5  367.33  5978.7  367.69  6014.6  368.42  6178.7  369.82  6289.9  371.31
#Mann=7,-1,0
  3927.9    0.05       0  4919.0    0.07       0  5038.9    0.07       0
  5044.9    0.07       0  5228.5    0.05       0  5559.3     0.1       0
  5806.0    0.05       0
Bank Sta=5038.9,5044.9
Exp/Cntr=0.3,0.1

Type RM Length L Ch R = 1,17510,310,310,310
BEGIN DESCRIPTION:
Mapping XS c655ef72
END DESCRIPTION:
XS GIS Cut Line= 3
      2114312.19     13440228.21      2113309.58     13440115.36
      2112142.07     13440315.01
#Sta/Elev= 30
  4082.8  368.29  4120.2  367.51  4180.6  367.47  4230.9  366.66  4381.9  365.54
  4693.6  361.46  4734.1  361.33  4804.5  360.49  4915.2  360.03  4942.4  359.49
  4942.9  358.69  4947.9  358.69  4948.4  359.49  5015.8  360.06  5066.2  359.93
  5410.9  361.49  5471.0  362.54  5512.3  362.42  5563.1  363.36  5596.2  363.39
  5711.4  365.10  5716.4  364.93  5826.5  366.42  5877.6  366.55  5909.9  367.15
  5950.2  367.66  6010.2  368.67  6121.1  370.01  6187.1  371.09  6276.2  371.72
#Mann=8,-1,0
  4082.8     0.1       0  4693.6    0.07       0  4942.4    0.07       0
  4948.4    0.07       0  5410.9     0.1       0  5909.9    0.05       0
  5950.2     0.1       0  6010.2    0.05       0
Bank Sta=4942.4,4948.4
Exp/Cntr=0.3,0.1

Type RM Length L Ch R = 1,17200,72,72,72
BEGIN DESCRIPTION:
Mapping XS 29a76b5c
END DESCRIPTION:
XS GIS Cut Line= 4
      2114559.61     13440045.93      2113674.16     13439824.56
      2113114.27     13439815.88      2112178.41     13439945.86
#Sta/Elev= 30
  3815.2  370.27  3822.0  370.24  3871.5  369.37  4026.1  368.26  4108.6  368.04
  4160.1  367.01  4201.3  366.86  4414.8  363.59  4536.4  362.50  4724.9  360.20
  4847.1  359.81  4894.1  358.76  4894.6  357.96  4899.6  357.96  4900.1  358.76
  4967.1  359.03  5017.1  359.97  5027.2  360.46  5107.1  359.58  5227.1  360.04
  5470.2  362.80  5509.2  362.83  5549.6  363.66  5694.7  364.72  5794.3  365.59
  5951.5  367.06  6054.4  368.16  6084.7  367.85  6190.4  369.11  6232.7  369.11
#Mann=9,-1,0
  3815.2    0.05       0  3822.0     0.1       0  4536.4    0.07       0
  4894.1    0.07       0  4900.1    0.07       0  5470.2     0.1       0
  5694.7    0.05       0  5794.3     0.1       0  5951.5    0.05       0
Bank Sta=4894.1,4900.1
Exp/Cntr=0.3,0.1

Type RM Length L Ch R = 1,17128,78,78,78
BEGIN DESCRIPTION:
Mapping XS b12b1075
END DESCRIPTION:
XS GIS Cut Line= 4
      2114562.01     13439959.88      2113652.27     13439758.48
      2112860.60     13439730.71      2112236.27     13439800.08
#Sta/Elev= 30
  3806.6  369.95  4128.0  367.69  4546.8  361.81  4715.1  360.10  4725.3  360.38
  4755.6  364.50  4805.7  364.18  4825.7  363.66  4875.7  359.29  4932.8  358.32
  4933.3  357.52  4938.3  357.52  4938.8  358.32  4955.8  359.11  4975.5  361.37
  4980.5  360.79  4985.8  361.97  5035.8  364.62  5165.9  366.06  5195.9  366.20
  5263.2  363.83  5306.0  364.47  5356.0  361.18  5471.0  362.60  5586.5  363.51
  5646.8  361.77  5676.9  362.81  5776.1  364.99  5932.3  366.12  6158.7  367.91
#Mann=8,-1,0
  3806.6     0.1       0  4546.8    0.07       0  4932.8    0.07       0
  4938.8    0.07       0  5471.0     0.1       0  5676.9    0.05       0
  5776.1     0.1       0  5932.3    0.05       0
Bank Sta=4932.8,4938.8
Exp/Cntr=0.3,0.1

Type RM Length L Ch R = 1,17050,104,104,104
BEGIN DESCRIPTION:
Mapping XS abbbd52e
END DESCRIPTION:
XS GIS Cut Line= 3
      2114534.22     13439814.04      2113680.05     13439668.21
      2112492.56     13439682.09
#Sta/Elev= 30
  3844.2  369.55  3855.9  369.50  3903.7  368.84  4011.7  368.26  4127.5  367.55
  4284.4  364.83  4534.6  361.28  4640.2  359.97  4700.4  359.76  4710.7  359.49
  4735.8  357.34  4775.8  355.81  4862.5  354.10  4902.8  353.84  4903.3  353.04
  4908.3  353.04  4908.8  353.84  4975.8  354.31  5065.8  355.83  5125.8  355.67
  5195.8  356.30  5280.3  357.75  5315.8  358.40  5345.8  360.55  5365.8  361.36
  5475.8  361.87  5592.2  363.07  5673.6  363.67  5772.0  364.60  5898.3  365.14
#Mann=11,-1,0
  3844.2    0.05       0  3855.9     0.1       0  3903.7    0.05       0
  4011.7     0.1       0  4534.6    0.07       0  4902.8    0.07       0
  4908.8    0.07       0  5280.3    0.08       0  5592.2     0.1       0
  5673.6    0.05       0  5772.0     0.1       0
Bank Sta=4902.8,4908.8
Exp/Cntr=0.3,0.1

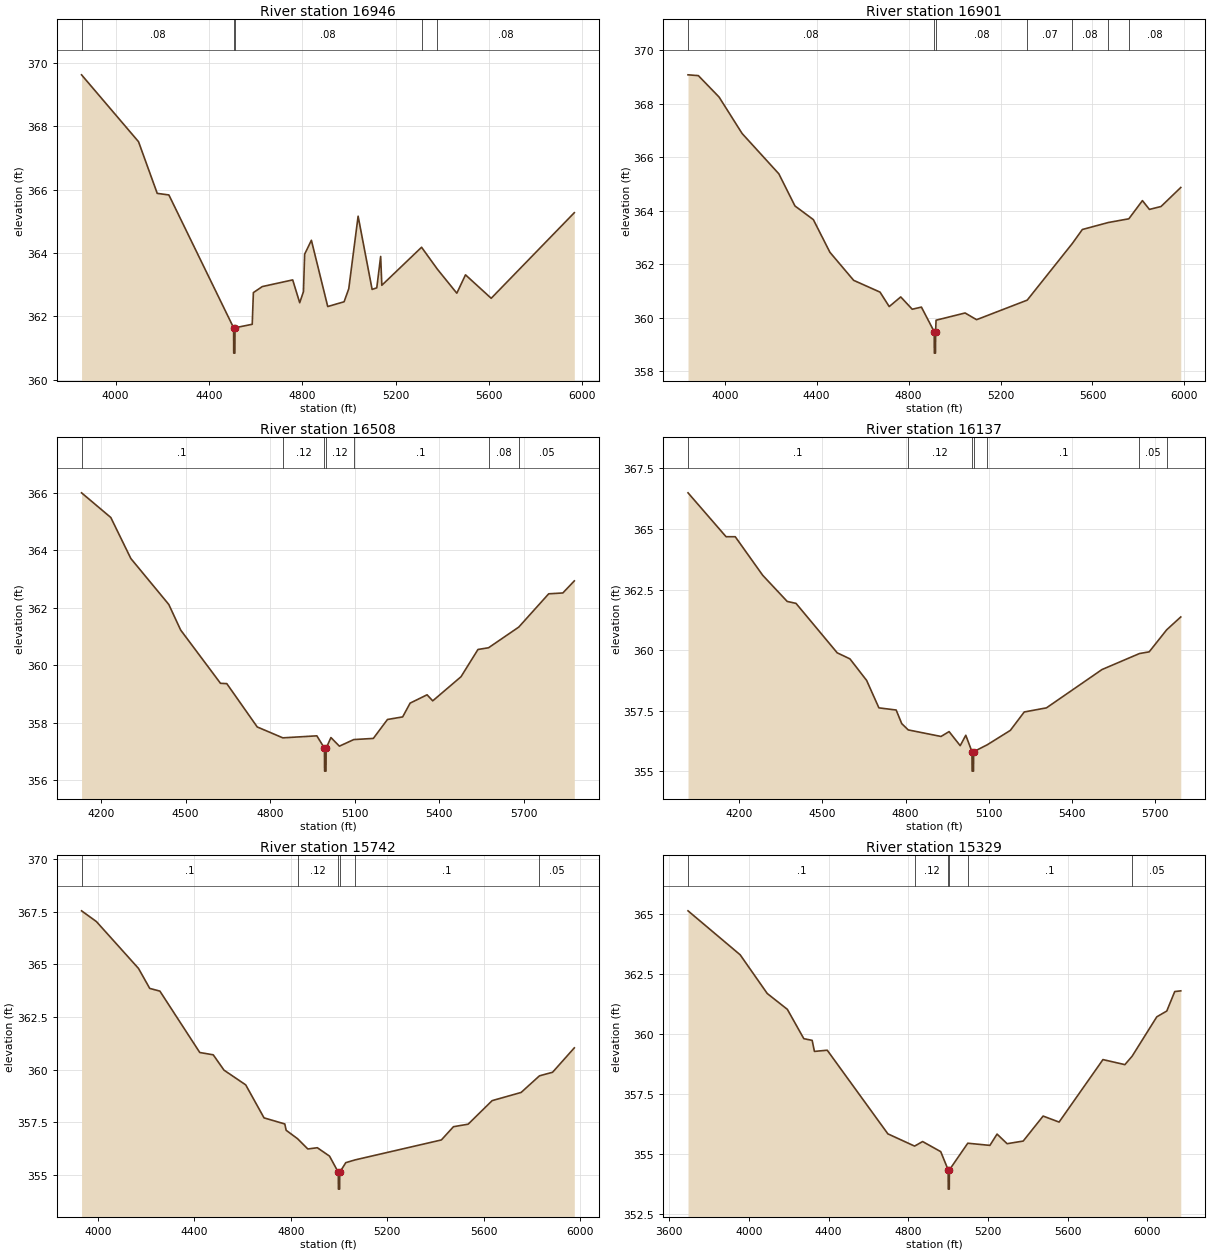
Type RM Length L Ch R = 1,16946,45,45,45
BEGIN DESCRIPTION:
Mapping XS 36b2dc59
END DESCRIPTION:
XS GIS Cut Line= 3
      2114568.92     13439633.48      2113353.66     13439577.93
      2112458.92     13439605.67
#Sta/Elev= 30
  3854.0  369.62  4098.2  367.51  4178.3  365.88  4228.3  365.83  4505.6  361.64
  4506.1  360.84  4511.1  360.84  4511.6  361.64  4585.4  361.75  4590.4  362.75
  4628.7  362.94  4758.9  363.15  4788.9  362.43  4805.0  362.78  4810.0  363.96
  4839.0  364.40  4909.0  362.31  4979.1  362.46  4999.1  362.87  5039.2  365.16
  5099.2  362.85  5119.2  362.90  5135.8  363.89  5140.8  362.98  5311.1  364.18
  5378.7  363.49  5462.2  362.73  5499.4  363.31  5609.5  362.57  5965.7  365.27
#Mann=5,-1,0
  3854.0    0.08       0  4505.6    0.07       0  4511.6    0.08       0
  5311.1    0.07       0  5378.7    0.08       0
Bank Sta=4505.6,4511.6
Exp/Cntr=0.3,0.1

Type RM Length L Ch R = 1,16901,393,393,393
BEGIN DESCRIPTION:
Mapping XS 8343097d
END DESCRIPTION:
XS GIS Cut Line= 4
      2114589.99     13439568.49      2113869.47     13439546.79
      2112727.98     13439525.08      2112450.20     13439568.49
#Sta/Elev= 30
  3840.4  369.08  3885.4  369.05  3975.5  368.25  4075.5  366.89  4235.6  365.38
  4305.6  364.18  4385.6  363.67  4457.6  362.45  4561.0  361.40  4675.7  360.96
  4715.7  360.42  4765.8  360.78  4815.8  360.32  4855.8  360.40  4911.5  359.48
  4912.0  358.68  4917.0  358.68  4917.5  359.48  4919.5  359.91  5045.8  360.18
  5095.8  359.93  5316.0  360.66  5512.5  362.78  5555.9  363.30  5668.5  363.56
  5758.2  363.70  5817.3  364.38  5847.7  364.05  5898.3  364.16  5984.1  364.87
#Mann=7,-1,0
  3840.4    0.08       0  4911.5    0.07       0  4917.5    0.08       0
  5316.0    0.07       0  5512.5    0.08       0  5668.5    0.05       0
  5758.2    0.08       0
Bank Sta=4911.5,4917.5
Exp/Cntr=0.3,0.1

Type RM Length L Ch R = 1,16508,371,371,371
BEGIN DESCRIPTION:
Mapping XS 9d3fd642
END DESCRIPTION:
XS GIS Cut Line= 4
      2114318.97     13439439.05      2113728.66     13439189.04
      2113443.93     13439182.09      2112624.45     13439251.54
#Sta/Elev= 30
  4131.0  366.01  4234.8  365.15  4305.9  363.72  4440.5  362.12  4482.5  361.23
  4624.0  359.37  4646.3  359.36  4754.3  357.85  4845.1  357.47  4965.8  357.54
  4992.8  357.11  4993.3  356.31  4998.3  356.31  4998.8  357.11  5015.8  357.48
  5045.8  357.18  5096.9  357.41  5166.2  357.45  5216.4  358.11  5270.3  358.20
  5296.7  358.68  5356.9  358.97  5377.0  358.76  5477.3  359.60  5537.5  360.55
  5575.0  360.61  5682.2  361.33  5788.4  362.49  5838.6  362.52  5879.3  362.94
#Mann=7,-1,0
  4131.0     0.1       0  4845.1    0.12       0  4992.8    0.07       0
  4998.8    0.12       0  5096.9     0.1       0  5575.0    0.08       0
  5682.2    0.05       0
Bank Sta=4992.8,4998.8
Exp/Cntr=0.3,0.1

Type RM Length L Ch R = 1,16137,395,395,395
BEGIN DESCRIPTION:
Mapping XS 76fa0b71
END DESCRIPTION:
XS GIS Cut Line= 4
      2114499.45     13439175.13      2113853.66     13438876.54
      2113360.60     13438834.87      2112791.18     13438814.04
#Sta/Elev= 30
  4015.6  366.49  4152.7  364.68  4185.8  364.68  4284.7  363.09  4373.1  362.01
  4404.8  361.93  4553.4  359.89  4599.3  359.64  4659.5  358.75  4703.6  357.62
  4765.9  357.53  4785.9  356.97  4809.4  356.71  4927.5  356.44  4956.6  356.64
  4996.7  356.06  5016.8  356.49  5039.1  355.81  5039.6  355.01  5044.6  355.01
  5045.1  355.81  5094.6  356.10  5177.3  356.69  5227.5  357.45  5307.6  357.62
  5507.7  359.20  5642.7  359.86  5677.8  359.93  5740.9  360.84  5791.7  361.37
#Mann=7,-1,0
  4015.6     0.1       0  4809.4    0.12       0  5039.1    0.07       0
  5045.1    0.12       0  5094.6     0.1       0  5642.7    0.05       0
  5740.9     0.1       0
Bank Sta=5039.1,5045.1
Exp/Cntr=0.3,0.1

Type RM Length L Ch R = 1,15742,413,413,413
BEGIN DESCRIPTION:
Mapping XS a575454c
END DESCRIPTION:
XS GIS Cut Line= 4
      2114763.39     13438904.32      2114027.27     13438661.26
      2113645.32     13438473.76      2112805.06     13438529.32
#Sta/Elev= 30
  3932.8  367.55  3994.3  367.04  4168.9  364.81  4215.4  363.86  4257.6  363.73
  4422.9  360.81  4478.7  360.70  4523.4  359.97  4613.4  359.27  4689.3  357.70
  4775.4  357.41  4781.0  357.11  4828.1  356.71  4870.9  356.22  4910.3  356.28
  4960.8  355.88  4997.2  355.11  4997.7  354.31  5002.7  354.31  5003.2  355.11
  5028.3  355.57  5066.5  355.70  5424.5  356.65  5474.6  357.28  5535.5  357.40
  5634.9  358.52  5755.2  358.91  5831.1  359.70  5885.5  359.87  5975.6  361.03
#Mann=6,-1,0
  3932.8     0.1       0  4828.1    0.12       0  4997.2    0.07       0
  5003.2    0.12       0  5066.5     0.1       0  5831.1    0.05       0
Bank Sta=4997.2,5003.2
Exp/Cntr=0.3,0.1

Type RM Length L Ch R = 1,15329,380,380,380
BEGIN DESCRIPTION:
Mapping XS 801c3130
END DESCRIPTION:
XS GIS Cut Line= 4
      2115110.64     13438640.44      2114270.32     13438293.21
      2113520.32     13438189.04      2112714.74     13438216.82
#Sta/Elev= 30
  3694.8  365.13  3956.5  363.30  4092.3  361.69  4193.3  361.03  4275.9  359.81
  4317.7  359.74  4329.1  359.28  4393.4  359.33  4697.6  355.85  4831.8  355.34
  4871.9  355.53  4962.8  355.11  5000.2  354.35  5000.7  353.55  5005.7  353.55
  5006.2  354.35  5098.5  355.46  5209.5  355.37  5245.5  355.84  5295.9  355.44
  5376.6  355.55  5476.6  356.59  5556.7  356.34  5776.8  358.94  5886.9  358.73
  5923.1  359.08  6047.0  360.72  6097.0  360.96  6137.0  361.77  6167.3  361.80
#Mann=6,-1,0
  3694.8     0.1       0  4831.8    0.12       0  5000.2    0.07       0
  5006.2    0.12       0  5098.5     0.1       0  5923.1    0.05       0
Bank Sta=5000.2,5006.2
Exp/Cntr=0.3,0.1

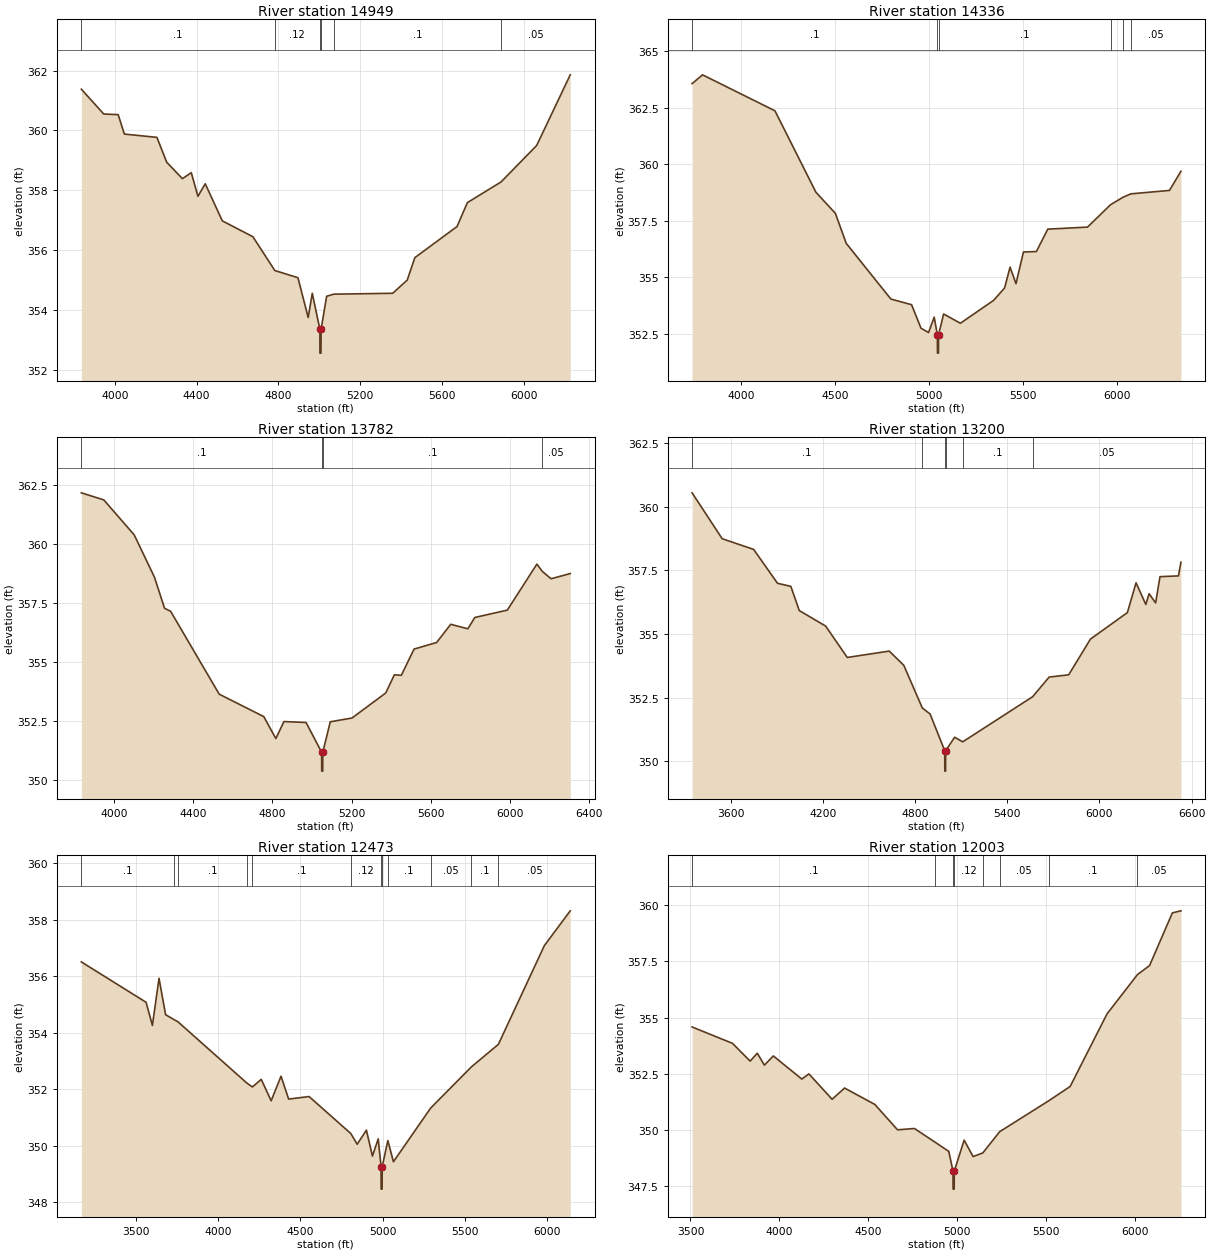
Type RM Length L Ch R = 1,14949,613,613,613
BEGIN DESCRIPTION:
Mapping XS c768047c
END DESCRIPTION:
XS GIS Cut Line= 4
      2115041.17     13438182.10      2114291.16     13437869.59
      2113784.21     13437897.37      2112729.35     13438077.81
#Sta/Elev= 30
  3836.6  361.38  3946.1  360.55  4016.6  360.53  4046.9  359.88  4206.1  359.77
  4253.8  358.94  4330.7  358.39  4374.1  358.59  4406.6  357.80  4442.3  358.22
  4525.8  356.98  4675.3  356.45  4782.6  355.32  4895.6  355.08  4945.7  353.75
  4965.7  354.56  5002.8  353.36  5003.3  352.56  5008.3  352.56  5008.8  353.36
  5035.9  354.46  5070.6  354.53  5358.9  354.56  5429.9  355.00  5467.2  355.75
  5673.4  356.79  5724.2  357.59  5888.7  358.28  6063.0  359.50  6227.0  361.86
#Mann=6,-1,0
  3836.6     0.1       0  4782.6    0.12       0  5002.8    0.07       0
  5008.8    0.12       0  5070.6     0.1       0  5888.7    0.05       0
Bank Sta=5002.8,5008.8
Exp/Cntr=0.3,0.1

Type RM Length L Ch R = 1,14336,554,554,554
BEGIN DESCRIPTION:
Mapping XS 804b832c
END DESCRIPTION:
XS GIS Cut Line= 4
      2115207.81     13437848.75      2114478.66     13437404.32
      2113930.05     13437369.59      2112825.90     13437834.86
#Sta/Elev= 30
  3737.4  363.56  3793.0  363.95  4178.4  362.36  4396.5  358.76  4499.8  357.83
  4557.9  356.50  4795.4  354.04  4905.6  353.79  4955.7  352.75  4995.8  352.56
  5025.9  353.24  5042.9  352.45  5043.4  351.65  5048.4  351.65  5048.9  352.45
  5076.0  353.38  5165.3  352.97  5341.8  353.98  5400.6  354.53  5429.7  355.45
  5461.2  354.72  5500.9  356.12  5569.7  356.14  5630.4  357.13  5841.9  357.22
  5964.5  358.21  6031.0  358.54  6072.5  358.69  6277.8  358.84  6339.2  359.69
#Mann=6,-1,0
  3737.4     0.1       0  5042.9    0.07       0  5048.9     0.1       0
  5964.5    0.05       0  6031.0     0.1       0  6072.5    0.05       0
Bank Sta=5042.9,5048.9
Exp/Cntr=0.3,0.1

Type RM Length L Ch R = 1,13782,582,582,582
BEGIN DESCRIPTION:
Mapping XS 573f89dc
END DESCRIPTION:
XS GIS Cut Line= 4
      2115075.89     13437029.32      2114186.99     13436841.82
      2113742.55     13436925.15      2112868.77     13437604.75
#Sta/Elev= 30
  3835.5  362.15  3948.8  361.85  4102.1  360.37  4204.3  358.58  4255.4  357.26
  4286.1  357.13  4531.4  353.62  4756.2  352.67  4817.2  351.74  4857.9  352.46
  4969.8  352.42  5048.2  351.16  5048.7  350.36  5053.7  350.36  5054.2  351.16
  5091.9  352.45  5201.7  352.61  5371.8  353.67  5415.3  354.44  5450.6  354.42
  5514.8  355.53  5628.8  355.81  5699.8  356.58  5786.3  356.39  5821.6  356.87
  5985.4  357.18  6134.7  359.13  6162.3  358.82  6206.5  358.51  6303.1  358.73
#Mann=4,-1,0
  3835.5     0.1       0  5048.2    0.07       0  5054.2     0.1       0
  6162.3    0.05       0
Bank Sta=5048.2,5054.2
Exp/Cntr=0.3,0.1

Type RM Length L Ch R = 1,13200,727,727,727
BEGIN DESCRIPTION:
Mapping XS f36a1d45
END DESCRIPTION:
XS GIS Cut Line= 4
      2115416.21     13436570.99      2114207.82     13436300.15
      2113353.66     13436612.65      2112597.21     13437320.52
#Sta/Elev= 30
  3347.4  360.54  3543.3  358.74  3748.3  358.32  3903.9  356.99  3990.6  356.87
  4045.5  355.92  4217.6  355.31  4358.0  354.08  4631.4  354.33  4726.4  353.77
  4846.6  352.10  4897.6  351.86  4992.8  350.42  4993.3  349.62  4998.3  349.62
  4998.8  350.42  5057.3  350.95  5110.1  350.77  5565.3  352.54  5672.7  353.31
  5800.2  353.40  5941.8  354.80  6182.2  355.84  6238.8  357.01  6302.4  356.16
  6323.8  356.58  6366.3  356.22  6394.7  357.25  6514.8  357.28  6531.3  357.82
#Mann=6,-1,0
  3347.4     0.1       0  4846.6    0.12       0  4992.8    0.07       0
  4998.8    0.12       0  5110.1     0.1       0  5565.3    0.05       0
Bank Sta=4992.8,4998.8
Exp/Cntr=0.3,0.1

Type RM Length L Ch R = 1,12473,470,470,470
BEGIN DESCRIPTION:
Mapping XS 575bb3bd
END DESCRIPTION:
XS GIS Cut Line= 4
      2115075.87     13435932.09      2113416.16     13436008.48
      2112881.43     13436452.93      2112500.58     13436930.73
#Sta/Elev= 30
  3171.0  356.51  3563.9  355.08  3602.3  354.26  3642.4  355.93  3682.4  354.64
  3735.4  354.46  3757.1  354.39  4175.4  352.22  4209.3  352.08  4263.0  352.35
  4323.1  351.59  4383.1  352.46  4429.3  351.65  4553.3  351.74  4806.8  350.43
  4845.5  350.05  4901.5  350.55  4937.9  349.63  4973.1  350.24  4990.4  349.26
  4990.9  348.46  4996.9  348.46  4997.4  349.26  5031.6  350.18  5065.5  349.43
  5291.2  351.33  5538.6  352.79  5702.6  353.59  5981.9  357.09  6138.8  358.32
#Mann=12,-1,0
  3171.0     0.1       0  3735.4    0.12       0  3757.1     0.1       0
  4175.4    0.12       0  4209.3     0.1       0  4806.8    0.12       0
  4990.4    0.07       0  4997.4    0.12       0  5031.6     0.1       0
  5291.2    0.05       0  5538.6     0.1       0  5702.6    0.05       0
Bank Sta=4990.4,4997.4
Exp/Cntr=0.3,0.1

Type RM Length L Ch R = 1,12003,463,463,463
BEGIN DESCRIPTION:
Mapping XS 845c94b5
END DESCRIPTION:
XS GIS Cut Line= 4
      2114450.88     13435536.26      2113325.88     13435605.71
      2112784.21     13435987.65      2112242.53     13436779.34
#Sta/Elev= 30
  3509.2  354.58  3736.4  353.85  3835.7  353.06  3875.8  353.41  3915.9  352.88
  3966.0  353.29  4126.3  352.26  4166.3  352.49  4296.6  351.36  4366.7  351.86
  4537.0  351.13  4664.6  350.00  4759.5  350.06  4873.7  349.46  4952.8  349.04
  4976.5  348.16  4977.0  347.36  4983.0  347.36  4983.6  348.16  5039.0  349.54
  5089.5  348.81  5143.7  348.97  5239.3  349.92  5514.2  351.29  5635.2  351.93
  5842.5  355.16  6013.5  356.91  6081.6  357.31  6210.2  359.66  6258.4  359.75
#Mann=8,-1,0
  3509.2     0.1       0  4873.7    0.12       0  4976.5    0.07       0
  4983.6    0.12       0  5143.7     0.1       0  5239.3    0.05       0
  5514.2     0.1       0  6013.5    0.05       0
Bank Sta=4976.5,4983.6
Exp/Cntr=0.3,0.1

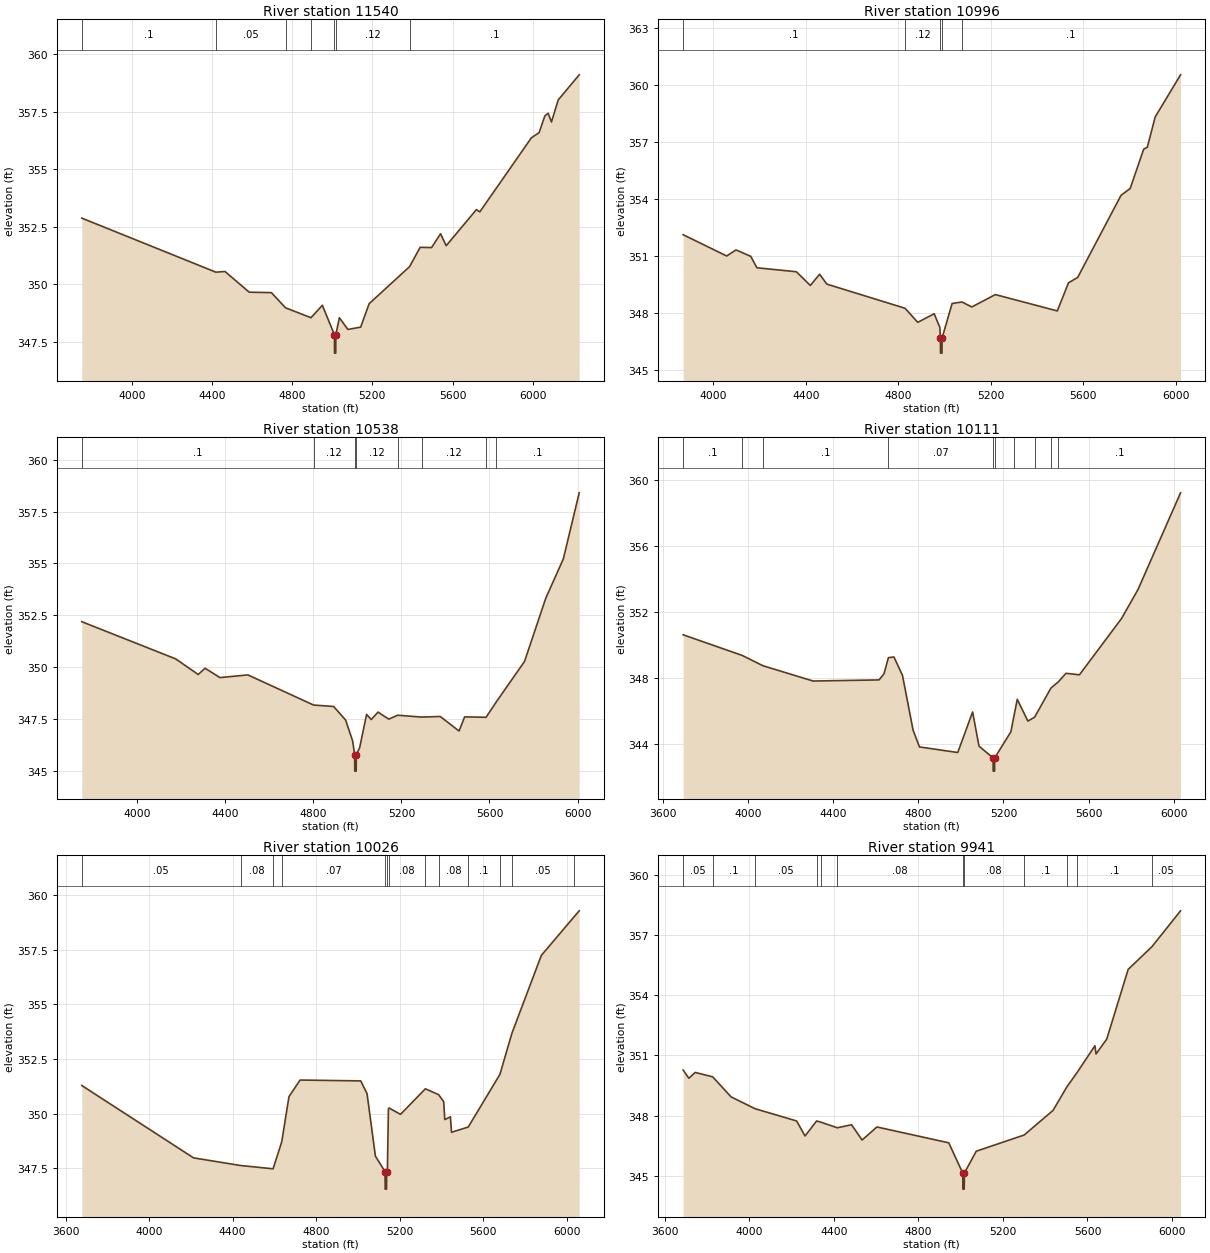
Type RM Length L Ch R = 1,11540,544,544,544
BEGIN DESCRIPTION:
Mapping XS db41ba28
END DESCRIPTION:
XS GIS Cut Line= 4
      2113985.65     13435279.31      2112874.49     13435397.37
      2112443.93     13435841.82      2112110.59     13436508.52
#Sta/Elev= 30
  3750.5  352.87  4419.5  350.52  4465.1  350.55  4585.8  349.65  4696.4  349.63
  4767.1  348.97  4894.0  348.54  4950.7  349.08  5010.9  347.80  5011.4  347.00
  5017.5  347.00  5018.0  347.80  5035.6  348.54  5078.0  348.03  5141.8  348.13
  5184.2  349.15  5385.8  350.76  5438.6  351.60  5495.7  351.59  5540.4  352.19
  5568.5  351.67  5719.3  353.24  5736.1  353.14  5993.4  356.36  6032.3  356.59
  6060.5  357.31  6077.1  357.43  6093.8  357.05  6127.5  358.01  6232.1  359.10
#Mann=7,-1,0
  3750.5     0.1       0  4419.5    0.05       0  4767.1     0.1       0
  4894.0    0.12       0  5010.9    0.07       0  5018.0    0.12       0
  5385.8     0.1       0
Bank Sta=5010.9,5018
Exp/Cntr=0.3,0.1

Type RM Length L Ch R = 1,10996,458,458,458
BEGIN DESCRIPTION:
Mapping XS 5f6a14cf
END DESCRIPTION:
XS GIS Cut Line= 4
      2113742.53     13435216.81      2112916.16     13435140.43
      2112311.99     13435029.32      2111631.44     13434841.82
#Sta/Elev= 30
  3870.2  352.14  4058.5  351.02  4098.7  351.34  4162.7  351.00  4189.1  350.40
  4359.8  350.19  4420.1  349.47  4460.2  350.06  4491.4  349.54  4829.6  348.27
  4884.3  347.53  4955.5  347.98  4979.9  347.26  4982.2  346.71  4982.8  345.91
  4989.1  345.91  4989.7  346.71  5032.9  348.52  5075.1  348.60  5118.1  348.34
  5219.8  348.99  5487.6  348.13  5536.0  349.61  5575.6  349.89  5763.0  354.21
  5802.6  354.57  5861.0  356.64  5876.6  356.74  5910.9  358.34  6020.3  360.55
#Mann=5,-1,0
  3870.2     0.1       0  4829.6    0.12       0  4982.2    0.07       0
  4989.7    0.12       0  5075.1     0.1       0
Bank Sta=4982.2,4989.7
Exp/Cntr=0.3,0.1

Type RM Length L Ch R = 1,10538,427,427,427
BEGIN DESCRIPTION:
Mapping XS 3a408083
END DESCRIPTION:
XS GIS Cut Line= 3
      2113888.37     13435091.81      2112631.43     13434661.26
      2111708.87     13434779.18
#Sta/Elev= 30
  3748.7  352.20  4175.1  350.41  4277.2  349.66  4308.5  349.96  4376.3  349.51
  4502.8  349.64  4801.1  348.19  4892.3  348.12  4946.7  347.47  4978.4  346.47
  4987.7  345.81  4988.3  345.01  4994.7  345.01  4995.2  345.81  5010.1  346.12
  5041.9  347.74  5063.0  347.49  5093.9  347.85  5142.8  347.51  5182.7  347.70
  5292.6  347.61  5376.2  347.64  5461.8  346.94  5487.1  347.62  5584.6  347.60
  5630.9  348.34  5759.3  350.29  5855.6  353.33  5935.3  355.22  6007.4  358.40
#Mann=8,-1,0
  3748.7     0.1       0  4801.1    0.12       0  4987.7    0.07       0
  4995.2    0.12       0  5182.7    0.07       0  5292.6    0.12       0
  5584.6    0.07       0  5630.9     0.1       0
Bank Sta=4987.7,4995.2
Exp/Cntr=0.3,0.1

Type RM Length L Ch R = 1,10111,85,85,85
BEGIN DESCRIPTION:
Mapping XS 58cc5bc0
END DESCRIPTION:
XS GIS Cut Line= 4
      2113846.69     13434300.15      2112527.27     13434327.93
      2112131.43     13434320.98      2111666.15     13434737.66
#Sta/Elev= 30
  3692.8  350.63  3970.0  349.38  4068.4  348.75  4304.6  347.82  4614.7  347.89
  4637.8  348.26  4658.6  349.24  4684.7  349.28  4724.7  348.17  4774.7  344.84
  4804.7  343.82  4984.8  343.48  5054.8  345.94  5084.8  343.87  5151.1  343.15
  5151.6  342.35  5158.0  342.35  5158.6  343.15  5234.8  344.74  5248.5  345.65
  5264.8  346.71  5314.8  345.39  5346.7  345.63  5423.0  347.39  5458.8  347.78
  5493.9  348.29  5557.4  348.20  5755.5  351.62  5833.3  353.39  6033.0  359.25
#Mann=10,-1,0
  3692.8     0.1       0  3970.0    0.05       0  4068.4     0.1       0
  4658.6    0.07       0  5151.1    0.07       0  5158.6    0.07       0
  5248.5     0.1       0  5346.7    0.08       0  5423.0    0.12       0
  5458.8     0.1       0
Bank Sta=5151.1,5158.6
Exp/Cntr=0.3,0.1

Type RM Length L Ch R = 1,10026,85,85,85
BEGIN DESCRIPTION:
Mapping XS 7cb657ba
END DESCRIPTION:
XS GIS Cut Line= 4
      2113839.76     13434237.65      2112846.71     13434258.48
      2112138.38     13434230.71      2111492.59     13434439.02
#Sta/Elev= 30
  3677.9  351.29  4212.8  347.98  4438.1  347.63  4593.5  347.48  4634.8  348.71
  4669.5  350.78  4722.9  351.54  5013.1  351.50  5043.2  350.92  5083.2  348.06
  5129.4  347.35  5130.0  346.55  5136.4  346.55  5137.0  347.35  5140.5  347.37
  5145.5  350.22  5149.0  350.26  5203.3  349.97  5322.5  351.14  5385.8  350.87
  5410.1  350.55  5415.3  349.73  5442.1  349.86  5447.4  349.15  5527.6  349.39
  5679.2  351.80  5736.2  353.67  5877.4  357.24  6033.5  359.00  6058.6  359.28
#Mann=13,-1,0
  3677.9    0.05       0  4438.1    0.08       0  4593.5     0.1       0
  4634.8    0.07       0  5129.4    0.07       0  5137.0    0.07       0
  5149.0    0.08       0  5322.5     0.1       0  5385.8    0.08       0
  5527.6     0.1       0  5679.2    0.08       0  5736.2    0.05       0
  6033.5     0.1       0
Bank Sta=5129.4,5137
Exp/Cntr=0.3,0.1

Type RM Length L Ch R = 1,9941,376,376,376
BEGIN DESCRIPTION:
Mapping XS e3e72b02
END DESCRIPTION:
XS GIS Cut Line= 3
      2113812.02     13434168.21      2112159.21     13434161.26
      2111472.12     13434300.07
#Sta/Elev= 30
  3686.5  350.27  3713.5  349.86  3743.5  350.15  3826.5  349.93  3913.5  348.93
  4027.1  348.34  4223.5  347.73  4263.5  346.98  4318.2  347.73  4338.3  347.67
  4416.1  347.39  4483.5  347.54  4533.5  346.78  4603.5  347.43  4943.5  346.64
  5009.7  345.13  5010.3  344.33  5016.7  344.33  5017.3  345.13  5073.5  346.22
  5300.5  347.03  5437.3  348.26  5501.2  349.41  5550.3  350.14  5635.2  351.48
  5640.3  351.07  5691.0  351.81  5792.5  355.29  5904.8  356.42  6040.3  358.21
#Mann=12,-1,0
  3686.5    0.05       0  3826.5     0.1       0  4027.1    0.05       0
  4318.2     0.1       0  4338.3    0.05       0  4416.1    0.08       0
  5009.7    0.07       0  5017.3    0.08       0  5300.5     0.1       0
  5501.2    0.05       0  5550.3     0.1       0  5904.8    0.05       0
Bank Sta=5009.7,5017.3
Exp/Cntr=0.3,0.1

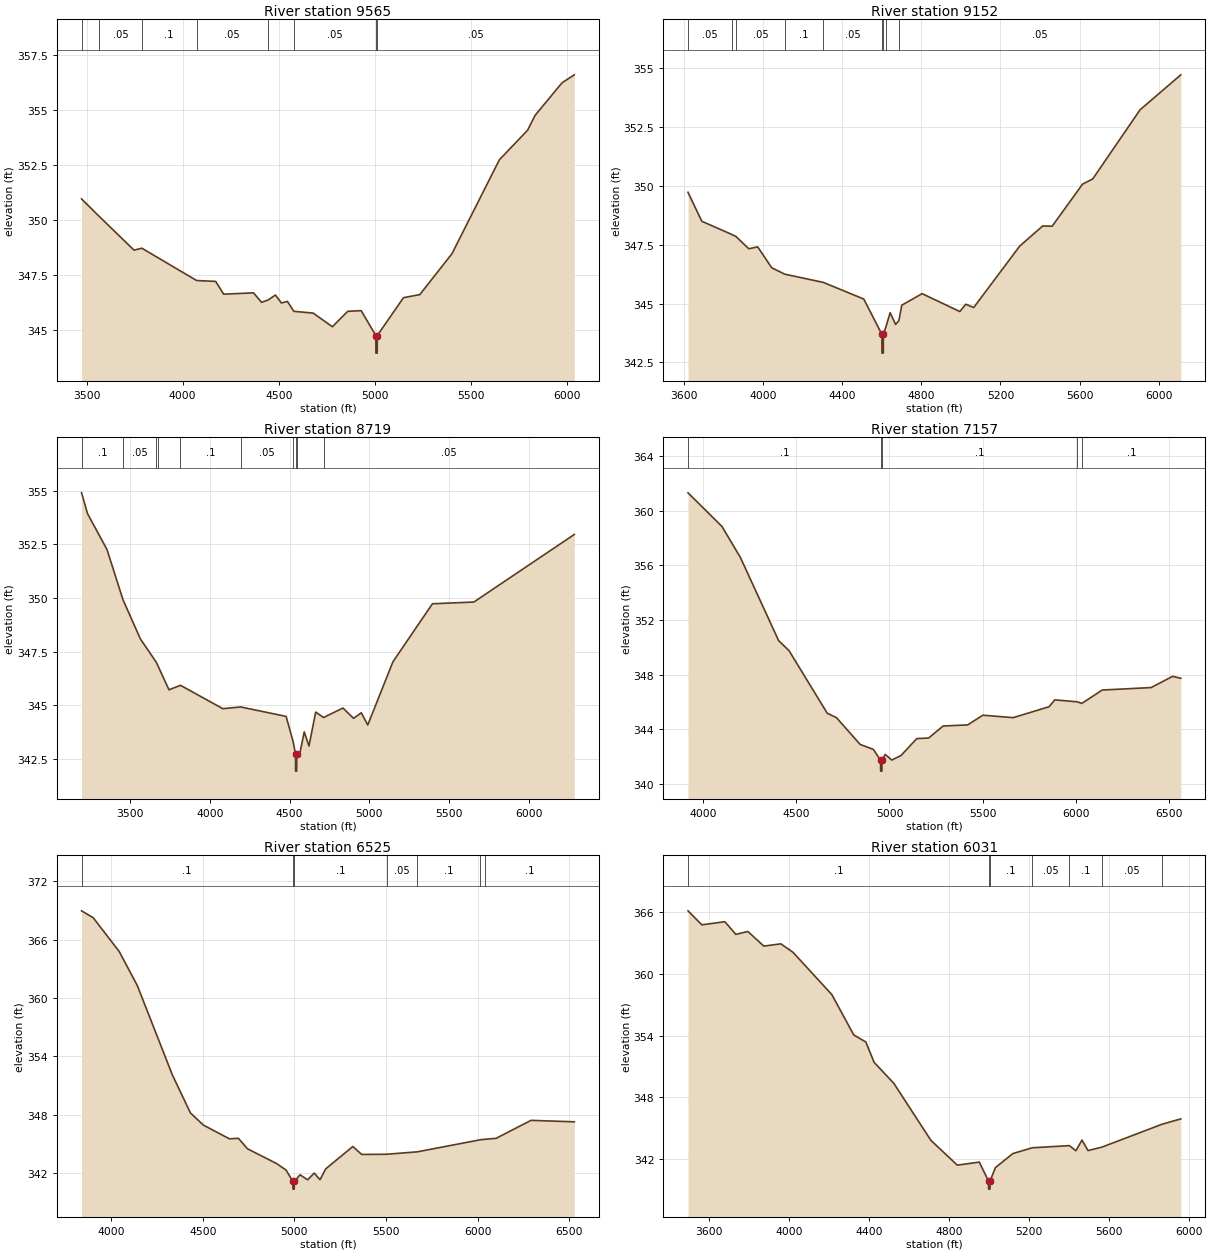
Type RM Length L Ch R = 1,9565,413,413,413
BEGIN DESCRIPTION:
Mapping XS 78aecc5a
END DESCRIPTION:
XS GIS Cut Line= 4
      2113978.67     13434119.60      2112832.82     13433807.09
      2112270.32     13433807.09      2111492.80     13434050.07
#Sta/Elev= 30
  3473.8  350.94  3566.3  350.14  3747.1  348.61  3787.5  348.70  4073.0  347.23
  4172.1  347.19  4213.5  346.61  4369.0  346.67  4410.5  346.24  4443.8  346.34
  4483.0  346.57  4514.1  346.21  4545.2  346.28  4579.0  345.83  4679.3  345.75
  4779.3  345.13  4859.3  345.83  4929.3  345.86  5005.5  344.73  5006.1  343.93
  5012.5  343.93  5013.2  344.73  5149.3  346.45  5234.3  346.59  5401.9  348.45
  5648.7  352.72  5795.3  354.06  5834.6  354.74  5975.0  356.22  6038.6  356.58
#Mann=8,-1,0
  3473.8     0.1       0  3566.3    0.05       0  3787.5     0.1       0
  4073.0    0.05       0  4443.8     0.1       0  4579.0    0.05       0
  5005.5   0.035       0  5013.2    0.05       0
Bank Sta=5005.5,5013.2
Exp/Cntr=0.3,0.1

Type RM Length L Ch R = 1,9152,433,433,433
BEGIN DESCRIPTION:
Mapping XS 62244363
END DESCRIPTION:
XS GIS Cut Line= 4
      2113874.49     13434001.54      2112923.10     13433480.71
      2112388.38     13433432.09      2111541.15     13433626.54
#Sta/Elev= 30
  3620.9  349.73  3690.5  348.50  3842.2  347.94  3863.7  347.85  3928.1  347.33
  3973.1  347.41  4044.2  346.52  4109.7  346.25  4304.6  345.90  4509.5  345.19
  4600.8  343.69  4601.4  342.89  4607.9  342.89  4608.5  343.69  4619.5  343.96
  4642.6  344.61  4670.1  344.11  4686.7  344.27  4701.6  344.93  4804.0  345.42
  4994.8  344.66  5024.9  344.97  5065.1  344.83  5297.2  347.44  5413.6  348.30
  5461.6  348.29  5615.3  350.08  5666.6  350.30  5905.7  353.24  6111.7  354.73
#Mann=9,-1,0
  3620.9    0.05       0  3842.2     0.1       0  3863.7    0.05       0
  4109.7     0.1       0  4304.6    0.05       0  4600.8   0.035       0
  4608.5    0.05       0  4619.5     0.1       0  4686.7    0.05       0
Bank Sta=4600.8,4608.5
Exp/Cntr=0.3,0.1

Type RM Length L Ch R = 1,8719,1562,1562,1562
BEGIN DESCRIPTION:
Mapping XS 55b5cfac
END DESCRIPTION:
XS GIS Cut Line= 4
      2114221.75     13433980.73      2112992.55     13433133.48
      2112305.05     13433022.37      2111438.50     13433265.00
#Sta/Elev= 30
  3195.9  354.90  3233.4  353.93  3355.8  352.25  3455.6  349.92  3564.8  348.09
  3664.8  347.00  3672.3  346.88  3744.0  345.72  3816.2  345.93  4081.4  344.84
  4193.9  344.92  4478.4  344.48  4522.1  343.31  4537.4  342.73  4538.0  341.93
  4544.5  341.93  4545.1  342.73  4564.4  342.76  4592.0  343.76  4621.7  343.10
  4663.7  344.68  4713.3  344.43  4834.6  344.87  4901.4  344.39  4949.7  344.65
  4990.2  344.08  5148.3  347.03  5395.7  349.73  5655.3  349.81  6285.1  352.96
#Mann=10,-1,0
  3195.9     0.1       0  3455.6    0.05       0  3664.8     0.1       0
  3672.3    0.05       0  3816.2     0.1       0  4193.9    0.05       0
  4522.1     0.1       0  4537.4   0.035       0  4545.1     0.1       0
  4713.3    0.05       0
Bank Sta=4537.4,4545.1
Exp/Cntr=0.3,0.1

Type RM Length L Ch R = 1,7157,632,632,632
BEGIN DESCRIPTION:
Mapping XS ec1f97cc
END DESCRIPTION:
XS GIS Cut Line= 3
      2114596.68     13433911.23      2113631.43     13432890.43
      2112409.63     13432661.34
#Sta/Elev= 30
  3917.3  361.30  4099.8  358.84  4198.9  356.57  4404.0  350.50  4460.6  349.75
  4665.7  345.18  4715.1  344.86  4842.5  342.90  4913.3  342.54  4951.8  341.75
  4952.5  340.95  4959.2  340.95  4959.8  341.75  4976.8  342.17  5012.4  341.76
  5061.8  342.09  5146.8  343.33  5210.3  343.37  5288.3  344.25  5420.3  344.33
  5501.7  345.04  5664.5  344.86  5857.8  345.66  5888.3  346.16  6008.7  346.02
  6033.3  345.90  6143.1  346.88  6406.0  347.06  6521.3  347.88  6565.3  347.74
#Mann=5,-1,0
  3917.3     0.1       0  4951.8    0.07       0  4959.8     0.1       0
  6008.7    0.05       0  6033.3     0.1       0
Bank Sta=4951.8,4959.8
Exp/Cntr=0.3,0.1

Type RM Length L Ch R = 1,6525,494,494,494
BEGIN DESCRIPTION:
Mapping XS 4699b8e7
END DESCRIPTION:
XS GIS Cut Line= 4
      2115013.40     13433376.56      2114360.60     13432737.65
      2113357.90     13432485.47      2112619.31     13432530.25
#Sta/Elev= 30
  3839.3  368.98  3902.9  368.27  4044.4  364.80  4143.4  361.29  4334.3  352.10
  4433.3  348.17  4504.0  346.92  4645.5  345.51  4694.9  345.56  4744.5  344.48
  4902.4  342.97  4954.4  342.30  4991.6  341.13  4992.3  340.33  4999.1  340.33
  4999.8  341.13  5030.9  341.81  5072.0  341.29  5108.0  341.98  5140.0  341.30
  5171.0  342.42  5318.8  344.72  5366.9  343.90  5503.4  343.92  5670.4  344.17
  6013.9  345.41  6039.2  345.46  6100.1  345.56  6290.5  347.41  6526.6  347.26
#Mann=7,-1,0
  3839.3     0.1       0  4991.6    0.07       0  4999.8     0.1       0
  5503.4    0.05       0  5670.4     0.1       0  6013.9    0.05       0
  6039.2     0.1       0
Bank Sta=4991.6,4999.8
Exp/Cntr=0.3,0.1

Type RM Length L Ch R = 1,6031,490,490,490
BEGIN DESCRIPTION:
Mapping XS fb7a3f9b
END DESCRIPTION:
XS GIS Cut Line= 4
      2115423.06     13432675.13      2114367.55     13432272.37
      2113520.32     13432182.09      2113049.07     13432265.26
#Sta/Elev= 30
  3497.3  366.14  3566.3  364.78  3681.3  365.08  3736.1  363.85  3796.2  364.13
  3875.8  362.71  3960.7  362.93  4020.8  362.12  4215.3  358.00  4324.9  354.07
  4385.1  353.39  4426.4  351.41  4524.8  349.37  4710.1  343.82  4842.0  341.41
  4951.4  341.71  4997.6  339.88  4998.3  339.08  5005.1  339.08  5005.8  339.88
  5031.9  341.17  5119.3  342.54  5216.3  343.10  5401.2  343.31  5434.1  342.81
  5464.3  343.85  5494.6  342.83  5563.2  343.16  5864.2  345.39  5957.6  345.91
#Mann=7,-1,0
  3497.3     0.1       0  4997.6    0.07       0  5005.8     0.1       0
  5216.3    0.05       0  5401.2     0.1       0  5563.2    0.05       0
  5864.2     0.1       0
Bank Sta=4997.6,5005.8
Exp/Cntr=0.3,0.1