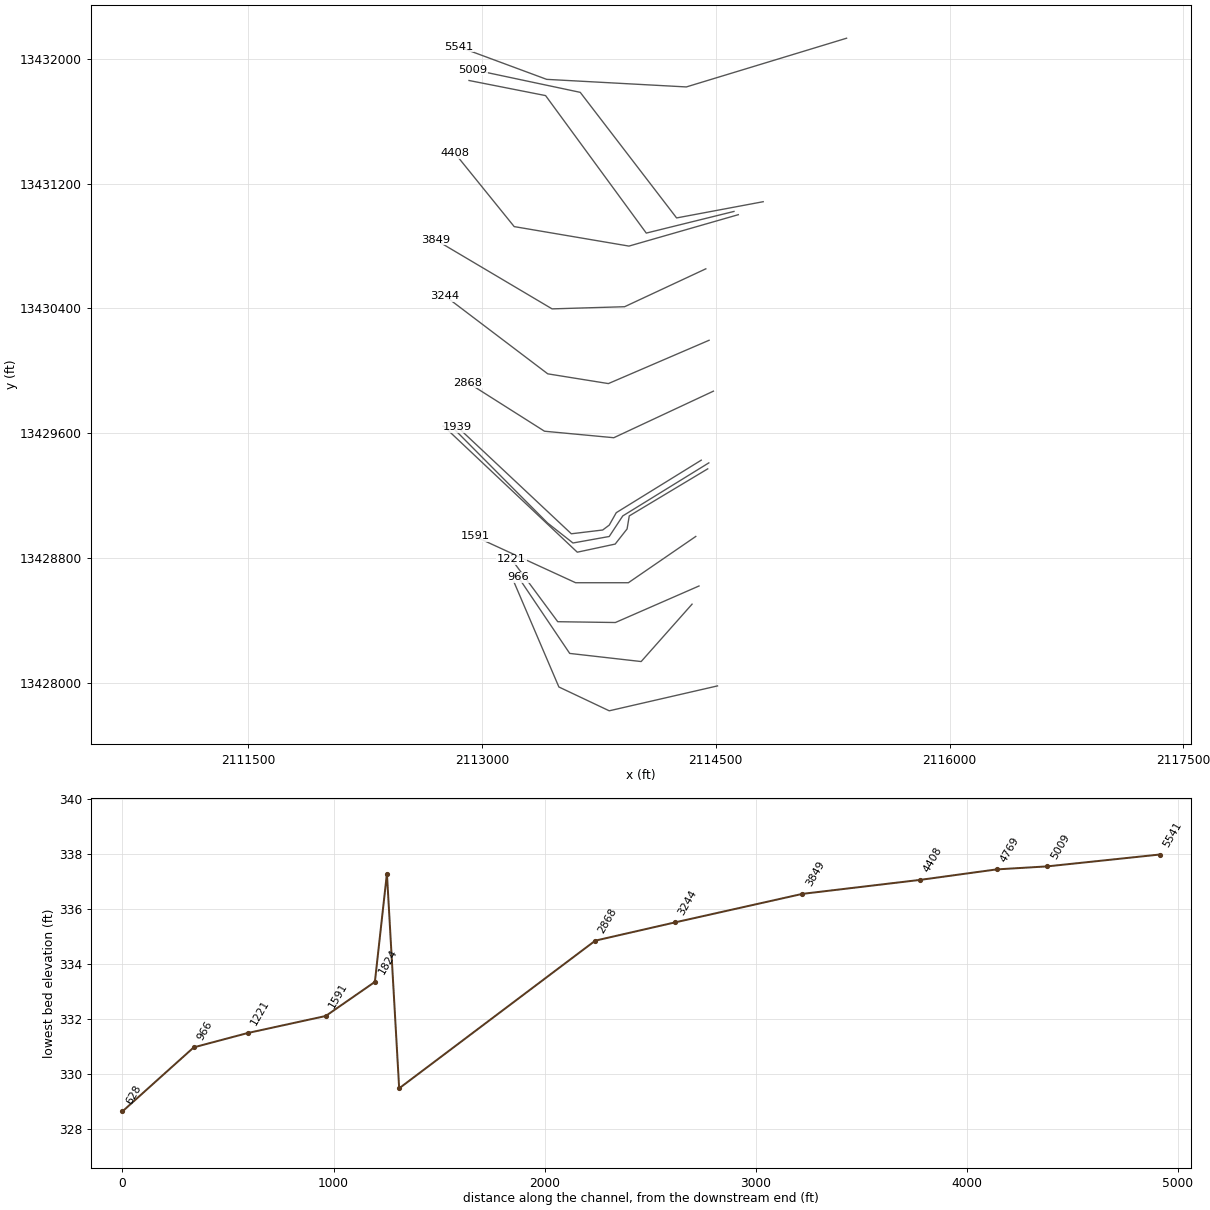
HEC-RAS study UNT 023 in La Jarita Watershed.prj: UNT 023 in La Jarita Watershed Base Level Engineering

--- UNT 023 in La Jarita Watershed.g01 (geometry) --- (continued)

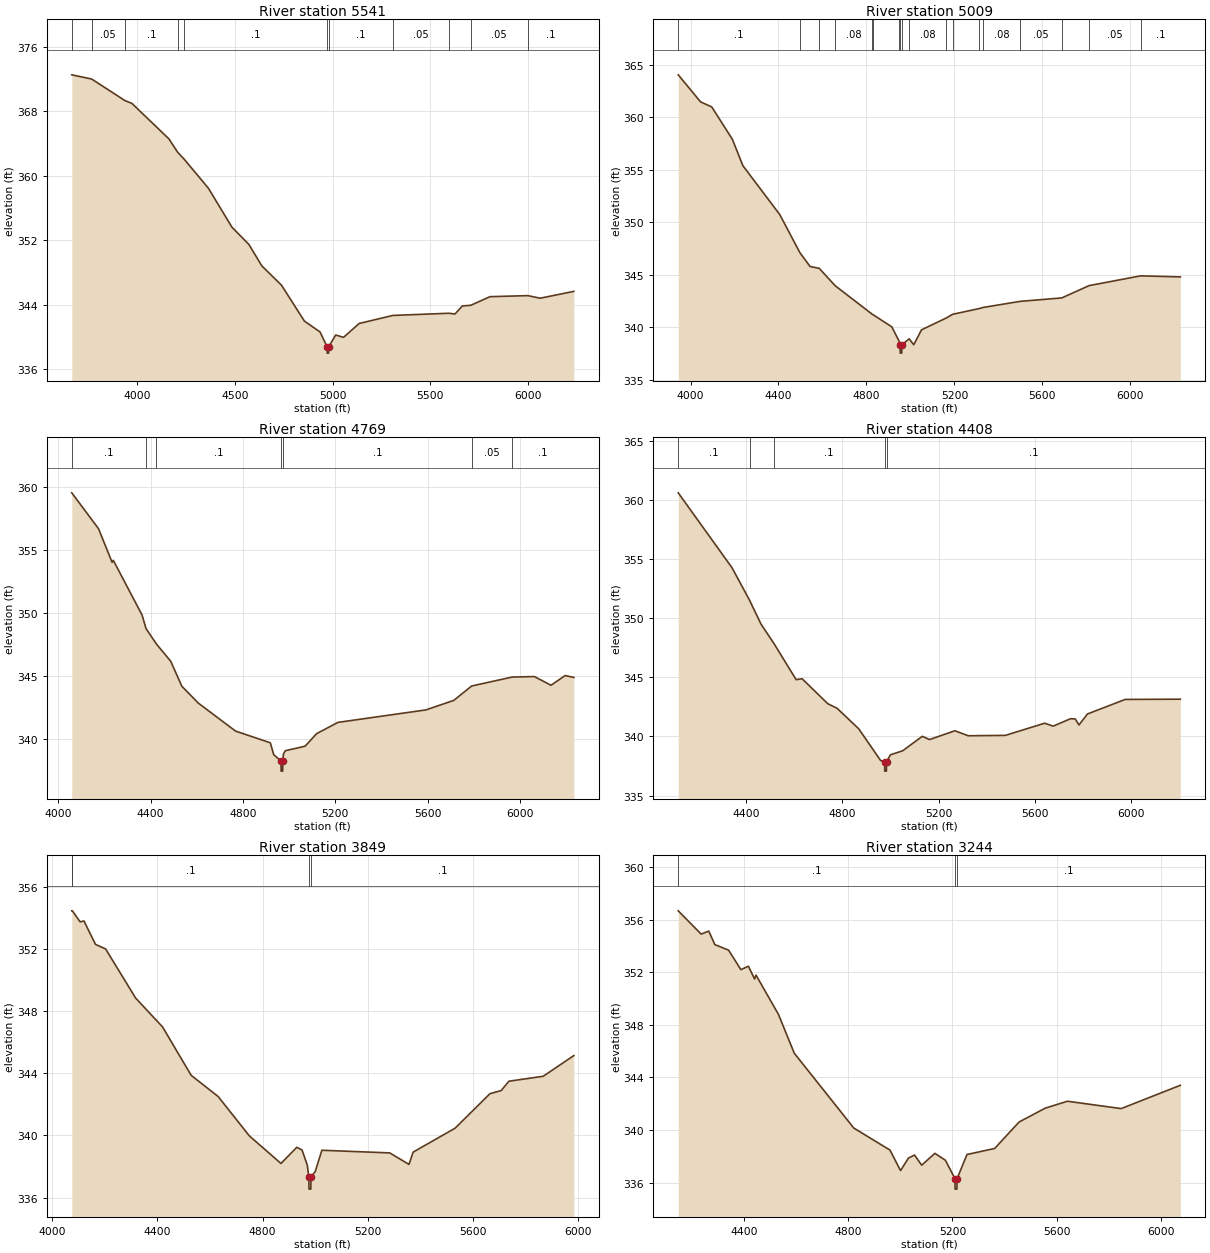
Type RM Length L Ch R = 1,5541,532,532,532
BEGIN DESCRIPTION:
Mapping XS ca66f67d
END DESCRIPTION:
XS GIS Cut Line= 4
      2115339.80     13432133.49      2114311.99     13431820.98
      2113416.16     13431869.59      2112853.62     13432077.94
#Sta/Elev= 30
  3663.5  372.54  3765.2  372.02  3935.9  369.34  3971.6  368.99  4160.9  364.59
  4206.6  362.90  4239.0  362.07  4363.3  358.46  4483.8  353.62  4570.9  351.47
  4636.7  348.82  4737.8  346.41  4854.9  341.96  4935.0  340.61  4971.0  338.78
  4971.7  337.98  4978.5  337.98  4979.3  338.78  5015.2  340.23  5055.2  339.94
  5135.3  341.66  5307.7  342.66  5593.6  342.93  5626.1  342.84  5663.8  343.84
  5707.1  343.92  5805.1  344.99  5998.9  345.12  6062.7  344.80  6234.8  345.65
#Mann=11,-1,0
  3663.5     0.1       0  3765.2    0.05       0  3935.9     0.1       0
  4206.6    0.05       0  4239.0     0.1       0  4971.0    0.07       0
  4979.3     0.1       0  5307.7    0.05       0  5593.6     0.1       0
  5707.1    0.05       0  5998.9     0.1       0
Bank Sta=4971,4979.3
Exp/Cntr=0.3,0.1

Type RM Length L Ch R = 1,5009,240,240,240
BEGIN DESCRIPTION:
Mapping XS 5a9cdb41
END DESCRIPTION:
XS GIS Cut Line= 4
      2114805.02     13431084.87      2114249.49     13430980.71
      2113631.43     13431786.26      2112943.98     13431932.08
#Sta/Elev= 30
  3944.1  364.06  4045.9  361.48  4096.7  361.00  4190.5  357.91  4238.0  355.41
  4405.8  350.75  4497.7  347.11  4543.8  345.80  4585.1  345.63  4657.9  343.97
  4826.0  341.26  4828.0  341.24  4915.5  340.05  4949.5  338.65  4953.0  338.35
  4953.7  337.55  4960.6  337.55  4961.3  338.35  4994.2  338.91  5015.2  338.35
  5050.5  339.77  5162.4  340.89  5192.4  341.25  5313.9  341.80  5330.5  341.90
  5498.7  342.48  5688.7  342.81  5812.4  343.98  6046.6  344.91  6227.4  344.81
#Mann=18,-1,0
  3944.1     0.1       0  4497.7    0.08       0  4585.1     0.1       0
  4657.9    0.08       0  4826.0     0.1       0  4828.0    0.08       0
  4949.5     0.1       0  4953.0    0.07       0  4961.3     0.1       0
  4994.2    0.08       0  5162.4    0.05       0  5192.4    0.08       0
  5313.9     0.1       0  5330.5    0.08       0  5498.7    0.05       0
  5688.7     0.1       0  5812.4    0.05       0  6046.6     0.1       0
Bank Sta=4953,4961.3
Exp/Cntr=0.3,0.1

Type RM Length L Ch R = 1,4769,361,361,361
BEGIN DESCRIPTION:
Mapping XS cac4505f
END DESCRIPTION:
XS GIS Cut Line= 4
      2114617.51     13431022.36      2114055.05     13430883.48
      2113409.21     13431765.43      2112918.05     13431862.28
#Sta/Elev= 30
  4059.1  359.54  4175.0  356.69  4233.7  354.02  4238.9  354.18  4363.3  349.84
  4380.6  348.76  4424.9  347.55  4487.6  346.16  4535.5  344.18  4606.9  342.84
  4768.0  340.62  4918.5  339.69  4933.2  338.75  4964.5  338.24  4965.2  337.44
  4972.1  337.44  4972.8  338.24  4975.0  338.78  4983.3  339.06  5069.0  339.42
  5119.2  340.42  5211.1  341.31  5591.7  342.30  5712.9  343.06  5789.8  344.20
  5965.4  344.91  6061.2  344.95  6133.4  344.26  6194.5  345.03  6232.2  344.88
#Mann=7,-1,0
  4059.1     0.1       0  4380.6    0.08       0  4424.9     0.1       0
  4964.5    0.07       0  4972.8     0.1       0  5789.8    0.05       0
  5965.4     0.1       0
Bank Sta=4964.5,4972.8
Exp/Cntr=0.3,0.1

Type RM Length L Ch R = 1,4408,559,559,559
BEGIN DESCRIPTION:
Mapping XS 6a3e2396
END DESCRIPTION:
XS GIS Cut Line= 4
      2114645.37     13431001.55      2113943.93     13430800.15
      2113207.82     13430925.15      2112825.86     13431397.39
#Sta/Elev= 30
  4119.8  360.58  4343.3  354.24  4415.6  351.51  4463.5  349.48  4516.9  347.85
  4609.2  344.79  4633.9  344.87  4740.3  342.76  4779.2  342.37  4868.8  340.64
  4960.1  337.95  4976.2  337.86  4976.9  337.06  4983.8  337.06  4984.6  337.86
  5000.6  338.44  5051.4  338.78  5132.5  340.00  5162.9  339.73  5268.1  340.47
  5323.3  340.05  5477.4  340.08  5640.8  341.11  5675.9  340.86  5747.9  341.49
  5767.7  341.47  5783.0  340.96  5818.2  341.89  5974.9  343.12  6203.6  343.14
#Mann=5,-1,0
  4119.8     0.1       0  4415.6    0.08       0  4516.9     0.1       0
  4976.2    0.07       0  4984.6     0.1       0
Bank Sta=4976.2,4984.6
Exp/Cntr=0.3,0.1

Type RM Length L Ch R = 1,3849,605,605,605
BEGIN DESCRIPTION:
Mapping XS f074aa21
END DESCRIPTION:
XS GIS Cut Line= 4
      2114436.95     13430654.30      2113916.16     13430411.26
      2113450.88     13430397.37      2112702.43     13430840.90
#Sta/Elev= 30
  4074.1  354.45  4076.4  354.45  4105.9  353.74  4120.4  353.80  4164.5  352.29
  4202.8  352.00  4317.1  348.84  4419.6  346.98  4528.4  343.87  4630.8  342.51
  4750.0  339.97  4870.1  338.20  4930.1  339.24  4950.1  339.07  4970.1  338.10
  4975.9  337.35  4976.7  336.55  4983.6  336.55  4984.3  337.35  5000.1  337.67
  5025.7  339.05  5283.9  338.88  5357.1  338.14  5372.8  338.93  5532.6  340.47
  5665.2  342.69  5708.0  342.89  5737.2  343.49  5867.9  343.81  5984.3  345.14
#Mann=4,-1,0
  4074.1    0.05       0  4076.4     0.1       0  4975.9    0.07       0
  4984.3     0.1       0
Bank Sta=4975.9,4984.3
Exp/Cntr=0.3,0.1

Type RM Length L Ch R = 1,3244,376,376,376
BEGIN DESCRIPTION:
Mapping XS 1b371275
END DESCRIPTION:
XS GIS Cut Line= 4
      2114457.86     13430196.00      2113811.99     13429918.21
      2113423.10     13429980.71      2112763.81     13430480.38
#Sta/Elev= 30
  4149.0  356.66  4236.9  354.89  4265.9  355.12  4289.5  354.09  4342.0  353.67
  4389.1  352.19  4418.0  352.45  4441.6  351.48  4447.0  351.78  4533.1  348.79
  4593.7  345.84  4821.9  340.15  4960.4  338.48  5001.0  336.92  5031.3  337.87
  5054.6  338.10  5082.0  337.33  5132.6  338.23  5173.1  337.70  5209.4  336.31
  5210.2  335.51  5217.1  335.51  5217.8  336.31  5255.6  338.14  5361.7  338.60
  5455.3  340.61  5555.2  341.66  5640.5  342.19  5846.5  341.63  6073.2  343.40
#Mann=3,-1,0
  4149.0     0.1       0  5209.4    0.07       0  5217.8     0.1       0
Bank Sta=5209.4,5217.8
Exp/Cntr=0.3,0.1

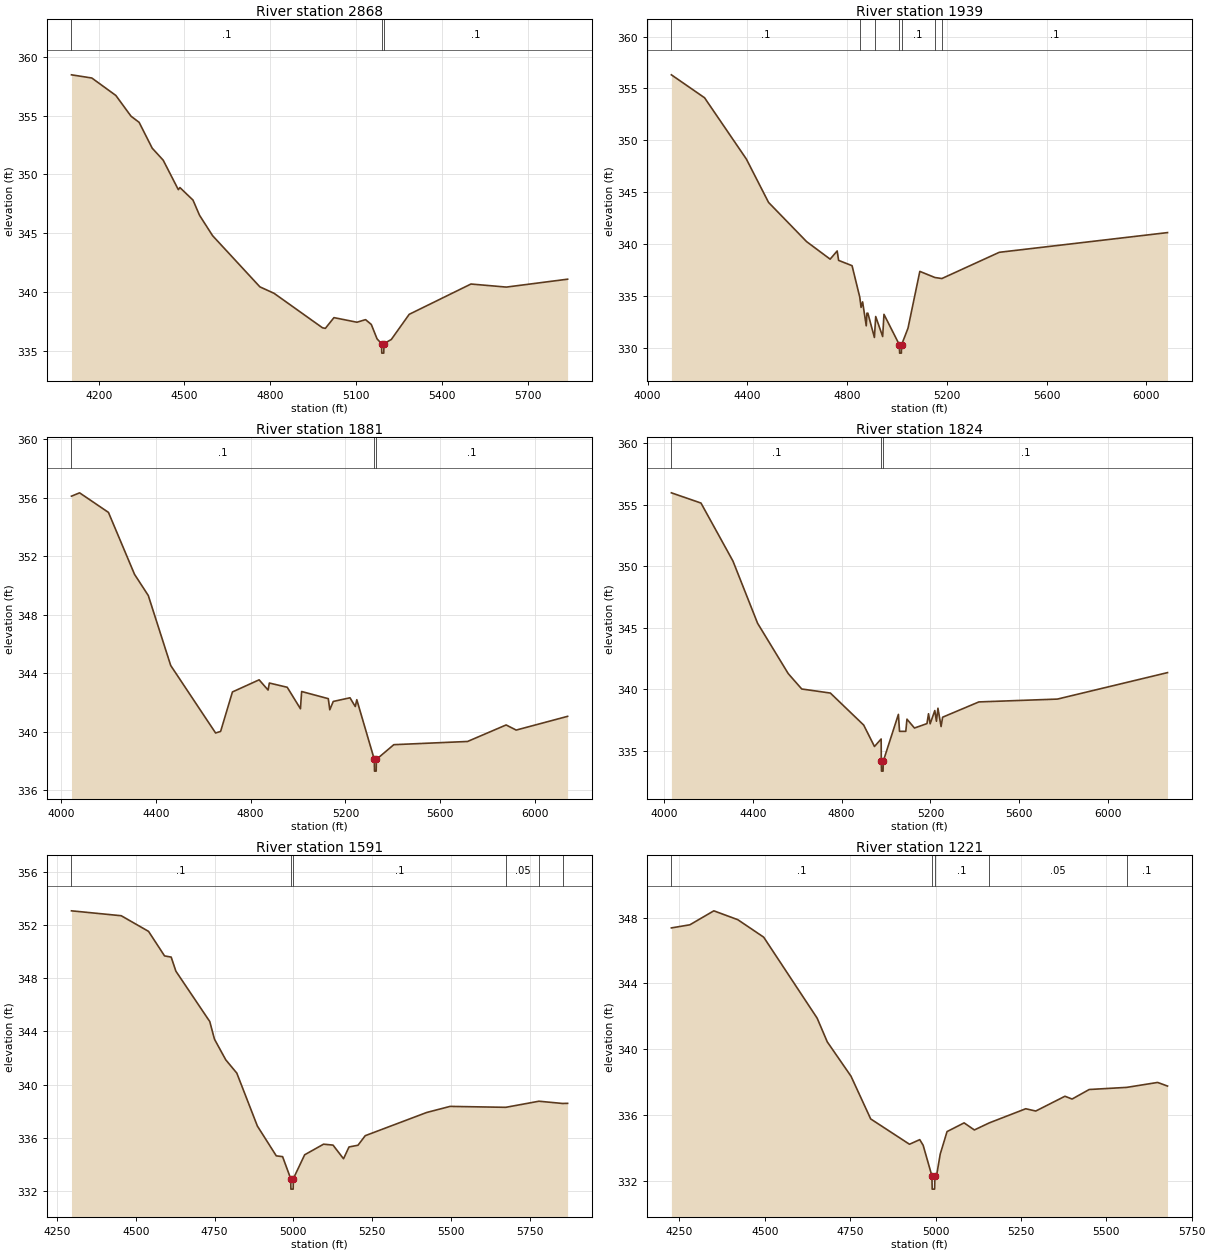
Type RM Length L Ch R = 1,2868,929,929,929
BEGIN DESCRIPTION:
Mapping XS d3dbf5f3
END DESCRIPTION:
XS GIS Cut Line= 4
      2114485.63     13429869.61      2113846.71     13429570.98
      2113402.27     13429612.65      2112909.63     13429924.88
#Sta/Elev= 30
  4104.8  358.45  4176.0  358.18  4260.0  356.70  4313.1  354.94  4341.4  354.42
  4387.1  352.23  4425.6  351.21  4478.5  348.71  4484.0  348.89  4529.7  347.83
  4552.6  346.54  4598.3  344.81  4763.7  340.47  4813.4  339.92  4982.5  337.00
  4992.6  336.95  5022.7  337.86  5103.1  337.47  5133.2  337.69  5153.3  337.28
  5173.4  336.06  5189.2  335.65  5189.9  334.85  5196.9  334.85  5197.6  335.65
  5223.3  336.01  5285.8  338.14  5501.8  340.71  5625.6  340.45  5839.7  341.12
#Mann=3,-1,0
  4104.8     0.1       0  5189.2    0.07       0  5197.6     0.1       0
Bank Sta=5189.2,5197.6
Exp/Cntr=0.3,0.1

Type RM Length L Ch R = 1,1939,58,58,58
BEGIN DESCRIPTION:
Mapping XS 96e19df7
END DESCRIPTION:
XS GIS Cut Line= 6
      2114407.65     13429426.98      2113862.53     13429090.19
      2113817.39     13429010.33      2113775.72     13428979.08
      2113574.34     13428954.77      2112845.14     13429638.83
#Sta/Elev= 30
  4095.7  356.31  4228.6  354.10  4396.5  348.18  4485.2  344.01  4637.7  340.23
  4732.1  338.54  4760.3  339.33  4766.1  338.42  4820.0  337.91  4850.8  334.89
  4856.1  333.89  4862.3  334.42  4876.9  332.11  4879.6  333.33  4883.4  333.33
  4909.6  330.99  4912.8  332.23  4914.8  333.01  4942.7  331.08  4947.9  333.22
  5009.8  330.28  5010.6  329.48  5017.7  329.48  5018.5  330.28  5044.2  331.88
  5091.7  337.36  5152.1  336.77  5180.0  336.67  5410.2  339.20  6084.7  341.10
#Mann=7,-1,0
  4095.7     0.1       0  4850.8    0.05       0  4912.8     0.1       0
  5009.8    0.07       0  5018.5     0.1       0  5152.1    0.05       0
  5180.0     0.1       0
Bank Sta=5009.8,5018.5
Exp/Cntr=0.3,0.1

Type RM Length L Ch R = 1,1881,57,57,57
BEGIN DESCRIPTION:
Mapping XS 0bcbcb15
END DESCRIPTION:
XS GIS Cut Line= 6
      2114456.31     13429409.65      2113904.20     13429069.36
      2113817.39     13428937.41      2113584.75     13428895.74
      2113421.56     13429024.22      2112831.29     13429617.95
#Sta/Elev= 30
  4044.6  356.11  4078.8  356.34  4200.6  355.00  4310.6  350.76  4368.6  349.31
  4463.2  344.52  4652.5  339.90  4673.7  340.01  4723.5  342.71  4836.1  343.54
  4873.8  342.84  4879.2  343.32  4954.6  343.03  5010.3  341.56  5015.4  342.74
  5127.8  342.25  5134.1  341.49  5148.7  342.06  5219.3  342.31  5241.6  341.71
  5248.0  342.18  5321.9  338.09  5322.7  337.29  5329.8  337.29  5330.6  338.09
  5404.1  339.10  5715.2  339.32  5877.8  340.45  5920.3  340.10  6137.1  341.04
#Mann=3,-1,0
  4044.6     0.1       0  5321.9    0.07       0  5330.6     0.1       0
Bank Sta=5321.9,5330.6
Exp/Cntr=0.3,0.1

Type RM Length L Ch R = 1,1824,233,233,233
BEGIN DESCRIPTION:
Mapping XS 1f0a4a9f
END DESCRIPTION:
XS GIS Cut Line= 6
      2114449.29     13429371.41      2113945.86     13429069.36
      2113931.97     13428986.02      2113855.59     13428888.80
      2113612.53     13428836.72      2112754.93     13429645.71
#Sta/Elev= 30
  4034.2  355.95  4167.3  355.12  4311.2  350.41  4422.0  345.36  4559.9  341.27
  4620.7  340.02  4749.5  339.69  4899.5  337.09  4948.0  335.35  4978.1  335.96
  4978.8  334.15  4979.6  333.35  4986.7  333.35  4987.5  334.15  5055.7  337.96
  5060.8  336.58  5089.0  336.58  5094.2  337.57  5128.0  336.85  5184.3  337.21
  5191.2  338.01  5198.5  337.19  5219.5  338.27  5226.8  337.40  5233.6  338.46
  5247.8  336.97  5254.7  337.73  5417.8  338.97  5771.2  339.20  6266.7  341.35
#Mann=3,-1,0
  4034.2     0.1       0  4978.8    0.07       0  4987.5     0.1       0
Bank Sta=4978.8,4987.5
Exp/Cntr=0.3,0.1

Type RM Length L Ch R = 1,1591,370,370,370
BEGIN DESCRIPTION:
Mapping XS 248079d5
END DESCRIPTION:
XS GIS Cut Line= 4
      2114372.57     13428937.76      2113940.25     13428640.86
      2113601.70     13428640.86      2112955.86     13428937.74
#Sta/Elev= 30
  4296.1  353.10  4454.0  352.73  4540.6  351.55  4591.4  349.70  4612.4  349.61
  4627.3  348.55  4734.8  344.75  4749.7  343.42  4785.6  341.86  4820.6  340.86
  4885.8  336.87  4945.8  334.62  4965.8  334.56  4991.4  332.91  4992.2  332.11
  4999.3  332.11  5000.1  332.91  5035.8  334.70  5095.8  335.50  5125.8  335.43
  5159.1  334.40  5176.5  335.29  5205.0  335.42  5227.9  336.14  5422.8  337.89
  5497.2  338.35  5673.8  338.28  5779.1  338.74  5854.2  338.57  5869.9  338.58
#Mann=6,-1,0
  4296.1     0.1       0  4991.4    0.07       0  5000.1     0.1       0
  5673.8    0.05       0  5779.1     0.1       0  5854.2    0.05       0
Bank Sta=4991.4,5000.1
Exp/Cntr=0.3,0.1

Type RM Length L Ch R = 1,1221,255,255,255
BEGIN DESCRIPTION:
Mapping XS 3ae4be25
END DESCRIPTION:
XS GIS Cut Line= 4
      2114393.33     13428620.01      2113856.91     13428385.65
      2113487.12     13428390.86      2113190.95     13428790.96
#Sta/Elev= 30
  4226.3  347.38  4280.4  347.57  4350.6  348.42  4420.8  347.88  4496.5  346.82
  4653.2  341.89  4682.8  340.45  4752.3  338.36  4810.0  335.76  4923.6  334.22
  4953.6  334.50  4963.6  334.16  4989.3  332.29  4990.1  331.49  4997.2  331.49
  4998.0  332.29  5003.6  332.40  5013.6  333.62  5033.6  334.99  5083.6  335.52
  5113.6  335.09  5157.3  335.52  5264.1  336.38  5293.4  336.24  5378.9  337.14
  5399.8  336.97  5449.9  337.55  5559.9  337.68  5650.3  337.98  5679.3  337.76
#Mann=5,-1,0
  4226.3     0.1       0  4989.3    0.07       0  4998.0     0.1       0
  5157.3    0.05       0  5559.9     0.1       0
Bank Sta=4989.3,4998
Exp/Cntr=0.3,0.1

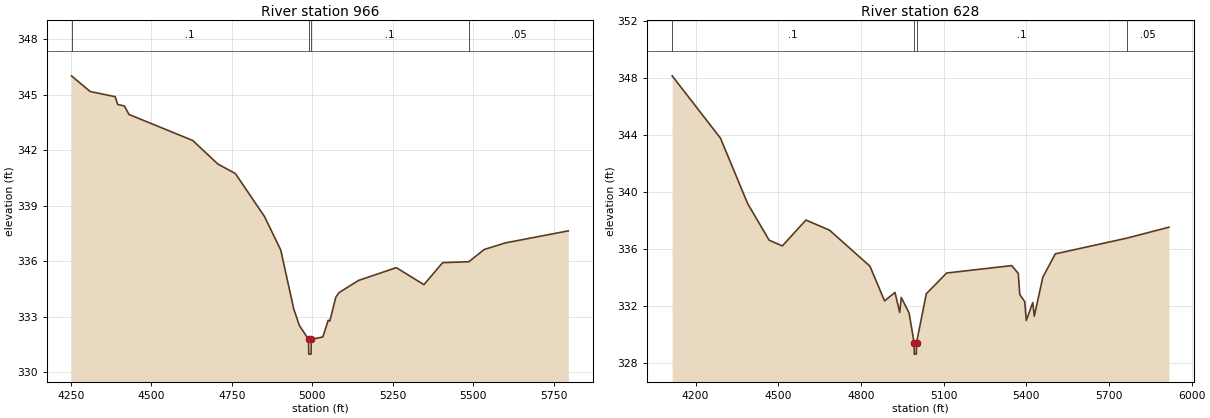
Type RM Length L Ch R = 1,966,338,338,338
BEGIN DESCRIPTION:
Mapping XS 32cf4699
END DESCRIPTION:
XS GIS Cut Line= 4
      2114348.65     13428503.39      2114022.25     13428135.33
      2113563.92     13428187.41      2113234.03     13428677.03
#Sta/Elev= 30
  4251.8  346.03  4309.9  345.18  4387.7  344.90  4395.2  344.48  4416.1  344.40
  4430.4  343.94  4628.6  342.53  4706.3  341.26  4761.1  340.74  4851.7  338.41
  4902.0  336.60  4942.3  333.42  4959.8  332.52  4988.2  331.77  4989.0  330.97
  4996.1  330.97  4996.9  331.77  5032.8  331.90  5049.4  332.80  5054.4  332.76
  5073.1  334.05  5083.2  334.30  5144.0  334.96  5261.0  335.65  5346.8  334.73
  5405.0  335.92  5486.5  335.97  5533.9  336.63  5599.9  336.99  5795.4  337.64
#Mann=4,-1,0
  4251.8     0.1       0  4988.2    0.07       0  4996.9     0.1       0
  5486.5    0.05       0
Bank Sta=4988.2,4996.9
Exp/Cntr=0.3,0.1

Type RM Length L Ch R = 1,628,0,0,0
BEGIN DESCRIPTION:
Mapping XS baee5af2
END DESCRIPTION:
XS GIS Cut Line= 4
      2114511.88     13427979.09      2113817.39     13427819.36
      2113494.47     13427972.13      2113206.29     13428645.72
#Sta/Elev= 30
  4115.1  348.13  4290.5  343.76  4388.9  339.19  4466.9  336.62  4514.9  336.22
  4600.5  338.03  4686.2  337.32  4832.6  334.80  4885.7  332.37  4923.6  332.96
  4940.8  331.56  4946.3  332.61  4974.6  331.53  4993.0  329.44  4993.8  328.64
  5000.9  328.64  5001.7  329.44  5037.3  332.87  5111.1  334.32  5347.3  334.84
  5370.9  334.29  5376.3  332.82  5394.5  332.31  5399.9  331.00  5423.5  332.25
  5429.0  331.30  5460.0  334.03  5505.2  335.66  5766.6  336.77  5917.6  337.53
#Mann=4,-1,0
  4115.1     0.1       0  4993.0    0.07       0  5001.7     0.1       0
  5766.6    0.05       0
Bank Sta=4993,5001.7
Exp/Cntr=0.3,0.1

Chan Stop Cuts=-1