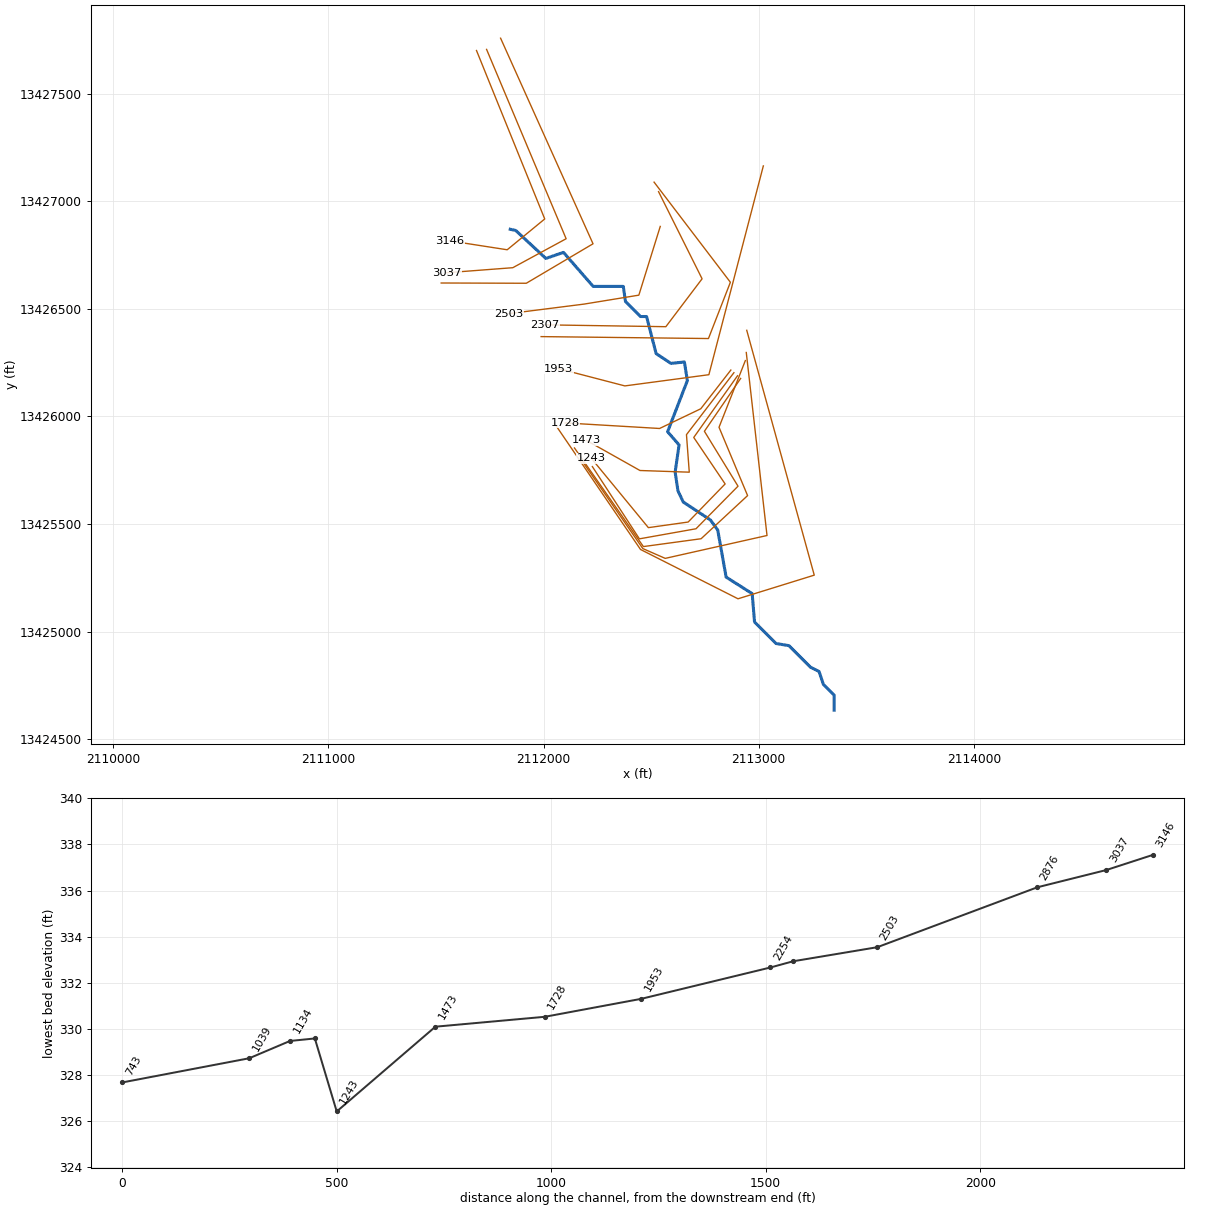
--- UNT 028 in La Jarita Watershed.prj (project) ---

Proj Title=UNT 028 in La Jarita Watershed Base Level Engineering
Current Plan=p01
Default Exp/Contr=0.3,0.1
English Units
Geom File=g01
Flow File=f01
Plan File=p01
BEGIN DESCRIPTION:
UNT 028 in La Jarita Watershed
END DESCRIPTION:

--- UNT 028 in La Jarita Watershed.p01 (plan) ---

Plan Title=Multiple Run
Short Identifier=Multiple
Geom File=g01
Flow File=f01
Subcritical Flow
K Sum by GR= 0
Std Step Tol= 0.01
Critical Tol= 0.01
Num of Std Step Trials= 20
Max Error Tol= 0.3
Flow Tol Ratio= 0.001
Split Flow NTrial= 30
Split Flow Tol= 0.02
Split Flow Ratio= 0.02
Log Output Level= 0
Friction Slope Method= 1
Unsteady Friction Slope Method= 2
Unsteady Bridges Friction Slope Method= 1
Parabolic Critical Depth
Global Vel Dist=  1 , 1 , 1
Global Log Level= 0
CheckData=True
Encroach Param= -1, 0, 0, 0
BEGIN DESCRIPTION:
Multiple Run
END DESCRIPTION:

--- UNT 028 in La Jarita Watershed.f01 (steady flow) ---

Flow Title=Multiple
Number of Profiles=7
Profile Names=10-year,25-year,50-year,1pct_min,100-year,1pct_plu,500-year
River Rch & RM= UNT 028 in La Ja,Reach-1,3146
      74      95     110      64     128     256     175
River Rch & RM= UNT 028 in La Ja,Reach-1,1192
     108     141     167      98     196     392     277
Boundary for River Rch & Prof#=UNT 028 in La Ja,Reach-1,1
Up Type=0
Dn Type=3
Dn Slope=0.005
Boundary for River Rch & Prof#=UNT 028 in La Ja,Reach-1,2
Up Type=0
Dn Type=3
Dn Slope=0.005
Boundary for River Rch & Prof#=UNT 028 in La Ja,Reach-1,3
Up Type=0
Dn Type=3
Dn Slope=0.005
Boundary for River Rch & Prof#=UNT 028 in La Ja,Reach-1,4
Up Type=0
Dn Type=3
Dn Slope=0.005
Boundary for River Rch & Prof#=UNT 028 in La Ja,Reach-1,5
Up Type=0
Dn Type=3
Dn Slope=0.005
Boundary for River Rch & Prof#=UNT 028 in La Ja,Reach-1,6
Up Type=0
Dn Type=3
Dn Slope=0.005
Boundary for River Rch & Prof#=UNT 028 in La Ja,Reach-1,7
Up Type=0
Dn Type=3
Dn Slope=0.005

--- UNT 028 in La Jarita Watershed.g01 (geometry) ---

Geom Title=Existing Conditions

River Reach=UNT 028 in La Ja,Reach-1
Reach XY= 30
      2111845.17     13426870.17      2111870.80     13426864.54
      2112010.80     13426734.54      2112092.60     13426762.64
      2112230.80     13426604.54      2112370.80     13426604.54
      2112380.80     13426534.54      2112450.80     13426464.54
      2112478.99     13426464.54      2112523.26     13426292.25
      2112592.27     13426246.68      2112654.77     13426253.19
      2112668.59     13426166.75      2112576.65     13425928.97
      2112630.03     13425867.77      2112611.80     13425741.47
      2112624.82     13425654.23      2112649.56     13425602.15
      2112775.87     13425518.82      2112809.72     13425471.94
      2112848.78     13425253.19      2112969.88     13425176.37
      2112980.80     13425044.54      2113080.80     13424944.54
      2113140.80     13424934.54      2113240.80     13424834.54
      2113280.80     13424814.54      2113300.80     13424754.54
      2113350.80     13424704.54      2113350.80     13424634.54

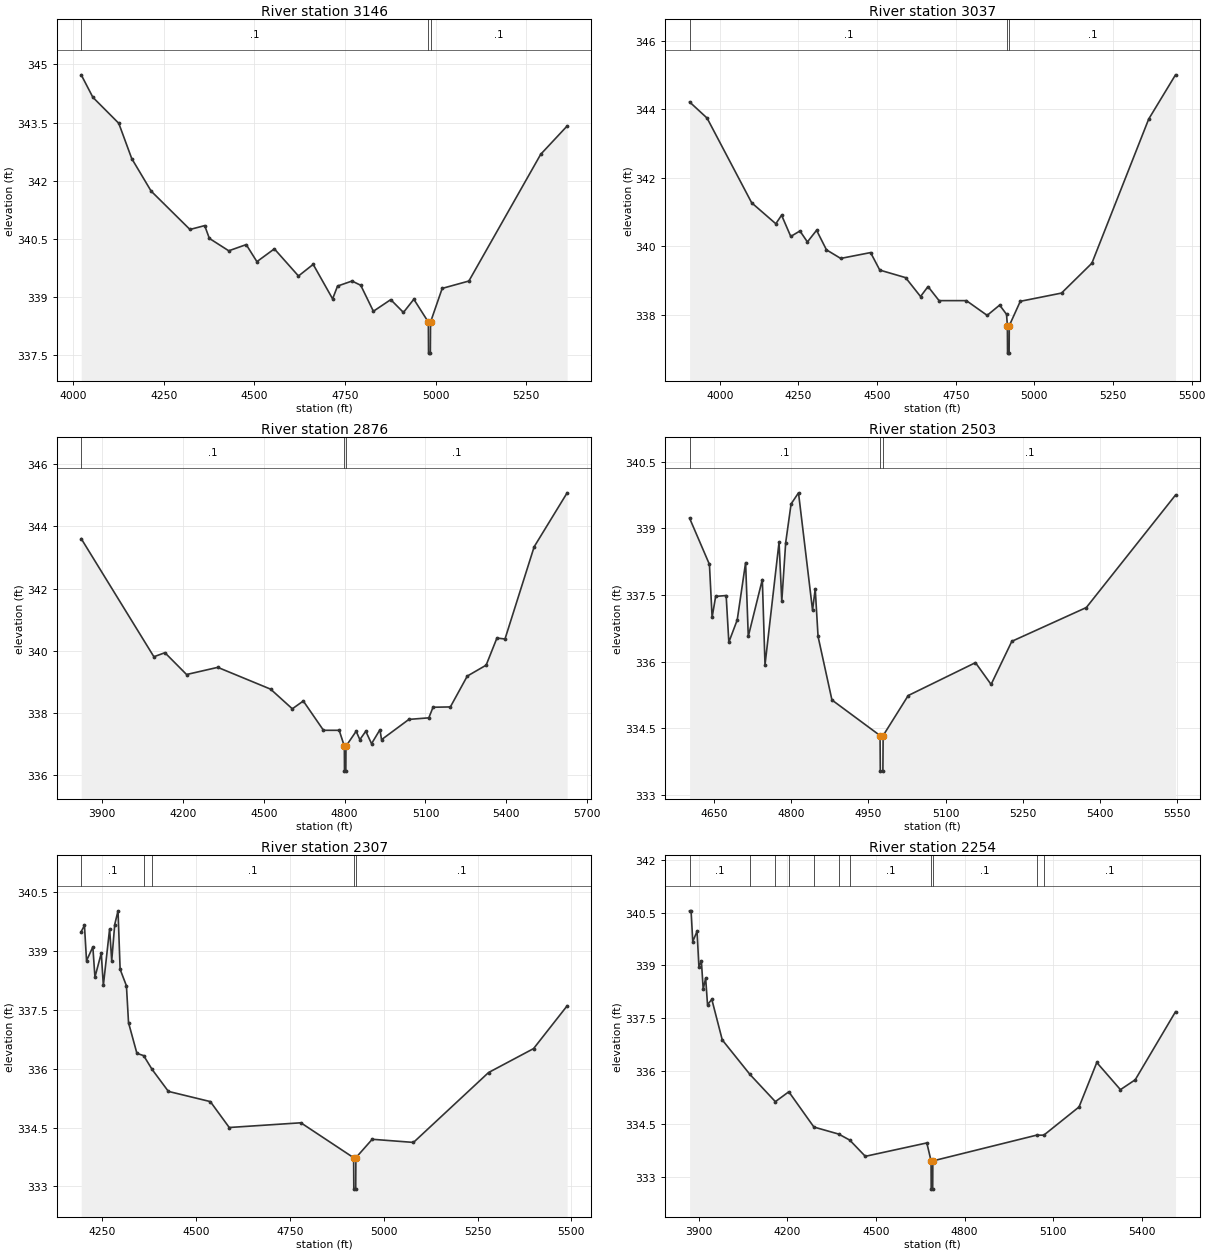
Type RM Length L Ch R = 1,3146,109,109,109
BEGIN DESCRIPTION:
Mapping XS 5beef419
END DESCRIPTION:
XS GIS Cut Line= 4
      2111688.38     13427701.08      2112005.57     13426918.06
      2111831.09     13426774.83      2111562.87     13426816.50
#Sta/Elev= 30
  4021.5  344.73  4053.7  344.15  4125.2  343.48  4161.0  342.57  4214.6  341.73
  4321.8  340.74  4362.5  340.84  4375.4  340.51  4429.0  340.19  4477.2  340.35
  4506.7  339.91  4554.9  340.24  4621.5  339.54  4662.1  339.84  4715.8  338.95
  4729.4  339.28  4769.4  339.41  4793.5  339.30  4828.4  338.63  4876.3  338.93
  4911.4  338.60  4940.1  338.94  4980.2  338.35  4980.7  337.55  4985.7  337.55
  4986.2  338.35  5018.4  339.22  5092.1  339.41  5290.5  342.68  5363.5  343.41
#Mann=3,-1,0
  4021.5     0.1       0  4980.2    0.07       0  4986.2     0.1       0
Bank Sta=4980.2,4986.2
Exp/Cntr=0.3,0.1

Type RM Length L Ch R = 1,3037,161,161,161
BEGIN DESCRIPTION:
Mapping XS a0a8d9e9
END DESCRIPTION:
XS GIS Cut Line= 4
      2111735.27     13427706.27      2112105.05     13426826.09
      2111857.13     13426691.50      2111549.92     13426668.07
#Sta/Elev= 30
  3903.8  344.21  3959.4  343.74  4101.3  341.27  4178.0  340.66  4196.3  340.91
  4225.5  340.29  4254.7  340.45  4278.4  340.13  4307.6  340.47  4339.0  339.90
  4384.3  339.65  4479.3  339.82  4508.5  339.31  4590.6  339.09  4638.1  338.54
  4661.9  338.83  4697.0  338.42  4783.8  338.42  4849.9  337.99  4889.6  338.29
  4911.5  338.02  4914.2  337.69  4914.7  336.89  4919.7  336.89  4920.2  337.69
  4955.2  338.40  5086.3  338.64  5182.8  339.51  5363.4  343.71  5448.7  345.00
#Mann=3,-1,0
  3903.8     0.1       0  4914.2    0.07       0  4920.2     0.1       0
Bank Sta=4914.2,4920.2
Exp/Cntr=0.3,0.1

Type RM Length L Ch R = 1,2876,373,373,373
BEGIN DESCRIPTION:
Mapping XS c33c6b82
END DESCRIPTION:
XS GIS Cut Line= 4
      2111800.37     13427758.36      2112230.05     13426802.65
      2111919.80     13426619.16      2111524.30     13426620.36
#Sta/Elev= 30
  3822.2  343.60  4092.0  339.81  4132.9  339.94  4213.3  339.24  4329.1  339.47
  4525.3  338.77  4605.8  338.14  4646.6  338.39  4721.5  337.45  4779.8  337.45
  4799.0  336.94  4799.5  336.14  4804.5  336.14  4805.0  336.94  4842.8  337.42
  4856.5  337.15  4878.5  337.42  4899.9  337.02  4931.2  337.47  4937.0  337.15
  5038.6  337.80  5112.5  337.85  5128.2  338.19  5192.5  338.20  5255.3  339.19
  5325.3  339.54  5365.3  340.41  5395.3  340.38  5503.6  343.34  5626.0  345.07
#Mann=3,-1,0
  3822.2     0.1       0  4799.0    0.07       0  4805.0     0.1       0
Bank Sta=4799,4805
Exp/Cntr=0.3,0.1

Type RM Length L Ch R = 1,2503,196,196,196
BEGIN DESCRIPTION:
Mapping XS 12f624f2
END DESCRIPTION:
XS GIS Cut Line= 4
      2112542.54     13426883.37      2112443.07     13426563.89
      2112187.86     13426522.23      2111839.45     13426478.03
#Sta/Elev= 30
  4602.3  339.23  4640.9  338.19  4646.1  337.00  4653.0  337.47  4673.4  337.49
  4678.6  336.44  4694.9  336.94  4711.2  338.23  4716.4  336.57  4743.7  337.85
  4748.9  335.93  4776.2  338.69  4781.5  337.36  4789.1  338.68  4799.6  339.55
  4814.0  339.80  4841.3  337.16  4846.5  337.64  4852.0  336.57  4879.0  335.14
  4972.5  334.34  4973.0  333.54  4978.0  333.54  4978.5  334.34  5027.2  335.24
  5157.9  335.98  5188.3  335.49  5228.6  336.46  5373.4  337.22  5546.7  339.75
#Mann=3,-1,0
  4602.3     0.1       0  4972.5    0.07       0  4978.5     0.1       0
Bank Sta=4972.5,4978.5
Exp/Cntr=0.3,0.1

Type RM Length L Ch R = 1,2307,53,53,53
BEGIN DESCRIPTION:
Mapping XS 28f019a6
END DESCRIPTION:
XS GIS Cut Line= 4
      2112534.72     13427044.87      2112737.01     13426639.86
      2112568.59     13426417.24      2112005.54     13426425.87
#Sta/Elev= 30
  4193.9  339.49  4202.5  339.65  4208.1  338.75  4224.9  339.10  4230.5  338.33
  4247.3  338.94  4252.9  338.12  4269.6  339.56  4275.2  338.75  4283.2  339.67
  4292.0  340.02  4297.6  338.53  4314.4  338.11  4320.0  337.17  4342.3  336.39
  4360.4  336.33  4382.8  335.98  4426.2  335.42  4538.0  335.16  4588.4  334.50
  4779.3  334.62  4919.9  333.73  4920.4  332.93  4925.4  332.93  4925.9  333.73
  4969.4  334.20  5079.4  334.12  5279.4  335.90  5399.4  336.51  5488.9  337.60
#Mann=5,-1,0
  4193.9     0.1       0  4360.4    0.08       0  4382.8     0.1       0
  4919.9    0.07       0  4925.9     0.1       0
Bank Sta=4919.9,4925.9
Exp/Cntr=0.3,0.1

Type RM Length L Ch R = 1,2254,301,301,301
BEGIN DESCRIPTION:
Mapping XS e7a02bb6
END DESCRIPTION:
XS GIS Cut Line= 4
      2112513.88     13427089.14      2112868.55     13426623.79
      2112766.60     13426362.20      2111988.70     13426371.17
#Sta/Elev= 30
  3869.4  340.55  3874.5  340.55  3880.2  339.68  3894.7  339.97  3901.0  338.96
  3909.3  339.13  3915.5  338.33  3923.8  338.64  3930.1  337.89  3944.6  338.04
  3980.0  336.89  4073.8  335.91  4159.6  335.14  4205.1  335.42  4290.0  334.42
  4374.1  334.22  4411.2  334.05  4463.9  333.59  4672.0  333.97  4686.3  333.46
  4686.8  332.66  4691.8  332.66  4692.3  333.46  5043.3  334.19  5067.7  334.19
  5186.9  334.99  5246.9  336.25  5326.9  335.48  5376.9  335.76  5513.2  337.69
#Mann=11,-1,0
  3869.4     0.1       0  4073.8    0.08       0  4159.6     0.1       0
  4205.1    0.08       0  4290.0     0.1       0  4374.1    0.08       0
  4411.2     0.1       0  4686.3    0.07       0  4692.3     0.1       0
  5043.3    0.05       0  5067.7     0.1       0
Bank Sta=4686.3,4692.3
Exp/Cntr=0.3,0.1

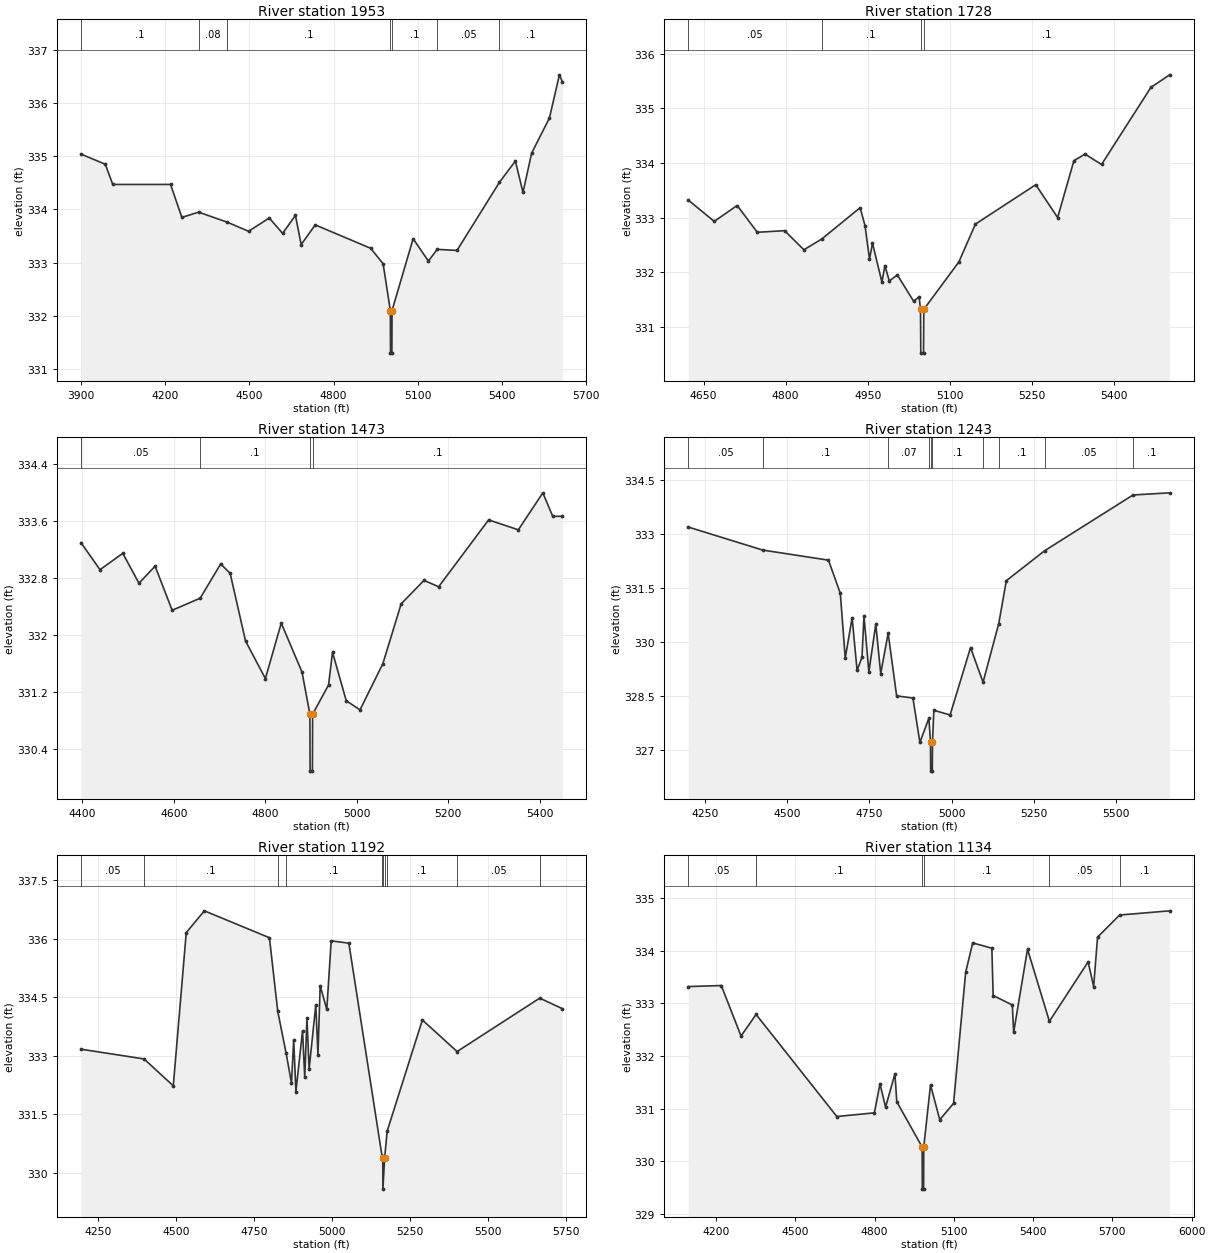
Type RM Length L Ch R = 1,1953,225,225,225
BEGIN DESCRIPTION:
Mapping XS ca69ae26
END DESCRIPTION:
XS GIS Cut Line= 4
      2113021.70     13427164.59      2112768.59     13426194.10
      2112377.96     13426142.02      2112069.01     13426222.50
#Sta/Elev= 30
  3899.6  335.04  3986.3  334.85  4012.9  334.47  4218.9  334.47  4259.3  333.85
  4318.9  333.95  4421.4  333.76  4497.1  333.59  4570.9  333.84  4618.5  333.55
  4664.2  333.89  4684.6  333.34  4734.8  333.71  4932.5  333.27  4976.8  332.98
  5002.6  332.10  5003.1  331.30  5008.1  331.30  5008.6  332.10  5083.8  333.45
  5138.2  333.03  5169.8  333.25  5240.2  333.23  5391.5  334.51  5448.4  334.91
  5475.4  334.32  5506.4  335.06  5569.9  335.72  5605.3  336.53  5615.9  336.40
#Mann=7,-1,0
  3899.6     0.1       0  4318.9    0.08       0  4421.4     0.1       0
  5002.6    0.07       0  5008.6     0.1       0  5169.8    0.05       0
  5391.5     0.1       0
Bank Sta=5002.6,5008.6
Exp/Cntr=0.3,0.1

Type RM Length L Ch R = 1,1728,255,255,255
BEGIN DESCRIPTION:
Mapping XS 1d6e2e64
END DESCRIPTION:
XS GIS Cut Line= 4
      2112870.62     13426215.58      2112730.83     13426035.68
      2112539.42     13425944.10      2112100.90     13425970.05
#Sta/Elev= 30
  4622.0  333.32  4669.5  332.93  4711.4  333.22  4748.2  332.73  4798.0  332.76
  4833.3  332.41  4866.3  332.61  4936.0  333.18  4945.0  332.85  4953.1  332.24
  4958.6  332.53  4975.8  331.82  4981.3  332.12  4989.3  331.84  5004.0  331.95
  5033.7  331.47  5043.8  331.55  5046.3  331.32  5046.8  330.52  5051.8  330.52
  5052.3  331.32  5116.5  332.19  5146.6  332.88  5256.8  333.60  5296.8  333.00
  5326.5  334.04  5346.9  334.16  5377.0  333.97  5467.1  335.38  5501.3  335.61
#Mann=4,-1,0
  4622.0    0.05       0  4866.3     0.1       0  5046.3    0.07       0
  5052.3     0.1       0
Bank Sta=5046.3,5052.3
Exp/Cntr=0.3,0.1

Type RM Length L Ch R = 1,1473,230,230,230
BEGIN DESCRIPTION:
Mapping XS 35576975
END DESCRIPTION:
XS GIS Cut Line= 5
      2112884.95     13426203.42      2112664.42     13425915.46
      2112677.44     13425740.98      2112448.27     13425748.79
      2112199.16     13425888.92
#Sta/Elev= 30
  4396.9  333.30  4438.5  332.92  4488.3  333.15  4523.7  332.73  4559.0  332.97
  4596.3  332.35  4657.6  332.52  4702.3  333.00  4723.1  332.87  4756.7  331.92
  4800.2  331.39  4834.9  332.17  4880.4  331.48  4897.5  330.89  4898.0  330.09
  4903.0  330.09  4903.5  330.89  4938.3  331.30  4947.0  331.76  4977.0  331.08
  5007.1  330.95  5057.1  331.60  5097.1  332.44  5147.1  332.77  5179.1  332.68
  5288.4  333.62  5353.4  333.48  5407.0  334.00  5428.6  333.67  5449.7  333.67
#Mann=4,-1,0
  4396.9    0.05       0  4657.6     0.1       0  4897.5    0.07       0
  4903.5     0.1       0
Bank Sta=4897.5,4903.5
Exp/Cntr=0.3,0.1

Type RM Length L Ch R = 1,1243,51,51,51
BEGIN DESCRIPTION:
Mapping XS 871fbb42
END DESCRIPTION:
XS GIS Cut Line= 6
      2112901.72     13426189.16      2112698.27     13425902.44
      2112844.11     13425686.29      2112672.23     13425509.21
      2112487.34     13425483.16      2112221.74     13425806.05
#Sta/Elev= 30
  4199.1  333.19  4425.7  332.55  4625.6  332.27  4661.6  331.35  4676.6  329.55
  4697.6  330.67  4712.6  329.21  4727.5  329.57  4733.6  330.72  4748.5  329.17
  4769.5  330.49  4784.5  329.12  4807.1  330.24  4832.9  328.50  4882.5  328.44
  4903.6  327.21  4931.0  327.88  4935.9  327.21  4936.4  326.41  4941.4  326.41
  4941.9  327.21  4946.1  328.10  4995.5  327.97  5057.6  329.84  5095.7  328.88
  5143.5  330.51  5166.5  331.70  5282.7  332.53  5551.7  334.08  5663.0  334.14
#Mann=10,-1,0
  4199.1    0.05       0  4425.7     0.1       0  4807.1    0.07       0
  4931.0     0.1       0  4935.9    0.07       0  4941.9     0.1       0
  5095.7    0.07       0  5143.5     0.1       0  5282.7    0.05       0
  5551.7     0.1       0
Bank Sta=4935.9,4941.9
Exp/Cntr=0.3,0.1

Type RM Length L Ch R = 1,1192,58,58,58
BEGIN DESCRIPTION:
Mapping XS 5c091f59
END DESCRIPTION:
XS GIS Cut Line= 6
      2112916.25     13426176.74      2112747.75     13425931.08
      2112904.00     13425675.87      2112708.69     13425477.96
      2112445.67     13425431.08      2112226.94     13425766.99
#Sta/Elev= 30
  4195.0  333.17  4397.2  332.92  4490.9  332.23  4532.4  336.16  4590.5  336.72
  4799.1  336.03  4825.8  334.14  4852.8  333.06  4869.8  332.30  4876.9  333.41
  4884.0  332.08  4905.2  333.64  4912.3  332.45  4919.4  333.96  4926.4  332.66
  4947.7  334.31  4954.7  333.03  4961.8  334.80  4983.0  334.19  4997.1  335.95
  5053.7  335.89  5160.0  330.43  5162.4  330.38  5162.9  329.58  5168.4  330.38
  5176.6  331.07  5289.4  333.92  5400.7  333.11  5665.6  334.48  5738.2  334.21
#Mann=10,-1,0
  4195.0    0.05       0  4397.2     0.1       0  4825.8    0.07       0
  4852.8     0.1       0  5160.0    0.07       0  5162.4    0.07       0
  5168.4    0.07       0  5176.6     0.1       0  5400.7    0.05       0
  5665.6     0.1       0
Bank Sta=5162.4,5168.4
Exp/Cntr=0.3,0.1

Type RM Length L Ch R = 1,1134,95,95,95
BEGIN DESCRIPTION:
Mapping XS 66ce0e5d
END DESCRIPTION:
XS GIS Cut Line= 6
      2112938.10     13426259.75      2112815.71     13425949.83
      2112948.52     13425632.12      2112732.37     13425431.60
      2112464.14     13425395.14      2112143.81     13425853.50
#Sta/Elev= 30
  4094.4  333.32  4219.6  333.34  4294.3  332.38  4351.3  332.79  4656.9  330.85
  4799.1  330.92  4820.2  331.47  4841.5  331.03  4876.8  331.66  4883.9  331.13
  4979.9  330.27  4980.4  329.47  4985.4  329.47  4985.9  330.27  5011.5  331.45
  5046.6  330.79  5098.8  331.10  5144.5  333.59  5171.2  334.15  5243.7  334.05
  5248.7  333.15  5321.2  332.97  5326.2  332.45  5378.7  334.03  5461.5  332.66
  5608.1  333.79  5629.0  333.32  5643.8  334.26  5727.3  334.68  5916.5  334.76
#Mann=6,-1,0
  4094.4    0.05       0  4351.3     0.1       0  4979.9    0.07       0
  4985.9     0.1       0  5461.5    0.05       0  5727.3     0.1       0
Bank Sta=4979.9,4985.9
Exp/Cntr=0.3,0.1

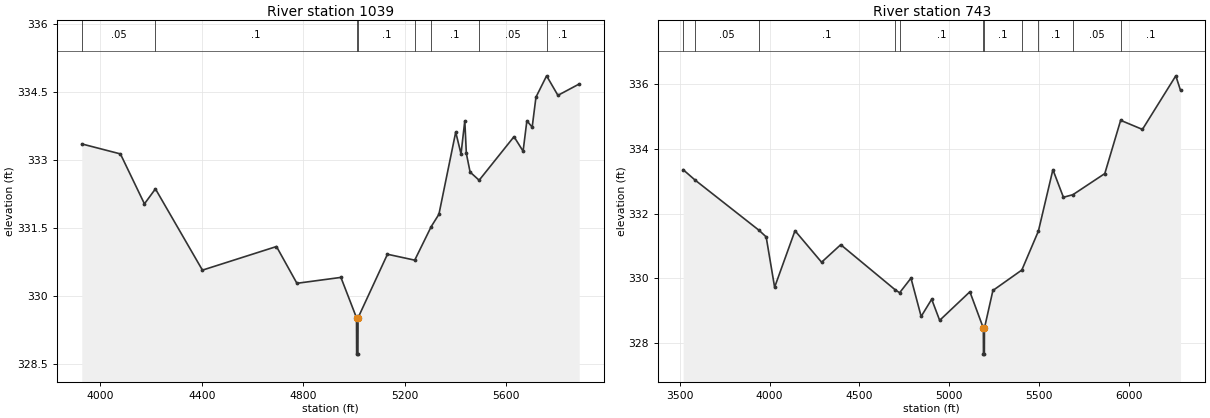
Type RM Length L Ch R = 1,1039,296,296,296
BEGIN DESCRIPTION:
Mapping XS 0209295c
END DESCRIPTION:
XS GIS Cut Line= 5
      2112942.44     13426297.36      2113038.81     13425446.64
      2112565.72     13425340.30      2112461.55     13425385.87
      2112173.79     13425801.29
#Sta/Elev= 30
  3927.5  333.35  4079.7  333.13  4174.4  332.03  4217.7  332.36  4402.9  330.57
  4694.7  331.09  4775.2  330.28  4948.6  330.41  5010.1  329.52  5010.6  328.72
  5015.6  328.72  5016.1  329.52  5132.0  330.92  5239.5  330.79  5304.5  331.53
  5334.8  331.80  5401.0  333.61  5421.9  333.13  5436.8  333.86  5442.9  333.14
  5457.7  332.73  5493.3  332.55  5630.7  333.51  5666.5  333.19  5681.4  333.86
  5702.3  333.72  5717.2  334.38  5759.1  334.85  5803.7  334.42  5887.6  334.67
#Mann=8,-1,0
  3927.5    0.05       0  4217.7     0.1       0  5010.1    0.07       0
  5016.1     0.1       0  5239.5    0.08       0  5304.5     0.1       0
  5493.3    0.05       0  5759.1     0.1       0
Bank Sta=5010.1,5016.1
Exp/Cntr=0.3,0.1

Type RM Length L Ch R = 1,743,0,0,0
BEGIN DESCRIPTION:
Mapping XS cf3fb20d
END DESCRIPTION:
XS GIS Cut Line= 5
      2112944.60     13426400.44      2113258.41     13425262.33
      2112904.00     13425152.44      2112450.81     13425381.71
      2112051.49     13425966.81
#Sta/Elev= 30
  3518.7  333.35  3585.2  333.03  3941.8  331.48  3980.8  331.28  4027.8  329.73
  4141.2  331.47  4289.1  330.50  4395.7  331.04  4698.9  329.65  4723.4  329.56
  4786.6  330.01  4843.2  328.83  4901.8  329.36  4946.2  328.71  5114.4  329.59
  5189.4  328.47  5189.9  327.67  5194.9  327.67  5195.4  328.47  5242.5  329.63
  5403.5  330.26  5495.7  331.46  5576.3  333.35  5634.8  332.50  5687.8  332.58
  5865.1  333.23  5953.3  334.87  6074.5  334.59  6260.2  336.24  6286.6  335.79
#Mann=11,-1,0
  3518.7     0.1       0  3585.2    0.05       0  3941.8     0.1       0
  4698.9    0.05       0  4723.4     0.1       0  5189.4    0.07       0
  5195.4     0.1       0  5403.5    0.08       0  5495.7     0.1       0
  5687.8    0.05       0  5953.3     0.1       0
Bank Sta=5189.4,5195.4
Exp/Cntr=0.3,0.1

Chan Stop Cuts=-1