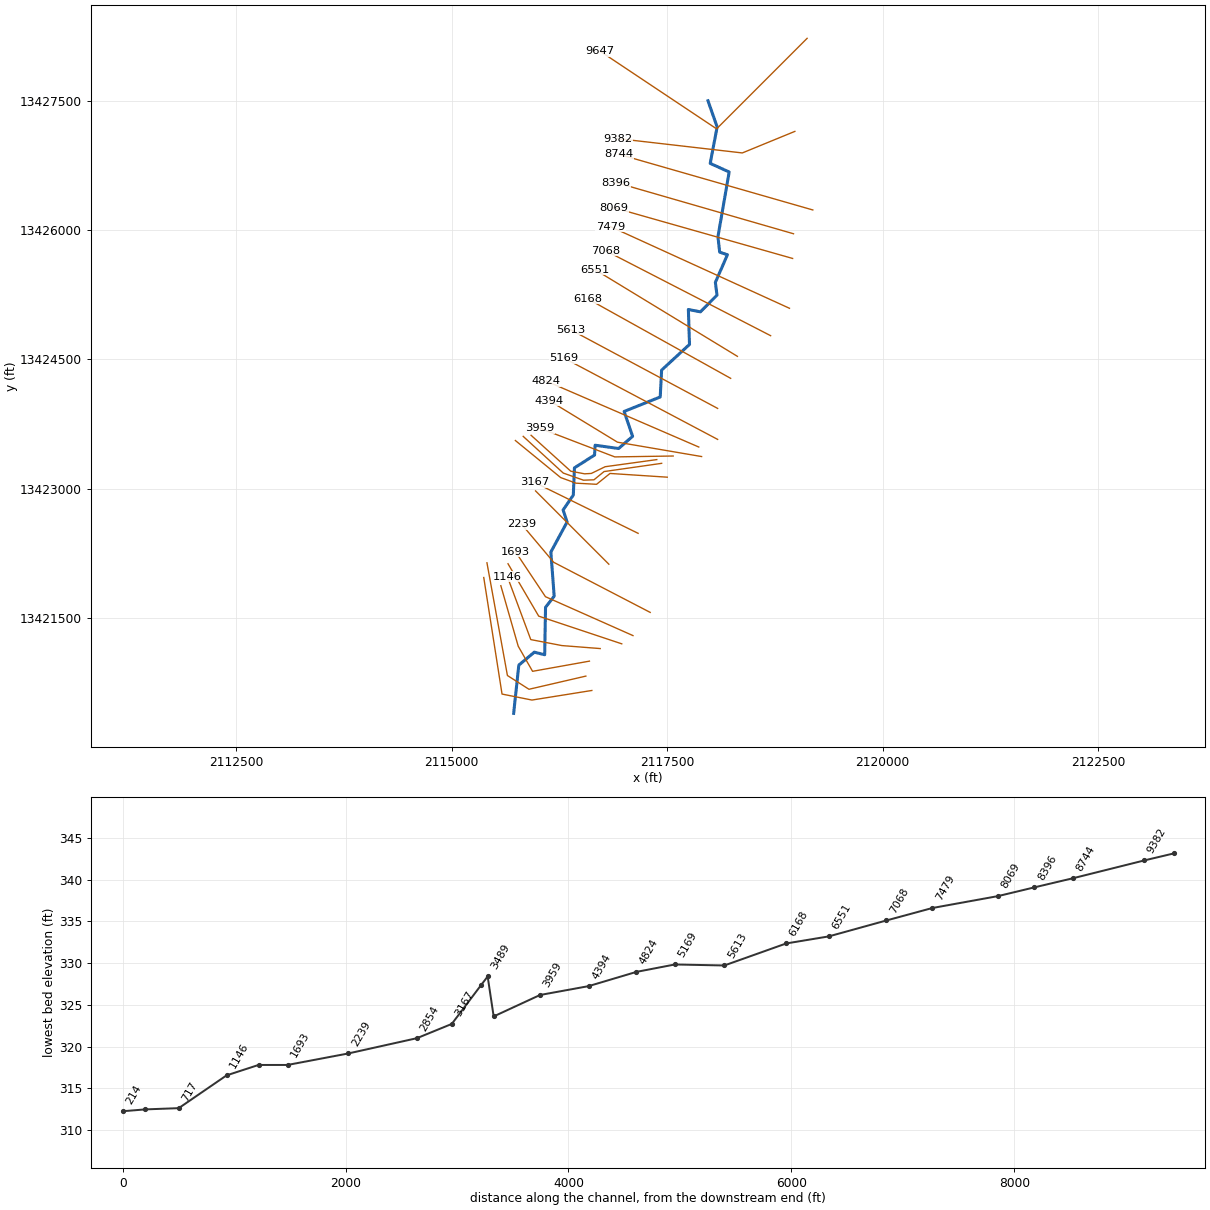
--- UNT 029 in La Jarita Watershed.prj (project) ---

Proj Title=UNT 029 in La Jarita Watershed Base Level Engineering
Current Plan=p01
Default Exp/Contr=0.3,0.1
English Units
Geom File=g01
Flow File=f01
Plan File=p01
Y Axis Title=Elevation
X Axis Title(PF)=Main Channel Distance
X Axis Title(XS)=Station
BEGIN DESCRIPTION:
UNT 029 in La Jarita Watershed
END DESCRIPTION:
DSS Export Rating Curves= 0
DSS Export Rating Curve Sorted= 0
DSS Export Volume Flow Curves= 0
DXF OffsetX= 0
DXF OffsetY= 0
DXF ScaleX= 1
DXF ScaleY= 10

--- UNT 029 in La Jarita Watershed.p01 (plan) ---

Plan Title=Multiple Run
Short Identifier=Multiple
Geom File=g01
Flow File=f01
Subcritical Flow
K Sum by GR= 0
Std Step Tol= 0.01
Critical Tol= 0.01
Num of Std Step Trials= 20
Max Error Tol= 0.3
Flow Tol Ratio= 0.001
Split Flow NTrial= 30
Split Flow Tol= 0.02
Split Flow Ratio= 0.02
Log Output Level= 0
Friction Slope Method= 1
Unsteady Friction Slope Method= 2
Unsteady Bridges Friction Slope Method= 1
Parabolic Critical Depth
Global Vel Dist=  1 , 1 , 1
Global Log Level= 0
CheckData=True
Encroach Param= -1, 0, 0, 0
BEGIN DESCRIPTION:
Multiple Run
END DESCRIPTION:

--- UNT 029 in La Jarita Watershed.f01 (steady flow) ---

Flow Title=Multiple
Number of Profiles=7
Profile Names=10-year,25-year,50-year,1pct_min,100-year,1pct_plu,500-year
River Rch & RM= UNT 029 in La Ja,Reach-1,9647
     123     162     192     114     228     454     323
River Rch & RM= UNT 029 in La Ja,Reach-1,9382
     188     253     306     184     367     733     538
River Rch & RM= UNT 029 in La Ja,Reach-1,8396
     222     302     367     222     444     885     658
River Rch & RM= UNT 029 in La Ja,Reach-1,5169
     239     327     399     242     483     963     719
River Rch & RM= UNT 029 in La Ja,Reach-1,3543
     257     353     431     262     524    1045     784
Boundary for River Rch & Prof#=UNT 029 in La Ja,Reach-1,1
Up Type=0
Dn Type=3
Dn Slope=0.005
Boundary for River Rch & Prof#=UNT 029 in La Ja,Reach-1,2
Up Type=0
Dn Type=3
Dn Slope=0.005
Boundary for River Rch & Prof#=UNT 029 in La Ja,Reach-1,3
Up Type=0
Dn Type=3
Dn Slope=0.005
Boundary for River Rch & Prof#=UNT 029 in La Ja,Reach-1,4
Up Type=0
Dn Type=3
Dn Slope=0.005
Boundary for River Rch & Prof#=UNT 029 in La Ja,Reach-1,5
Up Type=0
Dn Type=3
Dn Slope=0.005
Boundary for River Rch & Prof#=UNT 029 in La Ja,Reach-1,6
Up Type=0
Dn Type=3
Dn Slope=0.005
Boundary for River Rch & Prof#=UNT 029 in La Ja,Reach-1,7
Up Type=0
Dn Type=3
Dn Slope=0.005

--- UNT 029 in La Jarita Watershed.g01 (geometry) ---

Geom Title=Existing Conditions
Program Version=5.05

River Reach=UNT 029 in La Ja,Reach-1
Reach XY= 30
        2117975.     13427500.36      2118081.43     13427197.54
       2118000.8     13426774.54       2118220.8     13426674.54
       2118090.8     13425924.54       2118110.8     13425744.54
       2118200.8     13425714.54       2118060.8     13425394.54
      2118079.62     13425245.47      2117887.57     13425052.33
      2117747.59     13425079.46       2117760.8     13424674.54
      2117437.26     13424376.33      2117420.99     13424064.92
      2117002.15     13423896.73      2117100.89      13423608.1
      2116938.13     13423467.04      2116665.78     13423505.02
      2116659.27     13423391.09      2116425.98     13423242.44
      2116412.96     13422926.68      2116294.68     13422754.15
       2116340.8     13422614.54      2116152.54     13422265.87
       2116190.8     13421754.54       2116090.8     13421624.54
       2116080.8     13421074.54       2115960.8     13421104.54
       2115780.8     13420954.54       2115720.8     13420394.54

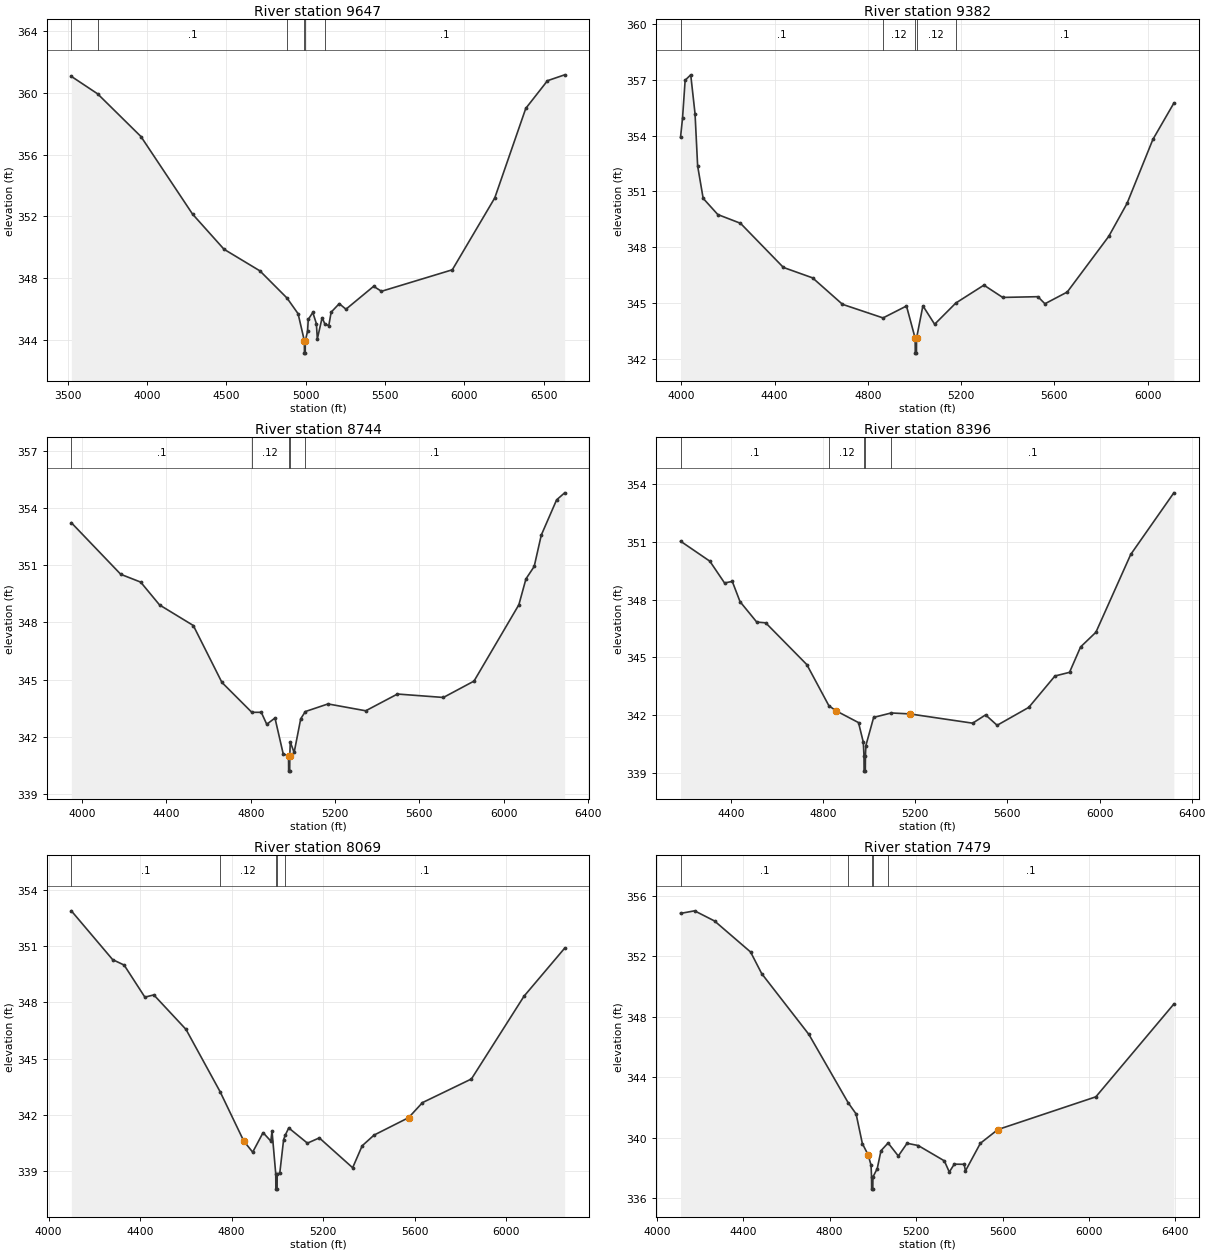
Type RM Length L Ch R = 1 ,9647    ,265,265,265
BEGIN DESCRIPTION:
UNT 029 in La Jarita Watershed 13.0
END DESCRIPTION:
XS GIS Cut Line= 3
      2119124.99     13428224.99        2118075.       13427175.
        2116725.       13428075.
#Sta/Elev= 30
    3524  361.06  3689.6  359.93  3962.4  357.17  4287.7  352.15  4485.6  349.88
  4711.9  348.48  4882.8  346.72  4952.3  345.71  4991.8  343.96  4992.3  343.16
  4997.3  343.16  4997.8  343.96  5011.9  344.57  5016.4  345.34    5045  345.79
  5067.5  345.07  5073.5  344.08  5103.6  345.45  5120.1  345.07  5145.6  344.93
  5160.6  345.81  5211.7  346.36  5253.8     346  5428.1  347.48  5477.6  347.16
  5923.8  348.55  6191.2   353.2  6386.5  358.99  6523.2  360.78  6631.4  361.16
#Mann= 6 ,-1 , 0
    3524     .05       0  3689.6      .1       0  4882.8     .12       0
  4991.8     .07       0  4997.8     .12       0  5120.1      .1       0
Bank Sta=4991.8,4997.8
XS Rating Curve= 0 ,0
Exp/Cntr=0.3,0.1

Type RM Length L Ch R = 1 ,9382    ,638,638,638
BEGIN DESCRIPTION:
Mapping XS d2683b20
END DESCRIPTION:
XS GIS Cut Line= 3
      2118982.95     13427145.61      2118373.55      13426895.6
       2116925.6     13427062.27
#Sta/Elev= 30
  3996.3   353.9  4004.9  354.93  4016.1  356.97  4040.1  357.26  4058.6  355.17
  4069.7  352.37  4093.4  350.63  4156.2  349.76  4253.5  349.29  4437.6  346.92
  4562.9  346.36  4691.1  344.94  4865.1  344.21  4965.6  344.85  5002.8  343.12
  5003.3  342.32  5008.3  342.32  5008.8  343.12    5036  344.86  5086.4  343.87
  5177.3  345.01  5297.8  345.97  5378.3  345.31  5529.3  345.35  5559.5  344.97
  5655.2   345.6  5833.3  348.59  5911.8  350.36  6022.5  353.79  6112.5  355.74
#Mann= 5 ,-1 , 0
  3996.3      .1       0  4865.1     .12       0  5002.8     .07       0
  5008.8     .12       0  5177.3      .1       0
Bank Sta=5002.8,5008.8
XS Rating Curve= 0 ,0
Exp/Cntr=0.3,0.1

Type RM Length L Ch R = 1 ,8744    ,348,348,348
BEGIN DESCRIPTION:
Mapping XS d0e51b9c
END DESCRIPTION:
XS GIS Cut Line= 2
      2119191.29     13426234.13      2116941.25     13426879.98
#Sta/Elev= 30
  3948.7  353.24  4183.2  350.53  4277.8  350.12  4367.4  348.92  4527.5  347.84
  4663.3  344.85  4805.1  343.28    4850  343.28    4876  342.65    4915  342.98
    4954   341.1  4979.4  340.99  4979.9  340.19  4984.9  340.19  4985.4  340.99
  4987.6  341.72    5006  341.17  5037.2  342.94  5059.1  343.32  5166.7  343.72
  5345.7  343.36  5496.2  344.24  5714.2  344.06  5859.5  344.92  6072.3  348.93
    6106  350.29    6145  350.94  6178.7  352.59  6251.4  354.44  6289.6  354.81
#Mann= 5 ,-1 , 0
  3948.7      .1       0  4805.1     .12       0  4979.4     .07       0
  4985.4     .12       0  5059.1      .1       0
Bank Sta=4979.4,4985.4
XS Rating Curve= 0 ,0
Exp/Cntr=0.3,0.1

Type RM Length L Ch R = 1 ,8396    ,327,327,327
BEGIN DESCRIPTION:
Mapping XS 05adf733
END DESCRIPTION:
XS GIS Cut Line= 2
       2118967.3      13425958.1      2116909.97     13426551.86
#Sta/Elev= 30
  4181.4  351.03  4308.7  349.99  4372.5  348.86  4406.1  348.94  4439.7  347.89
  4512.2  346.83  4551.1  346.79  4729.7  344.62  4825.2  342.49 4855.36 342.229
    4954  341.61  4974.8  340.59  4977.7  339.89  4978.2  339.09  4983.5  339.09
    4984  339.89    4986  340.42  5019.7  341.88    5096  342.11 5176.25342.0616
  5449.4  341.58  5505.6  342.01  5555.6  341.47    5693   342.4  5806.7  344.03
  5869.9  344.22    5918  345.54  5984.4   346.3  6135.5  350.34  6322.7  353.54
#Mann= 5 ,-1 , 0
  4181.4      .1       0  4825.2     .12       0  4977.7     .07       0
    4984     .12       0    5096      .1       0
Bank Sta=4855.36,5176.25
XS Rating Curve= 0 ,0
Exp/Cntr=0.3,0.1

Type RM Length L Ch R = 1 ,8069    ,590,590,590
BEGIN DESCRIPTION:
Mapping XS f859f8b5
END DESCRIPTION:
XS GIS Cut Line= 2
      2118956.87     13425671.65      2116884.28     13426260.09
#Sta/Elev= 30
  4099.7  352.87  4280.1  350.27  4330.3  349.98  4420.9  348.27    4460  348.39
  4600.6  346.55  4749.1  343.24 4852.85340.6019  4891.7  340.01  4937.1  341.05
    4971   340.6  4976.2  341.13  4992.5  338.84    4993  338.04  4998.3  338.04
  4998.8  338.84  5010.1   338.9  5026.8  340.68  5034.5  340.93  5049.2   341.3
  5130.8  340.49  5182.7  340.77  5328.3  339.18  5369.9  340.35  5421.8  340.92
 5572.79341.8496  5633.2  342.65    5847  343.91  6076.7  348.32  6254.2  350.88
#Mann= 5 ,-1 , 0
  4099.7      .1       0  4749.1     .12       0  4992.5     .07       0
  4998.8     .12       0  5034.5      .1       0
Bank Sta=4852.85,5572.79
XS Rating Curve= 0 ,0
Exp/Cntr=0.3,0.1

Type RM Length L Ch R = 1 ,7479    ,411,411,411
BEGIN DESCRIPTION:
Mapping XS f9e92f98
END DESCRIPTION:
XS GIS Cut Line= 2
      2118920.45     13425093.51      2116843.88     13426040.72
#Sta/Elev= 30
  4110.1  354.83  4175.2     355  4267.4  354.33  4434.2  352.28  4485.7  350.85
  4704.1  346.83  4885.7  342.32  4922.4  341.58  4951.4  339.62 4977.64 338.886
  4991.5   338.2  4993.9  337.41  4994.4  336.61  4999.7  336.61  5000.2  337.41
  5020.1  337.96  5037.6  339.15  5070.5  339.66  5117.7   338.8  5158.3  339.64
  5209.9  339.49  5330.6  338.48  5353.6  337.74  5376.7  338.26  5422.7  338.25
  5428.2  337.81  5497.4  339.64 5578.23340.5458  6031.7  342.71  6392.5  348.84
#Mann= 5 ,-1 , 0
  4110.1      .1       0  4885.7     .12       0  4993.9     .07       0
  5000.2     .12       0  5070.5      .1       0
Bank Sta=4977.64,5578.23
XS Rating Curve= 0 ,0
Exp/Cntr=0.3,0.1

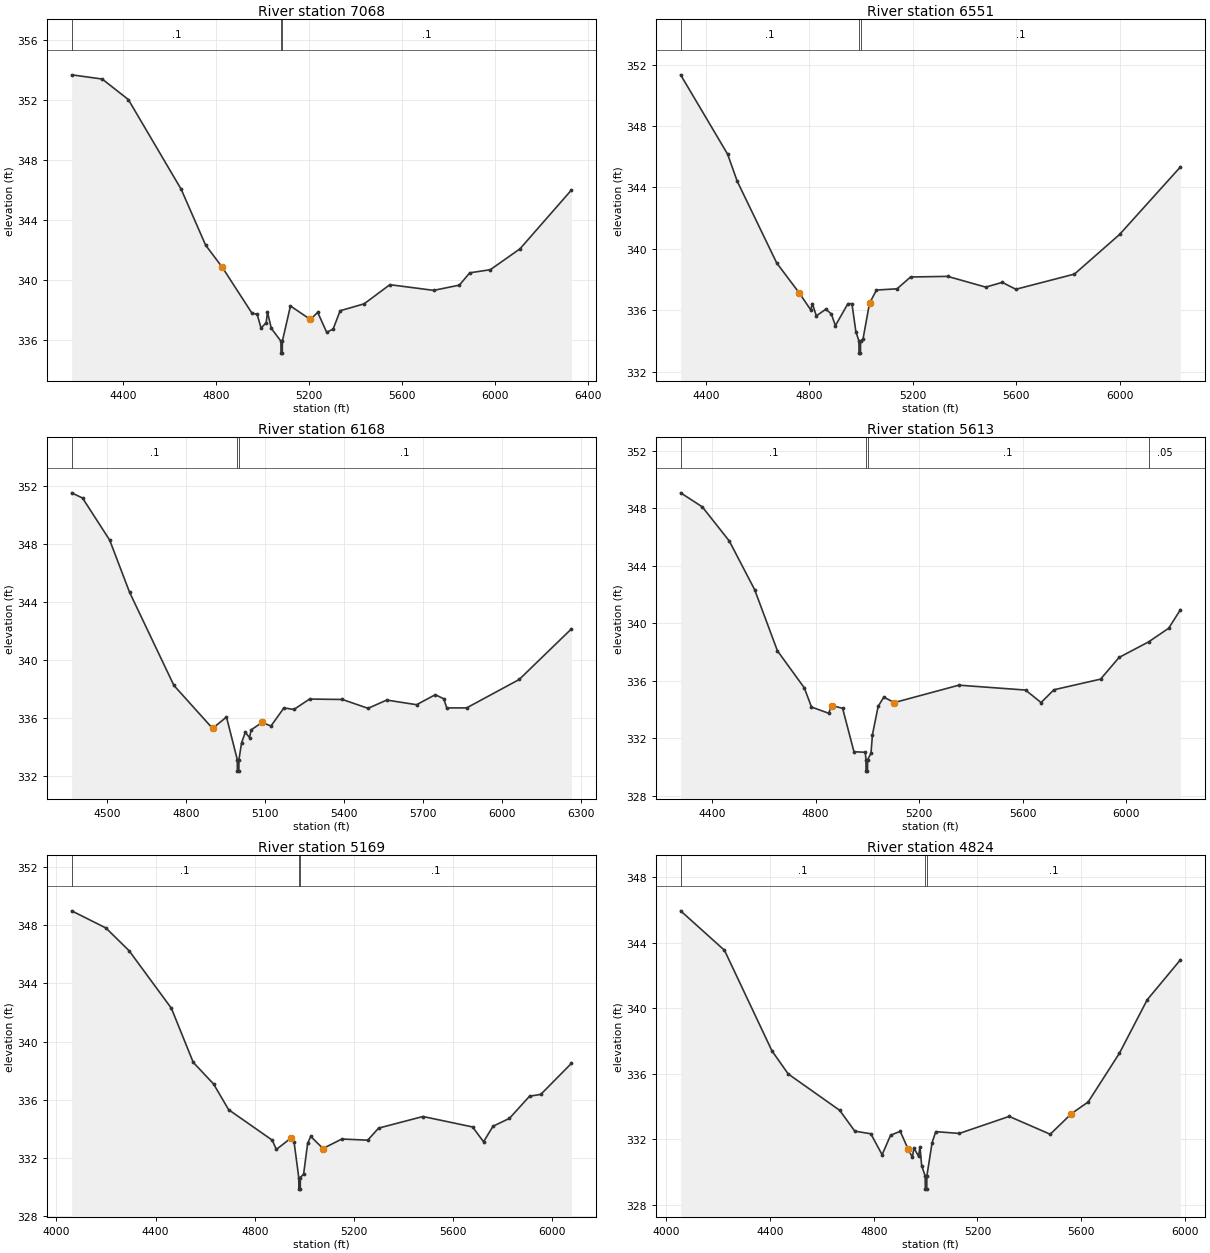
Type RM Length L Ch R = 1 ,7068    ,517,517,517
BEGIN DESCRIPTION:
Mapping XS 037aa991
END DESCRIPTION:
XS GIS Cut Line= 2
      2118701.72     13424775.79      2116790.39      13425760.1
#Sta/Elev= 30
  4180.2   353.7  4311.5  353.42    4424  352.05  4651.3  346.06  4756.5  342.33
 4827.38340.8667  4956.1  337.78  4978.2  337.72  4994.8  336.79  5016.9  337.15
  5022.6  337.85  5039.1  336.77  5080.3  335.92  5080.8  335.12  5086.1  335.12
  5086.6  335.92  5121.4  338.27  5206.8337.3686  5238.6  337.84  5277.3  336.51
  5305.1  336.73  5335.1  337.95  5438.2  338.41    5549  339.69  5737.3  339.31
  5848.1  339.66  5892.5  340.48  5981.1  340.69  6108.5  342.08  6330.1  346.01
#Mann= 3 ,-1 , 0
  4180.2      .1       0  5080.3     .07       0  5086.6      .1       0
Bank Sta=4827.38,5206.8
XS Rating Curve= 0 ,0
Exp/Cntr=0.3,0.1

Type RM Length L Ch R = 1 ,6551    ,383,383,383
BEGIN DESCRIPTION:
Mapping XS a5013ba6
END DESCRIPTION:
XS GIS Cut Line= 2
      2118316.22     13424536.25      2116666.44     13425540.69
#Sta/Elev= 30
  4302.9  351.34  4484.5  346.17  4521.3  344.42  4674.3  339.08 4761.91337.1169
    4806  336.02  4811.8  336.44  4827.3  335.64  4864.1  336.07  4885.4  335.76
  4900.9     335  4949.4  336.43  4964.9  336.43  4980.3  334.59  4991.9  334.01
  4992.4  333.21  4997.8  333.21  4998.3  334.01  5007.5  334.11 5032.84336.4557
  5059.8  337.32  5139.2   337.4  5191.5  338.17  5334.9  338.21    5482  337.51
    5546  337.82  5598.3  337.37  5824.9  338.36  5999.2  340.94  6234.4  345.34
#Mann= 3 ,-1 , 0
  4302.9      .1       0  4991.9     .07       0  4998.3      .1       0
Bank Sta=4761.91,5032.84
XS Rating Curve= 0 ,0
Exp/Cntr=0.3,0.1

Type RM Length L Ch R = 1 ,6168    ,555,555,555
BEGIN DESCRIPTION:
Mapping XS fed94d9f
END DESCRIPTION:
XS GIS Cut Line= 2
      2118238.11     13424281.03      2116581.88      13425202.9
#Sta/Elev= 30
  4367.1  351.55  4408.4  351.19  4511.3  348.29  4586.8  344.69  4754.9  338.27
  4901.5335.3072  4954.3  336.09  4995.2  333.16  4995.7  332.36  5001.1  332.36
  5001.6  333.16  5011.6  334.32  5025.8  335.04  5041.8  334.67  5047.6   335.2
  5089.2335.7192    5123  335.47  5172.2  336.72  5209.9  336.61  5269.4  337.33
    5394   337.3  5491.2  336.69  5562.1  337.26  5675.3  336.94  5746.2  337.63
  5778.2  337.35  5789.8  336.72  5865.1  336.72  6064.5  338.68  6262.6  342.17
#Mann= 3 ,-1 , 0
  4367.1      .1       0  4995.2     .07       0  5001.6      .1       0
Bank Sta=4901.5,5089.2
XS Rating Curve= 0 ,0
Exp/Cntr=0.3,0.1

Type RM Length L Ch R = 1 ,5613    ,444,444,444
BEGIN DESCRIPTION:
Mapping XS 6fa31552
END DESCRIPTION:
XS GIS Cut Line= 2
      2118087.11     13423932.05      2116383.97     13424843.52
#Sta/Elev= 30
  4278.3  349.08  4362.2   348.1  4466.3  345.73  4564.2  342.35  4652.4  338.09
  4756.4  335.51    4784  334.18  4849.8  333.75 4863.63334.2782  4904.3  334.09
  4948.2  331.07    4992  331.03  4994.5  330.52    4995  329.72  5000.5  329.72
    5001  330.52    5014  330.96  5019.7  332.26  5041.6  334.22  5063.5  334.87
    5104334.4874  5353.7   335.7  5611.3  335.36  5671.4  334.49  5721.1  335.38
  5901.4  336.12  5972.9  337.63  6086.9  338.71  6164.6  339.66    6210  340.95
#Mann= 4 ,-1 , 0
  4278.3      .1       0  4994.5     .07       0    5001      .1       0
  6086.9     .05       0
Bank Sta=4863.63,5104
XS Rating Curve= 0 ,0
Exp/Cntr=0.3,0.1

Type RM Length L Ch R = 1 ,5169    ,345,345,345
BEGIN DESCRIPTION:
Mapping XS 02c91f2e
END DESCRIPTION:
XS GIS Cut Line= 2
      2118087.06      13423572.7      2116305.83      13424515.4
#Sta/Elev= 30
  4061.8     349  4199.9  347.82  4293.6  346.25    4464  342.29    4552  338.57
  4634.4  337.07  4694.7  335.31  4870.7  333.21  4887.1  332.57 4946.05333.3561
  4958.7  333.08  4977.5  330.64    4978  329.84  4983.5  329.84    4984  330.64
  4997.1  330.87  5013.4     333  5025.8  333.47 5075.27332.6355  5151.1  333.29
  5255.5  333.21  5299.5  334.04  5478.4  334.84  5678.6  334.12  5722.6   333.1
  5760.9  334.17  5826.9  334.71  5908.3  336.24  5953.3  336.36  6077.1   338.5
#Mann= 3 ,-1 , 0
  4061.8      .1       0  4977.5     .07       0    4984      .1       0
Bank Sta=4946.05,5075.27
XS Rating Curve= 0 ,0
Exp/Cntr=0.3,0.1

Type RM Length L Ch R = 1 ,4824    ,430,430,430
BEGIN DESCRIPTION:
Mapping XS 50b799d9
END DESCRIPTION:
XS GIS Cut Line= 2
      2117868.33     13423484.15      2116098.75     13424249.23
#Sta/Elev= 30
  4055.2  345.94  4224.4  343.53  4407.5  337.39  4470.3  335.98  4668.9  333.76
    4727  332.49  4788.8  332.33  4832.4  331.05    4865  332.24  4902.3  332.48
 4931.86331.4229  4949.3  330.89  4954.8  331.47  4972.8  330.96  4978.3  331.54
  4984.9  330.39  4998.5  329.75    4999  328.95  5004.5  328.95    5005  329.75
  5025.2  331.79  5039.3  332.46  5130.1  332.35  5322.6  333.39  5480.8   332.3
 5562.78333.5595  5627.2  334.27  5747.5  337.24    5855  340.51  5983.1  342.95
#Mann= 3 ,-1 , 0
  4055.2      .1       0  4998.5     .07       0    5005      .1       0
Bank Sta=4931.86,5562.78
XS Rating Curve= 0 ,0
Exp/Cntr=0.3,0.1

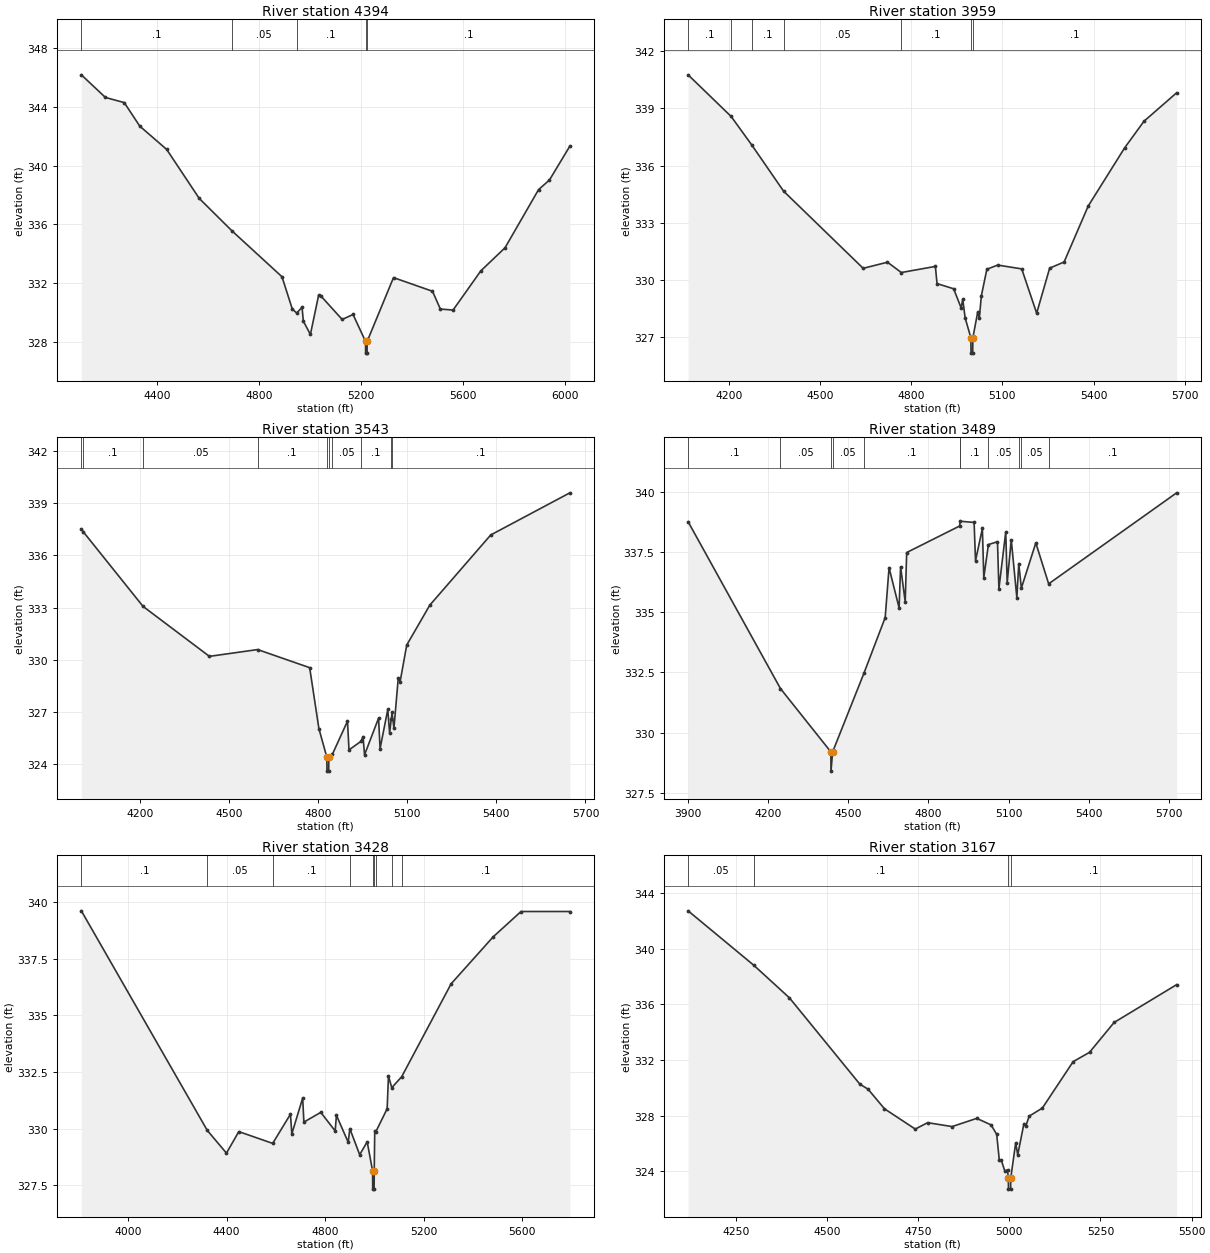
Type RM Length L Ch R = 1 ,4394    ,435,435,435
BEGIN DESCRIPTION:
Mapping XS 77f37bbd
END DESCRIPTION:
XS GIS Cut Line= 3
      2117900.96     13423373.72      2116925.29     13423540.38
      2116133.61     13424023.03
#Sta/Elev= 30
  4102.6  346.18  4197.1  344.64    4271  344.29  4331.8  342.69  4437.6   341.1
  4565.2  337.77  4693.1  335.57  4889.8  332.44  4930.4  330.24  4947.7  329.97
  4968.6  330.36  4973.7  329.42  5001.4  328.51  5033.8  331.19    5042  331.14
  5126.1  329.53  5168.7  329.87  5217.7  328.04  5218.2  327.24  5223.7  327.24
  5224.2  328.04  5327.5  332.38  5480.5  331.45  5511.4  330.24  5561.2  330.17
  5670.2  332.84  5765.1  334.41  5896.8  338.37  5939.4  339.02  6019.6  341.33
#Mann= 5 ,-1 , 0
  4102.6      .1       0  4693.1     .05       0  4947.7      .1       0
  5217.7     .07       0  5224.2      .1       0
Bank Sta=5217.7,5224.2
XS Rating Curve= 0 ,0
Exp/Cntr=0.3,0.1

Type RM Length L Ch R = 1 ,3959    ,416,416,416
BEGIN DESCRIPTION:
Mapping XS 4a7660d8
END DESCRIPTION:
XS GIS Cut Line= 3
      2117571.43     13423379.97      2116894.39     13423369.56
      2116024.59     13423702.89
#Sta/Elev= 30
  4065.1  340.75  4206.8  338.57  4274.6  337.08  4379.5  334.66  4641.6  330.62
  4721.6  330.94  4767.2   330.4  4879.3  330.72  4884.7  329.82  4939.4  329.55
  4964.1  328.55  4969.4     329  4977.2  328.03  4996.2  326.98  4996.7  326.18
  5002.2  326.18  5002.7  326.98  5018.8  328.34  5024.1  328.03  5030.7  329.18
  5048.8  330.57  5084.3  330.79  5163.6  330.59  5212.8  328.27  5255.6  330.63
  5303.1  330.95  5382.5  333.88  5502.6  336.93  5566.2  338.32  5673.7  339.81
#Mann= 7 ,-1 , 0
  4065.1      .1       0  4206.8     .05       0  4274.6      .1       0
  4379.5     .05       0  4767.2      .1       0  4996.2     .07       0
  5002.7      .1       0
Bank Sta=4996.2,5002.7
XS Rating Curve= 0 ,0
Exp/Cntr=0.3,0.1

Type RM Length L Ch R = 1 ,3543    ,54,54,54
BEGIN DESCRIPTION:
Mapping XS b1d3d933
END DESCRIPTION:
XS GIS Cut Line= 6
      2117381.32      13423338.3      2116782.41     13423255.84
      2116621.82     13423177.72      2116543.69     13423173.38
       2116383.1     13423203.76      2115923.29     13423620.19
#Sta/Elev= 30
  4001.7  337.51  4008.8  337.34  4209.5  333.07  4433.1   330.2  4595.6  330.59
  4770.9  329.55    4802  326.05  4828.7  324.41  4829.2  323.61  4834.9  323.61
  4835.4  324.41  4847.8  324.59  4898.3  326.48  4903.4  324.83  4943.8  325.32
  4950.7  325.59  4955.8  324.55    5003  326.65  5008.1   324.9    5034  327.15
  5040.2  325.81  5045.9  326.62  5048.4  326.98  5054.8  326.08  5069.4  328.97
  5075.6  328.75  5097.9  330.85  5175.6  333.14  5380.8  337.17  5647.5  339.59
#Mann= 10 ,-1 , 0
  4001.7     .05       0  4008.8      .1       0  4209.5     .05       0
  4595.6      .1       0  4828.7     .07       0  4835.4      .1       0
  4847.8     .05       0  4943.8      .1       0  5045.9     .05       0
  5048.4      .1       0
Bank Sta=4828.7,4835.4
XS Rating Curve= 0 ,0
Exp/Cntr=0.3,0.1

Type RM Length L Ch R = 1 ,3489    ,61,61,61
BEGIN DESCRIPTION:
Mapping XS 088ed284
END DESCRIPTION:
XS GIS Cut Line= 6
      2117437.79     13423294.91      2116769.39     13423199.42
       2116652.2     13423103.93      2116530.67     13423099.59
       2116296.3     13423182.06      2115831.86     13423607.43
#Sta/Elev= 30
  3899.5  338.76  4245.5  331.83  4434.3   329.2  4434.8   328.4    4441   329.2
    4558  332.46  4637.9  334.78  4652.3  336.85    4690  335.18  4695.6  336.89
  4712.9  335.43  4718.4  337.48  4916.4  338.58  4919.3  338.78    4971  338.73
  4976.3  337.14    5002  338.48  5007.3  336.44  5024.6  337.81  5058.6  337.93
  5063.9  335.98  5089.6  338.34  5094.9  336.23  5110.2  338.01  5131.1  335.61
  5138.3  337.02    5148     336  5202.2  337.88  5250.3  336.18  5729.8  339.96
#Mann= 11 ,-1 , 0
  3899.5      .1       0  4245.5     .05       0  4434.3     .07       0
    4441     .05       0    4558      .1       0  4916.4     .05       0
  4919.3      .1       0  5024.6     .05       0  5138.3      .1       0
    5148     .05       0  5250.3      .1       0
Bank Sta=4434.3,4441
XS Rating Curve= 0 ,0
Exp/Cntr=0.3,0.1

Type RM Length L Ch R = 1 ,3428    ,261,261,261
BEGIN DESCRIPTION:
Mapping XS 3bf7ae0d
END DESCRIPTION:
XS GIS Cut Line= 6
       2117502.9     13423134.32      2116838.83     13423177.72
      2116682.58     13423051.85      2116443.87     13423064.87
      2116265.91     13423129.98      2115740.74     13423559.66
#Sta/Elev= 30
  3809.9  339.62  4321.4  329.92  4399.1  328.92  4449.2  329.87  4586.7  329.35
    4659  330.64  4664.4  329.77  4708.5  331.35  4713.5  330.29    4782  330.72
  4840.5   329.9  4845.6  330.59  4893.4   329.4    4900     330    4940  328.85
  4970.5  329.42  4992.4  328.13  4992.9  327.33  4998.6  327.33  4999.1  328.13
  5001.1  329.91  5004.5  329.84  5051.5  330.88  5056.8  332.33  5070.2  331.81
  5110.3  332.29  5311.4   336.4  5481.9  338.47  5595.1  339.59  5793.4  339.59
#Mann= 9 ,-1 , 0
  3809.9      .1       0  4321.4     .05       0  4586.7      .1       0
    4900     .05       0  4992.4    .035       0  4999.1     .05       0
  5004.5      .1       0  5070.2     .05       0  5110.3      .1       0
Bank Sta=4992.4,4999.1
XS Rating Curve= 0 ,0
Exp/Cntr=0.3,0.1

Type RM Length L Ch R = 1 ,3167    ,313,313,313
BEGIN DESCRIPTION:
Mapping XS 97aec36d
END DESCRIPTION:
XS GIS Cut Line= 2
      2117164.38     13422483.26      2115962.07     13423073.56
#Sta/Elev= 30
  4119.5  342.73  4299.4  338.82  4397.3  336.47  4590.4  330.26  4612.9   329.9
  4657.9  328.49  4742.3  327.03  4776.1  327.49  4843.3  327.21  4910.8   327.8
  4950.2  327.33  4965.5  326.65  4972.7  324.81  4978.3  324.78  4987.8  324.01
  4995.2   324.1  4997.4  323.51  4997.9  322.71  5003.6  322.71  5004.1  323.51
  5017.7  326.05  5023.2  325.17  5040.1  327.41  5045.7  327.27  5054.6  327.96
  5090.7  328.54  5175.1  331.88    5220  332.55  5287.5   334.7  5458.9  337.42
#Mann= 4 ,-1 , 0
  4119.5     .05       0  4299.4      .1       0  4997.4     .07       0
  5004.1      .1       0
Bank Sta=4997.4,5004.1
XS Rating Curve= 0 ,0
Exp/Cntr=0.3,0.1

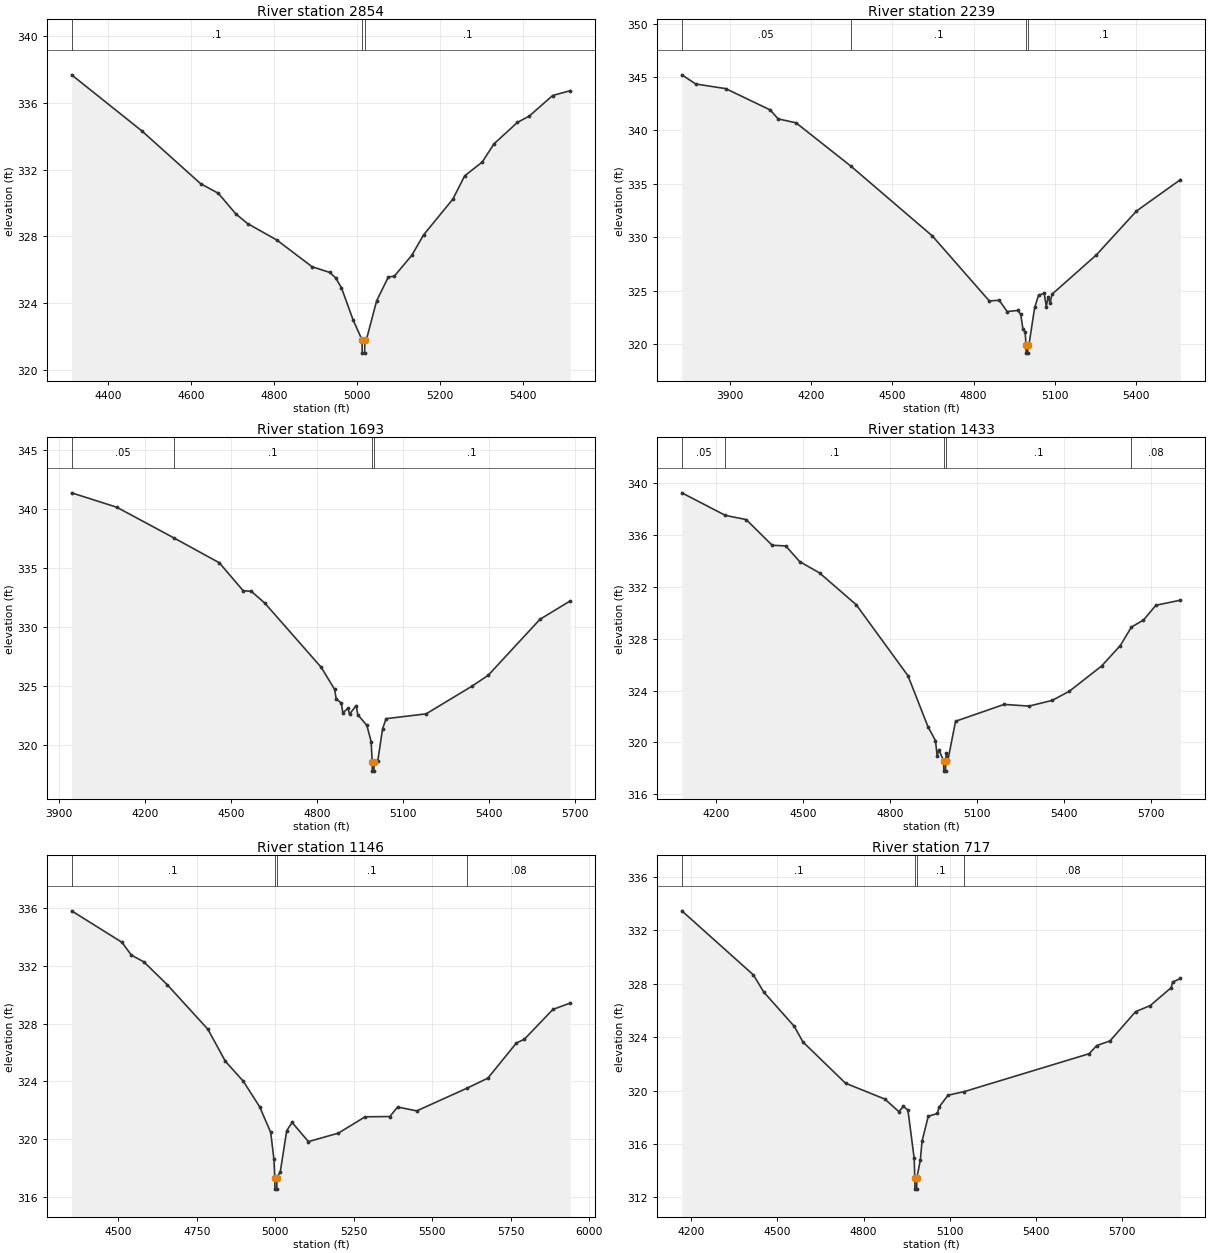
Type RM Length L Ch R = 1 ,2854    ,615,615,615
BEGIN DESCRIPTION:
UNT 029 in La Jarita Watershed 2.0
END DESCRIPTION:
XS GIS Cut Line= 3
      2116824.97     13422125.03        2116325.       13422625.
      2115975.03     13422974.97
#Sta/Elev= 30
  4311.5  337.69  4481.2  334.32  4622.6  331.16    4665  330.59  4707.4  329.35
  4735.7  328.77  4806.4  327.78  4891.3  326.18  4933.7  325.84  4947.9  325.52
    4962  324.92  4990.3  322.98  5011.6   321.8  5012.1     321  5017.9     321
  5018.4   321.8  5022.1   321.8  5046.9  324.14  5075.1  325.57  5089.3  325.61
  5131.7  326.87    5160  328.09  5230.7  330.24    5259  331.63  5301.4  332.46
  5329.7  333.55  5386.3  334.84  5414.5  335.21  5471.1  336.45  5513.5  336.74
#Mann= 3 ,-1 , 0
  4311.5      .1       0  5011.6     .07       0  5018.4      .1       0
Bank Sta=5011.6,5018.4
XS Rating Curve= 0 ,0
Exp/Cntr=0.3,0.1

Type RM Length L Ch R = 1 ,2239    ,546,546,546
BEGIN DESCRIPTION:
Mapping XS 3d122a2a
END DESCRIPTION:
XS GIS Cut Line= 3
      2117304.77     13421565.87      2116184.99     13422147.46
      2115811.77     13422590.11
#Sta/Elev= 30
  3723.1   345.2  3774.5  344.34  3885.1  343.91  4049.6  341.91  4078.5  341.08
  4144.8  340.71  4346.6  336.67  4647.9  330.13  4857.8  324.06  4894.7  324.11
  4924.1  323.06  4962.4  323.16    4974  322.81  4982.1  321.46  4990.4  321.15
  4993.6  319.97  4994.1  319.17  4999.9  319.17  5000.4  319.97  5004.7  319.98
  5025.6  323.44  5039.9  324.58  5060.7  324.77  5068.5  323.52    5075  324.42
  5082.8  323.84  5089.3  324.67  5253.1  328.35  5401.4  332.46  5563.9   335.4
#Mann= 4 ,-1 , 0
  3723.1     .05       0  4346.6      .1       0  4993.6     .07       0
  5000.4      .1       0
Bank Sta=4993.6,5000.4
XS Rating Curve= 0 ,0
Exp/Cntr=0.3,0.1

Type RM Length L Ch R = 1 ,1693    ,260,260,260
BEGIN DESCRIPTION:
Mapping XS b511df95
END DESCRIPTION:
XS GIS Cut Line= 3
      2117105.14     13421296.76      2116089.51     13421748.15
      2115742.28     13422268.99
#Sta/Elev= 30
  3944.7   341.4    4102  340.18  4300.1  337.59  4459.2  335.47  4542.4   333.1
  4571.2  333.04  4617.7  332.05  4814.7  326.59  4861.2  324.72  4866.6  323.93
  4884.4  323.56  4889.9  322.74  4907.7  323.12  4913.1  322.63  4936.4  323.35
  4941.9  322.58  4973.5  321.67  4988.4   320.3    4992  318.59  4992.5  317.79
  4998.3  317.79  4998.8  318.59  5011.6  318.67  5028.2  321.37  5040.4  322.24
    5180  322.65  5339.2  324.99  5396.3  325.92  5576.6  330.67  5682.1  332.23
#Mann= 4 ,-1 , 0
  3944.7     .05       0  4300.1      .1       0    4992     .07       0
  4998.8      .1       0
Bank Sta=4992,4998.8
XS Rating Curve= 0 ,0
Exp/Cntr=0.3,0.1

Type RM Length L Ch R = 1 ,1433    ,287,287,287
BEGIN DESCRIPTION:
Mapping XS fe21efc5
END DESCRIPTION:
XS GIS Cut Line= 3
       2116974.9     13421201.28      2116011.38     13421522.46
       2115655.5     13422130.07
#Sta/Elev= 30
  4081.6  339.23  4231.9  337.49  4303.5  337.17  4393.1  335.19  4439.9  335.14
    4488  333.93  4556.5  333.06    4683  330.61  4861.5  325.14  4930.7   321.2
  4956.4  320.14  4962.3  318.94  4967.6  319.45  4984.6  318.59  4985.1  317.79
    4991  317.79  4991.5  318.59  4993.9  319.19  4999.2  318.64  5025.6  321.63
  5192.9  322.93  5278.9   322.8  5359.1  323.24  5417.7  323.94    5529  325.88
  5593.7  327.46  5632.2  328.89  5673.8  329.43  5716.8  330.57  5801.4  330.96
#Mann= 5 ,-1 , 0
  4081.6     .05       0  4231.9      .1       0  4984.6     .07       0
  4991.5      .1       0  5632.2     .08       0
Bank Sta=4984.6,4991.5
XS Rating Curve= 0 ,0
Exp/Cntr=0.3,0.1

Type RM Length L Ch R = 1 ,1146    ,429,429,429
BEGIN DESCRIPTION:
Mapping XS 9b298684
END DESCRIPTION:
XS GIS Cut Line= 4
      2116724.98     13421146.33      2116280.57     13421181.05
      2115919.46      13421250.5       2115649.3     13421977.85
#Sta/Elev= 30
  4350.8  335.82  4511.3  333.64  4541.4  332.75  4581.5  332.28  4655.7   330.7
  4785.1  327.62  4840.9   325.4  4897.9  324.02  4949.9  322.26  4985.5  320.47
  4995.7  318.61  4998.4  317.34  4998.9  316.54  5004.8  316.54  5005.3  317.34
  5016.1  317.76  5036.5  320.59  5053.7  321.16  5105.7  319.83  5201.1  320.42
  5286.4  321.55  5365.1  321.57  5390.1  322.23  5450.9  321.96  5611.9  323.54
  5677.8  324.23  5768.8  326.67  5793.9  326.92    5885  328.99  5940.2  329.43
#Mann= 4 ,-1 , 0
  4350.8      .1       0  4998.4     .07       0  5005.3      .1       0
  5611.9     .08       0
Bank Sta=4998.4,5005.3
XS Rating Curve= 0 ,0
Exp/Cntr=0.3,0.1

Type RM Length L Ch R = 1 ,717     ,301,301,301
BEGIN DESCRIPTION:
Mapping XS 75b423bf
END DESCRIPTION:
XS GIS Cut Line= 4
        2116600.     13421000.49       2115940.3     13420882.44
      2115773.63     13421174.11      2115572.25     13421875.46
#Sta/Elev= 30
  4167.4  333.47  4416.3  328.67    4453  327.37  4558.5  324.82    4589  323.64
  4737.1  320.55  4873.9  319.36  4922.9  318.42  4938.7  318.82  4954.5  318.52
  4976.1  314.93  4978.4  313.41  4978.9  312.61  4984.8  312.61  4985.3  313.41
  4997.7  314.82  5003.5   316.2  5025.1  318.07  5056.8  318.28  5062.5  318.75
  5093.9  319.65  5150.4  319.92  5585.3  322.76  5611.4  323.37    5658  323.72
  5746.7  325.91  5798.1  326.37  5870.7  327.71  5875.9  328.13  5903.2   328.4
#Mann= 4 ,-1 , 0
  4167.4      .1       0  4978.4     .07       0  4985.3      .1       0
  5150.4     .08       0
Bank Sta=4978.4,4985.3
XS Rating Curve= 0 ,0
Exp/Cntr=0.3,0.1

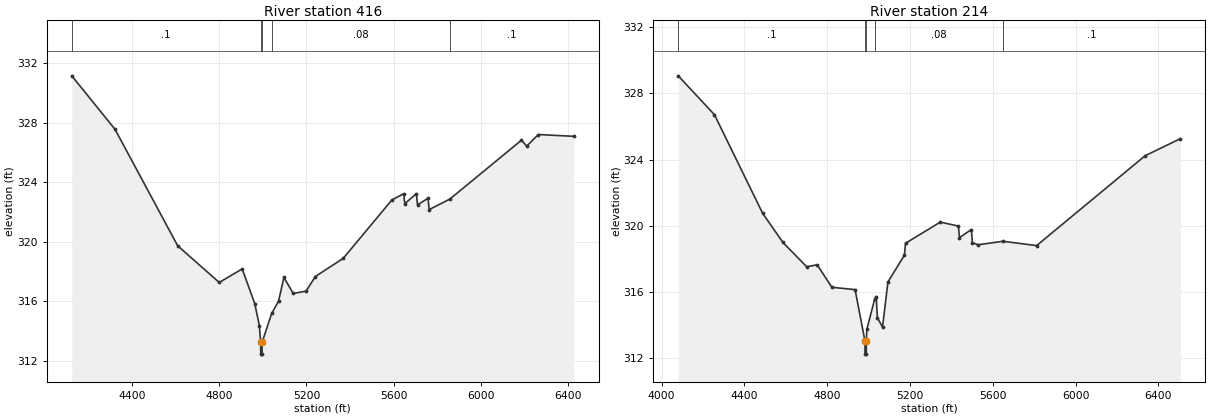
Type RM Length L Ch R = 1 ,416     ,202,202,202
BEGIN DESCRIPTION:
Mapping XS 9f18033c
END DESCRIPTION:
XS GIS Cut Line= 4
      2116558.31     13420826.88      2115898.63     13420674.11
      2115648.63     13420833.83      2115411.11     13422141.32
#Sta/Elev= 30
  4123.7  331.14  4322.1  327.55  4609.5  319.73  4800.1  317.27  4905.3  318.18
  4962.9  315.85    4984  314.38  4989.9  313.26  4990.4  312.46  4996.3  312.46
  4996.8  313.26  5040.5  315.19    5072  316.01  5096.7  317.61  5139.4  316.53
  5198.5  316.69    5241  317.67  5368.8  318.89  5592.5  322.82  5645.9  323.22
    5651  322.56  5704.3  323.23  5709.4  322.48  5757.7  322.92  5762.8  322.16
    5858  322.87  6186.2  326.82  6210.2  326.42  6263.6   327.2  6426.4  327.08
#Mann= 5 ,-1 , 0
  4123.7      .1       0  4989.9     .07       0  4996.8      .1       0
  5040.5     .08       0    5858      .1       0
Bank Sta=4989.9,4996.8
XS Rating Curve= 0 ,0
Exp/Cntr=0.3,0.1

Type RM Length L Ch R = 1 ,214     ,0,0,0
BEGIN DESCRIPTION:
UNT 029 in La Jarita Watershed 1.0
END DESCRIPTION:
XS GIS Cut Line= 4
      2116627.76     13420660.21      2115933.35     13420549.11
      2115586.13     13420618.55      2115374.07     13421970.59
#Sta/Elev= 30
    4080  329.06    4255  326.71  4487.9  320.75  4585.9  318.99  4700.6  317.52
  4751.2  317.64  4822.3  316.28  4934.5  316.14  4982.1  313.04  4982.6  312.24
  4988.5  312.24    4989  313.04  4991.2  313.73  5028.8  315.55  5036.5  315.72
  5042.2  314.45  5067.1  313.87  5093.2   316.6    5173  318.22  5178.1  318.94
  5346.3  320.22  5433.7  319.98  5438.8  319.28  5496.3  319.77  5501.4  318.97
  5528.5  318.85  5649.1  319.06  5811.9   318.8  6335.9  324.23  6505.9  325.26
#Mann= 5 ,-1 , 0
    4080      .1       0  4982.1     .07       0    4989      .1       0
  5028.8     .08       0  5649.1      .1       0
Bank Sta=4982.1,4989
XS Rating Curve= 0 ,0
Exp/Cntr=0.3,0.1
LCMann Table=0

Chan Stop Cuts=-1
Use User Specified Reach Order=0
Composite Channel Slope=5