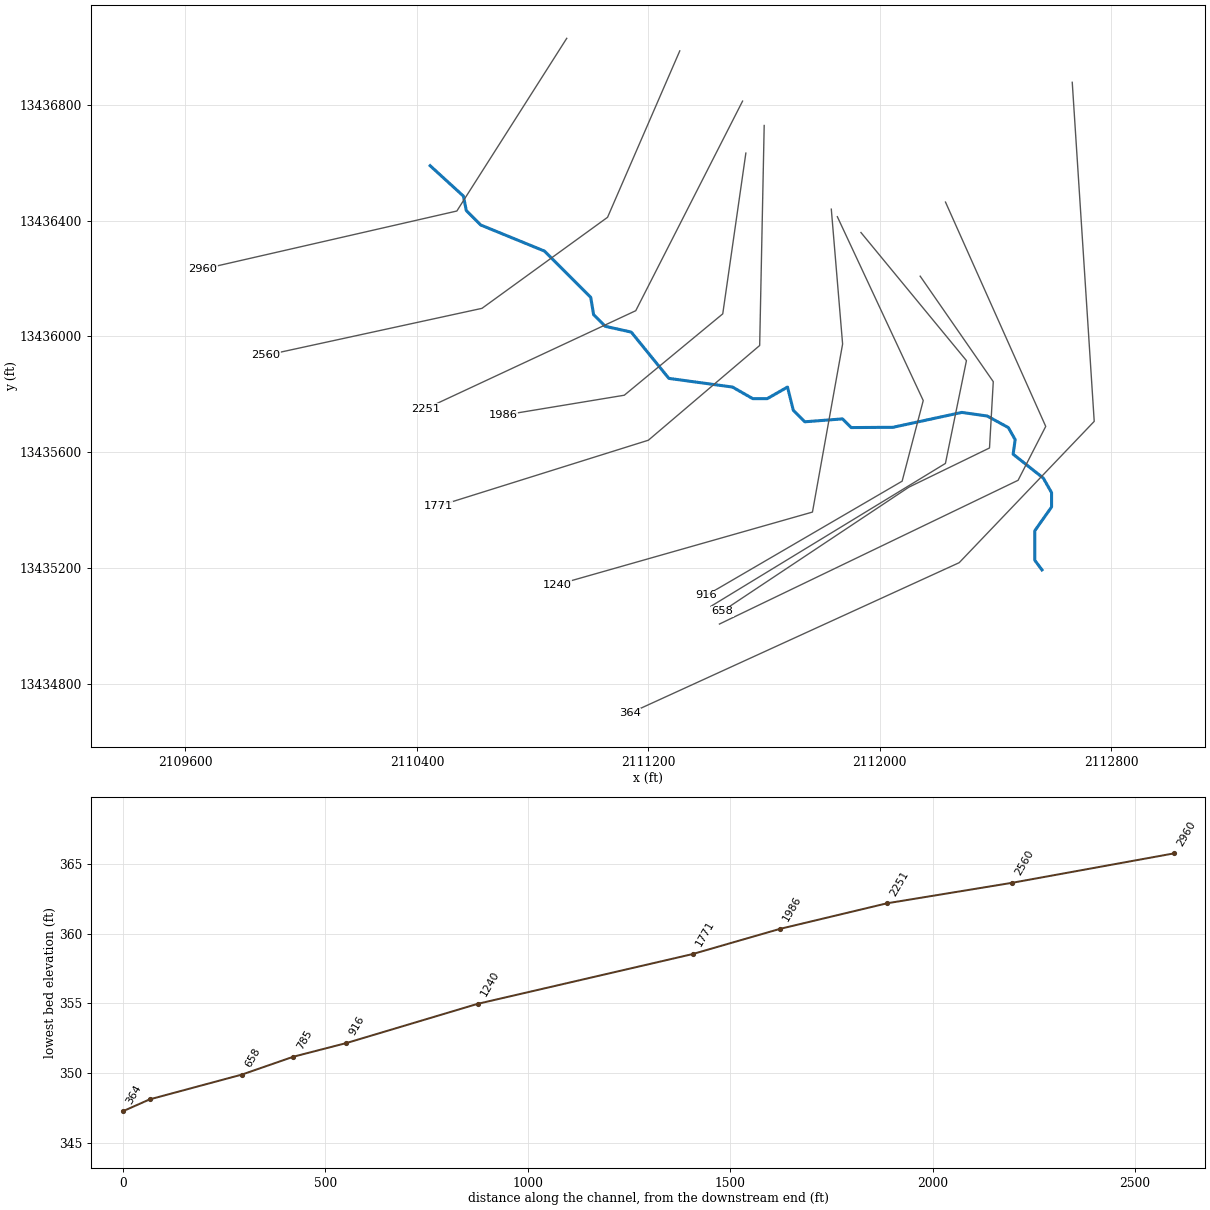
--- UNT 044 in La Jarita Watershed.prj (project) ---

Proj Title=UNT 044 in La Jarita Watershed Base Level Engineering
Current Plan=p01
Default Exp/Contr=0.3,0.1
English Units
Geom File=g01
Flow File=f01
Plan File=p01
BEGIN DESCRIPTION:
UNT 044 in La Jarita Watershed
END DESCRIPTION:

--- UNT 044 in La Jarita Watershed.p01 (plan) ---

Plan Title=Multiple Run
Short Identifier=Multiple
Geom File=g01
Flow File=f01
Subcritical Flow
K Sum by GR= 0
Std Step Tol= 0.01
Critical Tol= 0.01
Num of Std Step Trials= 20
Max Error Tol= 0.3
Flow Tol Ratio= 0.001
Split Flow NTrial= 30
Split Flow Tol= 0.02
Split Flow Ratio= 0.02
Log Output Level= 0
Friction Slope Method= 1
Unsteady Friction Slope Method= 2
Unsteady Bridges Friction Slope Method= 1
Parabolic Critical Depth
Global Vel Dist=  1 , 1 , 1
Global Log Level= 0
CheckData=True
Encroach Param= -1, 0, 0, 0
BEGIN DESCRIPTION:
Multiple Run
END DESCRIPTION:

--- UNT 044 in La Jarita Watershed.f01 (steady flow) ---

Flow Title=Multiple
Number of Profiles=7
Profile Names=10-year,25-year,50-year,1pct_min,100-year,1pct_plu,500-year
River Rch & RM= UNT 044 in La Ja,Reach-1,2960
      49      61      70      40      80     160     106
Boundary for River Rch & Prof#=UNT 044 in La Ja,Reach-1,1
Up Type=0
Dn Type=3
Dn Slope=0.005
Boundary for River Rch & Prof#=UNT 044 in La Ja,Reach-1,2
Up Type=0
Dn Type=3
Dn Slope=0.005
Boundary for River Rch & Prof#=UNT 044 in La Ja,Reach-1,3
Up Type=0
Dn Type=3
Dn Slope=0.005
Boundary for River Rch & Prof#=UNT 044 in La Ja,Reach-1,4
Up Type=0
Dn Type=3
Dn Slope=0.005
Boundary for River Rch & Prof#=UNT 044 in La Ja,Reach-1,5
Up Type=0
Dn Type=3
Dn Slope=0.005
Boundary for River Rch & Prof#=UNT 044 in La Ja,Reach-1,6
Up Type=0
Dn Type=3
Dn Slope=0.005
Boundary for River Rch & Prof#=UNT 044 in La Ja,Reach-1,7
Up Type=0
Dn Type=3
Dn Slope=0.005

--- UNT 044 in La Jarita Watershed.g01 (geometry) ---

Geom Title=Existing Conditions

River Reach=UNT 044 in La Ja,Reach-1
Reach XY= 30
      2110445.80     13436589.54      2110560.80     13436484.54
      2110570.80     13436434.54      2110620.80     13436384.54
      2110840.80     13436294.54      2111000.80     13436134.54
      2111010.80     13436074.54      2111050.80     13436034.54
      2111140.80     13436014.54      2111270.80     13435854.54
      2111490.80     13435824.54      2111560.80     13435784.54
      2111610.80     13435784.54      2111680.80     13435824.54
      2111700.80     13435744.54      2111740.80     13435704.54
      2111870.80     13435714.54      2111900.80     13435684.54
      2112045.45     13435685.53      2112282.95     13435736.92
      2112370.80     13435724.54      2112444.12     13435684.52
      2112467.55     13435642.86      2112460.61     13435592.51
      2112564.78     13435510.04      2112593.42     13435459.70
      2112593.42     13435410.22      2112535.26     13435327.75
      2112535.26     13435226.19      2112560.26     13435192.56

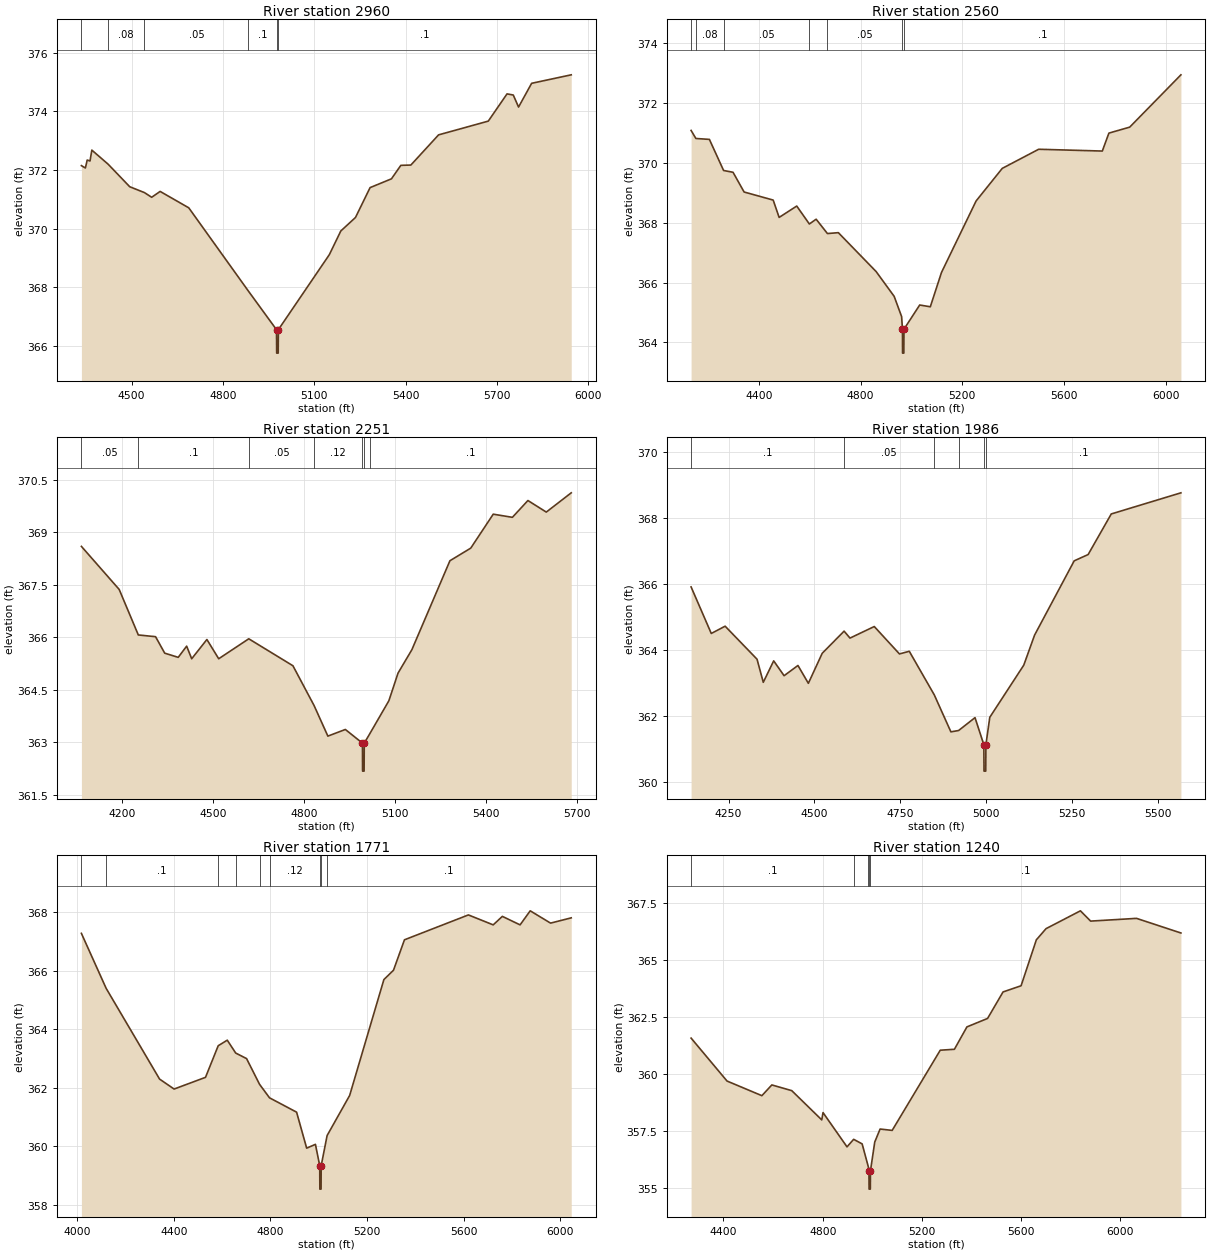
Type RM Length L Ch R = 1,2960,400,400,400
BEGIN DESCRIPTION:
UNT 044 in La Jarita Watershed 3.0
END DESCRIPTION:
XS GIS Cut Line= 3
      2110917.87     13437029.72      2110538.12     13436432.96
      2109659.50     13436231.80
#Sta/Elev= 30
  4334.9  372.15  4348.0  372.07  4353.9  372.34  4363.2  372.31  4369.2  372.68
  4422.6  372.20  4493.6  371.43  4541.9  371.23  4565.7  371.07  4593.5  371.27
  4687.5  370.71  4883.2  367.87  4975.7  366.55  4976.2  365.75  4981.2  365.75
  4981.7  366.55  5149.1  369.11  5186.9  369.92  5235.0  370.38  5283.0  371.40
  5353.2  371.70  5384.0  372.16  5416.9  372.17  5507.9  373.20  5671.2  373.67
  5732.8  374.60  5753.3  374.56  5770.6  374.15  5813.5  374.96  5943.6  375.25
#Mann=6,-1,0
  4334.9     0.1       0  4422.6    0.08       0  4541.9    0.05       0
  4883.2     0.1       0  4975.7    0.07       0  4981.7     0.1       0
Bank Sta=4975.7,4981.7
Exp/Cntr=0.3,0.1

Type RM Length L Ch R = 1,2560,309,309,309
BEGIN DESCRIPTION:
Mapping XS 8b2f2e62
END DESCRIPTION:
XS GIS Cut Line= 4
      2111308.52     13436986.36      2111058.95     13436411.26
      2110624.92     13436096.59      2109878.08     13435934.23
#Sta/Elev= 30
  4133.3  371.09  4152.2  370.82  4205.3  370.79  4261.2  369.75  4298.3  369.69
  4341.9  369.03  4456.3  368.76  4479.7  368.18  4549.0  368.56  4598.6  367.96
  4625.3  368.12  4669.8  367.64  4712.7  367.67  4861.2  366.37  4932.3  365.54
  4961.7  364.86  4964.9  364.44  4965.4  363.64  4970.4  363.64  4970.9  364.44
  5032.8  365.25  5074.5  365.19  5118.6  366.34  5254.7  368.73  5357.6  369.82
  5500.9  370.46  5751.3  370.40  5777.2  371.00  5859.1  371.20  6060.6  372.95
#Mann=7,-1,0
  4133.3    0.05       0  4152.2    0.08       0  4261.2    0.05       0
  4598.6     0.1       0  4669.8    0.05       0  4964.9    0.07       0
  4970.9     0.1       0
Bank Sta=4964.9,4970.9
Exp/Cntr=0.3,0.1

Type RM Length L Ch R = 1,2251,265,265,265
BEGIN DESCRIPTION:
UNT 044 in La Jarita Watershed 2.0
END DESCRIPTION:
XS GIS Cut Line= 3
      2111525.55     13436812.78      2111156.42     13436088.46
      2110430.49     13435749.78
#Sta/Elev= 30
  4067.0  368.59  4191.5  367.36  4254.5  366.06  4311.4  366.01  4341.5  365.54
  4386.0  365.42  4413.8  365.74  4430.4  365.38  4480.5  365.93  4519.4  365.38
  4618.5  365.95  4764.0  365.18  4833.9  364.04  4879.1  363.17  4936.7  363.36
  4993.0  362.97  4993.5  362.17  4998.5  362.17  4999.0  362.97  5016.7  363.23
  5080.1  364.18  5110.3  364.97  5156.0  365.64  5281.3  368.18  5349.9  368.54
  5424.0  369.51  5487.1  369.42  5538.3  369.90  5598.8  369.57  5681.0  370.12
#Mann=7,-1,0
  4067.0    0.05       0  4254.5     0.1       0  4618.5    0.05       0
  4833.9    0.12       0  4993.0    0.07       0  4999.0    0.12       0
  5016.7     0.1       0
Bank Sta=4993,4999
Exp/Cntr=0.3,0.1

Type RM Length L Ch R = 1,1986,215,215,215
BEGIN DESCRIPTION:
Mapping XS e627d4e1
END DESCRIPTION:
XS GIS Cut Line= 4
      2111536.91     13436633.15      2111457.05     13436077.58
      2111116.77     13435796.33      2110698.29     13435727.16
#Sta/Elev= 30
  4140.9  365.91  4199.7  364.50  4240.1  364.72  4333.0  363.72  4351.2  363.02
  4381.5  363.67  4411.8  363.22  4452.2  363.53  4482.5  362.99  4522.9  363.90
  4586.6  364.57  4603.8  364.36  4674.5  364.71  4747.9  363.88  4776.5  363.96
  4849.3  362.64  4897.7  361.52  4920.2  361.56  4968.0  361.95  4993.7  361.13
  4994.2  360.33  4999.2  360.33  4999.7  361.13  5011.0  361.96  5110.0  363.54
  5141.5  364.45  5256.9  366.70  5297.5  366.89  5364.9  368.12  5567.8  368.76
#Mann=6,-1,0
  4140.9     0.1       0  4586.6    0.05       0  4849.3    0.12       0
  4920.2     0.1       0  4993.7    0.07       0  4999.7     0.1       0
Bank Sta=4993.7,4999.7
Exp/Cntr=0.3,0.1

Type RM Length L Ch R = 1,1771,531,531,531
BEGIN DESCRIPTION:
Mapping XS 80f80f43
END DESCRIPTION:
XS GIS Cut Line= 4
      2111600.27     13436728.57      2111584.65     13435968.21
      2111200.01     13435640.86      2110472.99     13435412.99
#Sta/Elev= 30
  4017.8  367.27  4120.3  365.39  4341.4  362.29  4401.5  361.95  4531.5  362.35
  4584.1  363.43  4621.5  363.62  4656.5  363.18  4701.5  362.99  4755.3  362.11
  4796.5  361.65  4908.5  361.16  4950.2  359.93  4986.5  360.06  5004.3  359.33
  5004.8  358.53  5009.8  358.53  5010.3  359.33  5034.8  360.36  5128.1  361.73
  5269.8  365.69  5309.6  366.01  5355.0  367.05  5619.7  367.90  5722.3  367.56
  5760.2  367.85  5833.6  367.56  5875.5  368.04  5959.8  367.62  6045.3  367.80
#Mann=9,-1,0
  4017.8    0.05       0  4120.3     0.1       0  4584.1    0.05       0
  4656.5     0.1       0  4755.3    0.05       0  4796.5    0.12       0
  5004.3    0.07       0  5010.3    0.12       0  5034.8     0.1       0
Bank Sta=5004.3,5010.3
Exp/Cntr=0.3,0.1

Type RM Length L Ch R = 1,1240,324,324,324
BEGIN DESCRIPTION:
Mapping XS df1449bd
END DESCRIPTION:
XS GIS Cut Line= 4
      2111832.20     13436439.37      2111871.26     13435973.27
      2111767.09     13435392.54      2110885.31     13435141.72
#Sta/Elev= 30
  4269.4  361.57  4414.3  359.69  4554.8  359.05  4594.9  359.52  4675.2  359.27
  4796.1  357.99  4801.2  358.31  4897.9  356.81  4924.7  357.14  4958.9  356.94
  4983.5  355.95  4986.4  355.76  4986.9  354.96  4991.9  354.96  4992.4  355.76
  5009.7  357.02  5031.3  357.59  5079.9  357.53  5273.8  361.04  5330.8  361.08
  5381.3  362.06  5464.5  362.43  5526.9  363.59  5599.6  363.86  5661.1  365.87
  5700.2  366.36  5838.8  367.14  5879.9  366.69  6064.9  366.81  6243.9  366.17
#Mann=5,-1,0
  4269.4     0.1       0  4924.7    0.12       0  4983.5     0.1       0
  4986.4    0.07       0  4992.4     0.1       0
Bank Sta=4986.4,4992.4
Exp/Cntr=0.3,0.1

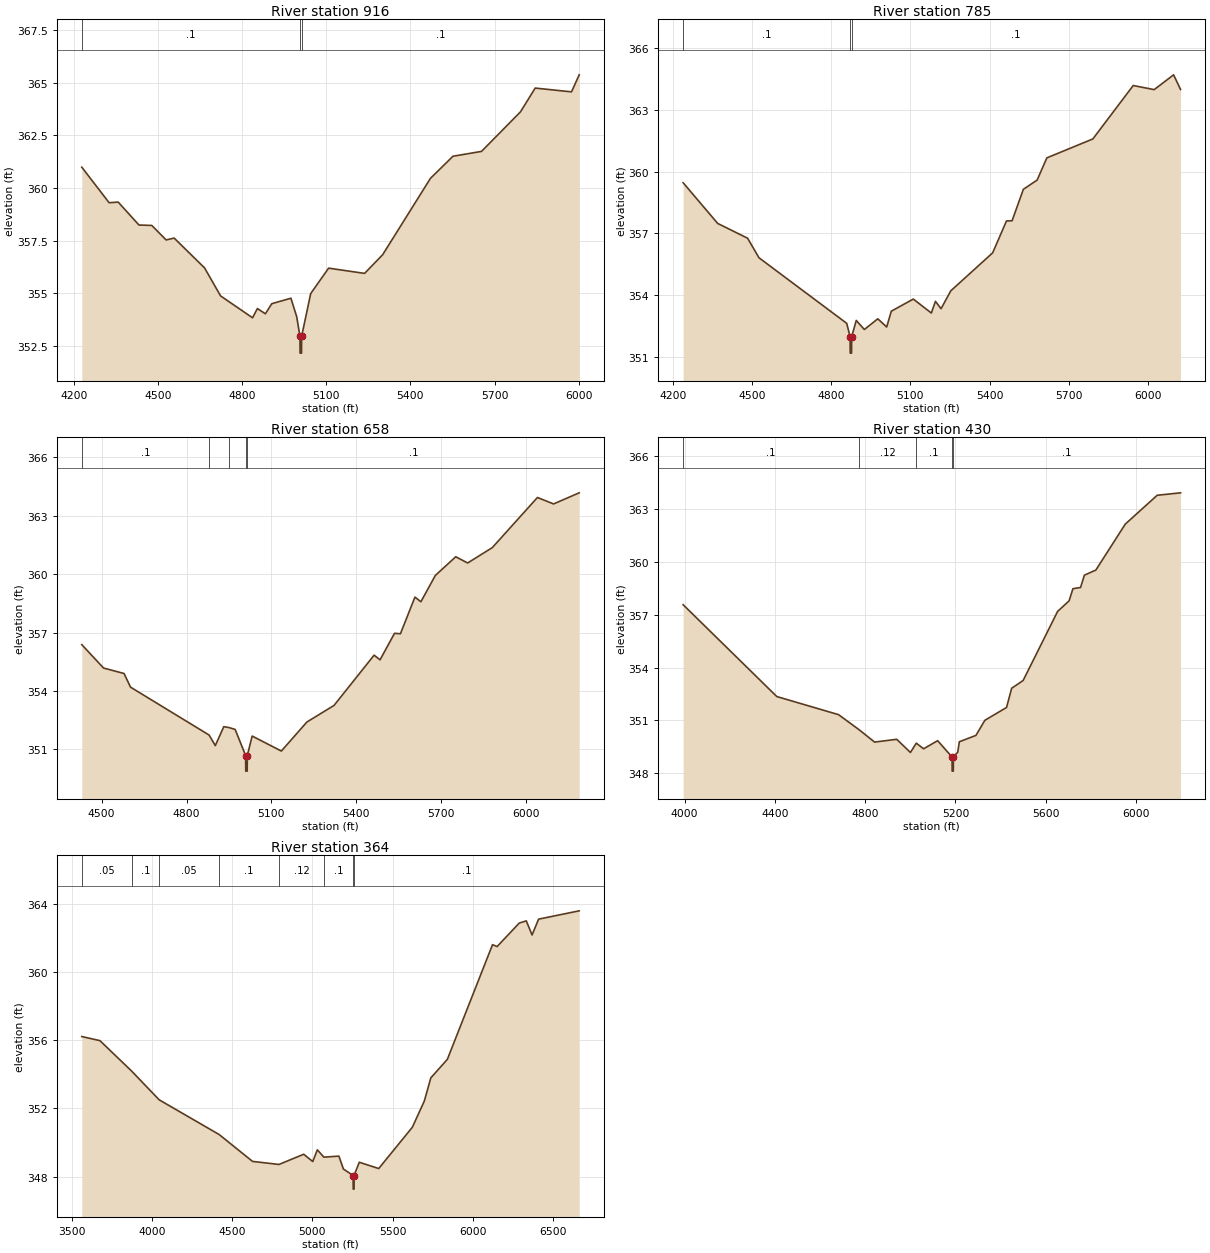
Type RM Length L Ch R = 1,916,131,131,131
BEGIN DESCRIPTION:
Mapping XS d823b30d
END DESCRIPTION:
XS GIS Cut Line= 4
      2111853.04     13436413.36      2112149.91     13435777.96
      2112076.99     13435499.31      2111399.47     13435104.36
#Sta/Elev= 30
  4228.4  360.99  4325.9  359.30  4358.2  359.33  4432.3  358.24  4478.0  358.22
  4529.2  357.53  4557.7  357.62  4666.3  356.20  4723.3  354.87  4837.3  353.83
  4854.6  354.27  4883.0  354.02  4905.9  354.50  4974.1  354.76  4994.8  353.88
  5006.3  352.95  5006.8  352.15  5011.8  352.15  5012.3  352.95  5044.6  354.98
  5108.5  356.19  5236.8  355.94  5301.3  356.83  5471.7  360.46  5552.0  361.51
  5653.7  361.74  5792.6  363.62  5845.1  364.75  5974.6  364.57  6002.0  365.38
#Mann=3,-1,0
  4228.4     0.1       0  5006.3    0.07       0  5012.3     0.1       0
Bank Sta=5006.3,5012.3
Exp/Cntr=0.3,0.1

Type RM Length L Ch R = 1,785,127,127,127
BEGIN DESCRIPTION:
Mapping XS 764c2c1a
END DESCRIPTION:
XS GIS Cut Line= 4
      2111934.65     13436358.66      2112299.21     13435915.98
      2112226.58     13435560.65      2111416.37     13435067.00
#Sta/Elev= 30
  4238.7  359.46  4369.7  357.48  4483.1  356.76  4526.1  355.81  4858.6  352.62
  4871.4  351.97  4871.9  351.17  4876.9  351.17  4877.4  351.97  4894.8  352.76
  4925.4  352.32  4976.5  352.84  5010.1  352.44  5027.5  353.21  5111.0  353.80
  5179.3  353.12  5194.8  353.69  5216.1  353.33  5252.9  354.20  5411.7  356.05
  5464.0  357.60  5485.3  357.61  5528.0  359.14  5580.2  359.59  5617.0  360.67
  5791.3  361.59  5944.3  364.19  6023.7  363.99  6097.3  364.71  6123.6  364.00
#Mann=3,-1,0
  4238.7     0.1       0  4871.4    0.07       0  4877.4     0.1       0
Bank Sta=4871.4,4877.4
Exp/Cntr=0.3,0.1

Type RM Length L Ch R = 1,658,228,228,228
BEGIN DESCRIPTION:
Mapping XS 4a369b1d
END DESCRIPTION:
XS GIS Cut Line= 5
      2112139.36     13436207.76      2112391.94     13435843.21
      2112378.92     13435614.04      2112100.27     13435478.62
      2111455.24     13435049.47
#Sta/Elev= 30
  4430.0  356.38  4506.9  355.18  4579.3  354.90  4602.2  354.20  4880.0  351.74
  4901.8  351.20  4931.8  352.17  4949.0  352.13  4971.9  352.03  5008.9  350.69
  5009.4  349.89  5014.4  349.89  5014.9  350.69  5032.0  351.69  5135.2  350.92
  5225.4  352.41  5321.2  353.26  5462.9  355.84  5483.9  355.60  5535.0  356.96
  5556.0  356.94  5607.2  358.82  5628.2  358.58  5679.3  359.93  5751.4  360.89
  5793.5  360.57  5880.7  361.36  6040.0  363.93  6097.1  363.60  6187.6  364.17
#Mann=5,-1,0
  4430.0     0.1       0  4880.0    0.12       0  4949.0     0.1       0
  5008.9    0.07       0  5014.9     0.1       0
Bank Sta=5008.9,5014.9
Exp/Cntr=0.3,0.1

Type RM Length L Ch R = 1,430,66,66,66
BEGIN DESCRIPTION:
Mapping XS 4e1c3af3
END DESCRIPTION:
XS GIS Cut Line= 4
      2112226.80     13436463.86      2112573.22     13435688.61
      2112477.73     13435502.41      2111445.59     13435005.54
#Sta/Elev= 30
  3993.5  357.57  4408.5  352.35  4682.2  351.32  4772.5  350.47  4841.9  349.76
  4939.8  349.92  5000.7  349.17  5026.5  349.70  5059.0  349.38  5121.3  349.84
  5185.1  348.91  5185.6  348.11  5190.6  348.11  5191.1  348.91  5210.3  349.19
  5217.3  349.78  5290.8  350.14  5330.5  351.00  5426.5  351.73  5449.1  352.82
  5499.9  353.26  5652.8  357.19  5703.6  357.79  5720.6  358.48  5754.4  358.55
  5771.4  359.25  5822.2  359.54  5952.5  362.15  6093.8  363.79  6197.4  363.93
#Mann=5,-1,0
  3993.5     0.1       0  4772.5    0.12       0  5026.5     0.1       0
  5185.1    0.07       0  5191.1     0.1       0
Bank Sta=5185.1,5191.1
Exp/Cntr=0.3,0.1

Type RM Length L Ch R = 1,364,0,0,0
BEGIN DESCRIPTION:
UNT 044 in La Jarita Watershed 1.0
END DESCRIPTION:
XS GIS Cut Line= 4
      2112664.86     13436877.81      2112740.81     13435705.97
      2112274.23     13435217.68      2111134.90     13434696.85
#Sta/Elev= 30
  3562.0  356.23  3675.0  355.99  3872.9  354.20  4044.7  352.51  4418.7  350.47
  4627.0  348.89  4791.7  348.71  4946.1  349.31  5002.7  348.88  5031.0  349.57
  5071.9  349.14  5165.6  349.20  5193.9  348.44  5254.4  348.06  5254.9  347.26
  5259.9  347.26  5260.4  348.06  5292.7  348.84  5414.0  348.47  5623.9  350.90
  5698.5  352.44  5739.0  353.80  5842.1  354.89  6123.8  361.63  6152.4  361.52
  6290.4  362.90  6334.4  363.03  6370.5  362.20  6411.1  363.13  6664.4  363.62
#Mann=8,-1,0
  3562.0    0.05       0  3872.9     0.1       0  4044.7    0.05       0
  4418.7     0.1       0  4791.7    0.12       0  5071.9     0.1       0
  5254.4    0.07       0  5260.4     0.1       0
Bank Sta=5254.4,5260.4
Exp/Cntr=0.3,0.1

Chan Stop Cuts=-1