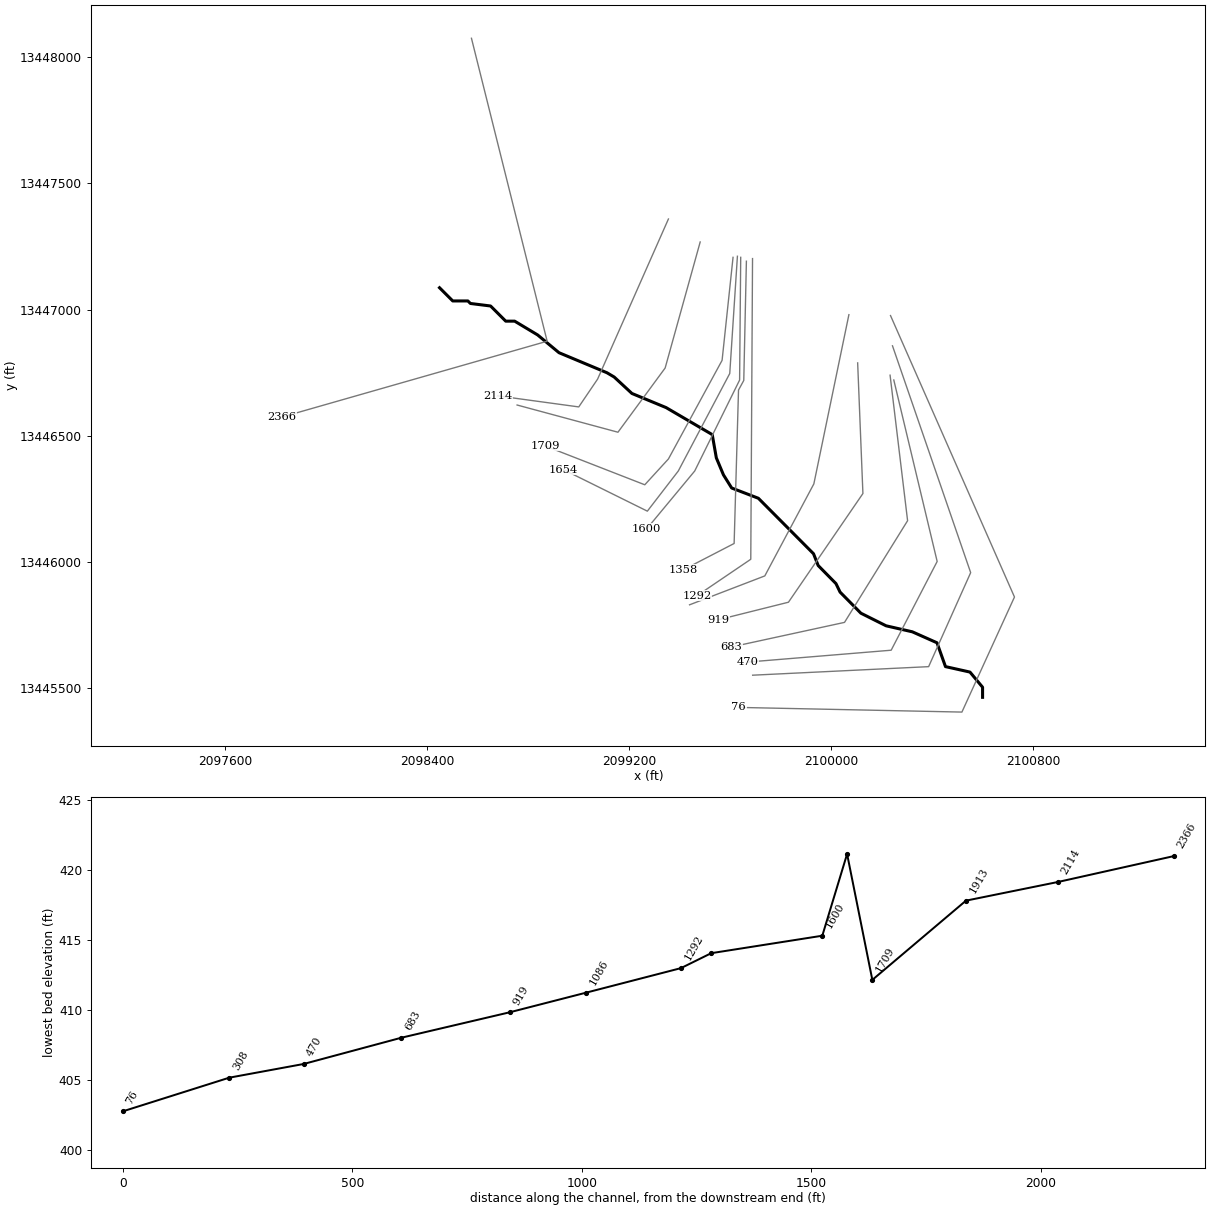
--- UNT 047 in La Jarita Watershed.prj (project) ---

Proj Title=UNT 047 in La Jarita Watershed Base Level Engineering
Current Plan=p01
Default Exp/Contr=0.3,0.1
English Units
Geom File=g01
Flow File=f01
Plan File=p01
Y Axis Title=Elevation
X Axis Title(PF)=Main Channel Distance
X Axis Title(XS)=Station
BEGIN DESCRIPTION:
UNT 047 in La Jarita Watershed
END DESCRIPTION:
DSS Export Rating Curves= 0
DSS Export Rating Curve Sorted= 0
DSS Export Volume Flow Curves= 0
DXF OffsetX= 0
DXF OffsetY= 0
DXF ScaleX= 1
DXF ScaleY= 10

--- UNT 047 in La Jarita Watershed.p01 (plan) ---

Plan Title=Multiple Run
Short Identifier=Multiple
Geom File=g01
Flow File=f01
Subcritical Flow
K Sum by GR= 0
Std Step Tol= 0.01
Critical Tol= 0.01
Num of Std Step Trials= 20
Max Error Tol= 0.3
Flow Tol Ratio= 0.001
Split Flow NTrial= 30
Split Flow Tol= 0.02
Split Flow Ratio= 0.02
Log Output Level= 0
Friction Slope Method= 1
Unsteady Friction Slope Method= 2
Unsteady Bridges Friction Slope Method= 1
Parabolic Critical Depth
Global Vel Dist=  1 , 1 , 1
Global Log Level= 0
CheckData=True
Encroach Param= -1, 0, 0, 0
BEGIN DESCRIPTION:
Multiple Run
END DESCRIPTION:

--- UNT 047 in La Jarita Watershed.f01 (steady flow) ---

Flow Title=Multiple
Number of Profiles=7
Profile Names=10-year,25-year,50-year,1pct_min,100-year,1pct_plu,500-year
River Rch & RM= UNT 047 in La Ja,Reach-1,2366
      85     110     130      77     153     305     214
River Rch & RM= UNT 047 in La Ja,Reach-1,76
     238     325     395     240     479     955     713
Boundary for River Rch & Prof#=UNT 047 in La Ja,Reach-1,1
Up Type=0
Dn Type=3
Dn Slope=0.005
Boundary for River Rch & Prof#=UNT 047 in La Ja,Reach-1,2
Up Type=0
Dn Type=3
Dn Slope=0.005
Boundary for River Rch & Prof#=UNT 047 in La Ja,Reach-1,3
Up Type=0
Dn Type=3
Dn Slope=0.005
Boundary for River Rch & Prof#=UNT 047 in La Ja,Reach-1,4
Up Type=0
Dn Type=3
Dn Slope=0.005
Boundary for River Rch & Prof#=UNT 047 in La Ja,Reach-1,5
Up Type=0
Dn Type=3
Dn Slope=0.005
Boundary for River Rch & Prof#=UNT 047 in La Ja,Reach-1,6
Up Type=0
Dn Type=3
Dn Slope=0.005
Boundary for River Rch & Prof#=UNT 047 in La Ja,Reach-1,7
Up Type=0
Dn Type=3
Dn Slope=0.005

--- UNT 047 in La Jarita Watershed.g01 (geometry) ---

Geom Title=Existing Conditions
Program Version=5.05

River Reach=UNT 047 in La Ja,Reach-1
Reach XY= 30
      2098448.43     13447086.91       2098500.8     13447034.54
       2098560.8     13447034.54       2098570.8     13447024.54
       2098650.8     13447014.54       2098710.8     13446954.54
      2098746.16     13446954.54      2098837.31     13446899.88
      2098921.94     13446829.57      2099112.05     13446750.15
      2099140.69     13446733.22        2099211.     13446668.11
      2099346.42     13446612.12      2099529.28     13446505.22
      2099545.55     13446412.99      2099573.76     13446345.72
      2099606.32     13446293.63      2099712.14     13446252.98
      2099930.75     13446033.22       2099949.2     13445986.56
      2100019.73     13445914.94        2100036.     13445881.31
      2100118.47     13445797.76      2100218.29     13445747.84
      2100322.46     13445723.97      2100420.12     13445680.57
      2100453.75     13445586.17       2100550.8     13445564.54
       2100600.8     13445504.54       2100600.8     13445464.54

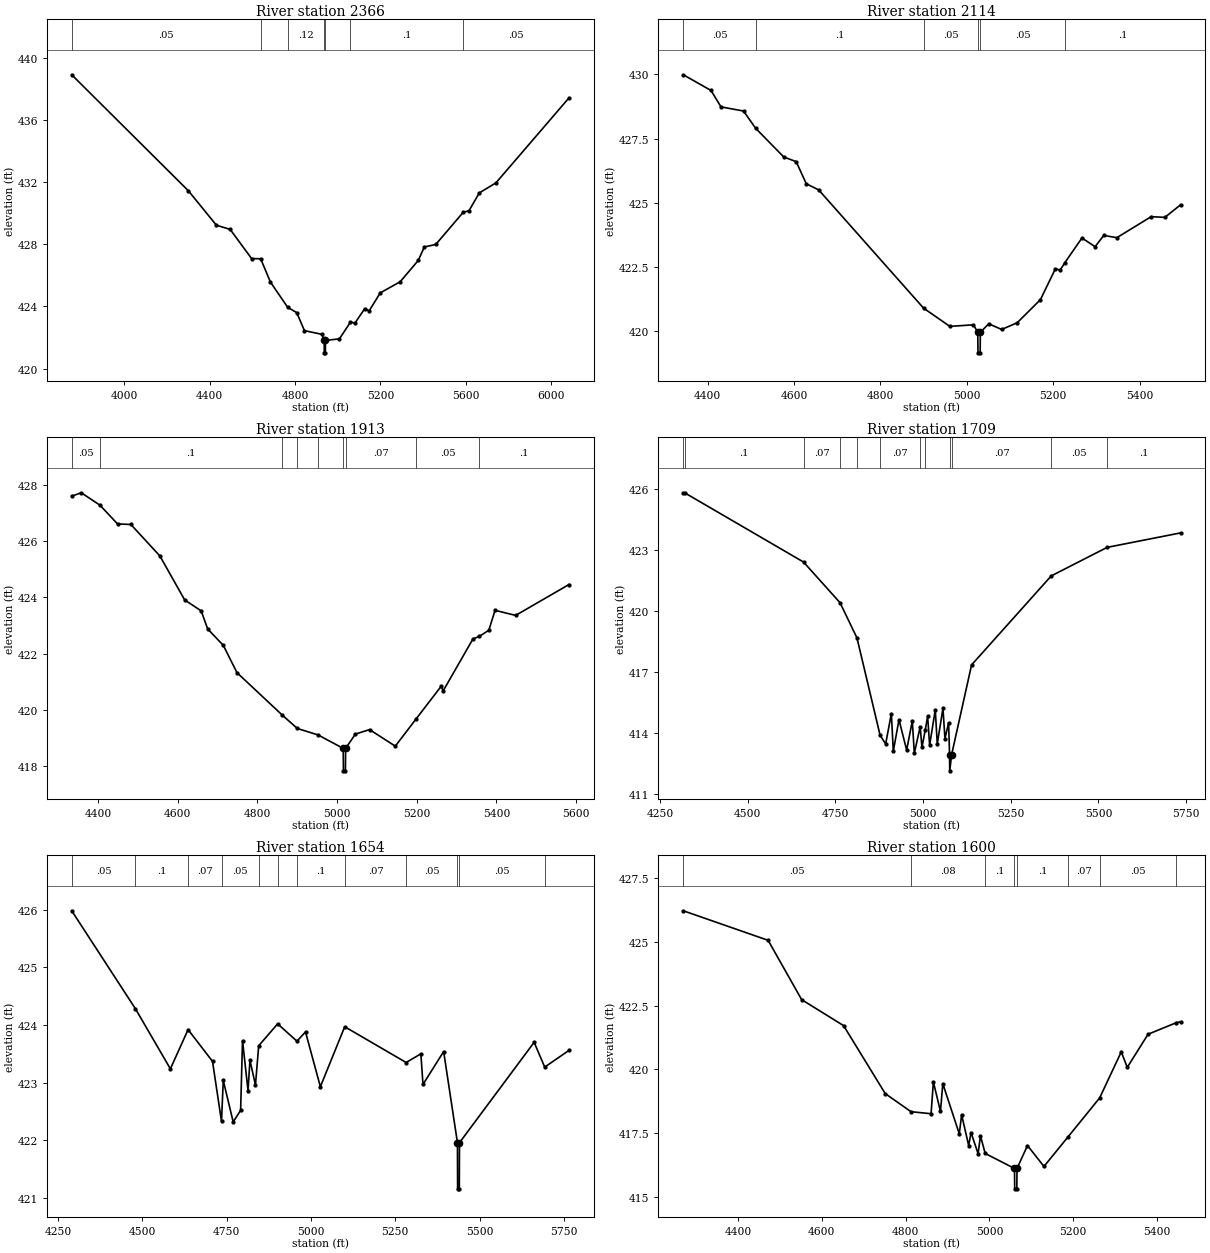
Type RM Length L Ch R = 1 ,2366    ,252,252,252
BEGIN DESCRIPTION:
UNT 047 in La Jarita Watershed 5.0
END DESCRIPTION:
XS GIS Cut Line= 3
      2098575.01     13448074.97        2098875.       13446875.
      2097825.02     13446575.01
#Sta/Elev= 30
  3754.1  438.92  4300.4  431.45  4431.8  429.23  4496.2  428.96  4596.7  427.08
  4639.2  427.07  4684.3  425.58  4765.7  423.94    4808   423.6  4844.1  422.44
  4926.6   422.2  4936.5  421.81    4937  421.01    4942  421.01  4942.5  421.81
  5007.9  421.91  5059.8  422.99  5080.7  422.93  5126.2  423.85    5147  423.71
    5199  424.87  5292.6  425.59  5377.1  426.96  5405.7  427.83    5459  427.99
    5587  430.05    5615  430.17  5663.1  431.31  5741.1  431.96    6083  437.43
#Mann= 7 ,-1 , 0
  3754.1     .05       0  4639.2      .1       0  4765.7     .12       0
  4936.5     .07       0  4942.5     .12       0  5059.8      .1       0
    5587     .05       0
Bank Sta=4936.5,4942.5
XS Rating Curve= 0 ,0
Exp/Cntr=0.3,0.1

Type RM Length L Ch R = 1 ,2114    ,201,201,201
BEGIN DESCRIPTION:
UNT 047 in La Jarita Watershed 4.0
END DESCRIPTION:
XS GIS Cut Line= 4
      2099355.67     13447359.16        2099075.       13446725.
      2099000.25     13446614.79      2098678.89     13446658.64
#Sta/Elev= 30
    4344  429.98  4408.1  429.37  4431.3  428.73  4483.4  428.57  4511.3   427.9
  4576.6  426.78  4605.3   426.6  4628.6  425.74  4657.4   425.5  4900.1   420.9
  4960.9  420.19  5015.6  420.25  5025.6  419.96  5026.1  419.16  5031.1  419.16
  5031.6  419.96    5051  420.29  5080.9  420.07  5116.8  420.33  5170.7  421.23
  5205.2  422.43  5216.3  422.38  5226.8  422.66  5266.8  423.63  5297.1  423.29
  5317.3  423.73  5347.5  423.64  5427.1  424.46  5458.6  424.43    5495  424.92
#Mann= 6 ,-1 , 0
    4344     .05       0  4511.3      .1       0  4900.1     .05       0
  5025.6    .035       0  5031.6     .05       0  5226.8      .1       0
Bank Sta=5025.6,5031.6
XS Rating Curve= 0 ,0
Exp/Cntr=0.3,0.1

Type RM Length L Ch R = 1 ,1913    ,204,204,204
BEGIN DESCRIPTION:
Mapping XS cb9170e7
END DESCRIPTION:
XS GIS Cut Line= 4
      2099481.56     13447268.09      2099342.67     13446768.91
      2099155.64     13446514.57      2098755.86     13446622.34
#Sta/Elev= 30
  4334.1  427.61  4358.1  427.73  4404.8  427.29  4449.1  426.62  4482.6   426.6
  4555.3  425.48  4617.6  423.91  4659.1  423.52  4675.2  422.88  4714.6  422.29
  4748.8  421.32    4863   419.8  4900.3  419.33  4952.3   419.1  5015.5  418.62
    5016  417.82    5021  417.82  5021.5  418.62    5046  419.13  5081.5  419.29
  5146.2   418.7  5197.8  419.66  5261.1  420.83  5266.3  420.67    5341  422.52
  5356.7  422.61  5380.9  422.83  5396.5  423.54  5448.2  423.36    5582  424.46
#Mann= 9 ,-1 , 0
  4334.1     .05       0  4404.8      .1       0    4863     .07       0
  4900.3     .05       0  4952.3     .07       0  5015.5     .07       0
  5021.5     .07       0  5197.8     .05       0  5356.7      .1       0
Bank Sta=5015.5,5021.5
XS Rating Curve= 0 ,0
Exp/Cntr=0.3,0.1

Type RM Length L Ch R = 1 ,1709    ,55,55,55
BEGIN DESCRIPTION:
Mapping XS 8bc38655
END DESCRIPTION:
XS GIS Cut Line= 5
      2099611.76     13447207.27      2099568.36      13446799.3
      2099355.69     13446408.67      2099261.95     13446306.41
      2098866.34     13446460.45
#Sta/Elev= 30
    4316   425.8  4320.7  425.79  4658.9   422.4  4763.2   420.4  4811.4  418.67
  4877.4  413.89  4893.2  413.47  4909.4  414.96    4915  413.12  4931.2  414.66
    4953  413.17  4969.2   414.6  4974.9  413.01  4991.6  414.31  4996.7   413.3
    5006  414.15  5012.9  414.82  5018.6  413.41  5034.7  415.15  5040.4  413.47
  5056.6  415.22  5062.3  413.73  5072.7  414.51  5075.4  412.95  5075.9  412.15
  5081.4  412.95  5138.2  417.35  5365.5  421.72  5524.9  423.12  5734.3  423.83
#Mann= 12 ,-1 , 0
    4316     .05       0  4320.7      .1       0  4658.9     .07       0
  4763.2     .05       0  4811.4      .1       0  4877.4     .07       0
  4991.6      .1       0    5006     .07       0  5075.4     .07       0
  5081.4     .07       0  5365.5     .05       0  5524.9      .1       0
Bank Sta=5075.4,5081.4
XS Rating Curve= 0 ,0
Exp/Cntr=0.3,0.1

Type RM Length L Ch R = 1 ,1654    ,54,54,54
BEGIN DESCRIPTION:
Mapping XS 713c4db9
END DESCRIPTION:
XS GIS Cut Line= 5
      2099629.12     13447211.62      2099598.74     13446747.21
      2099394.75     13446360.93      2099272.18     13446201.92
       2098939.1     13446366.66
#Sta/Elev= 30
  4290.4  425.98  4479.5  424.28    4583  423.24  4635.5  423.92  4707.9  423.37
  4734.6  422.33  4739.8  423.04  4769.2  422.32  4791.3  422.52  4796.9  423.73
  4813.3  422.86  4818.9  423.39  4835.3  422.96  4844.9  423.64  4901.1  424.02
  4958.3  423.72  4983.7  423.88  5027.8  422.93    5100  423.97  5282.2  423.35
  5325.8   423.5  5332.1  422.97  5393.4  423.54  5434.3  421.96  5434.8  421.16
  5439.8  421.16  5440.3  421.96  5661.7   423.7  5693.1  423.27    5765  423.56
#Mann= 12 ,-1 , 0
  4290.4     .05       0  4479.5      .1       0  4635.5     .07       0
  4734.6     .05       0  4844.9     .08       0  4901.1     .07       0
  4958.3      .1       0    5100     .07       0  5282.2     .05       0
  5434.3     .07       0  5440.3     .05       0  5693.1      .1       0
Bank Sta=5434.3,5440.3
XS Rating Curve= 0 ,0
Exp/Cntr=0.3,0.1

Type RM Length L Ch R = 1 ,1600    ,242,242,242
BEGIN DESCRIPTION:
Mapping XS 975903b1
END DESCRIPTION:
XS GIS Cut Line= 4
      2099642.14     13447207.31       2099637.8     13446721.17
      2099459.85     13446360.93      2099269.41     13446131.53
#Sta/Elev= 30
  4269.9  426.23  4472.2  425.07  4552.2  422.74  4652.2  421.72  4751.6  419.05
    4813  418.34  4860.9  418.26  4866.4  419.51  4883.3  418.35  4888.9  419.44
  4928.2  417.47  4933.8  418.22  4950.6  417.01  4956.2  417.52  4973.1  416.69
  4978.7  417.39    4990   416.7  5059.9  416.11  5060.4  415.31  5065.4  415.31
  5065.9  416.11  5090.9  417.01  5130.2  416.19  5187.1  417.34    5263  418.88
  5314.6  420.69  5328.9  420.08  5378.4  421.38    5445  421.83    5456  421.87
#Mann= 8 ,-1 , 0
  4269.9     .05       0    4813     .08       0    4990      .1       0
  5059.9     .07       0  5065.9      .1       0  5187.1     .07       0
    5263     .05       0    5445      .1       0
Bank Sta=5059.9,5065.9
XS Rating Curve= 0 ,0
Exp/Cntr=0.3,0.1

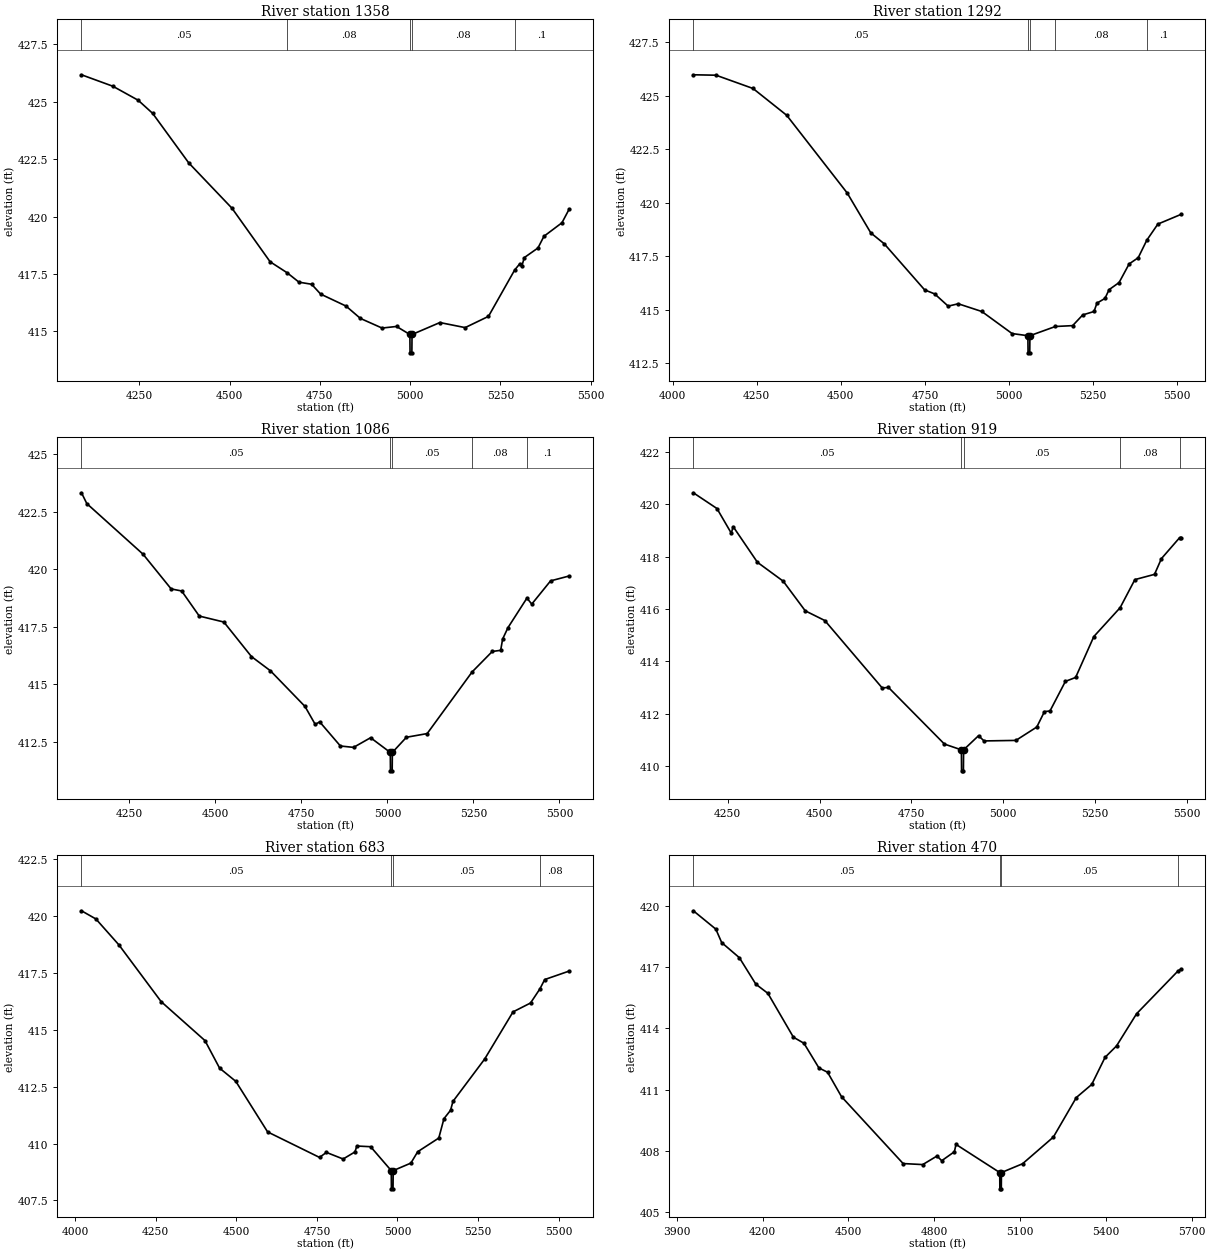
Type RM Length L Ch R = 1 ,1358    ,66,66,66
BEGIN DESCRIPTION:
Mapping XS eb8c2900
END DESCRIPTION:
XS GIS Cut Line= 5
      2099664.71     13447191.94       2099654.3      13446719.7
      2099633.46      13446681.5       2099616.1     13446073.86
      2099414.97     13445969.83
#Sta/Elev= 30
    4090  426.18    4177  425.68    4247  425.07    4287   424.5    4387  422.34
    4507  420.36  4612.4  418.03  4659.6  417.55  4692.4  417.14  4727.3  417.05
  4752.4  416.62  4822.5   416.1  4862.5  415.56  4922.5  415.14  4962.5  415.21
  4999.5  414.86    5000  414.06    5005  414.06  5005.5  414.86  5082.6  415.38
  5152.6  415.16  5217.2  415.65  5289.7  417.67  5304.3  417.95    5310  417.86
  5316.3  418.21  5354.2  418.63  5370.8  419.14  5420.7  419.73  5440.2  420.31
#Mann= 5 ,-1 , 0
    4090     .05       0  4659.6     .08       0  4999.5     .07       0
  5005.5     .08       0  5289.7      .1       0
Bank Sta=4999.5,5005.5
XS Rating Curve= 0 ,0
Exp/Cntr=0.3,0.1

Type RM Length L Ch R = 1 ,1292    ,206,206,206
BEGIN DESCRIPTION:
Mapping XS 8435d853
END DESCRIPTION:
XS GIS Cut Line= 3
      2099689.02     13447202.35      2099682.07     13446011.36
       2099468.4     13445866.61
#Sta/Elev= 30
  4061.6  425.97    4129  425.95    4239  425.33    4339  424.08    4519  420.45
    4589  418.59    4629  418.08    4749  415.93    4779  415.74    4819  415.17
    4849  415.28    4919  414.92    5009  413.89    5056  413.79  5056.5  412.99
  5061.5  412.99    5062  413.79  5137.7  414.22    5189  414.26    5219  414.76
  5252.6  414.92  5261.2  415.31    5285  415.53  5297.4  415.94    5327  416.27
  5356.9  417.14  5383.9  417.43  5409.5  418.25  5442.3     419  5510.7  419.45
#Mann= 5 ,-1 , 0
  4061.6     .05       0    5056     .03       0    5062     .05       0
  5137.7     .08       0  5409.5      .1       0
Bank Sta=5056,5062
XS Rating Curve= 0 ,0
Exp/Cntr=0.3,0.1

Type RM Length L Ch R = 1 ,1086    ,167,167,167
BEGIN DESCRIPTION:
Mapping XS 94e872b8
END DESCRIPTION:
XS GIS Cut Line= 4
      2100070.97     13446980.15      2099932.07     13446309.97
      2099737.63     13445945.39      2099439.54     13445831.01
#Sta/Elev= 30
  4110.9  423.33  4126.4  422.86  4289.8  420.66  4371.5  419.15  4402.1  419.06
  4453.2  417.97  4524.7  417.71  4604.8  416.21  4660.1  415.59  4760.5  414.04
  4790.2  413.26  4803.2  413.37  4863.4  412.32  4901.6  412.26  4951.2  412.68
  5008.4  412.04  5008.9  411.24  5013.9  411.24  5014.4  412.04  5055.3   412.7
  5115.6  412.86  5246.2  415.54  5304.8  416.43  5329.2  416.48  5334.9  416.97
  5350.6  417.47  5405.5  418.75  5419.6  418.49  5474.3   419.5  5527.8  419.71
#Mann= 5 ,-1 , 0
  4110.9     .05       0  5008.4     .03       0  5014.4     .05       0
  5246.2     .08       0  5405.5      .1       0
Bank Sta=5008.4,5014.4
XS Rating Curve= 0 ,0
Exp/Cntr=0.3,0.1

Type RM Length L Ch R = 1 ,919     ,236,236,236
BEGIN DESCRIPTION:
Mapping XS 6af4d685
END DESCRIPTION:
XS GIS Cut Line= 4
      2100105.68     13446789.17      2100126.52     13446271.78
      2099831.38     13445841.22      2099553.64     13445771.79
#Sta/Elev= 30
  4156.8  420.43    4221  419.83    4260  418.89  4265.1  419.14  4331.1  417.78
  4401.2  417.06  4461.2  415.93  4514.4  415.56  4670.5  412.99  4687.5  413.01
  4839.8  410.85  4885.9  410.63  4886.4  409.83  4891.4  409.83  4891.9  410.63
  4932.6  411.17  4947.5  410.97  5034.1  410.99    5091   411.5  5111.9  412.09
  5126.8  412.11  5168.8  413.24  5196.6  413.39  5246.2  414.95  5317.7  416.05
  5357.8  417.12  5411.2  417.32    5430  417.92  5479.6  418.72  5482.9  418.72
#Mann= 5 ,-1 , 0
  4156.8     .05       0  4885.9     .03       0  4891.9     .05       0
  5317.7     .08       0  5479.6      .1       0
Bank Sta=4885.9,4891.9
XS Rating Curve= 0 ,0
Exp/Cntr=0.3,0.1

Type RM Length L Ch R = 1 ,683     ,213,213,213
BEGIN DESCRIPTION:
Mapping XS 73607ecf
END DESCRIPTION:
XS GIS Cut Line= 4
      2100234.16     13446740.51       2100303.6     13446164.14
       2100053.6     13445761.36      2099605.72     13445664.15
#Sta/Elev= 30
  4019.4  420.22  4064.2  419.86  4135.7  418.72  4266.7  416.23  4402.6  414.52
    4448  413.31  4498.3  412.73    4597  410.51  4758.1  409.39  4779.4  409.61
  4831.4  409.32    4868  409.63  4873.9  409.89  4916.7  409.86  4980.7  408.81
  4981.2  408.01  4986.2  408.01  4986.7  408.81  5041.6  409.14  5062.8  409.64
  5128.2  410.24  5144.2  411.09  5164.7  411.46  5172.2  411.85  5270.6  413.71
  5358.6  415.78  5412.9  416.17    5442  416.79  5456.9   417.2  5532.3  417.57
#Mann= 4 ,-1 , 0
  4019.4     .05       0  4980.7     .03       0  4986.7     .05       0
    5442     .08       0
Bank Sta=4980.7,4986.7
XS Rating Curve= 0 ,0
Exp/Cntr=0.3,0.1

Type RM Length L Ch R = 1 ,470     ,162,162,162
BEGIN DESCRIPTION:
Mapping XS 2fff975f
END DESCRIPTION:
XS GIS Cut Line= 4
      2100248.92     13446721.42      2100420.79     13446002.68
       2100238.5     13445651.12      2099670.75     13445604.24
#Sta/Elev= 30
  3957.7  419.77  4036.3  418.87  4056.8  418.21  4118.5  417.47  4176.2  416.17
  4218.3  415.72  4307.5  413.57  4344.5  413.27  4396.8  412.06    4427  411.85
  4475.8  410.65  4691.2  407.37  4759.8  407.32  4809.7  407.74  4826.2  407.51
  4870.5  407.95  4876.1  408.31    5029  406.93  5029.5  406.13  5034.5  406.13
    5035  406.93  5108.8  407.36  5216.6  408.67  5296.9  410.61  5350.7  411.25
  5397.3  412.58  5437.4  413.14  5507.6  414.72  5651.2   416.8  5662.4  416.91
#Mann= 4 ,-1 , 0
  3957.7     .05       0    5029     .03       0    5035     .05       0
  5651.2     .08       0
Bank Sta=5029,5035
XS Rating Curve= 0 ,0
Exp/Cntr=0.3,0.1

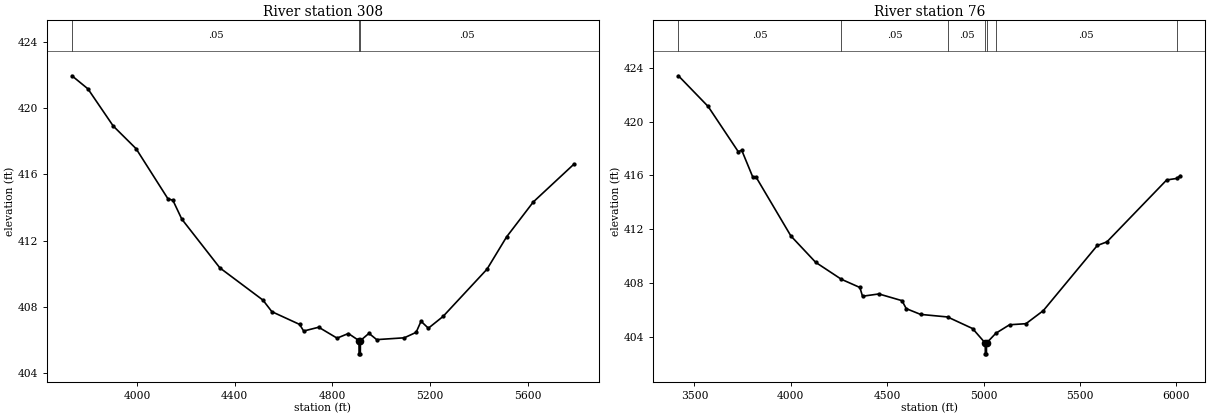
Type RM Length L Ch R = 1 ,308     ,232,232,232
BEGIN DESCRIPTION:
Mapping XS 3b325a0d
END DESCRIPTION:
XS GIS Cut Line= 4
      2100243.72     13446856.82       2100553.6     13445958.41
      2100386.94     13445586.02       2099689.5     13445552.18
#Sta/Elev= 30
  3732.8  421.97  3798.2  421.18    3902  418.93  3995.6  417.56  4126.1  414.53
  4146.4  414.44  4182.9   413.3  4338.9  410.35  4515.5   408.4    4552   407.7
  4665.6  406.93  4682.3  406.53    4744  406.76  4819.1   406.1  4865.5  406.38
  4908.9  405.95  4909.4  405.15  4914.4  405.15  4914.9  405.95  4949.8  406.39
  4981.5  406.01  5094.6  406.12  5143.1  406.45  5163.2  407.12  5193.2   406.7
  5253.3  407.41  5433.5  410.27  5513.6  412.22  5623.4  414.34  5789.4  416.62
#Mann= 3 ,-1 , 0
  3732.8     .05       0  4908.9    .035       0  4914.9     .05       0
Bank Sta=4908.9,4914.9
XS Rating Curve= 0 ,0
Exp/Cntr=0.3,0.1

Type RM Length L Ch R = 1 ,76      ,0,0,0
BEGIN DESCRIPTION:
UNT 047 in La Jarita Watershed 1.0
END DESCRIPTION:
XS GIS Cut Line= 4
      2100235.89     13446976.66      2100727.21      13445861.8
      2100518.88     13445406.07      2099634.29     13445424.56
#Sta/Elev= 30
  3416.7   423.4  3570.9  421.12  3727.2  417.76  3745.1  417.87  3802.7  415.87
  3820.5  415.85  4000.2   411.5  4128.8  409.54  4262.2  408.28  4358.3  407.67
  4371.9  407.02  4456.7  407.19  4576.9  406.69  4598.7   406.1  4673.2  405.67
  4813.2  405.48  4942.9  404.62  5008.7  403.54  5009.2  402.74  5014.8  402.74
  5015.3  403.54  5063.8  404.27  5134.8   404.9    5220  404.98    5310  405.95
  5590.1  410.79  5640.1  411.06  5950.2  415.66  6001.2  415.77  6020.9  415.97
#Mann= 7 ,-1 , 0
  3416.7     .05       0  4262.2     .05       0  4813.2     .05       0
  5008.7     .03       0  5015.3     .05       0  5063.8     .05       0
  6001.2     .05       0
Bank Sta=5008.7,5015.3
XS Rating Curve= 0 ,0
Exp/Cntr=0.3,0.1
LCMann Table=0

Chan Stop Cuts=-1
Use User Specified Reach Order=0
Composite Channel Slope=5