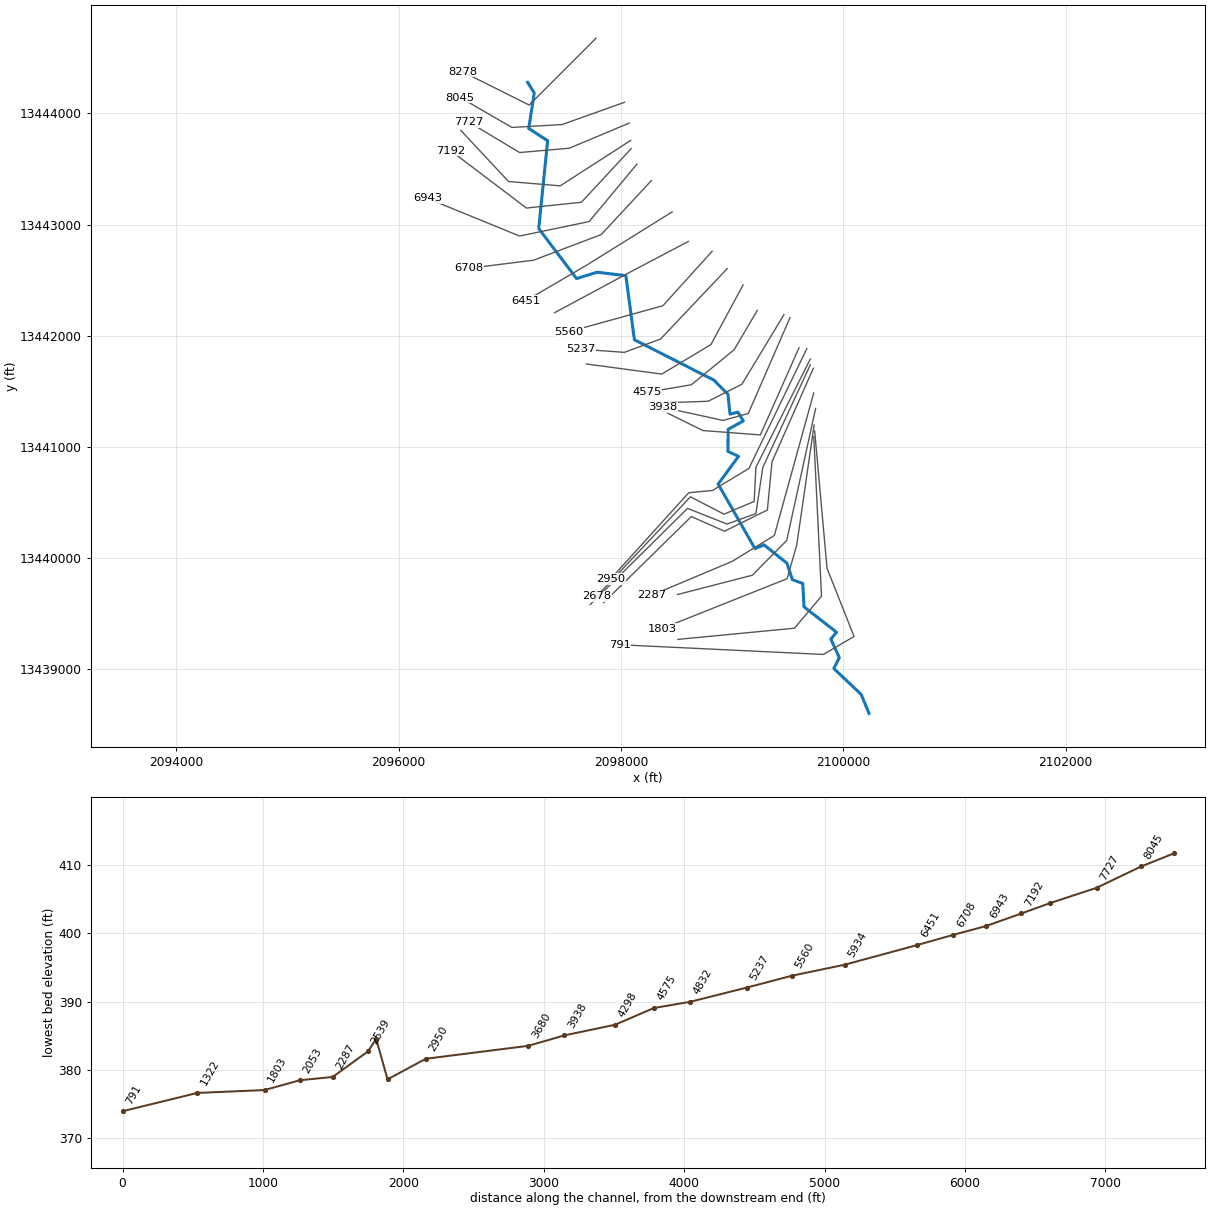
--- UNT 050 in La Jarita Watershed.prj (project) ---

Proj Title=UNT 050 in La Jarita Watershed Base Level Engineering
Current Plan=p01
Default Exp/Contr=0.3,0.1
English Units
Geom File=g01
Flow File=f01
Plan File=p01
Y Axis Title=Elevation
X Axis Title(PF)=Main Channel Distance
X Axis Title(XS)=Station
BEGIN DESCRIPTION:
UNT 050 in La Jarita Watershed
END DESCRIPTION:
DSS Export Rating Curves= 0
DSS Export Rating Curve Sorted= 0
DSS Export Volume Flow Curves= 0
DXF OffsetX= 0
DXF OffsetY= 0
DXF ScaleX= 1
DXF ScaleY= 10

--- UNT 050 in La Jarita Watershed.p01 (plan) ---

Plan Title=Multiple Run
Short Identifier=Multiple
Geom File=g01
Flow File=f01
Subcritical Flow
K Sum by GR= 0
Std Step Tol= 0.01
Critical Tol= 0.01
Num of Std Step Trials= 20
Max Error Tol= 0.3
Flow Tol Ratio= 0.001
Split Flow NTrial= 30
Split Flow Tol= 0.02
Split Flow Ratio= 0.02
Log Output Level= 0
Friction Slope Method= 1
Unsteady Friction Slope Method= 2
Unsteady Bridges Friction Slope Method= 1
Parabolic Critical Depth
Global Vel Dist=  1 , 1 , 1
Global Log Level= 0
CheckData=True
Encroach Param= -1, 0, 0, 0
BEGIN DESCRIPTION:
Multiple Run
END DESCRIPTION:

--- UNT 050 in La Jarita Watershed.f01 (steady flow) ---

Flow Title=Multiple
Number of Profiles=7
Profile Names=10-year,25-year,50-year,1pct_min,100-year,1pct_plu,500-year
River Rch & RM= UNT 050 in La Ja,Reach-1,8278
     110     145     173     103     205     409     293
River Rch & RM= UNT 050 in La Ja,Reach-1,6943
     132     176     210     126     251     501     364
River Rch & RM= UNT 050 in La Ja,Reach-1,2678
     229     316     386     236     471     939     709
Boundary for River Rch & Prof#=UNT 050 in La Ja,Reach-1,1
Up Type=0
Dn Type=3
Dn Slope=0.005
Boundary for River Rch & Prof#=UNT 050 in La Ja,Reach-1,2
Up Type=0
Dn Type=3
Dn Slope=0.005
Boundary for River Rch & Prof#=UNT 050 in La Ja,Reach-1,3
Up Type=0
Dn Type=3
Dn Slope=0.005
Boundary for River Rch & Prof#=UNT 050 in La Ja,Reach-1,4
Up Type=0
Dn Type=3
Dn Slope=0.005
Boundary for River Rch & Prof#=UNT 050 in La Ja,Reach-1,5
Up Type=0
Dn Type=3
Dn Slope=0.005
Boundary for River Rch & Prof#=UNT 050 in La Ja,Reach-1,6
Up Type=0
Dn Type=3
Dn Slope=0.005
Boundary for River Rch & Prof#=UNT 050 in La Ja,Reach-1,7
Up Type=0
Dn Type=3
Dn Slope=0.005

--- UNT 050 in La Jarita Watershed.g01 (geometry) ---

Geom Title=Existing Conditions
Program Version=5.05

River Reach=UNT 050 in La Ja,Reach-1
Reach XY= 30
       2097160.8     13444279.28       2097220.8     13444184.54
       2097170.8     13443864.54       2097340.8     13443754.54
       2097260.8     13442964.54       2097600.8     13442514.54
      2097786.83     13442571.85      2098044.64      13442540.6
       2098120.8     13441964.54      2098837.61     13441600.49
      2098962.61     13441474.19       2098980.8     13441294.54
       2099050.8     13441314.54       2099100.8     13441234.54
      2098963.91     13441159.09      2098962.61     13440959.87
      2099057.66      13440915.6      2098874.43     13440666.68
      2099205.38     13440086.17      2099286.76     13440119.81
      2099492.92     13439954.88      2099541.75     13439807.31
      2099635.06     13439772.58        2099647.     13439562.08
      2099938.88     13439334.22      2099887.88     13439273.45
      2099963.84     13439105.27      2099913.93      13439008.7
       2100160.8     13438774.54       2100230.8     13438604.54

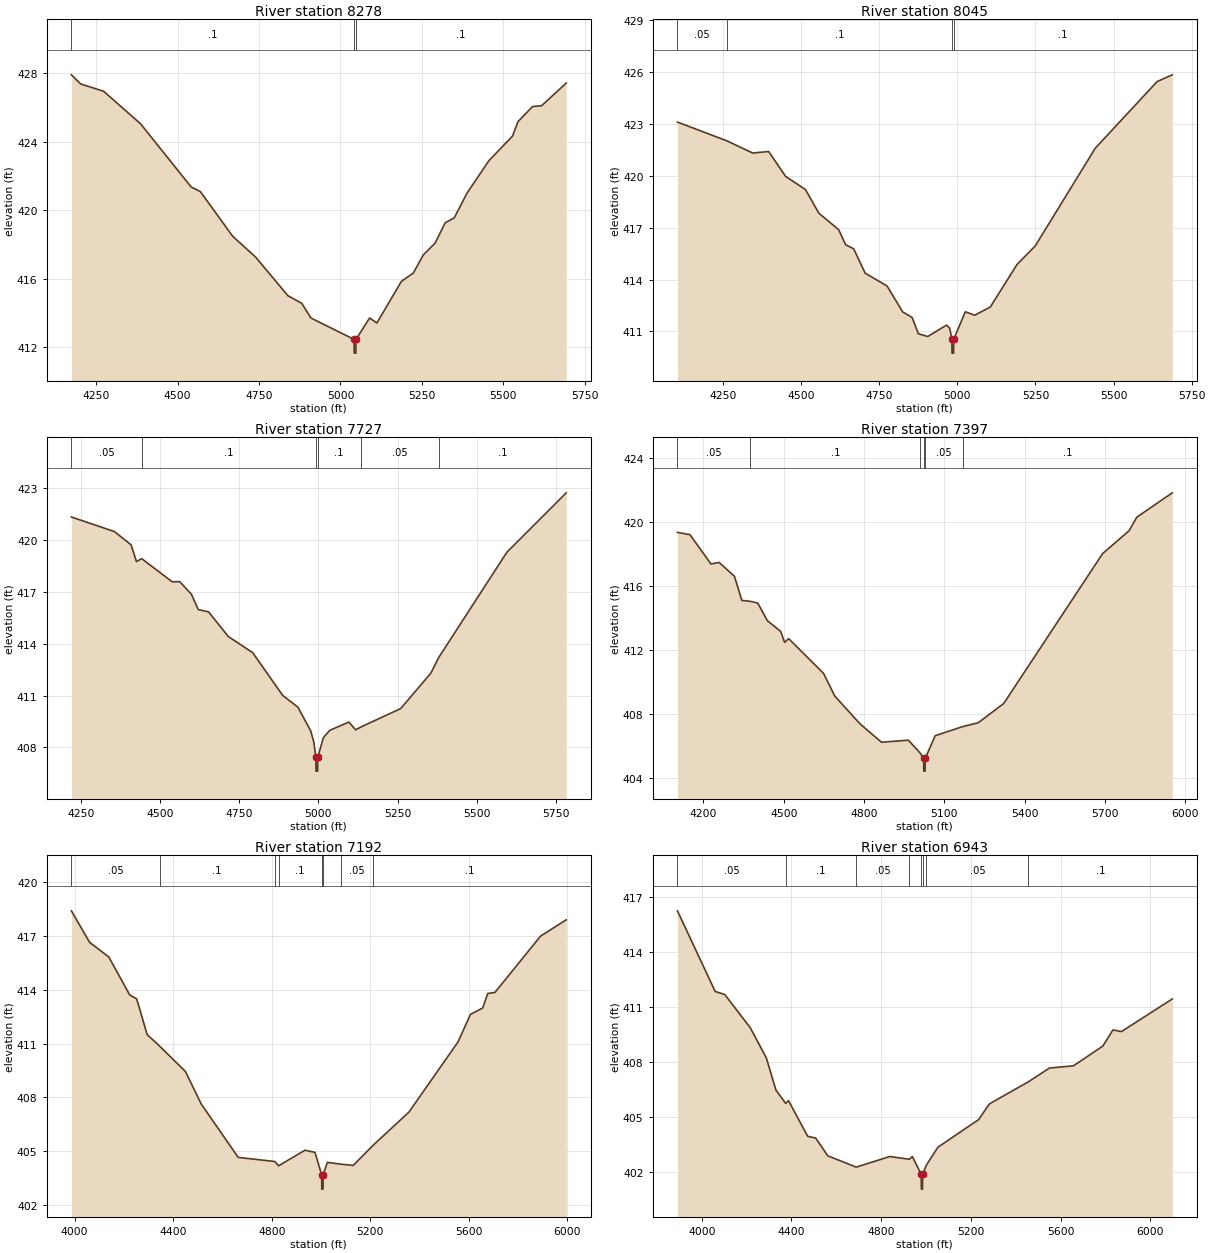
Type RM Length L Ch R = 1 ,8278    ,233,233,233
BEGIN DESCRIPTION:
UNT 050 in La Jarita Watershed 10.0
END DESCRIPTION:
XS GIS Cut Line= 3
      2097775.01     13444675.01        2097175.       13444075.
      2096574.97     13444375.02
#Sta/Elev= 30
  4173.8  427.89  4202.1  427.36  4272.8  426.93  4385.9  425.04  4541.5  421.35
  4569.8  421.08  4668.8  418.48  4739.5  417.26  4838.5  415.01  4880.9  414.57
  4909.2  413.71  5041.7  412.46  5042.2  411.66  5047.2  411.66  5047.7  412.46
  5089.4  413.71  5111.8  413.42  5187.3  415.85  5223.6  416.33  5254.3  417.39
  5290.7  418.08  5321.4  419.26  5349.4  419.55  5388.5  420.99  5455.6  422.88
  5528.3  424.32    5545  425.16  5589.7  426.04  5617.7  426.09  5693.2  427.41
#Mann= 3 ,-1 , 0
  4173.8      .1       0  5041.7     .07       0  5047.7      .1       0
Bank Sta=5041.7,5047.7
XS Rating Curve= 0 ,0
Exp/Cntr=0.3,0.1

Type RM Length L Ch R = 1 ,8045    ,318,318,318
BEGIN DESCRIPTION:
Mapping XS 38014c2f
END DESCRIPTION:
XS GIS Cut Line= 4
      2098031.07     13444099.37      2097471.14      13443899.7
      2097019.75     13443873.66      2096555.37     13444142.74
#Sta/Elev= 30
  4104.7   423.1  4263.8  422.01  4345.5  421.31  4396.5   421.4  4450.9  419.96
  4514.5   419.2    4557  417.84  4620.7  416.88    4643  416.01  4668.5  415.78
  4705.3  414.37  4775.4  413.63  4825.5  412.13  4855.6  411.81  4875.6  410.87
  4905.6  410.71  4965.7  411.37  4975.8  411.19  4982.8  410.55  4983.3  409.75
  4988.3  409.75  4988.8  410.55  5025.8  412.14  5055.9  411.94    5106  412.42
  5191.5  414.88  5249.4  415.94  5441.6  421.59  5639.5  425.44    5688  425.83
#Mann= 4 ,-1 , 0
  4104.7     .05       0  4263.8      .1       0  4982.8     .07       0
  4988.8      .1       0
Bank Sta=4982.8,4988.8
XS Rating Curve= 0 ,0
Exp/Cntr=0.3,0.1

Type RM Length L Ch R = 1 ,7727    ,330,330,330
BEGIN DESCRIPTION:
Mapping XS 28611ae3
END DESCRIPTION:
XS GIS Cut Line= 4
      2098074.45     13443912.73      2097536.24     13443687.03
      2097089.19     13443647.97      2096634.61     13443920.72
#Sta/Elev= 30
  4220.2  421.34  4355.8   420.5  4408.8  419.73  4425.6  418.76  4442.2  418.93
  4538.5  417.59  4562.3   417.6  4599.1  416.87  4620.8  415.98  4653.3  415.85
  4715.8  414.42  4792.5  413.49  4887.5  411.01  4935.6  410.33  4975.7  408.96
  4985.7  408.31  4992.1  407.43  4992.6  406.63  4997.6  406.63  4998.1  407.43
  5015.9  408.57  5035.9  408.99  5096.2  409.47  5117.8  409.02  5133.7  409.18
  5259.9  410.25  5355.1   412.3  5380.1  413.21  5595.6  419.31  5782.7  422.74
#Mann= 6 ,-1 , 0
  4220.2     .05       0  4442.2      .1       0  4992.1     .07       0
  4998.1      .1       0  5133.7     .05       0  5380.1      .1       0
Bank Sta=4992.1,4998.1
XS Rating Curve= 0 ,0
Exp/Cntr=0.3,0.1

Type RM Length L Ch R = 1 ,7397    ,205,205,205
BEGIN DESCRIPTION:
Mapping XS 88285bc9
END DESCRIPTION:
XS GIS Cut Line= 4
      2098087.42     13443756.45      2097453.78     13443348.49
      2096989.37     13443387.55      2096559.81     13443847.48
#Sta/Elev= 30
  4102.9  419.36  4149.6  419.22  4228.2  417.38  4258.5  417.48    4316  416.61
  4343.6   415.1  4375.4  415.04  4403.1  414.93  4438.8  413.83  4488.3  413.16
  4503.5  412.47  4518.7   412.7  4648.7  410.53    4691   409.1  4784.7  407.37
  4865.3  406.21  4965.7  406.34  5010.1  405.53  5022.9   405.2  5023.4   404.4
  5028.4   404.4  5028.9   405.2    5066  406.62  5170.7   407.2  5226.6  407.43
  5322.2  408.64  5691.6  418.03  5790.8  419.47  5819.1  420.31  5951.9  421.84
#Mann= 6 ,-1 , 0
  4102.9     .05       0  4375.4      .1       0  5010.1     .05       0
  5022.9     .07       0  5028.9     .05       0  5170.7      .1       0
Bank Sta=5022.9,5028.9
XS Rating Curve= 0 ,0
Exp/Cntr=0.3,0.1

Type RM Length L Ch R = 1 ,7192    ,249,249,249
BEGIN DESCRIPTION:
Mapping XS 0412edab
END DESCRIPTION:
XS GIS Cut Line= 4
      2098091.77     13443682.66      2097644.75     13443200.92
      2097149.96     13443148.83       2096469.3     13443664.74
#Sta/Elev= 30
  3986.9   418.4  4060.9  416.64  4138.6  415.83  4223.6  413.71  4251.9  413.49
  4294.4   411.5  4344.7  410.86  4449.8  409.44  4513.8  407.63    4664  404.65
  4812.9  404.42  4827.9  404.18  4934.9  405.05  4975.7  404.93  5002.8  403.68
  5003.3  402.88  5008.3  402.88  5008.8  403.68  5025.9  404.37  5083.1  404.27
    5131   404.2  5209.8   405.3  5356.8  407.17  5556.5  411.09  5606.5  412.62
  5656.4  412.98  5677.2  413.79  5706.3  413.85  5891.5  416.99  5995.7   417.9
#Mann= 8 ,-1 , 0
  3986.9     .05       0  4344.7      .1       0  4812.9     .05       0
  4827.9      .1       0  5002.8     .07       0  5008.8      .1       0
  5083.1     .05       0  5209.8      .1       0
Bank Sta=5002.8,5008.8
XS Rating Curve= 0 ,0
Exp/Cntr=0.3,0.1

Type RM Length L Ch R = 1 ,6943    ,235,235,235
BEGIN DESCRIPTION:
Mapping XS 3947620f
END DESCRIPTION:
XS GIS Cut Line= 4
      2098143.88      13443543.8      2097714.19     13443027.31
      2097089.19      13442897.1      2096260.23     13443235.63
#Sta/Elev= 30
  3891.8  416.25    4060  411.85    4103  411.68  4216.3  409.87  4287.9  408.23
  4330.8  406.47  4374.1  405.74  4386.8  405.89  4472.7  403.94  4507.9  403.85
  4561.9  402.88  4688.6  402.26  4838.6  402.84  4925.3  402.69  4939.2  402.84
  4978.6  401.86  4979.1  401.06  4984.1  401.06  4984.6  401.86  5001.3  402.37
  5053.1  403.35  5234.9  404.86  5282.2  405.71  5456.3  406.92  5550.2  407.67
  5657.1  407.79  5788.1  408.87  5833.1  409.75    5871  409.66  6097.5  411.44
#Mann= 8 ,-1 , 0
  3891.8     .05       0  4374.1      .1       0  4688.6     .05       0
  4925.3      .1       0  4978.6     .07       0  4984.6      .1       0
  5001.3     .05       0  5456.3      .1       0
Bank Sta=4978.6,4984.6
XS Rating Curve= 0 ,0
Exp/Cntr=0.3,0.1

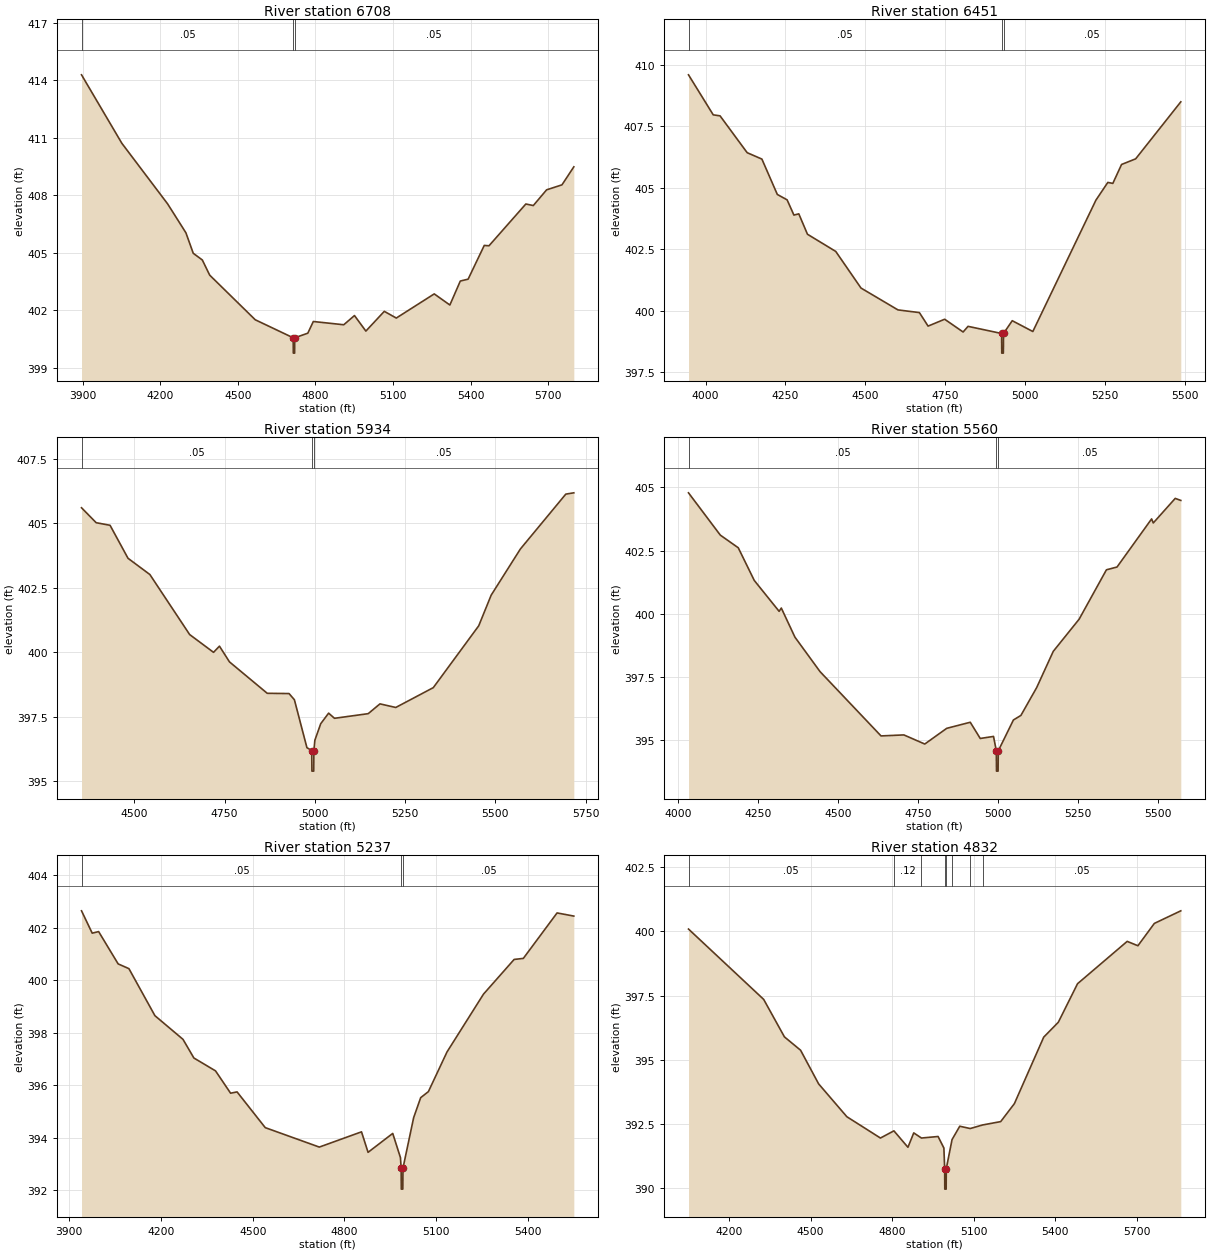
Type RM Length L Ch R = 1 ,6708    ,257,257,257
BEGIN DESCRIPTION:
Mapping XS 0e59d780
END DESCRIPTION:
XS GIS Cut Line= 4
      2098274.09     13443396.23       2097822.7     13442910.12
      2097215.06     13442680.08      2096629.58     13442606.36
#Sta/Elev= 30
  3896.2  414.28    4052  410.71  4228.9  407.55  4299.7  406.04  4328.1  404.97
  4363.2  404.62  4391.6  403.83  4567.8   401.5  4714.5  400.56    4715  399.76
    4720  399.76  4720.5  400.56    4771   400.8  4792.3  401.41    4910  401.24
  4951.4  401.72  4995.5  400.91  5066.7  401.94  5113.1  401.59  5259.8  402.85
  5320.2  402.27  5360.5  403.52  5390.8  403.62  5453.2  405.38  5471.4  405.36
  5613.9  407.54  5642.8  407.46  5694.2  408.28  5753.6  408.54  5799.4  409.48
#Mann= 3 ,-1 , 0
  3896.2     .05       0  4714.5     .03       0  4720.5     .05       0
Bank Sta=4714.5,4720.5
XS Rating Curve= 0 ,0
Exp/Cntr=0.3,0.1

Type RM Length L Ch R = 1 ,6451    ,517,517,517
BEGIN DESCRIPTION:
UNT 050 in La Jarita Watershed 6.0
END DESCRIPTION:
XS GIS Cut Line= 3
      2098460.75     13443114.13      2097687.28     13442632.34
      2097142.98     13442314.61
#Sta/Elev= 30
  3946.7   409.6  4024.2  407.97  4045.5  407.93  4130.4  406.43  4176.5  406.17
  4224.8  404.73  4255.5  404.51  4276.8  403.89  4292.1  403.94  4319.2  403.11
  4407.8  402.41  4486.8  400.92  4602.5  400.03  4669.7  399.92  4696.9  399.37
  4748.8  399.65  4806.6  399.13    4822  399.36  4927.1  399.07  4927.6  398.27
  4932.6  398.27  4933.1  399.07  4960.4  399.59  5024.9  399.15  5222.5   404.5
  5259.7  405.22  5275.4  405.18  5302.7  405.95  5346.9  406.18  5488.2   408.5
#Mann= 3 ,-1 , 0
  3946.7     .05       0  4927.1     .03       0  4933.1     .05       0
Bank Sta=4927.1,4933.1
XS Rating Curve= 0 ,0
Exp/Cntr=0.3,0.1

Type RM Length L Ch R = 1 ,5934    ,374,374,374
BEGIN DESCRIPTION:
Mapping XS b9c531dd
END DESCRIPTION:
XS GIS Cut Line= 3
      2098606.59     13442848.51      2098101.35     13442582.86
      2097403.44     13442207.87
#Sta/Elev= 30
  4354.1  405.61  4394.7  405.03  4433.1  404.93  4482.8  403.65  4543.3  403.02
  4653.5  400.69  4719.6     400    4736  400.24  4763.7  399.63  4868.3  398.41
  4928.7   398.4  4943.5  398.16  4978.2   396.3  4991.5  396.19    4992  395.39
    4997  395.39  4997.5  396.19  5000.2  396.59  5016.4  397.23  5038.3  397.64
  5054.5  397.44  5147.9  397.62  5180.4     398  5224.2  397.86  5328.1  398.63
  5453.9  401.03  5488.4  402.22  5569.2  404.01    5695  406.14  5717.2  406.19
#Mann= 3 ,-1 , 0
  4354.1     .05       0  4991.5    .035       0  4997.5     .05       0
Bank Sta=4991.5,4997.5
XS Rating Curve= 0 ,0
Exp/Cntr=0.3,0.1

Type RM Length L Ch R = 1 ,5560    ,323,323,323
BEGIN DESCRIPTION:
Mapping XS a51605c6
END DESCRIPTION:
XS GIS Cut Line= 3
      2098820.09     13442759.94      2098377.39     13442270.36
      2097530.99     13442035.97
#Sta/Elev= 30
  4032.2  404.78  4131.6  403.11  4187.7  402.61  4237.7  401.32  4315.4   400.1
  4322.2  400.23  4364.8  399.08  4443.2  397.72  4633.8  395.18  4705.1  395.22
  4770.5  394.86  4839.1  395.48  4912.6  395.72  4943.8  395.08  4985.3  395.16
  4994.1  394.59  4994.6  393.79  4999.6  393.79  5000.1  394.59  5047.5  395.81
  5070.9  395.99  5120.2  397.09    5172  398.52  5252.8  399.79  5338.1  401.74
  5371.2  401.85  5479.3  403.75  5484.5  403.59  5553.1  404.56  5570.5  404.48
#Mann= 3 ,-1 , 0
  4032.2     .05       0  4994.1    .035       0  5000.1     .05       0
Bank Sta=4994.1,5000.1
XS Rating Curve= 0 ,0
Exp/Cntr=0.3,0.1

Type RM Length L Ch R = 1 ,5237    ,405,405,405
BEGIN DESCRIPTION:
Mapping XS 99a1ac11
END DESCRIPTION:
XS GIS Cut Line= 4
      2098955.51      13442603.7      2098356.55     13441970.88
      2098031.03     13441851.09      2097640.37     13441879.74
#Sta/Elev= 30
  3940.1  402.64    3975  401.79    3996  401.85  4059.9  400.62  4095.1  400.44
  4180.1  398.65  4271.9  397.75  4307.5  397.04  4378.3  396.55  4427.6   395.7
  4448.7  395.75  4540.9  394.39  4717.7  393.65  4855.7  394.23  4877.1  393.45
  4957.8  394.17    4983  393.25  4985.3  392.85  4985.8  392.05  4990.8  392.05
  4991.3  392.85  5026.2  394.77  5049.2  395.53  5074.4  395.76  5135.3  397.27
  5254.6  399.47  5354.8  400.79  5384.9  400.83  5495.2  402.56    5550  402.44
#Mann= 3 ,-1 , 0
  3940.1     .05       0  4985.3    .035       0  4991.3     .05       0
Bank Sta=4985.3,4991.3
XS Rating Curve= 0 ,0
Exp/Cntr=0.3,0.1

Type RM Length L Ch R = 1 ,4832    ,257,257,257
BEGIN DESCRIPTION:
Mapping XS aade1e6a
END DESCRIPTION:
XS GIS Cut Line= 4
      2099098.72     13442457.82      2098809.68      13441921.4
      2098366.97     13441655.78      2097688.66     13441746.74
#Sta/Elev= 30
  4051.2  400.09  4327.6  397.35  4403.9  395.89  4463.3  395.37  4529.6  394.06
  4633.4  392.78  4756.9  391.95  4806.4  392.23    4858  391.59  4879.4  392.15
  4907.7  391.95  4968.8  392.01  4990.2  391.56    4993  390.76  4993.5  389.96
  4998.5  389.96    4999  390.76  5020.2  391.89  5048.5  392.41    5087  392.32
  5132.8  392.46    5199  392.59  5249.4  393.29  5357.2  395.88  5410.9  396.46
  5481.5  397.96  5664.1  399.61  5703.5  399.44    5764  400.31  5861.2   400.8
#Mann= 8 ,-1 , 0
  4051.2     .05       0  4806.4     .12       0  4907.7      .1       0
    4993     .07       0    4999      .1       0  5020.2     .05       0
    5087      .1       0  5132.8     .05       0
Bank Sta=4993,4999
XS Rating Curve= 0 ,0
Exp/Cntr=0.3,0.1

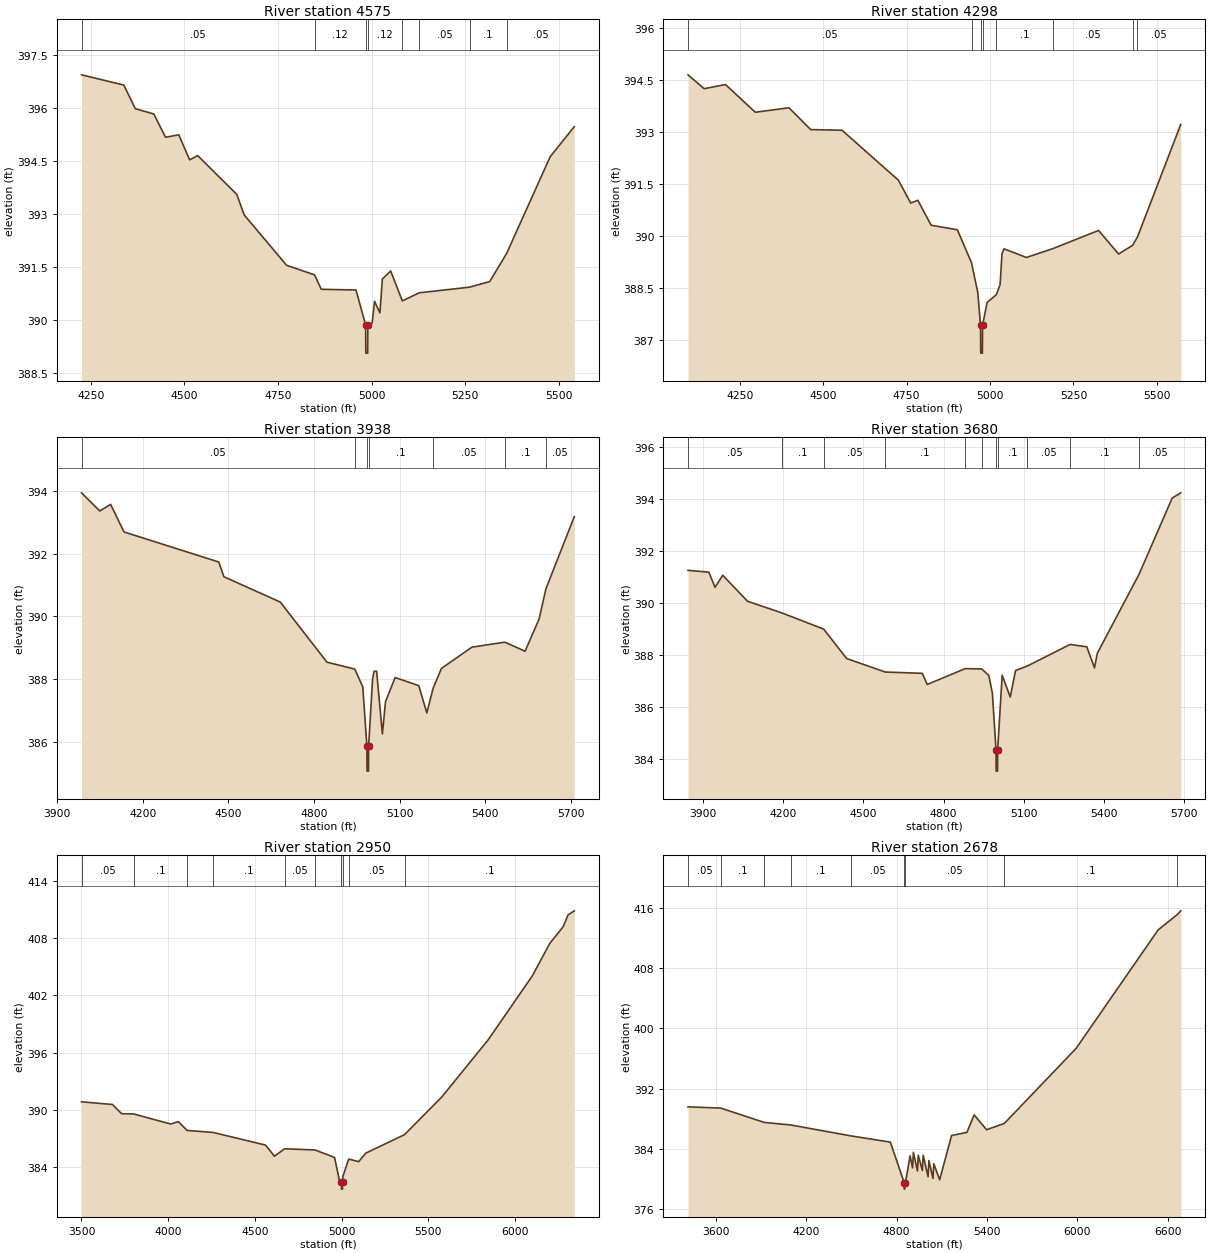
Type RM Length L Ch R = 1 ,4575    ,277,277,277
BEGIN DESCRIPTION:
Mapping XS 33529414
END DESCRIPTION:
XS GIS Cut Line= 4
      2099226.34     13442228.68      2099018.01     13441874.53
       2098632.6     13441559.42      2098231.58     13441491.72
#Sta/Elev= 30
  4225.5  396.95  4338.3  396.66    4369  395.99  4418.4  395.84  4449.7  395.18
    4485  395.25  4514.1  394.54  4535.5  394.66    4640  393.56  4659.5  392.98
  4772.9  391.55  4847.4  391.28  4865.5  390.87  4958.1  390.85  4983.8  389.86
  4984.3  389.06  4989.3  389.06  4989.8  389.86  5001.2  389.91  5007.7  390.53
    5022   390.2  5028.5  391.16  5050.7  391.39  5081.8  390.54  5126.7  390.77
  5261.3  390.93  5315.2  391.09  5360.4  391.89  5476.6  394.63  5540.9  395.48
#Mann= 8 ,-1 , 0
  4225.5     .05       0  4847.4     .12       0  4983.8     .07       0
  4989.8     .12       0  5081.8      .1       0  5126.7     .05       0
  5261.3      .1       0  5360.4     .05       0
Bank Sta=4983.8,4989.8
XS Rating Curve= 0 ,0
Exp/Cntr=0.3,0.1

Type RM Length L Ch R = 1 ,4298    ,360,360,360
BEGIN DESCRIPTION:
Mapping XS bf8ea6ca
END DESCRIPTION:
XS GIS Cut Line= 4
      2099465.95     13442189.67      2099088.32     13441564.63
      2098783.64     13441410.99      2098378.74     13441398.01
#Sta/Elev= 30
  4094.9  394.64  4143.2  394.24  4207.2  394.36  4296.5  393.56  4397.4  393.69
  4462.5  393.06  4556.5  393.04  4725.3   391.6  4762.2  390.94  4783.5  391.02
  4823.5   390.3  4901.9  390.17  4944.4  389.22  4963.2  388.36  4971.5  387.41
    4972  386.61    4977  386.61  4977.5  387.41  4991.1  388.07  5019.1   388.3
  5030.1  388.59  5035.7  389.47  5041.7  389.62  5108.9  389.37  5189.6  389.63
  5325.1  390.15  5385.1  389.47  5427.1  389.72  5441.7  389.96  5571.5  393.21
#Mann= 8 ,-1 , 0
  4094.9     .05       0  4944.4     .12       0  4971.5     .07       0
  4977.5     .12       0  5019.1      .1       0  5189.6     .05       0
  5427.1      .1       0  5441.7     .05       0
Bank Sta=4971.5,4977.5
XS Rating Curve= 0 ,0
Exp/Cntr=0.3,0.1

Type RM Length L Ch R = 1 ,3938    ,258,258,258
BEGIN DESCRIPTION:
Mapping XS 6a6e12c6
END DESCRIPTION:
XS GIS Cut Line= 4
       2099520.6     13442163.56      2099145.62     13441301.61
      2098919.05     13441239.11      2098379.96     13441356.31
#Sta/Elev= 30
  3985.3  393.95  4049.2  393.37  4087.2  393.58  4134.1   392.7  4466.1  391.74
    4484  391.27  4681.7  390.46  4845.3  388.54  4942.8  388.32  4970.8  387.75
  4985.2  385.86  4985.7  385.06  4990.7  385.06  4991.2  385.86  5005.1     388
  5010.3  388.25  5019.3  388.25  5039.5  386.25  5050.4  387.28  5084.2  388.05
    5167  387.79  5195.2  386.92  5217.4  387.71  5246.3  388.34  5353.3  389.02
  5468.5  389.18  5539.5  388.89  5588.7  389.92  5612.4  390.88    5712  393.19
#Mann= 7 ,-1 , 0
  3985.3     .05       0  4942.8      .1       0  4985.2     .07       0
  4991.2      .1       0  5217.4     .05       0  5468.5      .1       0
  5612.4     .05       0
Bank Sta=4985.2,4991.2
XS Rating Curve= 0 ,0
Exp/Cntr=0.3,0.1

Type RM Length L Ch R = 1 ,3680    ,730,730,730
BEGIN DESCRIPTION:
UNT 050 in La Jarita Watershed 5.0
END DESCRIPTION:
XS GIS Cut Line= 4
      2099601.34     13441891.88      2099253.91     13441108.69
      2098737.24     13441147.92      2098315.33     13441356.27
#Sta/Elev= 30
  3842.9  391.25  3920.9  391.18  3944.1   390.6  3972.9  391.06    4066  390.06
  4195.3  389.61  4351.1  388.99  4436.9  387.86  4581.5  387.34  4720.4  387.29
  4738.7  386.86  4880.6  387.47  4942.9  387.46  4969.4  387.21  4982.8  386.53
  4996.5  384.33    4997  383.53    5002  383.53  5002.5  384.33  5019.5  387.22
  5049.6  386.38  5069.7   387.4  5113.6  387.57  5273.7   388.4  5336.5  388.31
  5365.3   387.5  5375.8  388.06  5532.7  391.11  5656.3  394.03  5688.4  394.23
#Mann= 11 ,-1 , 0
  3842.9     .05       0  4195.3      .1       0  4351.1     .05       0
  4581.5      .1       0  4880.6     .12       0  4942.9      .1       0
  4996.5     .07       0  5002.5      .1       0  5113.6     .05       0
  5273.7      .1       0  5532.7     .05       0
Bank Sta=4996.5,5002.5
XS Rating Curve= 0 ,0
Exp/Cntr=0.3,0.1

Type RM Length L Ch R = 1 ,2950    ,272,272,272
BEGIN DESCRIPTION:
Mapping XS 4d30501b
END DESCRIPTION:
XS GIS Cut Line= 5
      2099672.07     13441885.33      2099151.26     13440807.25
      2098823.13     13440609.34      2098609.59      13440588.5
      2097906.49     13439812.49
#Sta/Elev= 30
  3500.4  390.82  3678.5  390.54  3731.7  389.57  3801.5  389.54  4014.1  388.49
  4059.3  388.73  4109.2  387.81  4259.3   387.6    4562  386.27  4612.8   385.1
  4671.5  385.88  4846.9  385.76  4959.8  384.97    4987  382.61  4999.3  382.44
  4999.8  381.64  5005.1  381.64  5005.6  382.44  5008.6  383.03  5041.5   384.8
  5099.1  384.53  5139.3  385.42  5363.3  387.37  5577.3  391.31  5846.3  397.35
  6101.1  404.08  6200.4  407.45  6278.1  409.23  6306.5  410.47  6342.6   410.9
#Mann= 10 ,-1 , 0
  3500.4     .05       0  3801.5      .1       0  4109.2     .05       0
  4259.3      .1       0  4671.5     .05       0  4846.9     .12       0
  4999.3     .07       0  5005.6     .12       0  5041.5     .05       0
  5363.3      .1       0
Bank Sta=4999.3,5005.6
XS Rating Curve= 0 ,0
Exp/Cntr=0.3,0.1

Type RM Length L Ch R = 1 ,2678    ,81,81,81
BEGIN DESCRIPTION:
Mapping XS 9bbb928b
END DESCRIPTION:
XS GIS Cut Line= 6
      2099703.36     13441791.66      2099213.76     13440817.67
      2099198.13     13440510.38       2098927.3      13440395.8
      2098625.22     13440552.05       2097781.5     13439656.25
#Sta/Elev= 30
  3415.6  389.57  3632.1  389.41  3921.9   387.5  4098.2  387.16  4496.8  385.71
  4758.8  384.88  4851.8  379.43  4852.3  378.63  4858.1  379.43  4890.1  383.06
  4906.4  381.46  4911.6  383.52  4938.9  381.05  4944.2  383.14  4971.5  381.11
  4976.8  383.14  5009.3  380.28  5014.6  382.43  5041.9  380.05  5047.1     382
  5086.2  379.88  5165.4  385.76  5267.2  386.18  5315.1   388.5  5397.8  386.53
  5515.8  387.37  5991.9  397.34  6536.9  413.11  6663.7  415.14  6686.9  415.64
#Mann= 9 ,-1 , 0
  3415.6     .05       0  3632.1      .1       0  3921.9     .05       0
  4098.2      .1       0  4496.8     .05       0  4851.8     .03       0
  4858.1     .05       0  5515.8      .1       0  6663.7     .08       0
Bank Sta=4851.8,4858.1
XS Rating Curve= 0 ,0
Exp/Cntr=0.3,0.1

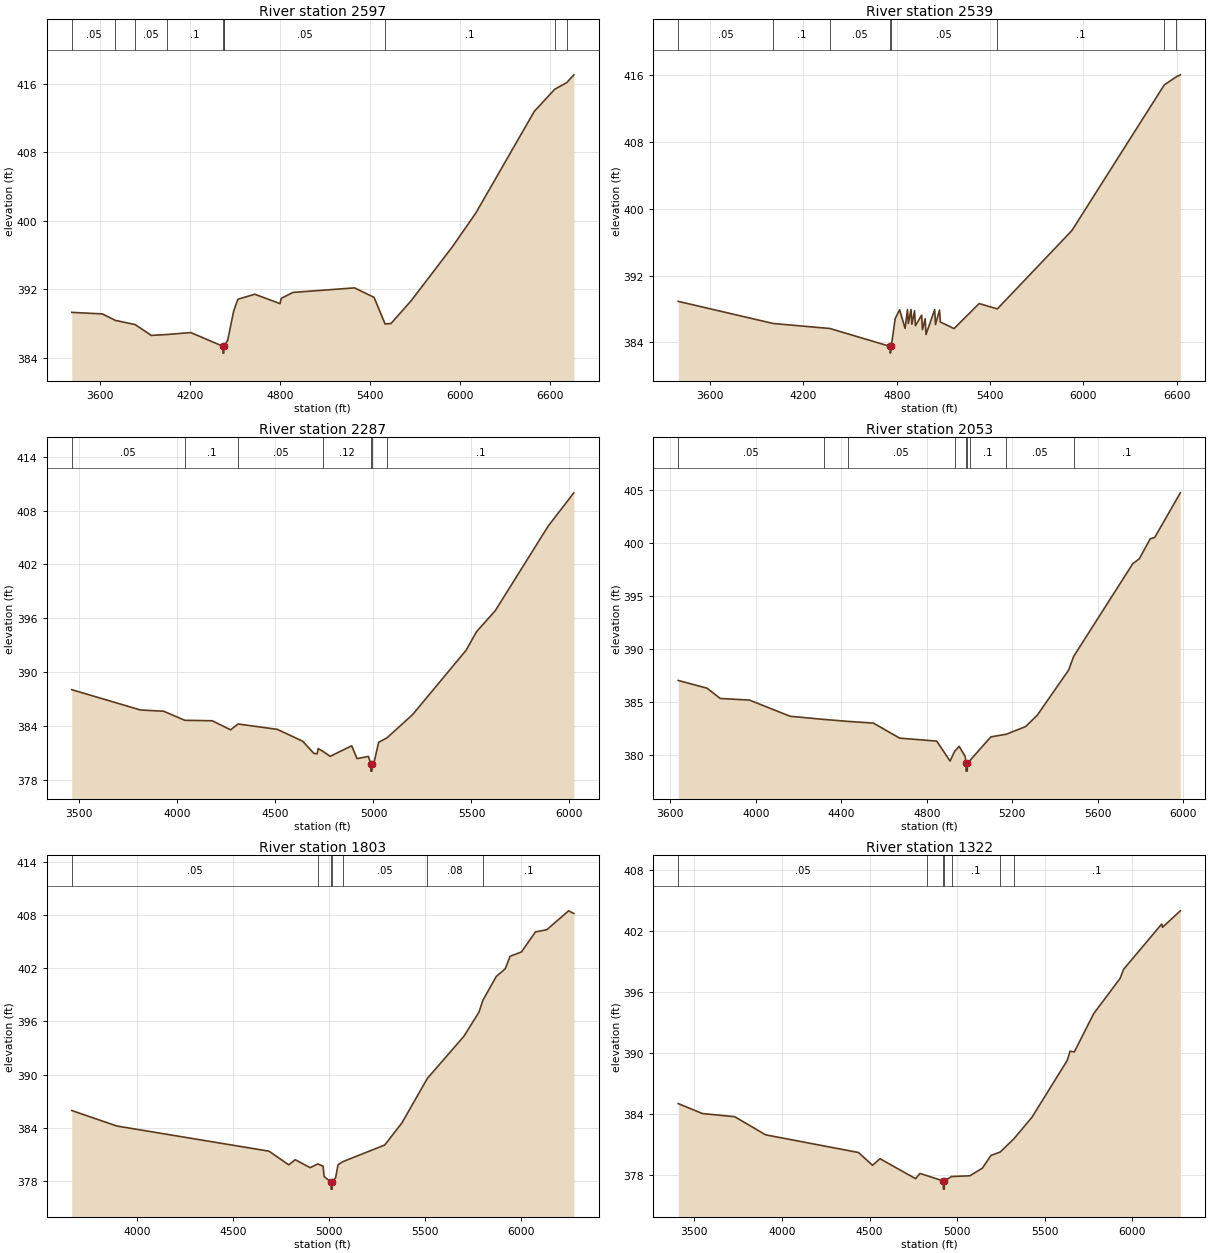
Type RM Length L Ch R = 1 ,2597    ,58,58,58
BEGIN DESCRIPTION:
Mapping XS 1e83876c
END DESCRIPTION:
XS GIS Cut Line= 6
      2099703.35     13441739.56      2099276.26     13440817.67
      2099213.76       13440401.      2098953.34     13440307.25
      2098599.18     13440447.88      2097724.16     13439583.28
#Sta/Elev= 30
  3414.2  389.32  3617.8  389.14  3705.3  388.38  3836.9  387.89  3944.1  386.63
  4045.7  386.73  4207.2  386.96  4421.3  385.36  4421.8  384.56  4427.1  384.56
  4427.6  385.36  4427.7  385.36  4452.9  386.05  4492.9  389.48  4520.9  390.85
  4633.2  391.44  4801.8  390.34  4809.4  390.95  4887.9  391.65  5298.2  392.18
  5428.1  391.07  5501.5  387.97    5541  388.02  5675.4  390.68  5951.2  397.01
  6106.7  400.94  6495.6  412.79  6631.4  415.37  6712.3  416.16  6759.1  417.06
#Mann= 10 ,-1 , 0
  3414.2     .05       0  3705.3      .1       0  3836.9     .05       0
  4045.7      .1       0  4421.3     .03       0  4427.6      .1       0
  4427.7     .05       0  5501.5      .1       0  6631.4     .08       0
  6712.3      .1       0
Bank Sta=4421.3,4427.6
XS Rating Curve= 0 ,0
Exp/Cntr=0.3,0.1

Type RM Length L Ch R = 1 ,2539    ,252,252,252
BEGIN DESCRIPTION:
Mapping XS 91321279
END DESCRIPTION:
XS GIS Cut Line= 6
      2099730.25     13441707.86      2099358.72     13440867.58
      2099317.06     13440433.56      2098931.64     13440242.58
      2098633.03     13440374.53      2097844.82     13439600.21
#Sta/Elev= 30
  3395.8  388.92    4006  386.27  4370.2  385.67  4758.5  383.52    4759  382.72
  4764.8  383.52  4790.1  386.87  4818.6  387.91  4853.7  385.68  4868.9  387.94
  4874.4  386.26  4891.6  387.95  4897.2  386.18  4914.4  387.79  4919.9     386
  4959.9  387.27  4965.5  385.53  4982.7  386.83  4988.2  384.95  5043.7  387.94
    5049  386.15  5074.9  387.88  5080.1  386.45  5168.3  385.66  5329.5  388.66
  5446.5  388.02  5925.8  397.41  6519.4  414.86  6597.4  415.83  6622.3  416.06
#Mann= 8 ,-1 , 0
  3395.8     .05       0    4006      .1       0  4370.2     .05       0
  4758.5     .03       0  4764.8     .05       0  5446.5      .1       0
  6519.4     .08       0  6597.4      .1       0
Bank Sta=4758.5,4764.8
XS Rating Curve= 0 ,0
Exp/Cntr=0.3,0.1

Type RM Length L Ch R = 1 ,2287    ,234,234,234
BEGIN DESCRIPTION:
Mapping XS f7c56547
END DESCRIPTION:
XS GIS Cut Line= 4
      2099733.73     13441485.68      2099379.56     13440204.39
      2099001.09     13439971.75      2098275.38     13439666.19
#Sta/Elev= 30
  3461.2  388.05  3811.2  385.79  3929.8  385.65  4037.9  384.64  4177.8  384.59
  4271.2  383.58  4309.6  384.23  4509.8  383.63  4639.1  382.31  4696.5  380.95
  4712.9  380.91  4718.1  381.49  4741.5  381.19  4779.5  380.63  4889.2   381.8
  4916.3  380.37  4974.3  380.62  4986.6  379.78  4987.1  378.98  4992.4  378.98
  4992.9  379.78  5005.1  380.13  5026.4  382.19  5068.9  382.68  5200.4  385.29
    5473  392.45  5525.8  394.51  5620.8  396.83  5892.4   406.3  6022.2  409.97
#Mann= 7 ,-1 , 0
  3461.2     .05       0  4037.9      .1       0  4309.6     .05       0
  4741.5     .12       0  4986.6     .07       0  4992.9     .12       0
  5068.9      .1       0
Bank Sta=4986.6,4992.9
XS Rating Curve= 0 ,0
Exp/Cntr=0.3,0.1

Type RM Length L Ch R = 1 ,2053    ,250,250,250
BEGIN DESCRIPTION:
Mapping XS 81b5cf10
END DESCRIPTION:
XS GIS Cut Line= 4
      2099751.09     13441346.79      2099490.67     13440159.25
      2099181.64     13439846.75      2098508.98     13439673.38
#Sta/Elev= 30
    3637  387.05  3771.9  386.32  3833.7  385.35  3970.2   385.2    4161  383.67
  4316.9  383.38  4430.1  383.19    4550  383.03  4673.6  381.61  4846.9  381.33
  4909.3  379.45  4930.7  380.37  4951.7  380.84    4980  379.88  4983.9   379.3
  4984.4   378.5  4989.7   378.5  4990.2   379.3  5000.5  379.46  5100.2  381.73
  5172.7  381.98  5262.9   382.7    5317  383.76  5464.3  388.03  5487.8  389.32
  5764.5  398.06  5794.8  398.52  5846.4  400.41  5867.1  400.53  5986.9  404.74
#Mann= 9 ,-1 , 0
    3637     .05       0  4316.9      .1       0  4430.1     .05       0
  4930.7     .12       0  4983.9     .07       0  4990.2     .12       0
  5000.5      .1       0  5172.7     .05       0  5487.8      .1       0
Bank Sta=4983.9,4990.2
XS Rating Curve= 0 ,0
Exp/Cntr=0.3,0.1

Type RM Length L Ch R = 1 ,1803    ,481,481,481
BEGIN DESCRIPTION:
Mapping XS 76c7af8f
END DESCRIPTION:
XS GIS Cut Line= 4
       2099737.2     13441197.48      2099580.95     13440117.58
      2099494.14      13439815.5      2098369.55     13439367.75
#Sta/Elev= 30
  3659.3  385.94  3894.2  384.19  4687.3  381.35  4789.8  379.81  4823.5  380.39
  4901.3  379.49  4940.6  379.91  4968.8  379.66    4974  378.49  5010.1  377.87
  5010.6  377.07  5015.9  377.07  5016.4  377.87  5034.1  378.36  5046.6  379.83
    5073  380.18  5289.9  382.05  5379.2  384.53  5511.9  389.56  5702.8  394.33
    5781  397.04    5801  398.37  5871.1  401.07  5917.7  401.93  5942.9  403.34
  6002.2  403.83    6075  406.09  6134.4  406.34  6247.8  408.47  6275.2  408.17
#Mann= 7 ,-1 , 0
  3659.3     .05       0  4940.6      .1       0  5010.1     .07       0
  5016.4      .1       0    5073     .05       0  5511.9     .08       0
    5801      .1       0
Bank Sta=5010.1,5016.4
XS Rating Curve= 0 ,0
Exp/Cntr=0.3,0.1

Type RM Length L Ch R = 1 ,1322    ,531,531,531
BEGIN DESCRIPTION:
Mapping XS 9468f411
END DESCRIPTION:
XS GIS Cut Line= 4
      2099734.44     13441092.76      2099803.89     13439658.78
      2099560.83     13439370.59      2098512.82     13439269.95
#Sta/Elev= 30
    3408  385.05  3545.9  384.07  3730.4  383.76  3906.3  381.98    4437  380.24
  4517.1  378.98  4559.4  379.63  4762.8  377.67  4787.4  378.18    4830  377.95
  4920.8  377.44  4921.3  376.64  4926.6  376.64  4927.1  377.44  4967.7  377.88
  5072.2  377.95  5143.7   378.7  5193.1  379.96  5245.9  380.29  5323.3  381.58
  5427.4  383.72  5628.4   389.3  5644.4   390.2  5668.6  390.13  5779.1  393.89
  5929.7  397.35  5949.8  398.25  6167.1   402.7  6172.1  402.38  6273.5     404
#Mann= 7 ,-1 , 0
    3408     .05       0    4830     .08       0  4920.8     .07       0
  4927.1     .08       0  4967.7      .1       0  5245.9     .08       0
  5323.3      .1       0
Bank Sta=4920.8,4927.1
XS Rating Curve= 0 ,0
Exp/Cntr=0.3,0.1

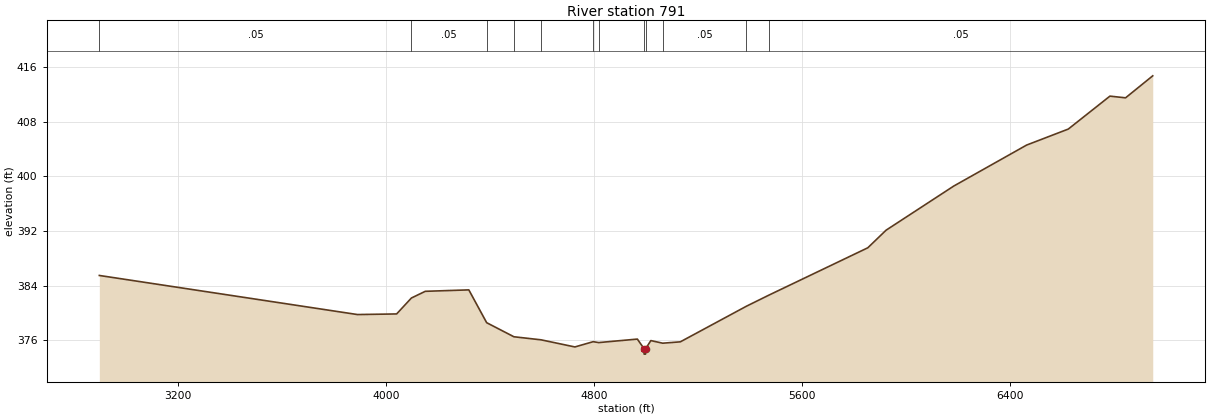
Type RM Length L Ch R = 1 ,791     ,0,0,0
BEGIN DESCRIPTION:
UNT 050 in La Jarita Watershed 1.0
END DESCRIPTION:
XS GIS Cut Line= 5
       2099742.4     13441143.65      2099853.36     13439909.21
      2100096.42     13439296.15      2099820.81     13439134.47
      2097990.62     13439221.75
#Sta/Elev= 30
  2897.2  385.48  3889.8  379.76  4040.4  379.85  4097.2  382.18  4150.6  383.16
    4318  383.37  4386.6  378.57  4491.4  376.51  4596.2  376.06  4725.9  375.02
  4796.2  375.79  4817.5  375.66  4966.1  376.17  4991.7  374.77  4992.2  373.97
  4997.5  373.97    4998  374.77    5018  375.95  5063.5  375.57  5131.5  375.77
  5385.5  380.98  5471.8   382.6  5852.3  389.53  5922.4   392.1  6182.7  398.56
    6463  404.56  6623.2   406.9  6783.3  411.72  6843.4  411.47  6947.9  414.69
#Mann= 12 ,-1 , 0
  2897.2     .05       0  4097.2     .05       0  4386.6     .05       0
  4491.4     .05       0  4596.2     .05       0  4796.2     .05       0
  4817.5     .05       0  4991.7     .03       0    4998     .05       0
  5063.5     .05       0  5385.5     .05       0  5471.8     .05       0
Bank Sta=4991.7,4998
XS Rating Curve= 0 ,0
Exp/Cntr=0.3,0.1
LCMann Table=0

Chan Stop Cuts=-1
Use User Specified Reach Order=0
Composite Channel Slope=5