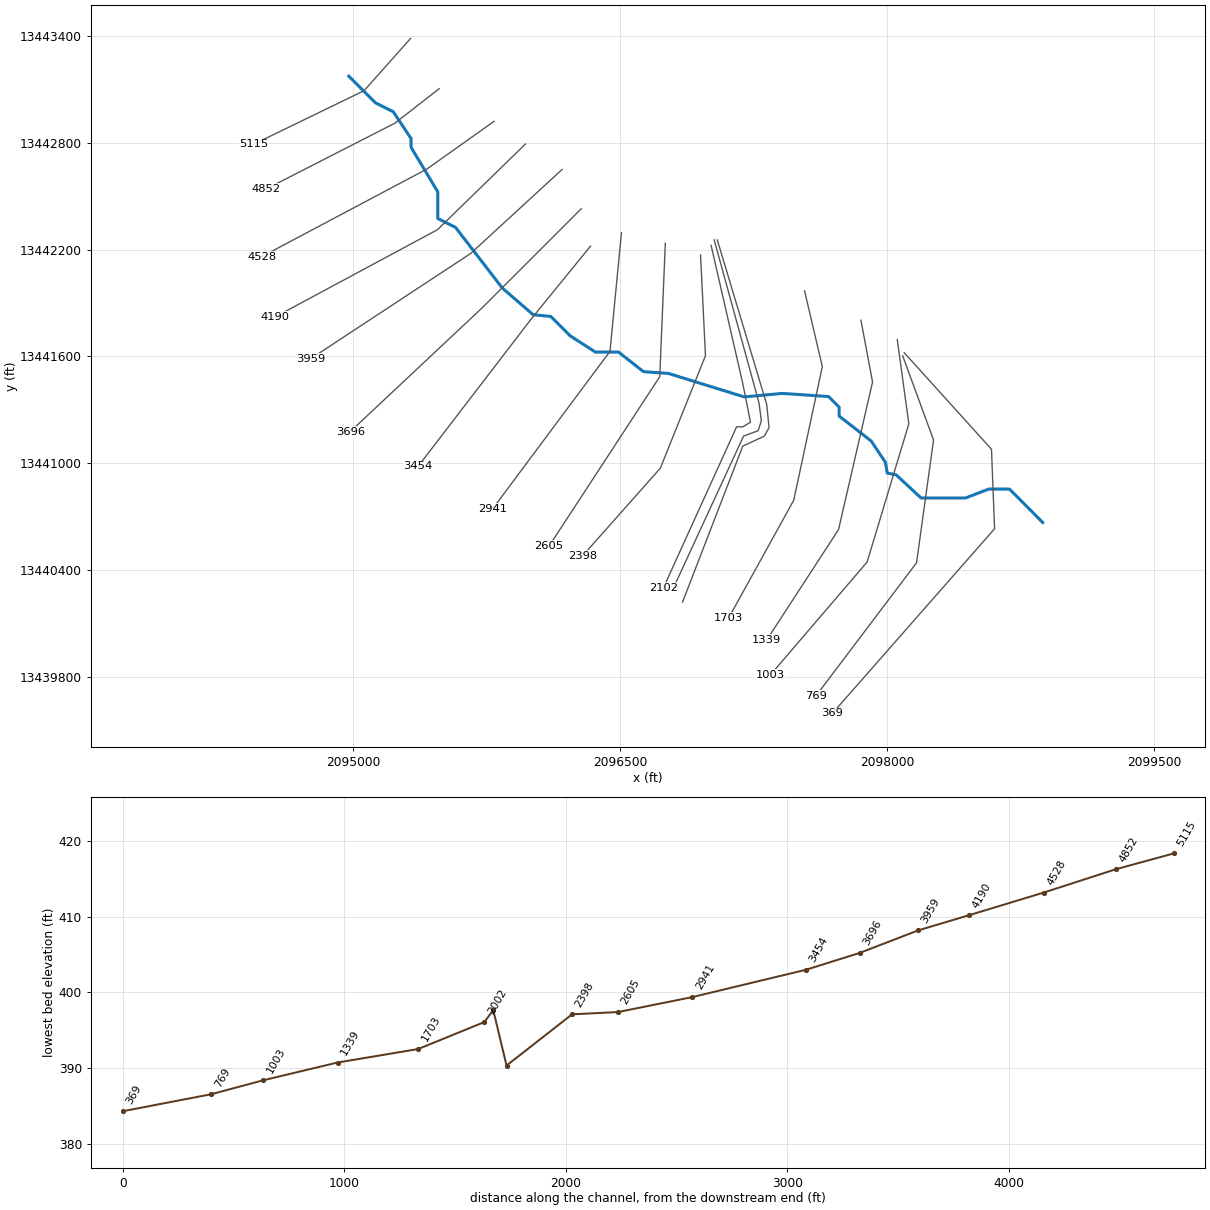
--- UNT 052 in La Jarita Watershed.prj (project) ---

Proj Title=UNT 052 in La Jarita Watershed Base Level Engineering
Current Plan=p01
Default Exp/Contr=0.3,0.1
English Units
Geom File=g01
Flow File=f01
Plan File=p01
BEGIN DESCRIPTION:
UNT 052 in La Jarita Watershed
END DESCRIPTION:

--- UNT 052 in La Jarita Watershed.p01 (plan) ---

Plan Title=Multiple Run
Short Identifier=Multiple
Geom File=g01
Flow File=f01
Subcritical Flow
K Sum by GR= 0
Std Step Tol= 0.01
Critical Tol= 0.01
Num of Std Step Trials= 20
Max Error Tol= 0.3
Flow Tol Ratio= 0.001
Split Flow NTrial= 30
Split Flow Tol= 0.02
Split Flow Ratio= 0.02
Log Output Level= 0
Friction Slope Method= 1
Unsteady Friction Slope Method= 2
Unsteady Bridges Friction Slope Method= 1
Parabolic Critical Depth
Global Vel Dist=  1 , 1 , 1
Global Log Level= 0
CheckData=True
Encroach Param= -1, 0, 0, 0
BEGIN DESCRIPTION:
Multiple Run
END DESCRIPTION:

--- UNT 052 in La Jarita Watershed.f01 (steady flow) ---

Flow Title=Multiple
Number of Profiles=7
Profile Names=10-year,25-year,50-year,1pct_min,100-year,1pct_plu,500-year
River Rch & RM= UNT 052 in La Ja,Reach-1,5115
     102     134     158      94     187     374     265
Boundary for River Rch & Prof#=UNT 052 in La Ja,Reach-1,1
Up Type=0
Dn Type=3
Dn Slope=0.005
Boundary for River Rch & Prof#=UNT 052 in La Ja,Reach-1,2
Up Type=0
Dn Type=3
Dn Slope=0.005
Boundary for River Rch & Prof#=UNT 052 in La Ja,Reach-1,3
Up Type=0
Dn Type=3
Dn Slope=0.005
Boundary for River Rch & Prof#=UNT 052 in La Ja,Reach-1,4
Up Type=0
Dn Type=3
Dn Slope=0.005
Boundary for River Rch & Prof#=UNT 052 in La Ja,Reach-1,5
Up Type=0
Dn Type=3
Dn Slope=0.005
Boundary for River Rch & Prof#=UNT 052 in La Ja,Reach-1,6
Up Type=0
Dn Type=3
Dn Slope=0.005
Boundary for River Rch & Prof#=UNT 052 in La Ja,Reach-1,7
Up Type=0
Dn Type=3
Dn Slope=0.005

--- UNT 052 in La Jarita Watershed.g01 (geometry) ---

Geom Title=Existing Conditions

River Reach=UNT 052 in La Ja,Reach-1
Reach XY= 30
      2094975.00     13443175.00      2095125.00     13443025.00
      2095225.00     13442975.00      2095325.00     13442824.05
      2095325.00     13442775.00      2095475.00     13442525.00
      2095475.00     13442375.00      2095575.00     13442325.00
      2095837.61     13441984.39      2096010.80     13441834.54
      2096110.80     13441824.54      2096220.80     13441714.54
      2096360.80     13441624.54      2096490.80     13441624.54
      2096630.80     13441514.54      2096770.80     13441504.54
      2097196.98     13441372.63      2097411.83     13441392.16
      2097670.80     13441374.54      2097730.80     13441314.54
      2097730.80     13441264.54      2097910.80     13441124.54
      2097990.80     13441004.54      2098000.80     13440944.54
      2098050.80     13440934.54      2098190.80     13440804.54
      2098440.80     13440804.54      2098570.80     13440854.54
      2098687.87     13440854.54      2098874.43     13440666.68

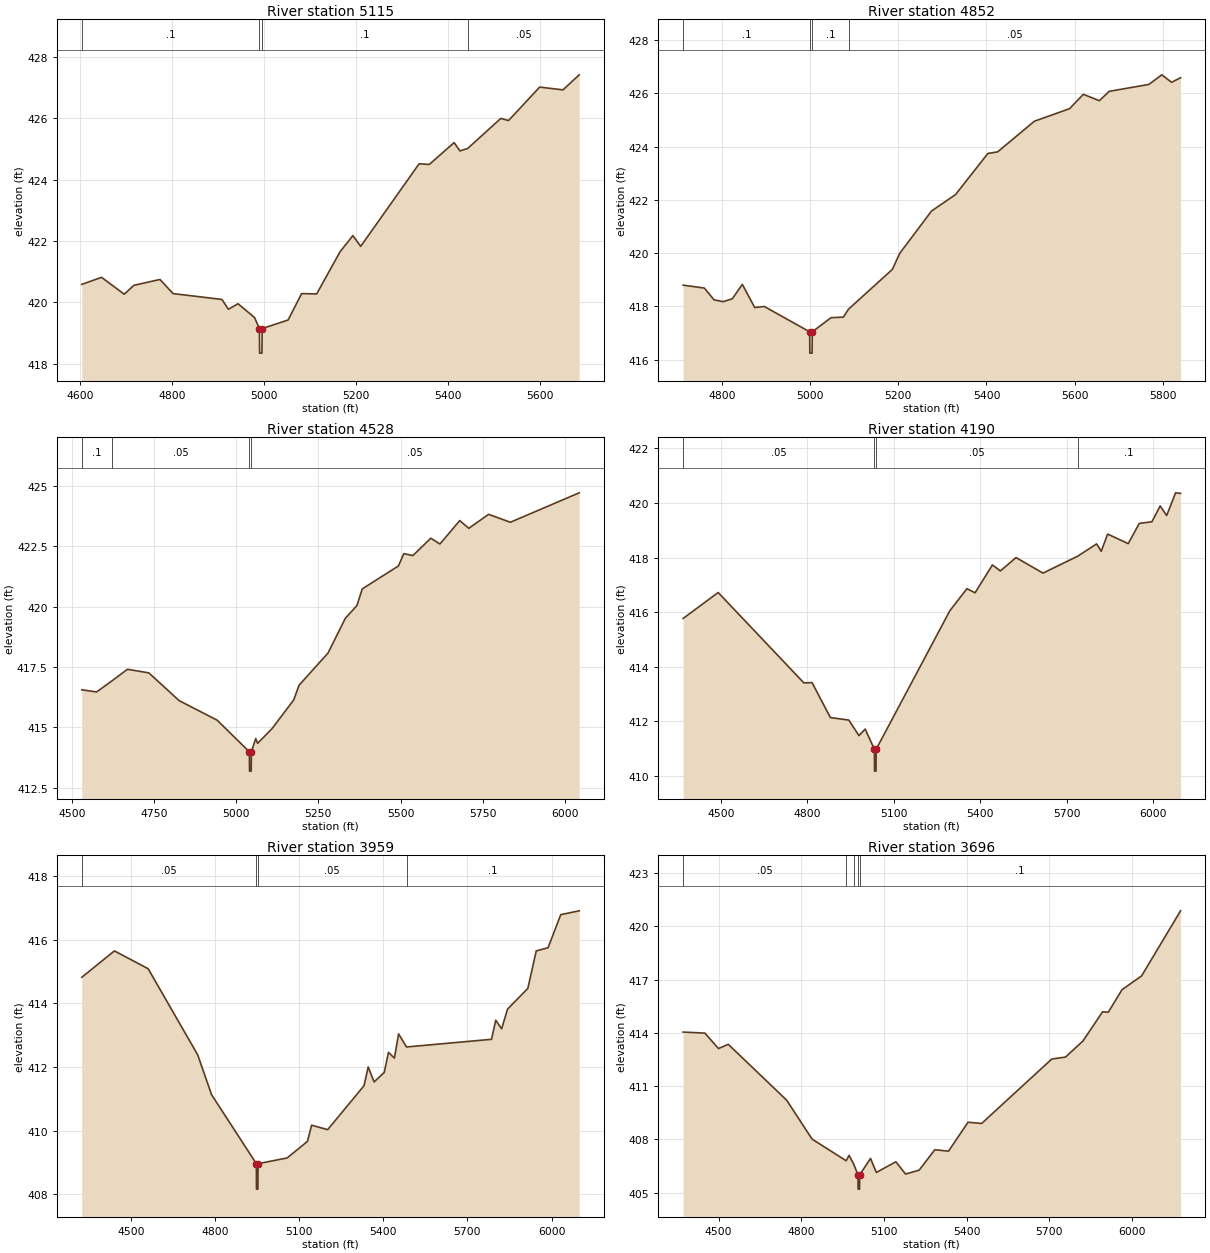
Type RM Length L Ch R = 1,5115,263,263,263
BEGIN DESCRIPTION:
UNT 052 in La Jarita Watershed 2.0
END DESCRIPTION:
XS GIS Cut Line= 3
      2095322.70     13443387.55      2095060.86     13443093.35
      2094441.63     13442792.94
#Sta/Elev= 30
  4603.0  420.59  4646.0  420.82  4695.4  420.27  4716.3  420.56  4773.1  420.75
  4801.6  420.29  4907.8  420.10  4922.0  419.78  4942.9  419.96  4978.8  419.51
  4989.4  419.15  4989.9  418.35  4994.9  418.35  4995.4  419.15  5051.9  419.43
  5081.2  420.29  5114.0  420.28  5164.7  421.65  5192.8  422.18  5209.8  421.83
  5336.8  424.52  5359.0  424.50  5413.0  425.21  5425.7  424.94  5442.5  425.02
  5514.6  426.00  5531.4  425.93  5599.1  427.02  5649.8  426.93  5685.1  427.42
#Mann=4,-1,0
  4603.0     0.1       0  4989.4    0.07       0  4995.4     0.1       0
  5442.5    0.05       0
Bank Sta=4989.4,4995.4
Exp/Cntr=0.3,0.1

Type RM Length L Ch R = 1,4852,324,324,324
BEGIN DESCRIPTION:
Mapping XS 95616b99
END DESCRIPTION:
XS GIS Cut Line= 3
      2095483.03     13443104.73      2095234.47     13442911.06
      2094511.04     13442541.18
#Sta/Elev= 30
  4712.4  418.80  4760.6  418.69  4782.4  418.25  4803.2  418.18  4824.0  418.29
  4846.6  418.83  4874.7  417.96  4896.4  418.00  4999.2  417.05  4999.7  416.25
  5004.7  416.25  5005.2  417.05  5047.8  417.58  5075.6  417.60  5087.4  417.90
  5186.7  419.39  5203.3  419.99  5275.5  421.58  5330.1  422.20  5403.2  423.74
  5425.4  423.80  5508.7  424.95  5588.5  425.42  5619.7  425.96  5655.9  425.72
  5678.3  426.07  5768.2  426.33  5797.5  426.69  5819.7  426.41  5840.0  426.58
#Mann=4,-1,0
  4712.4     0.1       0  4999.2    0.07       0  5005.2     0.1       0
  5087.4    0.05       0
Bank Sta=4999.2,5005.2
Exp/Cntr=0.3,0.1

Type RM Length L Ch R = 1,4528,338,338,338
BEGIN DESCRIPTION:
Mapping XS 22d48547
END DESCRIPTION:
XS GIS Cut Line= 3
      2095791.80     13442921.50      2095413.41     13442652.74
      2094486.23     13442161.07
#Sta/Elev= 30
  4530.1  416.55  4575.2  416.46  4622.0  416.92  4669.0  417.40  4734.2  417.25
  4826.5  416.10  4942.1  415.29  5040.1  413.98  5040.6  413.18  5045.6  413.18
  5046.1  413.98  5059.4  414.53  5065.1  414.33  5109.0  414.94  5175.0  416.13
  5191.3  416.74  5279.3  418.07  5332.0  419.51  5367.3  420.04  5383.6  420.73
  5493.6  421.68  5509.9  422.19  5537.6  422.11  5592.2  422.83  5619.9  422.59
  5680.2  423.56  5707.8  423.24  5768.1  423.82  5834.1  423.49  6043.7  424.71
#Mann=4,-1,0
  4530.1     0.1       0  4622.0    0.05       0  5040.1    0.03       0
  5046.1    0.05       0
Bank Sta=5040.1,5046.1
Exp/Cntr=0.3,0.1

Type RM Length L Ch R = 1,4190,231,231,231
BEGIN DESCRIPTION:
Mapping XS f7251625
END DESCRIPTION:
XS GIS Cut Line= 3
      2095968.00     13442793.90      2095473.19     13442312.10
      2094562.73     13441822.89
#Sta/Elev= 30
  4369.8  415.77  4491.3  416.72  4788.4  413.41  4816.7  413.42  4880.3  412.14
  4944.0  412.05  4979.3  411.48  5000.6  411.72  5032.9  410.98  5033.4  410.18
  5038.4  410.18  5038.9  410.98  5294.2  416.05  5353.5  416.86  5381.8  416.71
  5441.9  417.73  5469.5  417.51  5523.8  418.00  5617.2  417.43  5737.5  418.05
  5803.1  418.50  5819.0  418.23  5841.3  418.86  5912.7  418.51  5950.9  419.25
  5994.7  419.31  6023.3  419.89  6046.0  419.54  6076.7  420.37  6094.0  420.35
#Mann=4,-1,0
  4369.8    0.05       0  5032.9    0.03       0  5038.9    0.05       0
  5737.5     0.1       0
Bank Sta=5032.9,5038.9
Exp/Cntr=0.3,0.1

Type RM Length L Ch R = 1,3959,263,263,263
BEGIN DESCRIPTION:
Mapping XS b8bb65fe
END DESCRIPTION:
XS GIS Cut Line= 3
      2096173.71     13442650.64      2095659.82     13442178.42
      2094760.62     13441586.76
#Sta/Elev= 30
  4324.5  414.82  4440.9  415.65  4561.2  415.09  4738.1  412.38  4787.4  411.13
  4947.2  408.96  4947.7  408.16  4952.7  408.16  4953.2  408.96  5057.0  409.14
  5129.3  409.66  5144.4  410.17  5201.6  410.03  5331.1  411.41  5346.2  412.00
  5367.3  411.53  5403.4  411.83  5418.5  412.46  5439.6  412.28  5454.6  413.04
  5482.9  412.63  5786.0  412.87  5801.1  413.47  5822.1  413.20  5843.2  413.82
  5915.5  414.47  5945.6  415.65  5987.8  415.75  6033.0  416.79  6098.8  416.91
#Mann=4,-1,0
  4324.5    0.05       0  4947.2    0.03       0  4953.2    0.05       0
  5482.9     0.1       0
Bank Sta=4947.2,4953.2
Exp/Cntr=0.3,0.1

Type RM Length L Ch R = 1,3696,242,242,242
BEGIN DESCRIPTION:
Mapping XS a14165b2
END DESCRIPTION:
XS GIS Cut Line= 3
      2096281.35     13442430.16      2095720.58     13441869.39
      2094982.84     13441177.03
#Sta/Elev= 30
  4371.2  414.04  4450.1  413.98  4499.6  413.11  4534.9  413.35  4747.0  410.20
  4839.0  408.01  4962.6  406.79  4973.3  407.09  4989.8  406.61  5005.7  405.99
  5006.2  405.19  5011.2  405.19  5011.7  405.99  5051.1  406.92  5072.3  406.13
  5143.0  406.73  5178.4  406.04  5227.7  406.26  5284.4  407.41  5334.2  407.33
  5405.0  408.96  5454.3  408.89  5708.8  412.52  5758.6  412.63  5822.1  413.54
  5893.0  415.18  5914.0  415.16  5963.8  416.43  6034.6  417.20  6176.0  420.87
#Mann=5,-1,0
  4371.2    0.05       0  4962.6    0.12       0  4989.8     0.1       0
  5005.7    0.07       0  5011.7     0.1       0
Bank Sta=5005.7,5011.7
Exp/Cntr=0.3,0.1

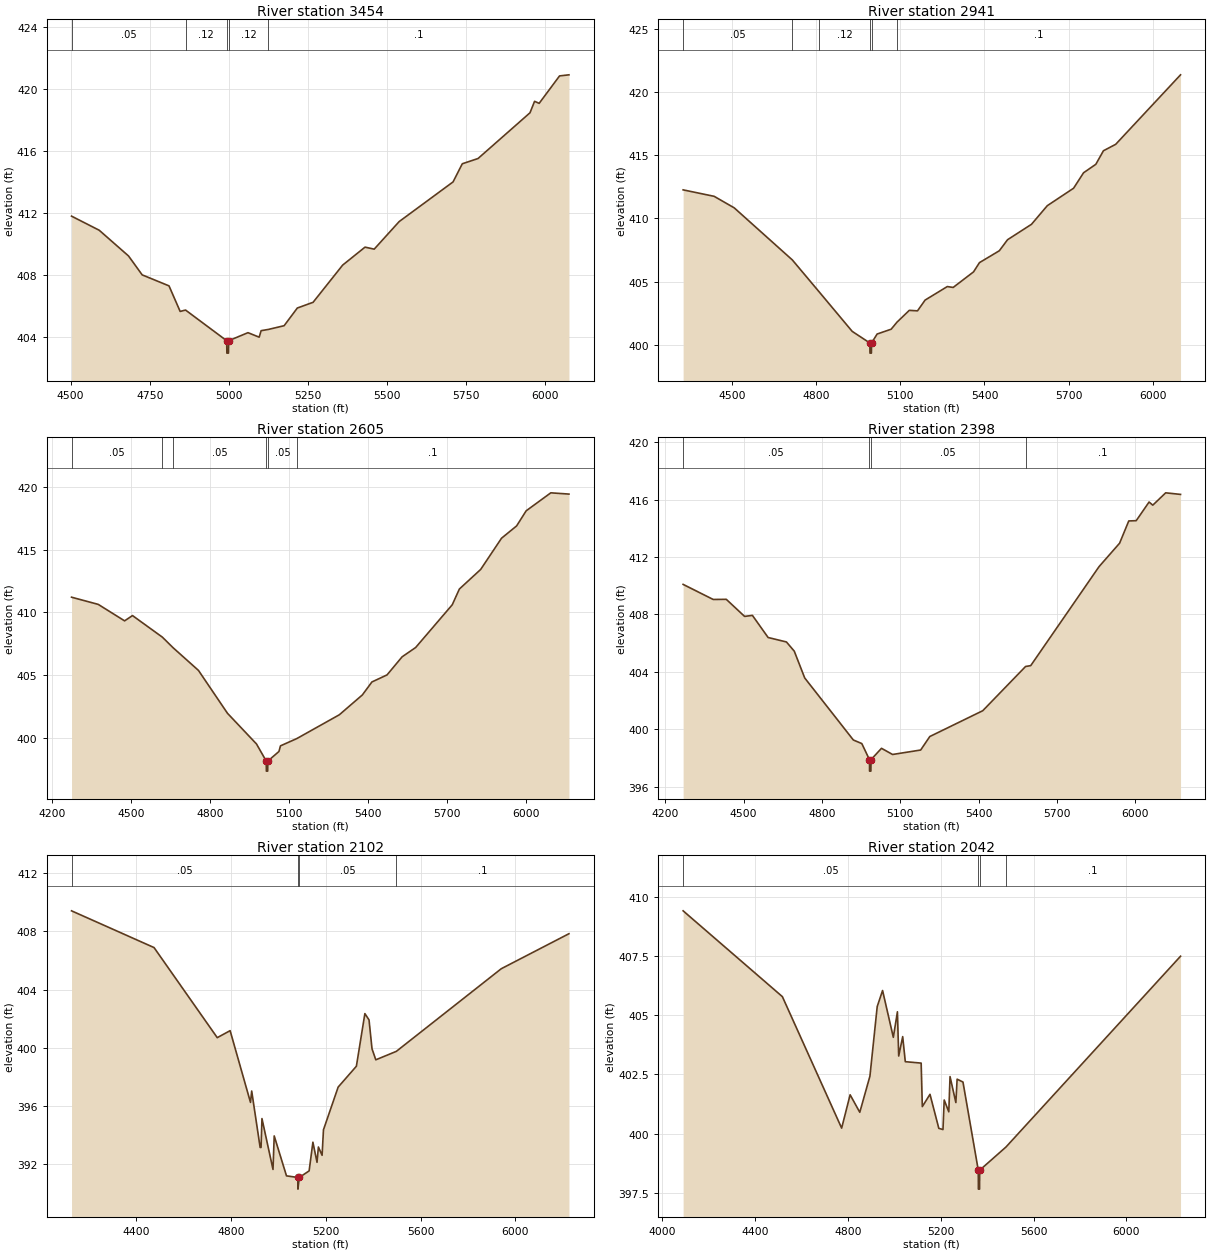
Type RM Length L Ch R = 1,3454,513,513,513
BEGIN DESCRIPTION:
Mapping XS a25a70a4
END DESCRIPTION:
XS GIS Cut Line= 3
      2096333.41     13442220.07      2096000.10     13441810.37
      2095364.81     13440982.61
#Sta/Elev= 30
  4503.0  411.81  4590.5  410.90  4683.1  409.24  4726.2  408.02  4811.0  407.31
  4846.2  405.66  4863.2  405.75  4993.3  403.77  4993.8  402.97  4998.8  402.97
  4999.3  403.77  5060.5  404.29  5095.8  404.00  5102.1  404.42  5125.1  404.50
  5174.7  404.74  5216.4  405.88  5266.2  406.25  5359.6  408.65  5430.3  409.81
  5459.3  409.68  5538.2  411.46  5708.5  414.02  5737.6  415.19  5787.4  415.53
  5951.5  418.48  5966.0  419.22  5980.5  419.09  6044.9  420.86  6074.6  420.93
#Mann=5,-1,0
  4503.0    0.05       0  4863.2    0.12       0  4993.3    0.07       0
  4999.3    0.12       0  5125.1     0.1       0
Bank Sta=4993.3,4999.3
Exp/Cntr=0.3,0.1

Type RM Length L Ch R = 1,2941,336,336,336
BEGIN DESCRIPTION:
Mapping XS 5b73b389
END DESCRIPTION:
XS GIS Cut Line= 3
      2096507.16     13442295.07      2096442.75     13441628.46
      2095783.02     13440743.03
#Sta/Elev= 30
  4325.4  412.26  4436.0  411.75  4507.6  410.84  4715.0  406.72  4809.8  404.22
  4928.3  401.08  4991.3  400.16  4991.8  399.36  4996.8  399.36  4997.3  400.16
  5017.3  400.87  5067.3  401.25  5088.2  401.81  5132.0  402.74  5161.2  402.70
  5188.3  403.55  5267.5  404.62  5288.4  404.55  5361.1  405.78  5382.2  406.51
  5453.1  407.45  5482.3  408.32  5567.8  409.54  5624.1  411.01  5717.9  412.39
  5753.4  413.61  5797.2  414.28  5824.3  415.35  5868.1  415.86  6099.3  421.35
#Mann=6,-1,0
  4325.4    0.05       0  4715.0     0.1       0  4809.8    0.12       0
  4991.3    0.07       0  4997.3    0.12       0  5088.2     0.1       0
Bank Sta=4991.3,4997.3
Exp/Cntr=0.3,0.1

Type RM Length L Ch R = 1,2605,207,207,207
BEGIN DESCRIPTION:
Mapping XS 0b948db7
END DESCRIPTION:
XS GIS Cut Line= 3
      2096753.69     13442236.10      2096722.44     13441486.07
      2096100.90     13440534.67
#Sta/Elev= 30
  4275.1  411.21  4376.3  410.64  4476.4  409.33  4506.4  409.75  4619.9  408.03
  4660.0  407.20  4756.6  405.39  4866.7  401.98  4976.8  399.54  5013.8  398.18
  5014.3  397.38  5019.3  397.38  5019.8  398.18  5061.9  398.94  5067.8  399.39
  5129.9  399.97  5291.0  401.86  5378.5  403.44  5414.7  404.47  5472.0  405.03
  5529.3  406.47  5580.6  407.21  5719.5  410.61  5746.5  411.86  5827.4  413.42
  5906.4  415.90  5963.7  416.88  5999.9  418.08  6093.4  419.51  6162.2  419.41
#Mann=6,-1,0
  4275.1    0.05       0  4619.9     0.1       0  4660.0    0.05       0
  5013.8    0.03       0  5019.8    0.05       0  5129.9     0.1       0
Bank Sta=5013.8,5019.8
Exp/Cntr=0.3,0.1

Type RM Length L Ch R = 1,2398,296,296,296
BEGIN DESCRIPTION:
Mapping XS aa8af8d2
END DESCRIPTION:
XS GIS Cut Line= 4
      2096951.60     13442170.12      2096979.38     13441604.13
      2096725.91     13440972.18      2096289.56     13440480.42
#Sta/Elev= 30
  4268.1  410.09  4383.4  409.04  4433.4  409.05  4503.5  407.86  4533.5  407.93
  4593.6  406.39  4663.7  406.08  4693.7  405.44  4733.8  403.57  4920.0  399.25
  4952.4  399.00  4981.7  397.88  4982.2  397.08  4987.2  397.08  4987.7  397.88
  5027.8  398.67  5070.2  398.24  5177.8  398.55  5212.8  399.49  5415.7  401.29
  5579.6  404.37  5599.3  404.43  5861.1  411.33  5939.7  412.96  5974.8  414.51
  6003.3  414.53  6052.6  415.83  6066.8  415.61  6116.2  416.47  6173.1  416.36
#Mann=4,-1,0
  4268.1    0.05       0  4981.7    0.03       0  4987.7    0.05       0
  5579.6     0.1       0
Bank Sta=4981.7,4987.7
Exp/Cntr=0.3,0.1

Type RM Length L Ch R = 1,2102,60,60,60
BEGIN DESCRIPTION:
Mapping XS 4b1dbe8d
END DESCRIPTION:
XS GIS Cut Line= 6
      2097011.08     13442224.31      2097189.02     13441447.44
      2097232.42     13441230.43      2097189.02     13441204.39
      2097154.30     13441204.39      2096742.58     13440298.61
#Sta/Elev= 30
  4127.4  409.40  4475.5  406.88  4742.2  400.70  4796.5  401.18  4882.4  396.26
  4887.5  397.04  4923.1  393.17  4927.0  393.17  4930.8  395.15  4977.4  391.66
  4982.5  393.96  5034.3  391.22  5082.1  391.11  5082.6  390.31  5088.1  391.11
  5129.8  391.56  5145.7  393.53  5163.1  392.15  5168.9  393.20  5184.5  392.63
  5190.3  394.38  5252.3  397.31  5329.2  398.74  5365.0  402.35  5382.5  401.92
  5395.1  399.94  5411.1  399.18  5497.7  399.76  5940.6  405.43  6226.0  407.83
#Mann=4,-1,0
  4127.4    0.05       0  5082.1    0.03       0  5088.1    0.05       0
  5497.7     0.1       0
Bank Sta=5082.1,5088.1
Exp/Cntr=0.3,0.1

Type RM Length L Ch R = 1,2042,40,40,40
BEGIN DESCRIPTION:
Mapping XS b36a7740
END DESCRIPTION:
XS GIS Cut Line= 6
      2097028.43     13442254.73      2097280.16     13441338.94
      2097293.19     13441239.11      2097275.82     13441182.69
      2097193.36     13441152.31      2096798.40     13440297.29
#Sta/Elev= 30
  4091.6  409.42  4518.9  405.79  4774.0  400.23  4810.5  401.64  4852.1  400.90
  4895.8  402.43  4927.1  405.37  4950.2  406.05  4996.5  404.07  5014.1  405.15
  5019.6  403.28  5036.8  404.10  5048.0  403.04  5116.3  402.98  5121.3  401.14
  5154.3  401.66  5192.3  400.22  5210.2  400.17  5215.5  401.42  5235.3  400.92
  5240.6  402.41  5265.7  401.31  5271.1  402.30  5296.3  402.18  5362.2  398.45
  5362.7  397.65  5367.7  397.65  5368.2  398.45  5481.3  399.43  6232.9  407.50
#Mann=4,-1,0
  4091.6    0.05       0  5362.2    0.03       0  5368.2    0.05       0
  5481.3     0.1       0
Bank Sta=5362.2,5368.2
Exp/Cntr=0.3,0.1

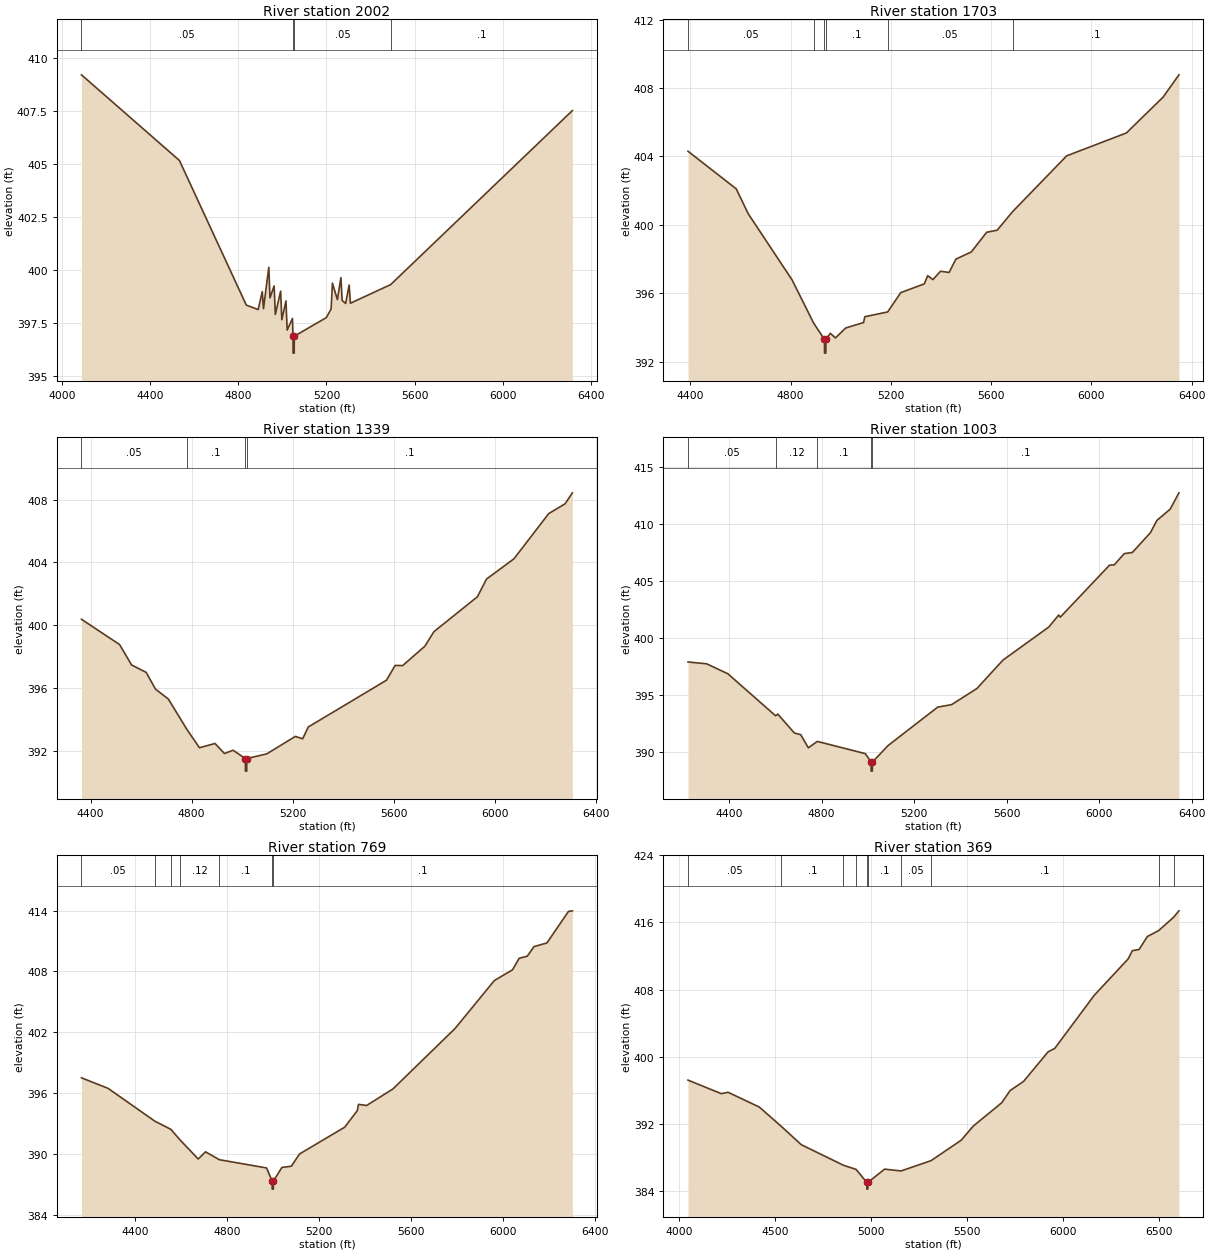
Type RM Length L Ch R = 1,2002,299,299,299
BEGIN DESCRIPTION:
Mapping XS 32337abe
END DESCRIPTION:
XS GIS Cut Line= 6
      2097045.79     13442254.73      2097323.57     13441330.26
      2097336.59     13441200.05      2097310.55     13441152.31
      2097189.02     13441095.88      2096850.63     13440219.54
#Sta/Elev= 30
  4089.2  409.22  4533.4  405.17  4836.7  398.33  4890.4  398.12  4909.1  398.97
  4914.5  398.16  4938.7  400.12  4944.0  398.67  4962.8  399.24  4968.2  397.89
  4992.3  398.99  4997.7  397.64  5016.5  398.53  5021.9  397.15  5046.0  397.70
  5048.3  396.86  5048.8  396.06  5053.8  396.06  5054.3  396.86  5199.5  397.74
  5221.3  398.15  5227.0  399.37  5249.7  398.59  5265.5  399.63  5271.3  398.55
  5287.1  398.41  5303.0  399.28  5308.7  398.42  5491.1  399.30  6315.2  407.53
#Mann=4,-1,0
  4089.2    0.05       0  5048.3    0.03       0  5054.3    0.05       0
  5491.1     0.1       0
Bank Sta=5048.3,5054.3
Exp/Cntr=0.3,0.1

Type RM Length L Ch R = 1,1703,364,364,364
BEGIN DESCRIPTION:
Mapping XS 8ecfee99
END DESCRIPTION:
XS GIS Cut Line= 4
      2097536.24     13441968.27      2097636.07     13441542.93
      2097475.48     13440792.06      2097110.90     13440132.35
#Sta/Elev= 30
  4390.9  404.30  4583.3  402.10  4630.9  400.65  4805.8  396.78  4892.0  394.25
  4935.2  393.29  4935.7  392.49  4940.7  392.49  4941.2  393.29  4958.6  393.65
  4979.1  393.38  5020.0  393.96  5091.2  394.28  5096.3  394.62  5187.5  394.90
  5239.6  396.03  5333.4  396.54  5347.2  397.02  5367.7  396.79  5398.3  397.28
  5432.4  397.21  5459.7  397.99  5521.1  398.41  5582.4  399.56  5624.3  399.68
  5686.0  400.77  5901.5  404.03  6139.8  405.37  6286.4  407.47  6349.4  408.77
#Mann=6,-1,0
  4390.9    0.05       0  4892.0     0.1       0  4935.2    0.07       0
  4941.2     0.1       0  5187.5    0.05       0  5686.0     0.1       0
Bank Sta=4935.2,4941.2
Exp/Cntr=0.3,0.1

Type RM Length L Ch R = 1,1339,336,336,336
BEGIN DESCRIPTION:
Mapping XS d784d4dd
END DESCRIPTION:
XS GIS Cut Line= 4
      2097853.08     13441803.35      2097918.19     13441456.13
      2097727.21     13440627.13      2097323.54     13440006.43
#Sta/Elev= 30
  4364.0  400.38  4515.0  398.77  4562.5  397.47  4620.2  397.00  4657.4  395.93
  4708.2  395.30  4781.0  393.38  4831.3  392.20  4892.9  392.47  4930.4  391.83
  4964.7  392.04  5013.0  391.51  5013.5  390.71  5018.5  390.71  5019.0  391.51
  5098.1  391.81  5211.0  392.92  5240.2  392.77  5262.3  393.52  5572.2  396.50
  5606.3  397.44  5636.2  397.43  5723.8  398.66  5760.0  399.59  5932.0  401.81
  5968.3  402.94  6077.0  404.23  6214.7  407.11  6279.3  407.73  6308.4  408.43
#Mann=4,-1,0
  4364.0    0.05       0  4781.0     0.1       0  5013.0    0.07       0
  5019.0     0.1       0
Bank Sta=5013,5019
Exp/Cntr=0.3,0.1

Type RM Length L Ch R = 1,1003,234,234,234
BEGIN DESCRIPTION:
Mapping XS d0b7af17
END DESCRIPTION:
XS GIS Cut Line= 4
      2098057.08     13441694.79      2098122.18     13441221.75
      2097887.80     13440444.84      2097345.27     13439811.16
#Sta/Elev= 30
  4222.5  397.91  4303.0  397.75  4394.8  396.88  4601.4  393.20  4610.8  393.35
  4682.8  391.69  4709.9  391.55  4742.9  390.40  4781.8  390.96  4989.4  389.89
  5014.2  389.16  5014.7  388.36  5019.7  388.36  5020.2  389.16  5088.4  390.61
  5302.4  393.96  5362.6  394.18  5472.0  395.59  5584.3  398.07  5783.0  400.97
  5825.8  402.02  5832.4  401.83  6045.4  406.38  6066.2  406.41  6109.0  407.39
  6144.1  407.49  6222.2  409.22  6250.6  410.30  6307.7  411.28  6345.7  412.71
#Mann=5,-1,0
  4222.5    0.05       0  4601.4    0.12       0  4781.8     0.1       0
  5014.2    0.07       0  5020.2     0.1       0
Bank Sta=5014.2,5020.2
Exp/Cntr=0.3,0.1

Type RM Length L Ch R = 1,769,400,400,400
BEGIN DESCRIPTION:
Mapping XS 9d231c9e
END DESCRIPTION:
XS GIS Cut Line= 4
      2098087.46     13441603.68      2098261.07     13441130.60
      2098165.58     13440440.50      2097601.33     13439693.95
#Sta/Elev= 30
  4166.9  397.50  4282.7  396.46  4485.8  393.23  4556.4  392.41  4594.4  391.41
  4675.0  389.49  4706.8  390.20  4767.3  389.42  4972.4  388.61  4996.5  387.32
  4997.0  386.52  5002.0  386.52  5002.5  387.32  5039.1  388.66  5080.3  388.78
  5116.0  389.99  5312.5  392.63  5367.5  394.27  5372.4  394.88  5407.8  394.77
  5522.3  396.40  5792.9  402.37  5963.5  407.09  6042.6  408.15  6071.7  409.29
  6107.1  409.50  6136.2  410.44  6192.4  410.80  6286.1  413.91  6303.3  413.97
#Mann=7,-1,0
  4166.9    0.05       0  4485.8    0.12       0  4556.4     0.1       0
  4594.4    0.12       0  4767.3     0.1       0  4996.5    0.07       0
  5002.5     0.1       0
Bank Sta=4996.5,5002.5
Exp/Cntr=0.3,0.1

Type RM Length L Ch R = 1,369,0,0,0
BEGIN DESCRIPTION:
Mapping XS c7ac2829
END DESCRIPTION:
XS GIS Cut Line= 4
      2098096.15     13441621.05      2098586.59     13441078.52
      2098603.95     13440631.47      2097692.49     13439594.15
#Sta/Elev= 30
  4044.5  397.24  4217.7  395.63  4253.6  395.79  4416.5  394.03  4530.7  391.74
  4635.4  389.55  4854.9  387.11  4920.8  386.62  4976.5  385.07  4977.0  384.27
  4982.0  384.27  4982.5  385.07  5069.6  386.65  5155.0  386.43  5311.8  387.66
  5468.2  390.08  5531.8  391.77  5680.8  394.56  5723.5  395.99  5793.7  397.08
  5921.8  400.60  5956.9  401.02  6162.8  407.34  6339.3  411.66  6361.1  412.64
  6396.2  412.78  6438.9  414.31  6498.6  415.04  6575.7  416.60  6604.1  417.38
#Mann=10,-1,0
  4044.5    0.05       0  4530.7     0.1       0  4854.9    0.05       0
  4920.8     0.1       0  4976.5    0.07       0  4982.5     0.1       0
  5155.0    0.05       0  5311.8     0.1       0  6498.6    0.08       0
  6575.7     0.1       0
Bank Sta=4976.5,4982.5
Exp/Cntr=0.3,0.1

Chan Stop Cuts=-1