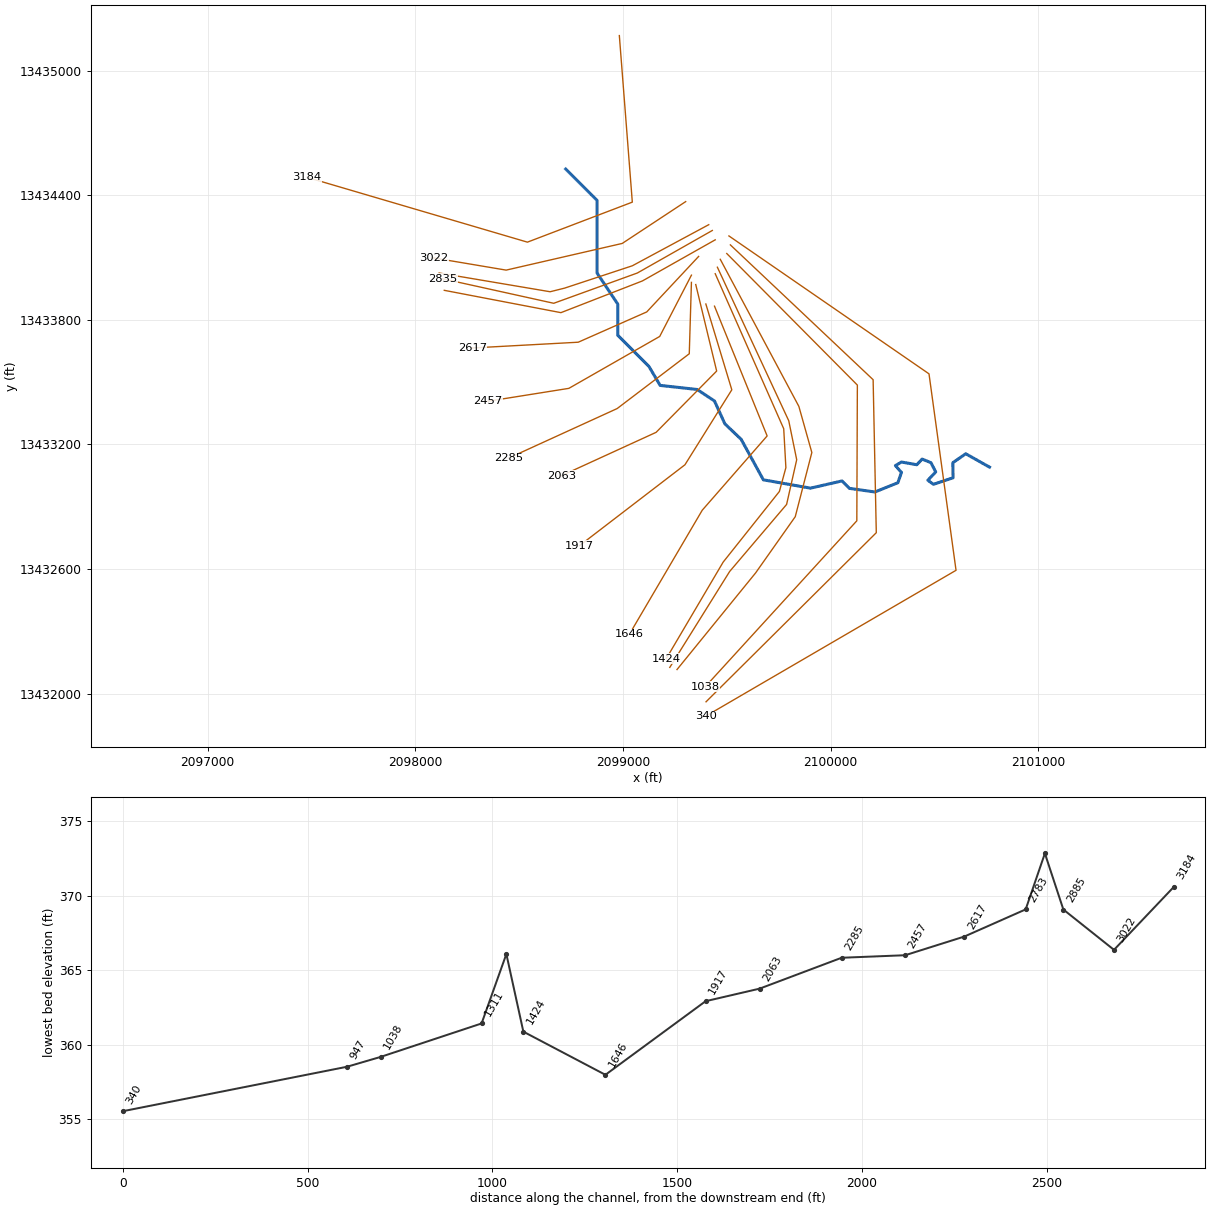
--- UNT 056 in La Jarita Watershed.prj (project) ---

Proj Title=UNT 056 in La Jarita Watershed Base Level Engineering
Current Plan=p01
Default Exp/Contr=0.3,0.1
English Units
Geom File=g01
Flow File=f01
Plan File=p01
Y Axis Title=Elevation
X Axis Title(PF)=Main Channel Distance
X Axis Title(XS)=Station
BEGIN DESCRIPTION:
UNT 056 in La Jarita Watershed
END DESCRIPTION:
DSS Export Rating Curves= 0
DSS Export Rating Curve Sorted= 0
DSS Export Volume Flow Curves= 0
DXF OffsetX= 0
DXF OffsetY= 0
DXF ScaleX= 1
DXF ScaleY= 10

--- UNT 056 in La Jarita Watershed.p01 (plan) ---

Plan Title=Multiple Run
Short Identifier=Multiple
Geom File=g01
Flow File=f01
Subcritical Flow
K Sum by GR= 0
Std Step Tol= 0.01
Critical Tol= 0.01
Num of Std Step Trials= 20
Max Error Tol= 0.3
Flow Tol Ratio= 0.001
Split Flow NTrial= 30
Split Flow Tol= 0.02
Split Flow Ratio= 0.02
Log Output Level= 0
Friction Slope Method= 1
Unsteady Friction Slope Method= 2
Unsteady Bridges Friction Slope Method= 1
Parabolic Critical Depth
Global Vel Dist=  1 , 1 , 1
Global Log Level= 0
CheckData=True
Encroach Param= -1, 0, 0, 0
BEGIN DESCRIPTION:
Multiple Run
END DESCRIPTION:

--- UNT 056 in La Jarita Watershed.f01 (steady flow) ---

Flow Title=Multiple
Number of Profiles=7
Profile Names=10-year,25-year,50-year,1pct_min,100-year,1pct_plu,500-year
River Rch & RM= UNT 056 in La Ja,Reach-1,3184
      99     129     153      90     181     360     256
Boundary for River Rch & Prof#=UNT 056 in La Ja,Reach-1,1
Up Type=0
Dn Type=3
Dn Slope=0.005
Boundary for River Rch & Prof#=UNT 056 in La Ja,Reach-1,2
Up Type=0
Dn Type=3
Dn Slope=0.005
Boundary for River Rch & Prof#=UNT 056 in La Ja,Reach-1,3
Up Type=0
Dn Type=3
Dn Slope=0.005
Boundary for River Rch & Prof#=UNT 056 in La Ja,Reach-1,4
Up Type=0
Dn Type=3
Dn Slope=0.005
Boundary for River Rch & Prof#=UNT 056 in La Ja,Reach-1,5
Up Type=0
Dn Type=3
Dn Slope=0.005
Boundary for River Rch & Prof#=UNT 056 in La Ja,Reach-1,6
Up Type=0
Dn Type=3
Dn Slope=0.005
Boundary for River Rch & Prof#=UNT 056 in La Ja,Reach-1,7
Up Type=0
Dn Type=3
Dn Slope=0.005

--- UNT 056 in La Jarita Watershed.g01 (geometry) ---

Geom Title=Existing Conditions
Program Version=5.05

River Reach=UNT 056 in La Ja,Reach-1
Reach XY= 30
      2098724.05     13434525.95        2098875.       13434375.
        2098875.       13434025.        2098975.       13433875.
        2098975.       13433725.        2099125.       13433575.
      2099178.97     13433483.77      2099356.92     13433464.24
      2099440.47      13433408.9      2099490.39     13433299.31
       2099569.6     13433223.35      2099675.93     13433029.13
      2099902.71     13432988.98      2100054.62      13433023.7
      2100090.43     13432987.89      2100213.04     13432970.53
      2100323.72     13433015.02      2100341.08     13433064.93
      2100311.78     13433097.49      2100341.08     13433114.85
      2100414.87     13433101.83      2100440.91     13433128.95
      2100483.23     13433111.59      2100506.01      13433067.1
      2100468.03     13433026.96      2100495.16     13433007.43
      2100589.56     13433038.89      2100588.48     13433111.59
       2100650.8     13433154.54      2100765.03      13433090.3

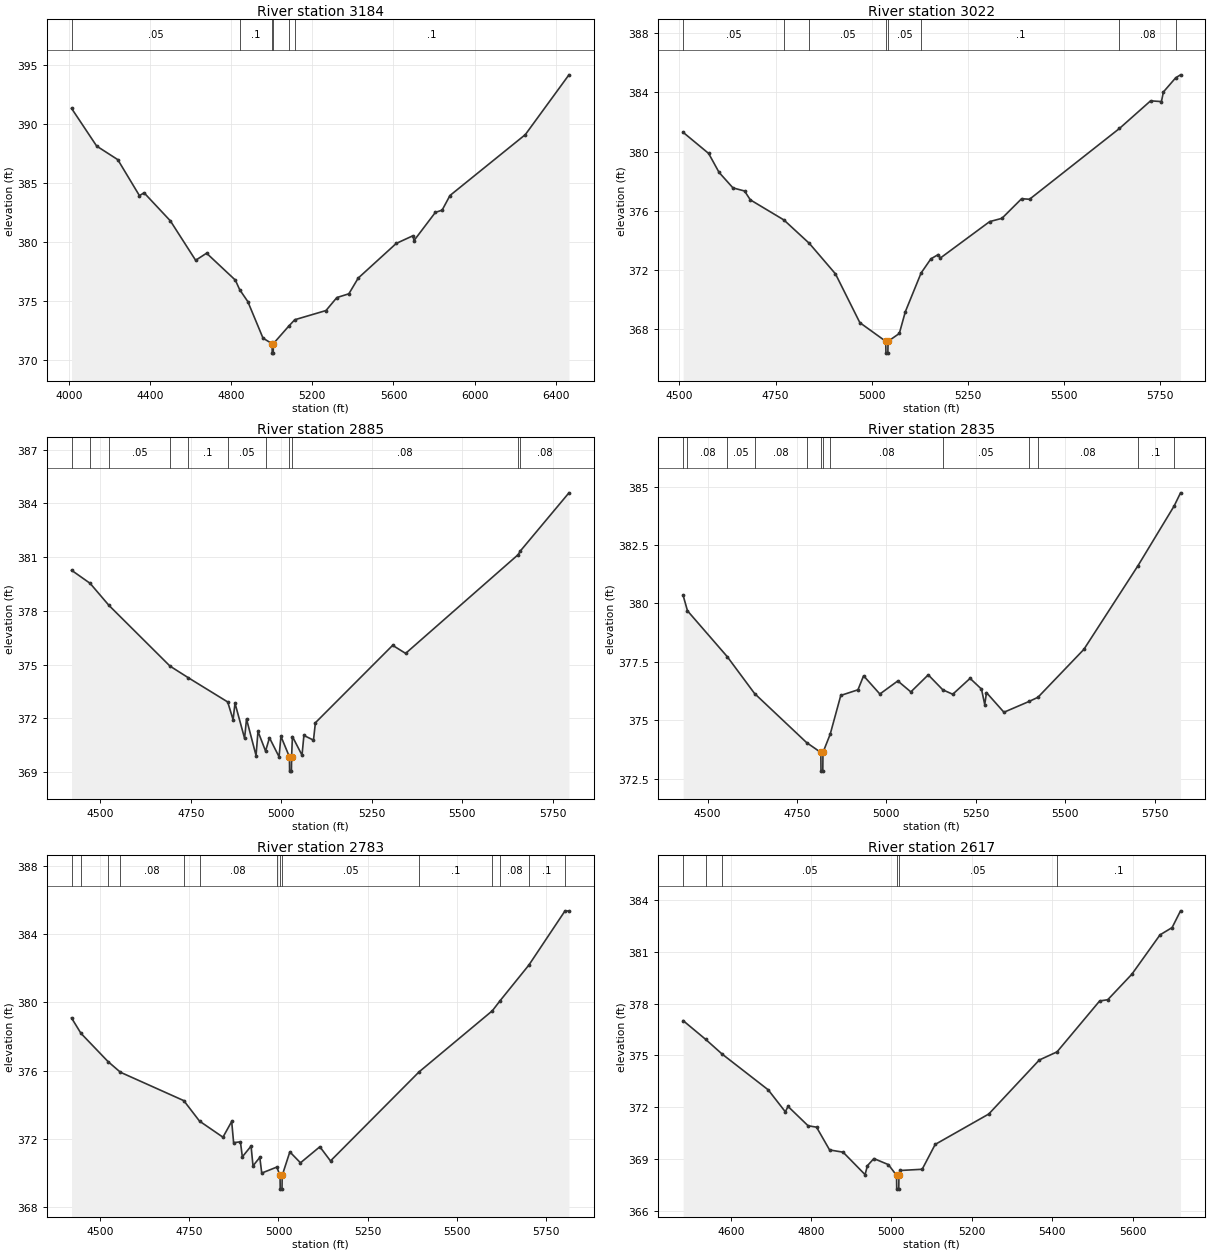
Type RM Length L Ch R = 1 ,3184    ,162,162,162
BEGIN DESCRIPTION:
UNT 056 in La Jarita Watershed 3.0
END DESCRIPTION:
XS GIS Cut Line= 4
      2098982.39     13435168.56       2099044.9     13434366.43
      2098539.69     13434173.72      2097478.61     13434485.81
#Sta/Elev= 30
  4013.6  391.33  4137.5  388.13  4241.5  386.98  4348.2  383.93  4371.1  384.17
  4500.7  381.79  4625.2  378.45  4679.2  379.05  4820.8  376.77  4842.2  375.96
  4882.3  374.95  4957.2  371.85    5002  371.38  5002.5  370.58  5007.5  370.58
    5008  371.38  5083.1  372.85  5113.7  373.41  5267.6  374.19  5321.1  375.29
  5380.3  375.61  5426.3  376.94  5613.9  379.88  5696.1  380.53  5701.3  380.12
  5806.6  382.51  5839.9   382.7  5878.5  383.94  6249.8   389.1  6464.9  394.17
#Mann= 6 ,-1 , 0
  4013.6     .05       0  4842.2      .1       0    5002     .07       0
    5008      .1       0  5083.1     .05       0  5113.7      .1       0
Bank Sta=5002,5008
XS Rating Curve= 0 ,0
Exp/Cntr=0.3,0.1

Type RM Length L Ch R = 1 ,3022    ,137,137,137
BEGIN DESCRIPTION:
Mapping XS e1df25c5
END DESCRIPTION:
XS GIS Cut Line= 4
      2099301.84     13434368.91      2098996.25      13434167.5
      2098437.23     13434039.03      2098088.22     13434097.78
#Sta/Elev= 30
  4509.6   381.3    4576  379.87    4603  378.59  4639.2  377.54  4669.3  377.33
  4684.4  376.73  4771.7  375.37    4838  373.78  4905.8  371.72  4969.2  368.42
  5036.5  367.16    5037  366.36    5042  366.36  5042.5  367.16  5071.8  367.69
  5087.4  369.16  5128.4  371.78  5153.9  372.74  5173.1  373.03  5178.3  372.79
  5306.8  375.26  5338.6  375.48  5389.9  376.81  5410.4  376.77  5644.2  381.56
  5725.2  383.43  5753.4  383.38  5758.5  384.03  5790.5  384.99  5803.1  385.19
#Mann= 8 ,-1 , 0
  4509.6     .05       0  4771.7      .1       0    4838     .05       0
  5036.5    .033       0  5042.5     .05       0  5128.4      .1       0
  5644.2     .08       0  5790.5      .1       0
Bank Sta=5036.5,5042.5
XS Rating Curve= 0 ,0
Exp/Cntr=0.3,0.1

Type RM Length L Ch R = 1 ,2885    ,50,50,50
BEGIN DESCRIPTION:
Mapping XS 292a176a
END DESCRIPTION:
XS GIS Cut Line= 5
      2099412.91     13434257.78      2099044.86     13434059.87
      2098718.48     13433952.23      2098649.03     13433934.87
      2098114.35     13434025.14
#Sta/Elev= 30
    4420  380.27  4471.3  379.54  4523.4  378.31  4692.3  374.92    4743  374.27
  4851.8  372.92  4866.7  371.93    4872  372.85  4898.5  370.89  4903.8  371.97
  4930.2  369.93  4935.5  371.28  4956.5  370.18  4967.3  370.92  4993.8  369.86
    4999     371  5022.5  369.86    5023  369.06    5028  369.06  5028.5  369.86
  5030.8  370.99  5057.3  369.95  5062.5  371.05    5089  370.79  5094.3  371.76
  5307.9  376.08  5343.8  375.63  5654.9  381.14  5660.8  381.34  5795.4  384.59
#Mann= 11 ,-1 , 0
    4420      .1       0  4471.3     .08       0  4523.4     .05       0
  4692.3     .08       0    4743      .1       0  4851.8     .05       0
  4956.5     .08       0  5022.5     .07       0  5028.5     .08       0
  5654.9      .1       0  5660.8     .08       0
Bank Sta=5022.5,5028.5
XS Rating Curve= 0 ,0
Exp/Cntr=0.3,0.1

Type RM Length L Ch R = 1 ,2835    ,52,52,52
BEGIN DESCRIPTION:
Mapping XS 7d5a3fab
END DESCRIPTION:
XS GIS Cut Line= 4
      2099430.28       13434230.      2099069.17     13434025.14
      2098666.39     13433879.31      2098131.71     13433997.36
#Sta/Elev= 30
  4431.5  380.34  4443.7  379.68  4554.8  377.72  4631.4  376.14  4776.9  374.04
  4816.6  373.62  4817.1  372.82  4822.1  372.82  4822.6  373.62  4842.8   374.4
  4872.4  376.06  4920.4   376.3  4936.2   376.9  4981.7  376.12  5031.9  376.68
  5068.3  376.21    5117  376.94  5157.7   376.3  5185.5  376.11    5234  376.79
  5265.9  376.33    5275  375.67  5279.9  376.18  5328.7  375.34  5398.7   375.8
  5423.8  375.98  5552.2  378.03  5703.5  381.61  5804.8  384.17  5822.6  384.73
#Mann= 13 ,-1 , 0
  4431.5     .05       0  4443.7     .08       0  4554.8     .05       0
  4631.4     .08       0  4776.9      .1       0  4816.6     .07       0
  4822.6      .1       0  4842.8     .08       0  5157.7     .05       0
  5398.7      .1       0  5423.8     .08       0  5703.5      .1       0
  5804.8     .05       0
Bank Sta=4816.6,4822.6
XS Rating Curve= 0 ,0
Exp/Cntr=0.3,0.1

Type RM Length L Ch R = 1 ,2783    ,166,166,166
BEGIN DESCRIPTION:
Mapping XS faf0f7dd
END DESCRIPTION:
XS GIS Cut Line= 4
       2099444.2     13434184.88      2099093.48     13433986.95
      2098701.11     13433834.17      2098139.29     13433941.68
#Sta/Elev= 30
  4419.3  379.09  4445.7  378.19    4522  376.53  4556.6  375.91  4734.3  374.25
  4778.5  373.05  4844.2  372.11  4868.7  373.03  4874.1  371.79  4893.2  371.84
  4898.6  370.96  4923.1  371.59  4928.5  370.43  4947.6  370.93    4953  370.01
  4995.3  370.36  5004.4  369.87  5004.9  369.07  5009.9  369.07  5010.4  369.87
  5031.9  371.25  5061.7  370.61  5116.1  371.55    5146  370.72  5394.4  375.93
  5600.1  379.51  5622.3  380.11  5702.8  382.19  5803.5  385.34  5815.1  385.36
#Mann= 14 ,-1 , 0
  4419.3     .05       0  4445.7     .08       0    4522     .05       0
  4556.6     .08       0  4734.3     .05       0  4778.5     .08       0
  4995.3     .05       0  5004.4    .035       0  5010.4     .05       0
  5394.4      .1       0  5600.1     .05       0  5622.3     .08       0
  5702.8      .1       0  5803.5     .05       0
Bank Sta=5004.4,5010.4
XS Rating Curve= 0 ,0
Exp/Cntr=0.3,0.1

Type RM Length L Ch R = 1 ,2617    ,160,160,160
BEGIN DESCRIPTION:
Mapping XS 62ac3fc0
END DESCRIPTION:
XS GIS Cut Line= 4
      2099364.34     13434105.04      2099114.31     13433837.64
      2098784.45     13433691.81      2098274.05     13433664.03
#Sta/Elev= 30
  4481.6  377.01  4537.4  375.93  4578.8  375.07  4693.4     373  4735.9  371.73
  4742.7  372.04  4792.6  370.92  4813.6  370.84  4846.1  369.52  4879.7  369.39
  4934.4  368.09  4940.3  368.61  4956.3  369.02  4992.4  368.67  5012.7  368.05
  5013.2  367.25  5018.2  367.25  5018.7  368.05  5021.9  368.33  5076.5   368.4
  5108.9  369.84  5242.2   371.6    5368  374.73  5412.1   375.2  5518.2  378.15
  5538.3  378.22  5598.4   379.7  5668.5  381.98  5698.5   382.4  5719.5  383.37
#Mann= 6 ,-1 , 0
  4481.6     .05       0  4537.4     .08       0  4578.8     .05       0
  5012.7    .035       0  5018.7     .05       0  5412.1      .1       0
Bank Sta=5012.7,5018.7
XS Rating Curve= 0 ,0
Exp/Cntr=0.3,0.1

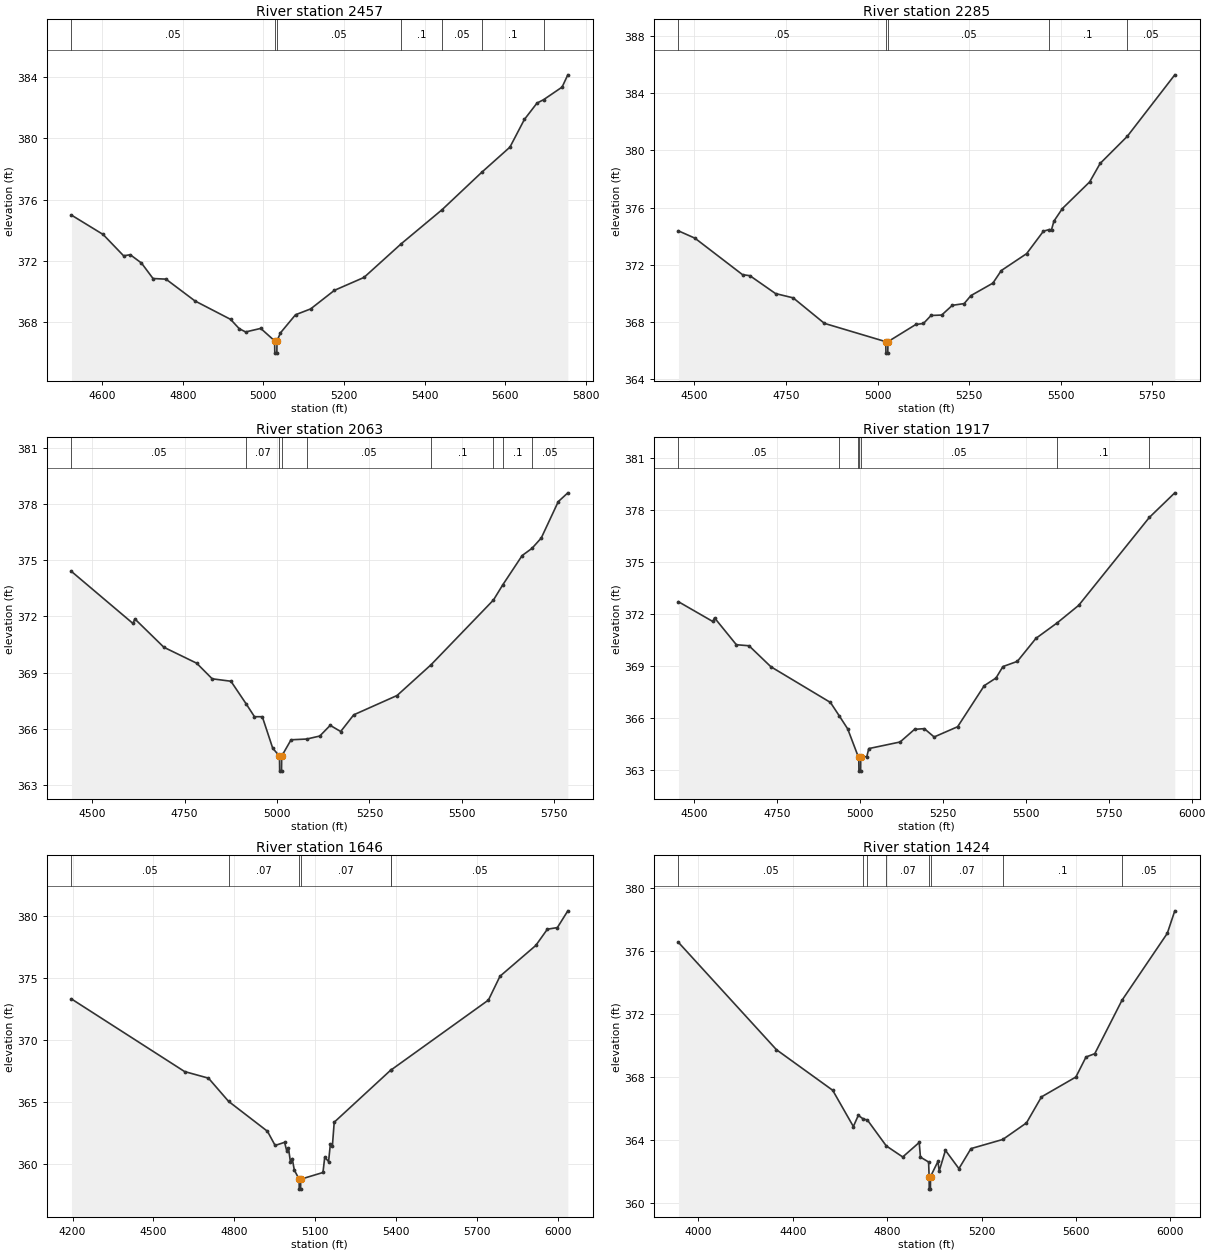
Type RM Length L Ch R = 1 ,2457    ,172,172,172
BEGIN DESCRIPTION:
Mapping XS 85c276c8
END DESCRIPTION:
XS GIS Cut Line= 4
      2099329.59     13434014.74      2099176.81     13433719.59
      2098739.31     13433469.59      2098348.48     13433407.33
#Sta/Elev= 30
  4523.7  374.99  4602.2  373.73  4653.1  372.34  4669.6  372.41  4697.4  371.87
  4726.1  370.86  4758.2  370.82  4830.2   369.4  4918.6   368.2  4940.2  367.59
    4956  367.38  4993.5  367.61  5027.9   366.8  5028.4     366  5033.4     366
  5033.9   366.8  5042.4  367.32  5079.8   368.5  5117.3  368.88  5176.3  370.09
  5249.7  370.93  5342.4  373.13  5443.4  375.34  5542.4  377.79    5612  379.42
  5647.8  381.22  5679.2  382.29  5695.5  382.51  5741.4  383.33  5755.7  384.13
#Mann= 7 ,-1 , 0
  4523.7     .05       0  5027.9    .035       0  5033.9     .05       0
  5342.4      .1       0  5443.4     .05       0  5542.4      .1       0
  5695.5     .05       0
Bank Sta=5027.9,5033.9
XS Rating Curve= 0 ,0
Exp/Cntr=0.3,0.1

Type RM Length L Ch R = 1 ,2285    ,222,222,222
BEGIN DESCRIPTION:
Mapping XS 1ab6003c
END DESCRIPTION:
XS GIS Cut Line= 4
      2099329.58     13433979.96      2099319.17     13433636.25
      2098971.95     13433372.37      2098448.86     13433133.34
#Sta/Elev= 30
  4456.5  374.37  4501.5  373.86  4631.5  371.31  4651.5  371.24  4721.6  369.99
  4769.8  369.69  4854.9  367.91  5022.5  366.63    5023  365.83    5028  365.83
  5028.5  366.63  5104.5  367.83  5125.3   367.9  5146.1  368.46  5175.2  368.49
  5204.3  369.17  5236.5  369.29  5255.1  369.85    5315  370.72    5338   371.6
  5407.1  372.78    5453  374.35  5468.7  374.46    5475  374.45  5481.6  375.05
  5504.7  375.93  5579.2  377.79  5607.8  379.08  5681.8  380.97  5811.6  385.27
#Mann= 5 ,-1 , 0
  4456.5     .05       0  5022.5    .035       0  5028.5     .05       0
  5468.7      .1       0  5681.8     .05       0
Bank Sta=5022.5,5028.5
XS Rating Curve= 0 ,0
Exp/Cntr=0.3,0.1

Type RM Length L Ch R = 1 ,2063    ,146,146,146
BEGIN DESCRIPTION:
Mapping XS c04bf515
END DESCRIPTION:
XS GIS Cut Line= 4
      2099350.42     13433969.58      2099451.11     13433552.92
      2099159.45     13433257.78      2098705.22     13433049.74
#Sta/Elev= 30
  4443.7   374.4    4610  371.63  4615.2  371.87  4693.8  370.36  4782.6  369.51
  4824.5  368.68  4875.2  368.55  4916.9  367.33  4938.9  366.66  4960.1  366.66
  4988.3  364.98  5006.6  364.56  5007.1  363.76  5012.1  363.76  5012.6  364.56
  5037.9  365.43  5080.3  365.47  5115.6  365.63  5143.9   366.2  5172.2  365.87
  5207.5  366.76  5324.8  367.79  5416.8  369.43  5585.7  372.88  5610.6  373.68
  5663.4  375.25  5689.8  375.63  5714.9  376.18    5761  378.12  5786.9  378.59
#Mann= 9 ,-1 , 0
  4443.7     .05       0  4916.9     .07       0  5006.6     .07       0
  5012.6     .07       0  5080.3     .05       0  5416.8      .1       0
  5585.7     .05       0  5610.6      .1       0  5689.8     .05       0
Bank Sta=5006.6,5012.6
XS Rating Curve= 0 ,0
Exp/Cntr=0.3,0.1

Type RM Length L Ch R = 1 ,1917    ,271,271,271
BEGIN DESCRIPTION:
Mapping XS d6961aa0
END DESCRIPTION:
XS GIS Cut Line= 4
      2099399.03     13433875.84      2099524.03     13433462.64
      2099298.34     13433101.53      2098791.36     13432712.62
#Sta/Elev= 30
  4452.7  372.69  4556.2  371.55  4561.5  371.76  4627.3  370.21  4665.5  370.15
  4731.4  368.94    4911  366.88  4937.5  366.11  4962.9  365.36  4994.9  363.75
  4996.4  363.72  4996.9  362.92  5001.9  362.92  5002.4  363.72  5020.7  363.76
  5026.5  364.22  5120.9   364.6  5164.6  365.33    5194  365.37  5223.6  364.89
  5294.4  365.48  5374.8  367.85  5410.1  368.29    5431  368.95  5474.5  369.25
  5530.7  370.58  5594.6  371.47  5659.4  372.48  5872.4  377.55  5949.2  378.97
#Mann= 7 ,-1 , 0
  4452.7     .05       0  4937.5     .07       0  4994.9     .05       0
  4996.4    .035       0  5002.4     .05       0  5594.6      .1       0
  5872.4     .05       0
Bank Sta=4996.4,5002.4
XS Rating Curve= 0 ,0
Exp/Cntr=0.3,0.1

Type RM Length L Ch R = 1 ,1646    ,222,222,222
BEGIN DESCRIPTION:
Mapping XS 3342acec
END DESCRIPTION:
XS GIS Cut Line= 4
      2099440.69     13433865.44      2099694.17     13433240.42
      2099381.67     13432882.78      2099030.96     13432285.54
#Sta/Elev= 30
  4195.8  373.31  4615.7  367.46  4704.2  366.93  4778.8  365.06  4923.1  362.65
  4951.5  361.51  4986.7  361.76  4994.3   361.1  5000.9  361.32  5008.5  360.16
  5015.1  360.45  5022.7  359.53  5040.6  358.79  5041.1  357.99  5046.1  357.99
  5046.6  358.79  5129.1  359.33  5135.7  360.57  5149.9  360.21  5156.6  361.62
  5164.2   361.5  5170.8  363.38  5380.7  367.58  5381.2  367.58  5743.1  373.22
    5786  375.14  5918.9  377.62  5961.9  378.93    5999  379.06  6037.8  380.41
#Mann= 6 ,-1 , 0
  4195.8     .05       0  4778.8     .07       0  5040.6     .07       0
  5046.6     .07       0  5380.7      .1       0  5381.2     .05       0
Bank Sta=5040.6,5046.6
XS Rating Curve= 0 ,0
Exp/Cntr=0.3,0.1

Type RM Length L Ch R = 1 ,1424    ,46,46,46
BEGIN DESCRIPTION:
Mapping XS f1501d21
END DESCRIPTION:
XS GIS Cut Line= 6
      2099444.17     13434021.67      2099774.03     13433275.14
      2099784.45     13433087.64       2099753.2     13432973.06
      2099482.36     13432632.78      2099208.08     13432167.54
#Sta/Elev= 30
  3915.6  376.53  4330.9  369.72    4569  367.15  4656.6  364.85  4677.5  365.56
  4699.3  365.32  4715.7  365.27  4796.1  363.62  4865.7  362.92  4935.6  363.84
  4940.7  362.91  4975.3   362.6  4977.5  361.68    4978  360.88    4983  360.88
  4983.5  361.68    5015  362.64  5020.2  362.02  5046.6  363.34  5103.7  362.18
  5154.8  363.45  5289.6  364.03  5389.9  365.08  5453.4  366.73  5599.2  367.99
  5642.1  369.26  5679.2  369.47  5794.2  372.85  5986.3   377.1  6018.2  378.53
#Mann= 8 ,-1 , 0
  3915.6     .05       0  4699.3     .07       0  4715.7     .05       0
  4796.1     .07       0  4977.5     .07       0  4983.5     .07       0
  5289.6      .1       0  5794.2     .05       0
Bank Sta=4977.5,4983.5
XS Rating Curve= 0 ,0
Exp/Cntr=0.3,0.1

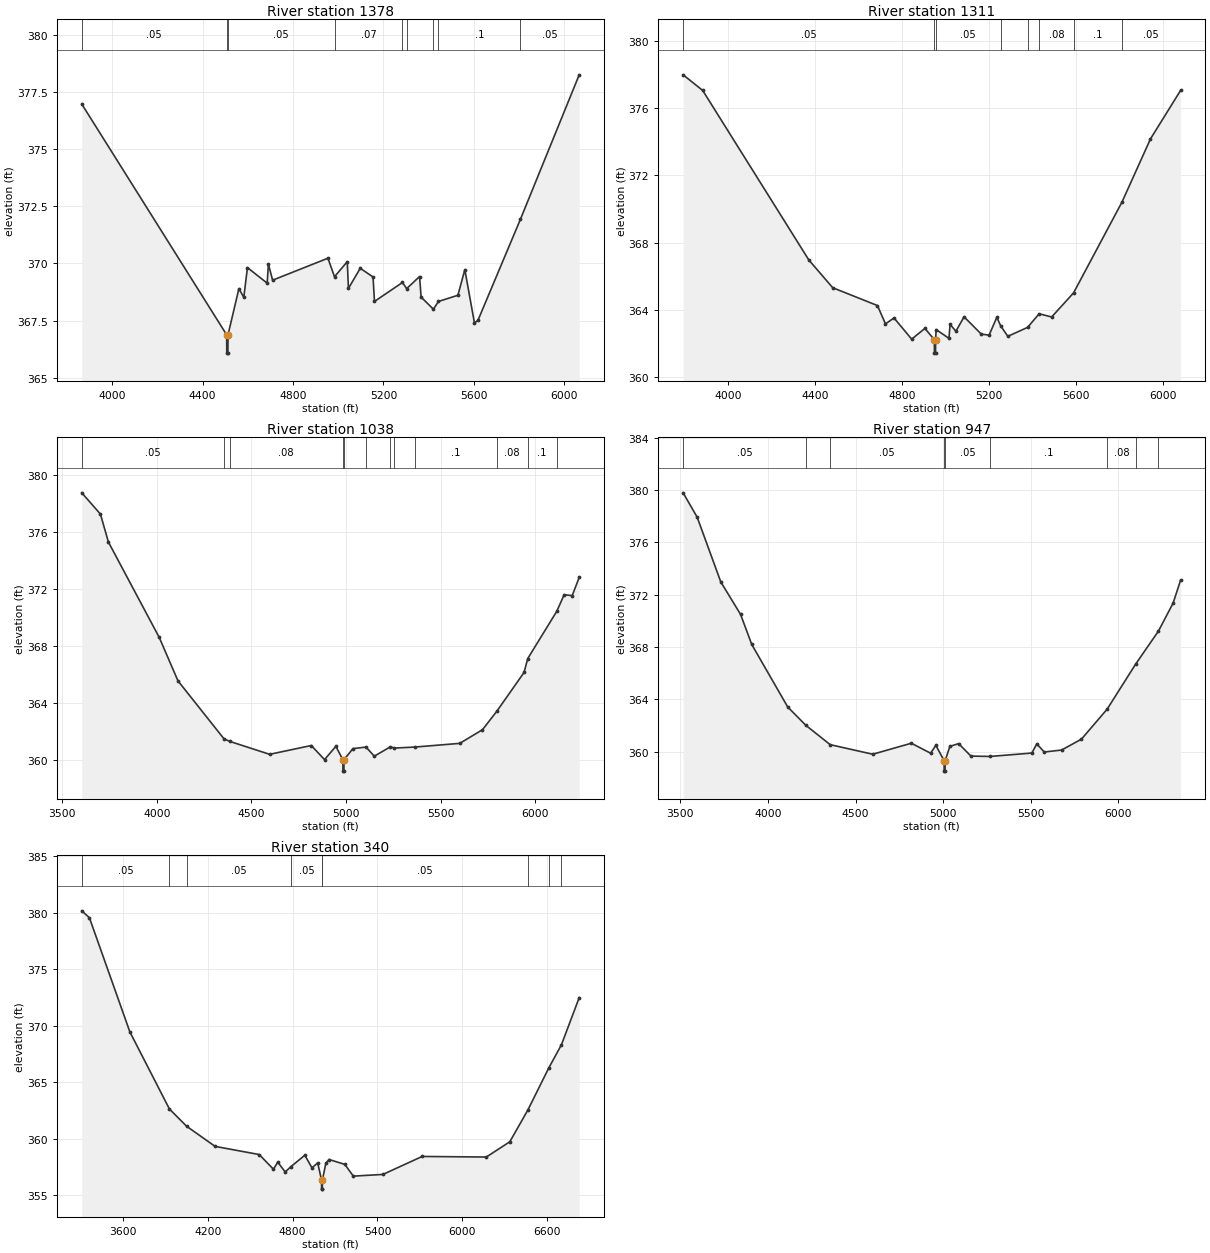
Type RM Length L Ch R = 1 ,1378    ,67,67,67
BEGIN DESCRIPTION:
Mapping XS 15ea2a9c
END DESCRIPTION:
XS GIS Cut Line= 6
       2099454.6     13434052.88      2099798.34     13433313.34
      2099836.53     13433125.84      2099787.92     13432910.56
      2099513.61     13432587.64       2099225.4      13432125.8
#Sta/Elev= 30
  3865.7  376.97  4506.5  366.88    4507  366.08    4512  366.08  4512.5  366.88
  4560.6   368.9  4582.3  368.52  4598.4  369.82  4685.7  369.14  4691.1  369.97
  4709.7  369.27  4954.4  370.23  4983.5  369.42    5040  370.08  5045.1  368.91
  5097.4  369.79  5153.9  369.41  5160.3  368.34  5284.1  369.17  5302.6   368.9
  5359.7  369.43  5366.5  368.53    5421     368  5443.4  368.34  5529.3  368.61
  5559.9  369.73  5602.5   367.4  5617.8  367.51  5805.7  371.93  6065.8  378.25
#Mann= 9 ,-1 , 0
  3865.7     .05       0  4506.5     .07       0  4512.5     .05       0
  4983.5     .07       0  5284.1     .08       0  5302.6      .1       0
    5421     .08       0  5443.4      .1       0  5805.7     .05       0
Bank Sta=4506.5,4512.5
XS Rating Curve= 0 ,0
Exp/Cntr=0.3,0.1

Type RM Length L Ch R = 1 ,1311    ,273,273,273
BEGIN DESCRIPTION:
Mapping XS 24e3dafc
END DESCRIPTION:
XS GIS Cut Line= 6
      2099468.49      13434091.1      2099846.95     13433382.78
      2099909.45     13433160.56      2099829.59     13432851.53
      2099638.61      13432580.7      2099260.14     13432115.42
#Sta/Elev= 30
  3794.2  377.98  3884.2  377.05    4372  366.97  4481.8  365.32  4687.4  364.26
  4724.3  363.17  4763.7  363.52  4844.9  362.26  4905.5   362.9  4948.9  362.23
  4949.4  361.43  4954.4  361.43  4954.9  362.23  4957.2  362.83  5016.1  362.31
  5021.3  363.14  5048.1  362.73  5085.5  363.59  5164.9  362.56  5200.6   362.5
  5236.3  363.56    5254  363.05  5286.8  362.43  5377.4  362.96  5430.8  363.77
  5488.2  363.58  5588.8  365.01  5811.4  370.41  5942.5  374.17  6080.7  377.05
#Mann= 8 ,-1 , 0
  3794.2     .05       0  4948.9    .035       0  4954.9     .05       0
    5254     .08       0  5377.4      .1       0  5430.8     .08       0
  5588.8      .1       0  5811.4     .05       0
Bank Sta=4948.9,4954.9
XS Rating Curve= 0 ,0
Exp/Cntr=0.3,0.1

Type RM Length L Ch R = 1 ,1038    ,91,91,91
BEGIN DESCRIPTION:
Mapping XS d2657de7
END DESCRIPTION:
XS GIS Cut Line= 4
      2099499.76     13434118.86       2100128.7     13433485.38
       2100126.1     13432831.73      2099395.58     13432032.12
#Sta/Elev= 30
    3603  378.74  3701.4  377.25  3743.8  375.28  4012.5  368.58  4111.5  365.53
    4354  361.47  4384.9  361.28  4596.1  360.37  4816.1  360.99  4886.1     360
  4946.1  360.93  4983.1  359.99  4983.6  359.19  4988.6  359.19  4989.1  359.99
  5036.1  360.77  5105.3  360.88  5149.3  360.24  5234.6   360.9  5255.6  360.81
  5362.9  360.88  5600.9  361.14  5721.2   362.1  5797.1   363.4  5940.7  366.12
  5960.5   367.1  6113.5  370.41  6152.9  371.58  6195.4  371.52  6232.4   372.8
#Mann= 12 ,-1 , 0
    3603     .05       0    4354      .1       0  4384.9     .08       0
  4983.1     .07       0  4989.1     .08       0  5105.3     .05       0
  5234.6      .1       0  5255.6     .05       0  5362.9      .1       0
  5797.1     .08       0  5960.5      .1       0  6113.5     .05       0
Bank Sta=4983.1,4989.1
XS Rating Curve= 0 ,0
Exp/Cntr=0.3,0.1

Type RM Length L Ch R = 1 ,947     ,607,607,607
BEGIN DESCRIPTION:
Mapping XS 528d219d
END DESCRIPTION:
XS GIS Cut Line= 4
      2099517.09     13434160.56      2100204.59     13433511.25
      2100219.85     13432774.44      2099399.97      13431960.1
#Sta/Elev= 30
  3516.2  379.78  3596.3  377.92    3731  372.98  3843.9   370.5  3907.8   368.2
  4112.9  363.43  4216.2  362.03  4355.4  360.55  4598.1  359.82  4818.2  360.66
  4928.2   359.9  4958.2   360.5  5005.2  359.33  5005.7  358.53  5010.7  358.53
  5011.2  359.33  5038.2  360.42  5088.2  360.63  5158.3  359.68  5267.1  359.65
  5505.9  359.91  5534.2  360.61  5576.6  359.99  5675.6  360.14  5788.8  360.97
  5935.5  363.26  6098.1   366.7  6228.6  369.23    6312  371.36  6354.4   373.1
#Mann= 9 ,-1 , 0
  3516.2     .05       0  4216.2      .1       0  4355.4     .05       0
  5005.2    .035       0  5011.2     .05       0  5267.1      .1       0
  5935.5     .08       0  6098.1      .1       0  6228.6     .05       0
Bank Sta=5005.2,5011.2
XS Rating Curve= 0 ,0
Exp/Cntr=0.3,0.1

Type RM Length L Ch R = 1 ,340     ,0,0,0
BEGIN DESCRIPTION:
UNT 056 in La Jarita Watershed 1.0
END DESCRIPTION:
XS GIS Cut Line= 4
       2099510.1     13434203.64      2100473.68     13433539.55
      2100603.89     13432593.37      2099398.65     13431891.04
#Sta/Elev= 30
  3307.5  380.17  3361.4  379.56  3648.1  369.45  3927.7  362.64  4049.6  361.11
  4251.3  359.33  4563.1  358.61    4664  357.31  4694.3  357.94    4747  357.07
  4788.7  357.55    4886  358.55  4936.6  357.43    4977  357.87  5004.3  356.35
  5004.8  355.55  5009.8  355.55  5010.3  356.35    5035  357.85  5057.7  358.17
  5168.8  357.74  5229.3   356.7  5438.5  356.85  5716.4  358.44  6170.5  358.39
  6336.7  359.74  6465.3  362.57  6610.8  366.23  6702.3  368.33  6827.8  372.49
#Mann= 9 ,-1 , 0
  3307.5     .05       0  3927.7     .05       0  4049.6     .05       0
  4788.7     .05       0  5004.3     .03       0  5010.3     .05       0
  6465.3     .05       0  6610.8     .05       0  6702.3     .05       0
Bank Sta=5004.3,5010.3
XS Rating Curve= 0 ,0
Exp/Cntr=0.3,0.1
LCMann Table=0

Chan Stop Cuts=-1
Use User Specified Reach Order=0
Composite Channel Slope=5