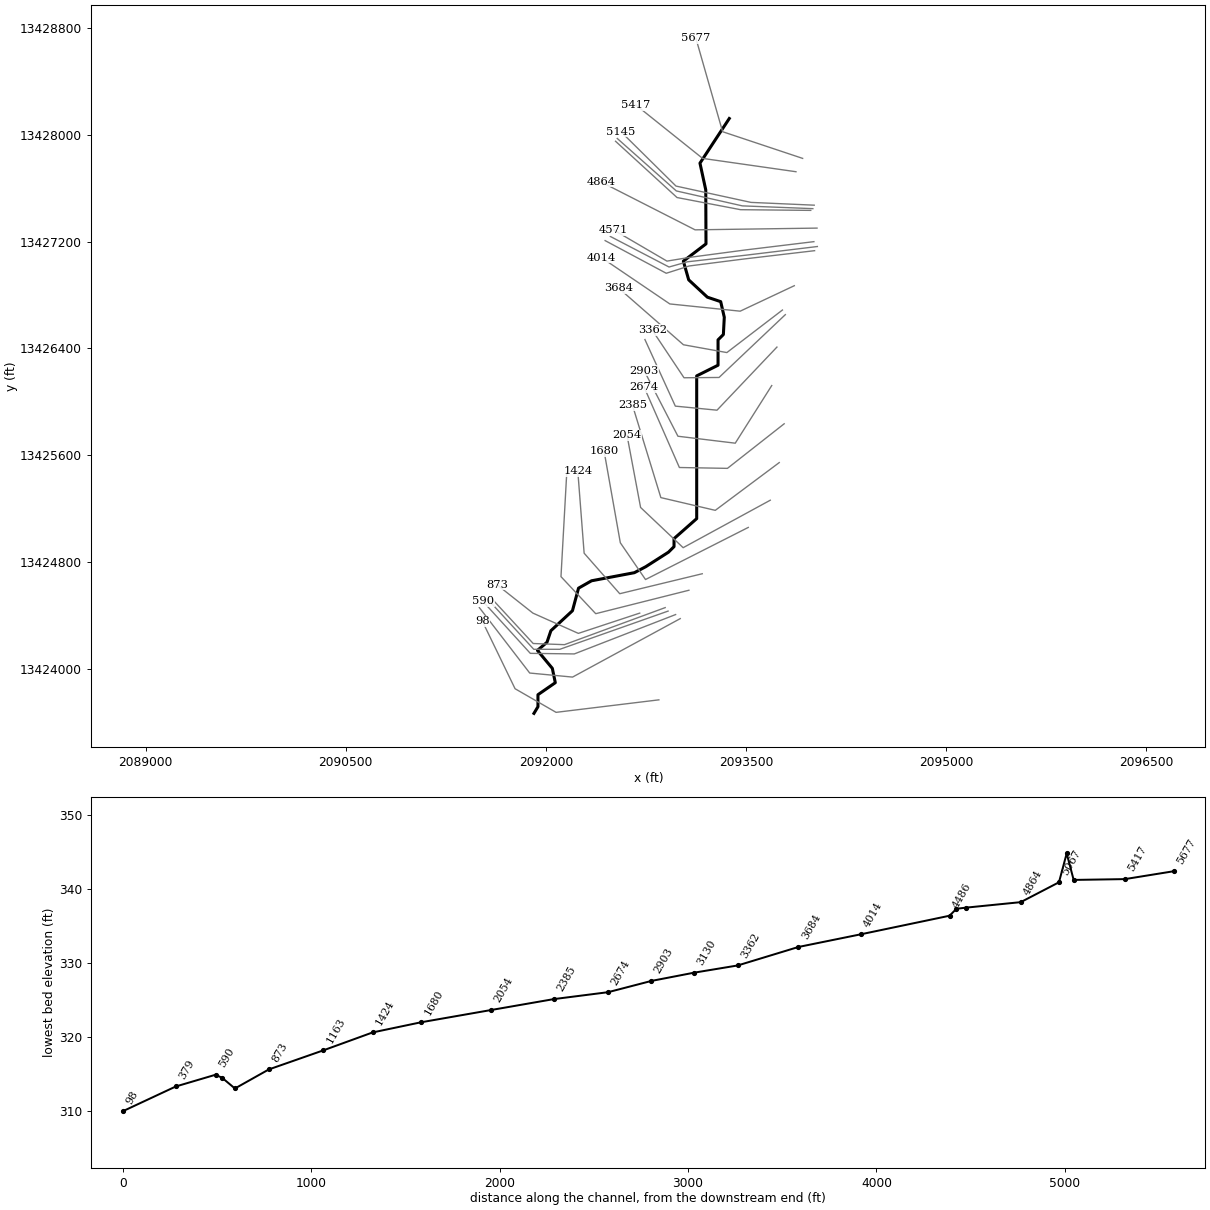
--- UNT 059 in La Jarita Watershed.prj (project) ---

Proj Title=UNT 059 in La Jarita Watershed Base Level Engineering
Current Plan=p01
Default Exp/Contr=0.3,0.1
English Units
Geom File=g01
Flow File=f01
Plan File=p01
BEGIN DESCRIPTION:
UNT 059 in La Jarita Watershed
END DESCRIPTION:

--- UNT 059 in La Jarita Watershed.p01 (plan) ---

Plan Title=Multiple Run
Short Identifier=Multiple
Geom File=g01
Flow File=f01
Subcritical Flow
K Sum by GR= 0
Std Step Tol= 0.01
Critical Tol= 0.01
Num of Std Step Trials= 20
Max Error Tol= 0.3
Flow Tol Ratio= 0.001
Split Flow NTrial= 30
Split Flow Tol= 0.02
Split Flow Ratio= 0.02
Log Output Level= 0
Friction Slope Method= 1
Unsteady Friction Slope Method= 2
Unsteady Bridges Friction Slope Method= 1
Parabolic Critical Depth
Global Vel Dist=  1 , 1 , 1
Global Log Level= 0
CheckData=True
Encroach Param= -1, 0, 0, 0
BEGIN DESCRIPTION:
Multiple Run
END DESCRIPTION:

--- UNT 059 in La Jarita Watershed.f01 (steady flow) ---

Flow Title=Multiple
Number of Profiles=7
Profile Names=10-year,25-year,50-year,1pct_min,100-year,1pct_plu,500-year
River Rch & RM= UNT 059 in La Ja,Reach-1,5677
     147     198     239     144     287     572     420
Boundary for River Rch & Prof#=UNT 059 in La Ja,Reach-1,1
Up Type=0
Dn Type=3
Dn Slope=0.005
Boundary for River Rch & Prof#=UNT 059 in La Ja,Reach-1,2
Up Type=0
Dn Type=3
Dn Slope=0.005
Boundary for River Rch & Prof#=UNT 059 in La Ja,Reach-1,3
Up Type=0
Dn Type=3
Dn Slope=0.005
Boundary for River Rch & Prof#=UNT 059 in La Ja,Reach-1,4
Up Type=0
Dn Type=3
Dn Slope=0.005
Boundary for River Rch & Prof#=UNT 059 in La Ja,Reach-1,5
Up Type=0
Dn Type=3
Dn Slope=0.005
Boundary for River Rch & Prof#=UNT 059 in La Ja,Reach-1,6
Up Type=0
Dn Type=3
Dn Slope=0.005
Boundary for River Rch & Prof#=UNT 059 in La Ja,Reach-1,7
Up Type=0
Dn Type=3
Dn Slope=0.005

--- UNT 059 in La Jarita Watershed.g01 (geometry) ---

Geom Title=Existing Conditions

River Reach=UNT 059 in La Ja,Reach-1
Reach XY= 30
      2093375.00     13428123.92      2093155.31     13427789.26
      2093198.72     13427588.73      2093200.45     13427184.22
      2093030.80     13427054.54      2093070.80     13426914.54
      2093210.80     13426784.54      2093310.70     13426751.06
      2093337.61     13426633.87      2093330.80     13426504.54
      2093290.80     13426464.54      2093290.80     13426274.54
      2093130.80     13426194.54      2093130.80     13425124.54
      2092960.80     13424974.54      2092960.80     13424914.54
      2092919.20     13424872.94      2092748.41     13424763.78
      2092663.78     13424719.29      2092342.60     13424658.53
      2092244.94     13424603.19      2092199.37     13424433.92
      2092037.69     13424284.18      2092008.40     13424197.37
      2091936.78     13424136.61      2092048.54     13424002.06
      2092070.80     13423894.54      2091940.80     13423804.54
      2091940.80     13423714.54      2091910.80     13423664.54

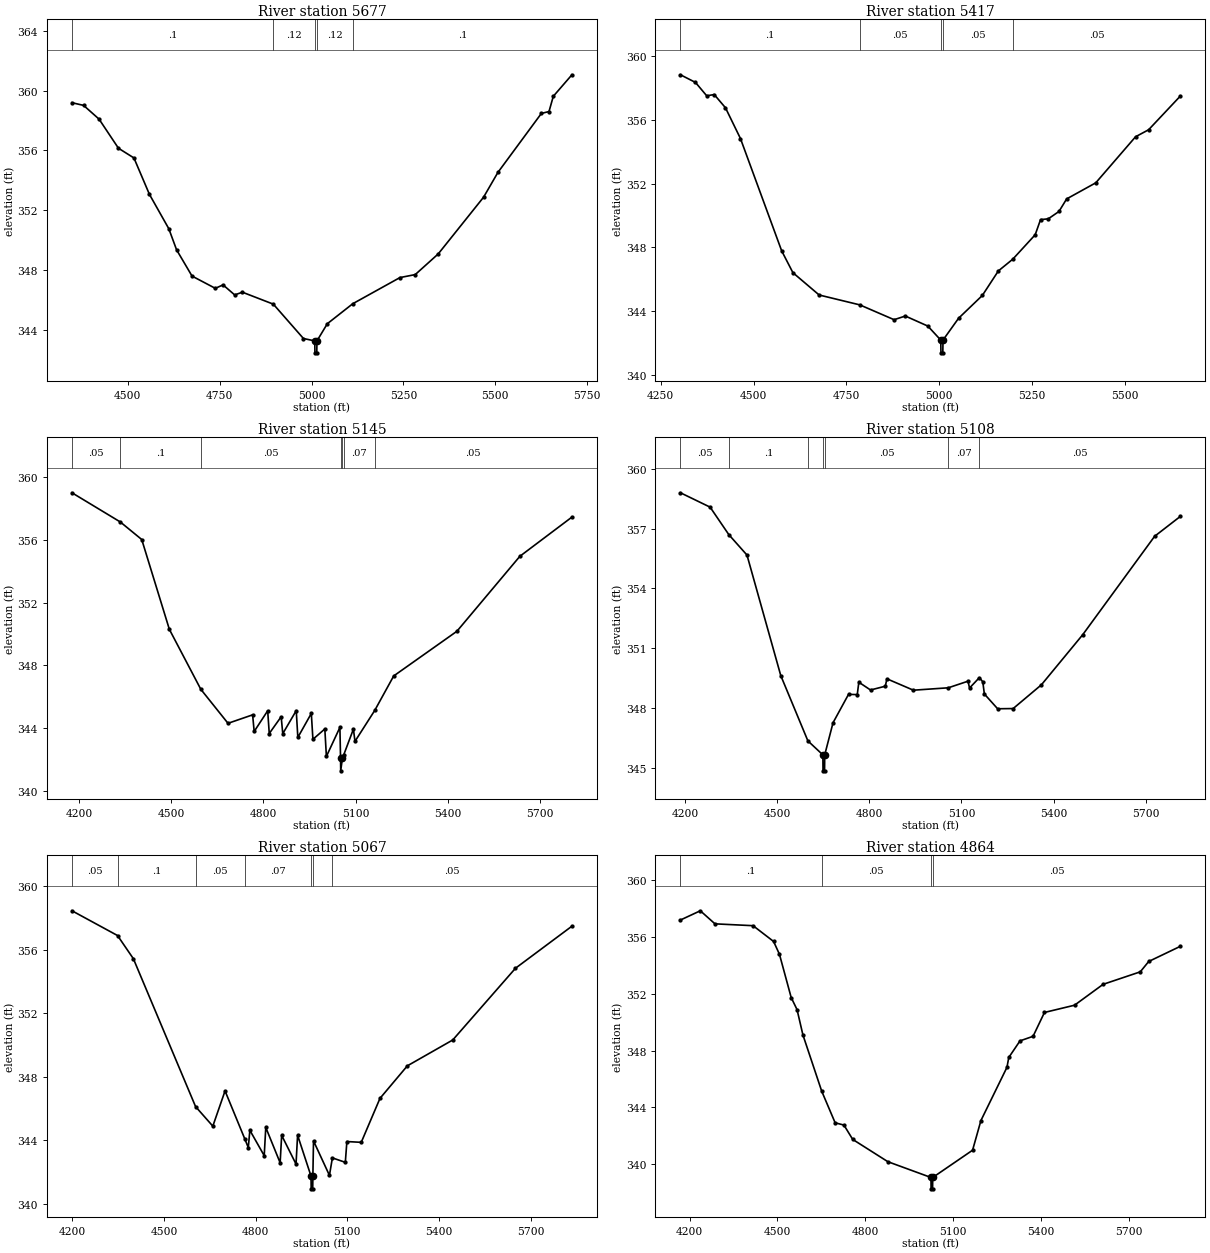
Type RM Length L Ch R = 1,5677,260,260,260
BEGIN DESCRIPTION:
UNT 059 in La Jarita Watershed 6.0
END DESCRIPTION:
XS GIS Cut Line= 3
      2093924.96     13427825.01      2093325.00     13428025.00
      2093125.01     13428724.97
#Sta/Elev= 30
  4348.1  359.20  4379.7  359.02  4421.8  358.10  4474.6  356.15  4516.7  355.50
  4558.9  353.06  4611.6  350.76  4632.7  349.35  4674.8  347.59  4738.1  346.77
  4759.2  347.00  4790.8  346.33  4811.9  346.51  4896.0  345.71  4977.9  343.41
  5008.7  343.25  5009.2  342.45  5014.2  342.45  5014.7  343.25  5042.9  344.40
  5112.2  345.74  5240.5  347.49  5282.1  347.69  5344.5  349.07  5468.0  352.87
  5507.0  354.53  5625.3  358.48  5646.1  358.61  5657.8  359.63  5708.5  361.07
#Mann=5,-1,0
  4348.1     0.1       0  4896.0    0.12       0  5008.7    0.07       0
  5014.7    0.12       0  5112.2     0.1       0
Bank Sta=5008.7,5014.7
Exp/Cntr=0.3,0.1

Type RM Length L Ch R = 1,5417,272,272,272
BEGIN DESCRIPTION:
UNT 059 in La Jarita Watershed 5.0
END DESCRIPTION:
XS GIS Cut Line= 3
      2093875.04     13427724.99      2093175.00     13427825.00
      2092674.97     13428225.02
#Sta/Elev= 30
  4303.0  358.83  4343.5  358.35  4373.8  357.51  4394.0  357.59  4424.3  356.76
  4464.7  354.83  4575.8  347.78  4606.1  346.41  4676.8  345.01  4786.4  344.39
  4878.8  343.46  4909.1  343.69  4969.7  343.06  5004.6  342.18  5005.1  341.38
  5010.1  341.38  5010.6  342.18  5052.6  343.55  5116.6  344.98  5159.8  346.52
  5198.8  347.26  5259.1  348.79  5273.5  349.74  5294.3  349.79  5323.1  350.25
  5343.9  351.04  5422.4  352.05  5529.6  354.94  5564.8  355.38  5650.5  357.50
#Mann=5,-1,0
  4303.0     0.1       0  4786.4    0.05       0  5004.6   0.033       0
  5010.6    0.05       0  5198.8    0.05       0
Bank Sta=5004.6,5010.6
Exp/Cntr=0.3,0.1

Type RM Length L Ch R = 1,5145,37,37,37
BEGIN DESCRIPTION:
Mapping XS 340fa66e
END DESCRIPTION:
XS GIS Cut Line= 4
      2094011.93     13427474.25      2093537.98     13427495.09
      2092975.48     13427617.48      2092564.01     13428023.74
#Sta/Elev= 30
  4176.6  359.00  4333.9  357.14  4403.8  356.02  4493.8  350.29  4596.2  346.47
  4684.8  344.30  4764.9  344.84  4770.0  343.78  4814.0  345.10  4819.1  343.65
  4857.9  344.72  4863.1  343.64  4907.0  345.11  4912.2  343.40  4956.1  344.93
  4961.3  343.28  5000.1  343.94  5005.2  342.19  5049.2  344.04  5051.3  342.07
  5051.8  341.27  5057.3  342.07  5061.3  342.27  5093.2  343.93  5098.3  343.15
  5162.6  345.12  5224.4  347.32  5430.3  350.17  5635.3  354.95  5804.9  357.45
#Mann=7,-1,0
  4176.6    0.05       0  4333.9     0.1       0  4596.2    0.05       0
  5051.3   0.033       0  5057.3    0.05       0  5061.3    0.07       0
  5162.6    0.05       0
Bank Sta=5051.3,5057.3
Exp/Cntr=0.3,0.1

Type RM Length L Ch R = 1,5108,41,41,41
BEGIN DESCRIPTION:
Mapping XS 60d8358c
END DESCRIPTION:
XS GIS Cut Line= 4
      2094001.57     13427448.21      2093472.87     13427469.05
      2092978.08     13427581.02      2092535.40     13427974.23
#Sta/Elev= 30
  4184.6  358.79  4281.2  358.07  4342.3  356.69  4401.3  355.67  4511.4  349.63
  4599.7  346.36  4648.5  345.66  4649.0  344.86  4654.0  344.86  4654.5  345.66
  4681.6  347.27  4732.0  348.69  4760.5  348.68  4765.6  349.30  4803.7  348.91
  4851.9  349.10  4857.1  349.47  4943.4  348.90  5056.8  349.02  5121.1  349.35
  5126.3  349.01  5158.3  349.53  5169.4  349.32  5174.5  348.71  5217.7  347.97
  5268.3  347.98  5360.3  349.17  5494.9  351.68  5729.1  356.61  5813.1  357.61
#Mann=7,-1,0
  4184.6    0.05       0  4342.3     0.1       0  4599.7    0.05       0
  4648.5   0.033       0  4654.5    0.05       0  5056.8    0.07       0
  5158.3    0.05       0
Bank Sta=4648.5,4654.5
Exp/Cntr=0.3,0.1

Type RM Length L Ch R = 1,5067,203,203,203
BEGIN DESCRIPTION:
Mapping XS ddc7b3c4
END DESCRIPTION:
XS GIS Cut Line= 4
      2093985.91     13427435.19      2093459.85     13427440.40
      2092983.29     13427531.55      2092522.38     13427953.40
#Sta/Elev= 30
  4199.2  358.47  4348.3  356.91  4400.1  355.45  4603.7  346.13  4660.1  344.90
  4700.1  347.12  4765.5  344.06  4776.2  343.55  4781.3  344.64  4828.3  343.04
  4833.4  344.82  4880.4  342.59  4885.4  344.32  4932.4  342.51  4937.5  344.33
  4981.5  341.75  4982.0  340.95  4987.0  340.95  4987.5  341.75  4989.6  343.97
  5041.7  341.80  5051.4  342.90  5093.7  342.62  5098.8  343.93  5145.8  343.88
  5207.1  346.65  5296.7  348.70  5445.3  350.33  5650.6  354.85  5835.3  357.50
#Mann=7,-1,0
  4199.2    0.05       0  4348.3     0.1       0  4603.7    0.05       0
  4765.5    0.07       0  4981.5    0.07       0  4987.5    0.07       0
  5051.4    0.05       0
Bank Sta=4981.5,4987.5
Exp/Cntr=0.3,0.1

Type RM Length L Ch R = 1,4864,293,293,293
BEGIN DESCRIPTION:
Mapping XS e8c72bb4
END DESCRIPTION:
XS GIS Cut Line= 3
      2094032.81     13427302.38      2093118.71     13427289.36
      2092412.94     13427648.75
#Sta/Elev= 30
  4168.9  357.19  4236.7  357.84  4286.7  356.92  4416.7  356.79  4486.7  355.68
  4506.7  354.78  4546.8  351.73  4566.8  350.88  4586.8  349.10  4650.9  345.14
  4696.8  342.91  4726.8  342.75  4756.8  341.74  4876.8  340.17  5023.8  339.06
  5024.3  338.26  5029.3  338.26  5029.8  339.06  5165.8  340.98  5194.3  343.07
  5283.2  346.82  5289.3  347.51  5327.7  348.68  5372.2  349.00  5411.1  350.68
  5513.7  351.19  5611.2  352.66  5738.1  353.54  5766.9  354.27  5875.1  355.34
#Mann=4,-1,0
  4168.9     0.1       0  4650.9    0.05       0  5023.8    0.03       0
  5029.8    0.05       0
Bank Sta=5023.8,5029.8
Exp/Cntr=0.3,0.1

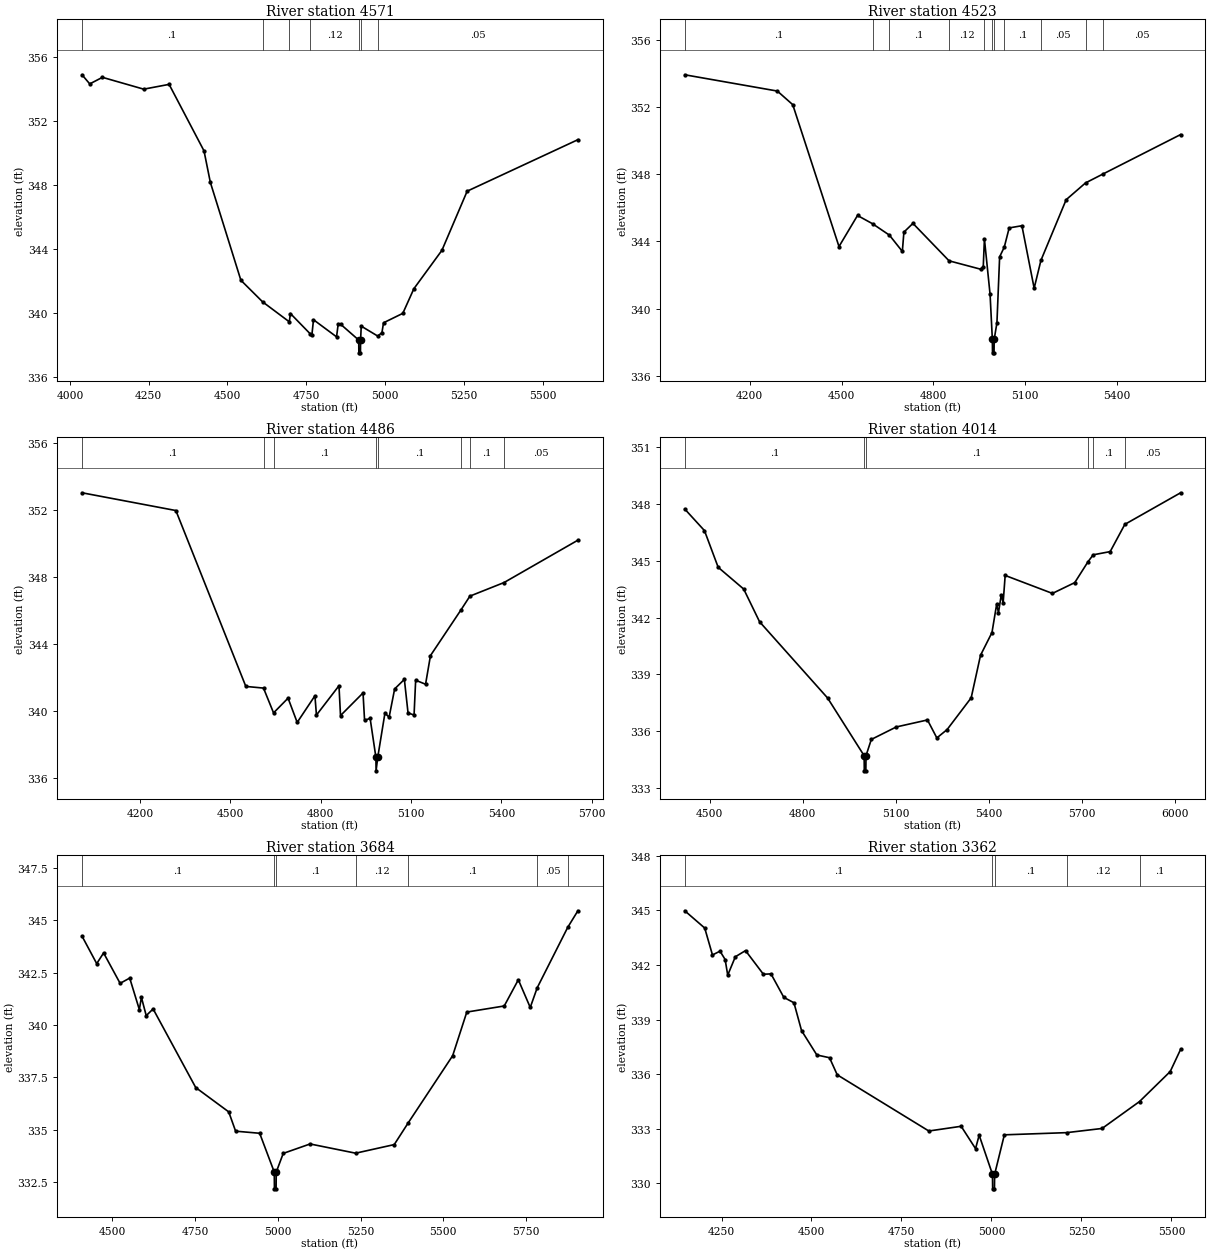
Type RM Length L Ch R = 1,4571,48,48,48
BEGIN DESCRIPTION:
Mapping XS dd7d9e6a
END DESCRIPTION:
XS GIS Cut Line= 5
      2094009.35     13427200.82      2093493.71     13427138.32
      2093082.25     13427083.63      2092907.77     13427054.98
      2092508.38     13427288.39
#Sta/Elev= 30
  4038.4  354.90  4062.9  354.33  4103.2  354.74  4234.2  354.00  4314.8  354.30
  4425.6  350.14  4445.7  348.17  4542.6  342.05  4611.5  340.70  4696.3  339.45
  4699.8  339.97  4763.1  338.69  4768.0  338.63  4773.1  339.58  4846.3  338.51
  4851.4  339.30  4859.1  339.30  4916.6  338.31  4917.1  337.51  4922.1  337.51
  4922.6  338.31  4924.6  339.18  4976.9  338.56  4990.3  338.77  4995.4  339.39
  5056.6  339.98  5091.7  341.52  5180.7  343.92  5260.8  347.62  5612.3  350.84
#Mann=7,-1,0
  4038.4     0.1       0  4611.5    0.12       0  4696.3     0.1       0
  4763.1    0.12       0  4916.6    0.03       0  4922.6    0.12       0
  4976.9    0.05       0
Bank Sta=4916.6,4922.6
Exp/Cntr=0.3,0.1

Type RM Length L Ch R = 1,4523,37,37,37
BEGIN DESCRIPTION:
Mapping XS 4e8cd61d
END DESCRIPTION:
XS GIS Cut Line= 5
      2094035.37     13427164.36      2093498.91     13427099.25
      2093061.41     13427049.77      2092923.39     13427010.71
      2092483.31     13427239.87
#Sta/Elev= 30
  3987.5  353.92  4290.1  352.95  4340.4  352.14  4491.5  343.69  4552.0  345.54
  4601.0  345.05  4656.2  344.37  4698.5  343.40  4703.6  344.55  4733.1  345.07
  4851.2  342.84  4954.5  342.34  4962.9  342.49  4966.7  344.14  4985.2  340.84
  4992.6  338.16  4993.1  337.36  4998.1  337.36  4998.6  338.16  5007.6  339.15
  5016.4  343.08  5031.5  343.65  5047.6  344.80  5089.2  344.93  5129.2  341.21
  5151.4  342.87  5233.8  346.48  5297.1  347.48  5353.0  348.00  5607.8  350.36
#Mann=11,-1,0
  3987.5     0.1       0  4601.0    0.12       0  4656.2     0.1       0
  4851.2    0.12       0  4966.7    0.05       0  4992.6    0.03       0
  4998.6    0.05       0  5031.5     0.1       0  5151.4    0.05       0
  5297.1     0.1       0  5353.0    0.05       0
Bank Sta=4992.6,4998.6
Exp/Cntr=0.3,0.1

Type RM Length L Ch R = 1,4486,472,472,472
BEGIN DESCRIPTION:
Mapping XS 1e89dd86
END DESCRIPTION:
XS GIS Cut Line= 5
      2094014.57     13427133.11      2093483.29     13427070.61
      2093074.44     13427018.52      2092902.56     13426963.84
      2092444.21     13427208.64
#Sta/Elev= 30
  4007.1  353.02  4318.8  351.96  4551.2  341.46  4609.9  341.36  4643.3  339.88
  4691.5  340.76  4721.8  339.31  4780.7  340.90  4785.8  339.75  4860.6  341.50
  4865.7  339.72  4940.5  341.07  4945.6  339.44  4964.1  339.55  4983.3  337.22
  4983.8  336.42  4989.3  337.22  5013.3  339.87  5027.1  339.62  5045.5  341.31
  5077.8  341.88  5090.0  339.88  5110.0  339.75  5115.3  341.83  5148.2  341.59
  5164.5  343.30  5266.3  346.04  5295.5  346.85  5408.8  347.66  5654.2  350.19
#Mann=8,-1,0
  4007.1     0.1       0  4609.9    0.12       0  4643.3     0.1       0
  4983.3    0.07       0  4989.3     0.1       0  5266.3    0.05       0
  5295.5     0.1       0  5408.8    0.05       0
Bank Sta=4983.3,4989.3
Exp/Cntr=0.3,0.1

Type RM Length L Ch R = 1,4014,330,330,330
BEGIN DESCRIPTION:
Mapping XS 24b0a5e8
END DESCRIPTION:
XS GIS Cut Line= 4
      2093862.48     13426870.58      2093456.69     13426679.62
      2092929.35     13426733.87      2092417.17     13427081.12
#Sta/Elev= 30
  4419.9  347.74  4483.4  346.60  4527.6  344.66  4609.8  343.51  4661.0  341.78
  4880.1  337.75  4997.8  334.70  4998.3  333.90  5003.3  333.90  5003.8  334.70
  5020.9  335.56  5101.3  336.22  5201.8  336.59  5232.0  335.64  5265.0  336.08
  5342.6  337.76  5372.7  340.01  5409.6  341.21  5424.6  342.70  5430.6  342.27
  5439.5  343.20  5445.6  342.79  5452.1  344.23  5604.3  343.28  5676.2  343.85
  5718.8  344.95  5735.6  345.32  5790.4  345.49  5837.6  346.93  6017.3  348.60
#Mann=6,-1,0
  4419.9     0.1       0  4997.8    0.07       0  5003.8     0.1       0
  5718.8    0.05       0  5735.6     0.1       0  5837.6    0.05       0
Bank Sta=4997.8,5003.8
Exp/Cntr=0.3,0.1

Type RM Length L Ch R = 1,3684,322,322,322
BEGIN DESCRIPTION:
Mapping XS 7f4c6466
END DESCRIPTION:
XS GIS Cut Line= 4
      2093773.54     13426688.31      2093356.86     13426369.29
      2093031.34     13426427.88      2092547.40     13426851.07
#Sta/Elev= 30
  4408.1  344.24  4452.5  342.93  4473.3  343.44  4523.2  341.99  4552.2  342.24
  4581.3  340.74  4587.6  341.32  4602.1  340.45  4622.9  340.77  4751.7  337.02
  4851.4  335.86  4872.2  334.94  4944.9  334.84  4989.0  332.99  4989.5  332.19
  4994.5  332.19  4995.0  332.99  5016.1  333.88  5097.3  334.33  5234.9  333.89
  5351.5  334.30  5393.5  335.33  5528.1  338.54  5570.8  340.62  5683.9  340.91
  5726.5  342.16  5762.5  340.84  5783.6  341.78  5875.8  344.66  5906.5  345.45
#Mann=7,-1,0
  4408.1     0.1       0  4989.0    0.07       0  4995.0     0.1       0
  5234.9    0.12       0  5393.5     0.1       0  5783.6    0.05       0
  5875.8     0.1       0
Bank Sta=4989,4995
Exp/Cntr=0.3,0.1

Type RM Length L Ch R = 1,3362,232,232,232
BEGIN DESCRIPTION:
Mapping XS 8e3cd897
END DESCRIPTION:
XS GIS Cut Line= 4
      2093795.22     13426653.56      2093298.27     13426182.66
      2093035.68     13426180.49      2092796.95     13426538.59
#Sta/Elev= 30
  4147.9  344.98  4203.4  344.03  4224.9  342.55  4245.9  342.76  4260.1  342.30
  4267.3  341.44  4288.4  342.45  4316.7  342.79  4366.4  341.49  4387.5  341.51
  4423.1  340.22  4451.3  339.92  4472.4  338.39  4514.9  337.05  4550.1  336.90
  4571.5  335.96  4826.0  332.87  4915.8  333.13  4955.8  331.90  4965.8  332.64
  5002.8  330.49  5003.3  329.69  5008.3  329.69  5008.8  330.49  5035.8  332.66
  5208.8  332.78  5307.3  333.01  5411.3  334.49  5496.6  336.14  5525.5  337.36
#Mann=5,-1,0
  4147.9     0.1       0  5002.8    0.07       0  5008.8     0.1       0
  5208.8    0.12       0  5411.3     0.1       0
Bank Sta=5002.8,5008.8
Exp/Cntr=0.3,0.1

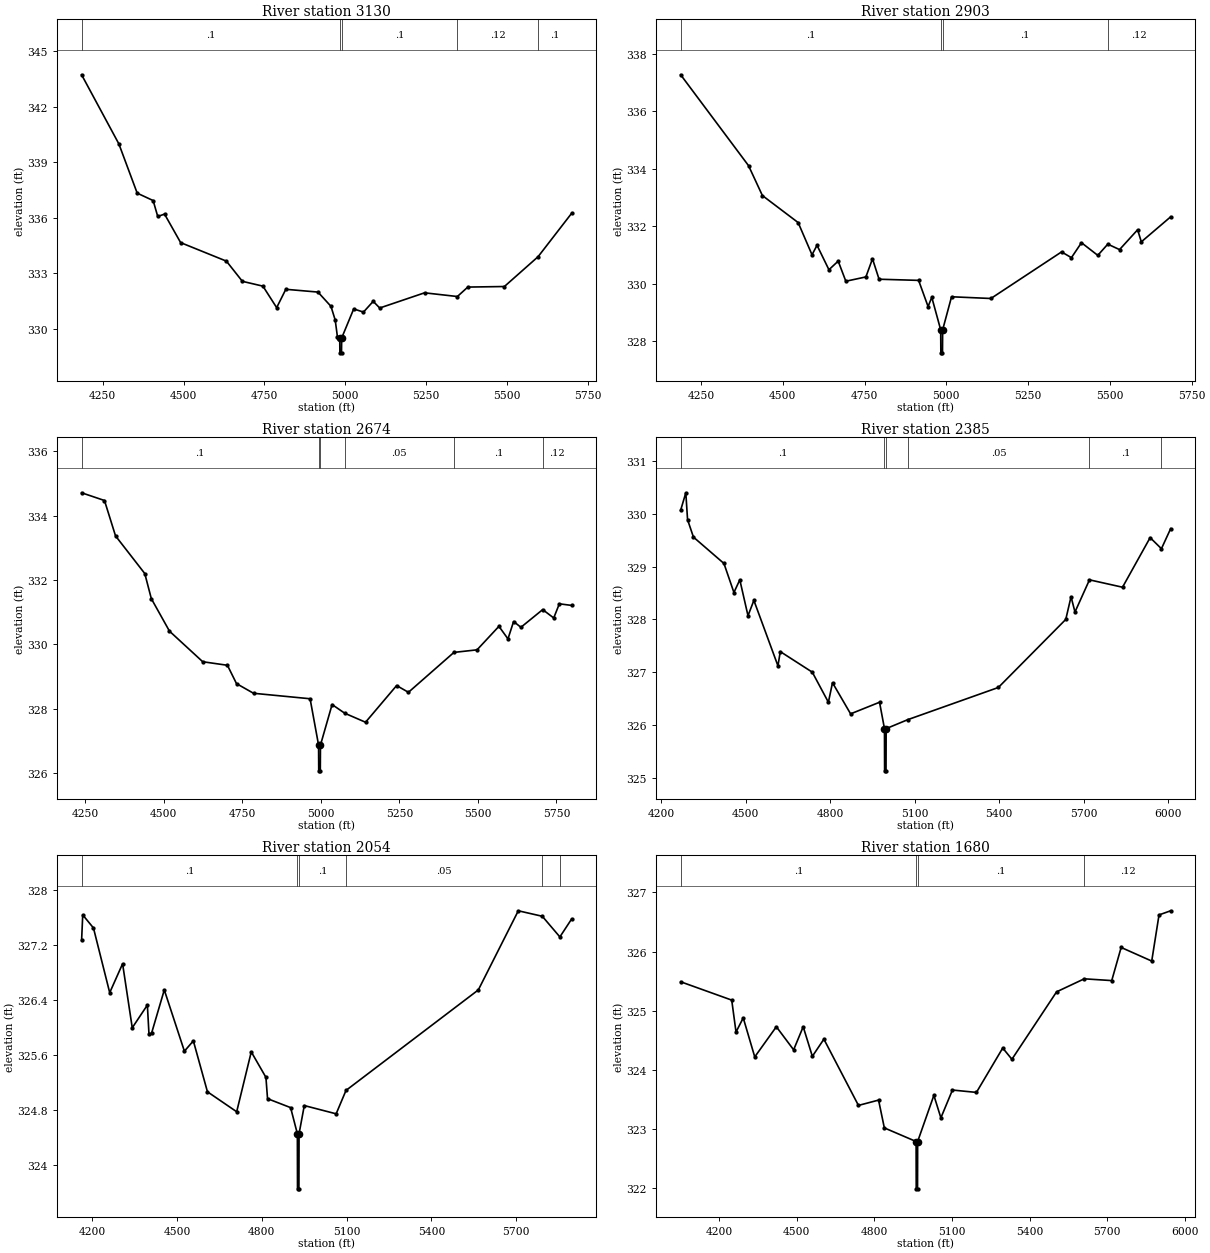
Type RM Length L Ch R = 1,3130,227,227,227
BEGIN DESCRIPTION:
Mapping XS bb45054d
END DESCRIPTION:
XS GIS Cut Line= 4
      2093732.27     13426410.50      2093283.08     13425937.43
      2092970.58     13425967.82      2092742.72     13426466.94
#Sta/Elev= 30
  4184.6  343.72  4299.8  339.99  4356.5  337.33  4405.8  336.93  4420.0  336.07
  4441.0  336.20  4490.8  334.66  4632.3  333.66  4681.7  332.57  4745.2  332.31
  4787.7  331.15  4816.0  332.14  4915.4  331.99  4955.6  331.22  4968.7  330.48
  4975.7  329.56  4982.7  329.51  4983.2  328.71  4988.2  328.71  4988.7  329.51
  5025.9  331.08  5056.1  330.91  5086.2  331.49  5106.3  331.13  5245.0  331.95
  5346.4  331.75  5378.7  332.26  5491.8  332.29  5596.0  333.90  5699.6  336.24
#Mann=5,-1,0
  4184.6     0.1       0  4982.7    0.07       0  4988.7     0.1       0
  5346.4    0.12       0  5596.0     0.1       0
Bank Sta=4982.7,4988.7
Exp/Cntr=0.3,0.1

Type RM Length L Ch R = 1,2903,229,229,229
BEGIN DESCRIPTION:
Mapping XS 97aacfea
END DESCRIPTION:
XS GIS Cut Line= 4
      2093693.22     13426121.87      2093419.80     13425690.04
      2092990.11     13425742.12      2092736.23     13426234.70
#Sta/Elev= 30
  4187.7  337.26  4395.2  334.10  4437.6  333.06  4546.9  332.12  4589.3  331.00
  4604.6  331.33  4641.0  330.48  4669.3  330.78  4692.7  330.08  4754.0  330.23
  4774.2  330.86  4794.3  330.15  4915.2  330.11  4944.1  329.20  4955.5  329.52
  4982.7  328.39  4983.2  327.59  4988.2  327.59  4988.7  328.39  5015.9  329.54
  5136.2  329.48  5352.2  331.10  5382.4  330.90  5413.1  331.42  5463.0  330.98
  5493.6  331.37  5529.5  331.18  5584.8  331.87  5596.1  331.45  5685.8  332.32
#Mann=4,-1,0
  4187.7     0.1       0  4982.7    0.07       0  4988.7     0.1       0
  5493.6    0.12       0
Bank Sta=4982.7,4988.7
Exp/Cntr=0.3,0.1

Type RM Length L Ch R = 1,2674,289,289,289
BEGIN DESCRIPTION:
Mapping XS 66ed1e24
END DESCRIPTION:
XS GIS Cut Line= 4
      2093786.57     13425835.45      2093361.21     13425501.24
      2093000.96     13425507.75      2092736.44     13426110.50
#Sta/Elev= 30
  4238.6  334.71  4311.4  334.47  4346.6  333.37  4439.7  332.20  4460.5  331.42
  4518.3  330.41  4624.1  329.46  4702.7  329.35  4731.6  328.78  4785.8  328.48
  4965.8  328.31  4992.8  326.87  4993.3  326.07  4998.3  326.07  4998.8  326.87
  5035.8  328.13  5076.1  327.86  5142.3  327.58  5241.2  328.72  5278.8  328.51
  5423.6  329.75  5497.2  329.83  5566.8  330.56  5595.6  330.17  5613.5  330.71
  5636.8  330.53  5706.1  331.08  5741.2  330.82  5759.1  331.26  5798.1  331.21
#Mann=6,-1,0
  4238.6     0.1       0  4992.8    0.07       0  4998.8     0.1       0
  5076.1    0.05       0  5423.6     0.1       0  5706.1    0.12       0
Bank Sta=4992.8,4998.8
Exp/Cntr=0.3,0.1

Type RM Length L Ch R = 1,2385,331,331,331
BEGIN DESCRIPTION:
Mapping XS 22df2a51
END DESCRIPTION:
XS GIS Cut Line= 4
      2093749.68     13425544.65      2093270.06     13425186.57
      2092862.07     13425282.05      2092649.71     13425973.31
#Sta/Elev= 30
  4268.7  330.07  4287.0  330.40  4293.2  329.89  4314.1  329.56  4422.5  329.06
  4457.9  328.51  4478.8  328.75  4507.9  328.07  4528.8  328.36  4614.3  327.12
  4622.6  327.39  4736.3  327.00  4793.5  326.43  4808.1  326.80  4872.4  326.21
  4975.2  326.43  4992.7  325.93  4993.2  325.13  4998.2  325.13  4998.7  325.93
  5075.5  326.10  5397.3  326.71  5636.8  328.00  5655.5  328.43  5669.5  328.14
  5721.0  328.75  5838.4  328.61  5936.5  329.55  5976.6  329.34  6009.4  329.72
#Mann=6,-1,0
  4268.7     0.1       0  4992.7    0.07       0  4998.7     0.1       0
  5075.5    0.05       0  5721.0     0.1       0  5976.6    0.12       0
Bank Sta=4992.7,4998.7
Exp/Cntr=0.3,0.1

Type RM Length L Ch R = 1,2054,374,374,374
BEGIN DESCRIPTION:
Mapping XS 3fd724bc
END DESCRIPTION:
XS GIS Cut Line= 4
      2093682.40     13425262.53      2093029.17     13424906.62
      2092710.16     13425208.27      2092608.24     13425750.43
#Sta/Elev= 30
  4162.0  327.27  4166.0  327.64  4204.0  327.45  4261.5  326.51  4307.1  326.93
  4341.3  326.00  4394.8  326.33  4400.5  325.91  4409.6  325.92  4454.7  326.55
  4525.9  325.66  4557.6  325.81  4607.5  325.07  4711.0  324.78  4762.6  325.65
  4814.5  325.28  4820.2  324.97  4901.9  324.84  4925.8  324.46  4926.3  323.66
  4931.3  323.66  4931.8  324.46  4950.3  324.87  5063.1  324.75  5098.0  325.09
  5566.4  326.55  5707.9  327.70  5792.9  327.62  5855.1  327.32  5896.6  327.58
#Mann=6,-1,0
  4162.0     0.1       0  4925.8    0.07       0  4931.8     0.1       0
  5098.0    0.05       0  5792.9     0.1       0  5855.1    0.12       0
Bank Sta=4925.8,4931.8
Exp/Cntr=0.3,0.1

Type RM Length L Ch R = 1,1680,256,256,256
BEGIN DESCRIPTION:
Mapping XS fe6a1383
END DESCRIPTION:
XS GIS Cut Line= 4
      2093517.47     13425058.53      2092747.06     13424667.90
      2092558.25     13424943.51      2092436.73     13425629.26
#Sta/Elev= 30
  4051.4  325.49  4248.8  325.18  4265.4  324.64  4293.3  324.88  4337.8  324.22
  4421.3  324.73  4488.1  324.34  4525.1  324.73  4560.5  324.23  4605.1  324.52
  4738.7  323.40  4816.5  323.49  4838.8  323.02  4961.6  322.79  4962.1  321.99
  4967.1  321.99  4967.6  322.79  5030.3  323.57  5057.4  323.19  5102.1  323.66
  5194.8  323.62  5296.5  324.37  5332.0  324.18  5504.7  325.32  5611.7  325.54
  5717.9  325.51  5754.3  326.07  5872.5  325.84  5900.7  326.62  5945.7  326.69
#Mann=4,-1,0
  4051.4     0.1       0  4961.6    0.07       0  4967.6     0.1       0
  5611.7    0.12       0
Bank Sta=4961.6,4967.6
Exp/Cntr=0.3,0.1

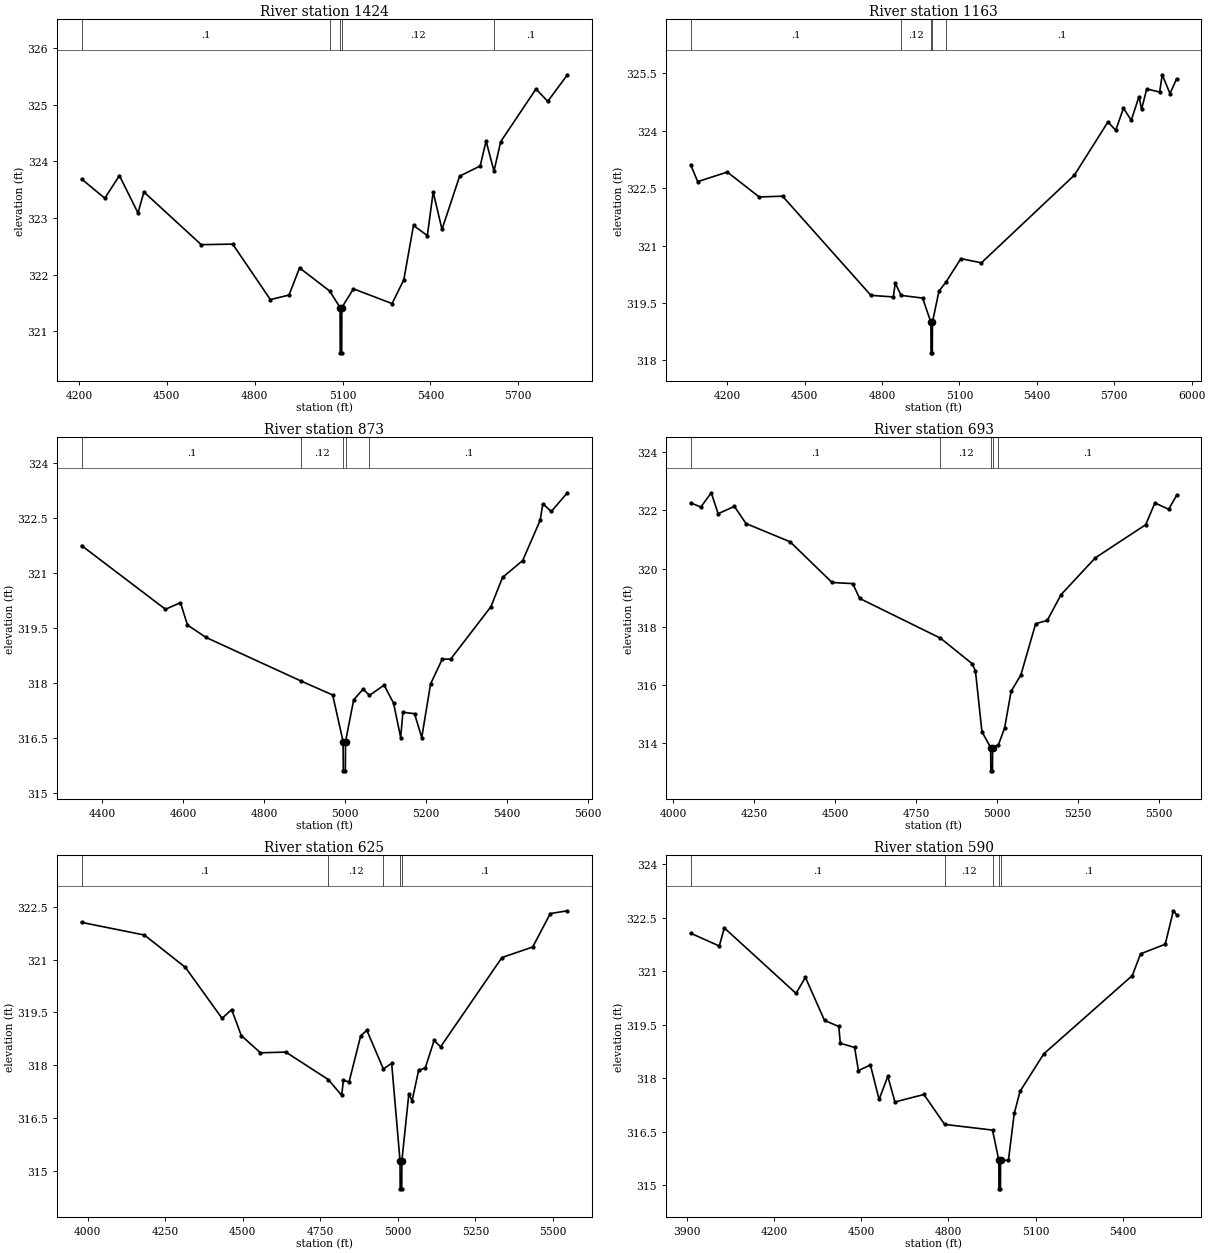
Type RM Length L Ch R = 1,1424,261,261,261
BEGIN DESCRIPTION:
Mapping XS 0730c601
END DESCRIPTION:
XS GIS Cut Line= 4
      2093172.36     13424711.30      2092553.91     13424561.57
      2092286.99     13424865.38      2092239.39     13425481.91
#Sta/Elev= 30
  4208.6  323.69  4288.2  323.35  4338.0  323.75  4401.4  323.09  4421.7  323.46
  4617.4  322.53  4724.8  322.54  4853.5  321.56  4917.1  321.64  4953.1  322.12
  5056.3  321.71  5091.5  321.42  5092.0  320.62  5097.0  320.62  5097.5  321.42
  5137.2  321.75  5269.0  321.49  5309.1  321.91  5342.2  322.87  5389.4  322.69
  5409.4  323.46  5439.5  322.80  5499.7  323.74  5569.9  323.92  5590.0  324.36
  5617.0  323.83  5640.1  324.35  5760.5  325.28  5800.6  325.06  5867.7  325.53
#Mann=5,-1,0
  4208.6     0.1       0  5056.3    0.12       0  5091.5    0.07       0
  5097.5    0.12       0  5617.0     0.1       0
Bank Sta=5091.5,5097.5
Exp/Cntr=0.3,0.1

Type RM Length L Ch R = 1,1163,290,290,290
BEGIN DESCRIPTION:
Mapping XS 49d18f9f
END DESCRIPTION:
XS GIS Cut Line= 4
      2093072.58     13424587.61      2092373.79     13424411.83
      2092113.38     13424689.60      2092156.75     13425470.38
#Sta/Elev= 30
  4058.2  323.11  4085.4  322.67  4200.1  322.92  4323.8  322.27  4414.4  322.29
  4756.9  319.70  4843.8  319.66  4851.1  320.02  4874.0  319.70  4957.1  319.63
  4989.3  319.00  4989.8  318.20  4994.8  318.20  4995.3  319.00  5020.6  319.81
  5048.9  320.06  5105.6  320.66  5185.0  320.55  5545.5  322.84  5675.7  324.23
  5705.8  324.01  5735.8  324.59  5765.8  324.27  5795.9  324.89  5805.9  324.56
  5825.9  325.09  5876.0  325.01  5886.0  325.46  5916.1  324.97  5941.5  325.35
#Mann=5,-1,0
  4058.2     0.1       0  4874.0    0.12       0  4989.3    0.07       0
  4995.3    0.12       0  5048.9     0.1       0
Bank Sta=4989.3,4995.3
Exp/Cntr=0.3,0.1

Type RM Length L Ch R = 1,873,180,180,180
BEGIN DESCRIPTION:
Mapping XS a9e8d8c8
END DESCRIPTION:
XS GIS Cut Line= 4
      2092703.61     13424416.15      2092243.58     13424264.26
      2091902.87     13424416.17      2091633.77     13424628.84
#Sta/Elev= 30
  4348.9  321.76  4556.3  320.02  4593.3  320.20  4610.7  319.59  4656.8  319.25
  4891.6  318.06  4969.5  317.68  4995.2  316.41  4995.7  315.61  5000.7  315.61
  5001.2  316.41  5021.4  317.55  5044.6  317.84  5060.4  317.67  5096.5  317.95
  5119.8  317.46  5137.5  316.52  5143.0  317.21  5171.7  317.17  5189.5  316.52
  5211.3  317.98  5240.2  318.66  5261.0  318.66  5360.4  320.09  5389.2  320.89
  5438.9  321.35  5482.2  322.45  5488.6  322.90  5509.6  322.69  5549.4  323.20
#Mann=5,-1,0
  4348.9     0.1       0  4891.6    0.12       0  4995.2    0.07       0
  5001.2    0.12       0  5060.4     0.1       0
Bank Sta=4995.2,5001.2
Exp/Cntr=0.3,0.1

Type RM Length L Ch R = 1,693,68,68,68
BEGIN DESCRIPTION:
Mapping XS 28ffafe6
END DESCRIPTION:
XS GIS Cut Line= 4
      2092894.59     13424457.38      2092139.42     13424179.62
      2091905.04     13424188.30      2091592.54     13424526.85
#Sta/Elev= 30
  4054.5  322.26  4086.0  322.12  4118.0  322.61  4139.3  321.89  4189.5  322.14
  4225.3  321.55  4361.6  320.92  4490.9  319.52  4554.8  319.48  4576.2  318.97
  4825.7  317.60  4923.6  316.72  4933.6  316.47  4953.6  314.38  4980.6  313.83
  4981.1  313.03  4986.1  313.03  4986.6  313.83  5004.7  313.93  5023.7  314.51
  5043.7  315.77  5073.7  316.33  5119.5  318.10  5155.2  318.21  5197.8  319.10
  5303.8  320.37  5459.2  321.51  5487.5  322.26  5530.1  322.04  5554.4  322.52
#Mann=5,-1,0
  4054.5     0.1       0  4825.7    0.12       0  4980.6    0.07       0
  4986.6    0.12       0  5004.7     0.1       0
Bank Sta=4980.6,4986.6
Exp/Cntr=0.3,0.1

Type RM Length L Ch R = 1,625,35,35,35
BEGIN DESCRIPTION:
Mapping XS 32872cb6
END DESCRIPTION:
XS GIS Cut Line= 4
      2092916.31     13424431.35      2092104.69     13424144.90
      2091909.38     13424144.90      2091563.29     13424521.27
#Sta/Elev= 30
  3979.7  322.06  4182.6  321.70  4314.7  320.78  4433.1  319.33  4464.0  319.58
  4495.0  318.84  4556.8  318.35  4638.6  318.37  4775.6  317.59  4818.8  317.14
  4824.6  317.57  4842.7  317.52  4880.1  318.83  4900.1  318.99  4953.4  317.89
  4980.1  318.05  5007.1  315.28  5007.6  314.48  5012.6  314.48  5013.1  315.28
  5035.4  317.17  5046.1  316.99  5067.1  317.85  5088.6  317.92  5117.0  318.70
  5138.0  318.52  5335.9  321.06  5435.1  321.36  5491.8  322.31  5547.0  322.39
#Mann=5,-1,0
  3979.7     0.1       0  4775.6    0.12       0  4953.4     0.1       0
  5007.1    0.07       0  5013.1     0.1       0
Bank Sta=5007.1,5013.1
Exp/Cntr=0.3,0.1

Type RM Length L Ch R = 1,590,211,211,211
BEGIN DESCRIPTION:
Mapping XS 704e7f15
END DESCRIPTION:
XS GIS Cut Line= 4
      2092972.79     13424405.33      2092213.20     13424110.18
      2091883.34     13424114.52      2091528.69     13424503.77
#Sta/Elev= 30
  3913.4  322.07  4011.9  321.71  4029.0  322.22  4275.8  320.38  4308.0  320.83
  4373.8  319.62  4422.9  319.45  4428.2  318.98  4477.3  318.86  4490.4  318.21
  4531.7  318.37  4561.6  317.40  4591.5  318.05  4616.1  317.33  4715.7  317.54
  4787.0  316.70  4951.7  316.54  4973.5  315.69  4974.0  314.89  4979.0  314.89
  4979.5  315.69  5006.5  315.69  5026.5  317.01  5046.5  317.63  5127.9  318.68
  5432.6  320.88  5461.0  321.49  5545.9  321.76  5573.8  322.70  5584.8  322.59
#Mann=5,-1,0
  3913.4     0.1       0  4787.0    0.12       0  4951.7     0.1       0
  4973.5    0.07       0  4979.5     0.1       0
Bank Sta=4973.5,4979.5
Exp/Cntr=0.3,0.1

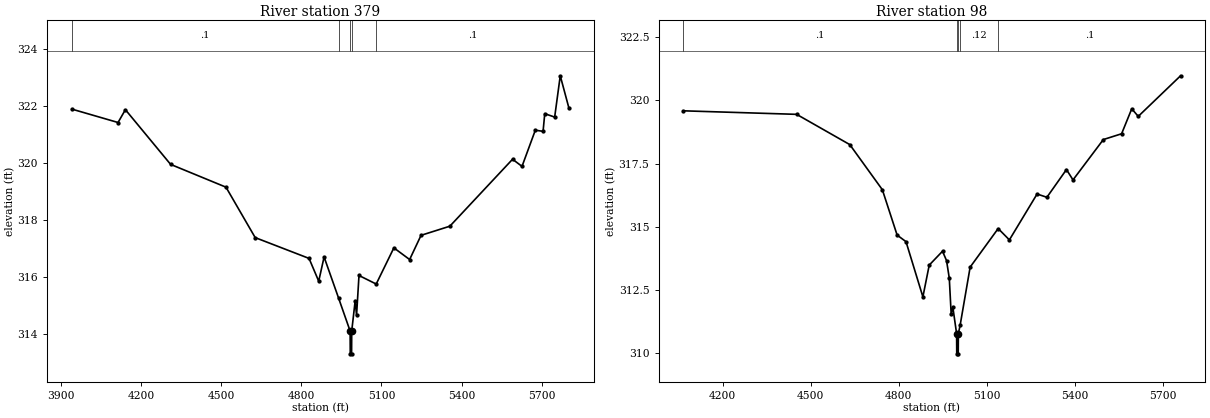
Type RM Length L Ch R = 1,379,281,281,281
BEGIN DESCRIPTION:
Mapping XS aa6031f3
END DESCRIPTION:
XS GIS Cut Line= 4
      2093007.44     13424374.92      2092200.18     13423936.57
      2091879.00     13423966.95      2091501.39     13424457.41
#Sta/Elev= 30
  3941.4  321.89  4114.3  321.42  4141.8  321.87  4311.0  319.95  4518.2  319.15
  4627.5  317.38  4829.0  316.65  4865.2  315.85  4885.3  316.70  4939.8  315.25
  4982.7  314.10  4983.2  313.30  4988.2  313.30  4988.7  314.10  5001.7  315.17
  5006.8  314.65  5015.9  316.05  5080.3  315.75  5146.4  317.02  5205.4  316.61
  5248.1  317.46  5355.9  317.78  5590.5  320.13  5625.9  319.88  5675.7  321.15
  5704.7  321.11  5711.0  321.73  5748.1  321.61  5769.0  323.06  5801.6  321.92
#Mann=5,-1,0
  3941.4     0.1       0  4939.8    0.12       0  4982.7    0.07       0
  4988.7    0.12       0  5080.3     0.1       0
Bank Sta=4982.7,4988.7
Exp/Cntr=0.3,0.1

Type RM Length L Ch R = 1,98,0,0,0
BEGIN DESCRIPTION:
UNT 059 in La Jarita Watershed 1.0
END DESCRIPTION:
XS GIS Cut Line= 4
      2092847.30     13423765.99      2092076.48     13423672.24
      2091769.19     13423849.33      2091524.38     13424354.58
#Sta/Elev= 30
  4066.9  319.59  4452.4  319.45  4633.3  318.25  4744.2  316.46  4794.5  314.66
  4824.7  314.40  4882.2  312.21  4903.8  313.47  4949.0  314.02  4962.7  313.65
  4972.1  312.95  4978.5  311.53  4984.2  311.80  4997.0  310.75  4997.5  309.95
  5002.5  309.95  5003.0  310.75  5009.1  311.09  5043.1  313.39  5138.5  314.92
  5176.7  314.47  5271.0  316.29  5304.4  316.16  5371.0  317.26  5393.3  316.85
  5496.6  318.45  5558.8  318.68  5593.3  319.67  5615.5  319.37  5759.5  320.98
#Mann=5,-1,0
  4066.9     0.1       0  4997.0    0.07       0  5003.0     0.1       0
  5009.1    0.12       0  5138.5     0.1       0
Bank Sta=4997,5003
Exp/Cntr=0.3,0.1

Chan Stop Cuts=-1