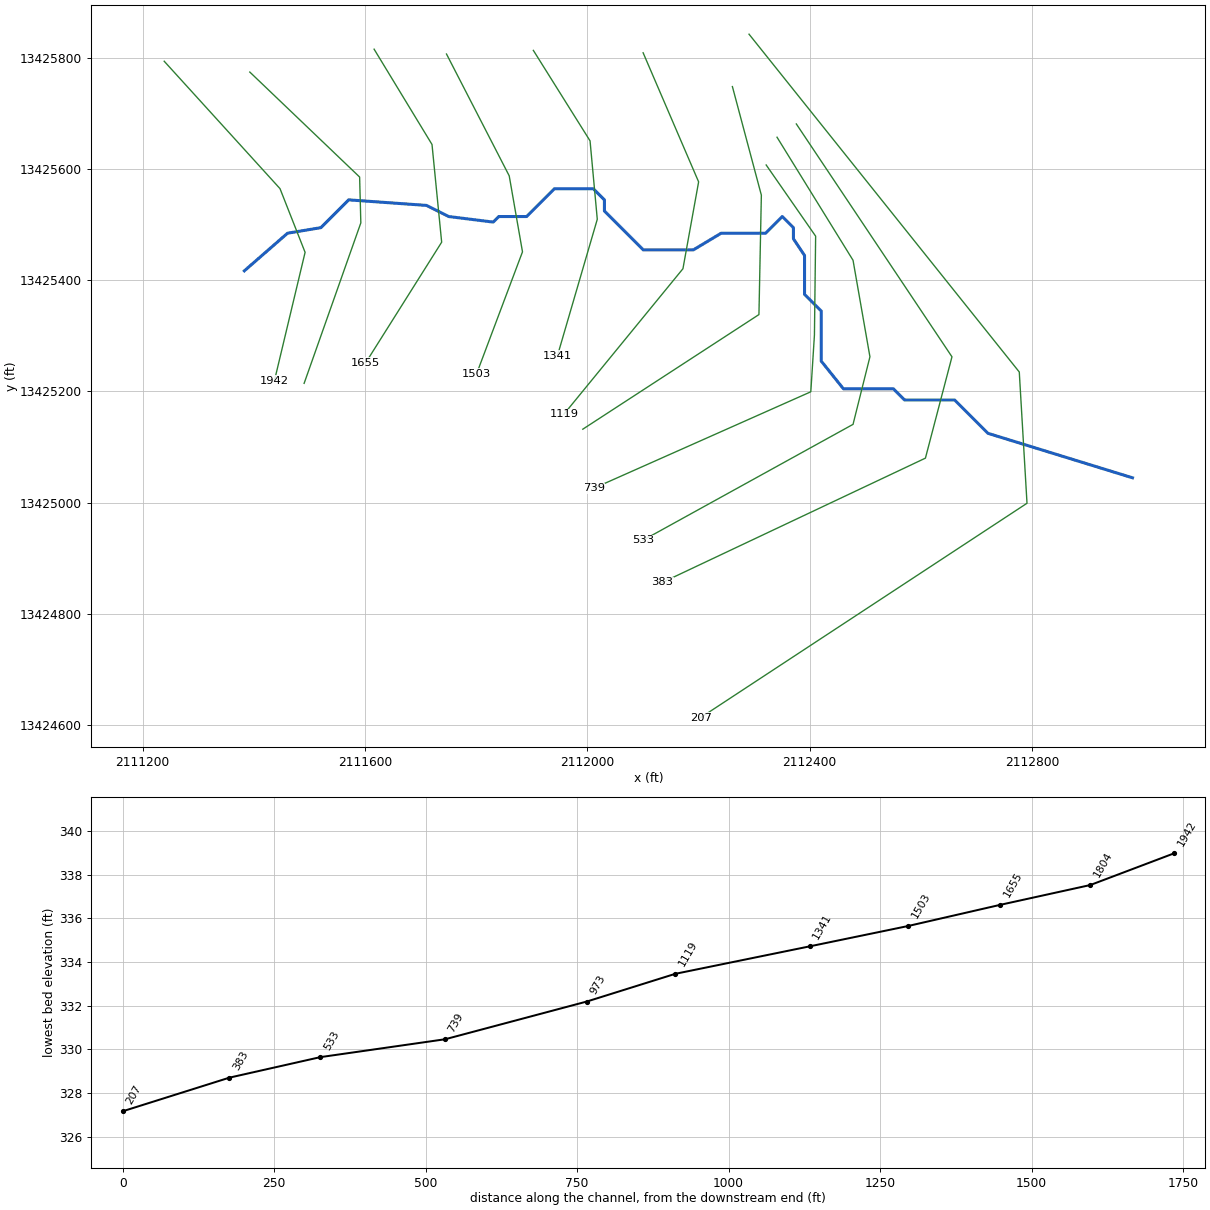
--- UNT 061 in La Jarita Watershed.prj (project) ---

Proj Title=UNT 061 in La Jarita Watershed Base Level Engineering
Current Plan=p01
Default Exp/Contr=0.3,0.1
English Units
Geom File=g01
Flow File=f01
Plan File=p01
BEGIN DESCRIPTION:
UNT 061 in La Jarita Watershed
END DESCRIPTION:

--- UNT 061 in La Jarita Watershed.p01 (plan) ---

Plan Title=Multiple Run
Short Identifier=Multiple
Geom File=g01
Flow File=f01
Subcritical Flow
K Sum by GR= 0
Std Step Tol= 0.01
Critical Tol= 0.01
Num of Std Step Trials= 20
Max Error Tol= 0.3
Flow Tol Ratio= 0.001
Split Flow NTrial= 30
Split Flow Tol= 0.02
Split Flow Ratio= 0.02
Log Output Level= 0
Friction Slope Method= 1
Unsteady Friction Slope Method= 2
Unsteady Bridges Friction Slope Method= 1
Parabolic Critical Depth
Global Vel Dist=  1 , 1 , 1
Global Log Level= 0
CheckData=True
Encroach Param= -1, 0, 0, 0
BEGIN DESCRIPTION:
Multiple Run
END DESCRIPTION:

--- UNT 061 in La Jarita Watershed.f01 (steady flow) ---

Flow Title=Multiple
Number of Profiles=7
Profile Names=10-year,25-year,50-year,1pct_min,100-year,1pct_plu,500-year
River Rch & RM= UNT 061 in La Ja,Reach-1,1942
      40      50      56      32      64     127      83
River Rch & RM= UNT 061 in La Ja,Reach-1,739
     108     141     167      98     196     392     277
Boundary for River Rch & Prof#=UNT 061 in La Ja,Reach-1,1
Up Type=0
Dn Type=3
Dn Slope=0.005
Boundary for River Rch & Prof#=UNT 061 in La Ja,Reach-1,2
Up Type=0
Dn Type=3
Dn Slope=0.005
Boundary for River Rch & Prof#=UNT 061 in La Ja,Reach-1,3
Up Type=0
Dn Type=3
Dn Slope=0.005
Boundary for River Rch & Prof#=UNT 061 in La Ja,Reach-1,4
Up Type=0
Dn Type=3
Dn Slope=0.005
Boundary for River Rch & Prof#=UNT 061 in La Ja,Reach-1,5
Up Type=0
Dn Type=3
Dn Slope=0.005
Boundary for River Rch & Prof#=UNT 061 in La Ja,Reach-1,6
Up Type=0
Dn Type=3
Dn Slope=0.005
Boundary for River Rch & Prof#=UNT 061 in La Ja,Reach-1,7
Up Type=0
Dn Type=3
Dn Slope=0.005

--- UNT 061 in La Jarita Watershed.g01 (geometry) ---

Geom Title=Existing Conditions

River Reach=UNT 061 in La Ja,Reach-1
Reach XY= 30
      2111383.13     13425416.87      2111460.80     13425484.54
      2111520.80     13425494.54      2111570.80     13425544.54
      2111710.80     13425534.54      2111750.80     13425514.54
      2111830.80     13425504.54      2111840.80     13425514.54
      2111890.80     13425514.54      2111940.80     13425564.54
      2112010.80     13425564.54      2112030.80     13425544.54
      2112030.80     13425524.54      2112100.80     13425454.54
      2112190.80     13425454.54      2112240.80     13425484.54
      2112320.80     13425484.54      2112350.80     13425514.54
      2112370.80     13425494.54      2112370.80     13425474.54
      2112390.80     13425444.54      2112390.80     13425374.54
      2112420.80     13425344.54      2112420.80     13425254.54
      2112460.80     13425204.54      2112550.80     13425204.54
      2112570.80     13425184.54      2112660.80     13425184.54
      2112720.80     13425124.54      2112980.80     13425044.54

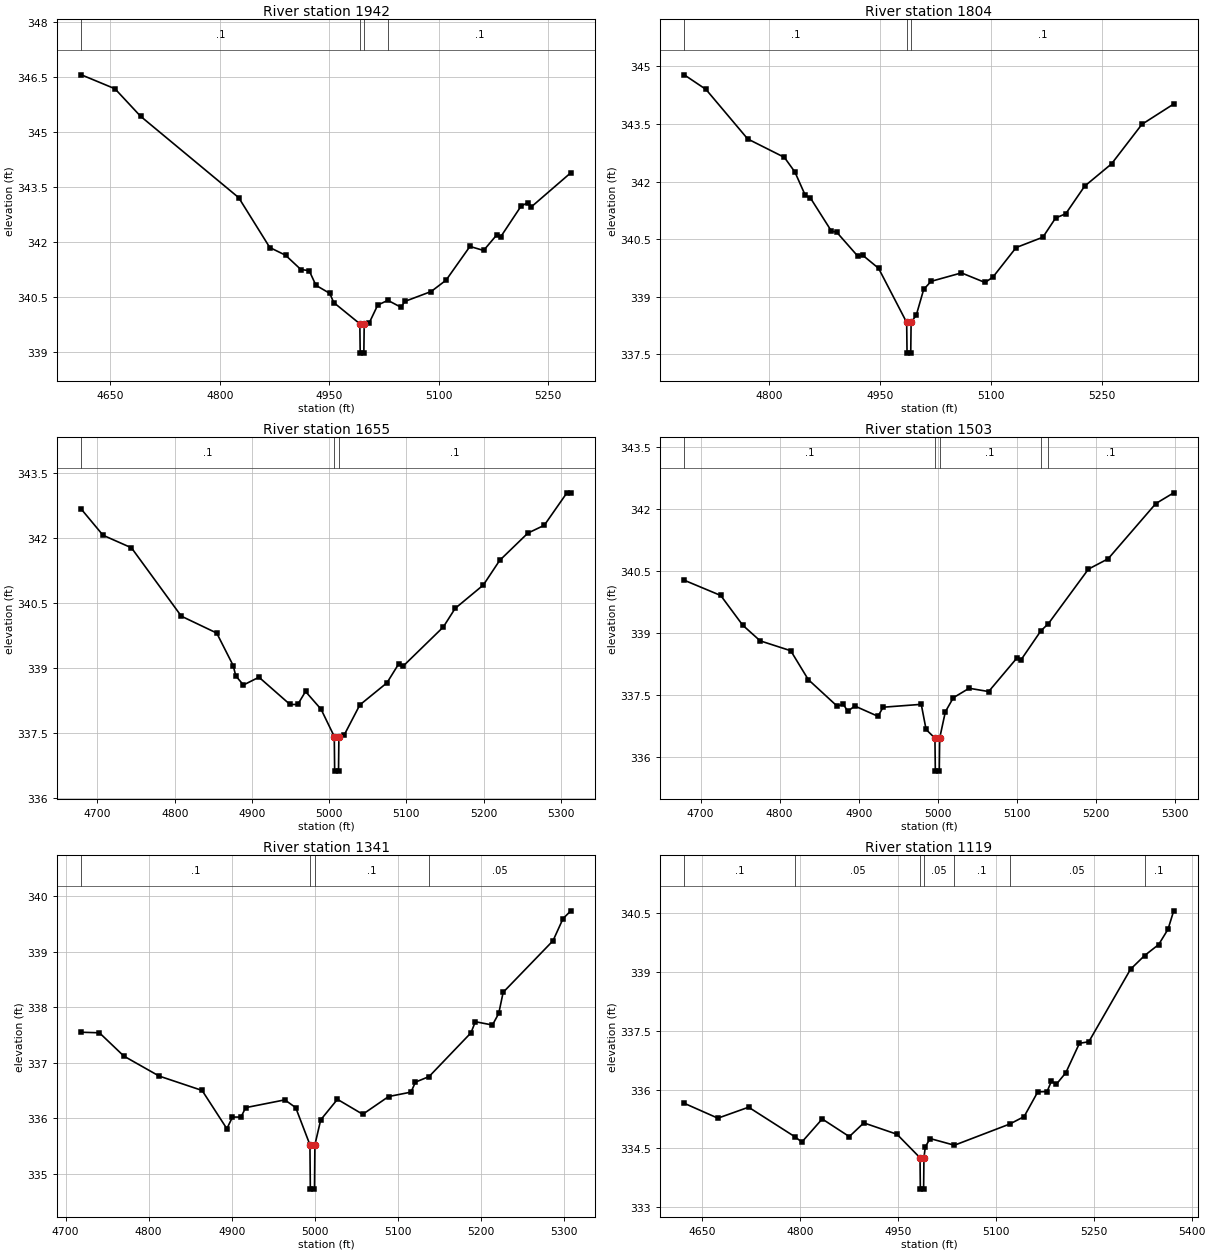
Type RM Length L Ch R = 1,1942,138,138,138
BEGIN DESCRIPTION:
UNT 061 in La Jarita Watershed 2.0
END DESCRIPTION:
XS GIS Cut Line= 4
      2111238.91     13425793.89      2111447.24     13425564.73
      2111492.38     13425450.15      2111437.11     13425218.71
#Sta/Elev= 30
  4610.3  346.57  4656.3  346.19  4691.4  345.44  4825.9  343.22  4868.5  341.86
  4890.1  341.65  4911.1  341.26  4922.5  341.23  4931.7  340.83  4950.7  340.61
  4956.1  340.36  4991.9  339.78  4992.4  338.98  4997.4  338.98  4997.9  339.78
  5004.9  339.81  5016.4  340.29  5030.3  340.42  5048.4  340.23  5053.5  340.39
  5089.6  340.66  5110.1  340.97  5142.8  341.89  5161.5  341.78  5179.8  342.21
  5184.9  342.15  5212.9  342.99  5221.8  343.08  5227.0  342.97  5281.1  343.90
#Mann=4,-1,0
  4610.3     0.1       0  4991.9    0.03       0  4997.9     0.1       0
  5030.3     0.1       0
Bank Sta=4991.9,4997.9
Exp/Cntr=0.3,0.1

Type RM Length L Ch R = 1,1804,149,149,149
BEGIN DESCRIPTION:
Mapping XS 7e5a49cc
END DESCRIPTION:
XS GIS Cut Line= 4
      2111392.96     13425774.40      2111590.47     13425585.57
      2111592.64     13425503.10      2111490.63     13425214.45
#Sta/Elev= 30
  4685.7  344.78  4715.1  344.40  4771.5  343.11  4821.1  342.63  4835.3  342.25
  4849.4  341.64  4856.4  341.57  4884.7  340.71  4891.9  340.68  4920.2  340.06
  4927.1  340.08  4948.5  339.74  4986.5  338.33  4987.0  337.53  4992.0  337.53
  4992.5  338.33  4999.5  338.52  5009.5  339.19  5019.5  339.40  5060.6  339.62
  5092.5  339.37  5103.1  339.51  5134.5  340.28  5170.7  340.55  5187.9  341.05
  5201.6  341.16  5227.2  341.88  5263.5  342.46  5304.6  343.49  5347.6  344.02
#Mann=3,-1,0
  4685.7     0.1       0  4986.5    0.07       0  4992.5     0.1       0
Bank Sta=4986.5,4992.5
Exp/Cntr=0.3,0.1

Type RM Length L Ch R = 1,1655,152,152,152
BEGIN DESCRIPTION:
Mapping XS a3ced60e
END DESCRIPTION:
XS GIS Cut Line= 4
      2111616.52     13425815.59      2111720.68     13425644.16
      2111738.04     13425468.38      2111601.33     13425251.38
#Sta/Elev= 30
  4679.2  342.67  4707.2  342.07  4744.0  341.78  4808.6  340.20  4854.4  339.81
  4875.7  339.06  4879.1  338.82  4889.0  338.61  4909.1  338.79  4949.3  338.16
  4959.3  338.16  4969.4  338.46  4989.5  338.05  5006.6  337.42  5007.1  336.62
  5012.1  336.62  5012.6  337.42  5019.6  337.46  5039.7  338.15  5074.8  338.66
  5090.1  339.10  5096.0  339.05  5147.8  339.95  5163.1  340.38  5199.6  340.92
  5220.8  341.49  5257.3  342.12  5278.5  342.30  5307.8  343.05  5312.9  343.05
#Mann=3,-1,0
  4679.2     0.1       0  5006.6    0.07       0  5012.6     0.1       0
Bank Sta=5006.6,5012.6
Exp/Cntr=0.3,0.1

Type RM Length L Ch R = 1,1503,162,162,162
BEGIN DESCRIPTION:
Mapping XS 1ee07853
END DESCRIPTION:
XS GIS Cut Line= 4
      2111746.74     13425806.89      2111859.57     13425587.74
      2111883.44     13425451.02      2111800.96     13425231.80
#Sta/Elev= 30
  4679.2  340.28  4725.4  339.91  4753.2  339.19  4775.3  338.81  4814.0  338.57
  4836.2  337.87  4872.5  337.23  4880.6  337.27  4886.2  337.10  4895.0  337.23
  4924.4  336.98  4930.9  337.20  4979.2  337.27  4985.3  336.66  4996.5  336.45
  4997.0  335.65  5002.0  335.65  5002.5  336.45  5009.7  337.09  5019.8  337.43
  5039.8  337.66  5064.5  337.58  5100.1  338.39  5105.5  338.35  5130.5  339.05
  5140.2  339.23  5190.8  340.55  5215.7  340.80  5276.1  342.14  5298.7  342.40
#Mann=5,-1,0
  4679.2     0.1       0  4996.5    0.07       0  5002.5     0.1       0
  5130.5    0.05       0  5140.2     0.1       0
Bank Sta=4996.5,5002.5
Exp/Cntr=0.3,0.1

Type RM Length L Ch R = 1,1341,222,222,222
BEGIN DESCRIPTION:
Mapping XS 5ba91b2a
END DESCRIPTION:
XS GIS Cut Line= 4
      2111902.98     13425813.41      2112004.97     13425650.67
      2112017.99     13425509.61      2111946.37     13425264.37
#Sta/Elev= 30
  4719.1  337.55  4740.8  337.54  4770.2  337.12  4812.6  336.76  4864.4  336.50
  4894.2  335.81  4901.0  336.02  4911.2  336.02  4916.9  336.19  4964.0  336.33
  4977.1  336.19  4994.2  335.52  4994.7  334.72  4999.7  334.72  5000.2  335.52
  5007.2  335.97  5027.3  336.34  5057.8  336.07  5088.9  336.39  5115.9  336.47
  5121.2  336.65  5137.6  336.75  5188.1  337.54  5193.3  337.74  5213.9  337.68
  5221.5  337.89  5226.8  338.27  5286.8  339.20  5298.9  339.60  5308.3  339.74
#Mann=4,-1,0
  4719.1     0.1       0  4994.2    0.07       0  5000.2     0.1       0
  5137.6    0.05       0
Bank Sta=4994.2,5000.2
Exp/Cntr=0.3,0.1

Type RM Length L Ch R = 1,1119,146,146,146
BEGIN DESCRIPTION:
Mapping XS f0e9962e
END DESCRIPTION:
XS GIS Cut Line= 4
      2112100.44     13425809.11      2112200.28     13425576.89
      2112172.07     13425420.64      2111958.00     13425159.00
#Sta/Elev= 30
  4622.9  335.65  4674.4  335.27  4721.5  335.55  4792.9  334.79  4803.0  334.66
  4834.2  335.25  4875.7  334.80  4897.9  335.15  4948.7  334.86  4984.0  334.26
  4984.5  333.46  4989.5  333.46  4990.0  334.26  4992.1  334.54  4999.5  334.75
  5036.7  334.58  5121.3  335.12  5143.4  335.31  5164.3  335.94  5178.6  335.95
  5185.1  336.21  5193.0  336.14  5207.3  336.43  5228.1  337.18  5242.5  337.22
  5306.4  339.07  5328.0  339.42  5349.5  339.70  5363.8  340.09  5372.5  340.56
#Mann=7,-1,0
  4622.9     0.1       0  4792.9    0.05       0  4984.0   0.035       0
  4990.0    0.05       0  5036.7     0.1       0  5121.3    0.05       0
  5328.0     0.1       0
Bank Sta=4984,4990
Exp/Cntr=0.3,0.1

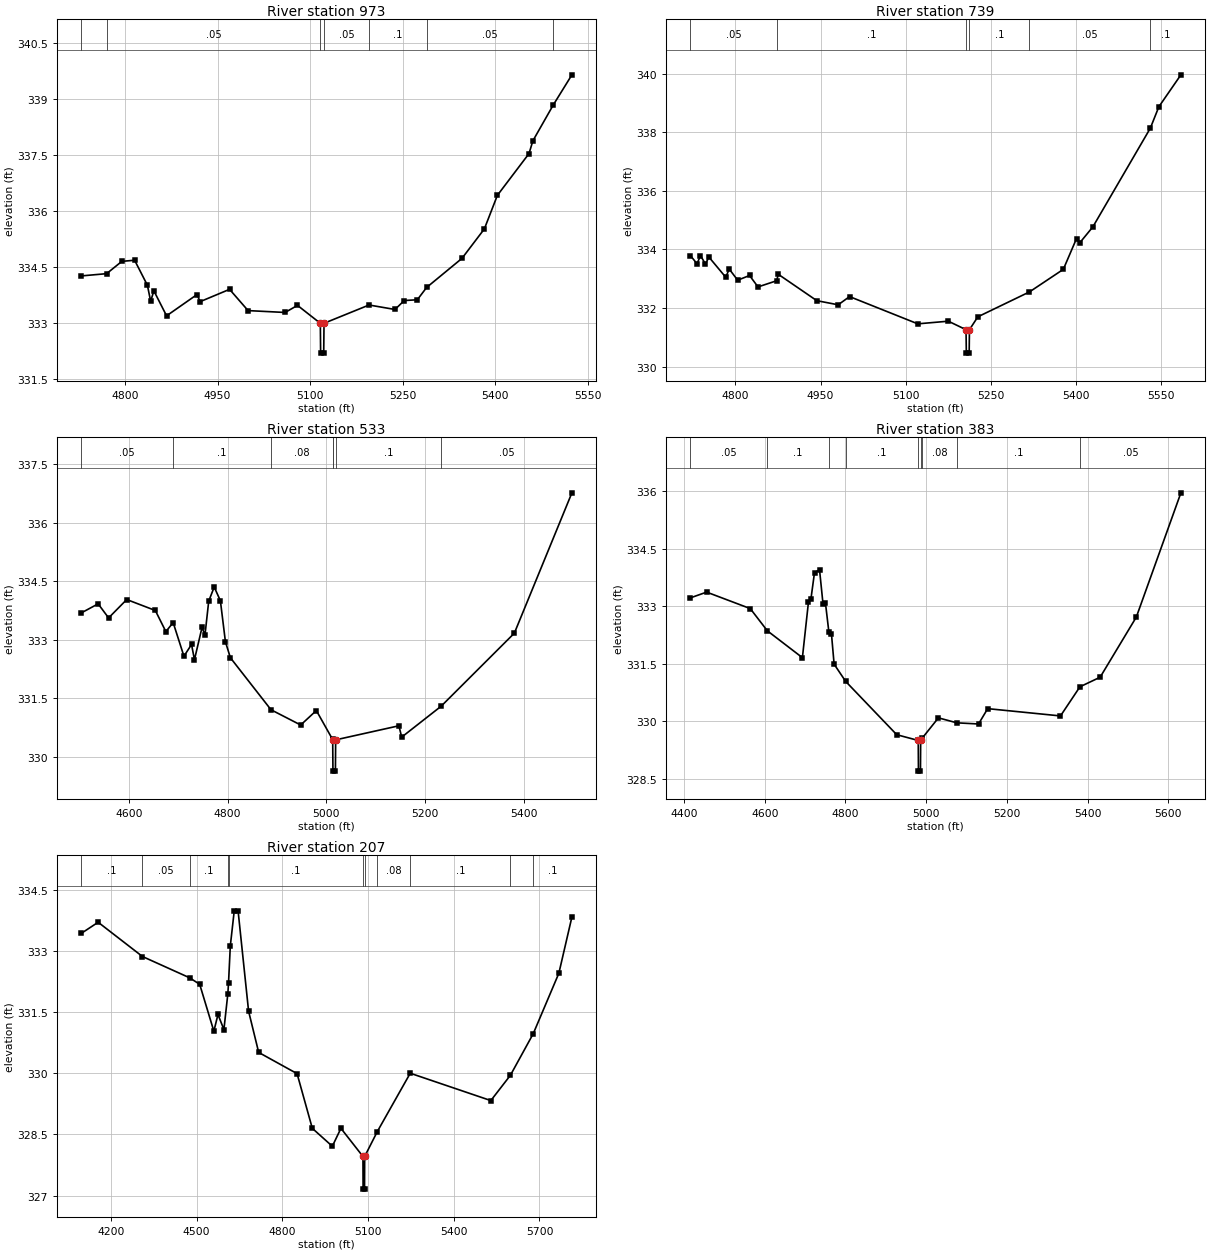
Type RM Length L Ch R = 1,973,234,234,234
BEGIN DESCRIPTION:
Mapping XS 12ae8659
END DESCRIPTION:
XS GIS Cut Line= 4
      2112261.05     13425748.30      2112313.13     13425553.01
      2112308.79     13425338.17      2111991.95     13425132.01
#Sta/Elev= 30
  4729.4  334.26  4770.2  334.32  4794.9  334.65  4815.6  334.68  4836.3  334.01
  4841.6  333.58  4846.8  333.86  4867.4  333.19  4916.7  333.76  4921.8  333.57
  4969.5  333.90  4999.5  333.33  5059.5  333.28  5079.6  333.47  5116.6  332.99
  5117.1  332.19  5122.1  332.19  5122.6  332.99  5195.6  333.48  5237.6  333.36
  5252.7  333.60  5273.8  333.62  5288.9  333.95  5346.2  334.73  5382.5  335.52
  5403.6  336.42  5454.9  337.54  5461.1  337.88  5494.1  338.84  5524.4  339.65
#Mann=7,-1,0
  4729.4     0.1       0  4770.2    0.05       0  5116.6   0.035       0
  5122.6    0.05       0  5195.6     0.1       0  5288.9    0.05       0
  5494.1     0.1       0
Bank Sta=5116.6,5122.6
Exp/Cntr=0.3,0.1

Type RM Length L Ch R = 1,739,206,206,206
BEGIN DESCRIPTION:
Mapping XS c5157742
END DESCRIPTION:
XS GIS Cut Line= 5
      2112321.81     13425607.27      2112410.78     13425479.23
      2112408.61     13425301.28      2112402.10     13425199.28
      2112011.43     13425025.65
#Sta/Elev= 30
  4720.9  333.79  4732.5  333.51  4738.6  333.79  4747.4  333.50  4753.4  333.74
  4783.1  333.05  4789.2  333.33  4804.1  332.95  4825.0  333.11  4839.9  332.72
  4872.6  332.93  4875.7  333.15  4943.5  332.25  4981.1  332.11  5001.1  332.39
  5121.2  331.46  5175.0  331.55  5206.2  331.26  5206.7  330.46  5211.7  330.46
  5212.2  331.26  5227.0  331.70  5317.9  332.55  5377.5  333.32  5400.7  334.37
  5406.2  334.22  5429.5  334.77  5530.7  338.14  5545.7  338.87  5584.5  339.96
#Mann=6,-1,0
  4720.9    0.05       0  4872.6     0.1       0  5206.2    0.07       0
  5212.2     0.1       0  5317.9    0.05       0  5530.7     0.1       0
Bank Sta=5206.2,5212.2
Exp/Cntr=0.3,0.1

Type RM Length L Ch R = 1,533,150,150,150
BEGIN DESCRIPTION:
Mapping XS 69800996
END DESCRIPTION:
XS GIS Cut Line= 5
      2112341.32     13425657.20      2112478.06     13425435.83
      2112508.44     13425262.22      2112478.06     13425140.69
      2112100.43     13424932.34
#Sta/Elev= 30
  4504.1  333.69  4537.9  333.92  4559.1  333.56  4595.8  334.03  4653.7  333.75
  4675.0  333.21  4689.8  333.44  4711.6  332.58  4727.0  332.88  4732.9  332.49
  4748.3  333.32  4754.2  333.12  4761.8  333.99  4772.9  334.35  4785.4  334.00
  4795.6  332.95  4805.7  332.54  4887.9  331.21  4948.0  330.82  4979.7  331.19
  5012.6  330.45  5012.8  330.44  5013.3  329.64  5018.3  329.64  5018.8  330.44
  5146.8  330.80  5152.5  330.51  5232.3  331.30  5380.6  333.17  5497.1  336.76
#Mann=7,-1,0
  4504.1    0.05       0  4689.8     0.1       0  4887.9    0.08       0
  5012.6     0.1       0  5012.8    0.07       0  5018.8     0.1       0
  5232.3    0.05       0
Bank Sta=5012.8,5018.8
Exp/Cntr=0.3,0.1

Type RM Length L Ch R = 1,383,176,176,176
BEGIN DESCRIPTION:
Mapping XS a7d4137b
END DESCRIPTION:
XS GIS Cut Line= 4
      2112376.05     13425681.07      2112656.01     13425262.22
      2112608.26     13425079.92      2112135.16     13424856.39
#Sta/Elev= 30
  4415.9  333.22  4456.1  333.37  4564.2  332.94  4606.6  332.36  4693.4  331.66
  4708.4  333.11  4714.4  333.18  4723.4  333.88  4735.9  333.95  4744.4  333.07
  4750.5  333.09  4759.0  332.33  4765.5  332.27  4772.0  331.49  4800.7  331.04
  4927.2  329.65  4980.5  329.50  4981.0  328.70  4986.0  328.70  4986.5  329.50
  4990.3  329.56  5030.5  330.09  5076.0  329.96  5129.9  329.93  5152.6  330.33
  5333.0  330.14  5381.2  330.90  5431.3  331.15  5521.0  332.72  5631.4  335.96
#Mann=9,-1,0
  4415.9    0.05       0  4606.6     0.1       0  4759.0    0.08       0
  4800.7     0.1       0  4980.5    0.07       0  4986.5     0.1       0
  4990.3    0.08       0  5076.0     0.1       0  5381.2    0.05       0
Bank Sta=4980.5,4986.5
Exp/Cntr=0.3,0.1

Type RM Length L Ch R = 1,207,0,0,0
BEGIN DESCRIPTION:
UNT 061 in La Jarita Watershed 3.0
END DESCRIPTION:
XS GIS Cut Line= 4
      2112290.96     13425842.54      2112777.10     13425234.87
      2112790.99     13424998.76      2112204.17     13424613.33
#Sta/Elev= 30
  4096.7  333.43  4155.2  333.70  4310.4  332.86  4475.1  332.34  4510.6  332.18
  4560.2  331.03  4574.6  331.44  4595.4  331.07  4609.2  331.95  4611.6  332.22
  4617.8  333.12  4631.4  333.97  4645.0  333.98  4681.8  331.52  4717.1  330.51
  4851.5  329.99  4904.8  328.65  4974.9  328.21  5005.0  328.65  5082.1  327.96
  5082.6  327.16  5087.6  327.16  5088.1  327.96  5132.3  328.57  5247.6  330.00
  5529.7  329.33  5598.2  329.95  5678.2  330.97  5767.8  332.45  5813.5  333.83
#Mann=11,-1,0
  4096.7     0.1       0  4310.4    0.05       0  4475.1     0.1       0
  4609.2    0.07       0  4611.6     0.1       0  5082.1    0.07       0
  5088.1     0.1       0  5132.3    0.08       0  5247.6     0.1       0
  5598.2    0.05       0  5678.2     0.1       0
Bank Sta=5082.1,5088.1
Exp/Cntr=0.3,0.1

Chan Stop Cuts=-1