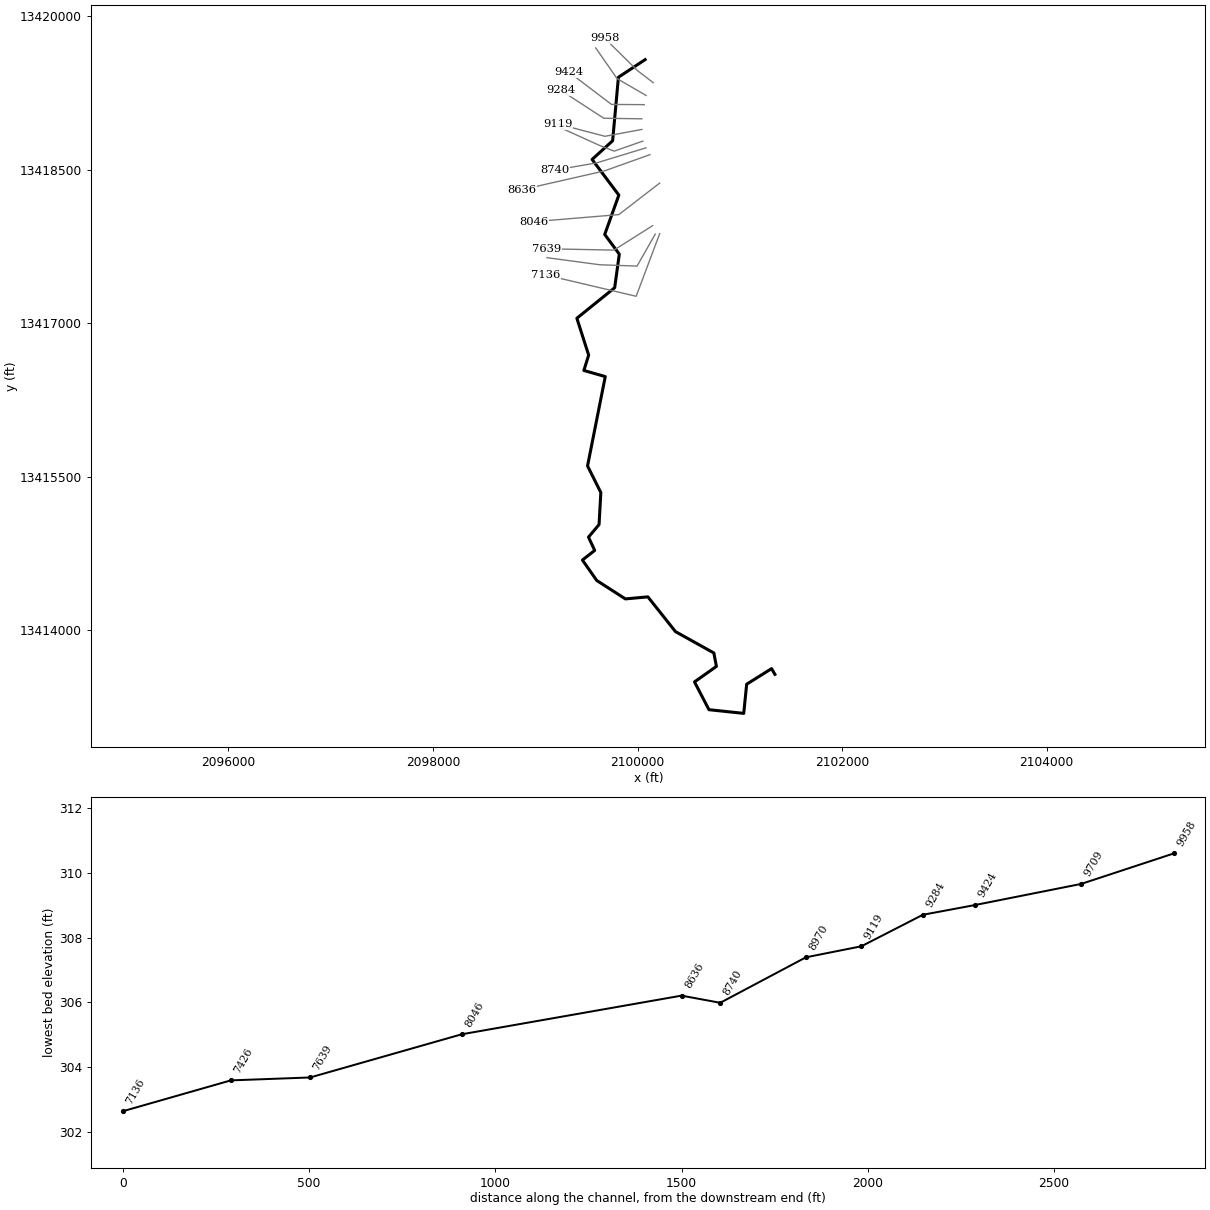
--- UNT 066 in La Jarita Watershed.prj (project) ---

Proj Title=UNT 066 in La Jarita Watershed Base Level Engineering
Current Plan=p01
Default Exp/Contr=0.3,0.1
English Units
Geom File=g01
Flow File=f01
Plan File=p01
Y Axis Title=Elevation
X Axis Title(PF)=Main Channel Distance
X Axis Title(XS)=Station
BEGIN DESCRIPTION:
UNT 066 in La Jarita Watershed
END DESCRIPTION:
DSS Export Rating Curves= 0
DSS Export Rating Curve Sorted= 0
DSS Export Volume Flow Curves= 0
DXF OffsetX= 0
DXF OffsetY= 0
DXF ScaleX= 1
DXF ScaleY= 10

--- UNT 066 in La Jarita Watershed.p01 (plan) ---

Plan Title=Multiple Run
Short Identifier=Multiple
Geom File=g01
Flow File=f01
Subcritical Flow
K Sum by GR= 0
Std Step Tol= 0.01
Critical Tol= 0.01
Num of Std Step Trials= 20
Max Error Tol= 0.3
Flow Tol Ratio= 0.001
Split Flow NTrial= 30
Split Flow Tol= 0.02
Split Flow Ratio= 0.02
Log Output Level= 0
Friction Slope Method= 1
Unsteady Friction Slope Method= 2
Unsteady Bridges Friction Slope Method= 1
Parabolic Critical Depth
Global Vel Dist=  1 , 1 , 1
Global Log Level= 0
CheckData=True
Encroach Param= -1, 0, 0, 0
BEGIN DESCRIPTION:
Multiple Run
END DESCRIPTION:

--- UNT 066 in La Jarita Watershed.f01 (steady flow) ---

Flow Title=Multiple
Program Version=5.05
Number of Profiles= 7
Profile Names=10-year,25-year,50-year,1pct_min,100-year,1pct_plu,500-year
River Rch & RM=UNT 066 in La Ja,Reach-1         ,9958
     146     196     235     141     281     561     408
River Rch & RM=UNT 066 in La Ja,Reach-1         ,8046
     168     225     272     163     325     649     475
Boundary for River Rch & Prof#=UNT 066 in La Ja,Reach-1         , 1
Up Type= 0
Dn Type= 3
Dn Slope=0.005
Boundary for River Rch & Prof#=UNT 066 in La Ja,Reach-1         , 2
Up Type= 0
Dn Type= 3
Dn Slope=0.005
Boundary for River Rch & Prof#=UNT 066 in La Ja,Reach-1         , 3
Up Type= 0
Dn Type= 3
Dn Slope=0.005
Boundary for River Rch & Prof#=UNT 066 in La Ja,Reach-1         , 4
Up Type= 0
Dn Type= 3
Dn Slope=0.005
Boundary for River Rch & Prof#=UNT 066 in La Ja,Reach-1         , 5
Up Type= 0
Dn Type= 3
Dn Slope=0.005
Boundary for River Rch & Prof#=UNT 066 in La Ja,Reach-1         , 6
Up Type= 0
Dn Type= 3
Dn Slope=0.005
Boundary for River Rch & Prof#=UNT 066 in La Ja,Reach-1         , 7
Up Type= 0
Dn Type= 3
Dn Slope=0.005
DSS Import GetInterval= 0
DSS Import GetPeak= 0
DSS Import FillOption= 0

--- UNT 066 in La Jarita Watershed.g01 (geometry) ---

Geom Title=Existing Conditions
Program Version=5.05

River Reach=UNT 066 in La Ja,Reach-1
Reach XY= 30
      2100073.89     13419577.29      2099812.72     13419405.08
      2099756.13      13418783.7      2099555.28     13418601.31
      2099816.94     13418252.51      2099678.92     13417867.96
      2099821.28     13417675.25      2099776.14     13417347.13
      2099406.35     13417048.51       2099521.8     13416688.27
      2099474.92      13416538.1      2099684.13      13416478.2
       2099510.8     13415604.54       2099640.8     13415344.54
      2099623.36     13415031.15      2099520.06     13414908.76
      2099580.83     13414778.55       2099460.8     13414684.54
       2099600.8     13414484.54       2099880.8     13414304.54
       2100100.8     13414324.54       2100370.8     13413984.54
      2100745.76     13413775.95       2100770.8     13413644.54
      2100556.52     13413492.96      2100698.01     13413221.26
      2101037.97     13413185.27      2101066.61     13413470.43
       2101310.1     13413622.77      2101342.66     13413566.78

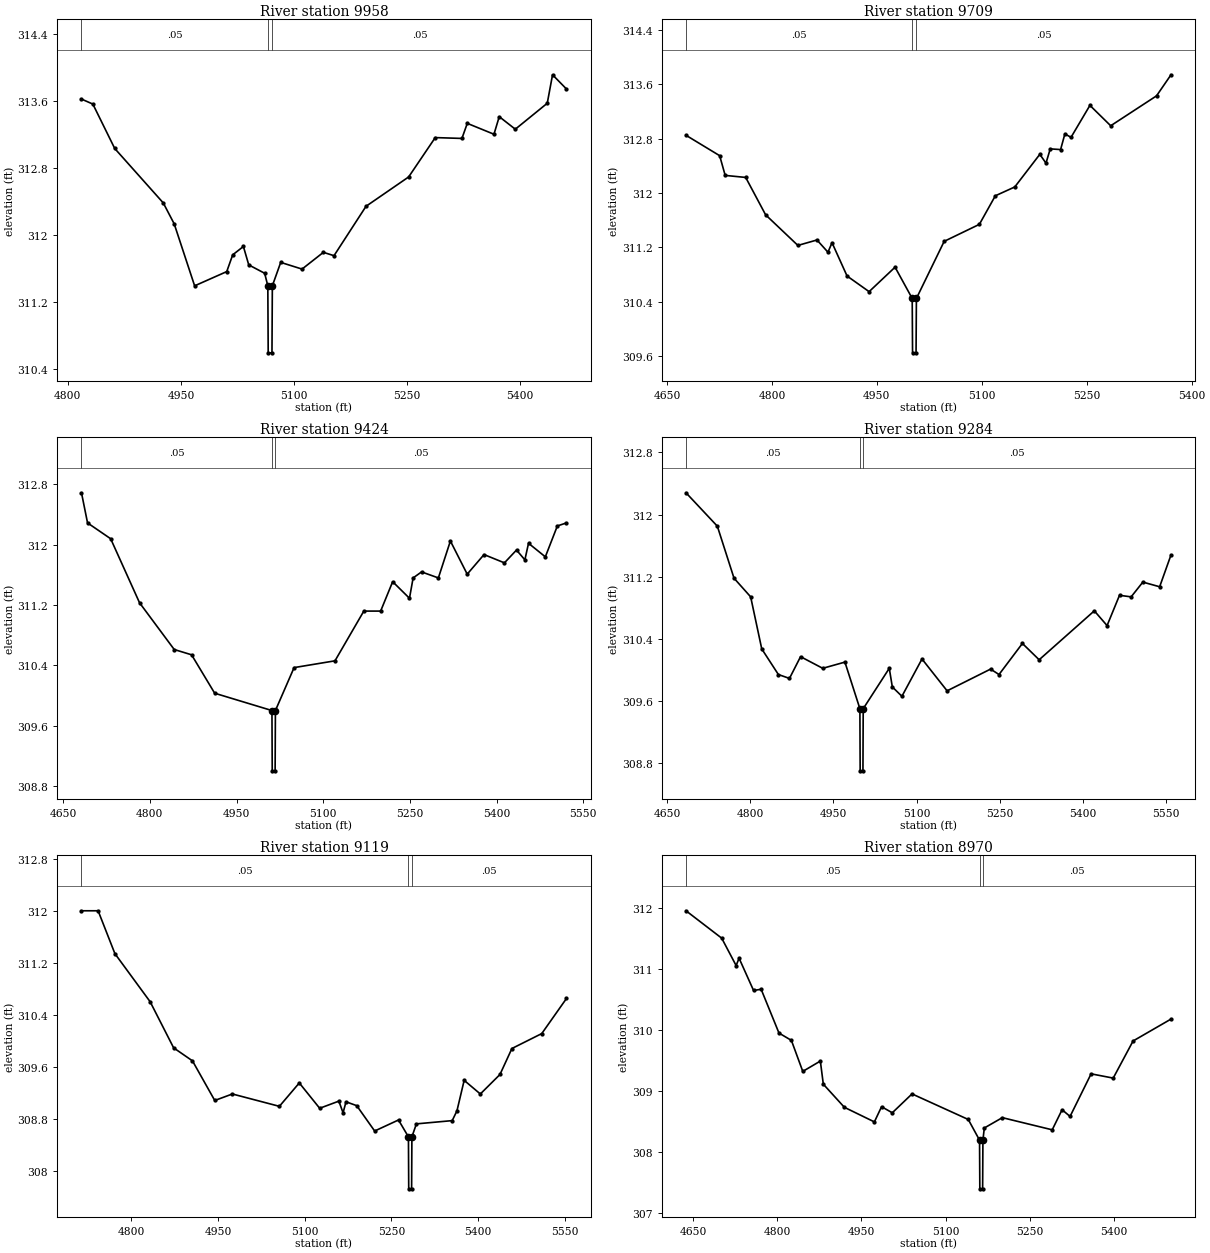
Type RM Length L Ch R = 1 ,9958    ,249,249,249
BEGIN DESCRIPTION:
Mapping XS 7ef91a8a
END DESCRIPTION:
XS GIS Cut Line= 3
      2100153.21     13419351.81      2100000.18     13419468.91
       2099679.3     13419785.41
#Sta/Elev= 30
  4818.1  313.62  4833.2  313.56  4862.2  313.03  4926.6  312.38  4941.1  312.13
  4968.2  311.39  5010.8  311.56  5018.7  311.76  5032.9  311.86    5040  311.64
  5061.1  311.54  5065.3  311.39  5065.8  310.59  5070.8  310.59  5071.3  311.39
  5082.4  311.67  5110.7  311.59    5139  311.79  5153.1  311.75  5195.6  312.34
  5252.1  312.69  5287.4  313.16  5322.8  313.15  5329.9  313.33  5365.3   313.2
  5372.3  313.41  5393.6  313.26    5436  313.57    5443  313.91  5461.5  313.74
#Mann= 3 ,-1 , 0
  4818.1     .05       0  5065.3     .03       0  5071.3     .05       0
Bank Sta=5065.3,5071.3
XS Rating Curve= 0 ,0
Exp/Cntr=0.3,0.1

Type RM Length L Ch R = 1 ,9709    ,285,285,285
BEGIN DESCRIPTION:
Mapping XS 9f5bda41
END DESCRIPTION:
XS GIS Cut Line= 3
      2100083.46     13419226.96      2099798.97     13419392.07
      2099591.15     13419691.24
#Sta/Elev= 30
  4677.2  312.85  4725.3  312.55  4733.2  312.26  4762.5  312.23    4791  311.68
  4837.1  311.23  4864.4  311.31  4880.1  311.13  4885.9  311.27  4907.4  310.78
  4938.9  310.55    4976  310.91  5000.5  310.45    5001  309.65    5006  309.65
  5006.5  310.45  5046.2  311.29  5096.5  311.54  5119.3  311.96  5147.1  312.09
  5182.9  312.57  5191.7  312.44  5197.8  312.65  5212.6  312.64  5218.7  312.87
  5227.5  312.82  5254.5  313.29  5284.2  312.99  5349.7  313.43  5370.4  313.74
#Mann= 3 ,-1 , 0
  4677.2     .05       0  5000.5     .03       0  5006.5     .05       0
Bank Sta=5000.5,5006.5
XS Rating Curve= 0 ,0
Exp/Cntr=0.3,0.1

Type RM Length L Ch R = 1 ,9424    ,140,140,140
BEGIN DESCRIPTION:
Mapping XS f0dbfc55
END DESCRIPTION:
XS GIS Cut Line= 3
       2100065.5     13419136.92      2099744.91     13419139.26
      2099331.67     13419452.75
#Sta/Elev= 30
  4681.7  312.69  4692.2  312.29  4732.2  312.08  4782.2  311.23  4842.2  310.61
  4872.2  310.54  4912.2  310.03  5011.3   309.8  5011.8     309  5016.8     309
  5017.3   309.8  5049.6  310.37  5120.4  310.46  5170.3  311.12  5199.4  311.12
  5220.2  311.51  5249.3  311.29  5255.6  311.56  5270.2  311.64  5299.3  311.56
  5320.1  312.05  5349.2  311.61  5378.3  311.87  5413.6  311.76  5434.5  311.93
    5449   311.8  5455.3  312.02  5484.4  311.84  5505.2  312.25    5521  312.29
#Mann= 3 ,-1 , 0
  4681.7     .05       0  5011.3     .03       0  5017.3     .05       0
Bank Sta=5011.3,5017.3
XS Rating Curve= 0 ,0
Exp/Cntr=0.3,0.1

Type RM Length L Ch R = 1 ,9284    ,165,165,165
BEGIN DESCRIPTION:
Mapping XS ff1404f4
END DESCRIPTION:
XS GIS Cut Line= 3
      2100041.54     13418998.41      2099669.06     13419004.03
      2099248.43     13419278.35
#Sta/Elev= 30
  4684.2  312.28  4740.7  311.85  4770.8  311.18  4800.8  310.94  4820.8  310.27
  4850.8  309.94  4870.8  309.89  4890.8  310.17  4930.8  310.02  4970.8   310.1
  4997.8   309.5  4998.3   308.7  5003.3   308.7  5003.8   309.5  5050.8  310.02
  5056.3  309.78  5073.6  309.66  5109.8  310.14  5155.1  309.73  5233.5  310.01
  5248.7  309.94  5290.9  310.34  5321.1  310.13  5420.6  310.76  5443.6  310.57
    5466  310.96    5487  310.94  5508.1  311.13  5538.4  311.07  5558.9  311.48
#Mann= 3 ,-1 , 0
  4684.2     .05       0  4997.8     .03       0  5003.8     .05       0
Bank Sta=4997.8,5003.8
XS Rating Curve= 0 ,0
Exp/Cntr=0.3,0.1

Type RM Length L Ch R = 1 ,9119    ,149,149,149
BEGIN DESCRIPTION:
Mapping XS 2f2592a7
END DESCRIPTION:
XS GIS Cut Line= 3
      2100041.93      13418894.6      2099681.89     13418827.58
      2099223.55     13418947.11
#Sta/Elev= 30
  4713.4  312.01  4742.2  312.01  4771.3  311.35  4832.3  310.61    4873   309.9
  4905.6   309.7  4944.2  309.09  4974.7  309.19  5056.1     309  5090.6  309.36
  5125.9  308.97  5159.1  309.08  5166.4   308.9  5171.5  309.07  5190.1  309.01
  5221.1  308.62  5262.4  308.79  5279.6  308.53  5280.1  307.73  5285.1  307.73
  5285.6  308.53  5293.4  308.73  5355.4  308.78  5363.6  308.93  5376.1   309.4
  5404.1  309.19  5438.1  309.49  5458.8  309.89  5510.5  310.12  5553.3  310.66
#Mann= 3 ,-1 , 0
  4713.4     .05       0  5279.6     .03       0  5285.6     .05       0
Bank Sta=5279.6,5285.6
XS Rating Curve= 0 ,0
Exp/Cntr=0.3,0.1

Type RM Length L Ch R = 1 ,8970    ,230,230,230
BEGIN DESCRIPTION:
Mapping XS a0956bd9
END DESCRIPTION:
XS GIS Cut Line= 4
      2100051.46     13418780.44      2099770.93     13418682.55
      2099630.31     13418737.43      2099251.15     13418909.14
#Sta/Elev= 30
  4637.3  311.96  4700.9  311.51  4726.6  311.06  4731.9  311.18  4757.7  310.65
  4771.2  310.67    4803  309.95  4825.1  309.83  4845.4  309.32  4876.7  309.49
    4882  309.11  4919.5  308.73    4973  308.49  4985.8  308.74  5004.9  308.64
  5040.1  308.95  5140.3  308.53  5160.4  308.19  5160.9  307.39  5165.9  307.39
  5166.4  308.19  5168.9  308.39    5201  308.56  5289.9  308.36  5307.5  308.69
  5321.7  308.58  5359.2  309.28  5398.6  309.21    5434  309.82  5501.6  310.18
#Mann= 3 ,-1 , 0
  4637.3     .05       0  5160.4     .03       0  5166.4     .05       0
Bank Sta=5160.4,5166.4
XS Rating Curve= 0 ,0
Exp/Cntr=0.3,0.1

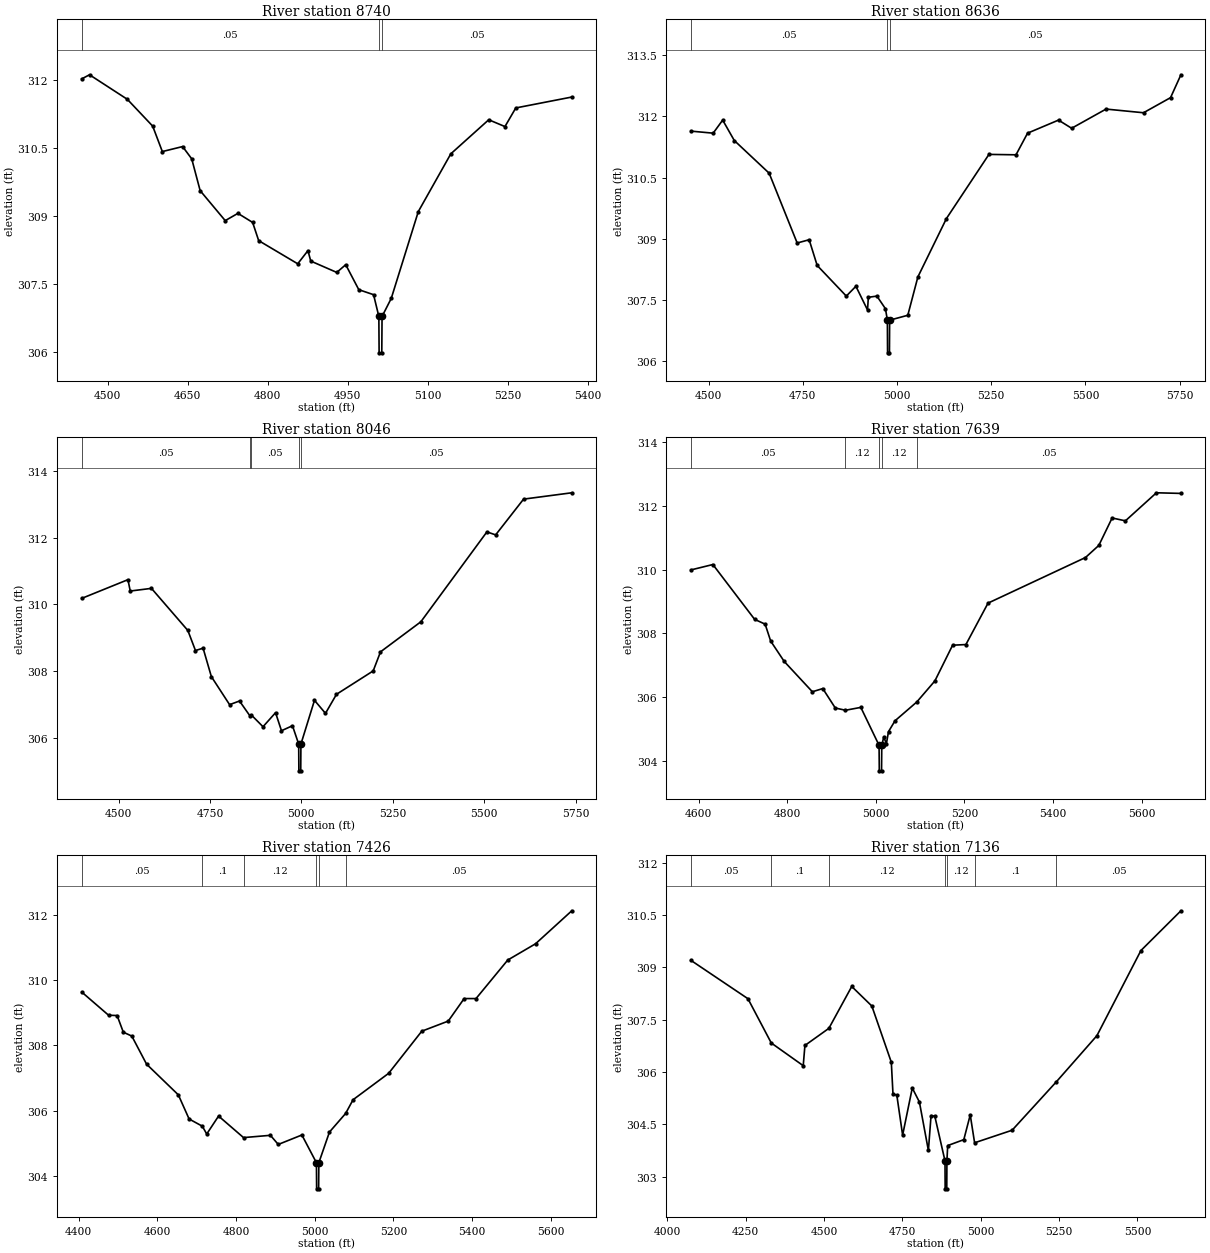
Type RM Length L Ch R = 1 ,8740    ,104,104,104
BEGIN DESCRIPTION:
Mapping XS 955b611c
END DESCRIPTION:
XS GIS Cut Line= 3
      2100082.25      13418714.8      2099600.37     13418567.75
      2099191.54     13418497.11
#Sta/Elev= 30
  4451.1  312.02  4465.7  312.11  4536.6  311.57  4584.1  310.98  4602.2  310.42
  4640.2  310.53  4657.3  310.26  4673.1  309.56  4720.1   308.9  4743.9  309.06
  4771.5  308.86  4782.8  308.46    4856  307.95  4875.2  308.24  4880.4  308.01
  4929.2  307.76    4946  307.93  4970.5  307.38  4998.2  307.27  5008.1  306.79
  5008.6  305.99  5013.6  305.99  5014.1  306.79  5031.4  307.19  5082.1   309.1
    5143  310.37  5214.1  311.12  5244.5  310.97  5264.8  311.38  5369.8  311.62
#Mann= 3 ,-1 , 0
  4451.1     .05       0  5008.1     .03       0  5014.1     .05       0
Bank Sta=5008.1,5014.1
XS Rating Curve= 0 ,0
Exp/Cntr=0.3,0.1

Type RM Length L Ch R = 1 ,8636    ,590,590,590
BEGIN DESCRIPTION:
UNT 066 in La Jarita Watershed 4.0
END DESCRIPTION:
XS GIS Cut Line= 3
      2100120.74       13418648.      2099675.89     13418489.13
      2098868.16     13418305.51
#Sta/Elev= 30
  4452.7  311.64  4511.9  311.59  4537.2  311.91    4568  311.41  4660.5  310.61
  4734.9   308.9  4766.7  308.98    4788  308.35  4865.3   307.6  4890.8  307.84
  4921.6  307.26  4923.8  307.57  4946.5   307.6  4969.2  307.29  4974.3  307.01
  4974.8  306.21  4979.8  306.21  4980.3  307.01  5028.5  307.13  5055.3  308.07
  5131.1   309.5  5243.9  311.07  5315.7  311.06  5346.4  311.59  5428.5  311.91
  5463.4  311.71  5554.7  312.18  5654.1  312.09  5725.9  312.46  5753.4  313.02
#Mann= 3 ,-1 , 0
  4452.7     .05       0  4974.3     .03       0  4980.3     .05       0
Bank Sta=4974.3,4980.3
XS Rating Curve= 0 ,0
Exp/Cntr=0.3,0.1

Type RM Length L Ch R = 1 ,8046    ,407,407,407
BEGIN DESCRIPTION:
Mapping XS 0a1d5582
END DESCRIPTION:
XS GIS Cut Line= 3
      2100216.19      13418370.2       2099816.9     13418062.05
      2098983.55     13417992.61
#Sta/Elev= 30
  4399.2  310.18  4525.6  310.74  4531.9   310.4  4589.9  310.48  4689.5  309.22
  4710.3  308.62  4731.2  308.69  4753.8  307.84  4803.7     307  4830.8  307.11
  4859.6  306.66  4863.3  306.69  4895.1  306.34  4929.4  306.76  4945.6  306.22
  4975.7  306.37  4992.7  305.82  4993.2  305.02  4998.3  305.02  4998.8  305.82
  5035.9  307.13    5066  306.74  5096.1  307.31  5196.5  308.01  5216.5  308.58
  5326.9  309.48  5507.6  312.17  5531.5  312.08  5607.9  313.15  5739.8  313.34
#Mann= 5 ,-1 , 0
  4399.2     .05       0  4859.6     .12       0  4863.3     .05       0
  4992.7     .03       0  4998.8     .05       0
Bank Sta=4992.7,4998.8
XS Rating Curve= 0 ,0
Exp/Cntr=0.3,0.1

Type RM Length L Ch R = 1 ,7639    ,213,213,213
BEGIN DESCRIPTION:
Mapping XS e2d018f0
END DESCRIPTION:
XS GIS Cut Line= 3
      2100146.74     13417953.53      2099769.16     13417714.83
      2099109.69     13417727.85
#Sta/Elev= 30
  4582.3  309.99    4632  310.16  4726.3  308.44    4750  308.29  4762.5  307.76
  4793.1  307.12  4856.6  306.17  4880.1  306.27  4908.4  305.66  4931.4  305.59
    4966  305.68  5007.2  304.49  5007.7  303.69  5012.8  303.69  5013.3  304.49
  5017.8  304.75  5023.7  304.54  5028.5  304.92  5043.2  305.26  5092.4  305.85
  5133.2  306.51  5173.2  307.63  5203.2  307.65  5253.2  308.95  5473.2  310.38
  5503.3  310.76  5533.3  311.62  5563.3  311.53  5633.3  312.41  5688.6  312.39
#Mann= 5 ,-1 , 0
  4582.3     .05       0  4931.4     .12       0  5007.2     .07       0
  5013.3     .12       0  5092.4     .05       0
Bank Sta=5007.2,5013.3
XS Rating Curve= 0 ,0
Exp/Cntr=0.3,0.1

Type RM Length L Ch R = 1 ,7426    ,290,290,290
BEGIN DESCRIPTION:
Mapping XS 68b1c13b
END DESCRIPTION:
XS GIS Cut Line= 4
      2100172.78     13417871.04      2099994.85     13417558.58
      2099630.27      13417571.6      2099113.79     13417641.04
#Sta/Elev= 30
  4407.9  309.63  4476.1  308.92  4497.8  308.91  4513.6   308.4  4535.2  308.28
  4572.7  307.42  4653.4  306.48  4680.8  305.74  4714.3  305.52  4725.6  305.28
  4755.7  305.83  4819.1  305.17  4887.4  305.24  4907.4  304.96  4967.4  305.25
  5004.4   304.4  5004.9   303.6    5010   303.6  5010.5   304.4  5037.5  305.34
  5078.6  305.91  5097.5  306.33    5188  307.14  5272.1  308.43  5339.4  308.74
  5379.8  309.43    5410  309.43  5490.6  310.61  5561.4  311.11  5653.4  312.12
#Mann= 6 ,-1 , 0
  4407.9     .05       0  4714.3      .1       0  4819.1     .12       0
  5004.4     .07       0  5010.5     .12       0  5078.6     .05       0
Bank Sta=5004.4,5010.5
XS Rating Curve= 0 ,0
Exp/Cntr=0.3,0.1

Type RM Length L Ch R = 1 ,7136    ,0,0,0
BEGIN DESCRIPTION:
Mapping XS 4f3a904a
END DESCRIPTION:
XS GIS Cut Line= 3
      2100216.22     13417875.46      2099986.17     13417263.44
      2099100.77     13417471.77
#Sta/Elev= 30
  4075.4   309.2  4257.5   308.1    4332  306.83  4433.9  306.18  4439.3  306.76
  4515.7  307.25  4588.7  308.45  4652.8  307.89  4714.9  306.28  4720.3  305.36
  4732.4  305.34    4751  304.19  4781.8  305.54  4804.5  305.14  4833.2  303.75
  4841.7  304.75  4853.7  304.73  4886.2  303.45  4886.7  302.65  4891.8  302.65
  4892.3  303.45  4894.8  303.89  4946.2  304.06  4966.7  304.77  4980.6  303.97
  5100.3  304.33  5241.6  305.72  5370.8  307.04  5511.2  309.48  5638.8  310.62
#Mann= 7 ,-1 , 0
  4075.4     .05       0    4332      .1       0  4515.7     .12       0
  4886.2     .07       0  4892.3     .12       0  4980.6      .1       0
  5241.6     .05       0
Bank Sta=4886.2,4892.3
XS Rating Curve= 0 ,0
Exp/Cntr=0.3,0.1
LCMann Table=0

Chan Stop Cuts=-1
Use User Specified Reach Order=0
Composite Channel Slope=5