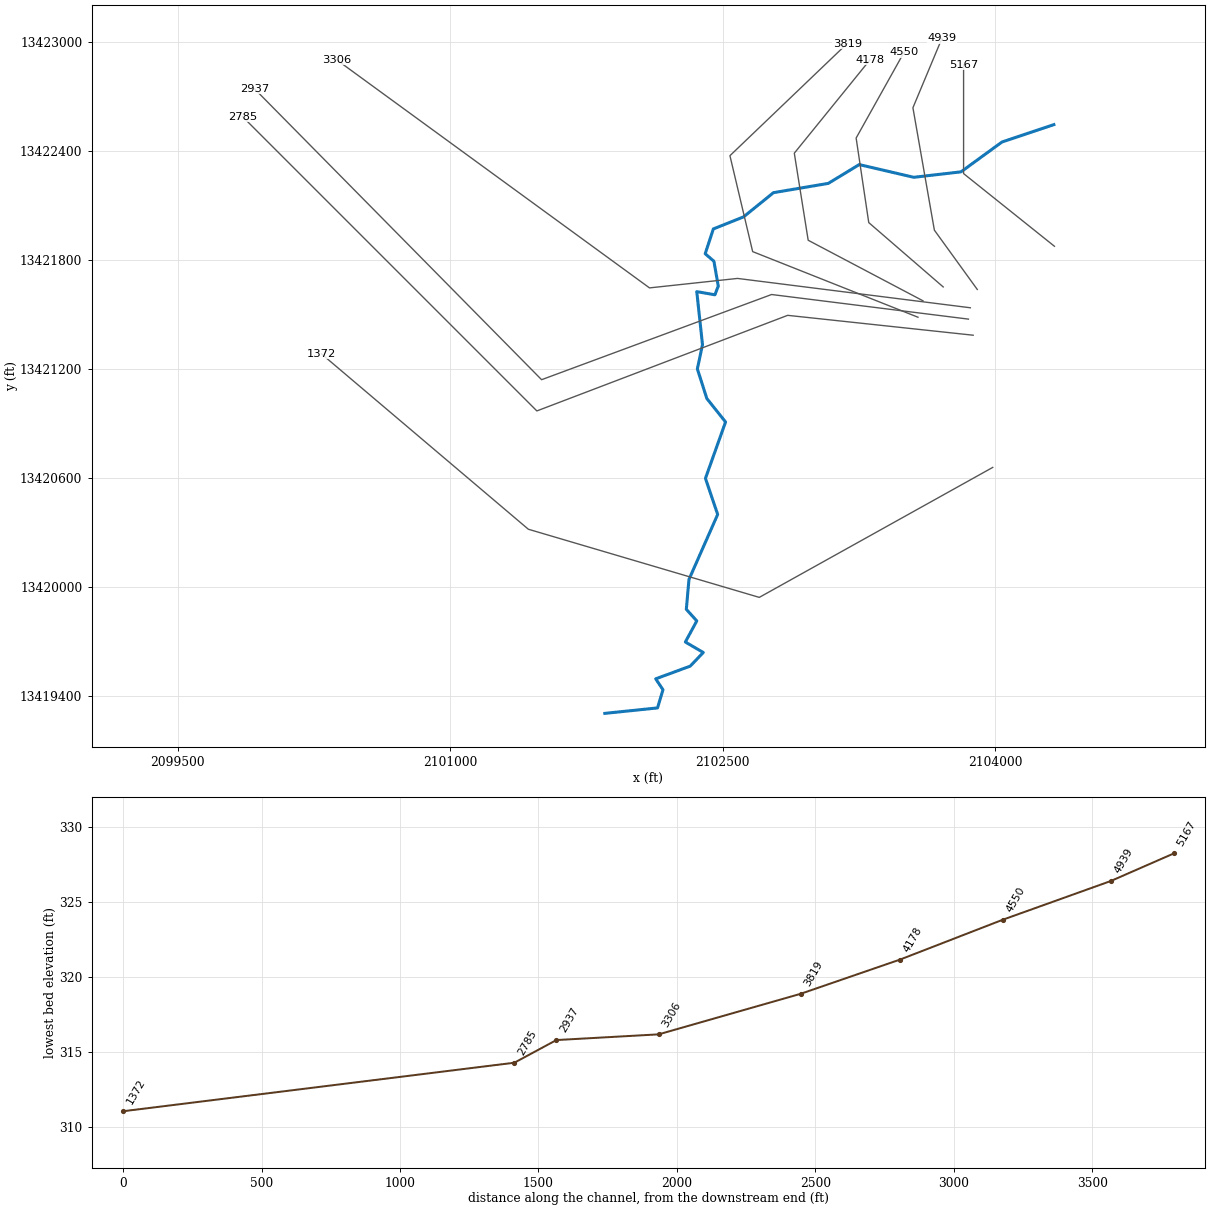
--- UNT 077 in La Jarita Watershed.prj (project) ---

Proj Title=UNT 077 in La Jarita Watershed Base Level Engineering
Current Plan=p01
Default Exp/Contr=0.3,0.1
English Units
Geom File=g01
Flow File=f01
Plan File=p01
BEGIN DESCRIPTION:
UNT 077 in La Jarita Watershed
END DESCRIPTION:

--- UNT 077 in La Jarita Watershed.p01 (plan) ---

Plan Title=Multiple Run
Short Identifier=Multiple
Geom File=g01
Flow File=f01
Subcritical Flow
K Sum by GR= 0
Std Step Tol= 0.01
Critical Tol= 0.01
Num of Std Step Trials= 20
Max Error Tol= 0.3
Flow Tol Ratio= 0.001
Split Flow NTrial= 30
Split Flow Tol= 0.02
Split Flow Ratio= 0.02
Log Output Level= 0
Friction Slope Method= 1
Unsteady Friction Slope Method= 2
Unsteady Bridges Friction Slope Method= 1
Parabolic Critical Depth
Global Vel Dist=  1 , 1 , 1
Global Log Level= 0
CheckData=True
Encroach Param= -1, 0, 0, 0
BEGIN DESCRIPTION:
Multiple Run
END DESCRIPTION:

--- UNT 077 in La Jarita Watershed.f01 (steady flow) ---

Flow Title=Multiple
Number of Profiles=7
Profile Names=10-year,25-year,50-year,1pct_min,100-year,1pct_plu,500-year
River Rch & RM= UNT 077 in La Ja,Reach-1,5167
     120     157     187     110     220     439     311
Boundary for River Rch & Prof#=UNT 077 in La Ja,Reach-1,1
Up Type=0
Dn Type=3
Dn Slope=0.005
Boundary for River Rch & Prof#=UNT 077 in La Ja,Reach-1,2
Up Type=0
Dn Type=3
Dn Slope=0.005
Boundary for River Rch & Prof#=UNT 077 in La Ja,Reach-1,3
Up Type=0
Dn Type=3
Dn Slope=0.005
Boundary for River Rch & Prof#=UNT 077 in La Ja,Reach-1,4
Up Type=0
Dn Type=3
Dn Slope=0.005
Boundary for River Rch & Prof#=UNT 077 in La Ja,Reach-1,5
Up Type=0
Dn Type=3
Dn Slope=0.005
Boundary for River Rch & Prof#=UNT 077 in La Ja,Reach-1,6
Up Type=0
Dn Type=3
Dn Slope=0.005
Boundary for River Rch & Prof#=UNT 077 in La Ja,Reach-1,7
Up Type=0
Dn Type=3
Dn Slope=0.005

--- UNT 077 in La Jarita Watershed.g01 (geometry) ---

Geom Title=Existing Conditions

River Reach=UNT 077 in La Ja,Reach-1
Reach XY= 30
      2104321.85     13422544.37      2104036.48     13422448.89
      2103810.80     13422284.54      2103550.80     13422254.54
      2103250.80     13422324.54      2103080.53     13422221.02
      2102778.88     13422170.03      2102613.95     13422036.56
      2102447.94     13421970.37      2102403.17     13421833.83
      2102451.19     13421792.42      2102475.06     13421655.70
      2102456.62     13421607.96      2102356.79     13421625.32
      2102388.26     13421333.44      2102360.05     13421199.97
      2102412.13     13421037.21      2102515.21     13420908.09
      2102404.53     13420597.76      2102471.81     13420399.19
      2102313.81     13420041.38      2102299.28     13419877.27
      2102356.79     13419813.25      2102293.86     13419697.15
      2102392.60     13419639.64      2102320.80     13419564.54
      2102130.80     13419494.54      2102170.80     13419434.54
      2102140.80     13419334.54      2101850.80     13419304.54

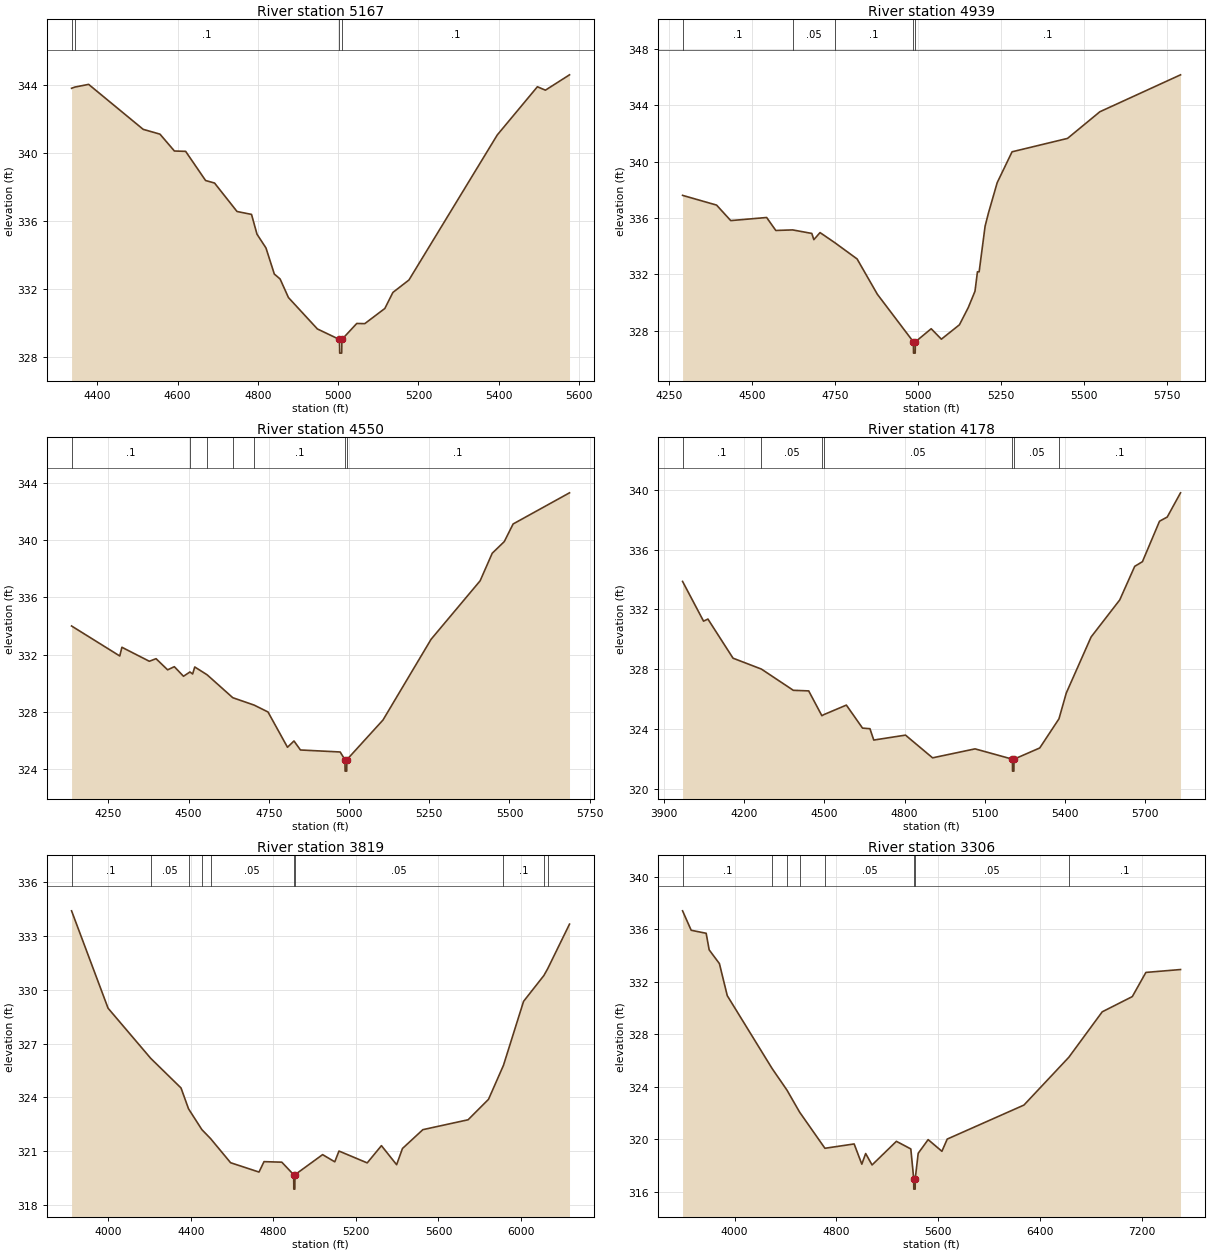
Type RM Length L Ch R = 1,5167,228,228,228
BEGIN DESCRIPTION:
UNT 077 in La Jarita Watershed 3.0
END DESCRIPTION:
XS GIS Cut Line= 3
      2104325.04     13421874.97      2103825.00     13422275.00
      2103825.00     13422875.04
#Sta/Elev= 30
  4335.9  343.79  4343.9  343.86  4378.4  344.02  4514.4  341.38  4556.1  341.10
  4592.1  340.11  4620.1  340.09  4669.7  338.38  4692.1  338.23  4748.1  336.56
  4784.2  336.39  4797.8  335.23  4820.2  334.42  4841.0  332.89  4855.4  332.60
  4876.2  331.51  4948.2  329.67  5003.3  329.05  5003.8  328.25  5008.8  328.25
  5009.3  329.05  5046.3  329.99  5066.3  329.98  5116.3  330.87  5136.3  331.81
  5176.3  332.54  5396.3  341.05  5496.3  343.88  5516.3  343.68  5576.3  344.58
#Mann=4,-1,0
  4335.9    0.05       0  4343.9     0.1       0  5003.3    0.07       0
  5009.3     0.1       0
Bank Sta=5003.3,5009.3
Exp/Cntr=0.3,0.1

Type RM Length L Ch R = 1,4939,389,389,389
BEGIN DESCRIPTION:
Mapping XS 0c5f0390
END DESCRIPTION:
XS GIS Cut Line= 4
      2103900.38     13421637.32      2103664.29     13421963.67
      2103546.24     13422637.29      2103705.98     13423019.26
#Sta/Elev= 30
  4291.1  337.60  4393.6  336.91  4436.3  335.81  4544.5  336.03  4572.1  335.11
  4622.8  335.15  4680.6  334.90  4686.8  334.46  4705.4  334.96  4749.0  334.26
  4817.1  333.09  4878.0  330.59  4986.7  327.21  4987.2  326.41  4992.2  326.41
  4992.7  327.21  5040.4  328.14  5071.1  327.40  5125.5  328.42  5152.1  329.64
  5172.4  330.80  5179.8  332.18  5184.9  332.18  5202.9  335.42  5213.0  336.35
  5239.3  338.50  5284.1  340.69  5451.2  341.64  5548.7  343.53  5791.8  346.15
#Mann=5,-1,0
  4291.1     0.1       0  4622.8    0.05       0  4749.0     0.1       0
  4986.7    0.07       0  4992.7     0.1       0
Bank Sta=4986.7,4992.7
Exp/Cntr=0.3,0.1

Type RM Length L Ch R = 1,4550,372,372,372
BEGIN DESCRIPTION:
Mapping XS 489fafaf
END DESCRIPTION:
XS GIS Cut Line= 4
      2103712.90     13421651.18      2103303.18     13422005.34
      2103233.74     13422470.62      2103496.82     13422941.40
#Sta/Elev= 30
  4135.7  334.00  4285.9  331.90  4292.5  332.51  4378.0  331.53  4398.9  331.71
  4435.0  330.93  4455.9  331.15  4484.4  330.48  4504.4  330.78  4512.9  330.64
  4519.5  331.13  4558.2  330.58  4637.9  328.98  4704.7  328.46  4747.7  327.98
  4808.4  325.51  4828.6  325.95  4848.8  325.32  4972.5  325.18  4987.4  324.64
  4987.9  323.84  4992.9  323.84  4993.4  324.64  5106.0  327.42  5255.8  333.07
  5408.5  337.16  5446.2  339.09  5483.9  339.91  5511.3  341.14  5687.0  343.32
#Mann=7,-1,0
  4135.7     0.1       0  4504.4    0.05       0  4558.2    0.08       0
  4637.9    0.05       0  4704.7     0.1       0  4987.4    0.07       0
  4993.4     0.1       0
Bank Sta=4987.4,4993.4
Exp/Cntr=0.3,0.1

Type RM Length L Ch R = 1,4178,359,359,359
BEGIN DESCRIPTION:
Mapping XS 59487c82
END DESCRIPTION:
XS GIS Cut Line= 4
      2103601.83     13421574.77      2102969.85     13421908.12
      2102893.46     13422387.29      2103309.62     13422900.54
#Sta/Elev= 30
  3970.7  333.88  4049.1  331.22  4065.4  331.36  4159.3  328.74  4265.4  328.01
  4384.5  326.59  4442.0  326.55  4491.2  324.89  4498.2  324.96  4582.7  325.60
  4643.1  324.06  4670.8  324.02  4685.1  323.26  4803.6  323.59  4904.8  322.07
  5063.6  322.67  5203.1  321.98  5203.6  321.18  5208.6  321.18  5209.1  321.98
  5305.2  322.73  5377.0  324.68  5404.4  326.41  5497.1  330.16  5604.1  332.64
  5660.1  334.89  5688.9  335.20  5752.8  337.91  5781.6  338.19  5831.2  339.81
#Mann=7,-1,0
  3970.7     0.1       0  4265.4    0.05       0  4491.2    0.08       0
  4498.2    0.05       0  5203.1    0.03       0  5209.1    0.05       0
  5377.0     0.1       0
Bank Sta=5203.1,5209.1
Exp/Cntr=0.3,0.1

Type RM Length L Ch R = 1,3819,513,513,513
BEGIN DESCRIPTION:
Mapping XS 74267971
END DESCRIPTION:
XS GIS Cut Line= 4
      2103573.99     13421484.52      2102664.29     13421845.62
      2102539.29     13422373.40      2103184.38     13422990.73
#Sta/Elev= 30
  3821.4  334.39  3998.4  328.97  4205.1  326.18  4352.1  324.53  4388.5  323.37
  4453.3  322.21  4495.5  321.71  4592.4  320.37  4730.1  319.85  4754.4  320.43
  4840.6  320.40  4898.3  319.70  4898.8  318.90  4903.8  318.90  4904.3  319.70
  5038.4  320.82  5097.5  320.42  5117.7  321.02  5254.7  320.36  5323.6  321.32
  5397.2  320.26  5425.5  321.16  5524.5  322.21  5743.7  322.76  5842.8  323.90
  5915.2  325.79  6012.6  329.35  6111.2  330.79  6129.3  331.16  6235.4  333.65
#Mann=10,-1,0
  3821.4     0.1       0  4205.1    0.05       0  4388.5     0.1       0
  4453.3    0.08       0  4495.5    0.05       0  4898.3    0.03       0
  4904.3    0.05       0  5915.2     0.1       0  6111.2    0.12       0
  6129.3     0.1       0
Bank Sta=4898.3,4904.3
Exp/Cntr=0.3,0.1

Type RM Length L Ch R = 1,3306,369,369,369
BEGIN DESCRIPTION:
Mapping XS 67e8aae6
END DESCRIPTION:
XS GIS Cut Line= 4
      2103862.21     13421536.59      2102580.96     13421698.05
      2102096.59     13421645.97      2100373.26     13422902.46
#Sta/Elev= 30
  3591.0  337.39  3658.7  335.91  3776.4  335.68  3799.9  334.42  3880.5  333.37
  3942.1  330.93  4293.9  325.39  4411.0  323.74  4510.5  322.06  4709.3  319.31
  4938.7  319.64  4999.0  318.10  5029.2  318.91  5079.5  318.04  5270.6  319.84
  5383.9  319.26  5406.6  317.00  5407.1  316.20  5418.1  316.20  5418.6  317.00
  5441.9  318.93  5520.0  319.97  5628.1  319.08  5669.8  320.01  6272.4  322.60
  6625.0  326.24  6887.3  329.70  7123.7  330.86  7230.3  332.70  7502.3  332.92
#Mann=8,-1,0
  3591.0     0.1       0  4293.9    0.05       0  4411.0     0.1       0
  4510.5    0.08       0  4709.3    0.05       0  5406.6    0.03       0
  5418.6    0.05       0  6625.0     0.1       0
Bank Sta=5406.6,5418.6
Exp/Cntr=0.3,0.1

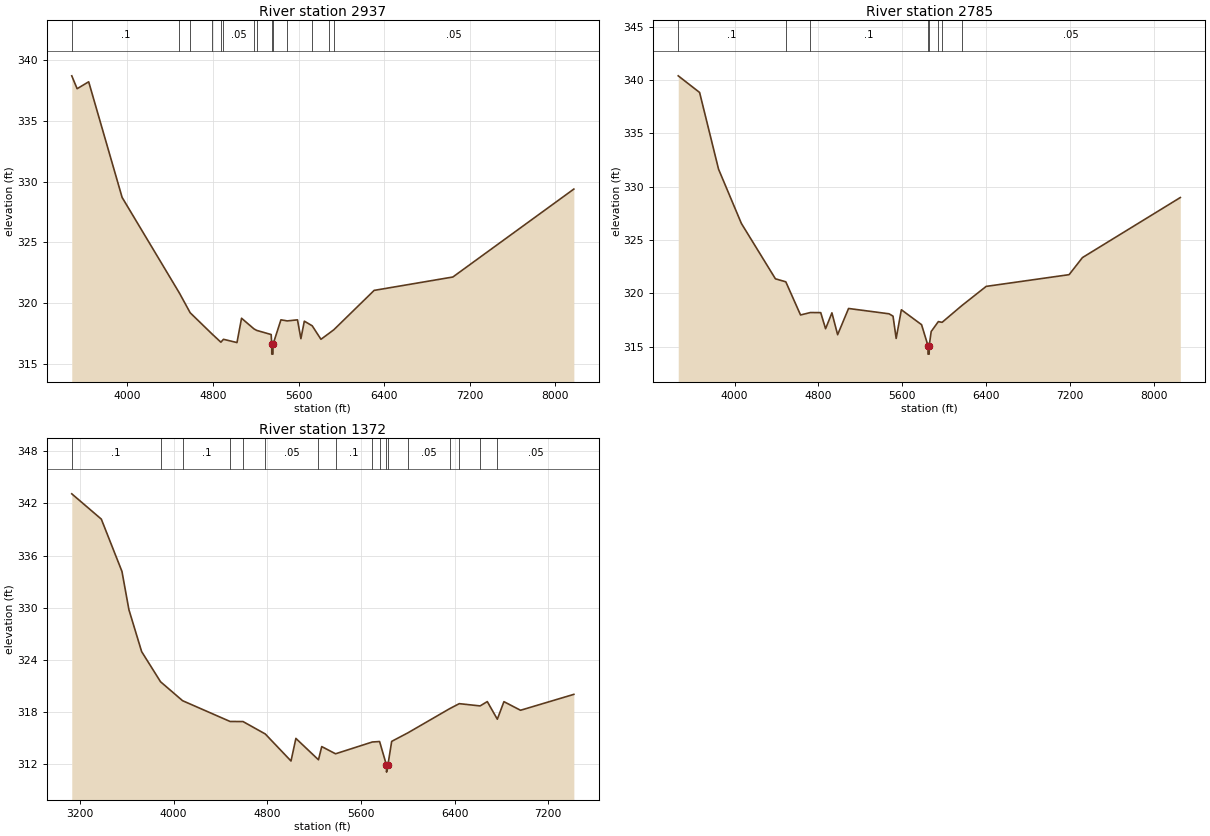
Type RM Length L Ch R = 1,2937,152,152,152
BEGIN DESCRIPTION:
Mapping XS 97b2df32
END DESCRIPTION:
XS GIS Cut Line= 4
      2103851.83     13421474.09      2102768.46     13421609.51
      2101502.84     13421140.76      2099923.18     13422741.40
#Sta/Elev= 30
  3481.4  338.70  3531.4  337.64  3639.4  338.21  3951.9  328.70  4487.7  320.83
  4587.7  319.22  4795.0  317.45  4874.5  316.80  4898.6  317.04  5024.8  316.77
  5067.4  318.77  5184.4  317.89  5209.4  317.77  5344.3  317.43  5349.4  316.62
  5349.9  315.82  5360.9  315.82  5361.4  316.62  5435.4  318.64  5494.2  318.55
  5590.0  318.64  5621.9  317.09  5653.9  318.53  5727.5  318.15  5809.2  317.04
  5883.2  317.52  5930.2  317.83  6306.2  321.06  7041.5  322.16  8171.7  329.39
#Mann=14,-1,0
  3481.4     0.1       0  4487.7    0.05       0  4587.7    0.08       0
  4795.0    0.05       0  4874.5    0.08       0  4898.6    0.05       0
  5184.4     0.1       0  5209.4    0.05       0  5349.4    0.04       0
  5361.4    0.05       0  5494.2    0.08       0  5727.5    0.05       0
  5883.2    0.08       0  5930.2    0.05       0
Bank Sta=5349.4,5361.4
Exp/Cntr=0.3,0.1

Type RM Length L Ch R = 1,2785,1413,1413,1413
BEGIN DESCRIPTION:
Mapping XS e3da3914
END DESCRIPTION:
XS GIS Cut Line= 4
      2103877.84     13421385.55      2102857.00     13421494.92
      2101476.79     13420968.88      2099856.98     13422588.70
#Sta/Elev= 30
  3461.5  340.40  3665.5  338.84  3846.5  331.65  4064.6  326.56  4389.6  321.37
  4488.7  321.09  4629.4  317.98  4724.2  318.21  4822.1  318.20  4868.6  316.69
  4929.1  318.18  4983.6  316.13  5088.0  318.59  5474.9  318.09  5512.6  317.87
  5542.7  315.78  5592.2  318.47  5785.2  317.07  5846.3  315.11  5846.8  314.31
  5857.8  314.31  5858.3  315.11  5877.0  316.43  5945.5  317.36  5981.1  317.29
  6168.5  318.85  6402.2  320.66  7194.1  321.76  7321.4  323.36  8256.0  328.99
#Mann=8,-1,0
  3461.5     0.1       0  4488.7    0.05       0  4724.2     0.1       0
  5846.3    0.07       0  5858.3     0.1       0  5945.5    0.05       0
  5981.1    0.08       0  6168.5    0.05       0
Bank Sta=5846.3,5858.3
Exp/Cntr=0.3,0.1

Type RM Length L Ch R = 1,1372,0,0,0
BEGIN DESCRIPTION:
UNT 077 in La Jarita Watershed 1.0
END DESCRIPTION:
XS GIS Cut Line= 4
      2103985.43     13420658.10      2102700.75     13419942.84
      2101429.92     13420317.84      2100291.03     13421283.12
#Sta/Elev= 30
  3130.6  343.11  3382.9  340.20  3559.3  334.18  3618.8  329.77  3727.4  324.95
  3888.9  321.48  4077.1  319.30  4482.8  316.91  4593.4  316.90  4783.5  315.47
  5003.2  312.36  5044.9  314.96  5237.7  312.50  5265.7  314.02  5383.6  313.19
  5698.1  314.55  5759.8  314.60  5818.6  311.88  5819.1  311.08  5830.6  311.88
  5863.1  314.62  5999.9  315.59  6359.1  318.39  6440.4  318.96  6618.2  318.70
  6679.6  319.20  6765.4  317.17  6821.8  319.19  6963.5  318.20  7418.9  320.03
#Mann=17,-1,0
  3130.6     0.1       0  3888.9    0.05       0  4077.1     0.1       0
  4482.8    0.05       0  4593.4     0.1       0  4783.5    0.05       0
  5237.7    0.12       0  5383.6     0.1       0  5698.1    0.12       0
  5759.8     0.1       0  5818.6    0.03       0  5830.6     0.1       0
  5999.9    0.05       0  6359.1     0.1       0  6440.4    0.05       0
  6618.2    0.08       0  6765.4    0.05       0
Bank Sta=5818.6,5830.6
Exp/Cntr=0.3,0.1

Chan Stop Cuts=-1