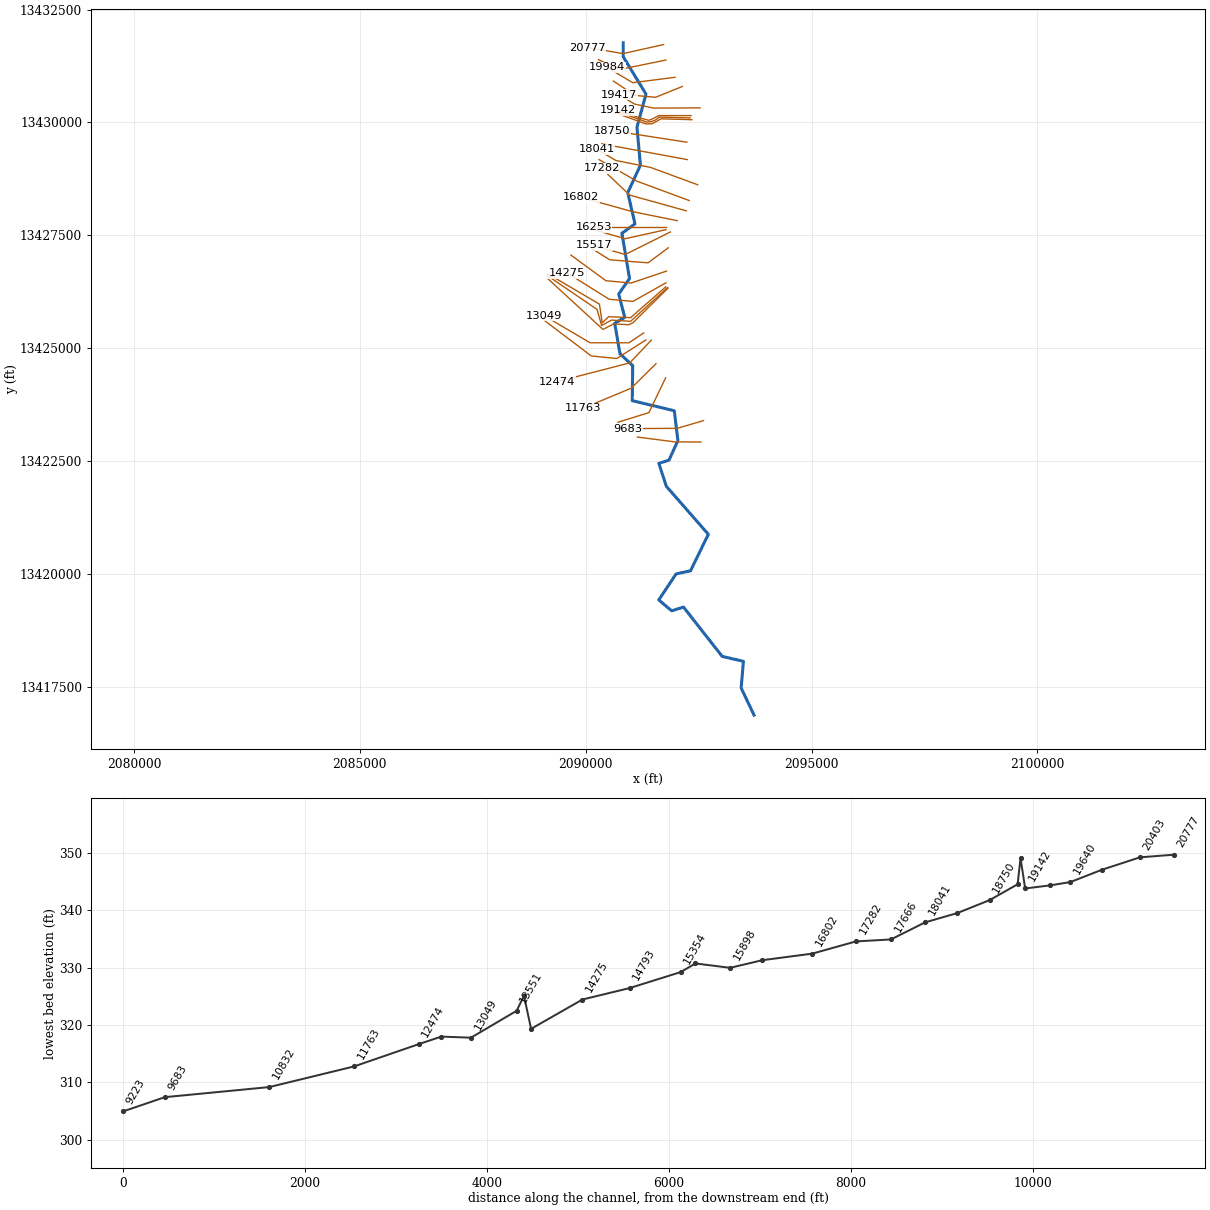
--- UNT 090 in La Jarita Watershed.prj (project) ---

Proj Title=UNT 090 in La Jarita Watershed Base Level Engineering
Current Plan=p01
Default Exp/Contr=0.3,0.1
English Units
Geom File=g01
Flow File=f01
Plan File=p01
BEGIN DESCRIPTION:
UNT 090 in La Jarita Watershed
END DESCRIPTION:

--- UNT 090 in La Jarita Watershed.p01 (plan) ---

Plan Title=Multiple Run
Short Identifier=Multiple
Geom File=g01
Flow File=f01
Subcritical Flow
K Sum by GR= 0
Std Step Tol= 0.01
Critical Tol= 0.01
Num of Std Step Trials= 20
Max Error Tol= 0.3
Flow Tol Ratio= 0.001
Split Flow NTrial= 30
Split Flow Tol= 0.02
Split Flow Ratio= 0.02
Log Output Level= 0
Friction Slope Method= 1
Unsteady Friction Slope Method= 2
Unsteady Bridges Friction Slope Method= 1
Parabolic Critical Depth
Global Vel Dist=  1 , 1 , 1
Global Log Level= 0
CheckData=True
Encroach Param= -1, 0, 0, 0
BEGIN DESCRIPTION:
Multiple Run
END DESCRIPTION:

--- UNT 090 in La Jarita Watershed.f01 (steady flow) ---

Flow Title=Multiple
Number of Profiles=7
Profile Names=10-year,25-year,50-year,1pct_min,100-year,1pct_plu,500-year
River Rch & RM= UNT 090 in La Ja,Reach-1,20777
     165     223     270     163     325     648     478
River Rch & RM= UNT 090 in La Ja,Reach-1,19142
     222     305     373     227     453     904     681
River Rch & RM= UNT 090 in La Ja,Reach-1,14793
     264     366     450     276     550    1098     836
River Rch & RM= UNT 090 in La Ja,Reach-1,9683
     351     493     612     379     755    1507    1167
River Rch & RM= UNT 090 in La Ja,Reach-1,7438
     382     539     670     415     828    1653    1285
Boundary for River Rch & Prof#=UNT 090 in La Ja,Reach-1,1
Up Type=0
Dn Type=3
Dn Slope=0.005
Boundary for River Rch & Prof#=UNT 090 in La Ja,Reach-1,2
Up Type=0
Dn Type=3
Dn Slope=0.005
Boundary for River Rch & Prof#=UNT 090 in La Ja,Reach-1,3
Up Type=0
Dn Type=3
Dn Slope=0.005
Boundary for River Rch & Prof#=UNT 090 in La Ja,Reach-1,4
Up Type=0
Dn Type=3
Dn Slope=0.005
Boundary for River Rch & Prof#=UNT 090 in La Ja,Reach-1,5
Up Type=0
Dn Type=3
Dn Slope=0.005
Boundary for River Rch & Prof#=UNT 090 in La Ja,Reach-1,6
Up Type=0
Dn Type=3
Dn Slope=0.005
Boundary for River Rch & Prof#=UNT 090 in La Ja,Reach-1,7
Up Type=0
Dn Type=3
Dn Slope=0.005

--- UNT 090 in La Jarita Watershed.g01 (geometry) ---

Geom Title=Existing Conditions

River Reach=UNT 090 in La Ja,Reach-1
Reach XY= 30
      2090830.80     13431764.54      2090830.80     13431454.54
      2091334.48     13430628.09      2091134.82     13429896.76
      2091210.80     13429054.54      2090930.80     13428444.54
      2091090.80     13427754.54      2090800.80     13427544.54
      2090970.80     13426544.54      2090730.09     13426198.84
      2090864.64     13425683.43      2090642.20     13425551.05
      2090758.30     13424877.23      2091040.80     13424614.54
      2091029.66     13423838.21      2091960.80     13423614.54
      2092040.80     13422954.54      2091844.32     13422522.33
      2091618.62     13422448.54      2091785.73     13421940.73
      2092714.54     13420878.45      2092319.58     13420068.99
      2092000.57     13420001.71      2091616.45     13419424.45
      2091902.91     13419183.57      2092164.41     13419266.03
      2093020.80     13418174.54      2093490.80     13418064.54
      2093440.80     13417474.54      2093725.00     13416875.00

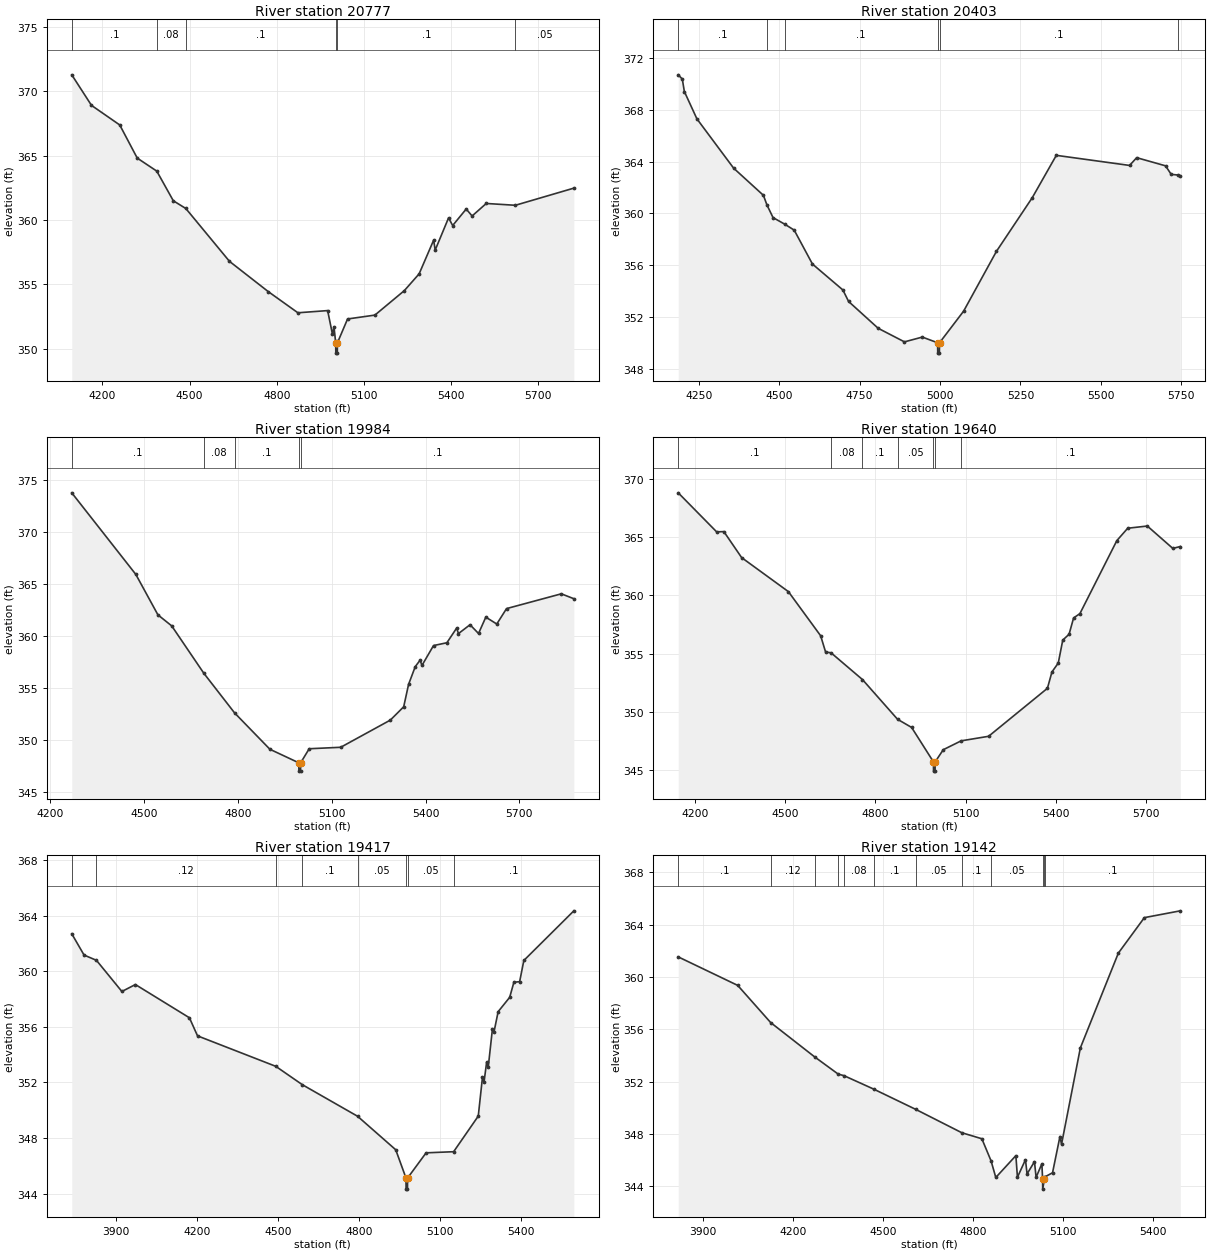
Type RM Length L Ch R = 1,20777,374,374,374
BEGIN DESCRIPTION:
UNT 090 in La Jarita Watershed 31.0
END DESCRIPTION:
XS GIS Cut Line= 3
      2091725.03     13431725.01      2090825.00     13431525.00
      2090029.65     13431659.94
#Sta/Elev= 30
  4094.2  371.26  4162.1  368.89  4259.4  367.37  4319.6  364.80  4386.9  363.79
  4443.8  361.49  4486.9  360.89  4637.2  356.79  4770.3  354.45  4872.8  352.80
  4975.2  352.97  4991.9  351.12  4997.0  351.72  5002.9  350.47  5003.4  349.67
  5008.4  349.67  5008.9  350.47  5043.8  352.32  5137.9  352.62  5239.3  354.52
  5290.2  355.82  5340.3  358.44  5345.4  357.66  5391.5  360.16  5405.7  359.57
  5452.3  360.85  5472.6  360.31  5521.3  361.28  5621.5  361.14  5822.9  362.47
#Mann=6,-1,0
  4094.2     0.1       0  4386.9    0.08       0  4486.9     0.1       0
  5002.9    0.07       0  5008.9     0.1       0  5621.5    0.05       0
Bank Sta=5002.9,5008.9
Exp/Cntr=0.3,0.1

Type RM Length L Ch R = 1,20403,419,419,419
BEGIN DESCRIPTION:
Mapping XS 4834739d
END DESCRIPTION:
XS GIS Cut Line= 3
      2091773.57     13431382.32      2090757.91     13431173.98
      2090281.53     13431390.51
#Sta/Elev= 30
  4186.6  370.71  4199.3  370.38  4205.6  369.42  4244.6  367.31  4358.7  363.50
  4451.3  361.40  4462.2  360.66  4481.2  359.68  4517.0  359.18  4547.0  358.71
  4603.7  356.09  4698.2  354.09  4716.0  353.20  4807.8  351.13  4889.5  350.08
  4945.1  350.45  4992.5  350.01  4993.0  349.21  4998.0  349.21  4998.5  350.01
  5073.3  352.45  5175.3  357.07  5286.7  361.22  5361.4  364.49  5589.1  363.71
  5611.1  364.31  5700.8  363.68  5718.4  363.02  5739.3  362.97  5746.7  362.91
#Mann=6,-1,0
  4186.6     0.1       0  4462.2    0.08       0  4517.0     0.1       0
  4992.5    0.07       0  4998.5     0.1       0  5739.3    0.05       0
Bank Sta=4992.5,4998.5
Exp/Cntr=0.3,0.1

Type RM Length L Ch R = 1,19984,344,344,344
BEGIN DESCRIPTION:
Mapping XS ad487b26
END DESCRIPTION:
XS GIS Cut Line= 3
      2091978.37     13431000.36      2091040.89     13430880.58
      2090473.17     13431219.13
#Sta/Elev= 30
  4268.2  373.77  4473.2  365.93  4543.8  362.05  4587.9  360.99  4690.4  356.45
  4789.1  352.63  4902.0  349.14  4994.4  347.84  4994.9  347.04  4999.9  347.04
  5000.4  347.84  5027.7  349.19  5128.5  349.33  5287.2  351.94  5330.0  353.22
  5345.6  355.37  5367.0  357.08  5382.6  357.70  5388.4  357.19  5425.4  359.10
  5468.2  359.37  5499.4  360.78  5505.2  360.25  5542.2  361.10  5569.4  360.26
  5592.7  361.83  5627.8  361.17  5659.0  362.65  5834.2  364.07  5874.3  363.60
#Mann=5,-1,0
  4268.2     0.1       0  4690.4    0.08       0  4789.1     0.1       0
  4994.4    0.07       0  5000.4     0.1       0
Bank Sta=4994.4,5000.4
Exp/Cntr=0.3,0.1

Type RM Length L Ch R = 1,19640,223,223,223
BEGIN DESCRIPTION:
Mapping XS 9c2f31ad
END DESCRIPTION:
XS GIS Cut Line= 4
      2092139.86     13430797.25      2091546.10     13430557.66
      2091087.77     13430599.33      2090613.80     13430917.04
#Sta/Elev= 30
  4143.6  368.80  4271.4  365.45  4295.5  365.47  4354.6  363.24  4510.2  360.32
  4617.6  356.53  4634.1  355.13  4652.1  355.07  4756.8  352.77  4873.6  349.36
  4920.4  348.66  4992.9  345.71  4993.4  344.91  4998.4  344.91  4998.9  345.71
  5025.8  346.75  5085.3  347.51  5176.6  347.90  5372.4  352.02  5387.4  353.42
  5408.5  354.19  5423.5  356.16  5444.5  356.66  5459.5  358.06  5480.5  358.43
  5603.5  364.70  5639.6  365.76  5704.9  365.95  5789.7  364.03  5814.7  364.19
#Mann=7,-1,0
  4143.6     0.1       0  4652.1    0.08       0  4756.8     0.1       0
  4873.6    0.05       0  4992.9   0.033       0  4998.9    0.05       0
  5085.3     0.1       0
Bank Sta=4992.9,4998.9
Exp/Cntr=0.3,0.1

Type RM Length L Ch R = 1,19417,275,275,275
BEGIN DESCRIPTION:
Mapping XS 03acb3fc
END DESCRIPTION:
XS GIS Cut Line= 4
      2092530.48     13430323.28      2091499.23     13430318.08
      2091082.56     13430406.62      2090739.40     13430614.59
#Sta/Elev= 30
  3737.6  362.69  3783.1  361.16  3829.0  360.78  3923.1  358.54  3973.1  359.04
  4173.1  356.65  4203.1  355.35  4492.7  353.16  4591.0  351.84  4795.5  349.57
  4936.8  347.16  4974.7  345.13  4975.2  344.33  4980.2  344.33  4980.7  345.13
  5049.2  346.94  5151.1  347.02  5242.3  349.58  5257.8  352.36  5263.6  352.02
  5273.3  353.46  5279.1  353.08  5294.6  355.82  5300.5  355.63  5315.9  357.09
  5358.6  358.12  5374.1  359.20  5395.5  359.25  5411.0  360.77  5596.1  364.34
#Mann=8,-1,0
  3737.6     0.1       0  3829.0    0.12       0  4492.7    0.08       0
  4591.0     0.1       0  4795.5    0.05       0  4974.7   0.033       0
  4980.7    0.05       0  5151.1     0.1       0
Bank Sta=4974.7,4980.7
Exp/Cntr=0.3,0.1

Type RM Length L Ch R = 1,19142,51,51,51
BEGIN DESCRIPTION:
Mapping XS 4b679231
END DESCRIPTION:
XS GIS Cut Line= 6
      2092333.25     13430152.29      2091617.13     13430152.29
      2091495.60     13430087.19      2091395.78     13430048.12
      2091213.48     13430095.87      2090719.34     13430269.26
#Sta/Elev= 30
  3818.5  361.54  4016.8  359.36  4126.6  356.52  4273.0  353.90  4351.7  352.58
  4371.2  352.46  4469.5  351.44  4610.6  349.88  4763.7  348.10  4830.5  347.64
  4861.2  345.95  4877.0  344.68  4943.9  346.35  4949.1  344.70  4975.9  346.04
  4981.2  344.95  5005.9  345.89  5011.3  344.69  5030.6  345.73  5032.9  344.59
  5033.4  343.79  5039.0  344.59  5041.7  344.74  5066.1  345.04  5090.8  347.81
  5096.1  347.22  5158.8  354.58  5285.5  361.83  5372.2  364.54  5492.0  365.06
#Mann=12,-1,0
  3818.5     0.1       0  4126.6    0.12       0  4273.0     0.1       0
  4351.7    0.12       0  4371.2    0.08       0  4469.5     0.1       0
  4610.6    0.05       0  4763.7     0.1       0  4861.2    0.05       0
  5032.9   0.033       0  5039.0    0.05       0  5041.7     0.1       0
Bank Sta=5032.9,5039
Exp/Cntr=0.3,0.1

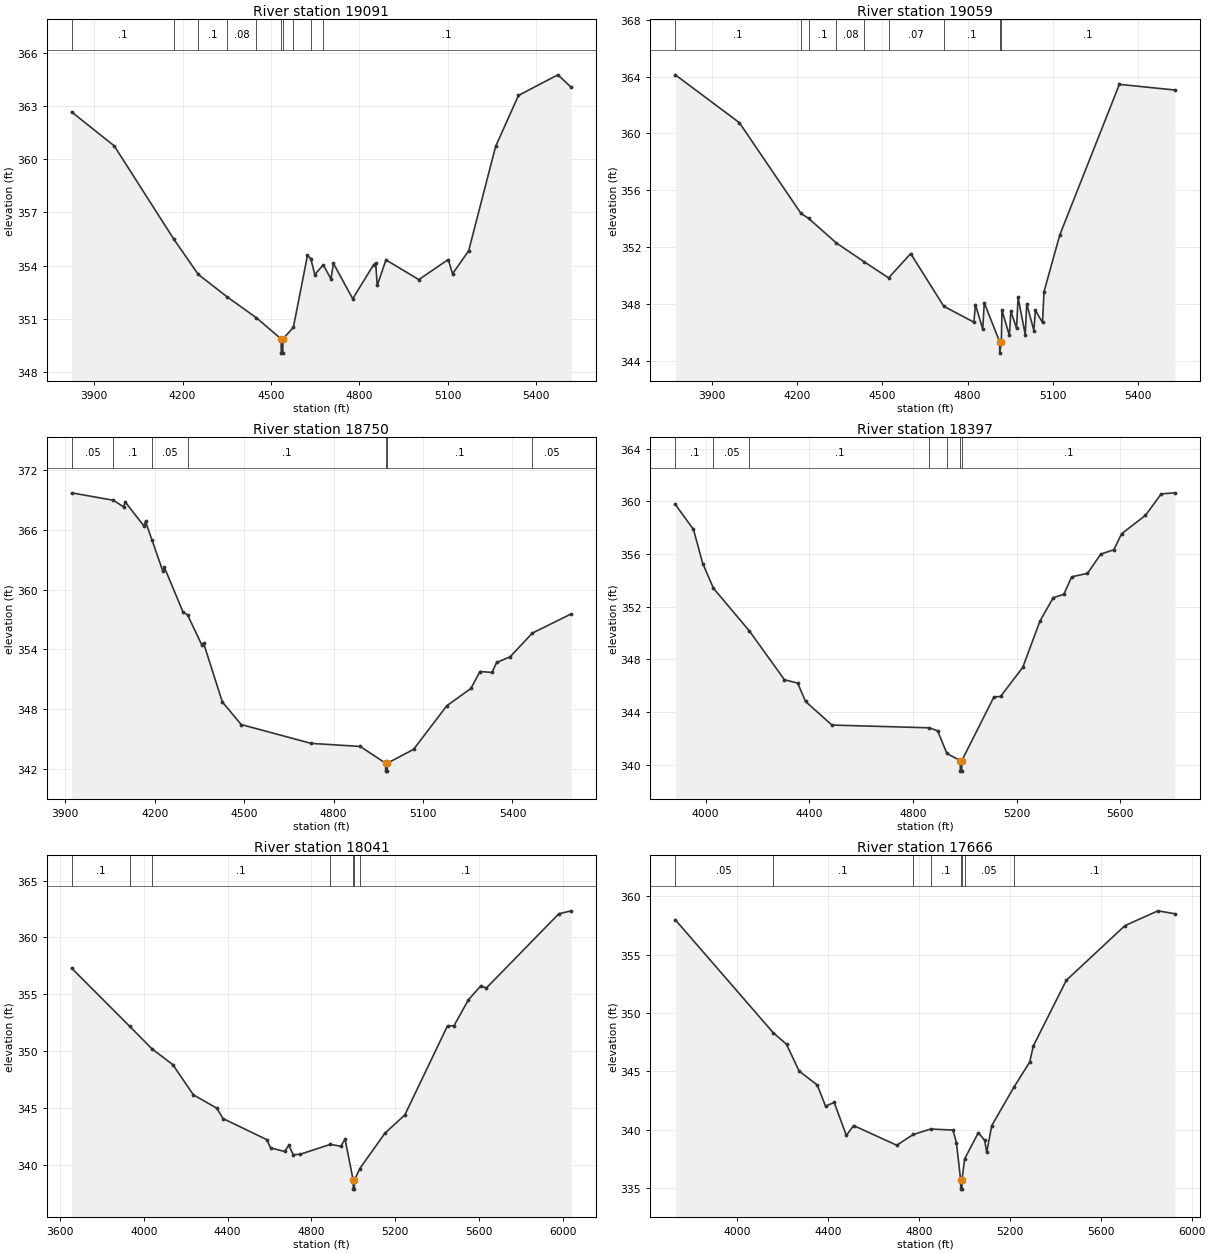
Type RM Length L Ch R = 1,19091,32,32,32
BEGIN DESCRIPTION:
Mapping XS 8072b762
END DESCRIPTION:
XS GIS Cut Line= 6
      2092309.38     13430100.21      2091634.49     13430119.74
      2091541.17     13430052.47      2091450.03     13430017.74
      2091348.03     13430009.06      2090686.10     13430245.62
#Sta/Elev= 30
  3824.1  362.66  3968.5  360.75  4171.2  355.48  4253.6  353.51  4352.0  352.24
  4450.5  351.07  4534.4  349.88  4534.9  349.08  4540.0  349.08  4540.5  349.88
  4575.9  350.53  4623.7  354.58  4635.2  354.39  4648.5  353.50  4677.1  354.05
  4703.3  353.26  4711.8  354.13  4777.1  352.14  4848.4  354.07  4855.1  354.13
  4860.3  352.89  4889.8  354.33  5001.3  353.22  5100.9  354.35  5115.7  353.55
  5170.2  354.84  5261.7  360.72  5339.1  363.59  5472.7  364.75  5517.9  364.05
#Mann=10,-1,0
  3824.1     0.1       0  4171.2    0.12       0  4253.6     0.1       0
  4352.0    0.08       0  4450.5     0.1       0  4534.4    0.07       0
  4540.5     0.1       0  4575.9    0.05       0  4635.2    0.07       0
  4677.1     0.1       0
Bank Sta=4534.4,4540.5
Exp/Cntr=0.3,0.1

Type RM Length L Ch R = 1,19059,309,309,309
BEGIN DESCRIPTION:
Mapping XS d74859f2
END DESCRIPTION:
XS GIS Cut Line= 6
      2092350.59     13430061.15      2091664.87     13430080.68
      2091571.56     13430026.42      2091463.05     13429970.00
      2091330.67     13429967.83      2090661.34     13430210.43
#Sta/Elev= 30
  3770.2  364.12  3995.9  360.75  4213.0  354.36  4239.8  354.01  4338.2  352.27
  4436.6  350.94  4521.8  349.82  4599.7  351.53  4716.3  347.82  4822.5  346.70
  4827.8  347.94  4853.7  346.21  4859.0  348.07  4913.1  345.32  4913.6  344.52
  4919.2  345.32  4921.5  347.53  4947.4  345.77  4952.7  347.47  4972.8  346.27
  4978.2  348.44  5003.3  345.83  5008.6  348.00  5033.8  346.11  5039.1  347.53
  5064.3  346.68  5069.6  348.85  5125.3  352.85  5335.2  363.45  5530.8  363.05
#Mann=9,-1,0
  3770.2     0.1       0  4213.0    0.12       0  4239.8     0.1       0
  4338.2    0.08       0  4436.6     0.1       0  4521.8    0.07       0
  4716.3     0.1       0  4913.1    0.07       0  4919.2     0.1       0
Bank Sta=4913.1,4919.2
Exp/Cntr=0.3,0.1

Type RM Length L Ch R = 1,18750,353,353,353
BEGIN DESCRIPTION:
Mapping XS 02b9cbd0
END DESCRIPTION:
XS GIS Cut Line= 2
      2092238.83     13429562.86      2090582.58     13429818.07
#Sta/Elev= 30
  3921.3  369.72  4061.6  368.97  4095.8  368.30  4100.9  368.81  4164.0  366.38
  4169.1  366.85  4190.8  364.98  4227.2  361.85  4232.3  362.24  4295.5  357.70
  4310.1  357.46  4358.7  354.38  4363.7  354.63  4426.9  348.70  4490.1  346.43
  4724.5  344.54  4889.4  344.23  4974.3  342.55  4974.8  341.75  4980.0  341.75
  4980.5  342.55  5068.5  343.94  5179.8  348.32  5260.8  350.06  5291.1  351.76
  5331.6  351.67  5346.9  352.67  5392.3  353.24  5466.6  355.62  5597.1  357.55
#Mann=7,-1,0
  3921.3    0.05       0  4061.6     0.1       0  4190.8    0.05       0
  4310.1     0.1       0  4974.3    0.07       0  4980.5     0.1       0
  5466.6    0.05       0
Bank Sta=4974.3,4980.5
Exp/Cntr=0.3,0.1

Type RM Length L Ch R = 1,18397,356,356,356
BEGIN DESCRIPTION:
Mapping XS fa55e9cc
END DESCRIPTION:
XS GIS Cut Line= 2
      2092249.25     13429177.45      2090353.39     13429526.41
#Sta/Elev= 30
  3883.1  359.77  3953.0  357.87  3989.1  355.27  4030.3  353.40  4169.2  350.15
  4304.3  346.45  4355.1  346.20  4385.6  344.80  4487.3  343.01  4863.7  342.80
  4895.3  342.57  4931.0  340.85  4982.5  340.31  4983.0  339.51  4988.2  339.51
  4988.7  340.31  5112.6  345.15  5138.1  345.18  5223.7  347.39  5290.6  350.93
  5341.4  352.68  5382.1  352.94  5412.6  354.27  5473.6  354.53  5524.5  355.99
  5575.3  356.33  5605.2  357.54  5697.3  358.94  5758.3  360.57  5810.8  360.65
#Mann=7,-1,0
  3883.1     0.1       0  4030.3    0.05       0  4169.2     0.1       0
  4863.7    0.12       0  4931.0     0.1       0  4982.5    0.07       0
  4988.7     0.1       0
Bank Sta=4982.5,4988.7
Exp/Cntr=0.3,0.1

Type RM Length L Ch R = 1,18041,375,375,375
BEGIN DESCRIPTION:
Mapping XS da78df6e
END DESCRIPTION:
XS GIS Cut Line= 4
      2092478.43     13428620.14      2091431.52     13429005.58
      2090671.10     13429156.62      2090243.98     13429406.64
#Sta/Elev= 30
  3655.0  357.30  3932.8  352.18  4038.7  350.21  4138.2  348.82  4236.4  346.17
  4347.6  345.00  4378.1  344.08  4585.9  342.24  4605.7  341.50  4672.0  341.19
  4691.8  341.73  4713.6  340.91  4745.6  340.94  4890.8  341.81  4940.4  341.65
  4960.8  342.27  4999.5  338.68  5000.0  337.88  5005.2  337.88  5005.7  338.68
  5031.3  339.69  5151.0  342.79  5246.2  344.40  5450.2  352.24  5480.7  352.23
  5549.9  354.52  5608.5  355.73  5635.8  355.56  5981.7  362.08  6040.8  362.34
#Mann=7,-1,0
  3655.0     0.1       0  3932.8    0.05       0  4038.7     0.1       0
  4890.8    0.12       0  4999.5    0.07       0  5005.7    0.12       0
  5031.3     0.1       0
Bank Sta=4999.5,5005.7
Exp/Cntr=0.3,0.1

Type RM Length L Ch R = 1,17666,384,384,384
BEGIN DESCRIPTION:
Mapping XS 362b2914
END DESCRIPTION:
XS GIS Cut Line= 3
      2092290.93     13428271.19      2091134.64     13428698.28
      2090296.13     13429177.43
#Sta/Elev= 30
  3727.8  357.99  4157.8  348.33  4217.1  347.32  4272.6  345.03  4352.4  343.83
  4389.0  342.02  4427.0  342.34  4480.3  339.51  4512.3  340.36  4702.3  338.67
  4775.6  339.60  4851.7  340.06  4949.4  339.97  4964.8  338.90  4983.3  335.71
  4983.8  334.91  4989.1  334.91  4989.6  335.71  5000.6  337.49  5061.3  339.75
  5088.7  339.10  5098.2  338.07  5120.3  340.36  5217.0  343.62  5287.3  345.80
  5303.2  347.18  5448.6  352.81  5706.3  357.49  5851.7  358.76  5926.2  358.51
#Mann=8,-1,0
  3727.8    0.05       0  4157.8     0.1       0  4775.6    0.05       0
  4851.7     0.1       0  4983.3    0.07       0  4989.6     0.1       0
  5000.6    0.05       0  5217.0     0.1       0
Bank Sta=4983.3,4989.6
Exp/Cntr=0.3,0.1

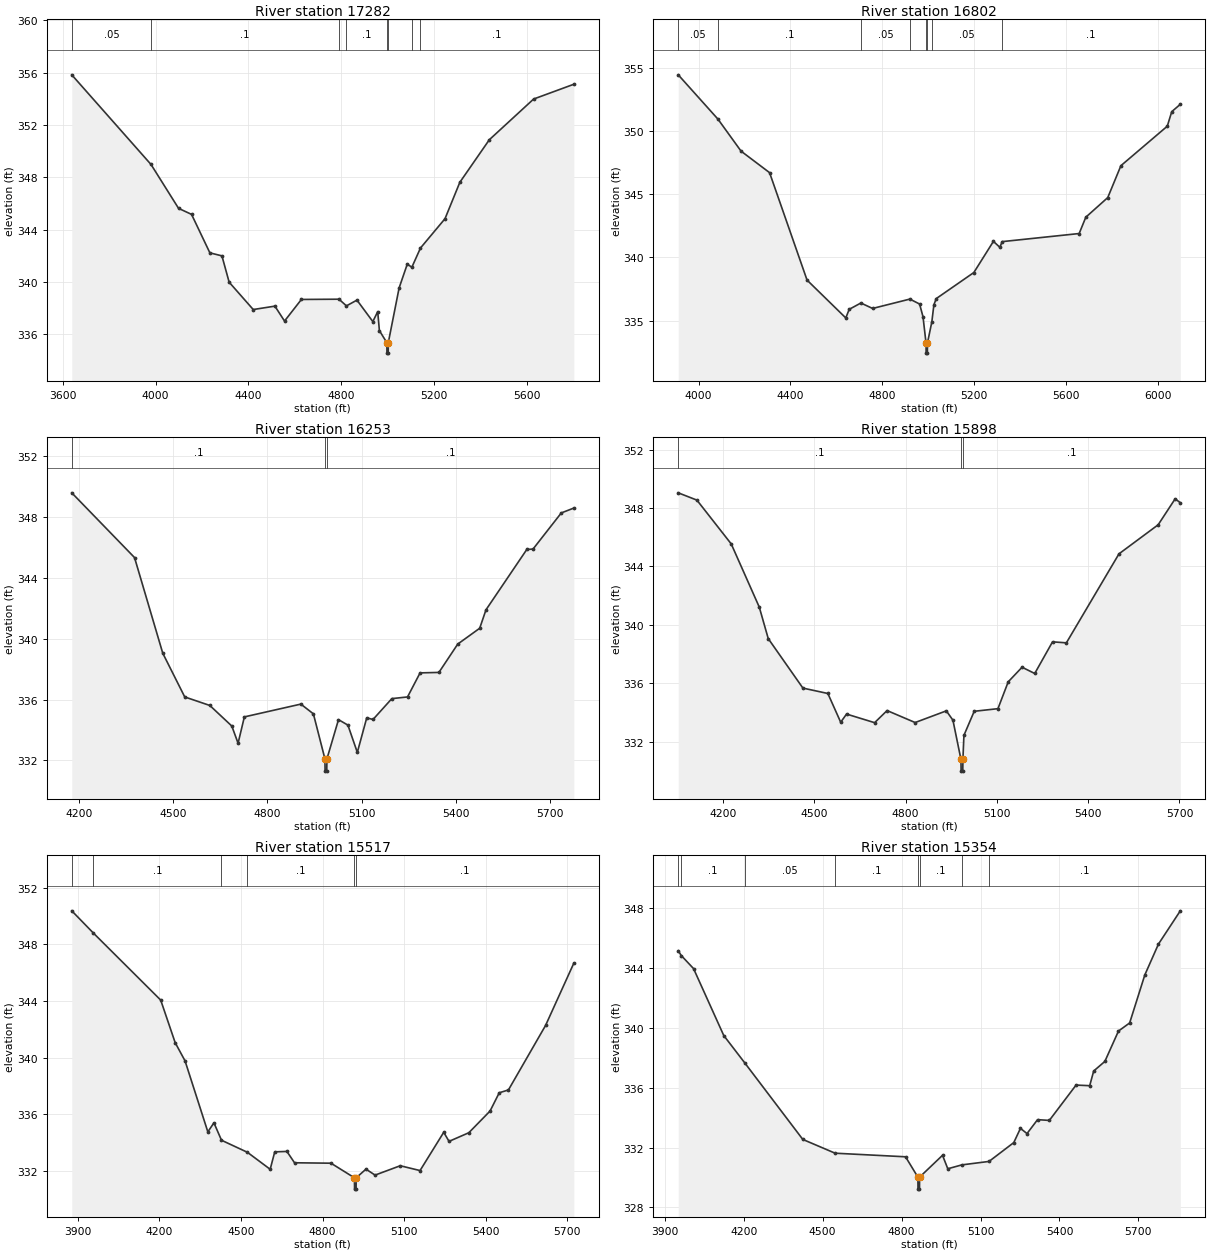
Type RM Length L Ch R = 1,17282,480,480,480
BEGIN DESCRIPTION:
UNT 090 in La Jarita Watershed 19.0
END DESCRIPTION:
XS GIS Cut Line= 3
      2092228.42     13428042.03      2090973.18     13428390.99
      2090349.06     13428983.91
#Sta/Elev= 30
  3638.7  355.83  3980.3  348.98  4098.9  345.63  4154.9  345.17  4233.9  342.23
  4285.8  342.00  4316.9  339.99  4420.7  337.90  4514.1  338.16  4555.6  337.02
  4628.3  338.67  4790.3  338.69  4822.4  338.18  4867.7  338.62  4936.1  336.98
  4957.2  337.74  4964.4  336.29  4996.5  335.37  4997.0  334.57  5002.3  334.57
  5002.8  335.37  5049.4  339.55  5084.6  341.37  5104.3  341.13  5141.5  342.60
  5247.2  344.84  5311.1  347.62  5438.1  350.87  5629.0  353.98  5802.4  355.11
#Mann=8,-1,0
  3638.7    0.05       0  3980.3     0.1       0  4790.3    0.05       0
  4822.4     0.1       0  4996.5    0.07       0  5002.8     0.1       0
  5104.3    0.05       0  5141.5     0.1       0
Bank Sta=4996.5,5002.8
Exp/Cntr=0.3,0.1

Type RM Length L Ch R = 1,16802,549,549,549
BEGIN DESCRIPTION:
UNT 090 in La Jarita Watershed 18.0
END DESCRIPTION:
XS GIS Cut Line= 3
      2092024.99     13427825.00      2091030.48     13428026.41
      2089900.29     13428338.90
#Sta/Elev= 30
  3911.4  354.43  4084.4  350.93  4185.1  348.40  4309.3  346.70  4472.6  338.21
  4641.4  335.22  4656.2  335.90  4707.0  336.40  4758.2  335.97  4920.5  336.71
  4962.9  336.32  4977.8  335.31  4990.9  333.24  4991.4  332.44  4996.7  332.44
  4997.2  333.24  5016.2  334.91  5025.2  336.26  5035.5  336.75  5199.3  338.81
  5284.5  341.27  5312.6  340.80  5322.6  341.25  5658.1  341.89  5687.0  343.18
  5782.6  344.73  5839.9  347.25  6041.9  350.37  6061.4  351.52  6098.7  352.10
#Mann=8,-1,0
  3911.4    0.05       0  4084.4     0.1       0  4707.0    0.05       0
  4920.5     0.1       0  4990.9    0.07       0  4997.2     0.1       0
  5016.2    0.05       0  5322.6     0.1       0
Bank Sta=4990.9,4997.2
Exp/Cntr=0.3,0.1

Type RM Length L Ch R = 1,16253,355,355,355
BEGIN DESCRIPTION:
UNT 090 in La Jarita Watershed 17.0
END DESCRIPTION:
XS GIS Cut Line= 3
      2091774.96     13427675.00      2090975.00     13427675.00
      2090174.96     13427675.00
#Sta/Elev= 30
  4176.3  349.57  4376.3  345.32  4466.3  339.04  4536.3  336.17  4616.3  335.61
  4686.3  334.26  4706.3  333.13  4726.3  334.86  4906.3  335.70  4946.3  335.06
  4983.1  332.10  4983.6  331.30  4988.9  331.30  4989.4  332.10  5026.3  334.68
  5056.3  334.32  5086.3  332.53  5116.3  334.80  5136.3  334.69  5196.3  336.06
  5246.3  336.17  5286.3  337.75  5346.3  337.78  5406.3  339.64  5476.3  340.68
  5496.3  341.89  5626.3  345.85  5646.3  345.88  5736.3  348.25  5776.3  348.57
#Mann=3,-1,0
  4176.3     0.1       0  4983.1    0.07       0  4989.4     0.1       0
Bank Sta=4983.1,4989.4
Exp/Cntr=0.3,0.1

Type RM Length L Ch R = 1,15898,381,381,381
BEGIN DESCRIPTION:
UNT 090 in La Jarita Watershed 16.0
END DESCRIPTION:
XS GIS Cut Line= 3
      2091774.98     13427624.99      2090875.00     13427425.00
      2090175.04     13427624.99
#Sta/Elev= 30
  4052.9  349.04  4114.3  348.54  4227.0  345.54  4319.2  341.21  4348.7  339.05
  4462.6  335.66  4544.6  335.29  4586.8  333.32  4606.0  333.88  4698.2  333.29
  4739.2  334.12  4831.4  333.30  4933.9  334.10  4955.6  333.46  4982.0  330.77
  4982.5  329.97  4987.9  329.97  4988.4  330.77  4991.7  332.42  5025.5  334.07
  5103.5  334.25  5137.3  336.09  5182.8  337.09  5224.4  336.66  5282.9  338.83
  5328.4  338.76  5501.3  344.86  5630.0  346.85  5685.9  348.63  5702.8  348.36
#Mann=3,-1,0
  4052.9     0.1       0  4982.0    0.07       0  4988.4     0.1       0
Bank Sta=4982,4988.4
Exp/Cntr=0.3,0.1

Type RM Length L Ch R = 1,15517,163,163,163
BEGIN DESCRIPTION:
UNT 090 in La Jarita Watershed 15.0
END DESCRIPTION:
XS GIS Cut Line= 3
      2091875.00     13427575.00      2090875.00     13427075.00
      2090175.04     13427274.99
#Sta/Elev= 30
  3877.6  350.37  3956.6  348.81  4204.6  344.07  4257.7  341.07  4294.1  339.78
  4377.9  334.77  4400.3  335.41  4428.1  334.18  4523.3  333.33  4607.1  332.13
  4623.9  333.36  4668.6  333.39  4696.6  332.59  4830.7  332.56  4916.9  331.53
  4917.4  330.73  4922.9  330.73  4923.4  331.53  4959.3  332.14  4992.8  331.72
  5085.3  332.38  5158.1  332.04  5245.2  334.74  5264.7  334.10  5337.5  334.71
  5415.5  336.24  5449.3  337.53  5483.1  337.73  5619.6  342.28  5723.6  346.68
#Mann=6,-1,0
  3877.6    0.05       0  3956.6     0.1       0  4428.1    0.05       0
  4523.3     0.1       0  4916.9    0.07       0  4923.4     0.1       0
Bank Sta=4916.9,4923.4
Exp/Cntr=0.3,0.1

Type RM Length L Ch R = 1,15354,561,561,561
BEGIN DESCRIPTION:
Mapping XS 57ef1359
END DESCRIPTION:
XS GIS Cut Line= 4
      2091827.33     13427224.31      2091379.43     13426890.99
      2090530.48     13426958.70      2090109.28     13427223.90
#Sta/Elev= 30
  3951.5  345.14  3963.2  344.82  4009.7  343.95  4124.5  339.48  4204.4  337.65
  4424.8  332.54  4547.6  331.62  4815.2  331.38  4862.1  330.02  4862.6  329.22
  4868.1  329.22  4868.6  330.02  4955.7  331.48  4975.7  330.58  5029.2  330.84
  5132.4  331.07  5226.5  332.33  5251.8  333.28  5276.7  332.93  5316.8  333.86
  5361.5  333.81  5463.1  336.17  5514.9  336.13  5530.1  337.11  5572.5  337.75
  5624.3  339.78  5666.7  340.32  5724.4  343.53  5776.2  345.59  5859.2  347.81
#Mann=8,-1,0
  3951.5    0.05       0  3963.2     0.1       0  4204.4    0.05       0
  4547.6     0.1       0  4862.1    0.07       0  4868.6     0.1       0
  5029.2    0.08       0  5132.4     0.1       0
Bank Sta=4862.1,4868.6
Exp/Cntr=0.3,0.1

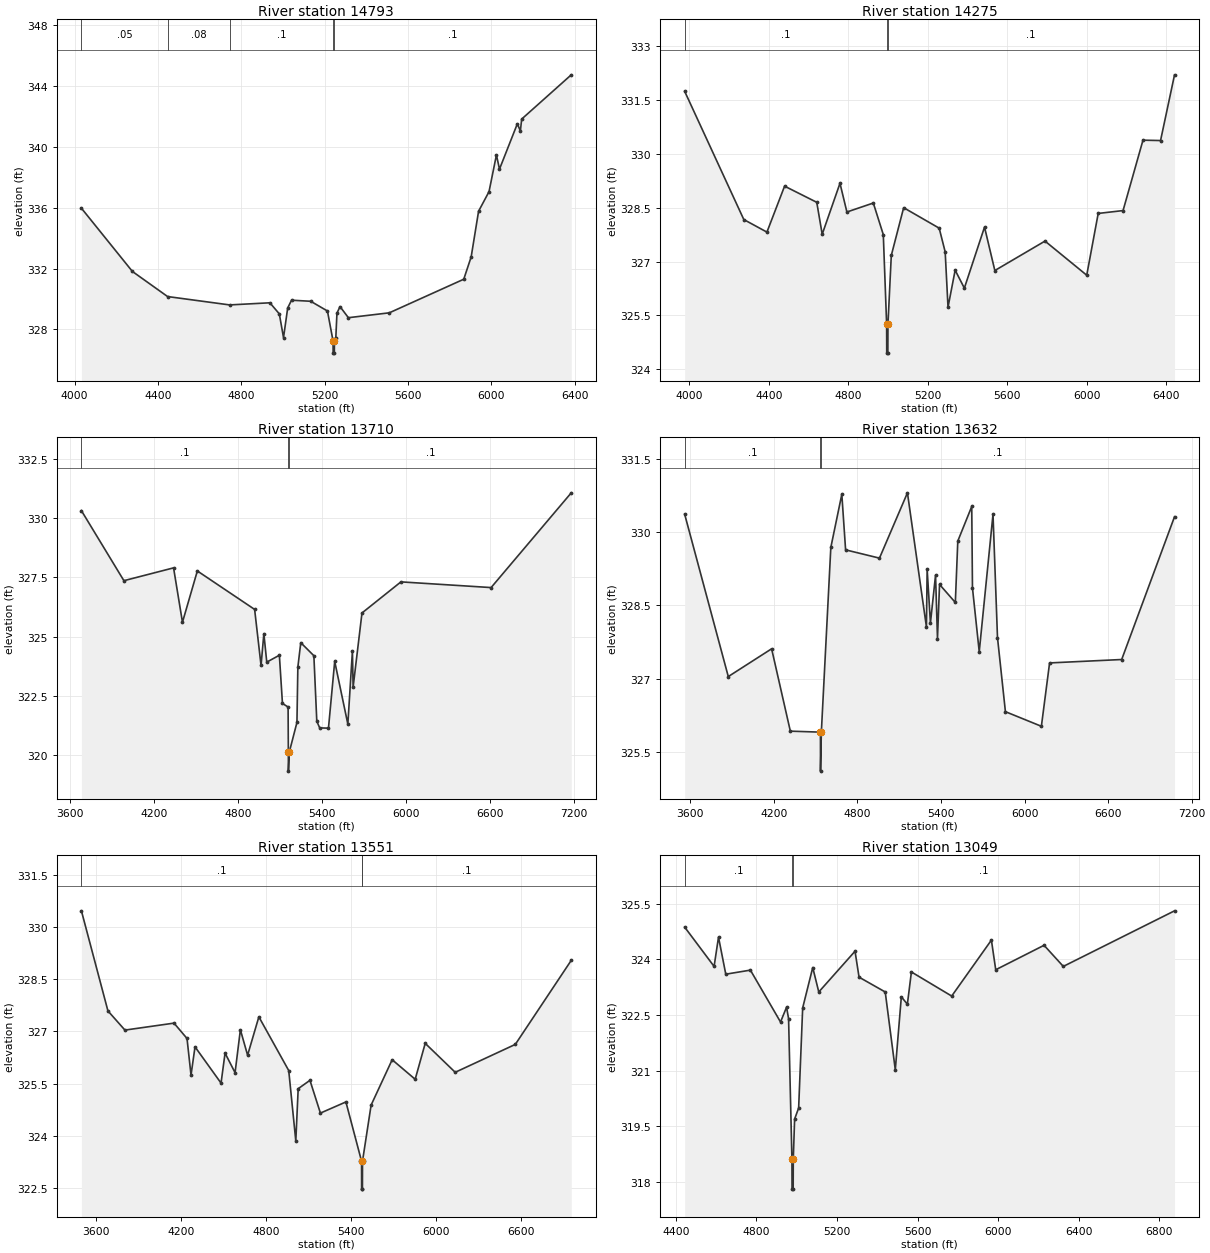
Type RM Length L Ch R = 1,14793,518,518,518
BEGIN DESCRIPTION:
UNT 090 in La Jarita Watershed 12.0
END DESCRIPTION:
XS GIS Cut Line= 4
      2091790.88     13426708.70      2091004.43     13426443.08
      2090447.14     13426495.16      2089671.13     13427062.85
#Sta/Elev= 30
  4032.3  335.97  4277.1  331.81  4446.0  330.16  4743.8  329.61  4937.0  329.75
  4982.3  329.02  5002.4  327.46  5022.5  329.41  5040.9  329.92  5133.0  329.85
  5213.3  329.21  5240.2  327.24  5240.7  326.44  5246.3  326.44  5246.8  327.24
  5253.5  327.45  5258.9  329.07  5273.6  329.50  5313.8  328.77  5510.1  329.09
  5867.6  331.30  5903.2  332.77  5938.7  335.77  5988.9  337.06  6024.4  339.47
  6039.1  338.54  6124.8  341.52  6139.4  341.05  6145.6  341.83  6383.6  344.74
#Mann=5,-1,0
  4032.3    0.05       0  4446.0    0.08       0  4743.8     0.1       0
  5240.2    0.07       0  5246.8     0.1       0
Bank Sta=5240.2,5246.8
Exp/Cntr=0.3,0.1

Type RM Length L Ch R = 1,14275,565,565,565
BEGIN DESCRIPTION:
Mapping XS dadca8fd
END DESCRIPTION:
XS GIS Cut Line= 4
      2091775.28     13426448.29      2091046.10     13426036.83
      2090520.06     13426083.70      2089588.90     13426666.32
#Sta/Elev= 30
  3976.7  331.74  4274.1  328.17  4390.4  327.82  4479.2  329.10  4641.0  328.65
  4668.4  327.76  4757.8  329.18  4792.6  328.38  4925.5  328.63  4975.7  327.75
  4992.5  325.25  4993.0  324.45  4998.6  324.45  4999.1  325.25  5015.9  327.17
  5078.1  328.50  5256.8  327.93  5286.9  327.27  5301.2  325.73  5337.1  326.76
  5383.4  326.26  5484.8  327.96  5536.7  326.75  5789.0  327.57  5998.9  326.62
  6056.6  328.34  6181.6  328.42  6281.8  330.38  6370.2  330.37  6440.5  332.20
#Mann=3,-1,0
  3976.7     0.1       0  4992.5    0.07       0  4999.1     0.1       0
Bank Sta=4992.5,4999.1
Exp/Cntr=0.3,0.1

Type RM Length L Ch R = 1,13710,78,78,78
BEGIN DESCRIPTION:
Mapping XS 403ee585
END DESCRIPTION:
XS GIS Cut Line= 6
      2091770.92     13426358.00      2090994.02     13425676.58
      2090507.91     13425698.28      2090364.68     13425559.40
      2090303.91     13425976.06      2089175.51     13426640.08
#Sta/Elev= 30
  3682.8  330.31  3986.5  327.36  4341.4  327.90  4405.0  325.61  4511.3  327.77
  4920.7  326.15  4966.6  323.79  4986.7  325.13  5007.4  323.93  5097.5  324.22
  5119.6  322.19  5159.9  322.04  5161.7  320.14  5162.2  319.34  5168.3  320.14
  5223.1  321.39  5229.6  323.72  5250.5  324.75  5344.1  324.20  5365.0  321.44
  5385.8  321.16  5448.4  321.15  5493.0  323.96  5586.9  321.32  5619.6  324.40
  5624.6  322.88  5687.9  326.00  5966.2  327.31  6610.6  327.07  7183.5  331.06
#Mann=3,-1,0
  3682.8     0.1       0  5161.7    0.07       0  5168.3     0.1       0
Bank Sta=5161.7,5168.3
Exp/Cntr=0.3,0.1

Type RM Length L Ch R = 1,13632,81,81,81
BEGIN DESCRIPTION:
Mapping XS 48c626ca
END DESCRIPTION:
XS GIS Cut Line= 6
      2091810.00     13426342.39      2090994.02     13425595.85
      2090570.41     13425623.63      2090351.66     13425502.10
      2090250.96     13425859.74      2089174.61     13426592.36
#Sta/Elev= 30
  3559.1  330.37  3872.2  327.04  4183.4  327.61  4317.8  325.92  4533.9  325.90
  4534.4  325.10  4540.5  325.90  4608.6  329.69  4687.5  330.78  4714.6  329.64
  4957.8  329.47  5158.7  330.81  5295.0  328.06  5300.2  329.24  5323.8  328.14
  5360.5  329.12  5374.4  327.82  5389.2  328.93  5502.6  328.56  5520.3  329.82
  5620.4  330.53  5625.6  328.86  5674.2  327.55  5773.1  330.37  5805.3  327.84
  5862.2  326.32  6120.5  326.02  6179.4  327.32  6697.1  327.39  7076.6  330.32
#Mann=3,-1,0
  3559.1     0.1       0  4533.9    0.07       0  4540.5     0.1       0
Bank Sta=4533.9,4540.5
Exp/Cntr=0.3,0.1

Type RM Length L Ch R = 1,13551,502,502,502
BEGIN DESCRIPTION:
Mapping XS a5d352af
END DESCRIPTION:
XS GIS Cut Line= 6
      2091823.01     13426331.96      2091046.10     13425563.74
      2090954.96     13425520.33      2090616.41     13425537.69
      2090382.04     13425416.17      2089171.93     13426530.82
#Sta/Elev= 30
  3496.2  330.46  3683.6  327.59  3803.7  327.04  4150.3  327.24  4242.2  326.80
  4270.5  325.75  4298.7  326.56  4482.6  325.52  4510.9  326.38  4581.6  325.82
  4619.2  327.05  4670.2  326.32  4749.7  327.42  4960.7  325.88  5010.7  323.86
  5027.5  325.36  5110.6  325.60  5184.5  324.66  5364.6  324.98  5475.2  323.28
  5475.7  322.48  5481.3  322.48  5481.8  323.28  5542.7  324.89  5691.4  326.19
  5854.0  325.63  5924.8  326.66  6136.7  325.83  6561.3  326.63  6956.5  329.04
#Mann=3,-1,0
  3496.2     0.1       0  5475.2    0.07       0  5481.8     0.1       0
Bank Sta=5475.2,5481.8
Exp/Cntr=0.3,0.1

Type RM Length L Ch R = 1,13049,326,326,326
BEGIN DESCRIPTION:
Mapping XS 0ef3083d
END DESCRIPTION:
XS GIS Cut Line= 4
      2091284.79     13425338.89      2090956.69     13425120.16
      2090097.32     13425120.16      2089081.68     13425719.12
#Sta/Elev= 30
  4443.7  324.87  4589.8  323.81  4611.7  324.60  4647.8  323.60  4770.1  323.71
  4919.7  322.31  4949.7  322.71  4959.7  322.40  4976.4  318.60  4976.9  317.80
  4982.5  317.80  4983.0  318.60  4989.7  319.69  5009.7  319.99  5029.7  322.69
  5079.7  323.78  5109.7  323.12  5289.7  324.22  5309.7  323.52  5439.7  323.12
  5489.7  321.02  5519.7  322.99  5549.7  322.79  5569.7  323.66  5769.8  323.01
  5967.0  324.52  5988.5  323.72  6228.5  324.38  6324.1  323.81  6876.5  325.31
#Mann=3,-1,0
  4443.7     0.1       0  4976.4    0.07       0  4983.0     0.1       0
Bank Sta=4976.4,4983
Exp/Cntr=0.3,0.1

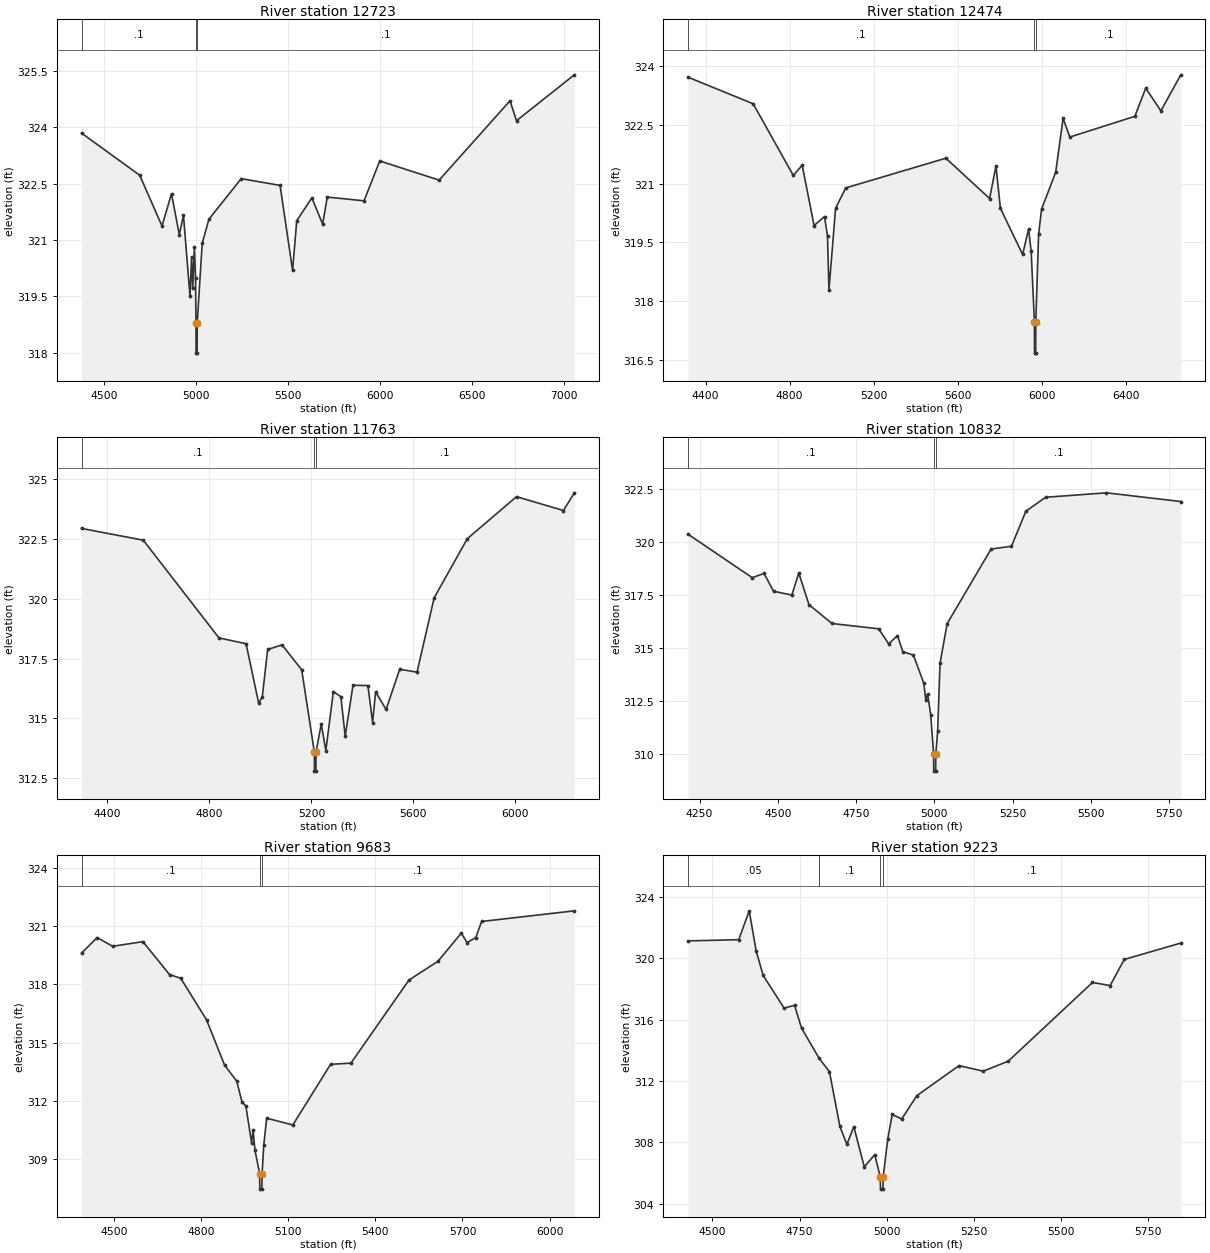
Type RM Length L Ch R = 1,12723,249,249,249
BEGIN DESCRIPTION:
Mapping XS 0f6cd0e0
END DESCRIPTION:
XS GIS Cut Line= 4
      2091331.71     13425182.67      2090685.86     13424771.20
      2090123.36     13424828.49      2089051.12     13425640.48
#Sta/Elev= 30
  4377.9  323.84  4693.7  322.72  4814.8  321.37  4866.4  322.23  4908.7  321.14
  4931.3  321.66  4966.9  319.50  4975.6  320.55  4981.5  319.71  4990.6  320.82
  4996.8  320.00  4999.4  318.79  4999.9  317.99  5005.5  317.99  5006.0  318.79
  5033.2  320.91  5069.6  321.55  5245.1  322.63  5456.2  322.45  5524.0  320.19
  5546.6  321.51  5628.7  322.12  5687.3  321.42  5712.5  322.14  5912.2  322.04
  5997.5  323.10  6319.9  322.59  6704.9  324.70  6740.2  324.17  7054.1  325.39
#Mann=3,-1,0
  4377.9     0.1       0  4999.4    0.07       0  5006.0     0.1       0
Bank Sta=4999.4,5006
Exp/Cntr=0.3,0.1

Type RM Length L Ch R = 1,12474,711,711,711
BEGIN DESCRIPTION:
UNT 090 in La Jarita Watershed 11.0
END DESCRIPTION:
XS GIS Cut Line= 3
      2091451.46     13425177.43      2090975.00     13424675.00
      2089373.32     13424260.78
#Sta/Elev= 30
  4316.0  323.72  4626.4  323.04  4817.3  321.21  4859.8  321.47  4916.4  319.93
  4966.1  320.16  4980.3  319.66  4987.2  318.29  5018.8  320.37  5066.8  320.89
  5544.0  321.65  5752.3  320.62  5782.6  321.45  5803.8  320.37  5909.6  319.19
  5938.0  319.84  5950.3  319.27  5965.7  317.47  5966.2  316.67  5971.8  316.67
  5972.3  317.47  5985.7  319.71  6000.0  320.35  6067.0  321.29  6102.4  322.67
  6134.3  322.19  6444.2  322.72  6495.8  323.44  6568.1  322.86  6662.8  323.78
#Mann=3,-1,0
  4316.0     0.1       0  5965.7    0.07       0  5972.3     0.1       0
Bank Sta=5965.7,5972.3
Exp/Cntr=0.3,0.1

Type RM Length L Ch R = 1,11763,931,931,931
BEGIN DESCRIPTION:
UNT 090 in La Jarita Watershed 10.0
END DESCRIPTION:
XS GIS Cut Line= 3
      2091555.63     13424656.60      2091008.77     13424114.95
      2089935.82     13423667.02
#Sta/Elev= 30
  4298.5  322.94  4540.5  322.45  4837.5  318.36  4943.6  318.12  4993.0  315.64
  5007.2  315.89  5028.4  317.88  5084.8  318.07  5161.7  317.03  5211.4  313.59
  5211.9  312.79  5217.5  312.79  5218.0  313.59  5238.5  314.76  5256.5  313.65
  5286.1  316.12  5315.4  315.90  5332.4  314.25  5363.0  316.38  5421.5  316.37
  5439.9  314.82  5451.6  316.10  5492.9  315.37  5546.0  317.05  5614.1  316.93
  5681.3  320.04  5811.2  322.51  6004.2  324.27  6188.4  323.69  6230.9  324.43
#Mann=3,-1,0
  4298.5     0.1       0  5211.4    0.07       0  5218.0     0.1       0
Bank Sta=5211.4,5218
Exp/Cntr=0.3,0.1

Type RM Length L Ch R = 1,10832,1149,1149,1149
BEGIN DESCRIPTION:
UNT 090 in La Jarita Watershed 9.0
END DESCRIPTION:
XS GIS Cut Line= 3
      2091769.19     13424344.11      2091399.40     13423573.28
      2090712.32     13423359.87
#Sta/Elev= 30
  4213.0  320.37  4418.2  318.32  4456.0  318.52  4486.2  317.68  4544.7  317.50
  4566.9  318.54  4599.4  317.05  4672.9  316.16  4822.0  315.91  4854.1  315.20
  4882.3  315.59  4899.4  314.83  4933.2  314.67  4966.2  313.35  4972.9  312.54
  4978.5  312.85  4988.4  311.86  4997.6  310.00  4998.1  309.20  5004.1  309.20
  5004.7  310.00  5010.6  311.08  5018.2  314.29  5040.9  316.15  5181.3  319.67
  5246.4  319.80  5292.4  321.45  5355.3  322.11  5550.0  322.32  5787.4  321.91
#Mann=3,-1,0
  4213.0     0.1       0  4997.6    0.07       0  5004.7     0.1       0
Bank Sta=4997.6,5004.7
Exp/Cntr=0.3,0.1

Type RM Length L Ch R = 1,9683,460,460,460
BEGIN DESCRIPTION:
UNT 090 in La Jarita Watershed 8.0
END DESCRIPTION:
XS GIS Cut Line= 3
      2092607.77     13423396.21      2092025.00     13423225.00
      2090935.81     13423219.12
#Sta/Elev= 30
  4388.4  319.62  4442.1  320.42  4495.5  319.97  4599.7  320.21  4691.3  318.51
  4729.9  318.32  4818.6  316.18  4881.1  313.83  4922.8  313.01  4940.5  311.95
  4954.1  311.73  4973.9  309.83  4979.1  310.49  4985.4  309.45  5001.5  308.24
  5002.3  307.44  5009.3  307.44  5010.0  308.24  5015.8  309.72  5025.8  311.10
  5115.8  310.75  5245.8  313.88  5315.8  313.94  5515.8  318.23  5615.8  319.20
  5695.8  320.65  5715.8  320.16  5745.8  320.42  5765.8  321.25  6085.0  321.80
#Mann=3,-1,0
  4388.4     0.1       0  5001.5    0.07       0  5010.0     0.1       0
Bank Sta=5001.5,5010
Exp/Cntr=0.3,0.1

Type RM Length L Ch R = 1,9223,265,265,265
BEGIN DESCRIPTION:
UNT 090 in La Jarita Watershed 7.0
END DESCRIPTION:
XS GIS Cut Line= 3
      2092550.47     13422922.24      2091975.00     13422925.00
      2091144.19     13423031.62
#Sta/Elev= 30
  4430.3  321.13  4575.8  321.21  4605.8  323.09  4625.8  320.47  4645.8  318.88
  4705.8  316.75  4735.8  316.93  4755.8  315.45  4806.5  313.47  4835.8  312.61
  4865.8  309.04  4885.8  307.87  4905.8  309.02  4935.8  306.40  4965.8  307.20
  4981.5  305.75  4982.3  304.95  4989.3  304.95  4990.0  305.75  5003.3  308.24
  5015.9  309.82  5043.1  309.52  5086.4  311.04  5207.4  313.00  5276.9  312.64
  5348.6  313.29  5590.2  318.42  5640.9  318.22  5681.3  319.92  5843.4  320.99
#Mann=4,-1,0
  4430.3    0.05       0  4806.5     0.1       0  4981.5    0.07       0
  4990.0     0.1       0
Bank Sta=4981.5,4990
Exp/Cntr=0.3,0.1