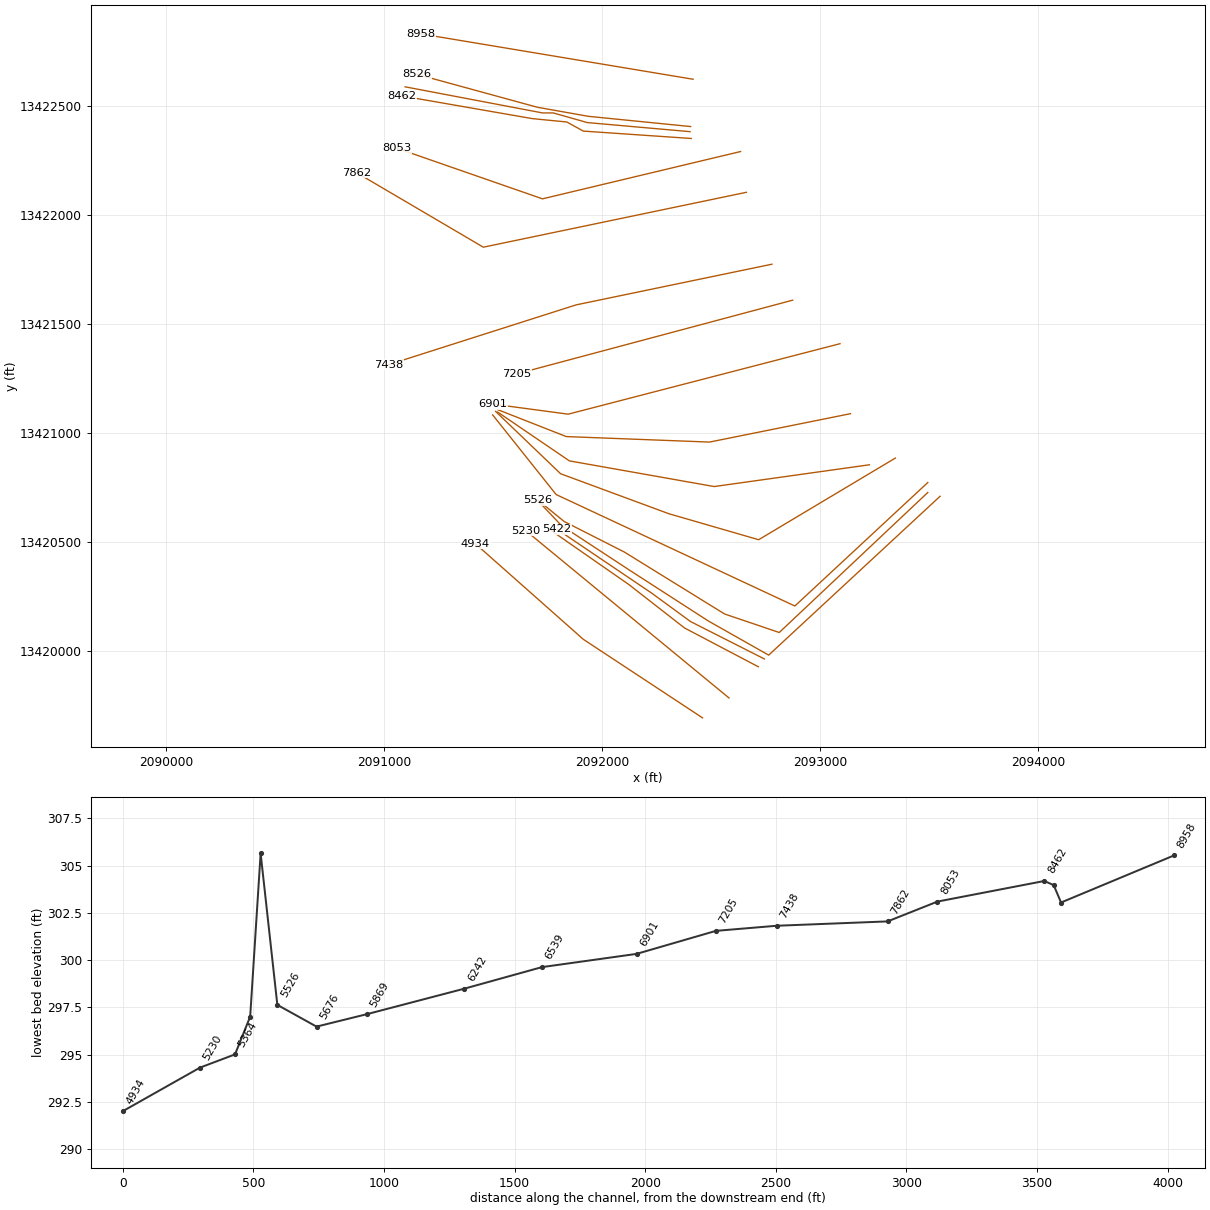
HEC-RAS study UNT 090 in La Jarita Watershed.prj: UNT 090 in La Jarita Watershed Base Level Engineering

--- UNT 090 in La Jarita Watershed.g01 (geometry) --- (continued)

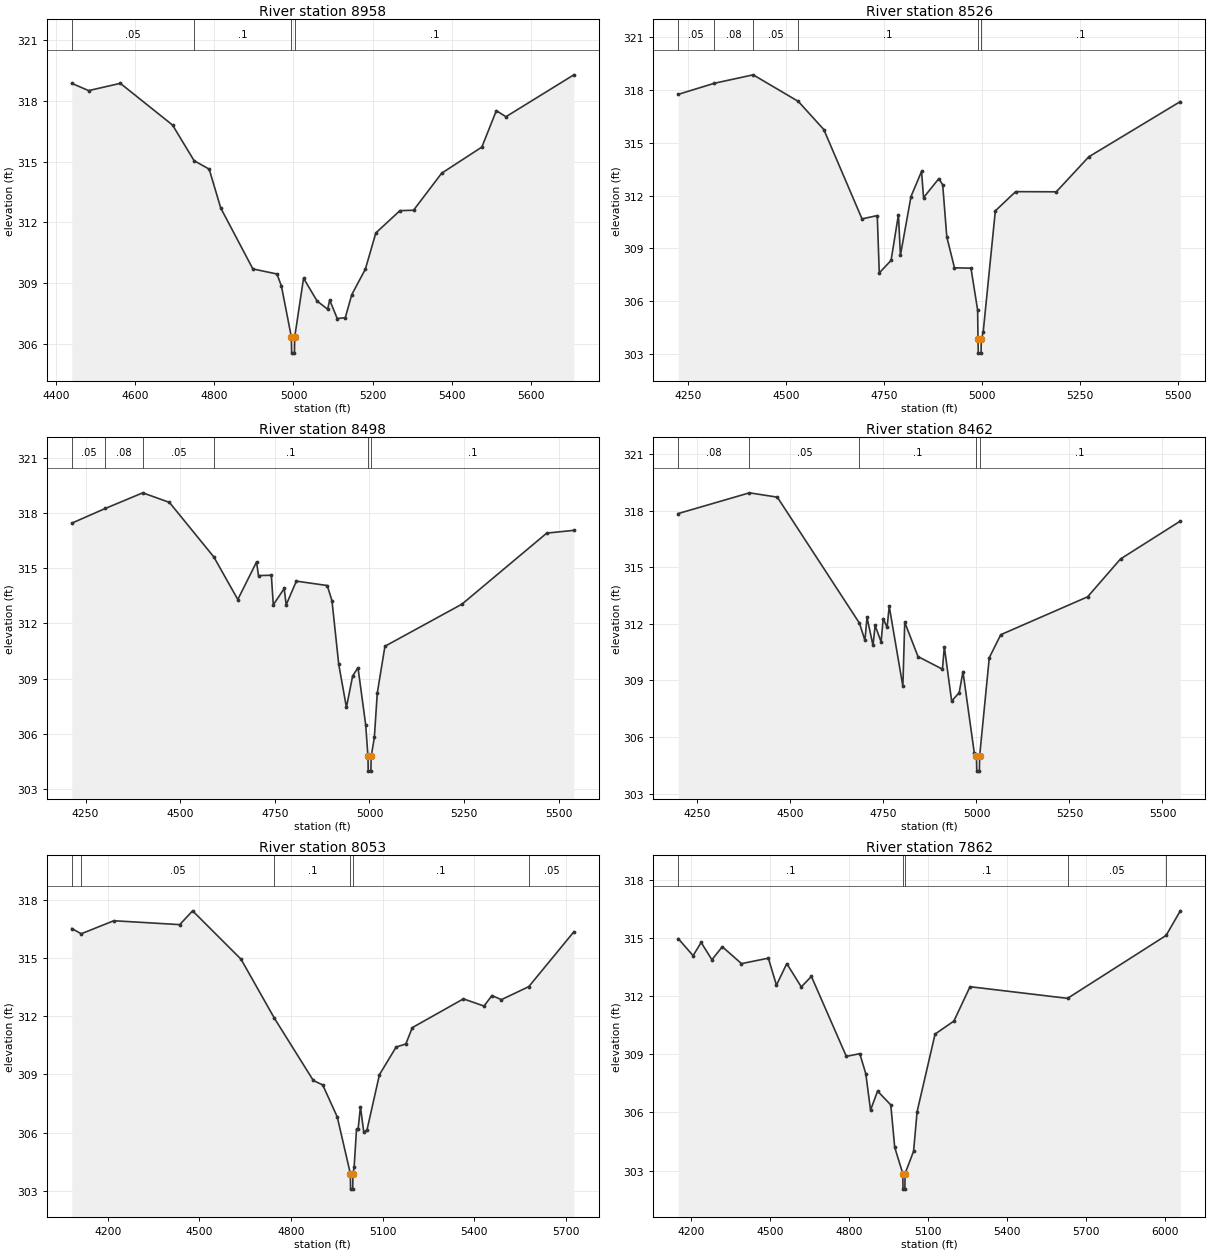
Type RM Length L Ch R = 1,8958,432,432,432
BEGIN DESCRIPTION:
Mapping XS 4b19f79b
END DESCRIPTION:
XS GIS Cut Line= 2
      2092415.88     13422623.63      2091165.92     13422831.96
#Sta/Elev= 30
  4440.4  318.87  4483.0  318.51  4562.9  318.87  4694.7  316.81  4749.1  315.05
  4787.2  314.63  4816.4  312.71  4897.5  309.70  4958.3  309.45  4969.6  308.85
  4994.6  306.34  4995.4  305.54  5002.4  305.54  5003.1  306.34  5025.4  309.24
  5059.7  308.11  5086.2  307.71  5091.3  308.16  5110.4  307.25  5130.7  307.29
  5147.1  308.43  5181.4  309.69  5207.9  311.48  5268.7  312.58  5303.0  312.60
  5374.0  314.43  5475.4  315.72  5512.0  317.52  5536.2  317.22  5707.6  319.29
#Mann=4,-1,0
  4440.4    0.05       0  4749.1     0.1       0  4994.6    0.07       0
  5003.1     0.1       0
Bank Sta=4994.6,5003.1
Exp/Cntr=0.3,0.1

Type RM Length L Ch R = 1,8526,28,28,28
BEGIN DESCRIPTION:
Mapping XS 9c29b415
END DESCRIPTION:
XS GIS Cut Line= 4
      2092404.65     13422406.61      2091935.86     13422453.49
      2091701.48     13422495.16      2091149.74     13422646.11
#Sta/Elev= 30
  4225.6  317.76  4317.7  318.39  4416.8  318.87  4532.0  317.36  4597.1  315.76
  4694.6  310.68  4733.5  310.87  4738.6  307.61  4768.7  308.32  4787.5  310.92
  4792.6  308.61  4819.5  311.95  4846.5  313.38  4851.6  311.89  4890.6  312.97
  4900.5  312.61  4910.9  309.66  4930.5  307.90  4972.6  307.88  4989.6  305.50
  4990.5  303.85  4991.3  303.05  4998.3  303.05  4999.0  303.85  5003.7  304.23
  5034.8  311.14  5086.6  312.23  5190.3  312.22  5273.3  314.21  5506.8  317.35
#Mann=6,-1,0
  4225.6    0.05       0  4317.7    0.08       0  4416.8    0.05       0
  4532.0     0.1       0  4990.5    0.07       0  4999.0     0.1       0
Bank Sta=4990.5,4999
Exp/Cntr=0.3,0.1

Type RM Length L Ch R = 1,8498,36,36,36
BEGIN DESCRIPTION:
Mapping XS 773b3558
END DESCRIPTION:
XS GIS Cut Line= 5
      2092402.02     13422383.18      2091930.65     13422424.85
      2091774.40     13422469.12      2091724.92     13422469.12
      2091094.70     13422588.91
#Sta/Elev= 30
  4213.4  317.45  4302.0  318.25  4401.0  319.10  4471.4  318.58  4588.9  315.61
  4652.1  313.30  4701.6  315.34  4706.8  314.60  4740.7  314.62  4745.9  313.01
  4774.7  313.90  4779.9  313.01  4806.8  314.30  4888.4  314.06  4900.9  313.24
  4918.8  309.77  4939.1  307.44  4955.6  309.15  4969.7  309.59  4990.0  306.49
  4996.0  304.77  4996.7  303.97  5003.7  303.97  5004.5  304.77  5012.9  305.80
  5020.6  308.21  5040.9  310.76  5244.5  313.05  5468.4  316.91  5540.0  317.06
#Mann=6,-1,0
  4213.4    0.05       0  4302.0    0.08       0  4401.0    0.05       0
  4588.9     0.1       0  4996.0    0.07       0  5004.5     0.1       0
Bank Sta=4996,5004.5
Exp/Cntr=0.3,0.1

Type RM Length L Ch R = 1,8462,409,409,409
BEGIN DESCRIPTION:
Mapping XS ac44bdd2
END DESCRIPTION:
XS GIS Cut Line= 5
      2092407.19     13422351.93      2091912.42     13422385.78
      2091836.90     13422427.45      2091678.05     13422443.08
      2091079.52     13422547.17
#Sta/Elev= 30
  4198.6  317.86  4390.0  318.96  4464.9  318.73  4685.7  312.04  4700.3  311.13
  4706.0  312.35  4722.0  310.86  4727.7  311.92  4743.8  311.05  4749.5  312.28
  4759.9  311.82  4765.6  312.94  4802.3  308.69  4807.3  312.09  4843.0  310.27
  4908.6  309.60  4913.7  310.79  4933.4  307.91  4953.6  308.35  4963.8  309.47
  4994.2  305.16  5000.1  304.99  5000.9  304.19  5007.9  304.19  5008.6  304.99
  5034.5  310.21  5065.3  311.43  5298.7  313.44  5387.2  315.45  5547.9  317.46
#Mann=5,-1,0
  4198.6    0.08       0  4390.0    0.05       0  4685.7     0.1       0
  5000.1    0.07       0  5008.6     0.1       0
Bank Sta=5000.1,5008.6
Exp/Cntr=0.3,0.1

Type RM Length L Ch R = 1,8053,191,191,191
BEGIN DESCRIPTION:
UNT 090 in La Jarita Watershed 6.0
END DESCRIPTION:
XS GIS Cut Line= 3
      2092633.75     13422292.03      2091725.00     13422075.00
      2091055.68     13422307.65
#Sta/Elev= 30
  4082.6  316.51  4113.6  316.24  4220.3  316.91  4435.9  316.71  4478.0  317.42
  4636.5  314.93  4745.4  311.90  4873.0  308.69  4903.8  308.46  4951.2  306.82
  4994.2  303.90  4994.9  303.10  5001.9  303.10  5002.7  303.90  5006.6  304.24
  5014.3  306.18  5019.5  306.18  5027.2  307.34  5038.1  306.03  5048.7  306.15
  5089.4  308.99  5143.9  310.41  5175.7  310.57  5196.9  311.41  5364.1  312.89
  5431.6  312.52  5457.4  313.06  5488.5  312.85  5578.1  313.52  5725.5  316.34
#Mann=6,-1,0
  4082.6    0.08       0  4113.6    0.05       0  4745.4     0.1       0
  4994.2    0.07       0  5002.7     0.1       0  5578.1    0.05       0
Bank Sta=4994.2,5002.7
Exp/Cntr=0.3,0.1

Type RM Length L Ch R = 1,7862,424,424,424
BEGIN DESCRIPTION:
Mapping XS a2be3110
END DESCRIPTION:
XS GIS Cut Line= 3
      2092660.21     13422104.96      2091453.65     13421853.23
      2090871.75     13422195.23
#Sta/Elev= 30
  4150.9  314.96  4207.3  314.08  4237.9  314.76  4278.8  313.87  4318.3  314.54
  4391.2  313.67  4493.3  313.95  4524.0  312.56  4563.3  313.67  4618.4  312.47
  4656.8  313.01  4789.6  308.89  4840.7  309.03  4863.4  308.00  4881.5  306.12
  4908.3  307.10  4958.4  306.39  4973.4  304.20  5004.1  302.85  5004.9  302.05
  5011.9  302.05  5012.7  302.85  5045.0  304.00  5058.4  306.04  5126.7  310.04
  5198.2  310.71  5259.5  312.48  5629.9  311.88  6004.3  315.12  6058.4  316.39
#Mann=5,-1,0
  4150.9     0.1       0  5004.1    0.07       0  5012.7     0.1       0
  5629.9    0.05       0  6004.3     0.1       0
Bank Sta=5004.1,5012.7
Exp/Cntr=0.3,0.1

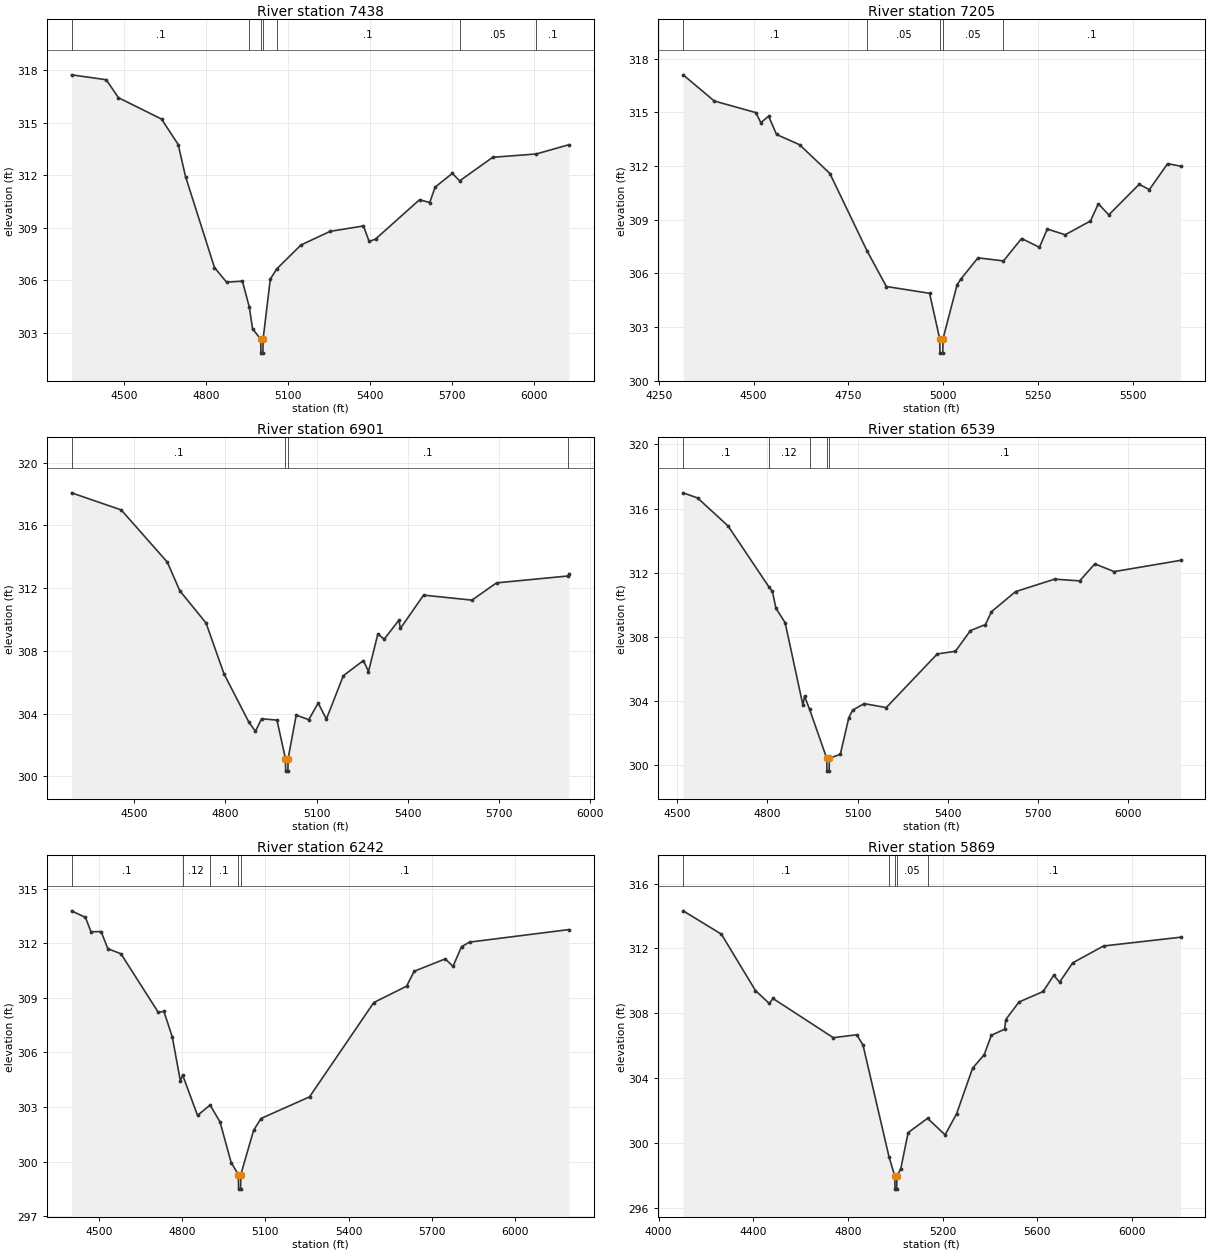
Type RM Length L Ch R = 1,7438,233,233,233
BEGIN DESCRIPTION:
Mapping XS 95b895ae
END DESCRIPTION:
XS GIS Cut Line= 3
      2092777.48     13421775.12      2091879.00     13421588.48
      2091018.16     13421314.00
#Sta/Elev= 30
  4307.6  317.75  4434.4  317.47  4479.5  316.44  4637.0  315.22  4698.2  313.76
  4724.9  311.93  4831.0  306.72  4875.3  305.88  4933.2  305.94  4958.5  304.46
  4970.4  303.21  5000.4  302.62  5001.1  301.82  5008.2  301.82  5009.0  302.62
  5035.3  306.05  5058.3  306.63  5147.6  308.01  5254.4  308.79  5376.4  309.10
  5397.4  308.21  5420.7  308.35  5581.7  310.60  5619.2  310.44  5638.8  311.32
  5701.8  312.11  5728.7  311.68  5849.8  313.03  6009.1  313.22  6128.8  313.75
#Mann=7,-1,0
  4307.6     0.1       0  4958.5    0.05       0  5000.4    0.03       0
  5009.0    0.05       0  5058.3     0.1       0  5728.7    0.05       0
  6009.1     0.1       0
Bank Sta=5000.4,5009
Exp/Cntr=0.3,0.1

Type RM Length L Ch R = 1,7205,304,304,304
BEGIN DESCRIPTION:
Mapping XS 1d64d393
END DESCRIPTION:
XS GIS Cut Line= 2
      2092872.89     13421610.17      2091605.52     13421271.62
#Sta/Elev= 30
  4314.1  317.09  4396.1  315.63  4505.9  314.98  4518.9  314.42  4539.6  314.78
  4560.3  313.76  4621.0  313.19  4701.1  311.58  4799.1  307.26  4850.1  305.27
  4964.0  304.89  4990.7  302.35  4991.5  301.55  4998.7  301.55  4999.4  302.35
  5036.5  305.36  5046.3  305.68  5091.6  306.87  5158.9  306.70  5206.6  307.95
  5253.8  307.46  5274.5  308.48  5321.7  308.16  5388.4  308.93  5409.1  309.89
  5436.7  309.27  5516.9  310.98  5543.6  310.68  5591.8  312.13  5625.9  311.99
#Mann=5,-1,0
  4314.1     0.1       0  4799.1    0.05       0  4990.7    0.03       0
  4999.4    0.05       0  5158.9     0.1       0
Bank Sta=4990.7,4999.4
Exp/Cntr=0.3,0.1

Type RM Length L Ch R = 1,6901,362,362,362
BEGIN DESCRIPTION:
Mapping XS 051db764
END DESCRIPTION:
XS GIS Cut Line= 3
      2093089.93     13421410.52      2091842.74     13421087.18
      2091499.03     13421133.23
#Sta/Elev= 30
  4294.4  318.07  4457.7  316.98  4609.4  313.65  4650.3  311.83  4736.7  309.77
  4795.4  306.54  4878.0  303.43  4899.0  302.87  4919.3  303.67  4969.8  303.58
  4997.6  301.13  4998.4  300.33  5005.6  300.33  5006.4  301.13  5033.0  303.90
  5074.3  303.61  5105.3  304.67  5132.2  303.65  5187.9  306.41  5253.9  307.38
  5270.6  306.68  5301.6  309.08  5322.2  308.74  5370.5  309.95  5375.7  309.43
  5451.7  311.55  5610.8  311.23  5691.5  312.33  5927.2  312.77  5929.6  312.92
#Mann=4,-1,0
  4294.4     0.1       0  4997.6    0.07       0  5006.4     0.1       0
  5927.2    0.05       0
Bank Sta=4997.6,5006.4
Exp/Cntr=0.3,0.1

Type RM Length L Ch R = 1,6539,297,297,297
BEGIN DESCRIPTION:
Mapping XS 8f079f0e
END DESCRIPTION:
XS GIS Cut Line= 4
      2093137.70     13421089.35      2092490.98     13420959.13
      2091834.06     13420984.40      2091519.47     13421107.97
#Sta/Elev= 30
  4519.4  316.98  4567.4  316.66  4669.1  314.91  4804.9  311.11  4816.5  310.83
  4828.2  309.78  4858.8  308.88  4918.1  303.73  4923.2  304.31  4940.1  303.48
  4997.2  300.43  4998.0  299.63  5005.2  299.63  5006.0  300.43  5042.4  300.68
  5070.6  302.96  5083.2  303.43  5121.5  303.84  5195.1  303.59  5365.2  306.94
  5425.3  307.10  5475.3  308.39  5525.3  308.77  5545.4  309.57  5625.4  310.82
  5755.5  311.60  5838.7  311.49  5889.2  312.55  5953.7  312.07  6174.5  312.77
#Mann=5,-1,0
  4519.4     0.1       0  4804.9    0.12       0  4940.1     0.1       0
  4997.2    0.07       0  5006.0     0.1       0
Bank Sta=4997.2,5006
Exp/Cntr=0.3,0.1

Type RM Length L Ch R = 1,6242,373,373,373
BEGIN DESCRIPTION:
Mapping XS a723b9f4
END DESCRIPTION:
XS GIS Cut Line= 4
      2093224.52     13420854.97      2092512.68     13420755.14
      2091848.35     13420872.87      2091519.03     13421097.10
#Sta/Elev= 30
  4401.9  313.78  4451.9  313.42  4472.1  312.63  4508.6  312.64  4532.7  311.70
  4579.9  311.42  4714.5  308.20  4734.6  308.26  4764.9  306.85  4794.0  304.43
  4802.2  304.76  4855.8  302.54  4901.0  303.11  4936.6  302.19  4977.0  299.95
  5002.9  299.29  5003.7  298.49  5010.9  298.49  5011.7  299.29  5057.8  301.72
  5084.4  302.37  5259.3  303.56  5490.7  308.74  5609.0  309.64  5636.3  310.46
  5748.0  311.14  5776.2  310.73  5806.8  311.81  5835.7  312.06  6193.8  312.75
#Mann=5,-1,0
  4401.9     0.1       0  4802.2    0.12       0  4901.0     0.1       0
  5002.9    0.07       0  5011.7     0.1       0
Bank Sta=5002.9,5011.7
Exp/Cntr=0.3,0.1

Type RM Length L Ch R = 1,5869,193,193,193
BEGIN DESCRIPTION:
Mapping XS 2cd9e2df
END DESCRIPTION:
XS GIS Cut Line= 5
      2093343.76     13420885.81      2092716.67     13420511.22
      2092304.35     13420630.58      2091808.24     13420813.79
      2091509.91     13421099.88
#Sta/Elev= 30
  4103.6  314.32  4265.2  312.88  4409.1  309.40  4467.5  308.60  4483.1  308.91
  4738.0  306.49  4837.5  306.67  4863.7  306.03  4973.3  299.15  4998.0  297.94
  4998.8  297.14  5006.0  297.14  5006.8  297.94  5023.2  298.40  5054.4  300.63
  5136.4  301.51  5210.6  300.49  5259.3  301.80  5326.6  304.60  5375.8  305.44
  5406.2  306.64  5461.8  307.01  5467.1  307.61  5522.6  308.69  5625.1  309.34
  5669.4  310.34  5694.5  309.92  5750.0  311.11  5880.0  312.15  6205.5  312.69
#Mann=5,-1,0
  4103.6     0.1       0  4973.3    0.05       0  4998.0   0.033       0
  5006.8    0.05       0  5136.4     0.1       0
Bank Sta=4998,5006.8
Exp/Cntr=0.3,0.1

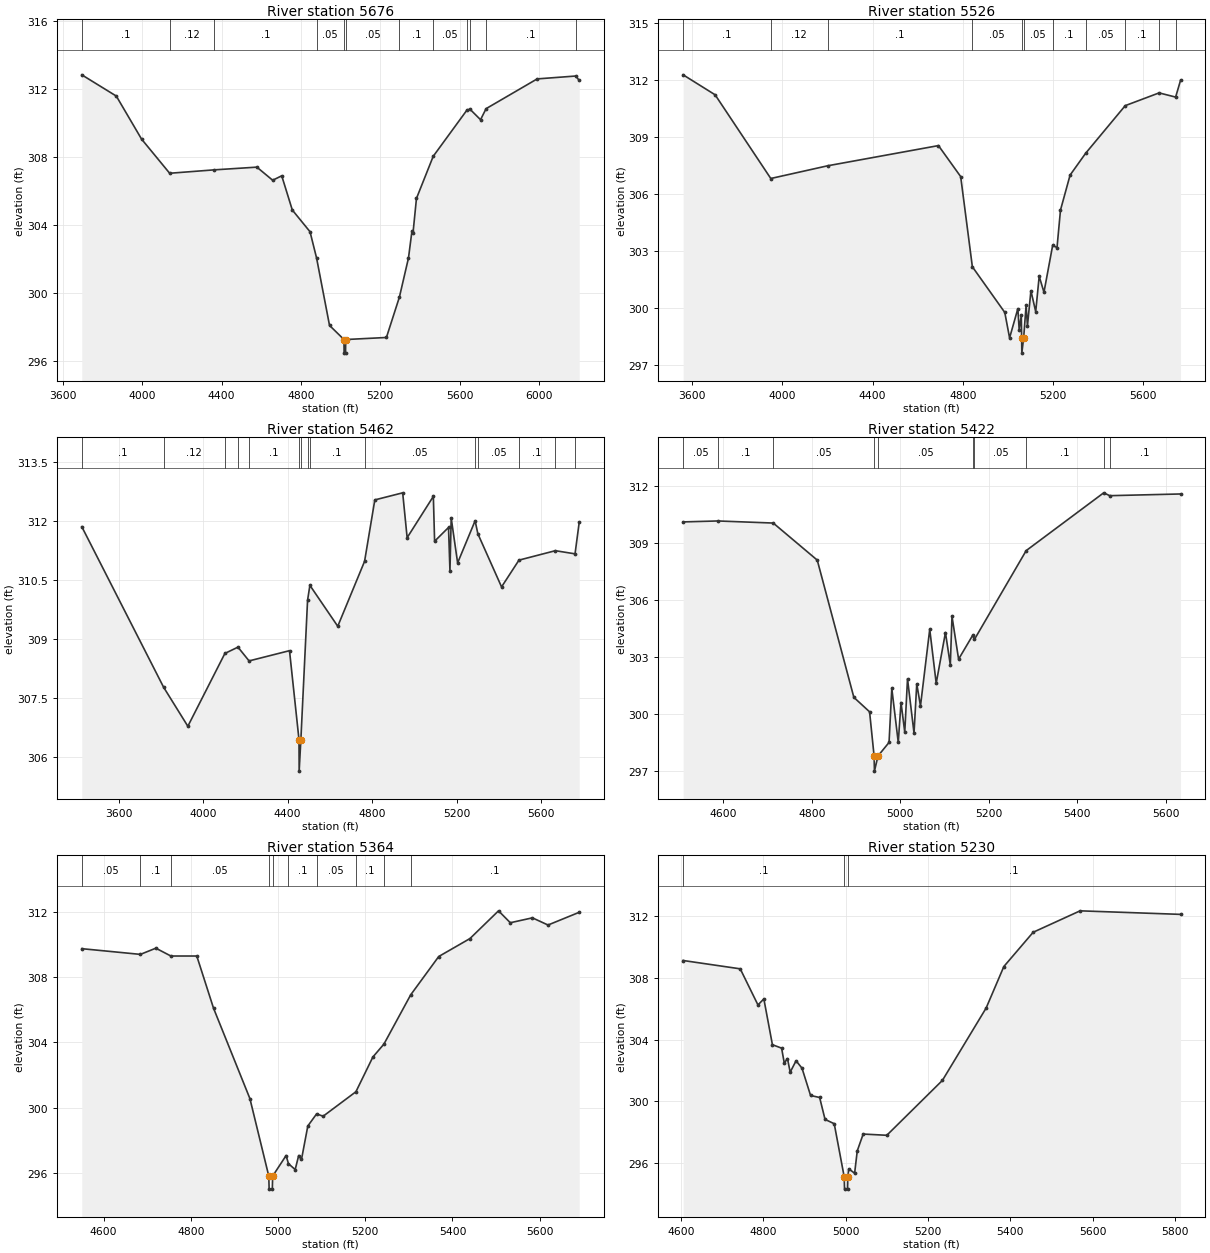
Type RM Length L Ch R = 1,5676,150,150,150
BEGIN DESCRIPTION:
Mapping XS 01f6723e
END DESCRIPTION:
XS GIS Cut Line= 4
      2093492.54     13420773.53      2092882.71     13420207.11
      2091787.61     13420718.43      2091496.35     13421083.86
#Sta/Elev= 30
  3695.1  312.85  3869.2  311.60  3996.5  309.07  4138.2  307.06  4362.6  307.26
  4578.0  307.42  4657.6  306.65  4703.3  306.91  4756.6  304.90  4846.0  303.62
  4879.1  302.07  4944.3  298.11  5017.1  297.28  5017.9  296.48  5025.1  296.48
  5025.9  297.28  5231.2  297.40  5296.8  299.78  5342.5  302.08  5359.8  303.65
  5365.3  303.55  5382.7  305.58  5467.3  308.06  5638.1  310.79  5653.2  310.82
  5705.8  310.21  5733.8  310.86  5991.3  312.61  6186.2  312.78  6203.3  312.52
#Mann=12,-1,0
  3695.1     0.1       0  4138.2    0.12       0  4362.6     0.1       0
  4879.1    0.05       0  5017.1   0.033       0  5025.9    0.05       0
  5296.8     0.1       0  5467.3    0.05       0  5638.1     0.1       0
  5653.2    0.05       0  5733.8     0.1       0  6186.2    0.05       0
Bank Sta=5017.1,5025.9
Exp/Cntr=0.3,0.1

Type RM Length L Ch R = 1,5526,64,64,64
BEGIN DESCRIPTION:
Mapping XS b52285fb
END DESCRIPTION:
XS GIS Cut Line= 6
      2093492.55     13420727.96      2092811.10     13420085.58
      2092560.42     13420170.51      2092100.35     13420454.79
      2091824.19     13420594.97      2091704.49     13420692.83
#Sta/Elev= 30
  3559.4  312.26  3701.3  311.21  3948.2  306.81  4201.1  307.48  4691.9  308.54
  4790.5  306.91  4842.3  302.17  4986.1  299.77  5007.4  298.43  5044.1  299.97
  5049.9  298.87  5059.5  299.62  5060.9  298.43  5061.7  297.63  5069.8  298.43
  5080.7  300.15  5086.6  299.06  5102.0  300.91  5123.3  299.81  5138.7  301.67
  5159.9  300.83  5198.4  303.29  5217.8  303.18  5233.2  305.15  5275.8  306.99
  5345.0  308.14  5520.4  310.64  5670.6  311.31  5743.9  311.09  5765.7  311.97
#Mann=11,-1,0
  3559.4     0.1       0  3948.2    0.12       0  4201.1     0.1       0
  4842.3    0.05       0  5060.9   0.033       0  5069.8    0.05       0
  5198.4     0.1       0  5345.0    0.05       0  5520.4     0.1       0
  5670.6    0.05       0  5743.9     0.1       0
Bank Sta=5060.9,5069.8
Exp/Cntr=0.3,0.1

Type RM Length L Ch R = 1,5462,40,40,40
BEGIN DESCRIPTION:
Mapping XS f78044a5
END DESCRIPTION:
XS GIS Cut Line= 6
      2093548.98     13420710.61      2092762.63     13419981.80
      2092486.64     13420137.95      2092126.40     13420370.16
      2091811.52     13420576.53      2091701.09     13420693.10
#Sta/Elev= 30
  3425.5  311.86  3813.0  307.78  3927.6  306.79  4103.0  308.64  4164.9  308.80
  4217.5  308.45  4408.9  308.71  4453.8  306.45  4454.6  305.65  4462.7  306.45
  4494.4  309.99  4505.4  310.37  4637.3  309.33  4764.3  310.98  4812.8  312.54
  4944.7  312.72  4965.8  311.58  5089.9  312.63  5095.8  311.49  5161.7  311.84
  5168.5  310.74  5174.4  312.08  5204.8  310.94  5287.6  312.01  5300.6  311.68
  5412.8  310.33  5495.2  311.01  5667.5  311.25  5760.7  311.17  5780.4  311.97
#Mann=15,-1,0
  3425.5     0.1       0  3813.0    0.12       0  4103.0     0.1       0
  4164.9    0.12       0  4217.5     0.1       0  4453.8   0.033       0
  4462.7     0.1       0  4494.4    0.05       0  4505.4     0.1       0
  4764.3    0.05       0  5287.6     0.1       0  5300.6    0.05       0
  5495.2     0.1       0  5667.5    0.05       0  5760.7     0.1       0
Bank Sta=4453.8,4462.7
Exp/Cntr=0.3,0.1

Type RM Length L Ch R = 1,5422,58,58,58
BEGIN DESCRIPTION:
Mapping XS e5dbf645
END DESCRIPTION:
XS GIS Cut Line= 4
      2092742.75     13419964.33      2092404.17     13420135.78
      2092226.22     13420265.99      2091792.17     13420558.98
#Sta/Elev= 30
  4509.4  310.12  4587.9  310.17  4713.0  310.06  4812.4  308.11  4895.1  300.89
  4930.6  300.13  4940.8  297.81  4941.6  297.01  4949.7  297.81  4974.6  298.52
  4980.8  301.36  4995.4  298.52  5001.6  300.62  5010.1  299.06  5016.3  301.87
  5031.0  299.01  5037.2  301.60  5045.6  300.44  5066.5  304.47  5081.1  301.63
  5102.0  304.30  5113.0  302.60  5116.8  305.15  5131.7  302.90  5163.4  304.15
  5167.5  303.94  5284.4  308.61  5459.5  311.65  5473.1  311.50  5633.1  311.59
#Mann=10,-1,0
  4509.4    0.05       0  4587.9     0.1       0  4713.0    0.05       0
  4940.8    0.04       0  4949.7    0.05       0  5163.4     0.1       0
  5167.5    0.05       0  5284.4     0.1       0  5459.5    0.05       0
  5473.1     0.1       0
Bank Sta=4940.8,4949.7
Exp/Cntr=0.3,0.1

Type RM Length L Ch R = 1,5364,134,134,134
BEGIN DESCRIPTION:
Mapping XS 6d8befe2
END DESCRIPTION:
XS GIS Cut Line= 4
      2092715.34     13419928.33      2092376.83     13420106.27
      2092120.75     13420305.92      2091764.84     13420553.33
#Sta/Elev= 30
  4550.0  309.75  4684.4  309.40  4719.8  309.78  4754.3  309.30  4813.7  309.30
  4852.1  306.10  4935.5  300.56  4978.8  295.81  4979.6  295.01  4986.9  295.01
  4987.7  295.81  5018.5  297.07  5023.9  296.57  5039.3  296.21  5047.4  297.07
  5053.8  296.83  5068.3  298.88  5088.4  299.62  5103.5  299.48  5178.6  300.98
  5217.5  303.11  5242.8  303.90  5304.2  306.92  5368.5  309.27  5440.1  310.37
  5505.6  312.07  5532.6  311.34  5583.3  311.64  5619.1  311.20  5690.6  311.98
#Mann=10,-1,0
  4550.0    0.05       0  4684.4     0.1       0  4754.3    0.05       0
  4978.8    0.04       0  4987.7    0.05       0  5023.9     0.1       0
  5088.4    0.05       0  5178.6     0.1       0  5242.8    0.05       0
  5304.2     0.1       0
Bank Sta=4978.8,4987.7
Exp/Cntr=0.3,0.1

Type RM Length L Ch R = 1,5230,296,296,296
BEGIN DESCRIPTION:
Mapping XS d627cdf9
END DESCRIPTION:
XS GIS Cut Line= 2
      2092580.81     13419785.10      2091648.81     13420552.38
#Sta/Elev= 30
  4605.7  309.13  4744.3  308.59  4787.3  306.25  4801.6  306.64  4822.4  303.67
  4844.7  303.45  4851.1  302.49  4859.0  302.77  4865.5  301.89  4879.8  302.63
  4894.2  302.15  4915.0  300.38  4937.0  300.25  4950.1  298.83  4972.4  298.55
  4996.6  295.11  4997.4  294.31  5004.7  294.31  5005.5  295.11  5007.5  295.63
  5021.9  295.34  5028.3  296.79  5042.7  297.88  5100.0  297.80  5235.0  301.36
  5341.1  306.05  5384.1  308.74  5455.2  310.96  5569.2  312.35  5812.9  312.12
#Mann=3,-1,0
  4605.7     0.1       0  4996.6    0.07       0  5005.5     0.1       0
Bank Sta=4996.6,5005.5
Exp/Cntr=0.3,0.1

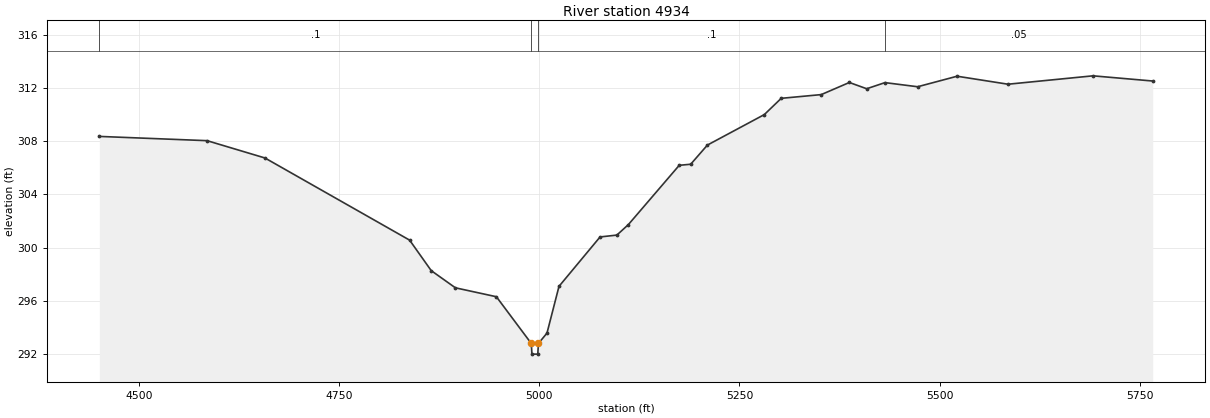
Type RM Length L Ch R = 1,4934,288,288,288
BEGIN DESCRIPTION:
Mapping XS 00bbc24a
END DESCRIPTION:
XS GIS Cut Line= 3
      2092459.30     13419693.94      2091912.42     13420054.19
      2091417.64     13420492.54
#Sta/Elev= 30
  4450.4  308.35  4585.0  308.03  4657.3  306.73  4838.0  300.56  4865.0  298.27
  4895.2  296.98  4946.4  296.31  4990.0  292.80  4990.8  292.00  4998.1  292.00
  4998.9  292.80  5009.6  293.58  5024.6  297.09  5075.9  300.80  5096.9  300.94
  5111.3  301.73  5174.8  306.18  5189.1  306.26  5210.0  307.70  5281.1  309.99
  5302.2  311.21  5352.2  311.49  5387.3  312.40  5409.0  311.93  5431.8  312.39
  5472.6  312.08  5521.9  312.87  5585.5  312.27  5691.7  312.90  5766.3  312.51
#Mann=4,-1,0
  4450.4     0.1       0  4990.0    0.07       0  4998.9     0.1       0
  5431.8    0.05       0
Bank Sta=4990,4998.9
Exp/Cntr=0.3,0.1