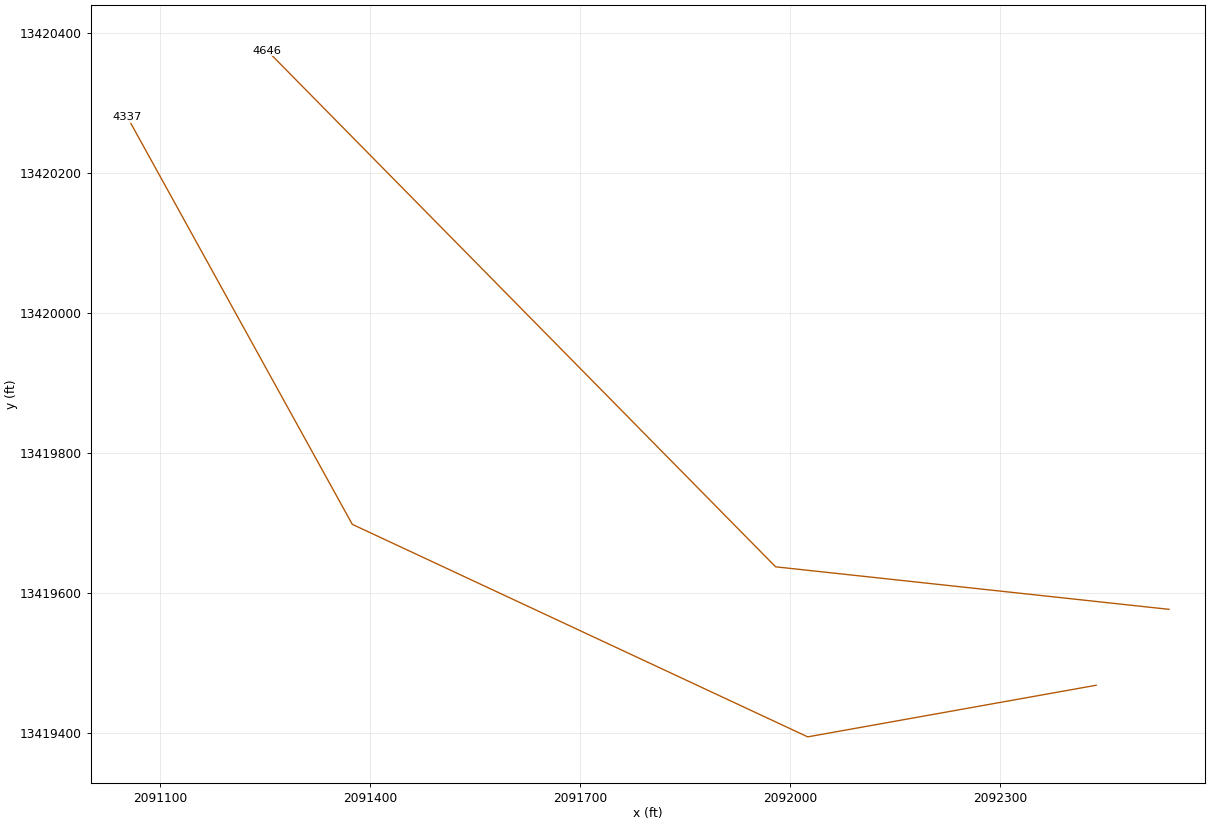
HEC-RAS study UNT 090 in La Jarita Watershed.prj: UNT 090 in La Jarita Watershed Base Level Engineering

--- UNT 090 in La Jarita Watershed.g01 (geometry) --- (continued)

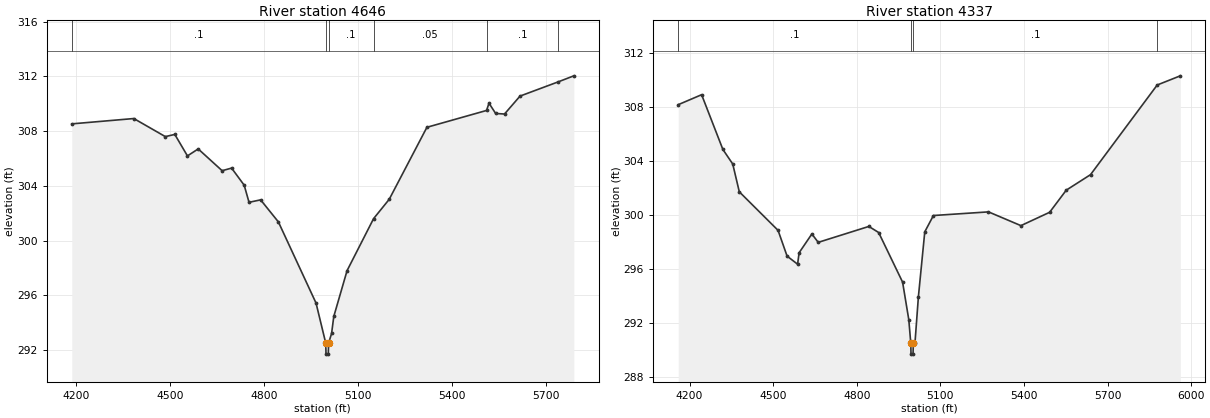
Type RM Length L Ch R = 1,4646,309,309,309
BEGIN DESCRIPTION:
Mapping XS dd4d966c
END DESCRIPTION:
XS GIS Cut Line= 3
      2092541.72     13419576.76      2091979.38     13419637.55
      2091252.70     13420375.37
#Sta/Elev= 30
  4186.6  308.53  4384.5  308.92  4485.0  307.60  4515.2  307.76  4555.5  306.19
  4589.8  306.70  4666.1  305.11  4696.3  305.30  4736.5  304.05  4751.9  302.80
  4788.9  302.98  4845.5  301.37  4965.6  295.44  4996.6  292.51  4997.4  291.71
  5004.7  291.71  5005.6  292.51  5015.2  293.22  5022.2  294.46  5064.6  297.81
  5149.2  301.61  5199.0  303.02  5319.2  308.28  5509.4  309.51  5517.2  310.04
  5538.4  309.29  5566.7  309.25  5616.2  310.56  5738.0  311.60  5787.8  312.04
#Mann=6,-1,0
  4186.6     0.1       0  4996.6    0.07       0  5005.6     0.1       0
  5149.2    0.05       0  5509.4     0.1       0  5738.0    0.05       0
Bank Sta=4996.6,5005.6
Exp/Cntr=0.3,0.1

Type RM Length L Ch R = 1,4337,0,0,0
BEGIN DESCRIPTION:
UNT 090 in La Jarita Watershed 1.0
END DESCRIPTION:
XS GIS Cut Line= 4
      2092437.56     13419468.24      2092025.27     13419394.46
      2091374.23     13419698.28      2091053.03     13420279.90
#Sta/Elev= 30
  4159.4  308.16  4243.3  308.90  4319.6  304.84  4355.0  303.76  4378.5  301.70
  4517.6  298.84  4550.0  296.93  4587.7  296.33  4593.2  297.18  4638.9  298.57
  4661.8  297.95  4843.4  299.13  4878.6  298.68  4964.5  295.00  4986.8  292.21
  4993.9  290.46  4994.7  289.66  5002.0  289.66  5002.9  290.46  5008.9  290.48
  5021.2  293.91  5044.1  298.73  5075.1  299.94  5272.7  300.21  5389.1  299.19
  5492.2  300.18  5551.8  301.82  5638.9  302.97  5878.2  309.62  5961.1  310.30
#Mann=4,-1,0
  4159.4     0.1       0  4993.9    0.07       0  5002.9     0.1       0
  5878.2    0.05       0
Bank Sta=4993.9,5002.9
Exp/Cntr=0.3,0.1

Chan Stop Cuts=-1