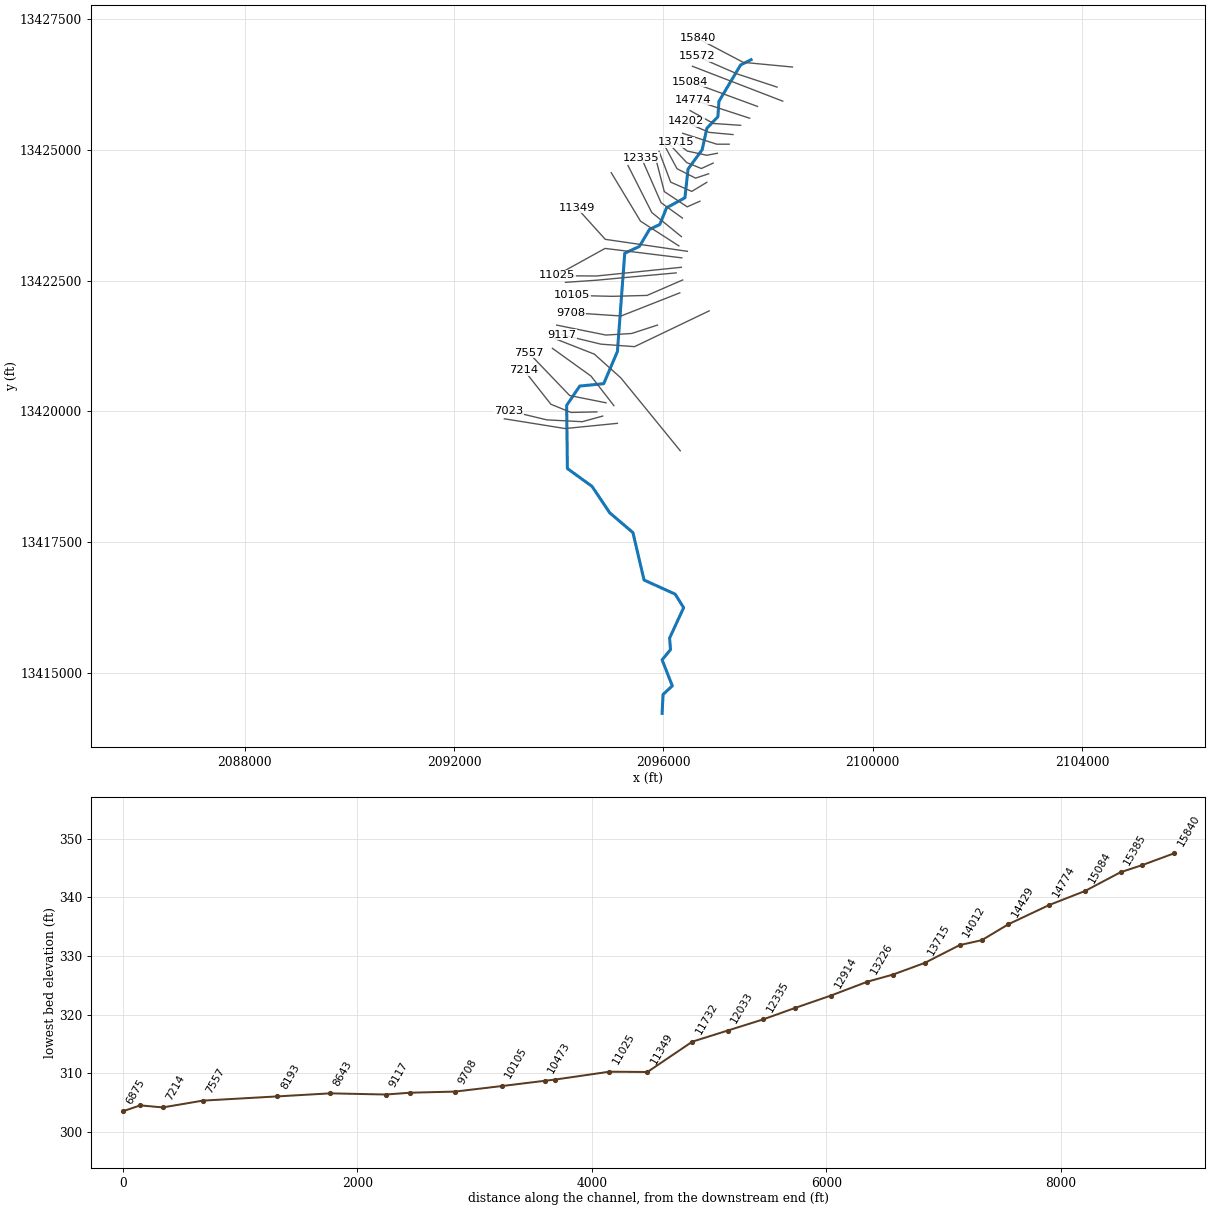
--- UNT 093 in La Jarita Watershed.prj (project) ---

Proj Title=UNT 093 in La Jarita Watershed Base Level Engineering
Current Plan=p01
Default Exp/Contr=0.3,0.1
English Units
Geom File=g01
Flow File=f01
Plan File=p01
BEGIN DESCRIPTION:
UNT 093 in La Jarita Watershed
END DESCRIPTION:

--- UNT 093 in La Jarita Watershed.p01 (plan) ---

Plan Title=Multiple Run
Short Identifier=Multiple
Geom File=g01
Flow File=f01
Subcritical Flow
K Sum by GR= 0
Std Step Tol= 0.01
Critical Tol= 0.01
Num of Std Step Trials= 20
Max Error Tol= 0.3
Flow Tol Ratio= 0.001
Split Flow NTrial= 30
Split Flow Tol= 0.02
Split Flow Ratio= 0.02
Log Output Level= 0
Friction Slope Method= 1
Unsteady Friction Slope Method= 2
Unsteady Bridges Friction Slope Method= 1
Parabolic Critical Depth
Global Vel Dist=  1 , 1 , 1
Global Log Level= 0
CheckData=True
Encroach Param= -1, 0, 0, 0
BEGIN DESCRIPTION:
Multiple Run
END DESCRIPTION:

--- UNT 093 in La Jarita Watershed.f01 (steady flow) ---

Flow Title=Multiple
Number of Profiles=7
Profile Names=10-year,25-year,50-year,1pct_min,100-year,1pct_plu,500-year
River Rch & RM= UNT 093 in La Ja,Reach-1,15840
     169     230     280     170     339     676     505
River Rch & RM= UNT 093 in La Ja,Reach-1,10105
     168     228     277     168     335     669     498
River Rch & RM= UNT 093 in La Ja,Reach-1,9117
     254     352     433     265     529    1056     804
River Rch & RM= UNT 093 in La Ja,Reach-1,5096
     285     397     490     302     602    1200     920
Boundary for River Rch & Prof#=UNT 093 in La Ja,Reach-1,1
Up Type=0
Dn Type=3
Dn Slope=0.005
Boundary for River Rch & Prof#=UNT 093 in La Ja,Reach-1,2
Up Type=0
Dn Type=3
Dn Slope=0.005
Boundary for River Rch & Prof#=UNT 093 in La Ja,Reach-1,3
Up Type=0
Dn Type=3
Dn Slope=0.005
Boundary for River Rch & Prof#=UNT 093 in La Ja,Reach-1,4
Up Type=0
Dn Type=3
Dn Slope=0.005
Boundary for River Rch & Prof#=UNT 093 in La Ja,Reach-1,5
Up Type=0
Dn Type=3
Dn Slope=0.005
Boundary for River Rch & Prof#=UNT 093 in La Ja,Reach-1,6
Up Type=0
Dn Type=3
Dn Slope=0.005
Boundary for River Rch & Prof#=UNT 093 in La Ja,Reach-1,7
Up Type=0
Dn Type=3
Dn Slope=0.005

--- UNT 093 in La Jarita Watershed.g01 (geometry) ---

Geom Title=Existing Conditions

River Reach=UNT 093 in La Ja,Reach-1
Reach XY= 30
      2097675.00     13426725.00      2097475.00     13426625.00
      2097060.80     13425929.54      2097040.80     13425634.54
      2096830.80     13425414.54      2096740.80     13425004.54
      2096470.80     13424634.54      2096410.80     13424084.54
      2096060.80     13423894.54      2095930.80     13423574.54
      2095733.13     13423479.13      2095540.80     13423154.54
      2095260.80     13423024.54      2095120.80     13421144.54
      2094858.90     13420529.77      2094400.80     13420484.54
      2094150.80     13420114.54      2094164.96     13418907.59
      2094635.01     13418566.45      2094974.86     13418059.94
      2095417.57     13417682.33      2095629.81     13416774.78
      2096224.86     13416505.25      2096386.32     13416246.13
      2096118.09     13415665.41      2096135.01     13415442.75
      2095974.86     13415248.74      2096170.17     13414751.34
      2095993.09     13414587.28      2095975.00     13414225.00

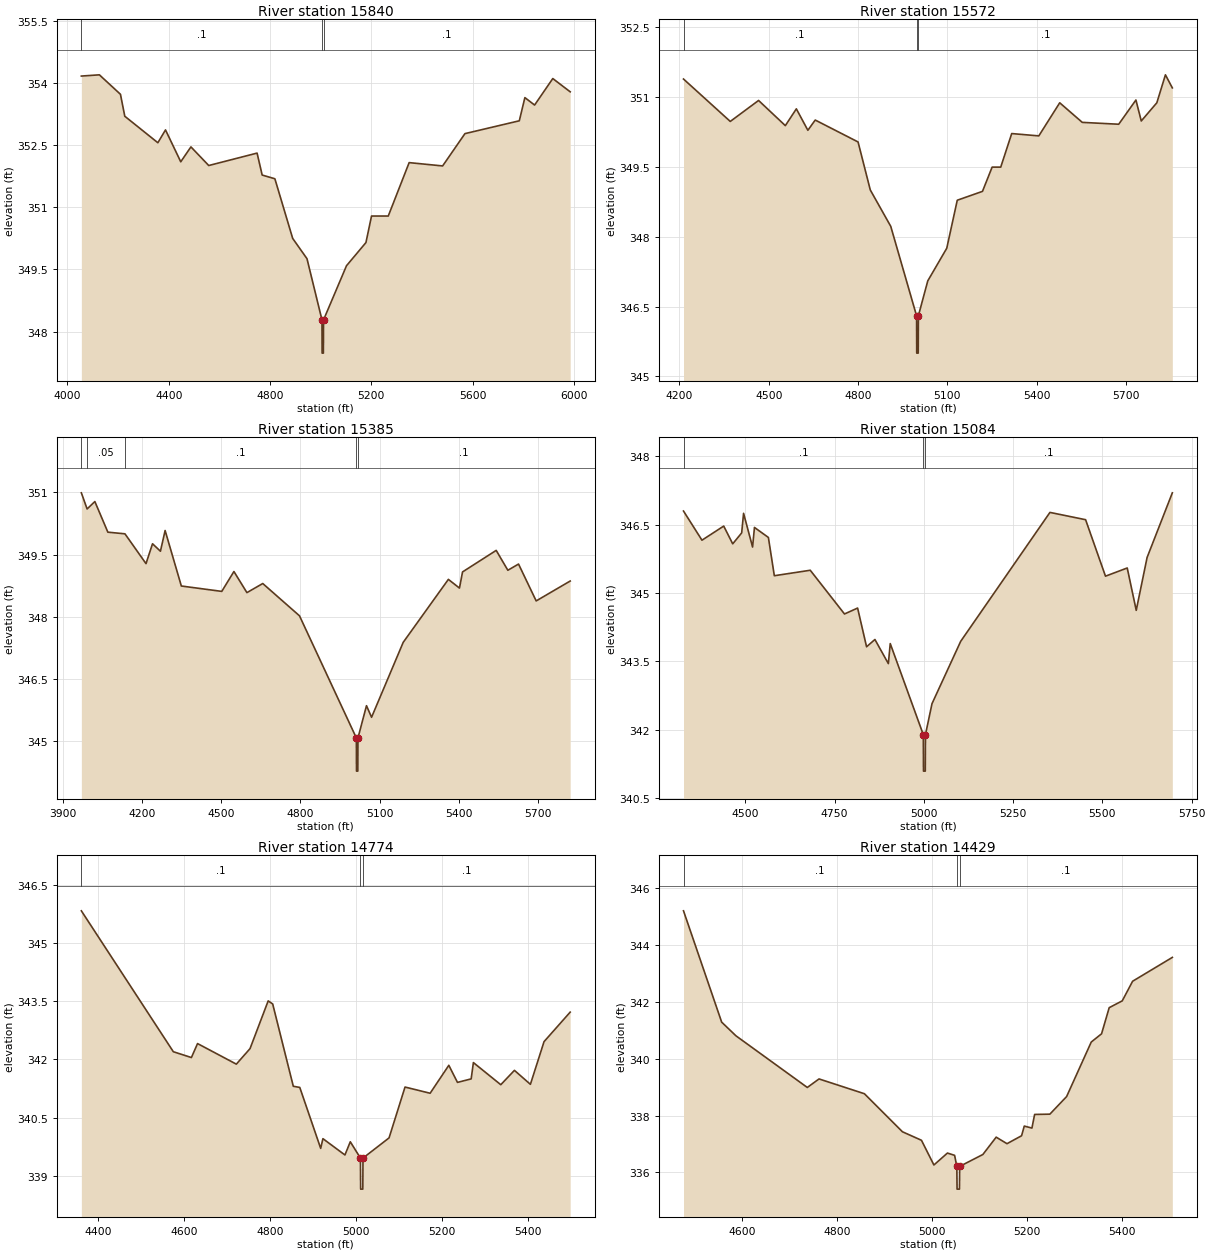
Type RM Length L Ch R = 1,15840,268,268,268
BEGIN DESCRIPTION:
UNT 093 in La Jarita Watershed 21.0
END DESCRIPTION:
XS GIS Cut Line= 3
      2098465.76     13426585.58      2097525.00     13426675.00
      2096653.24     13427134.18
#Sta/Elev= 30
  4055.0  354.17  4126.1  354.20  4209.4  353.73  4226.5  353.20  4357.1  352.56
  4387.3  352.87  4447.5  352.10  4487.7  352.46  4558.0  352.01  4748.9  352.31
  4769.0  351.78  4819.2  351.69  4889.5  350.25  4946.0  349.76  5005.2  348.28
  5005.7  347.48  5010.7  347.48  5011.2  348.28  5102.0  349.59  5178.8  350.15
  5200.8  350.79  5266.9  350.79  5349.4  352.08  5481.6  352.00  5569.7  352.78
  5784.4  353.09  5806.4  353.65  5844.8  353.47  5916.6  354.11  5985.3  353.79
#Mann=3,-1,0
  4055.0     0.1       0  5005.2    0.07       0  5011.2     0.1       0
Bank Sta=5005.2,5011.2
Exp/Cntr=0.3,0.1

Type RM Length L Ch R = 1,15572,187,187,187
BEGIN DESCRIPTION:
UNT 093 in La Jarita Watershed 20.0
END DESCRIPTION:
XS GIS Cut Line= 3
      2098171.65     13426201.47      2097416.45     13426451.47
      2096640.39     13426790.02
#Sta/Elev= 30
  4213.5  351.38  4370.6  350.47  4465.7  350.92  4555.6  350.38  4592.6  350.74
  4631.3  350.28  4656.0  350.50  4799.9  350.03  4841.0  349.00  4909.7  348.22
  4996.5  346.30  4997.0  345.50  5002.0  345.50  5002.5  346.30  5034.1  347.05
  5097.9  347.75  5133.2  348.78  5217.9  348.97  5250.3  349.49  5279.2  349.49
  5316.1  350.21  5407.1  350.16  5477.4  350.87  5553.1  350.45  5675.6  350.41
  5733.4  350.93  5751.3  350.48  5803.6  350.87  5832.5  351.47  5855.7  351.19
#Mann=3,-1,0
  4213.5     0.1       0  4996.5    0.07       0  5002.5     0.1       0
Bank Sta=4996.5,5002.5
Exp/Cntr=0.3,0.1

Type RM Length L Ch R = 1,15385,301,301,301
BEGIN DESCRIPTION:
Mapping XS 3dc3d66f
END DESCRIPTION:
XS GIS Cut Line= 2
      2098280.69     13425932.72      2096554.98     13426599.39
#Sta/Elev= 30
  3970.9  350.99  3992.7  350.60  4022.0  350.78  4071.2  350.04  4135.9  350.00
  4215.6  349.28  4240.2  349.76  4270.2  349.58  4287.9  350.08  4349.3  348.74
  4502.3  348.61  4548.3  349.09  4597.5  348.58  4657.4  348.80  4796.5  348.02
  5011.7  345.07  5012.2  344.27  5017.2  344.27  5017.7  345.07  5050.0  345.85
  5069.2  345.57  5189.0  347.38  5359.9  348.90  5401.9  348.69  5413.5  349.08
  5540.9  349.60  5585.0  349.12  5625.4  349.27  5692.2  348.38  5820.9  348.86
#Mann=5,-1,0
  3970.9     0.1       0  3992.7    0.05       0  4135.9     0.1       0
  5011.7    0.07       0  5017.7     0.1       0
Bank Sta=5011.7,5017.7
Exp/Cntr=0.3,0.1

Type RM Length L Ch R = 1,15084,310,310,310
BEGIN DESCRIPTION:
Mapping XS 8652b8dc
END DESCRIPTION:
XS GIS Cut Line= 2
      2097798.08     13425832.02      2096513.32     13426304.25
#Sta/Elev= 30
  4327.1  346.80  4378.8  346.16  4439.7  346.47  4464.9  346.08  4490.0  346.32
  4495.3  346.75  4520.5  346.01  4525.8  346.44  4564.8  346.22  4581.4  345.38
  4682.0  345.50  4777.9  344.54  4814.6  344.67  4839.7  343.82  4863.1  343.98
  4900.7  343.45  4906.0  343.89  4998.6  341.89  4999.1  341.09  5004.1  341.09
  5004.6  341.89  5022.9  342.57  5103.3  343.94  5353.2  346.77  5453.0  346.61
  5508.7  345.37  5569.6  345.55  5594.8  344.62  5625.2  345.78  5695.9  347.20
#Mann=3,-1,0
  4327.1     0.1       0  4998.6    0.07       0  5004.6     0.1       0
Bank Sta=4998.6,5004.6
Exp/Cntr=0.3,0.1

Type RM Length L Ch R = 1,14774,345,345,345
BEGIN DESCRIPTION:
Mapping XS 79340707
END DESCRIPTION:
XS GIS Cut Line= 2
      2097648.74     13425606.33      2096566.22     13425960.24
#Sta/Elev= 30
  4360.4  345.83  4574.7  342.20  4616.8  342.05  4631.1  342.41  4721.5  341.88
  4753.4  342.28  4795.7  343.51  4806.2  343.43  4854.2  341.31  4869.3  341.28
  4918.0  339.71  4923.2  339.96  4974.5  339.54  4987.0  339.88  5010.6  339.46
  5011.1  338.66  5016.1  338.66  5016.6  339.46  5077.3  339.98  5114.5  341.29
  5173.0  341.13  5216.5  341.85  5236.7  341.41  5268.6  341.50  5273.8  341.92
  5337.6  341.35  5369.4  341.72  5406.6  341.36  5438.4  342.46  5499.3  343.22
#Mann=3,-1,0
  4360.4     0.1       0  5010.6    0.07       0  5016.6     0.1       0
Bank Sta=5010.6,5016.6
Exp/Cntr=0.3,0.1

Type RM Length L Ch R = 1,14429,227,227,227
BEGIN DESCRIPTION:
Mapping XS f8ea968f
END DESCRIPTION:
XS GIS Cut Line= 3
      2097475.18     13425470.91      2096957.78     13425505.63
      2096509.90     13425752.14
#Sta/Elev= 30
  4477.1  345.21  4557.5  341.29  4587.5  340.81  4737.9  338.99  4762.6  339.29
  4858.1  338.77  4938.3  337.43  4978.4  337.13  5004.6  336.26  5033.1  336.68
  5048.2  336.60  5052.9  336.21  5053.4  335.41  5058.4  335.41  5058.9  336.21
  5107.8  336.63  5135.8  337.24  5158.6  337.01  5189.3  337.29  5195.0  337.63
  5211.1  337.56  5216.8  338.04  5248.9  338.05  5284.2  338.67  5336.1  340.59
  5357.8  340.88  5373.9  341.80  5401.4  342.04  5423.2  342.73  5506.9  343.57
#Mann=3,-1,0
  4477.1     0.1       0  5052.9    0.07       0  5058.9     0.1       0
Bank Sta=5052.9,5058.9
Exp/Cntr=0.3,0.1

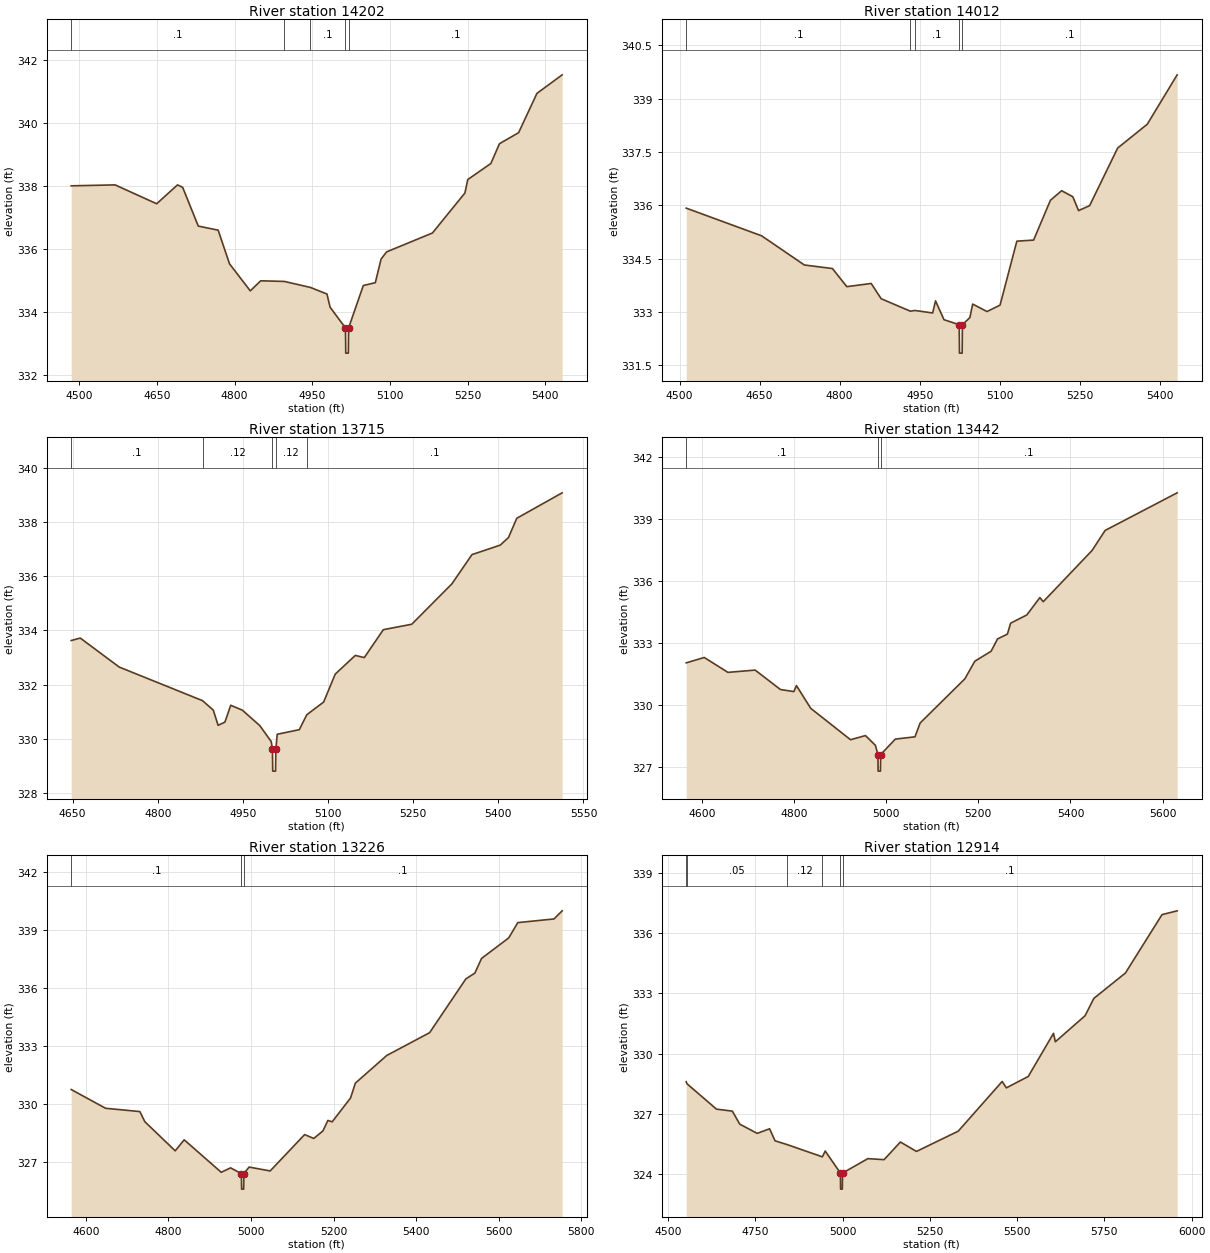
Type RM Length L Ch R = 1,14202,190,190,190
BEGIN DESCRIPTION:
Mapping XS 38317f3c
END DESCRIPTION:
XS GIS Cut Line= 4
      2097329.30     13425293.83      2096874.45     13425335.49
      2096627.92     13425443.13      2096430.02     13425543.82
#Sta/Elev= 30
  4484.7  338.01  4569.4  338.04  4649.7  337.44  4689.9  338.04  4699.9  337.96
  4730.0  336.73  4768.4  336.60  4790.3  335.53  4830.4  334.67  4850.5  334.99
  4896.2  334.97  4946.3  334.78  4978.4  334.57  4984.5  334.15  5014.2  333.49
  5014.7  332.69  5019.7  332.69  5020.2  333.49  5048.6  334.84  5071.8  334.93
  5082.9  335.68  5093.6  335.91  5182.0  336.51  5244.7  337.78  5250.3  338.21
  5294.8  338.72  5311.5  339.35  5348.4  339.70  5383.8  340.95  5432.5  341.54
#Mann=5,-1,0
  4484.7     0.1       0  4896.2    0.12       0  4946.3     0.1       0
  5014.2    0.07       0  5020.2     0.1       0
Bank Sta=5014.2,5020.2
Exp/Cntr=0.3,0.1

Type RM Length L Ch R = 1,14012,297,297,297
BEGIN DESCRIPTION:
Mapping XS 8a110260
END DESCRIPTION:
XS GIS Cut Line= 3
      2097256.40     13425109.80      2097020.28     13425109.80
      2096368.77     13425317.73
#Sta/Elev= 30
  4512.5  335.92  4653.9  335.14  4733.9  334.32  4786.5  334.22  4813.5  333.71
  4859.1  333.80  4877.9  333.37  4932.5  333.02  4941.1  333.04  4974.4  332.97
  4979.7  333.31  4995.6  332.78  5024.1  332.64  5024.6  331.84  5029.6  331.84
  5030.1  332.64  5044.1  332.84  5049.3  333.22  5076.2  333.01  5100.6  333.19
  5132.1  334.99  5163.5  335.02  5195.0  336.14  5216.0  336.41  5237.0  336.24
  5247.7  335.85  5268.5  335.99  5321.0  337.61  5376.5  338.28  5432.5  339.67
#Mann=5,-1,0
  4512.5     0.1       0  4932.5    0.12       0  4941.1     0.1       0
  5024.1    0.07       0  5030.1     0.1       0
Bank Sta=5024.1,5030.1
Exp/Cntr=0.3,0.1

Type RM Length L Ch R = 1,13715,273,273,273
BEGIN DESCRIPTION:
Mapping XS b73605ac
END DESCRIPTION:
XS GIS Cut Line= 4
      2097030.75     13424936.20      2096829.31     13424897.99
      2096457.78     13424977.86      2096235.57     13425147.99
#Sta/Elev= 30
  4647.6  333.63  4663.6  333.72  4732.2  332.65  4879.0  331.41  4897.9  331.06
  4906.4  330.50  4918.4  330.62  4928.6  331.24  4949.1  331.06  4979.8  330.49
  5000.0  329.90  5002.1  329.61  5002.6  328.81  5007.6  328.81  5008.1  329.61
  5010.5  330.17  5049.4  330.34  5062.6  330.89  5092.3  331.36  5112.7  332.39
  5148.1  333.08  5163.9  333.00  5197.5  334.03  5247.5  334.23  5318.2  335.72
  5353.6  336.80  5403.4  337.15  5417.9  337.43  5432.5  338.14  5512.5  339.08
#Mann=5,-1,0
  4647.6     0.1       0  4879.0    0.12       0  5002.1    0.07       0
  5008.1    0.12       0  5062.6     0.1       0
Bank Sta=5002.1,5008.1
Exp/Cntr=0.3,0.1

Type RM Length L Ch R = 1,13442,216,216,216
BEGIN DESCRIPTION:
Mapping XS 893484fa
END DESCRIPTION:
XS GIS Cut Line= 4
      2096950.80     13424748.67      2096725.14     13424644.52
      2096443.89     13424759.11      2096093.17     13425134.14
#Sta/Elev= 30
  4565.9  332.05  4605.1  332.31  4656.5  331.59  4715.5  331.70  4770.5  330.76
  4799.7  330.66  4805.2  330.95  4836.2  329.85  4922.6  328.33  4955.0  328.53
  4976.6  328.06  4982.0  327.61  4982.5  326.81  4987.5  326.81  4988.0  327.61
  5019.8  328.36  5062.5  328.47  5073.7  329.14  5170.9  331.28  5192.4  332.13
  5227.6  332.61  5241.8  333.21  5263.1  333.44  5270.1  333.97  5305.3  334.37
  5333.6  335.21  5340.9  335.01  5446.9  337.49  5475.3  338.46  5631.6  340.28
#Mann=3,-1,0
  4565.9     0.1       0  4982.0    0.07       0  4988.0     0.1       0
Bank Sta=4982,4988
Exp/Cntr=0.3,0.1

Type RM Length L Ch R = 1,13226,312,312,312
BEGIN DESCRIPTION:
Mapping XS c33287a6
END DESCRIPTION:
XS GIS Cut Line= 4
      2096864.01     13424543.82      2096614.03     13424460.49
      2096259.87     13424641.05      2096009.93     13425106.22
#Sta/Elev= 30
  4564.5  330.76  4647.8  329.79  4730.8  329.62  4742.7  329.10  4816.4  327.59
  4838.1  328.16  4927.9  326.48  4950.4  326.71  4976.7  326.41  4977.2  325.61
  4982.2  325.61  4982.7  326.41  4995.3  326.75  5046.4  326.55  5129.8  328.43
  5152.0  328.23  5174.2  328.62  5186.1  329.16  5196.5  329.09  5241.0  330.32
  5252.7  331.09  5328.7  332.52  5432.6  333.70  5520.3  336.48  5542.2  336.78
  5558.4  337.54  5624.2  338.60  5646.1  339.39  5733.8  339.58  5753.6  340.00
#Mann=3,-1,0
  4564.5     0.1       0  4976.7    0.07       0  4982.7     0.1       0
Bank Sta=4976.7,4982.7
Exp/Cntr=0.3,0.1

Type RM Length L Ch R = 1,12914,310,310,310
BEGIN DESCRIPTION:
Mapping XS a9095ef2
END DESCRIPTION:
XS GIS Cut Line= 4
      2096829.29     13424380.62      2096541.12     13424207.02
      2096138.34     13424384.11      2095916.13     13424974.35
#Sta/Elev= 30
  4551.4  328.60  4553.4  328.50  4638.1  327.23  4683.6  327.13  4705.0  326.48
  4754.9  326.02  4790.4  326.25  4806.0  325.65  4840.9  325.46  4941.7  324.85
  4949.8  325.14  4993.4  324.04  4993.9  323.24  4998.9  323.24  4999.4  324.04
  5072.0  324.76  5118.6  324.71  5165.3  325.59  5211.3  325.12  5331.0  326.13
  5457.0  328.61  5469.0  328.29  5531.8  328.86  5604.1  331.01  5609.4  330.59
  5694.7  331.89  5719.6  332.75  5810.3  334.02  5915.1  336.93  5958.5  337.12
#Mann=6,-1,0
  4551.4     0.1       0  4553.4    0.05       0  4840.9    0.12       0
  4941.7     0.1       0  4993.4    0.07       0  4999.4     0.1       0
Bank Sta=4993.4,4999.4
Exp/Cntr=0.3,0.1

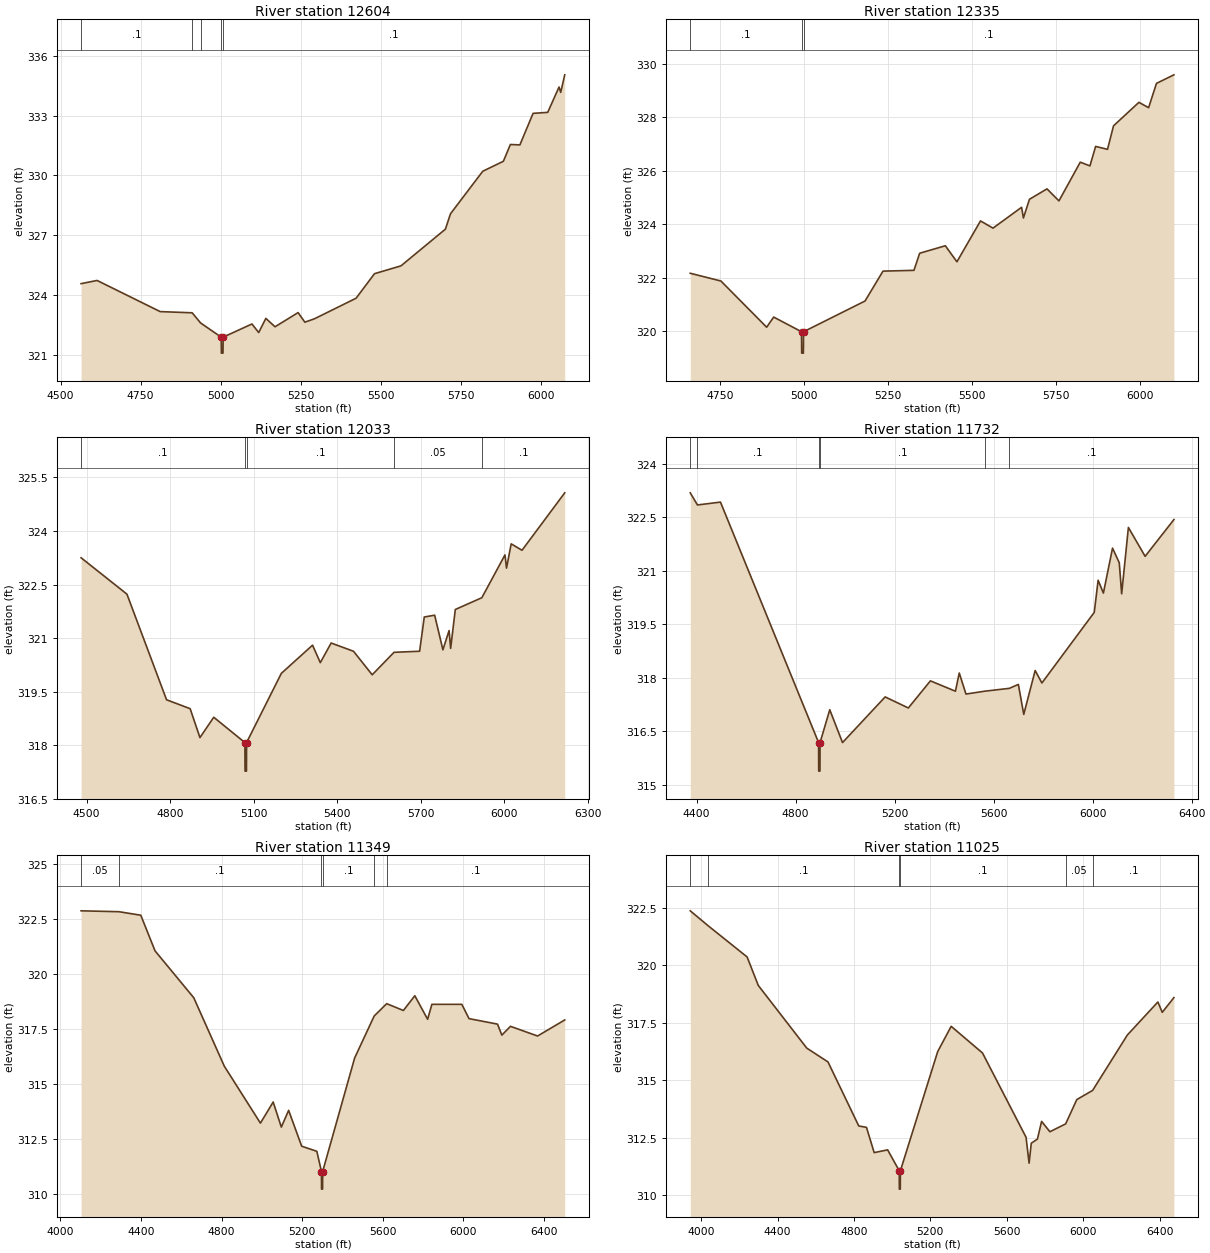
Type RM Length L Ch R = 1,12604,269,269,269
BEGIN DESCRIPTION:
Mapping XS e77ebd3f
END DESCRIPTION:
XS GIS Cut Line= 4
      2096697.34     13424019.51      2096454.31     13423911.88
      2096016.81     13424203.55      2095836.46     13424900.69
#Sta/Elev= 30
  4563.9  324.58  4613.9  324.74  4811.1  323.18  4911.0  323.12  4937.5  322.61
  5001.9  321.90  5002.4  321.10  5007.4  321.10  5007.9  321.90  5098.0  322.56
  5119.0  322.13  5141.4  322.84  5170.1  322.42  5242.2  323.13  5263.3  322.65
  5293.3  322.82  5423.4  323.85  5481.0  325.08  5563.6  325.47  5702.6  327.31
  5718.5  328.08  5819.3  330.21  5883.8  330.71  5905.7  331.55  5935.4  331.53
  5976.6  333.11  6022.4  333.16  6057.8  334.43  6063.0  334.16  6075.6  335.04
#Mann=5,-1,0
  4563.9     0.1       0  4911.0    0.12       0  4937.5     0.1       0
  5001.9    0.07       0  5007.9     0.1       0
Bank Sta=5001.9,5007.9
Exp/Cntr=0.3,0.1

Type RM Length L Ch R = 1,12335,302,302,302
BEGIN DESCRIPTION:
Mapping XS b979fb4b
END DESCRIPTION:
XS GIS Cut Line= 3
      2096364.00     13423696.63      2095954.31     13423991.74
      2095579.65     13424848.60
#Sta/Elev= 30
  4661.4  322.16  4752.7  321.87  4888.9  320.14  4909.8  320.52  4992.7  319.97
  4993.2  319.17  4998.2  319.17  4998.7  319.97  5181.7  321.12  5235.3  322.24
  5327.5  322.27  5344.5  322.91  5420.9  323.19  5455.4  322.59  5525.6  324.12
  5562.8  323.85  5648.0  324.63  5653.4  324.23  5671.4  324.93  5723.6  325.32
  5759.2  324.87  5822.7  326.32  5851.5  326.18  5868.4  326.91  5903.8  326.80
  5921.7  327.68  5997.3  328.56  6026.2  328.36  6049.6  329.27  6101.5  329.59
#Mann=3,-1,0
  4661.4     0.1       0  4992.7    0.07       0  4998.7     0.1       0
Bank Sta=4992.7,4998.7
Exp/Cntr=0.3,0.1

Type RM Length L Ch R = 1,12033,301,301,301
BEGIN DESCRIPTION:
Mapping XS 5740e3b4
END DESCRIPTION:
XS GIS Cut Line= 3
      2096343.23     13423342.41      2095777.23     13423804.24
      2095323.27     13424701.76
#Sta/Elev= 30
  4480.6  323.25  4645.2  322.23  4787.4  319.27  4872.1  319.02  4907.3  318.21
  4956.8  318.78  5068.7  318.07  5069.2  317.27  5074.2  317.27  5074.7  318.07
  5199.5  320.01  5311.5  320.80  5339.4  320.31  5378.3  320.86  5458.5  320.63
  5525.7  319.97  5604.0  320.60  5695.9  320.63  5712.6  321.59  5749.9  321.64
  5779.5  320.67  5801.7  321.21  5807.3  320.71  5824.0  321.80  5919.3  322.13
  6002.3  323.33  6007.9  322.96  6024.6  323.64  6063.5  323.46  6216.9  325.07
#Mann=5,-1,0
  4480.6     0.1       0  5068.7    0.07       0  5074.7     0.1       0
  5604.0    0.05       0  5919.3     0.1       0
Bank Sta=5068.7,5074.7
Exp/Cntr=0.3,0.1

Type RM Length L Ch R = 1,11732,383,383,383
BEGIN DESCRIPTION:
Mapping XS 9e5ce599
END DESCRIPTION:
XS GIS Cut Line= 3
      2096294.90     13423165.26      2095562.30     13423637.46
      2095003.26     13424564.56
#Sta/Elev= 30
  4374.1  323.18  4403.1  322.84  4496.2  322.92  4892.6  316.18  4893.1  315.38
  4898.1  315.38  4898.6  316.18  4937.8  317.10  4989.3  316.18  5161.6  317.46
  5255.2  317.15  5344.5  317.91  5445.5  317.62  5461.0  318.13  5488.2  317.54
  5563.6  317.62  5663.4  317.70  5699.8  317.81  5721.6  316.97  5767.7  318.20
  5794.9  317.85  6006.5  319.83  6022.1  320.73  6043.4  320.37  6080.3  321.63
  6107.5  321.22  6117.2  320.35  6144.4  322.21  6212.0  321.40  6328.3  322.43
#Mann=6,-1,0
  4374.1    0.05       0  4403.1     0.1       0  4892.6    0.07       0
  4898.6     0.1       0  5563.6    0.05       0  5663.4     0.1       0
Bank Sta=4892.6,4898.6
Exp/Cntr=0.3,0.1

Type RM Length L Ch R = 1,11349,324,324,324
BEGIN DESCRIPTION:
Mapping XS a8a8bfa4
END DESCRIPTION:
XS GIS Cut Line= 3
      2096458.09     13423061.08      2094888.69     13423290.24
      2094343.55     13423894.41
#Sta/Elev= 30
  4103.3  322.86  4291.0  322.82  4399.5  322.66  4470.2  321.04  4662.3  318.91
  4813.8  315.80  4993.1  313.21  5056.4  314.17  5096.8  313.03  5133.1  313.79
  5197.9  312.16  5273.0  311.93  5295.9  311.01  5296.4  310.21  5301.4  310.21
  5301.9  311.01  5460.6  316.17  5557.6  318.08  5619.6  318.64  5702.4  318.33
  5759.2  319.00  5822.7  317.93  5843.9  318.61  5992.4  318.61  6028.2  317.96
  6169.5  317.71  6191.1  317.21  6233.7  317.61  6368.3  317.17  6503.1  317.90
#Mann=6,-1,0
  4103.3    0.05       0  4291.0     0.1       0  5295.9    0.07       0
  5301.9     0.1       0  5557.6    0.05       0  5619.6     0.1       0
Bank Sta=5295.9,5301.9
Exp/Cntr=0.3,0.1

Type RM Length L Ch R = 1,11025,467,467,467
BEGIN DESCRIPTION:
Mapping XS 2cde6ea0
END DESCRIPTION:
XS GIS Cut Line= 3
      2096350.45     13422936.08      2094885.21     13423116.63
      2093961.59     13422606.20
#Sta/Elev= 30
  3943.2  322.38  4038.3  321.72  4240.9  320.37  4299.3  319.13  4553.2  316.40
  4664.1  315.80  4825.3  313.01  4865.6  312.95  4905.9  311.85  4976.4  311.97
  5037.1  311.06  5037.6  310.26  5042.6  310.26  5043.1  311.06  5238.4  316.25
  5308.9  317.35  5472.9  316.19  5700.8  312.52  5716.8  311.39  5728.3  312.26
  5760.4  312.44  5782.2  313.21  5825.7  312.76  5908.0  313.10  5966.6  314.16
  6049.4  314.56  6231.0  316.97  6390.9  318.41  6413.8  317.96  6474.8  318.60
#Mann=6,-1,0
  3943.2    0.05       0  4038.3     0.1       0  5037.1    0.07       0
  5043.1     0.1       0  5908.0    0.05       0  6049.4     0.1       0
Bank Sta=5037.1,5043.1
Exp/Cntr=0.3,0.1

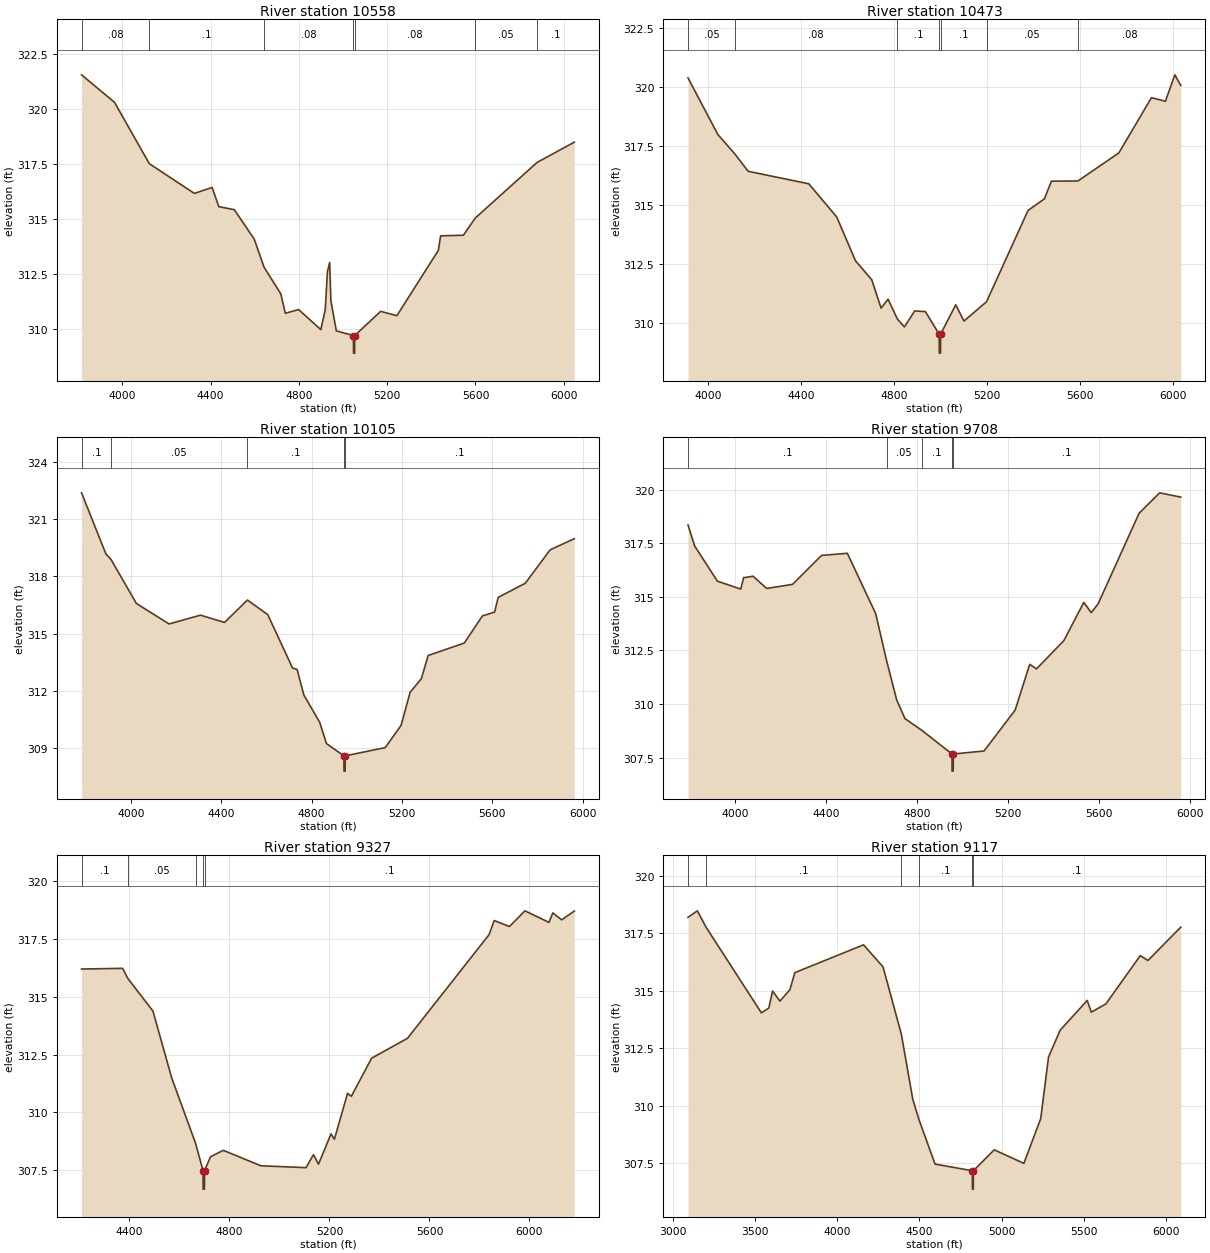
Type RM Length L Ch R = 1,10558,85,85,85
BEGIN DESCRIPTION:
Mapping XS da1ee8ce
END DESCRIPTION:
XS GIS Cut Line= 4
      2096343.55     13422756.10      2095336.60     13422651.93
      2094722.02     13422589.43      2094118.90     13422592.90
#Sta/Elev= 30
  3814.8  321.56  3964.1  320.31  4122.1  317.52  4326.1  316.17  4406.5  316.44
  4436.7  315.57  4507.0  315.43  4597.5  314.09  4642.2  312.81  4718.1  311.60
  4738.3  310.72  4798.6  310.89  4899.1  309.98  4919.2  310.88  4929.2  312.62
  4939.3  313.03  4944.7  311.30  4969.5  309.92  5046.9  309.71  5047.4  308.91
  5052.4  308.91  5052.9  309.71  5170.5  310.81  5243.7  310.61  5431.8  313.58
  5442.1  314.24  5545.5  314.27  5599.0  315.05  5879.7  317.58  6048.0  318.50
#Mann=7,-1,0
  3814.8    0.08       0  4122.1     0.1       0  4642.2    0.08       0
  5046.9    0.07       0  5052.9    0.08       0  5599.0    0.05       0
  5879.7     0.1       0
Bank Sta=5046.9,5052.9
Exp/Cntr=0.3,0.1

Type RM Length L Ch R = 1,10473,368,368,368
BEGIN DESCRIPTION:
Mapping XS 494401a0
END DESCRIPTION:
XS GIS Cut Line= 4
      2096242.87     13422648.46      2095437.30     13422575.54
      2094735.91     13422509.57      2094129.09     13422467.96
#Sta/Elev= 30
  3913.9  320.38  4042.3  317.98  4116.8  317.14  4172.8  316.42  4433.9  315.89
  4554.4  314.48  4634.7  312.63  4705.0  311.82  4745.2  310.62  4775.3  311.00
  4815.1  310.16  4845.6  309.82  4889.8  310.50  4936.0  310.47  4995.4  309.51
  4995.9  308.71  5000.9  308.71  5001.4  309.51  5066.6  310.76  5102.0  310.07
  5199.3  310.89  5377.9  314.76  5448.2  315.25  5478.3  316.00  5592.8  316.01
  5769.0  317.20  5909.3  319.54  5969.4  319.39  6010.1  320.51  6035.5  320.06
#Mann=7,-1,0
  3913.9    0.05       0  4116.8    0.08       0  4815.1     0.1       0
  4995.4    0.07       0  5001.4     0.1       0  5199.3    0.05       0
  5592.8    0.08       0
Bank Sta=4995.4,5001.4
Exp/Cntr=0.3,0.1

Type RM Length L Ch R = 1,10105,397,397,397
BEGIN DESCRIPTION:
Mapping XS eff50325
END DESCRIPTION:
XS GIS Cut Line= 4
      2096367.89     13422513.06      2095687.30     13422217.90
      2095027.58     13422200.54      2094248.15     13422217.86
#Sta/Elev= 30
  3781.5  322.37  3889.0  319.18  3912.6  318.87  4024.4  316.58  4168.9  315.51
  4307.8  315.97  4414.5  315.59  4515.9  316.76  4605.7  316.00  4715.7  313.20
  4735.7  313.13  4765.7  311.79  4835.7  310.37  4865.8  309.25  4942.8  308.61
  4943.3  307.81  4948.3  307.81  4948.8  308.61  5125.8  309.04  5195.9  310.20
  5235.9  311.93  5285.9  312.65  5315.9  313.86  5475.9  314.51  5556.0  315.93
  5610.0  316.13  5626.0  316.90  5746.0  317.64  5856.0  319.39  5962.9  319.97
#Mann=5,-1,0
  3781.5     0.1       0  3912.6    0.05       0  4515.9     0.1       0
  4942.8    0.07       0  4948.8     0.1       0
Bank Sta=4942.8,4948.8
Exp/Cntr=0.3,0.1

Type RM Length L Ch R = 1,9708,381,381,381
BEGIN DESCRIPTION:
UNT 093 in La Jarita Watershed 11.0
END DESCRIPTION:
XS GIS Cut Line= 3
      2096312.25     13422266.50      2095190.80     13421824.54
      2094232.40     13421888.04
#Sta/Elev= 30
  3794.6  318.35  3823.9  317.37  3923.7  315.73  4026.6  315.36  4038.9  315.89
  4080.8  315.96  4140.3  315.39  4254.0  315.58  4381.3  316.93  4494.9  317.03
  4619.3  314.22  4667.6  312.02  4711.5  310.20  4748.3  309.32  4822.7  308.77
  4954.8  307.67  4955.3  306.87  4960.3  306.87  4960.8  307.67  5096.0  307.81
  5232.6  309.72  5296.4  311.85  5326.5  311.64  5446.8  312.96  5534.2  314.74
  5567.0  314.26  5597.1  314.67  5777.5  318.90  5867.7  319.85  5960.5  319.65
#Mann=5,-1,0
  3794.6     0.1       0  4667.6    0.05       0  4822.7     0.1       0
  4954.8    0.07       0  4960.8     0.1       0
Bank Sta=4954.8,4960.8
Exp/Cntr=0.3,0.1

Type RM Length L Ch R = 1,9327,210,210,210
BEGIN DESCRIPTION:
Mapping XS 4f988c59
END DESCRIPTION:
XS GIS Cut Line= 4
      2095886.67     13421650.46      2095391.87     13421489.86
      2094901.42     13421459.48      2093960.86     13421650.19
#Sta/Elev= 30
  4208.2  316.21  4372.3  316.24  4393.5  315.80  4493.8  314.39  4569.3  311.48
  4664.2  308.67  4694.2  307.48  4694.7  306.68  4699.8  306.68  4700.3  307.48
  4723.9  308.08  4775.4  308.36  4925.7  307.69  5106.0  307.61  5136.1  308.17
  5156.1  307.76  5206.2  309.07  5219.8  308.84  5272.5  310.83  5287.6  310.70
  5368.7  312.35  5512.0  313.21  5838.6  317.70  5859.0  318.31  5920.2  318.05
  5981.9  318.73  6078.1  318.23  6093.6  318.64  6128.8  318.34  6179.5  318.72
#Mann=5,-1,0
  4208.2     0.1       0  4393.5    0.05       0  4664.2     0.1       0
  4694.2    0.07       0  4700.3     0.1       0
Bank Sta=4694.2,4700.3
Exp/Cntr=0.3,0.1

Type RM Length L Ch R = 1,9117,474,474,474
BEGIN DESCRIPTION:
Mapping XS 7e9c1abe
END DESCRIPTION:
XS GIS Cut Line= 4
      2096874.98     13421922.65      2095448.29     13421238.13
      2094805.93     13421285.87      2094050.76     13421468.15
#Sta/Elev= 30
  3089.2  318.20  3145.9  318.48  3200.8  317.75  3536.5  314.04  3581.8  314.25
  3604.4  314.99  3649.7  314.55  3710.3  315.05  3740.3  315.79  4159.1  317.00
  4277.9  316.04  4389.6  313.11  4459.1  310.28  4497.1  309.39  4595.0  307.46
  4822.3  307.17  4822.8  306.37  4827.9  306.37  4828.4  307.17  4955.7  308.08
  5136.2  307.49  5239.0  309.44  5286.6  312.12  5357.8  313.29  5522.4  314.58
  5547.3  314.07  5636.2  314.43  5845.6  316.53  5892.8  316.32  6092.6  317.77
#Mann=6,-1,0
  3089.2    0.05       0  3200.8     0.1       0  4389.6    0.05       0
  4497.1     0.1       0  4822.3    0.07       0  4828.4     0.1       0
Bank Sta=4822.3,4828.4
Exp/Cntr=0.3,0.1

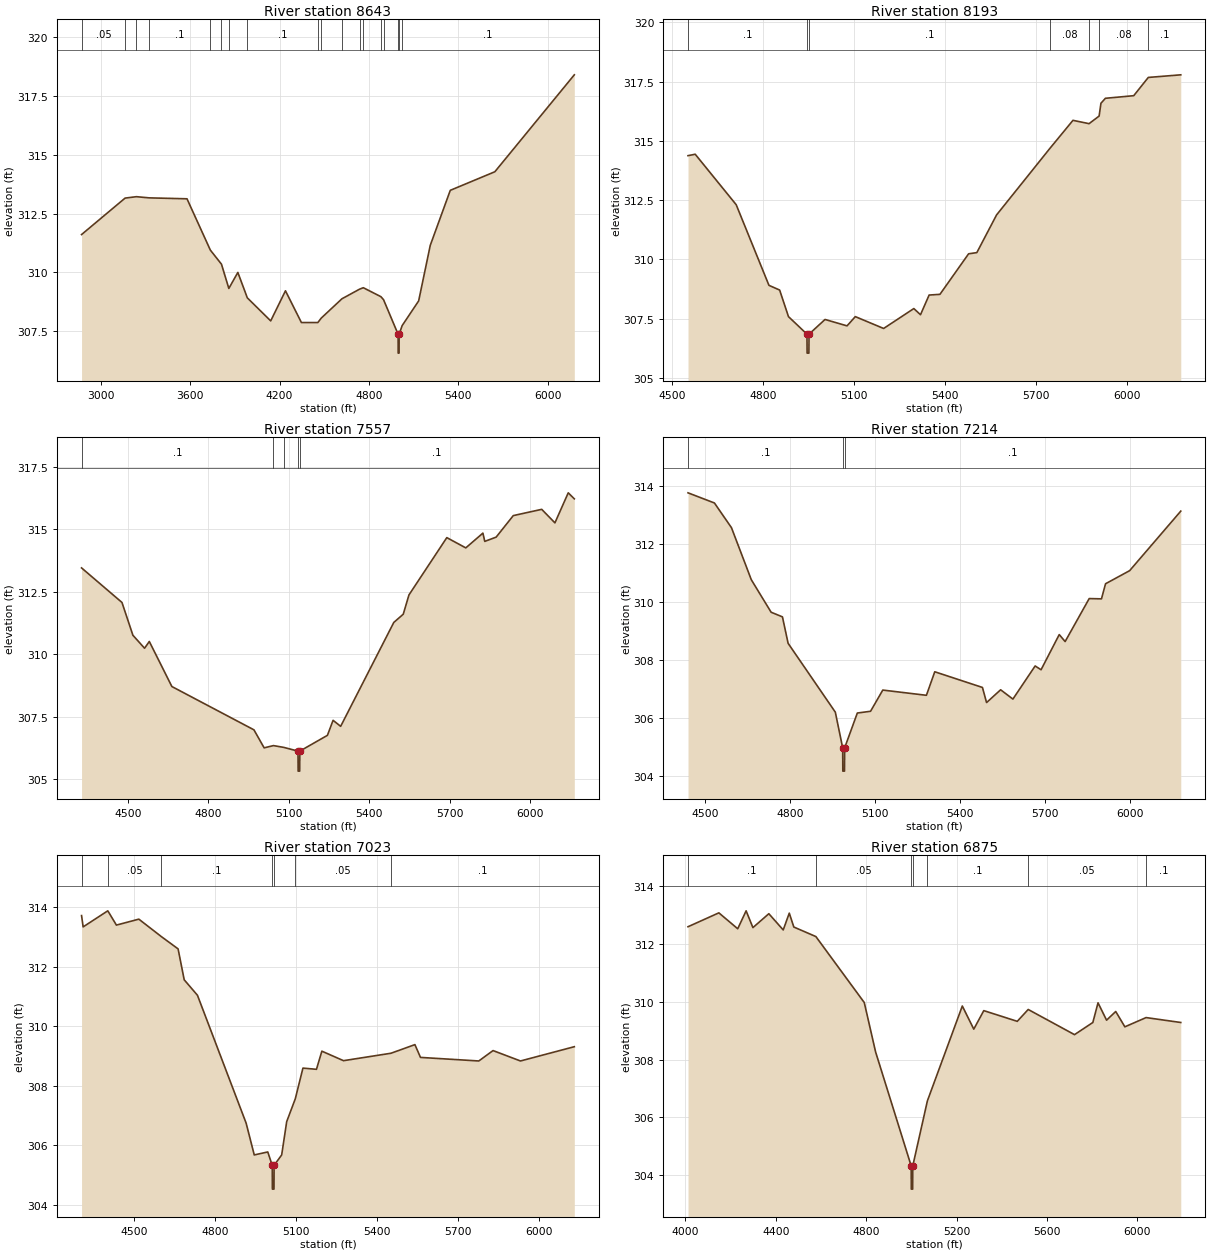
Type RM Length L Ch R = 1,8643,450,450,450
BEGIN DESCRIPTION:
Mapping XS be138fe3
END DESCRIPTION:
XS GIS Cut Line= 4
      2096322.29     13419246.11      2095187.88     13420639.17
      2094680.06     13421094.90      2093908.71     13421398.24
#Sta/Elev= 30
  2870.7  311.61  3163.1  313.16  3238.8  313.22  3324.8  313.17  3578.6  313.13
  3735.2  310.95  3810.0  310.35  3859.3  309.32  3919.9  310.00  3983.4  308.92
  4140.4  307.94  4239.5  309.22  4346.5  307.87  4456.9  307.87  4479.9  308.06
  4618.6  308.88  4737.2  309.29  4762.2  309.35  4880.0  308.97  4898.0  308.84
  4995.7  307.37  4996.2  306.57  5002.0  306.57  5002.5  307.37  5022.8  307.74
  5133.6  308.79  5211.4  311.15  5345.9  313.49  5645.1  314.28  6178.4  318.40
#Mann=18,-1,0
  2870.7    0.05       0  3163.1     0.1       0  3238.8    0.05       0
  3324.8     0.1       0  3735.2    0.05       0  3810.0     0.1       0
  3859.3    0.05       0  3983.4     0.1       0  4456.9    0.05       0
  4479.9     0.1       0  4618.6    0.05       0  4737.2     0.1       0
  4762.2    0.05       0  4880.0     0.1       0  4898.0    0.05       0
  4995.7    0.04       0  5002.5    0.05       0  5022.8     0.1       0
Bank Sta=4995.7,5002.5
Exp/Cntr=0.3,0.1

Type RM Length L Ch R = 1,8193,636,636,636
BEGIN DESCRIPTION:
Mapping XS 01ae5137
END DESCRIPTION:
XS GIS Cut Line= 3
      2095053.32     13420109.66      2094617.24     13420674.43
      2093879.31     13421205.51
#Sta/Elev= 30
  4553.5  314.38  4577.2  314.44  4712.2  312.31  4820.0  308.91  4855.3  308.71
  4884.3  307.59  4945.2  306.85  4945.7  306.05  4951.5  306.05  4952.0  306.85
  5004.7  307.47  5077.2  307.20  5104.4  307.59  5197.7  307.09  5297.1  307.93
  5319.1  307.67  5347.5  308.50  5383.1  308.53  5477.5  310.24  5504.6  310.29
  5569.6  311.88  5745.4  314.69  5821.2  315.87  5874.2  315.73  5907.3  316.05
  5913.3  316.59  5928.0  316.80  6021.3  316.91  6069.3  317.68  6176.2  317.79
#Mann=7,-1,0
  4553.5     0.1       0  4945.2    0.07       0  4952.0     0.1       0
  5745.4    0.08       0  5874.2     0.1       0  5907.3    0.08       0
  6069.3     0.1       0
Bank Sta=4945.2,4952
Exp/Cntr=0.3,0.1

Type RM Length L Ch R = 1,7557,343,343,343
BEGIN DESCRIPTION:
Mapping XS dd30ffc5
END DESCRIPTION:
XS GIS Cut Line= 3
      2094902.82     13420164.40      2094208.41     13420303.28
      2093427.18     13421119.24
#Sta/Elev= 30
  4326.8  313.45  4477.5  312.07  4518.3  310.76  4561.8  310.24  4579.5  310.51
  4663.7  308.71  4969.7  306.98  5007.8  306.26  5042.4  306.35  5080.4  306.28
  5134.1  306.13  5134.6  305.33  5140.4  305.33  5140.9  306.13  5243.8  306.76
  5264.9  307.36  5293.2  307.12  5491.3  311.27  5526.6  311.60  5547.9  312.37
  5689.1  314.66  5759.9  314.25  5823.7  314.84  5830.7  314.51  5873.1  314.68
  5937.0  315.54  6043.0  315.79  6092.3  315.25  6142.0  316.45  6164.6  316.21
#Mann=5,-1,0
  4326.8     0.1       0  5042.4    0.12       0  5080.4     0.1       0
  5134.1    0.07       0  5140.9     0.1       0
Bank Sta=5134.1,5140.9
Exp/Cntr=0.3,0.1

Type RM Length L Ch R = 1,7214,191,191,191
BEGIN DESCRIPTION:
Mapping XS 559e22a7
END DESCRIPTION:
XS GIS Cut Line= 4
      2094728.32     13419990.41      2094235.29     13419979.99
      2093849.88     13420136.24      2093335.99     13420789.02
#Sta/Elev= 30
  4439.5  313.75  4532.8  313.40  4592.9  312.55  4662.9  310.76  4732.9  309.64
  4772.9  309.48  4792.9  308.57  4959.6  306.20  4985.6  304.97  4986.1  304.17
  4992.0  304.17  4992.5  304.97  5037.3  306.17  5084.0  306.23  5127.2  306.96
  5281.2  306.78  5310.7  307.59  5479.1  307.05  5493.6  306.53  5543.3  306.97
  5586.6  306.65  5665.1  307.79  5686.0  307.66  5750.2  308.87  5771.0  308.63
  5856.0  310.11  5899.3  310.10  5913.7  310.62  5998.7  311.07  6179.3  313.12
#Mann=3,-1,0
  4439.5     0.1       0  4985.6    0.07       0  4992.5     0.1       0
Bank Sta=4985.6,4992.5
Exp/Cntr=0.3,0.1

Type RM Length L Ch R = 1,7023,148,148,148
BEGIN DESCRIPTION:
Mapping XS 097ebe13
END DESCRIPTION:
XS GIS Cut Line= 4
      2094839.44     13419910.54      2094450.57     13419802.91
      2093773.49     13419837.63      2093051.23     13420011.25
#Sta/Elev= 30
  4305.7  313.72  4311.6  313.34  4402.9  313.88  4434.8  313.40  4517.8  313.60
  4601.6  313.01  4663.1  312.60  4685.8  311.56  4734.8  311.04  4915.0  306.74
  4945.1  305.67  4995.1  305.77  5011.7  305.32  5012.2  304.52  5018.1  304.52
  5018.6  305.32  5046.6  305.67  5065.2  306.79  5097.1  307.56  5125.3  308.59
  5175.4  308.55  5195.4  309.16  5275.5  308.84  5451.3  309.09  5539.9  309.38
  5560.5  308.95  5776.4  308.83  5829.1  309.18  5930.7  308.83  6130.0  309.31
#Mann=7,-1,0
  4305.7     0.1       0  4402.9    0.05       0  4601.6     0.1       0
  5011.7    0.07       0  5018.6     0.1       0  5097.1    0.05       0
  5451.3     0.1       0
Bank Sta=5011.7,5018.6
Exp/Cntr=0.3,0.1

Type RM Length L Ch R = 1,6875,240,240,240
BEGIN DESCRIPTION:
UNT 093 in La Jarita Watershed 9.0
END DESCRIPTION:
XS GIS Cut Line= 3
      2095120.71     13419771.66      2094121.61     13419671.94
      2092960.97     13419858.47
#Sta/Elev= 30
  4012.2  312.59  4148.6  313.07  4232.1  312.52  4269.2  313.14  4299.3  312.56
  4369.7  313.04  4433.3  312.48  4460.1  313.06  4480.2  312.58  4577.8  312.25
  4791.8  309.97  4842.0  308.26  4999.4  304.32  4999.9  303.52  5005.8  303.52
  5006.3  304.32  5071.0  306.57  5225.5  309.85  5276.2  309.05  5320.5  309.69
  5468.6  309.32  5516.9  309.73  5721.8  308.86  5802.8  309.28  5825.8  309.96
  5863.6  309.36  5904.1  309.66  5944.5  309.13  6038.4  309.45  6191.8  309.28
#Mann=7,-1,0
  4012.2     0.1       0  4577.8    0.05       0  4999.4    0.04       0
  5006.3    0.05       0  5071.0     0.1       0  5516.9    0.05       0
  6038.4     0.1       0
Bank Sta=4999.4,5006.3
Exp/Cntr=0.3,0.1