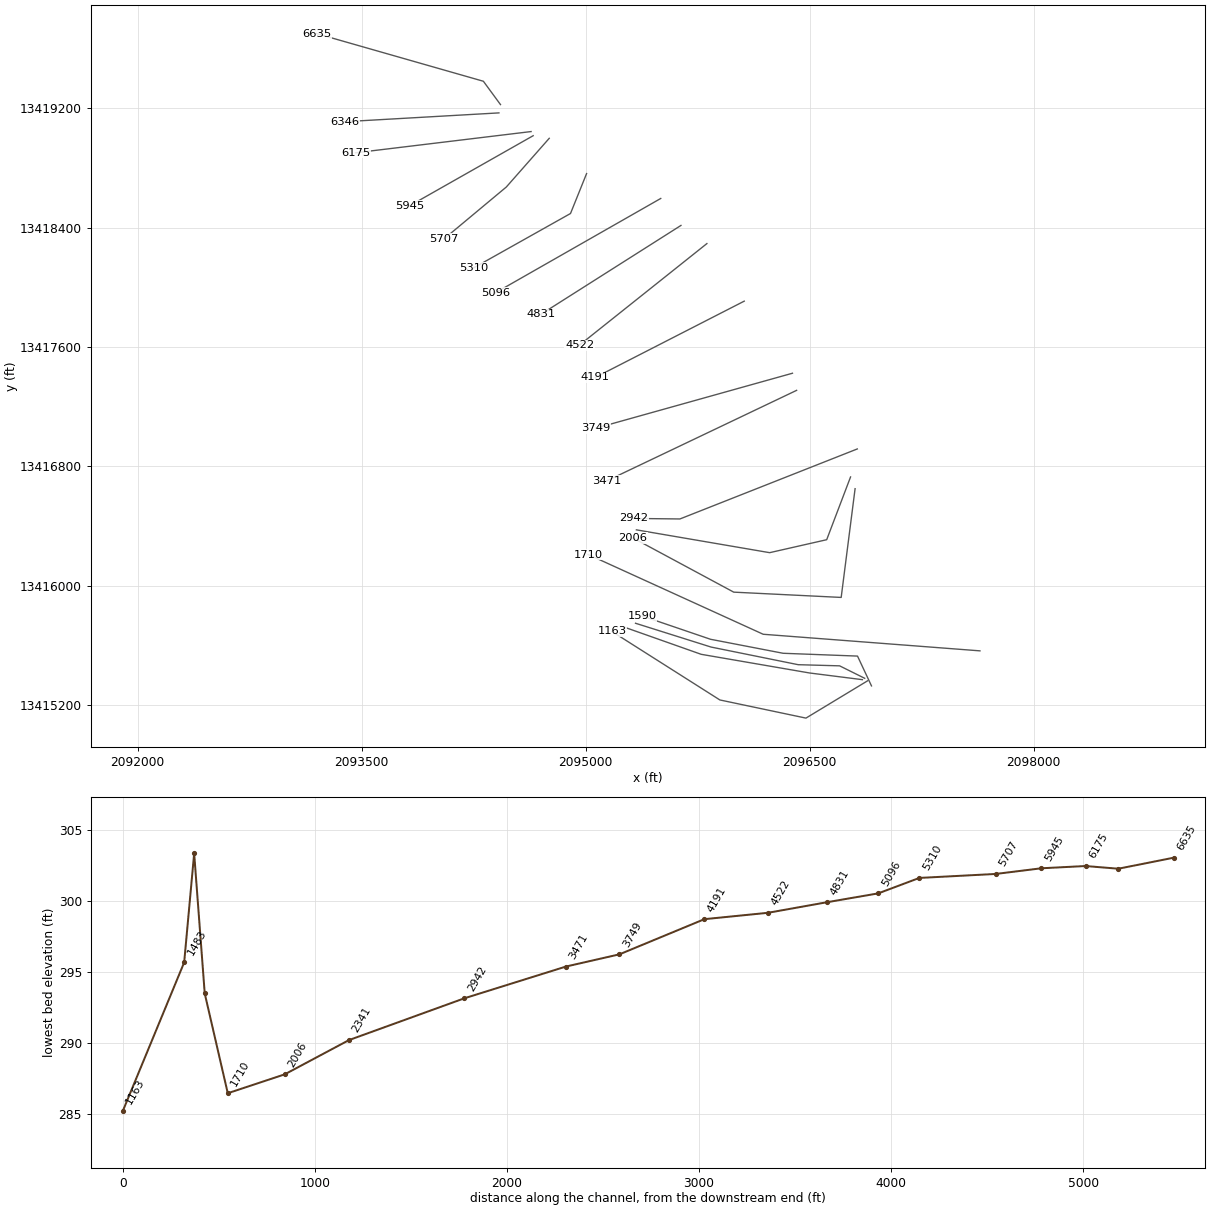
HEC-RAS study UNT 093 in La Jarita Watershed.prj: UNT 093 in La Jarita Watershed Base Level Engineering

--- UNT 093 in La Jarita Watershed.g01 (geometry) --- (continued)

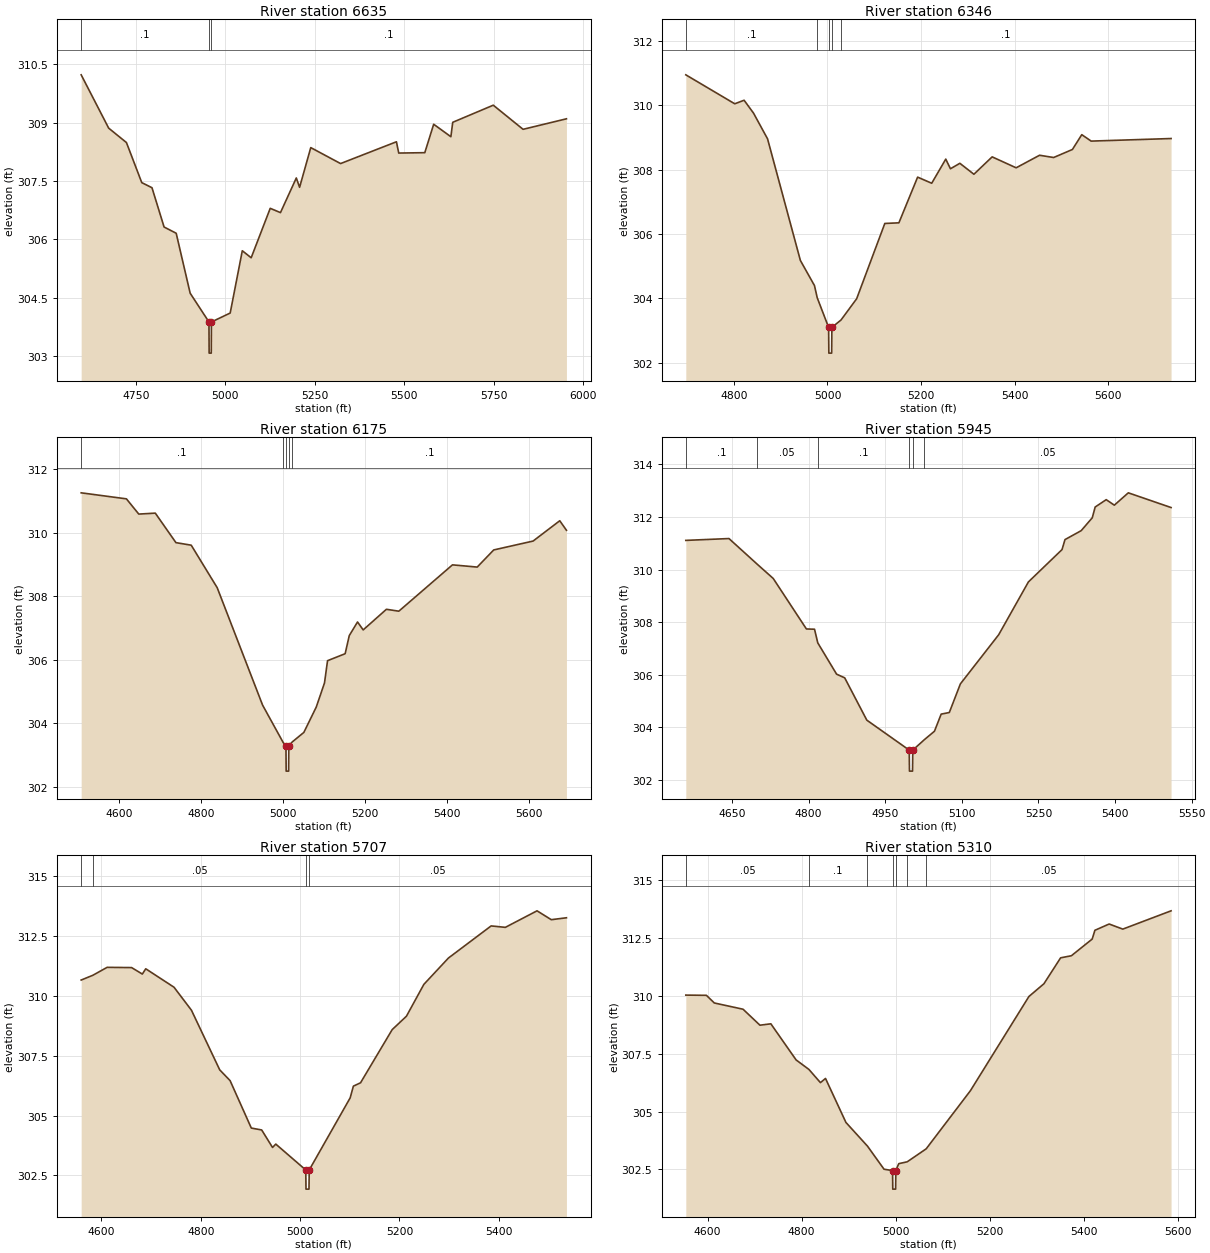
Type RM Length L Ch R = 1,6635,289,289,289
BEGIN DESCRIPTION:
Mapping XS 41211bd3
END DESCRIPTION:
XS GIS Cut Line= 3
      2094429.72     13419223.07      2094315.15     13419379.30
      2093198.57     13419698.32
#Sta/Elev= 30
  4597.8  310.23  4674.6  308.86  4724.2  308.49  4767.0  307.46  4795.5  307.33
  4829.3  306.32  4863.1  306.16  4902.1  304.62  4954.6  303.88  4955.1  303.08
  4961.0  303.08  4961.5  303.88  5013.9  304.11  5047.7  305.71  5072.5  305.53
  5125.7  306.80  5154.3  306.69  5198.5  307.58  5207.7  307.34  5238.9  308.36
  5322.1  307.95  5478.1  308.51  5484.5  308.22  5557.3  308.23  5582.1  308.96
  5630.1  308.64  5635.3  309.01  5748.5  309.45  5831.7  308.83  5952.8  309.10
#Mann=3,-1,0
  4597.8     0.1       0  4954.6    0.07       0  4961.5     0.1       0
Bank Sta=4954.6,4961.5
Exp/Cntr=0.3,0.1

Type RM Length L Ch R = 1,6346,171,171,171
BEGIN DESCRIPTION:
Mapping XS 3273ca79
END DESCRIPTION:
XS GIS Cut Line= 2
      2094419.32     13419167.49      2093384.61     13419108.46
#Sta/Elev= 30
  4697.5  310.95  4802.0  310.05  4822.0  310.16  4842.1  309.76  4872.1  308.96
  4942.2  305.18  4972.3  304.40  4978.2  304.02  5002.5  303.10  5003.0  302.30
  5009.0  302.30  5009.5  303.10  5029.0  303.33  5062.4  303.99  5122.5  306.33
  5152.6  306.35  5192.6  307.77  5222.7  307.58  5252.7  308.33  5262.7  308.03
  5282.8  308.20  5312.8  307.86  5351.8  308.40  5403.0  308.06  5453.0  308.45
  5483.1  308.38  5523.2  308.63  5543.2  309.09  5563.2  308.89  5733.9  308.97
#Mann=5,-1,0
  4697.5     0.1       0  4978.2    0.05       0  5002.5   0.033       0
  5009.5    0.05       0  5029.0     0.1       0
Bank Sta=5002.5,5009.5
Exp/Cntr=0.3,0.1

Type RM Length L Ch R = 1,6175,230,230,230
BEGIN DESCRIPTION:
Mapping XS 3c4fe360
END DESCRIPTION:
XS GIS Cut Line= 2
      2094634.61     13419042.49      2093458.78     13418900.28
#Sta/Elev= 30
  4507.0  311.26  4617.4  311.07  4647.6  310.59  4687.9  310.62  4738.3  309.69
  4775.6  309.61  4839.0  308.27  4949.8  304.57  5000.1  303.39  5006.8  303.29
  5007.3  302.49  5013.3  302.49  5013.8  303.29  5022.2  303.41  5050.5  303.71
  5080.8  304.51  5100.9  305.27  5108.3  305.97  5151.3  306.19  5161.3  306.76
  5181.5  307.19  5195.3  306.94  5252.0  307.59  5282.3  307.53  5413.2  308.99
  5473.6  308.92  5513.9  309.46  5610.0  309.74  5675.1  310.38  5691.4  310.08
#Mann=5,-1,0
  4507.0     0.1       0  5000.1    0.05       0  5006.8    0.07       0
  5013.8    0.05       0  5022.2     0.1       0
Bank Sta=5006.8,5013.8
Exp/Cntr=0.3,0.1

Type RM Length L Ch R = 1,5945,238,238,238
BEGIN DESCRIPTION:
Mapping XS 15852f92
END DESCRIPTION:
XS GIS Cut Line= 2
      2094648.48     13419014.71      2093822.07     13418545.95
#Sta/Elev= 30
  4559.6  311.11  4644.1  311.18  4698.5  310.22  4730.8  309.66  4795.7  307.74
  4811.6  307.73  4818.0  307.21  4854.8  306.02  4870.7  305.88  4914.0  304.27
  4997.0  303.13  4997.5  302.33  5003.5  302.33  5004.0  303.13  5026.3  303.52
  5046.5  303.85  5059.6  304.50  5075.5  304.56  5097.2  305.65  5172.2  307.52
  5230.4  309.53  5296.2  310.76  5302.0  311.14  5333.7  311.48  5355.4  311.97
  5361.1  312.38  5382.7  312.66  5398.6  312.45  5426.0  312.92  5509.7  312.36
#Mann=6,-1,0
  4559.6     0.1       0  4698.5    0.05       0  4818.0     0.1       0
  4997.0    0.07       0  5004.0     0.1       0  5026.3    0.05       0
Bank Sta=4997,5004
Exp/Cntr=0.3,0.1

Type RM Length L Ch R = 1,5707,397,397,397
BEGIN DESCRIPTION:
Mapping XS c62dc981
END DESCRIPTION:
XS GIS Cut Line= 3
      2094756.10     13418997.32      2094468.83     13418671.34
      2094052.15     13418324.10
#Sta/Elev= 30
  4559.3  310.66  4582.9  310.86  4611.5  311.19  4660.8  311.18  4682.4  310.91
  4689.3  311.13  4746.2  310.36  4781.3  309.40  4838.2  306.91  4859.1  306.46
  4901.8  304.48  4922.7  304.40  4944.5  303.67  4951.1  303.81  5011.4  302.73
  5011.9  301.93  5017.9  301.93  5018.4  302.73  5100.8  305.74  5107.3  306.23
  5121.7  306.37  5185.4  308.59  5214.1  309.15  5249.2  310.48  5298.7  311.58
  5384.6  312.92  5413.2  312.86  5477.0  313.55  5505.7  313.18  5536.2  313.26
#Mann=4,-1,0
  4559.3     0.1       0  4582.9    0.05       0  5011.4    0.03       0
  5018.4    0.05       0
Bank Sta=5011.4,5018.4
Exp/Cntr=0.3,0.1

Type RM Length L Ch R = 1,5310,214,214,214
BEGIN DESCRIPTION:
Mapping XS 81290518
END DESCRIPTION:
XS GIS Cut Line= 3
      2095006.11     13418761.21      2094898.49     13418493.88
      2094250.26     13418129.90
#Sta/Elev= 30
  4553.8  310.03  4597.6  310.02  4614.4  309.69  4675.5  309.42  4711.4  308.73
  4734.6  308.79  4788.3  307.23  4815.5  306.82  4840.0  306.25  4850.8  306.43
  4894.2  304.53  4939.9  303.51  4975.2  302.51  4993.3  302.45  4993.8  301.65
  4999.8  301.65  5000.3  302.45  5006.5  302.75  5024.5  302.83  5064.8  303.39
  5158.8  305.90  5283.2  309.97  5315.1  310.52  5350.6  311.64  5373.5  311.73
  5417.7  312.45  5423.5  312.83  5453.8  313.10  5482.8  312.88  5585.4  313.67
#Mann=7,-1,0
  4553.8    0.05       0  4815.5     0.1       0  4939.9    0.05       0
  4993.3    0.03       0  5000.3    0.05       0  5024.5     0.1       0
  5064.8    0.05       0
Bank Sta=4993.3,5000.3
Exp/Cntr=0.3,0.1

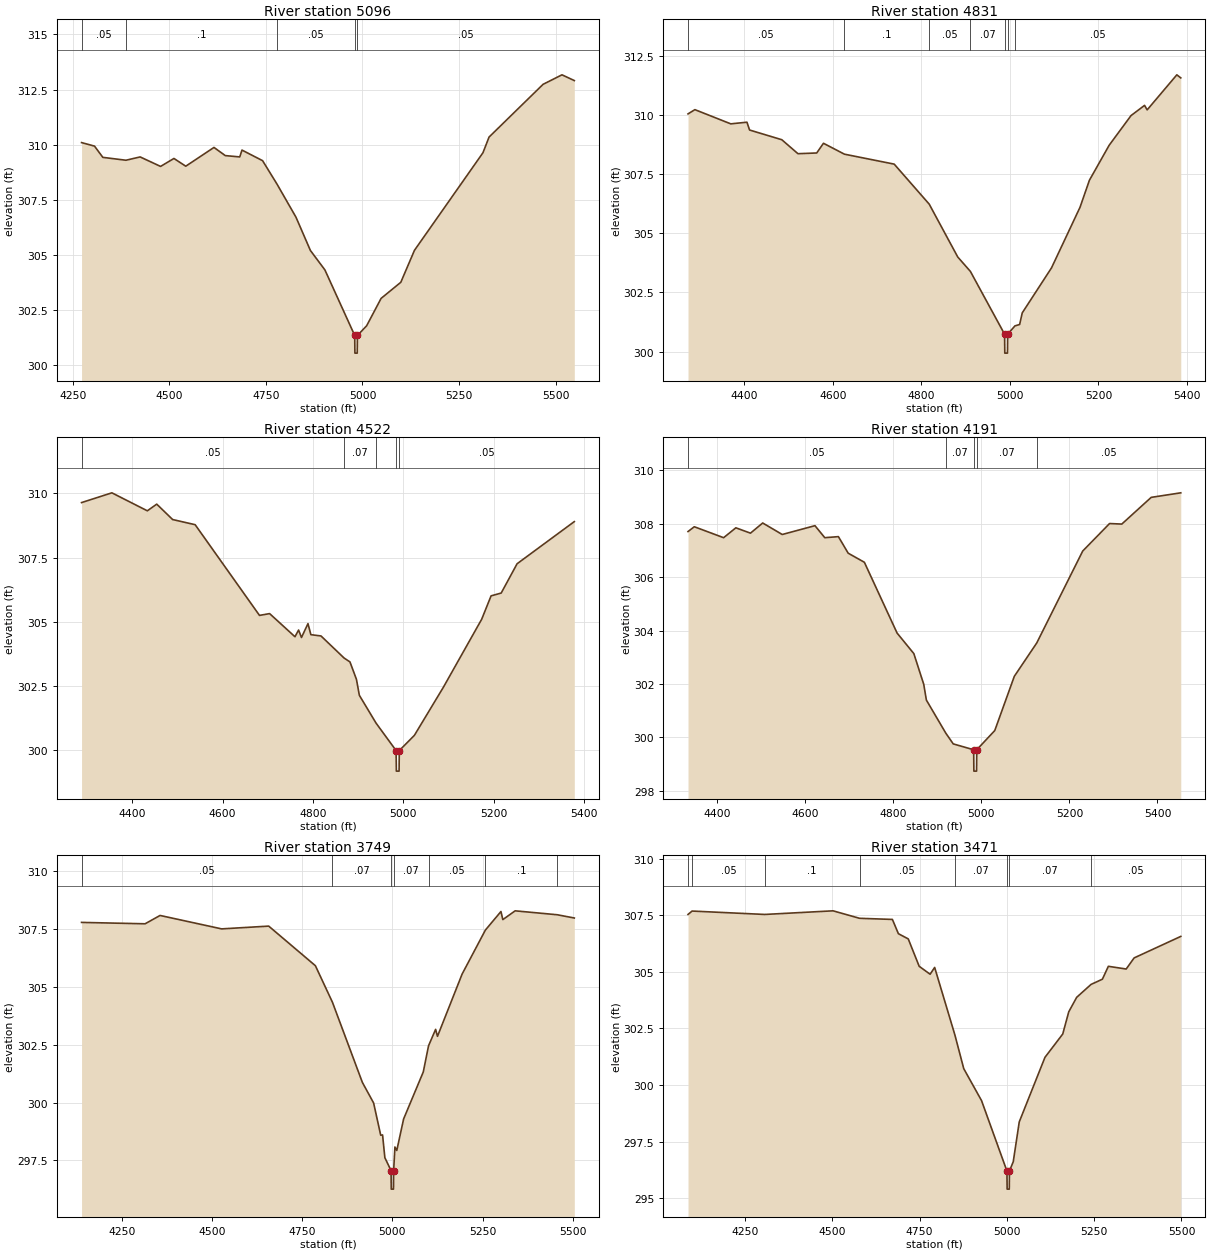
Type RM Length L Ch R = 1,5096,265,265,265
BEGIN DESCRIPTION:
Mapping XS 62ebc719
END DESCRIPTION:
XS GIS Cut Line= 2
      2095502.65     13418594.57      2094395.03     13417962.64
#Sta/Elev= 30
  4273.0  310.10  4306.5  309.94  4328.1  309.43  4387.9  309.30  4424.6  309.45
  4477.5  309.02  4512.1  309.38  4542.7  309.03  4615.7  309.88  4645.0  309.51
  4682.4  309.45  4688.2  309.76  4741.5  309.28  4779.1  308.21  4827.9  306.72
  4865.3  305.21  4902.8  304.33  4979.9  301.36  4980.4  300.56  4986.4  300.56
  4986.9  301.36  5010.8  301.80  5048.2  303.04  5099.2  303.77  5134.6  305.22
  5311.8  309.64  5327.6  310.35  5467.4  312.74  5516.3  313.17  5548.2  312.91
#Mann=5,-1,0
  4273.0    0.05       0  4387.9     0.1       0  4779.1    0.05       0
  4979.9    0.03       0  4986.9    0.05       0
Bank Sta=4979.9,4986.9
Exp/Cntr=0.3,0.1

Type RM Length L Ch R = 1,4831,309,309,309
BEGIN DESCRIPTION:
Mapping XS 5669982f
END DESCRIPTION:
XS GIS Cut Line= 2
      2095638.08     13418414.02      2094698.54     13417817.71
#Sta/Elev= 30
  4273.2  310.04  4288.7  310.22  4369.8  309.62  4406.3  309.69  4412.2  309.36
  4485.0  308.95  4521.5  308.36  4563.8  308.39  4579.1  308.80  4626.4  308.34
  4738.8  307.92  4817.9  306.23  4882.3  304.00  4910.9  303.39  4988.1  300.74
  4988.6  299.94  4994.6  299.94  4995.1  300.74  5011.5  301.09  5022.1  301.15
  5028.0  301.64  5094.1  303.54  5158.5  306.10  5179.7  307.24  5224.4  308.72
  5273.7  309.97  5304.2  310.40  5310.1  310.21  5377.1  311.69  5386.0  311.56
#Mann=7,-1,0
  4273.2    0.05       0  4626.4     0.1       0  4817.9    0.05       0
  4910.9    0.07       0  4988.1    0.07       0  4995.1    0.07       0
  5011.5    0.05       0
Bank Sta=4988.1,4995.1
Exp/Cntr=0.3,0.1

Type RM Length L Ch R = 1,4522,331,331,331
BEGIN DESCRIPTION:
Mapping XS 8bc10dbd
END DESCRIPTION:
XS GIS Cut Line= 2
      2095811.65     13418292.46      2094958.76     13417612.92
#Sta/Elev= 30
  4287.7  309.64  4354.8  310.02  4433.3  309.32  4454.1  309.58  4489.3  308.98
  4539.1  308.78  4681.5  305.25  4703.9  305.32  4760.0  304.42  4768.0  304.68
  4774.4  304.39  4788.8  304.93  4795.2  304.50  4817.6  304.45  4868.8  303.59
  4881.7  303.44  4896.1  302.76  4902.5  302.14  4939.4  301.06  4983.8  299.99
  4984.4  299.19  4990.4  299.19  4990.9  299.99  5024.2  300.58  5088.3  302.45
  5173.2  305.10  5194.0  306.01  5216.4  306.12  5251.6  307.26  5378.2  308.90
#Mann=5,-1,0
  4287.7    0.05       0  4868.8    0.07       0  4939.4    0.05       0
  4983.8   0.033       0  4990.9    0.05       0
Bank Sta=4983.8,4990.9
Exp/Cntr=0.3,0.1

Type RM Length L Ch R = 1,4191,442,442,442
BEGIN DESCRIPTION:
Mapping XS d72b365d
END DESCRIPTION:
XS GIS Cut Line= 2
      2096061.67     13417907.07      2095065.18     13417396.67
#Sta/Elev= 30
  4333.4  307.71  4347.7  307.89  4414.3  307.48  4442.1  307.85  4475.3  307.65
  4503.1  308.03  4547.5  307.60  4621.8  307.93  4644.2  307.48  4675.1  307.52
  4697.3  306.90  4734.1  306.56  4808.4  303.91  4846.5  303.14  4869.0  301.99
  4875.0  301.40  4919.2  300.16  4936.0  299.76  4982.4  299.54  4982.9  298.74
  4989.0  298.74  4989.5  299.54  5030.4  300.26  5074.8  302.29  5125.8  303.54
  5230.2  306.98  5291.2  308.01  5319.0  307.99  5385.8  308.99  5453.0  309.16
#Mann=5,-1,0
  4333.4    0.05       0  4919.2    0.07       0  4982.4    0.07       0
  4989.5    0.07       0  5125.8    0.05       0
Bank Sta=4982.4,4989.5
Exp/Cntr=0.3,0.1

Type RM Length L Ch R = 1,3749,278,278,278
BEGIN DESCRIPTION:
Mapping XS b855b2aa
END DESCRIPTION:
XS GIS Cut Line= 2
      2096384.58     13417424.43      2095069.35     13417056.58
#Sta/Elev= 30
  4138.6  307.78  4314.7  307.72  4356.2  308.08  4526.9  307.50  4657.3  307.62
  4786.7  305.91  4834.0  304.33  4916.9  300.87  4948.1  299.98  4967.7  298.59
  4972.9  298.60  4979.2  297.62  4996.4  297.06  4997.0  296.26  5003.1  296.26
  5003.6  297.06  5007.1  298.08  5012.3  297.93  5031.2  299.29  5085.7  301.32
  5100.3  302.45  5119.9  303.16  5125.1  302.86  5193.4  305.55  5257.9  307.45
  5301.0  308.25  5306.2  307.90  5340.3  308.28  5457.1  308.11  5504.3  307.97
#Mann=7,-1,0
  4138.6    0.05       0  4834.0    0.07       0  4996.4    0.07       0
  5003.6    0.07       0  5100.3    0.05       0  5257.9     0.1       0
  5457.1    0.05       0
Bank Sta=4996.4,5003.6
Exp/Cntr=0.3,0.1

Type RM Length L Ch R = 1,3471,529,529,529
BEGIN DESCRIPTION:
Mapping XS fc4374a7
END DESCRIPTION:
XS GIS Cut Line= 2
      2096412.36     13417309.84      2095139.01     13416702.66
#Sta/Elev= 30
  4087.3  307.53  4099.0  307.68  4307.0  307.53  4502.5  307.69  4578.4  307.36
  4672.4  307.31  4689.6  306.68  4717.8  306.45  4749.1  305.24  4780.4  304.89
  4793.4  305.19  4851.3  302.21  4876.7  300.72  4927.6  299.31  5000.3  296.20
  5000.9  295.40  5007.0  295.40  5007.5  296.20  5018.4  296.61  5035.6  298.37
  5109.2  301.22  5160.1  302.25  5177.3  303.23  5200.0  303.87  5241.1  304.44
  5273.6  304.67  5290.7  305.24  5341.7  305.12  5364.4  305.61  5498.0  306.56
#Mann=8,-1,0
  4087.3     0.1       0  4099.0    0.05       0  4307.0     0.1       0
  4578.4    0.05       0  4851.3    0.07       0  5000.3    0.07       0
  5007.5    0.07       0  5241.1    0.05       0
Bank Sta=5000.3,5007.5
Exp/Cntr=0.3,0.1

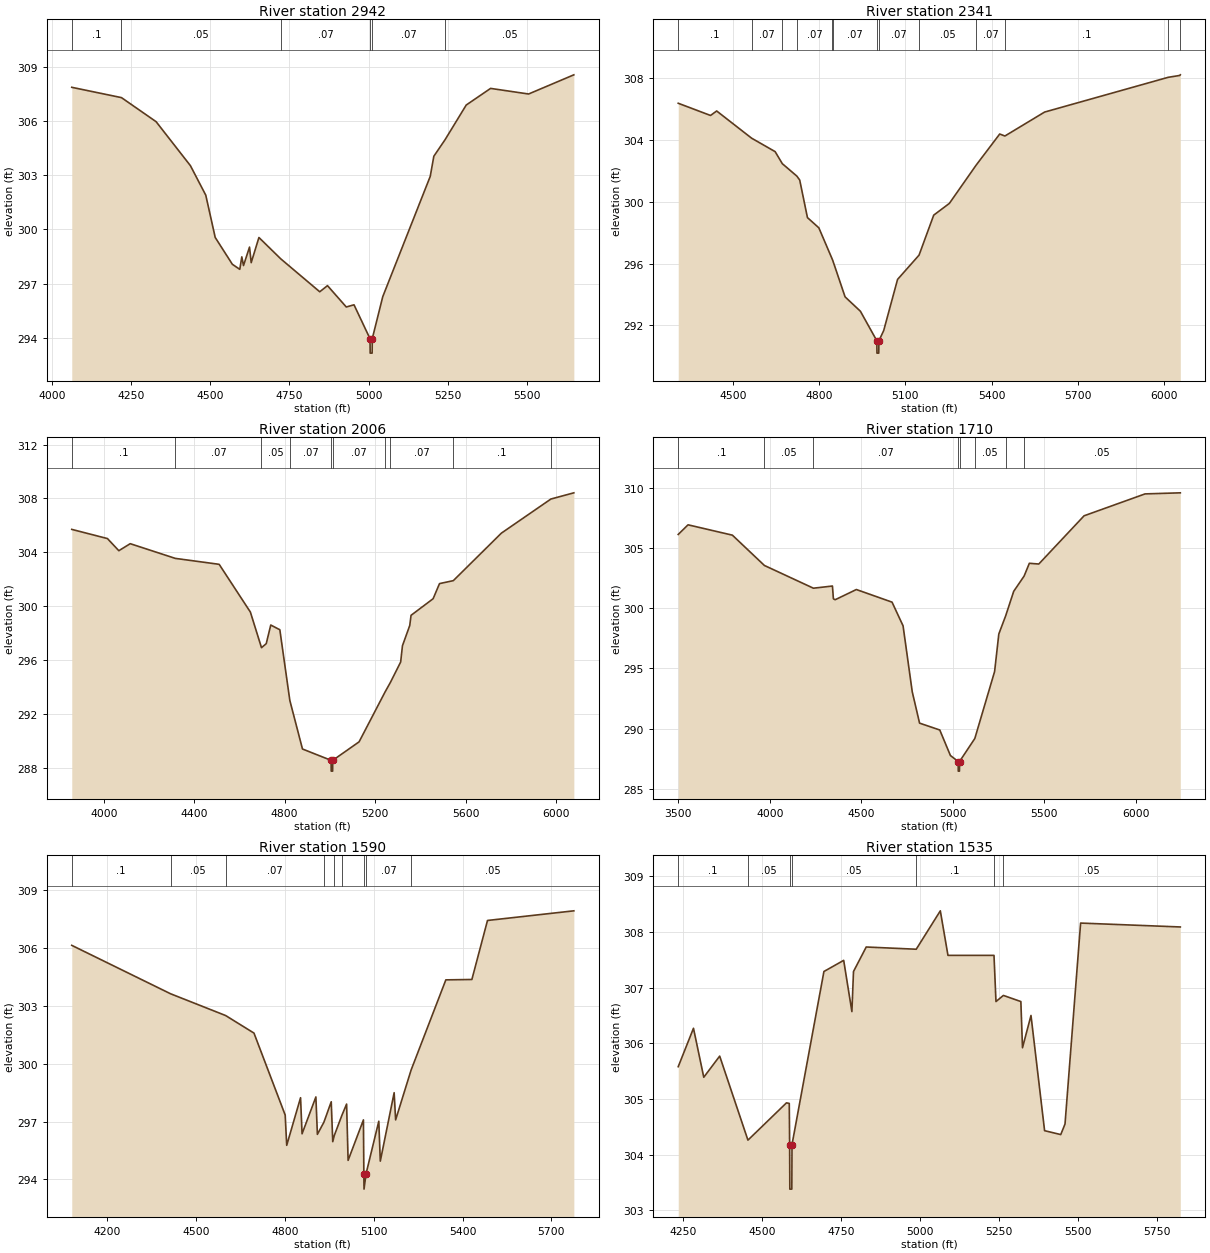
Type RM Length L Ch R = 1,2942,601,601,601
BEGIN DESCRIPTION:
Mapping XS 0f922f02
END DESCRIPTION:
XS GIS Cut Line= 3
      2096818.64     13416917.50      2095631.13     13416448.74
      2095322.13     13416452.21
#Sta/Elev= 30
  4062.6  307.85  4219.6  307.28  4329.0  305.95  4437.3  303.52  4485.8  301.89
  4515.7  299.55  4569.8  298.07  4593.3  297.79  4599.6  298.48  4605.0  298.00
  4624.0  299.02  4629.3  298.16  4653.7  299.55  4722.7  298.37  4845.8  296.55
  4870.2  296.89  4929.6  295.71  4954.0  295.83  5004.5  293.96  5005.1  293.16
  5011.2  293.16  5011.7  293.96  5044.8  296.28  5194.8  302.93  5206.1  304.04
  5241.4  304.95  5308.4  306.87  5385.4  307.79  5505.4  307.48  5648.3  308.54
#Mann=6,-1,0
  4062.6     0.1       0  4219.6    0.05       0  4722.7    0.07       0
  5004.5    0.07       0  5011.7    0.07       0  5241.4    0.05       0
Bank Sta=5004.5,5011.7
Exp/Cntr=0.3,0.1

Type RM Length L Ch R = 1,2341,335,335,335
BEGIN DESCRIPTION:
Mapping XS 5634a12a
END DESCRIPTION:
XS GIS Cut Line= 4
      2096773.48     13416729.96      2096613.77     13416309.85
      2096231.82     13416223.05      2095339.73     13416375.78
#Sta/Elev= 30
  4310.3  306.38  4422.6  305.59  4444.0  305.88  4565.5  304.12  4647.3  303.25
  4672.3  302.47  4723.2  301.66  4732.8  301.41  4759.7  298.98  4799.3  298.32
  4845.5  296.31  4847.7  296.21  4890.6  293.85  4943.9  292.92  5001.0  291.01
  5001.5  290.21  5007.7  290.21  5008.3  291.01  5024.9  291.67  5073.1  294.98
  5147.8  296.55  5198.9  299.14  5253.3  299.90  5346.2  302.37  5428.4  304.39
  5446.4  304.26  5584.5  305.81  6014.6  308.06  6054.7  308.18  6056.5  308.22
#Mann=13,-1,0
  4310.3     0.1       0  4565.5    0.07       0  4672.3    0.05       0
  4723.2    0.07       0  4845.5    0.05       0  4847.7    0.07       0
  5001.0    0.07       0  5008.3    0.07       0  5147.8    0.05       0
  5346.2    0.07       0  5446.4     0.1       0  6014.6    0.05       0
  6054.7     0.1       0
Bank Sta=5001,5008.3
Exp/Cntr=0.3,0.1

Type RM Length L Ch R = 1,2006,296,296,296
BEGIN DESCRIPTION:
UNT 093 in La Jarita Watershed 5.0
END DESCRIPTION:
XS GIS Cut Line= 4
      2096803.87     13416651.45      2096710.75     13415923.36
      2095991.37     13415958.72      2095317.01     13416321.46
#Sta/Elev= 30
  3858.7  305.71  4016.4  305.03  4066.8  304.13  4117.2  304.65  4316.5  303.56
  4510.4  303.12  4648.5  299.58  4697.6  296.94  4718.6  297.24  4738.6  298.62
  4778.7  298.27  4822.9  293.03  4878.8  289.43  5005.3  288.59  5005.9  287.79
  5012.1  287.79  5012.6  288.59  5129.1  289.96  5244.1  293.66  5267.7  294.37
  5313.0  295.88  5320.8  297.08  5353.2  298.59  5358.9  299.34  5456.5  300.57
  5484.7  301.69  5545.8  301.91  5758.2  305.43  5977.3  307.96  6078.7  308.42
#Mann=10,-1,0
  3858.7     0.1       0  4316.5    0.07       0  4697.6    0.05       0
  4822.9    0.07       0  5005.3    0.07       0  5012.6    0.07       0
  5244.1    0.05       0  5267.7    0.07       0  5545.8     0.1       0
  5977.3    0.05       0
Bank Sta=5005.3,5012.6
Exp/Cntr=0.3,0.1

Type RM Length L Ch R = 1,1710,120,120,120
BEGIN DESCRIPTION:
Mapping XS 2c9965db
END DESCRIPTION:
XS GIS Cut Line= 3
      2097639.99     13415565.65      2096188.58     13415676.76
      2095016.55     13416210.76
#Sta/Elev= 30
  3499.7  306.14  3553.3  306.94  3795.6  306.08  3970.6  303.56  4238.3  301.67
  4342.4  301.85  4347.5  300.79  4357.2  300.71  4473.1  301.56  4668.1  300.51
  4728.3  298.54  4778.4  293.06  4818.5  290.45  4928.9  289.88  4987.0  287.76
  5029.4  287.26  5030.0  286.46  5036.3  286.46  5036.9  287.26  5120.3  289.17
  5228.5  294.74  5251.5  297.86  5288.9  299.37  5332.9  301.41  5389.8  302.68
  5418.4  303.74  5470.0  303.68  5717.5  307.69  6050.6  309.51  6243.3  309.60
#Mann=8,-1,0
  3499.7     0.1       0  3970.6    0.05       0  4238.3    0.07       0
  5029.4    0.07       0  5036.9    0.07       0  5120.3    0.05       0
  5288.9    0.07       0  5389.8    0.05       0
Bank Sta=5029.4,5036.9
Exp/Cntr=0.3,0.1

Type RM Length L Ch R = 1,1590,55,55,55
BEGIN DESCRIPTION:
Mapping XS fd68181c
END DESCRIPTION:
XS GIS Cut Line= 5
      2096913.62     13415331.06      2096820.08     13415530.64
      2096322.10     13415549.43      2095835.99     13415643.18
      2095378.84     13415799.03
#Sta/Elev= 30
  4079.5  306.14  4413.3  303.63  4599.6  302.50  4695.3  301.59  4800.8  297.34
  4805.9  295.77  4852.7  298.24  4857.8  296.37  4904.5  298.28  4909.6  296.34
  4931.6  296.97  4956.4  298.03  4961.5  295.96  4966.7  296.28  4993.3  297.36
  5008.3  297.91  5013.4  294.99  5065.2  297.09  5066.6  294.30  5067.2  293.50
  5074.1  294.30  5117.1  297.02  5122.2  294.95  5169.0  298.50  5174.0  297.09
  5226.2  299.67  5343.7  304.35  5431.7  304.37  5484.5  307.43  5776.3  307.93
#Mann=9,-1,0
  4079.5     0.1       0  4413.3    0.05       0  4599.6    0.07       0
  4931.6    0.05       0  4966.7     0.1       0  4993.3    0.07       0
  5066.6    0.07       0  5074.1    0.07       0  5226.2    0.05       0
Bank Sta=5066.6,5074.1
Exp/Cntr=0.3,0.1

Type RM Length L Ch R = 1,1535,52,52,52
BEGIN DESCRIPTION:
Mapping XS 7b26ca63
END DESCRIPTION:
XS GIS Cut Line= 5
      2096868.22     13415381.89      2096700.21     13415465.34
      2096422.79     13415473.05      2095839.46     13415591.10
      2095333.83     13415750.41
#Sta/Elev= 30
  4234.3  305.58  4282.6  306.27  4315.2  305.39  4365.6  305.77  4455.1  304.26
  4577.2  304.93  4586.0  304.92  4587.2  304.18  4587.8  303.38  4594.1  303.38
  4594.7  304.18  4695.8  307.29  4758.4  307.49  4784.4  306.57  4789.5  307.29
  4829.8  307.73  4988.2  307.69  5064.5  308.38  5088.7  307.58  5234.5  307.58
  5240.8  306.75  5264.3  306.86  5319.6  306.75  5324.8  305.92  5351.7  306.50
  5394.8  304.43  5446.0  304.36  5459.5  304.55  5508.9  308.16  5824.7  308.09
#Mann=7,-1,0
  4234.3     0.1       0  4455.1    0.05       0  4587.2    0.07       0
  4594.7    0.05       0  4988.2     0.1       0  5234.5    0.07       0
  5264.3    0.05       0
Bank Sta=4587.2,4594.7
Exp/Cntr=0.3,0.1

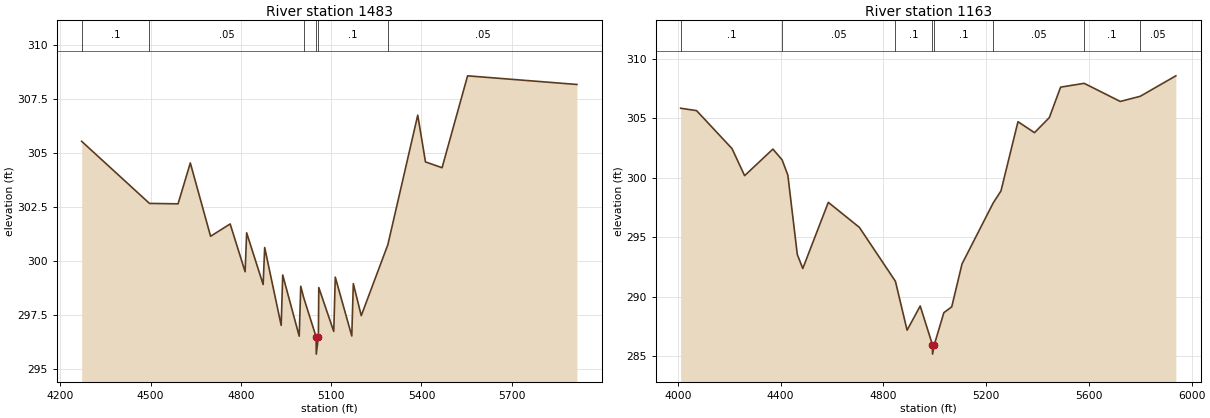
Type RM Length L Ch R = 1,1483,320,320,320
BEGIN DESCRIPTION:
Mapping XS a088c6ac
END DESCRIPTION:
XS GIS Cut Line= 4
      2096852.60     13415372.76      2096499.18     13415417.49
      2095773.49     13415542.49      2095252.66     13415726.51
#Sta/Elev= 30
  4271.3  305.53  4496.5  302.66  4591.4  302.64  4632.2  304.53  4699.5  301.14
  4764.5  301.71  4814.2  299.50  4819.3  301.30  4874.1  298.91  4879.2  300.62
  4934.0  297.02  4939.1  299.35  4993.9  296.52  4999.0  298.83  5008.4  298.32
  5050.0  296.49  5050.6  295.69  5057.5  296.49  5058.9  298.77  5108.6  296.74
  5113.7  299.25  5168.5  296.53  5173.6  298.95  5200.0  297.47  5288.3  300.75
  5387.6  306.74  5413.3  304.58  5468.4  304.31  5553.2  308.56  5916.3  308.16
#Mann=6,-1,0
  4271.3     0.1       0  4496.5    0.05       0  5008.4     0.1       0
  5050.0    0.03       0  5057.5     0.1       0  5288.3    0.05       0
Bank Sta=5050,5057.5
Exp/Cntr=0.3,0.1

Type RM Length L Ch R = 1,1163,400,400,400
BEGIN DESCRIPTION:
Mapping XS 4e489917
END DESCRIPTION:
XS GIS Cut Line= 4
      2096888.10     13415365.43      2096474.88     13415115.41
      2095898.49     13415236.93      2095176.28     13415695.26
#Sta/Elev= 30
  4011.1  305.83  4073.2  305.63  4211.2  302.44  4260.2  300.17  4370.3  302.40
  4406.0  301.50  4428.4  300.22  4465.3  293.55  4486.6  292.38  4585.9  297.93
  4706.8  295.83  4847.2  291.30  4892.5  287.20  4943.6  289.23  4991.0  285.99
  4991.6  285.19  4998.5  285.99  5035.6  288.67  5066.3  289.16  5106.3  292.76
  5227.4  297.87  5257.9  298.89  5324.1  304.70  5388.4  303.78  5446.0  305.04
  5490.0  307.60  5581.7  307.92  5722.1  306.40  5799.8  306.83  5938.5  308.55
#Mann=8,-1,0
  4011.1     0.1       0  4406.0    0.05       0  4847.2     0.1       0
  4991.0    0.07       0  4998.5     0.1       0  5227.4    0.05       0
  5581.7     0.1       0  5799.8    0.05       0
Bank Sta=4991,4998.5
Exp/Cntr=0.3,0.1