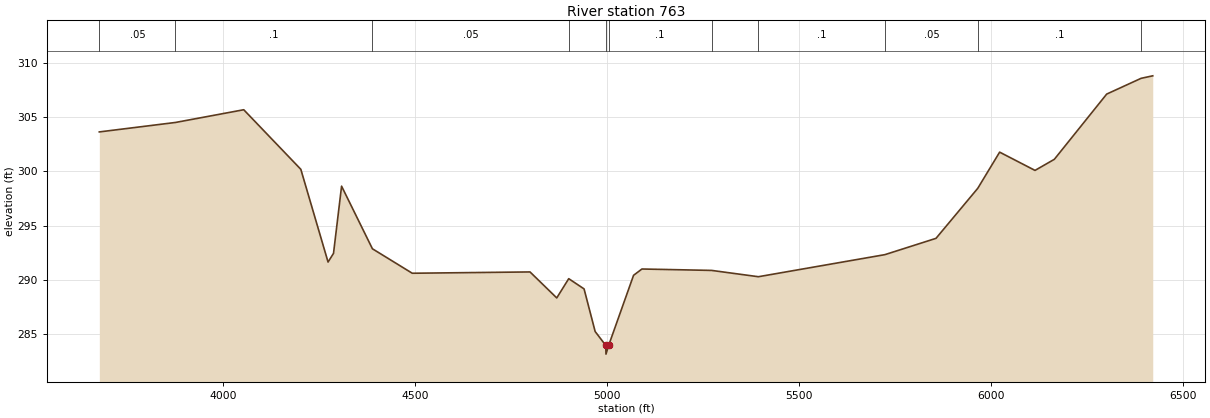
HEC-RAS study UNT 093 in La Jarita Watershed.prj: UNT 093 in La Jarita Watershed Base Level Engineering

--- UNT 093 in La Jarita Watershed.g01 (geometry) --- (continued)

Type RM Length L Ch R = 1,763,0,0,0
BEGIN DESCRIPTION:
UNT 093 in La Jarita Watershed 1.0
END DESCRIPTION:
XS GIS Cut Line= 4
      2097186.70     13415424.46      2096624.18     13414813.32
      2095662.38     13414910.55      2095110.32     13415677.87
#Sta/Elev= 30
  3677.6  303.63  3875.8  304.50  4053.6  305.67  4202.2  300.19  4273.1  291.66
  4287.3  292.46  4308.3  298.64  4388.6  292.88  4492.3  290.63  4798.9  290.75
  4868.5  288.36  4899.7  290.13  4939.6  289.19  4968.5  285.27  4996.1  283.99
  4996.7  283.19  5003.6  283.99  5068.5  290.44  5090.3  291.02  5271.8  290.89
  5393.5  290.31  5722.8  292.34  5855.9  293.84  5964.6  298.44  6021.6  301.77
  6113.7  300.09  6164.0  301.11  6300.3  307.11  6389.9  308.56  6420.2  308.79
#Mann=11,-1,0
  3677.6    0.05       0  3875.8     0.1       0  4388.6    0.05       0
  4899.7     0.1       0  4996.1    0.07       0  5003.6     0.1       0
  5271.8    0.05       0  5393.5     0.1       0  5722.8    0.05       0
  5964.6     0.1       0  6389.9    0.05       0
Bank Sta=4996.1,5003.6
Exp/Cntr=0.3,0.1

Chan Stop Cuts=-1