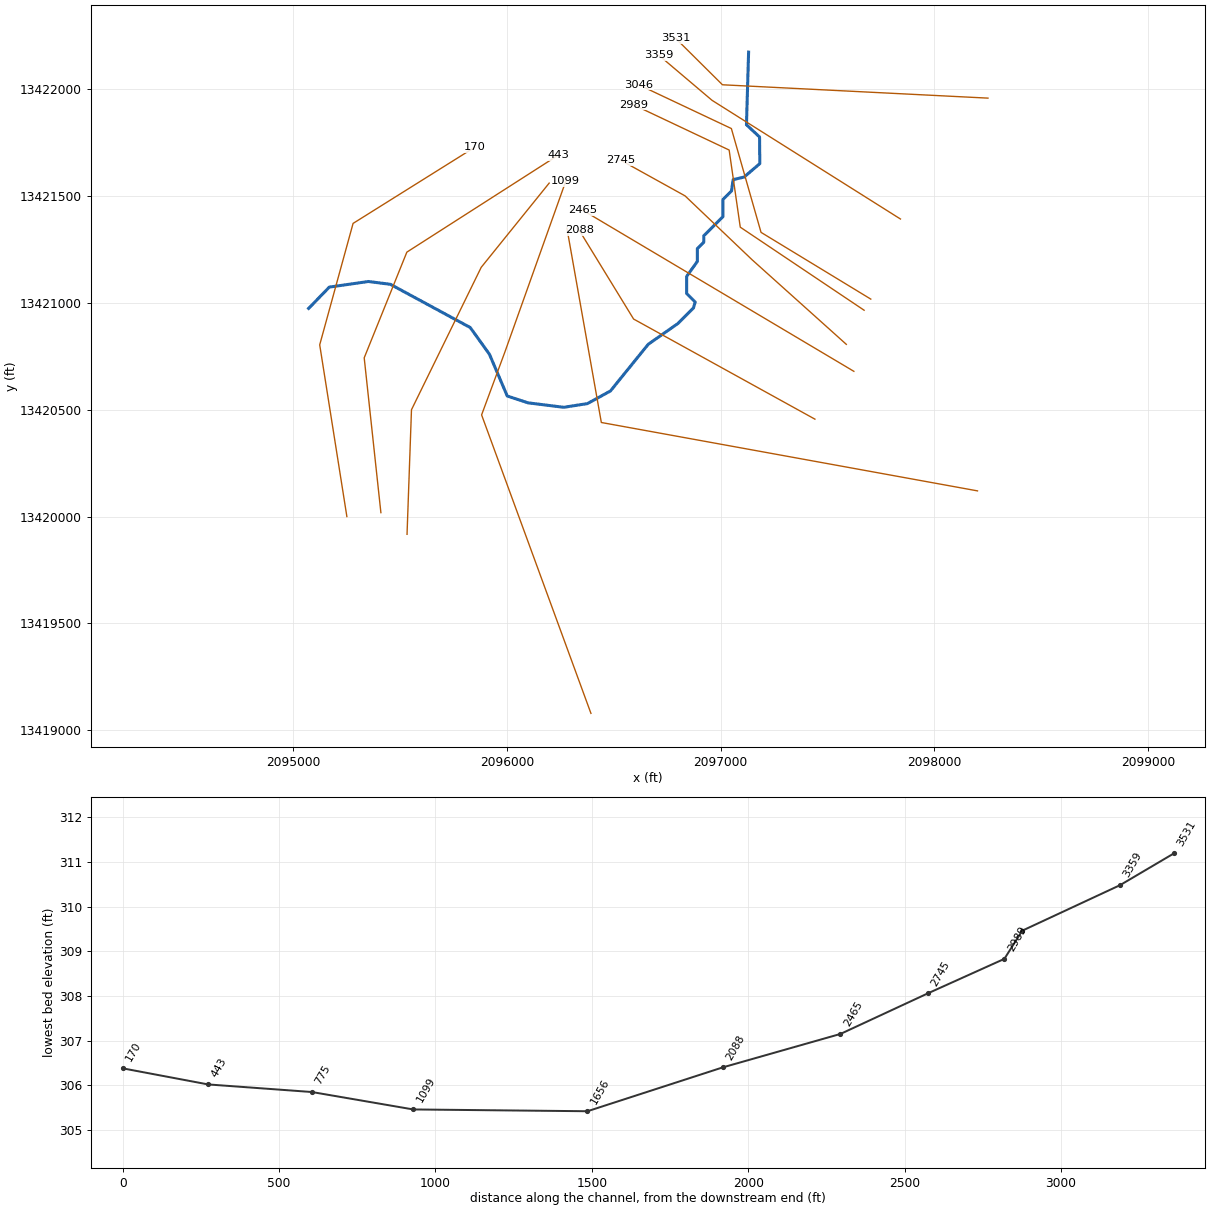
--- UNT 095 in La Jarita Watershed.prj (project) ---

Proj Title=UNT 095 in La Jarita Watershed Base Level Engineering
Current Plan=p01
Default Exp/Contr=0.3,0.1
English Units
Geom File=g01
Flow File=f01
Plan File=p01
BEGIN DESCRIPTION:
UNT 095 in La Jarita Watershed
END DESCRIPTION:

--- UNT 095 in La Jarita Watershed.p01 (plan) ---

Plan Title=Multiple Run
Short Identifier=Multiple
Geom File=g01
Flow File=f01
Subcritical Flow
K Sum by GR= 0
Std Step Tol= 0.01
Critical Tol= 0.01
Num of Std Step Trials= 20
Max Error Tol= 0.3
Flow Tol Ratio= 0.001
Split Flow NTrial= 30
Split Flow Tol= 0.02
Split Flow Ratio= 0.02
Log Output Level= 0
Friction Slope Method= 1
Unsteady Friction Slope Method= 2
Unsteady Bridges Friction Slope Method= 1
Parabolic Critical Depth
Global Vel Dist=  1 , 1 , 1
Global Log Level= 0
CheckData=True
Encroach Param= -1, 0, 0, 0
BEGIN DESCRIPTION:
Multiple Run
END DESCRIPTION:

--- UNT 095 in La Jarita Watershed.f01 (steady flow) ---

Flow Title=Multiple
Number of Profiles=7
Profile Names=10-year,25-year,50-year,1pct_min,100-year,1pct_plu,500-year
River Rch & RM= UNT 095 in La Ja,Reach-1,3531
      76      98     114      67     134     267     186
River Rch & RM= UNT 095 in La Ja,Reach-1,1099
     110     145     173     103     205     410     293
River Rch & RM= UNT 095 in La Ja,Reach-1,170
     254     352     433     265     529    1056     804
Boundary for River Rch & Prof#=UNT 095 in La Ja,Reach-1,1
Up Type=0
Dn Type=3
Dn Slope=0.005
Boundary for River Rch & Prof#=UNT 095 in La Ja,Reach-1,2
Up Type=0
Dn Type=3
Dn Slope=0.005
Boundary for River Rch & Prof#=UNT 095 in La Ja,Reach-1,3
Up Type=0
Dn Type=3
Dn Slope=0.005
Boundary for River Rch & Prof#=UNT 095 in La Ja,Reach-1,4
Up Type=0
Dn Type=3
Dn Slope=0.005
Boundary for River Rch & Prof#=UNT 095 in La Ja,Reach-1,5
Up Type=0
Dn Type=3
Dn Slope=0.005
Boundary for River Rch & Prof#=UNT 095 in La Ja,Reach-1,6
Up Type=0
Dn Type=3
Dn Slope=0.005
Boundary for River Rch & Prof#=UNT 095 in La Ja,Reach-1,7
Up Type=0
Dn Type=3
Dn Slope=0.005

--- UNT 095 in La Jarita Watershed.g01 (geometry) ---

Geom Title=Existing Conditions

River Reach=UNT 095 in La Ja,Reach-1
Reach XY= 30
      2097130.80     13422174.54      2097120.80     13421834.54
      2097182.17     13421777.25      2097183.25     13421652.47
      2097109.47     13421589.53      2097058.47     13421577.60
      2097050.80     13421524.54      2097010.80     13421484.54
      2097010.80     13421404.54      2096920.80     13421314.54
      2096920.80     13421284.54      2096890.80     13421254.54
      2096890.80     13421194.54      2096840.80     13421124.54
      2096840.80     13421044.54      2096880.80     13421004.54
      2096872.80     13420976.94      2096799.89     13420904.02
      2096661.00     13420806.80      2096483.91     13420588.05
      2096376.27     13420529.02      2096265.16     13420511.66
      2096098.50     13420532.50      2096000.80     13420564.54
      2095917.66     13420759.85      2095827.49     13420885.21
      2095453.62     13421087.53      2095350.26     13421100.73
      2095167.72     13421074.34      2095070.80     13420974.54

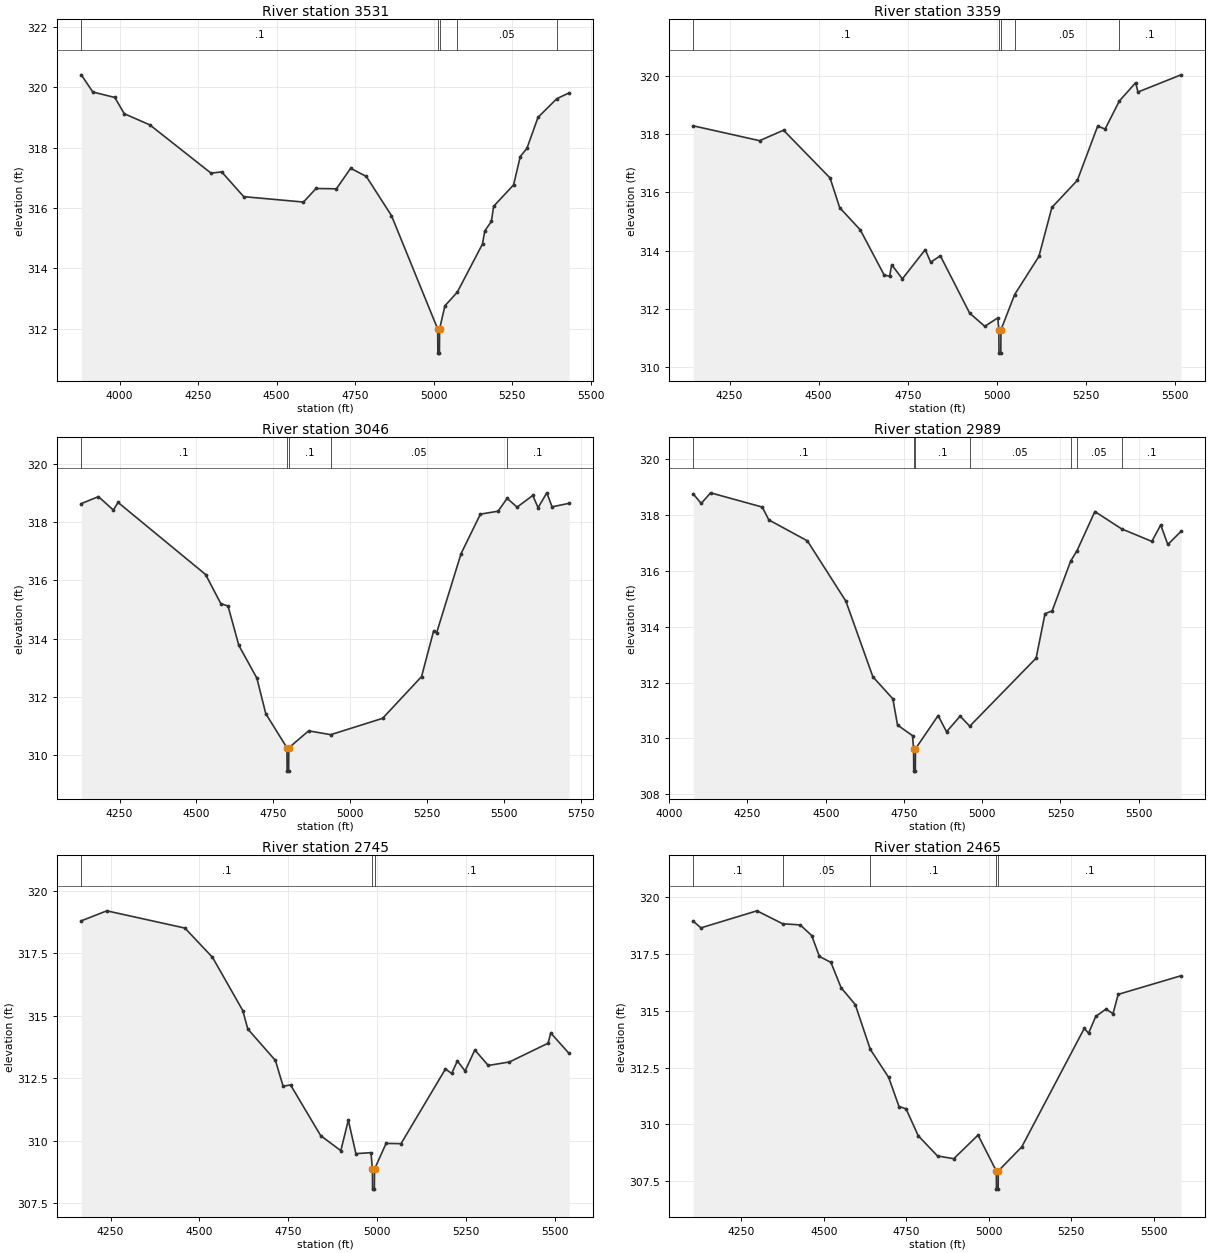
Type RM Length L Ch R = 1,3531,172,172,172
BEGIN DESCRIPTION:
UNT 095 in La Jarita Watershed 3.0
END DESCRIPTION:
XS GIS Cut Line= 3
      2098251.58     13421959.22      2097008.48     13422021.72
      2096789.32     13422239.17
#Sta/Elev= 30
  3877.8  320.42  3914.4  319.85  3984.5  319.67  4014.6  319.13  4096.1  318.76
  4290.8  317.16  4324.9  317.20  4395.0  316.38  4585.3  316.20  4625.3  316.65
  4690.2  316.64  4735.5  317.32  4785.5  317.05  4865.6  315.75  5012.8  311.99
  5013.3  311.19  5018.3  311.19  5018.8  311.99  5035.8  312.76  5075.1  313.21
  5155.5  314.81  5162.6  315.24  5183.8  315.56  5190.9  316.06  5254.5  316.77
  5275.7  317.71  5296.9  317.98  5332.3  319.01  5392.3  319.63  5431.2  319.82
#Mann=5,-1,0
  3877.8     0.1       0  5012.8    0.07       0  5018.8     0.1       0
  5075.1    0.05       0  5392.3     0.1       0
Bank Sta=5012.8,5018.8
Exp/Cntr=0.3,0.1

Type RM Length L Ch R = 1,3359,313,313,313
BEGIN DESCRIPTION:
Mapping XS a4c4ca5b
END DESCRIPTION:
XS GIS Cut Line= 3
      2097841.78     13421393.27      2096959.87     13421948.80
      2096710.29     13422160.25
#Sta/Elev= 30
  4147.9  318.28  4334.2  317.77  4401.3  318.13  4532.0  316.49  4559.1  315.47
  4616.8  314.71  4683.9  313.16  4699.1  313.12  4705.1  313.51  4735.0  313.03
  4799.2  314.03  4814.5  313.60  4841.6  313.82  4924.0  311.85  4966.4  311.40
  5002.9  311.69  5005.8  311.28  5006.3  310.48  5011.3  310.48  5011.8  311.28
  5050.2  312.49  5118.3  313.80  5154.8  315.48  5226.2  316.41  5283.3  318.27
  5304.2  318.17  5344.0  319.13  5389.9  319.76  5396.4  319.44  5517.3  320.03
#Mann=5,-1,0
  4147.9     0.1       0  5005.8    0.07       0  5011.8     0.1       0
  5050.2    0.05       0  5344.0     0.1       0
Bank Sta=5005.8,5011.8
Exp/Cntr=0.3,0.1

Type RM Length L Ch R = 1,3046,57,57,57
BEGIN DESCRIPTION:
Mapping XS bff3a81f
END DESCRIPTION:
XS GIS Cut Line= 4
      2097702.92     13421018.25      2097189.03     13421330.75
      2097050.14     13421816.86      2096616.08     13422021.74
#Sta/Elev= 30
  4125.4  318.63  4181.1  318.87  4229.6  318.41  4245.1  318.67  4529.8  316.20
  4579.4  315.20  4602.8  315.12  4637.9  313.77  4696.5  312.65  4725.6  311.43
  4794.5  310.26  4795.0  309.46  4800.0  309.46  4800.5  310.26  4865.1  310.84
  4937.1  310.71  5105.7  311.27  5232.4  312.70  5271.3  314.25  5281.7  314.21
  5361.1  316.92  5423.9  318.27  5481.4  318.37  5510.8  318.81  5543.3  318.51
  5594.3  318.91  5611.6  318.49  5639.9  319.00  5657.1  318.52  5712.4  318.64
#Mann=5,-1,0
  4125.4     0.1       0  4794.5   0.035       0  4800.5     0.1       0
  4937.1    0.05       0  5510.8     0.1       0
Bank Sta=4794.5,4800.5
Exp/Cntr=0.3,0.1

Type RM Length L Ch R = 1,2989,244,244,244
BEGIN DESCRIPTION:
Mapping XS f64cb983
END DESCRIPTION:
XS GIS Cut Line= 4
      2097671.65     13420966.18      2097091.81     13421355.05
      2097039.73     13421716.17      2096591.80     13421927.98
#Sta/Elev= 30
  4076.7  318.76  4102.1  318.42  4132.1  318.80  4297.2  318.29  4318.2  317.83
  4441.3  317.08  4564.3  314.92  4650.6  312.21  4714.4  311.42  4729.4  310.48
  4777.4  310.10  4780.7  309.63  4781.2  308.83  4786.2  308.83  4786.7  309.63
  4859.1  310.82  4886.0  310.24  4929.5  310.80  4960.2  310.44  5172.3  312.88
  5200.6  314.47  5223.4  314.57  5282.4  316.35  5303.0  316.73  5359.9  318.13
  5445.2  317.51  5542.0  317.06  5570.3  317.65  5593.0  316.95  5635.2  317.42
#Mann=7,-1,0
  4076.7     0.1       0  4780.7   0.035       0  4786.7     0.1       0
  4960.2    0.05       0  5282.4     0.1       0  5303.0    0.05       0
  5445.2     0.1       0
Bank Sta=4780.7,4786.7
Exp/Cntr=0.3,0.1

Type RM Length L Ch R = 1,2745,280,280,280
BEGIN DESCRIPTION:
Mapping XS 37f11a43
END DESCRIPTION:
XS GIS Cut Line= 4
      2097588.32     13420806.46      2097147.37     13421202.28
      2096833.34     13421501.60      2096529.96     13421669.69
#Sta/Elev= 30
  4167.8  318.80  4239.6  319.20  4459.4  318.51  4537.1  317.34  4622.3  315.21
  4636.5  314.47  4714.3  313.21  4735.9  312.18  4756.9  312.23  4841.8  310.20
  4898.4  309.60  4919.5  310.82  4940.9  309.48  4983.3  309.52  4987.3  308.86
  4987.8  308.06  4992.8  308.06  4993.3  308.86  5025.8  309.89  5067.9  309.88
  5193.0  312.87  5210.5  312.69  5226.5  313.19  5248.2  312.79  5275.7  313.63
  5313.5  313.01  5373.0  313.15  5481.8  313.90  5489.5  314.31  5541.0  313.49
#Mann=3,-1,0
  4167.8     0.1       0  4987.3    0.07       0  4993.3     0.1       0
Bank Sta=4987.3,4993.3
Exp/Cntr=0.3,0.1

Type RM Length L Ch R = 1,2465,377,377,377
BEGIN DESCRIPTION:
Mapping XS a936aae1
END DESCRIPTION:
XS GIS Cut Line= 2
      2097623.68     13420680.12      2096352.85     13421435.33
#Sta/Elev= 30
  4104.5  318.95  4127.9  318.66  4297.5  319.41  4375.6  318.84  4428.7  318.79
  4463.6  318.32  4486.8  317.40  4521.7  317.14  4552.7  316.02  4595.5  315.28
  4641.0  313.31  4696.8  312.07  4728.0  310.79  4749.4  310.69  4786.4  309.50
  4844.9  308.61  4894.0  308.49  4967.6  309.53  5023.0  307.95  5023.5  307.15
  5028.5  307.15  5029.0  307.95  5100.1  309.01  5289.5  314.23  5302.6  314.02
  5324.4  314.76  5355.3  315.08  5376.7  314.88  5392.3  315.73  5582.8  316.55
#Mann=5,-1,0
  4104.5     0.1       0  4375.6    0.05       0  4641.0     0.1       0
  5023.0    0.07       0  5029.0     0.1       0
Bank Sta=5023,5029
Exp/Cntr=0.3,0.1

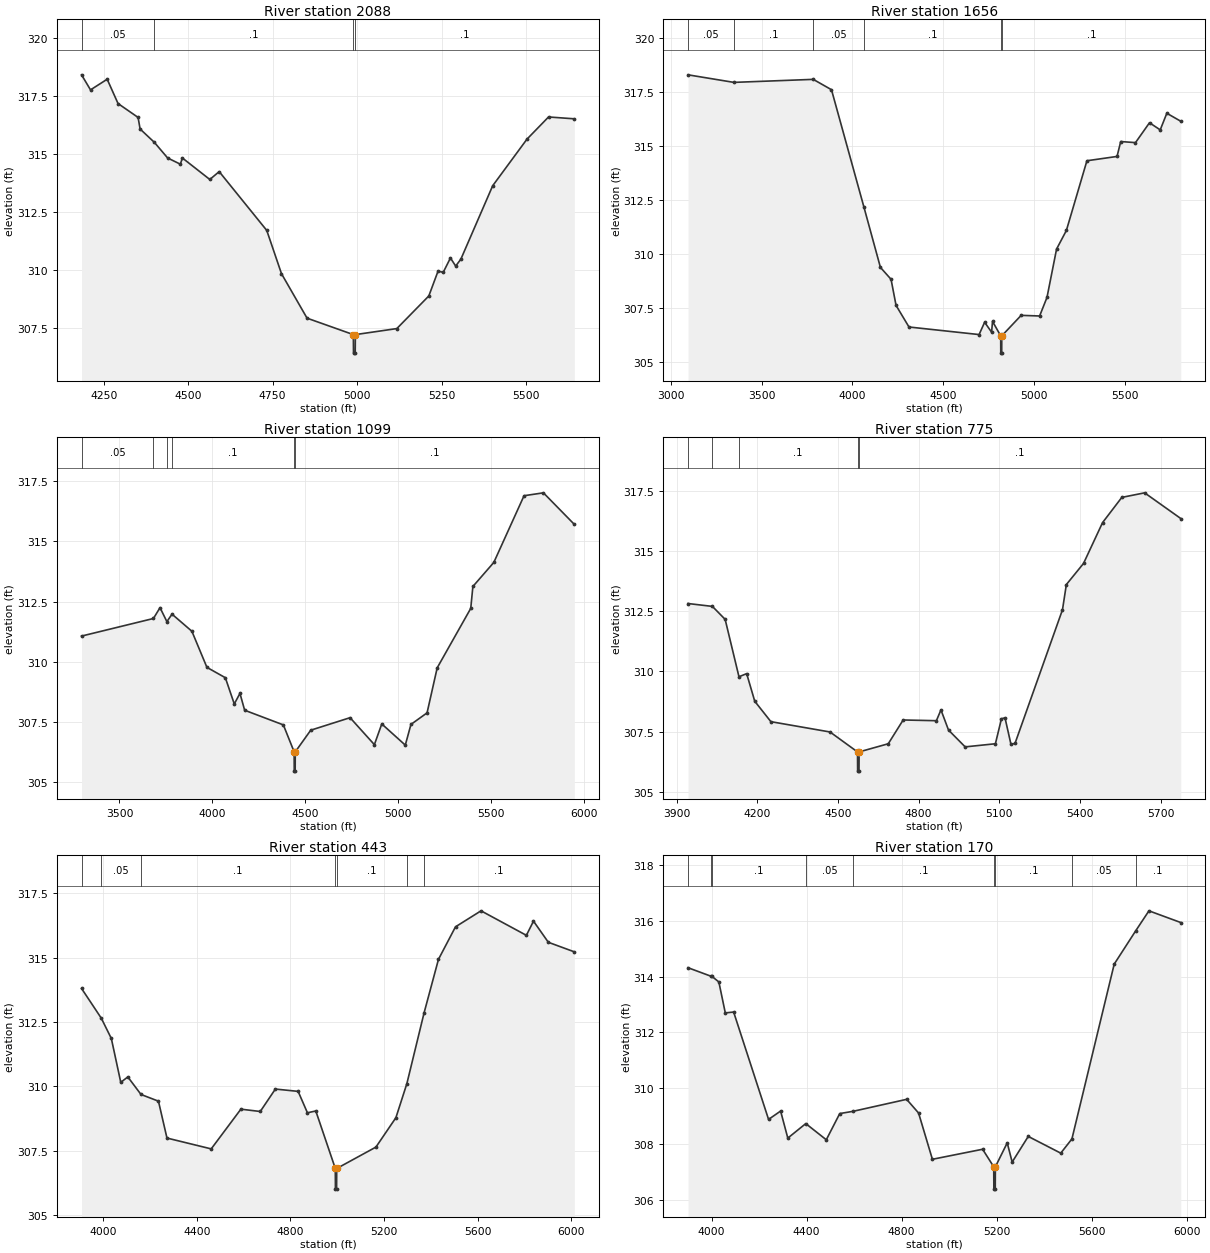
Type RM Length L Ch R = 1,2088,432,432,432
BEGIN DESCRIPTION:
Mapping XS b7e8f070
END DESCRIPTION:
XS GIS Cut Line= 3
      2097441.36     13420456.18      2096592.39     13420924.93
      2096337.65     13421340.83
#Sta/Elev= 30
  4184.7  318.42  4211.2  317.77  4260.5  318.23  4292.6  317.18  4351.9  316.58
  4357.9  316.08  4400.3  315.50  4439.2  314.83  4477.0  314.56  4482.8  314.83
  4564.1  313.90  4591.8  314.24  4732.5  311.70  4776.1  309.83  4851.7  307.91
  4988.6  307.20  4989.1  306.40  4994.1  306.40  4994.6  307.20  5117.2  307.46
  5211.9  308.87  5239.1  309.94  5254.5  309.89  5275.8  310.51  5291.3  310.16
  5306.7  310.46  5400.8  313.63  5502.1  315.64  5566.0  316.60  5642.2  316.52
#Mann=4,-1,0
  4184.7    0.05       0  4400.3     0.1       0  4988.6    0.07       0
  4994.6     0.1       0
Bank Sta=4988.6,4994.6
Exp/Cntr=0.3,0.1

Type RM Length L Ch R = 1,1656,557,557,557
BEGIN DESCRIPTION:
Mapping XS b367136d
END DESCRIPTION:
XS GIS Cut Line= 3
      2098202.56     13420120.36      2096441.35     13420440.56
      2096280.12     13421350.71
#Sta/Elev= 30
  3095.0  318.31  3347.8  317.96  3784.8  318.10  3885.3  317.62  4063.5  312.20
  4154.9  309.39  4213.4  308.84  4241.0  307.63  4312.2  306.63  4698.4  306.28
  4728.9  306.85  4767.3  306.39  4772.4  306.89  4817.4  306.22  4817.9  305.42
  4822.9  305.42  4823.4  306.22  4930.2  307.17  5031.8  307.14  5072.4  308.00
  5125.2  310.24  5179.2  311.10  5292.4  314.33  5458.3  314.53  5478.6  315.22
  5559.9  315.17  5637.1  316.09  5696.2  315.76  5732.5  316.53  5809.4  316.16
#Mann=6,-1,0
  3095.0    0.05       0  3347.8     0.1       0  3784.8    0.05       0
  4063.5     0.1       0  4817.4    0.07       0  4823.4     0.1       0
Bank Sta=4817.4,4823.4
Exp/Cntr=0.3,0.1

Type RM Length L Ch R = 1,1099,324,324,324
BEGIN DESCRIPTION:
UNT 095 in La Jarita Watershed 2.0
END DESCRIPTION:
XS GIS Cut Line= 4
      2096392.69     13419078.67      2095880.73     13420476.18
      2095989.96     13420771.11      2096274.68     13421569.73
#Sta/Elev= 30
  3296.3  311.07  3682.9  311.80  3718.4  312.25  3755.3  311.67  3783.0  311.98
  3889.8  311.27  3970.7  309.77  4069.8  309.34  4117.9  308.25  4148.4  308.69
  4173.6  307.99  4381.9  307.38  4439.9  306.26  4440.4  305.46  4445.4  305.46
  4445.9  306.26  4529.1  307.16  4740.8  307.68  4871.5  306.56  4911.3  307.42
  5037.8  306.54  5068.2  307.40  5154.9  307.88  5209.4  309.75  5389.9  312.22
  5401.4  313.13  5514.1  314.13  5676.6  316.90  5780.8  317.02  5947.0  315.71
#Mann=6,-1,0
  3296.3    0.05       0  3682.9     0.1       0  3755.3    0.05       0
  3783.0     0.1       0  4439.9    0.07       0  4445.9     0.1       0
Bank Sta=4439.9,4445.9
Exp/Cntr=0.3,0.1

Type RM Length L Ch R = 1,775,332,332,332
BEGIN DESCRIPTION:
Mapping XS 594ce80e
END DESCRIPTION:
XS GIS Cut Line= 4
      2095531.63     13419917.00      2095552.46     13420500.28
      2095878.85     13421166.95      2096197.17     13421561.39
#Sta/Elev= 30
  3942.4  312.83  4033.1  312.71  4080.5  312.17  4131.9  309.78  4160.5  309.91
  4190.6  308.76  4250.6  307.91  4470.7  307.48  4572.8  306.65  4573.3  305.85
  4578.3  305.85  4578.8  306.65  4687.2  306.99  4742.6  307.98  4866.2  307.95
  4883.2  308.40  4911.3  307.56  4973.2  306.86  5085.7  306.99  5108.2  308.03
  5121.4  308.07  5143.7  306.96  5158.8  307.01  5335.2  312.57  5349.6  313.62
  5413.5  314.50  5484.3  316.20  5555.9  317.25  5640.7  317.44  5775.2  316.37
#Mann=5,-1,0
  3942.4     0.1       0  4033.1    0.05       0  4131.9     0.1       0
  4572.8    0.07       0  4578.8     0.1       0
Bank Sta=4572.8,4578.8
Exp/Cntr=0.3,0.1

Type RM Length L Ch R = 1,443,273,273,273
BEGIN DESCRIPTION:
Mapping XS 28a75083
END DESCRIPTION:
XS GIS Cut Line= 4
      2095409.23     13420018.51      2095331.11     13420743.34
      2095530.76     13421238.13      2096239.65     13421692.16
#Sta/Elev= 30
  3908.1  313.80  3992.2  312.65  4035.3  311.86  4075.6  310.16  4105.7  310.37
  4162.0  309.69  4236.5  309.43  4272.9  308.00  4461.8  307.58  4588.5  309.12
  4671.3  309.03  4735.8  309.90  4833.0  309.81  4872.7  308.98  4908.5  309.05
  4991.8  306.82  4992.3  306.02  4997.3  306.02  4997.8  306.82  5165.3  307.65
  5250.6  308.79  5297.4  310.11  5371.1  312.86  5432.4  314.93  5505.1  316.19
  5614.1  316.81  5807.8  315.86  5838.2  316.41  5901.6  315.59  6012.5  315.22
#Mann=7,-1,0
  3908.1     0.1       0  3992.2    0.05       0  4162.0     0.1       0
  4991.8    0.07       0  4997.8     0.1       0  5297.4    0.05       0
  5371.1     0.1       0
Bank Sta=4991.8,4997.8
Exp/Cntr=0.3,0.1

Type RM Length L Ch R = 1,170,0,0,0
BEGIN DESCRIPTION:
UNT 095 in La Jarita Watershed 1.0
END DESCRIPTION:
XS GIS Cut Line= 4
      2095249.99     13420000.04      2095122.77     13420804.10
      2095279.02     13421372.68      2095847.60     13421728.58
#Sta/Elev= 30
  3901.1  314.32  3999.3  314.01  4000.2  314.02  4030.9  313.81  4058.0  312.70
  4093.2  312.73  4240.2  308.88  4290.9  309.18  4321.2  308.21  4396.9  308.73
  4483.2  308.15  4539.9  309.09  4595.7  309.17  4821.5  309.60  4871.7  309.11
  4929.9  307.45  5141.3  307.81  5188.2  307.18  5188.7  306.38  5194.5  306.38
  5195.0  307.18  5245.0  308.04  5265.7  307.35  5333.5  308.27  5470.3  307.67
  5517.3  308.18  5695.4  314.45  5785.6  315.64  5841.6  316.36  5975.6  315.94
#Mann=9,-1,0
  3901.1     0.1       0  3999.3    0.05       0  4000.2     0.1       0
  4396.9    0.05       0  4595.7     0.1       0  5188.2    0.07       0
  5195.0     0.1       0  5517.3    0.05       0  5785.6     0.1       0
Bank Sta=5188.2,5195
Exp/Cntr=0.3,0.1

Chan Stop Cuts=-1