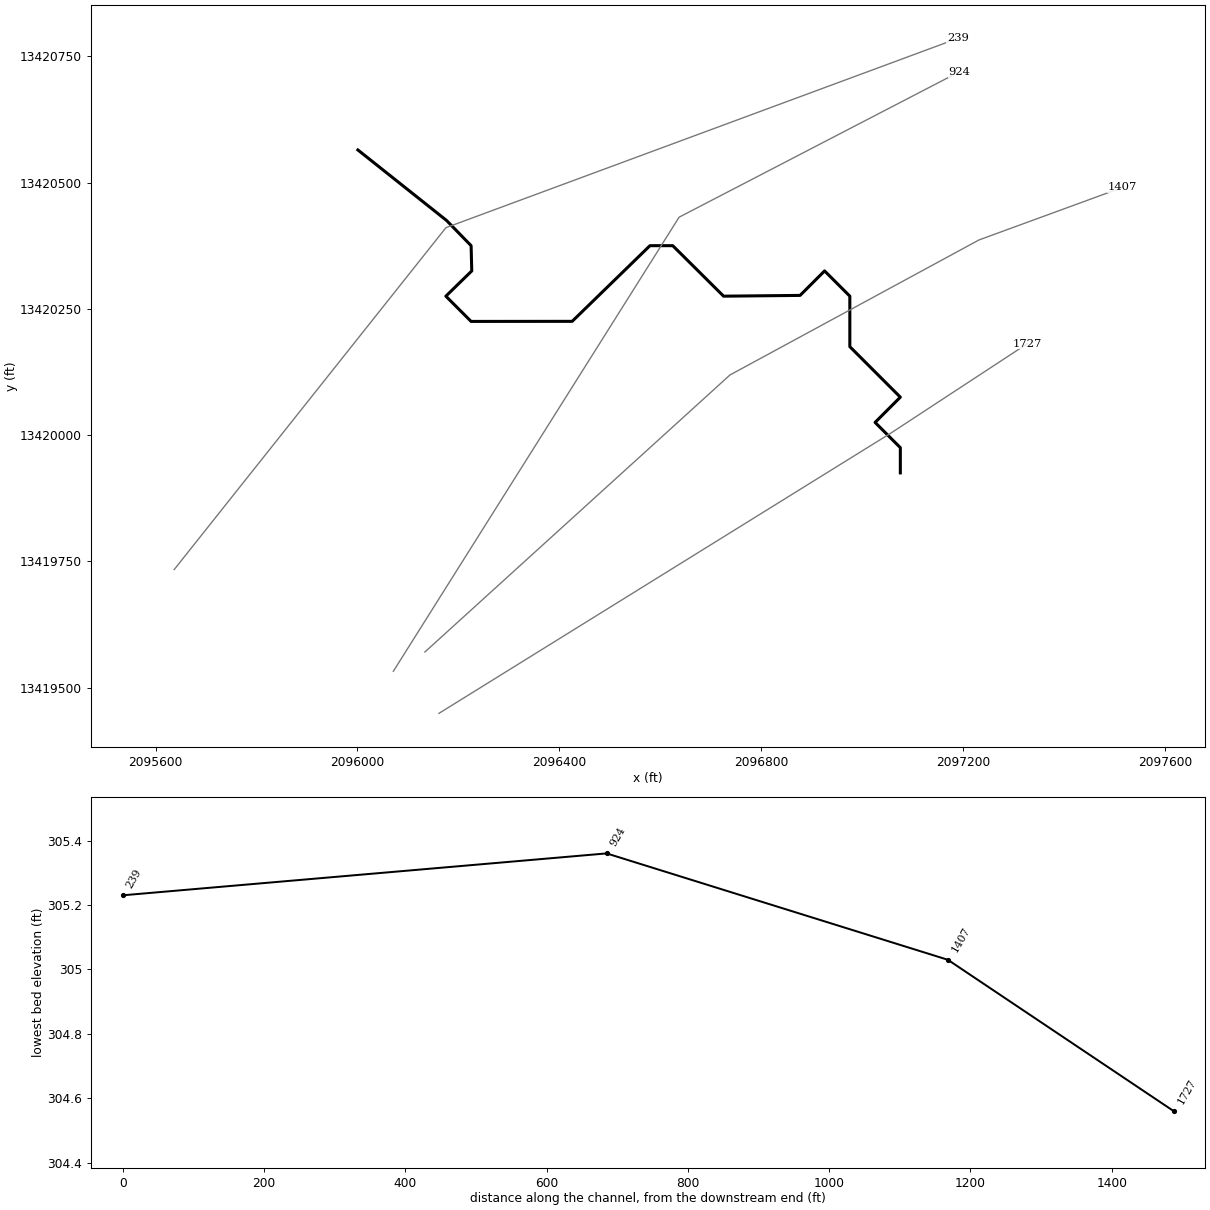
--- UNT 097 in La Jarita Watershed.prj (project) ---

Proj Title=UNT 097 in La Jarita Watershed Base Level Engineering
Current Plan=p01
Default Exp/Contr=0.3,0.1
English Units
Geom File=g01
Flow File=f01
Plan File=p01
BEGIN DESCRIPTION:
UNT 097 in La Jarita Watershed
END DESCRIPTION:

--- UNT 097 in La Jarita Watershed.p01 (plan) ---

Plan Title=Multiple Run
Short Identifier=Multiple
Geom File=g01
Flow File=f01
Subcritical Flow
K Sum by GR= 0
Std Step Tol= 0.01
Critical Tol= 0.01
Num of Std Step Trials= 20
Max Error Tol= 0.3
Flow Tol Ratio= 0.001
Split Flow NTrial= 30
Split Flow Tol= 0.02
Split Flow Ratio= 0.02
Log Output Level= 0
Friction Slope Method= 1
Unsteady Friction Slope Method= 2
Unsteady Bridges Friction Slope Method= 1
Parabolic Critical Depth
Global Vel Dist=  1 , 1 , 1
Global Log Level= 0
CheckData=True
Encroach Param= -1, 0, 0, 0
BEGIN DESCRIPTION:
Multiple Run
END DESCRIPTION:

--- UNT 097 in La Jarita Watershed.f01 (steady flow) ---

Flow Title=Multiple
Number of Profiles=7
Profile Names=10-year,25-year,50-year,1pct_min,100-year,1pct_plu,500-year
River Rch & RM= UNT 097 in La Ja,Reach-1,1727
      22      25      27      15      30      59      35
River Rch & RM= UNT 097 in La Ja,Reach-1,239
     110     145     173     103     205     410     293
Boundary for River Rch & Prof#=UNT 097 in La Ja,Reach-1,1
Up Type=0
Dn Type=3
Dn Slope=0.005
Boundary for River Rch & Prof#=UNT 097 in La Ja,Reach-1,2
Up Type=0
Dn Type=3
Dn Slope=0.005
Boundary for River Rch & Prof#=UNT 097 in La Ja,Reach-1,3
Up Type=0
Dn Type=3
Dn Slope=0.005
Boundary for River Rch & Prof#=UNT 097 in La Ja,Reach-1,4
Up Type=0
Dn Type=3
Dn Slope=0.005
Boundary for River Rch & Prof#=UNT 097 in La Ja,Reach-1,5
Up Type=0
Dn Type=3
Dn Slope=0.005
Boundary for River Rch & Prof#=UNT 097 in La Ja,Reach-1,6
Up Type=0
Dn Type=3
Dn Slope=0.005
Boundary for River Rch & Prof#=UNT 097 in La Ja,Reach-1,7
Up Type=0
Dn Type=3
Dn Slope=0.005

--- UNT 097 in La Jarita Watershed.g01 (geometry) ---

Geom Title=Existing Conditions

River Reach=UNT 097 in La Ja,Reach-1
Reach XY= 18
      2097075.00     13419925.00      2097075.00     13419975.00
      2097025.00     13420025.00      2097075.00     13420075.00
      2096975.00     13420175.00      2096975.00     13420275.00
      2096925.00     13420325.00      2096876.52     13420276.52
      2096725.00     13420275.00      2096624.33     13420375.00
      2096579.19     13420375.00      2096425.16     13420225.16
      2096225.00     13420225.00      2096175.00     13420275.00
      2096226.30     13420325.00      2096225.00     13420375.00
      2096176.30     13420425.00      2096000.80     13420564.54

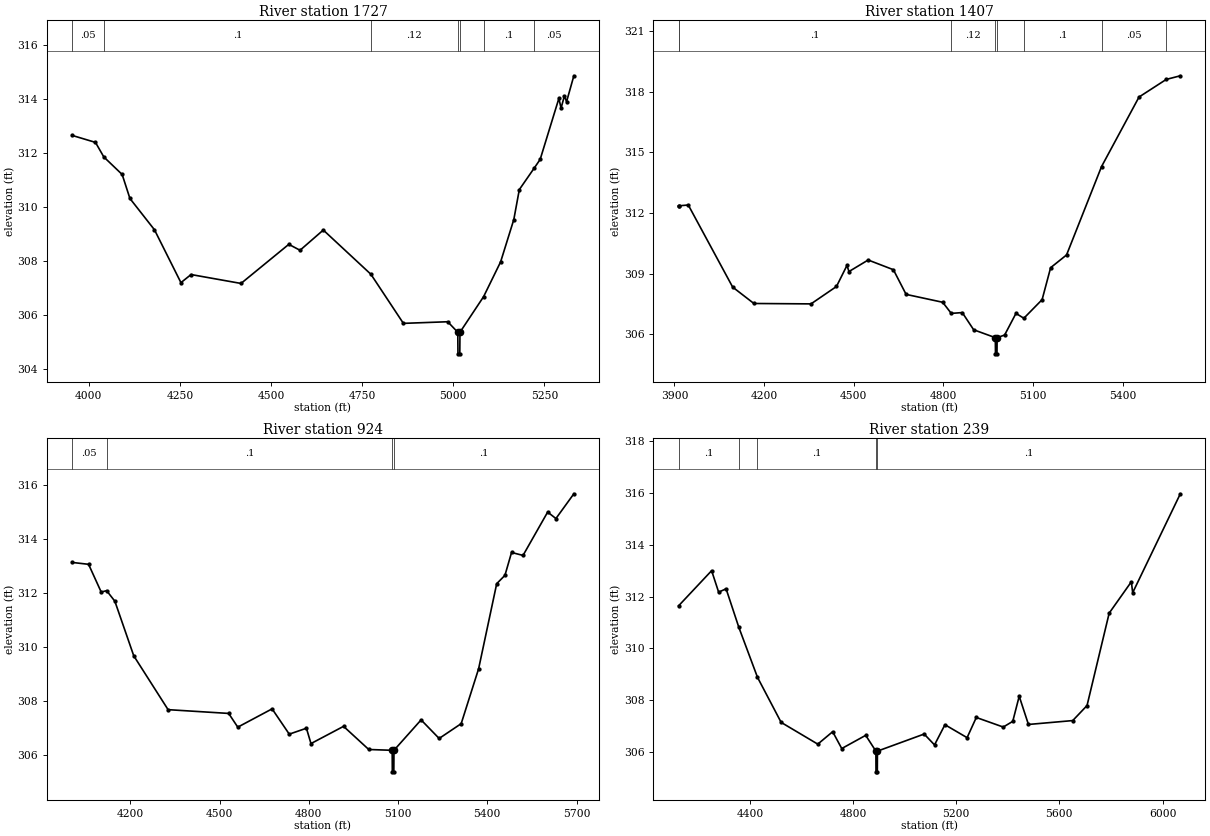
Type RM Length L Ch R = 1,1727,320,320,320
BEGIN DESCRIPTION:
UNT 097 in La Jarita Watershed 3.0
END DESCRIPTION:
XS GIS Cut Line= 3
      2096161.26     13419448.80      2097057.09     13420004.36
      2097326.63     13420181.03
#Sta/Elev= 30
  3954.2  312.66  4018.4  312.40  4041.3  311.86  4091.6  311.21  4112.9  310.32
  4180.2  309.16  4252.8  307.20  4280.6  307.50  4417.6  307.17  4548.7  308.62
  4579.5  308.40  4643.3  309.15  4773.9  307.51  4863.0  305.69  4984.6  305.75
  5012.2  305.36  5012.7  304.56  5017.7  304.56  5018.2  305.36  5083.0  306.68
  5129.7  307.97  5165.9  309.54  5181.0  310.65  5222.0  311.45  5238.2  311.77
  5289.5  314.03  5295.5  313.67  5304.6  314.12  5310.6  313.91  5330.6  314.87
#Mann=7,-1,0
  3954.2    0.05       0  4041.3     0.1       0  4773.9    0.12       0
  5012.2    0.07       0  5018.2    0.12       0  5083.0     0.1       0
  5222.0    0.05       0
Bank Sta=5012.2,5018.2
Exp/Cntr=0.3,0.1

Type RM Length L Ch R = 1,1407,483,483,483
BEGIN DESCRIPTION:
Mapping XS d3cc0fe4
END DESCRIPTION:
XS GIS Cut Line= 4
      2096133.47     13419570.32      2096737.64     13420118.94
      2097230.70     13420386.30      2097514.81     13420490.25
#Sta/Elev= 30
  3913.9  312.35  3915.5  312.35  3946.5  312.39  4095.1  308.33  4166.1  307.52
  4357.3  307.50  4442.5  308.36  4477.6  309.40  4484.4  309.10  4548.6  309.67
  4633.0  309.19  4675.6  307.97  4798.0  307.58  4826.7  307.03  4863.6  307.07
  4901.7  306.22  4974.2  305.83  4974.7  305.03  4979.7  305.03  4980.2  305.83
  5005.3  305.96  5043.3  307.03  5069.7  306.79  5130.8  307.71  5159.3  309.29
  5212.6  309.92  5329.7  314.29  5455.2  317.73  5546.3  318.60  5593.4  318.78
#Mann=8,-1,0
  3913.9    0.05       0  3915.5     0.1       0  4826.7    0.12       0
  4974.2    0.07       0  4980.2    0.12       0  5069.7     0.1       0
  5329.7    0.05       0  5546.3     0.1       0
Bank Sta=4974.2,4980.2
Exp/Cntr=0.3,0.1

Type RM Length L Ch R = 1,924,685,685,685
BEGIN DESCRIPTION:
UNT 097 in La Jarita Watershed 2.0
END DESCRIPTION:
XS GIS Cut Line= 3
      2096070.97     13419532.13      2096636.95     13420431.44
      2097191.22     13420718.97
#Sta/Elev= 30
  4004.1  313.14  4059.6  313.07  4102.0  312.04  4120.3  312.09  4147.9  311.70
  4211.5  309.67  4326.9  307.67  4530.6  307.53  4561.2  307.02  4676.6  307.70
  4734.3  306.76  4792.0  306.98  4807.3  306.41  4916.8  307.05  5001.6  306.19
  5080.3  306.16  5080.8  305.36  5085.8  305.36  5086.3  306.16  5177.5  307.29
  5238.2  306.60  5312.3  307.15  5370.9  309.19  5431.7  312.35  5459.4  312.66
  5481.6  313.51  5520.2  313.40  5603.0  315.01  5630.8  314.77  5691.1  315.69
#Mann=4,-1,0
  4004.1    0.05       0  4120.3     0.1       0  5080.3    0.07       0
  5086.3     0.1       0
Bank Sta=5080.3,5086.3
Exp/Cntr=0.3,0.1

Type RM Length L Ch R = 1,239,0,0,0
BEGIN DESCRIPTION:
UNT 097 in La Jarita Watershed 1.0
END DESCRIPTION:
XS GIS Cut Line= 3
      2095636.96     13419733.54      2096175.14     13420410.61
      2097189.01     13420785.60
#Sta/Elev= 30
  4123.2  311.64  4251.5  313.00  4278.7  312.17  4307.6  312.30  4357.1  310.81
  4429.4  308.88  4521.1  307.14  4663.2  306.30  4720.9  306.78  4756.1  306.13
  4849.0  306.64  4888.5  306.03  4889.0  305.23  4894.0  305.23  4894.5  306.03
  5075.7  306.69  5115.9  306.27  5156.3  307.05  5242.2  306.55  5277.9  307.33
  5382.4  306.96  5419.3  307.18  5444.3  308.15  5480.1  307.06  5651.9  307.21
  5707.3  307.79  5793.2  311.36  5879.1  312.57  5884.4  312.15  6069.1  315.97
#Mann=5,-1,0
  4123.2     0.1       0  4357.1    0.05       0  4429.4     0.1       0
  4888.5    0.07       0  4894.5     0.1       0
Bank Sta=4888.5,4894.5
Exp/Cntr=0.3,0.1

Chan Stop Cuts=-1