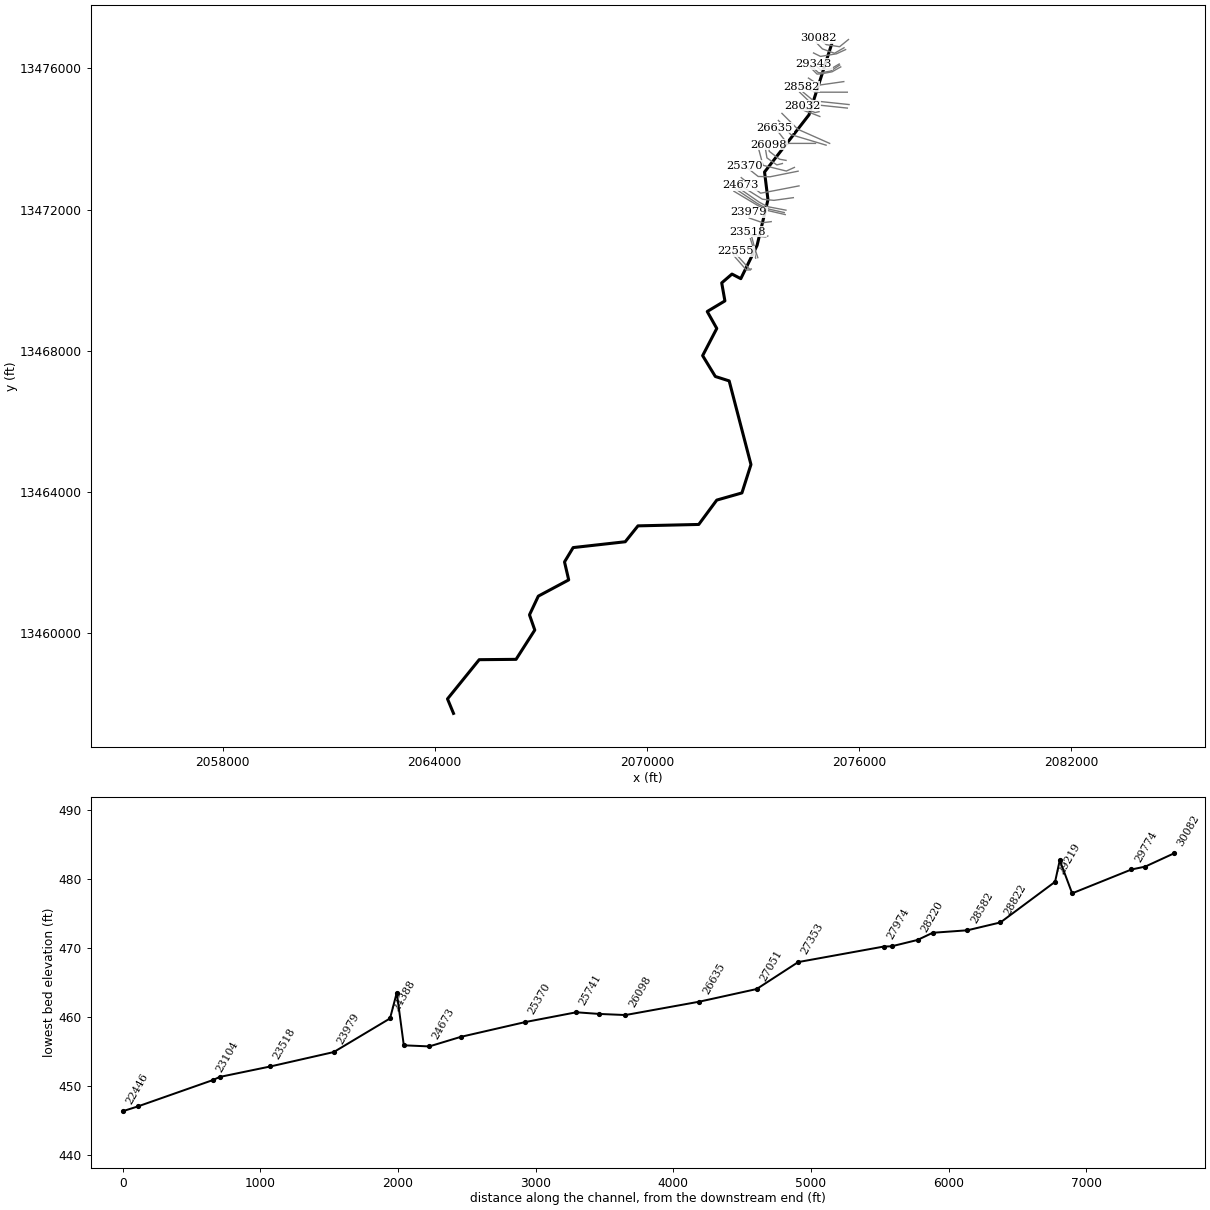
--- BEAR Br.prj (project) ---

Proj Title=BEAR Br Base Level Engineering
Current Plan=p01
Default Exp/Contr=0.3,0.1
English Units
Geom File=g01
Flow File=f01
Plan File=p01
BEGIN DESCRIPTION:
BEAR Br
END DESCRIPTION:

--- BEAR Br.p01 (plan) ---

Plan Title=Multiple Run
Short Identifier=Multiple
Geom File=g01
Flow File=f01
Subcritical Flow
K Sum by GR= 0
Std Step Tol= 0.01
Critical Tol= 0.01
Num of Std Step Trials= 20
Max Error Tol= 0.3
Flow Tol Ratio= 0.001
Split Flow NTrial= 30
Split Flow Tol= 0.02
Split Flow Ratio= 0.02
Log Output Level= 0
Friction Slope Method= 1
Unsteady Friction Slope Method= 2
Unsteady Bridges Friction Slope Method= 1
Parabolic Critical Depth
Global Vel Dist=  1 , 1 , 1
Global Log Level= 0
CheckData=True
Encroach Param= -1, 0, 0, 0
BEGIN DESCRIPTION:
Multiple Run
END DESCRIPTION:

--- BEAR Br.f01 (steady flow) ---

Flow Title=Multiple
Number of Profiles=7
Profile Names=10-year,25-year,50-year,1pct_min,100-year,1pct_plu,500-year
River Rch & RM= BEAR Br,Reach-1,30082
     161     216     261     157     313     625     458
River Rch & RM= BEAR Br,Reach-1,25370
     292     405     499     306     612    1220     931
River Rch & RM= BEAR Br,Reach-1,16890
     415     586     730     453     903    1802    1404
River Rch & RM= BEAR Br,Reach-1,13592
     454     643     803     498     994    1984    1550
River Rch & RM= BEAR Br,Reach-1,9514
     499     709     887     552    1101    2196    1723
River Rch & RM= BEAR Br,Reach-1,5302
     545     778     975     608    1214    2422    1909
Boundary for River Rch & Prof#=BEAR Br,Reach-1,1
Up Type=0
Dn Type=3
Dn Slope=0.005
Boundary for River Rch & Prof#=BEAR Br,Reach-1,2
Up Type=0
Dn Type=3
Dn Slope=0.005
Boundary for River Rch & Prof#=BEAR Br,Reach-1,3
Up Type=0
Dn Type=3
Dn Slope=0.005
Boundary for River Rch & Prof#=BEAR Br,Reach-1,4
Up Type=0
Dn Type=3
Dn Slope=0.005
Boundary for River Rch & Prof#=BEAR Br,Reach-1,5
Up Type=0
Dn Type=3
Dn Slope=0.005
Boundary for River Rch & Prof#=BEAR Br,Reach-1,6
Up Type=0
Dn Type=3
Dn Slope=0.005
Boundary for River Rch & Prof#=BEAR Br,Reach-1,7
Up Type=0
Dn Type=3
Dn Slope=0.005

--- BEAR Br.g01 (geometry) ---

Geom Title=Existing Conditions

River Reach=BEAR Br,Reach-1
Reach XY= 30
      2075230.80     13476684.54      2074590.80     13474684.54
      2073332.77     13473064.36      2073429.43     13472279.94
      2073120.80     13470984.54      2072660.80     13470044.54
      2072410.80     13470174.54      2072120.80     13469924.54
      2072210.80     13469414.54      2071710.80     13469114.54
      2071980.80     13468634.54      2071580.80     13467864.54
      2071939.84     13467274.44      2072331.51     13467149.44
      2072948.42     13464781.08      2072692.50     13463976.98
      2071980.80     13463774.54      2071470.80     13463084.54
      2069750.80     13463044.54      2069390.80     13462594.54
      2067916.29     13462429.16      2067672.15     13462023.34
      2067790.80     13461514.54      2066930.80     13461054.54
      2066680.80     13460524.54      2066830.80     13460094.54
      2066300.80     13459264.54      2065258.01     13459254.91
      2064360.80     13458144.54      2064530.80     13457734.54

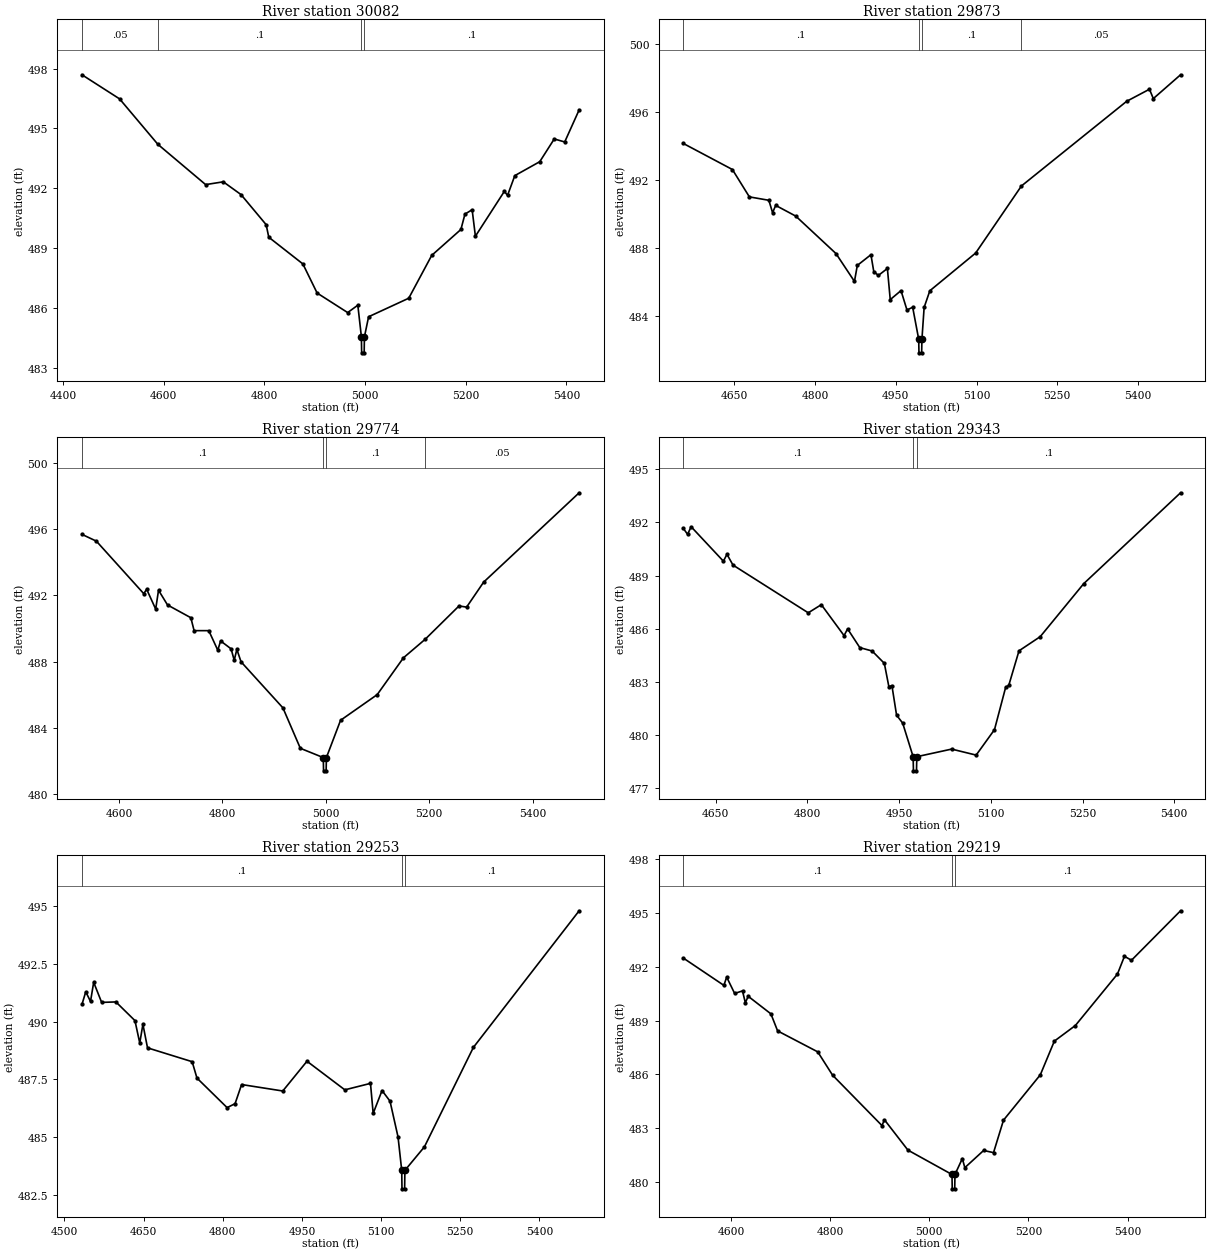
Type RM Length L Ch R = 1,30082,209,209,209
BEGIN DESCRIPTION:
Mapping XS f53ea9ae
END DESCRIPTION:
XS GIS Cut Line= 4
      2075708.16     13476817.02      2075456.45     13476612.72
      2075081.45     13476671.31      2074860.20     13476850.11
#Sta/Elev= 30
  4437.3  497.69  4512.1  496.48  4588.2  494.20  4683.1  492.18  4718.2  492.32
  4753.4  491.68  4803.4  490.17  4808.6  489.54  4876.4  488.20  4904.7  486.74
  4965.4  485.76  4985.6  486.13  4992.7  484.54  4993.2  483.74  4998.2  483.74
  4998.7  484.54  5007.0  485.55  5086.8  486.48  5132.5  488.63  5190.5  489.93
  5198.5  490.70  5212.8  490.92  5219.3  489.59  5276.8  491.84  5283.2  491.64
  5297.6  492.63  5347.2  493.33  5376.0  494.47  5396.8  494.32  5425.5  495.93
#Mann=4,-1,0
  4437.3    0.05       0  4588.2     0.1       0  4992.7    0.07       0
  4998.7     0.1       0
Bank Sta=4992.7,4998.7
Exp/Cntr=0.3,0.1

Type RM Length L Ch R = 1,29873,99,99,99
BEGIN DESCRIPTION:
Mapping XS 2cb169a9
END DESCRIPTION:
XS GIS Cut Line= 4
      2075582.66     13476583.37      2075311.41     13476427.13
      2074970.70     13476550.83      2074797.09     13476728.78
#Sta/Elev= 30
  4555.1  494.13  4646.2  492.60  4677.8  490.99  4714.0  490.79  4720.9  490.06
  4726.7  490.49  4764.0  489.86  4838.7  487.66  4873.1  486.02  4878.4  486.96
  4903.7  487.59  4909.0  486.60  4917.5  486.37  4934.3  486.78  4939.6  484.95
  4959.6  485.48  4970.7  484.34  4981.3  484.50  4992.5  482.62  4993.0  481.82
  4998.0  481.82  4998.5  482.62  5002.6  484.49  5013.2  485.47  5098.4  487.69
  5183.4  491.63  5379.0  496.61  5421.4  497.32  5428.6  496.77  5479.2  498.17
#Mann=4,-1,0
  4555.1     0.1       0  4992.5    0.07       0  4998.5     0.1       0
  5183.4    0.05       0
Bank Sta=4992.5,4998.5
Exp/Cntr=0.3,0.1

Type RM Length L Ch R = 1,29774,431,431,431
BEGIN DESCRIPTION:
Mapping XS 425b701a
END DESCRIPTION:
XS GIS Cut Line= 4
      2075626.12     13476531.32      2075367.83     13476411.94
      2074916.45     13476338.16      2074719.44     13476435.58
#Sta/Elev= 30
  4528.3  495.68  4556.2  495.27  4647.9  492.10  4653.4  492.37  4670.9  491.17
  4676.4  492.31  4693.8  491.42  4738.9  490.65  4745.2  489.87  4773.6  489.87
  4791.0  488.69  4796.5  489.25  4816.8  488.77  4822.8  488.08  4827.9  488.74
  4836.0  487.99  4917.0  485.21  4950.7  482.77  4995.1  482.21  4995.6  481.41
  5000.6  481.41  5001.1  482.21  5028.5  484.46  5099.4  486.01  5150.1  488.23
  5192.2  489.35  5257.6  491.36  5272.3  491.29  5305.3  492.80  5490.0  498.19
#Mann=4,-1,0
  4528.3     0.1       0  4995.1    0.07       0  5001.1     0.1       0
  5192.2    0.05       0
Bank Sta=4995.1,5001.1
Exp/Cntr=0.3,0.1

Type RM Length L Ch R = 1,29343,90,90,90
BEGIN DESCRIPTION:
Mapping XS d767f952
END DESCRIPTION:
XS GIS Cut Line= 4
      2075445.50     13476123.79      2075205.93     13475983.17
      2074906.45     13475967.55      2074729.69     13476123.51
#Sta/Elev= 30
  4597.0  491.66  4603.9  491.33  4609.7  491.76  4662.5  489.81  4668.3  490.20
  4678.2  489.59  4801.3  486.89  4822.7  487.35  4859.9  485.60  4865.7  485.98
  4885.7  484.92  4905.8  484.73  4925.8  484.03  4933.2  482.71  4938.2  482.77
  4945.8  481.10  4955.8  480.65  4972.9  478.75  4973.4  477.95  4978.4  477.95
  4978.9  478.75  5035.9  479.18  5076.0  478.84  5106.0  480.28  5124.3  482.68
  5129.3  482.78  5146.1  484.74  5180.8  485.54  5252.0  488.54  5410.4  493.68
#Mann=3,-1,0
  4597.0     0.1       0  4972.9    0.07       0  4978.9     0.1       0
Bank Sta=4972.9,4978.9
Exp/Cntr=0.3,0.1

Type RM Length L Ch R = 1,29253,34,34,34
BEGIN DESCRIPTION:
Mapping XS c9fc64bc
END DESCRIPTION:
XS GIS Cut Line= 5
      2075458.62     13476092.21      2075202.54     13475922.94
      2074930.19     13475874.11      2074857.49     13475877.36
      2074648.04     13476071.62
#Sta/Elev= 30
  4533.3  490.74  4540.5  491.29  4549.5  490.87  4555.5  491.70  4570.6  490.83
  4597.6  490.85  4633.7  490.04  4642.8  489.07  4648.8  489.88  4657.5  488.86
  4742.1  488.26  4751.2  487.55  4808.3  486.27  4823.4  486.44  4835.8  487.27
  4913.8  486.99  4959.7  488.28  5031.4  487.04  5080.0  487.32  5085.1  486.02
  5101.9  487.01  5117.0  486.55  5132.2  485.00  5139.2  483.55  5139.7  482.75
  5144.7  482.75  5145.2  483.55  5182.2  484.57  5275.0  488.88  5475.4  494.80
#Mann=3,-1,0
  4533.3     0.1       0  5139.2    0.07       0  5145.2     0.1       0
Bank Sta=5139.2,5145.2
Exp/Cntr=0.3,0.1

Type RM Length L Ch R = 1,29219,397,397,397
BEGIN DESCRIPTION:
Mapping XS 19dca1a1
END DESCRIPTION:
XS GIS Cut Line= 5
      2075489.03     13476041.22      2075241.60     13475902.32
      2074943.21     13475845.90      2074819.51     13475837.22
      2074613.34     13476043.39
#Sta/Elev= 30
  4503.8  492.49  4585.5  490.97  4591.2  491.43  4607.2  490.52  4623.1  490.66
  4628.8  490.00  4634.6  490.36  4680.4  489.38  4693.9  488.43  4774.9  487.26
  4804.8  485.96  4904.4  483.15  4909.5  483.47  4956.8  481.78  5045.7  480.42
  5046.2  479.62  5051.2  479.62  5051.7  480.42  5066.6  481.31  5071.6  480.80
  5109.5  481.76  5129.5  481.64  5149.6  483.45  5223.9  485.98  5252.2  487.86
  5294.6  488.73  5379.5  491.60  5393.6  492.59  5407.8  492.37  5506.8  495.13
#Mann=3,-1,0
  4503.8     0.1       0  5045.7    0.07       0  5051.7     0.1       0
Bank Sta=5045.7,5051.7
Exp/Cntr=0.3,0.1

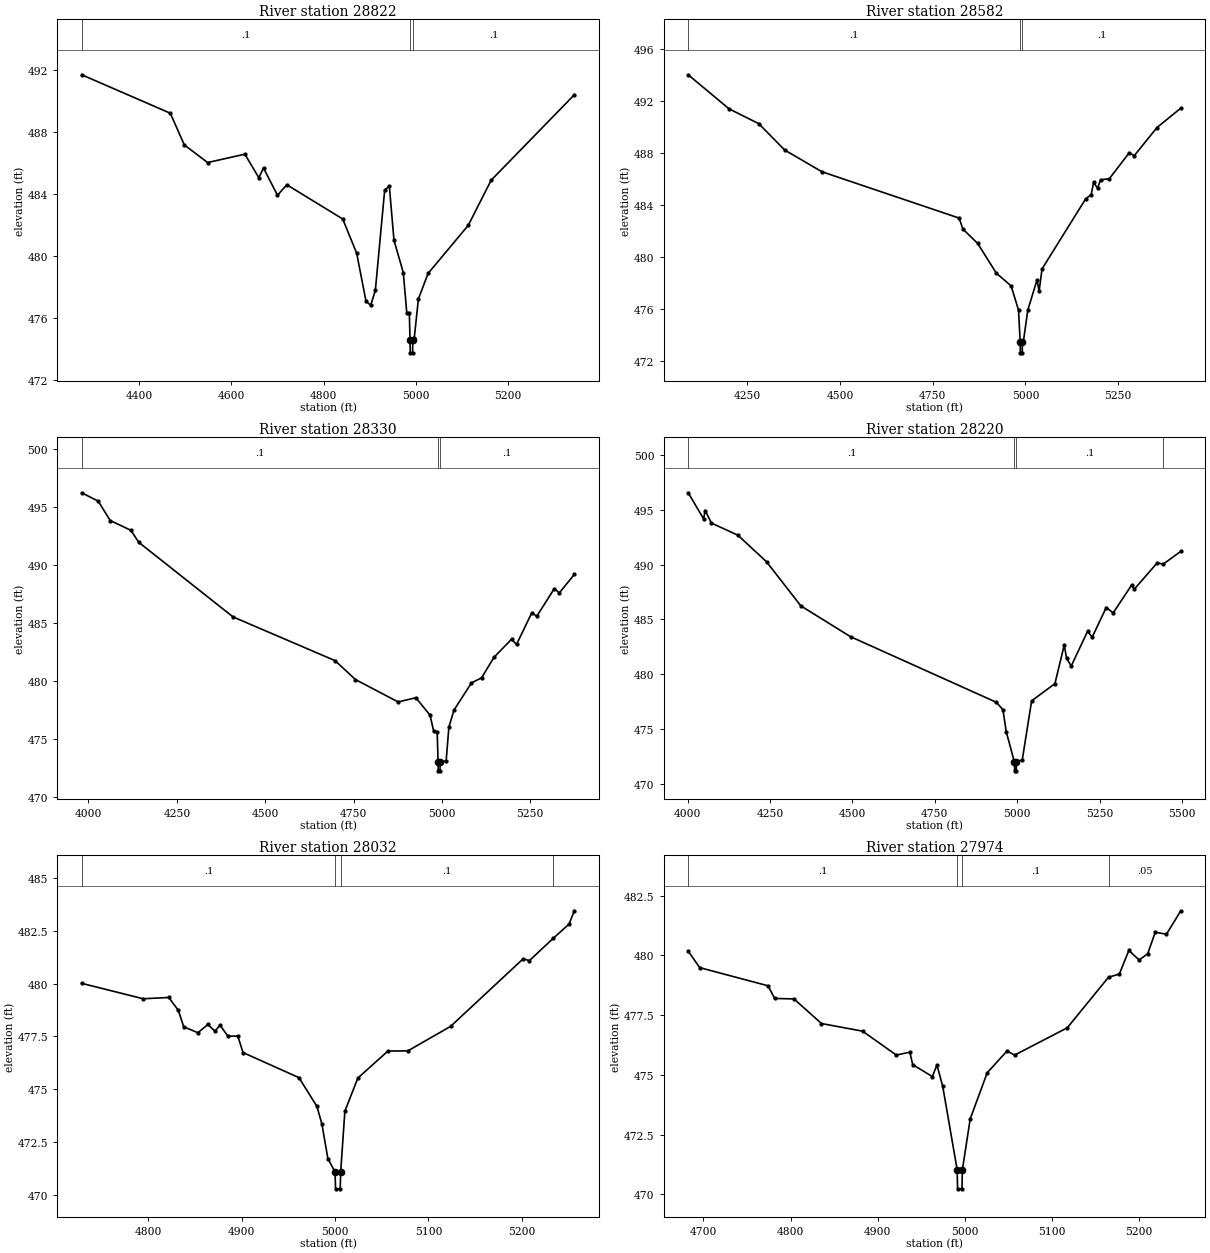
Type RM Length L Ch R = 1,28822,240,240,240
BEGIN DESCRIPTION:
BEAR Br 61.0
END DESCRIPTION:
XS GIS Cut Line= 3
      2075575.03     13475625.00      2074875.00     13475525.00
      2074574.99     13475725.01
#Sta/Elev= 30
  4275.8  491.66  4467.8  489.18  4498.1  487.14  4548.6  486.00  4629.4  486.54
  4659.7  485.02  4669.8  485.65  4700.1  483.89  4720.3  484.57  4841.5  482.36
  4871.8  480.15  4892.0  477.05  4902.1  476.80  4912.2  477.75  4932.4  484.21
  4942.5  484.49  4952.6  480.99  4972.8  478.90  4980.4  476.29  4985.9  476.29
  4987.4  474.53  4987.9  473.73  4992.9  473.73  4993.4  474.53  4996.5  474.66
  5005.5  477.20  5026.5  478.85  5113.6  481.95  5163.2  484.86  5343.5  490.37
#Mann=3,-1,0
  4275.8     0.1       0  4987.4    0.07       0  4993.4     0.1       0
Bank Sta=4987.4,4993.4
Exp/Cntr=0.3,0.1

Type RM Length L Ch R = 1,28582,252,252,252
BEGIN DESCRIPTION:
BEAR Br 60.0
END DESCRIPTION:
XS GIS Cut Line= 3
      2075674.98     13475325.00      2074775.00     13475325.00
      2074374.99     13475475.01
#Sta/Elev= 30
  4091.3  493.99  4201.3  491.37  4281.3  490.23  4351.3  488.20  4451.3  486.53
  4821.3  482.96  4831.3  482.12  4871.3  481.01  4921.3  478.73  4961.3  477.74
  4981.3  475.88  4985.8  473.39  4986.3  472.59  4991.3  472.59  4991.8  473.39
  4994.0  473.39  5006.4  475.89  5031.3  478.21  5036.7  477.33  5044.7  479.05
  5162.2  484.44  5177.3  484.77  5183.5  485.72  5194.2  485.26  5202.2  485.90
  5226.2  486.00  5279.6  487.99  5293.0  487.76  5354.4  489.93  5418.5  491.42
#Mann=3,-1,0
  4091.3     0.1       0  4985.8    0.07       0  4991.8     0.1       0
Bank Sta=4985.8,4991.8
Exp/Cntr=0.3,0.1

Type RM Length L Ch R = 1,28330,110,110,110
BEGIN DESCRIPTION:
BEAR Br 59.0
END DESCRIPTION:
XS GIS Cut Line= 3
      2075725.04     13474975.00      2074719.04     13475081.23
      2074425.03     13475324.98
#Sta/Elev= 30
  3981.0  496.20  4027.5  495.48  4061.5  493.81  4120.3  492.96  4141.9  491.94
  4409.0  485.50  4697.6  481.73  4755.3  480.10  4876.0  478.17  4926.3  478.53
  4966.5  477.02  4976.2  475.70  4986.6  475.54  4989.1  473.03  4989.6  472.23
  4994.6  472.23  4995.1  473.03  5011.8  473.06  5019.7  476.01  5034.0  477.46
  5083.5  479.81  5112.1  480.25  5147.3  482.02  5196.8  483.57  5211.1  483.13
  5254.1  485.85  5268.4  485.56  5317.9  487.94  5332.2  487.57  5374.5  489.16
#Mann=3,-1,0
  3981.0     0.1       0  4989.1    0.07       0  4995.1     0.1       0
Bank Sta=4989.1,4995.1
Exp/Cntr=0.3,0.1

Type RM Length L Ch R = 1,28220,188,188,188
BEGIN DESCRIPTION:
BEAR Br 58.0
END DESCRIPTION:
XS GIS Cut Line= 3
      2075675.04     13474875.00      2074684.66     13474978.89
      2074324.97     13475325.03
#Sta/Elev= 30
  4001.6  496.54  4048.2  494.17  4053.2  494.92  4072.0  493.78  4152.5  492.67
  4239.6  490.24  4343.5  486.23  4494.3  483.42  4936.7  477.44  4956.8  476.77
  4966.9  474.75  4991.7  471.99  4992.2  471.19  4997.2  471.19  4997.7  471.99
  5015.6  472.21  5043.9  477.57  5114.6  479.14  5142.9  482.66  5149.9  481.46
  5164.0  480.74  5213.7  483.91  5227.8  483.38  5270.3  486.08  5291.4  485.59
  5348.0  488.15  5355.2  487.74  5425.9  490.18  5442.2  490.01  5496.6  491.20
#Mann=4,-1,0
  4001.6     0.1       0  4991.7    0.07       0  4997.7     0.1       0
  5442.2    0.05       0
Bank Sta=4991.7,4997.7
Exp/Cntr=0.3,0.1

Type RM Length L Ch R = 1,28032,58,58,58
BEGIN DESCRIPTION:
Mapping XS 9915cdab
END DESCRIPTION:
XS GIS Cut Line= 4
      2074876.04     13474773.96      2074764.23     13474749.00
      2074522.26     13474842.31      2074408.65     13474946.27
#Sta/Elev= 30
  4728.5  480.01  4794.4  479.28  4821.8  479.34  4832.0  478.73  4837.8  477.95
  4853.0  477.67  4863.7  478.06  4871.3  477.74  4876.7  478.03  4885.1  477.51
  4895.8  477.51  4901.3  476.73  4961.3  475.54  4980.5  474.18  4985.9  473.34
  4992.3  471.70  5000.0  471.07  5000.5  470.27  5005.5  470.27  5006.0  471.07
  5010.5  473.95  5024.4  475.52  5056.6  476.80  5078.0  476.81  5123.8  477.97
  5201.5  481.17  5208.3  481.09  5233.7  482.14  5250.8  482.82  5256.4  483.45
#Mann=4,-1,0
  4728.5     0.1       0  5000.0    0.07       0  5006.0     0.1       0
  5233.7    0.05       0
Bank Sta=5000,5006
Exp/Cntr=0.3,0.1

Type RM Length L Ch R = 1,27974,621,621,621
BEGIN DESCRIPTION:
Mapping XS 01f93537
END DESCRIPTION:
XS GIS Cut Line= 4
      2074897.32     13474637.34      2074655.10     13474732.40
      2074519.69     13474777.97      2074369.89     13474839.96
#Sta/Elev= 30
  4682.5  480.18  4695.7  479.49  4774.1  478.73  4781.7  478.20  4803.9  478.18
  4835.4  477.15  4882.6  476.83  4921.3  475.83  4936.8  475.95  4940.1  475.43
  4962.6  474.93  4967.9  475.41  4974.5  474.53  4991.1  471.03  4991.6  470.23
  4996.6  470.23  4997.1  471.03  5006.1  473.16  5025.6  475.09  5048.3  476.00
  5057.1  475.83  5117.4  476.97  5164.8  479.09  5177.2  479.22  5188.1  480.21
  5199.9  479.81  5209.7  480.07  5218.4  480.97  5231.3  480.89  5247.7  481.87
#Mann=4,-1,0
  4682.5     0.1       0  4991.1    0.07       0  4997.1     0.1       0
  5164.8    0.05       0
Bank Sta=4991.1,4997.1
Exp/Cntr=0.3,0.1

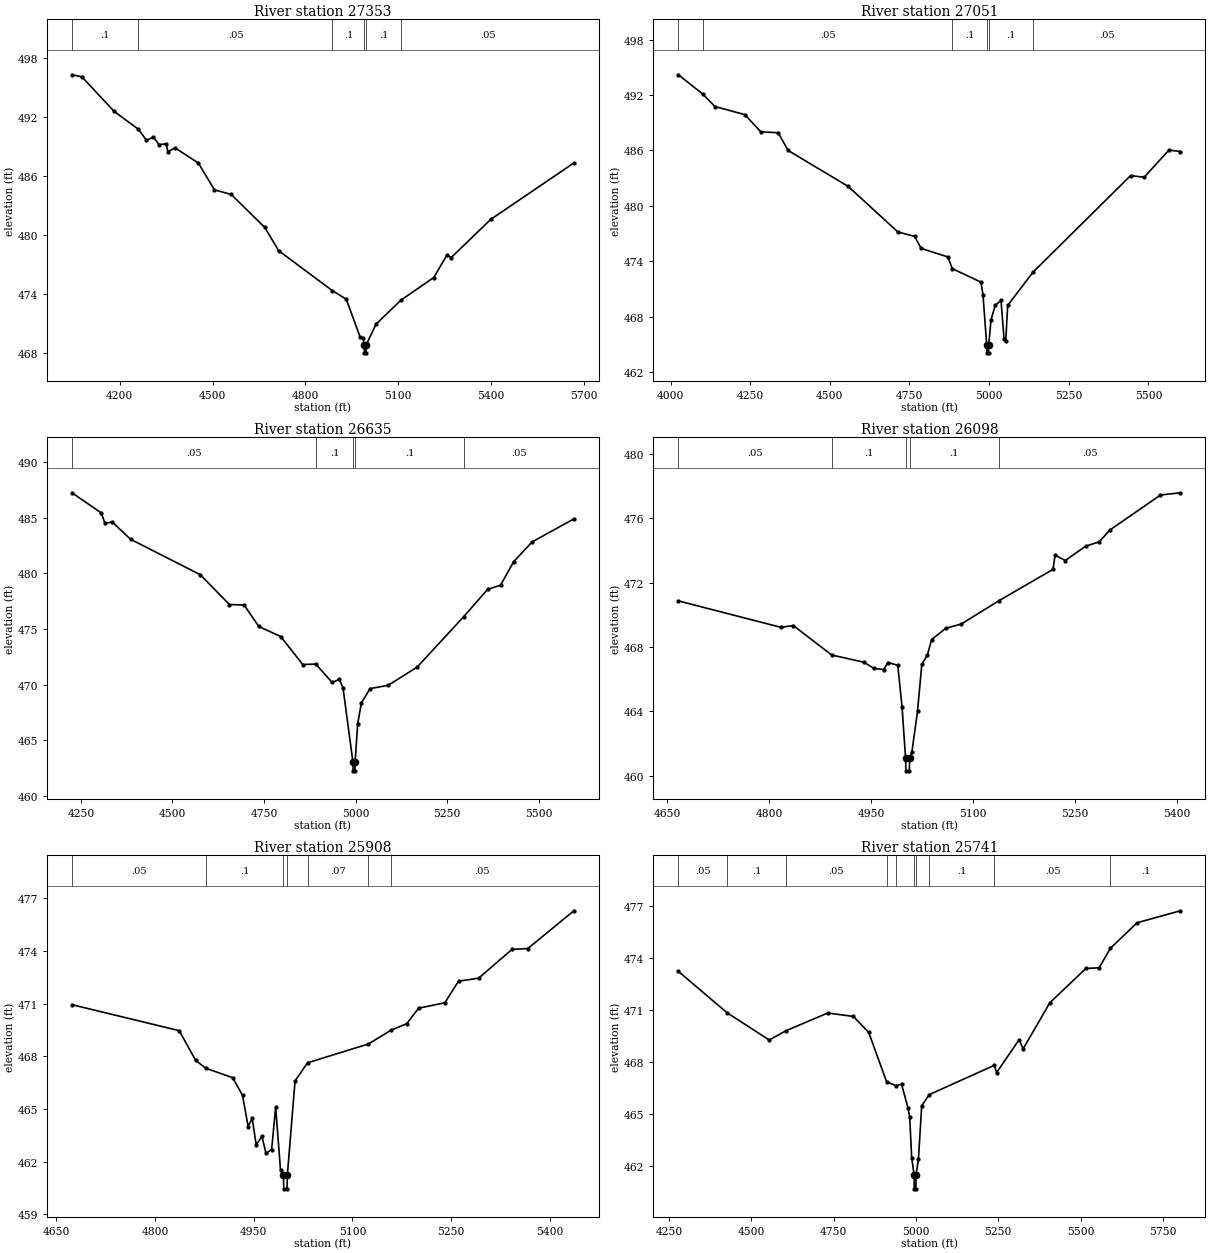
Type RM Length L Ch R = 1,27353,302,302,302
BEGIN DESCRIPTION:
BEAR Br 55.0
END DESCRIPTION:
XS GIS Cut Line= 3
      2075175.03     13473874.99      2074275.00     13474275.00
      2073825.01     13474724.99
#Sta/Elev= 30
  4045.6  496.33  4077.8  496.12  4181.7  492.60  4260.5  490.77  4286.4  489.65
  4309.0  489.98  4326.7  489.21  4350.0  489.29  4355.5  488.48  4378.7  488.88
  4453.9  487.33  4505.9  484.60  4560.0  484.13  4668.7  480.76  4713.2  478.40
  4886.9  474.32  4932.0  473.44  4975.8  469.64  4986.7  469.49  4989.9  468.78
  4990.4  467.98  4995.4  467.98  4995.9  468.78  5027.8  470.90  5108.3  473.35
  5214.4  475.66  5256.8  477.94  5270.9  477.70  5398.2  481.58  5666.9  487.34
#Mann=6,-1,0
  4045.6     0.1       0  4260.5    0.05       0  4886.9     0.1       0
  4989.9    0.07       0  4995.9     0.1       0  5108.3    0.05       0
Bank Sta=4989.9,4995.9
Exp/Cntr=0.3,0.1

Type RM Length L Ch R = 1,27051,416,416,416
BEGIN DESCRIPTION:
BEAR Br 54.0
END DESCRIPTION:
XS GIS Cut Line= 3
      2075074.97     13473825.01      2074075.00     13474125.00
      2073725.00     13474525.00
#Sta/Elev= 30
  4024.7  494.19  4101.1  492.10  4139.5  490.75  4233.5  489.87  4283.1  488.01
  4337.9  487.91  4369.2  485.99  4557.1  482.11  4713.7  477.16  4765.9  476.69
  4786.8  475.38  4870.3  474.46  4884.5  473.19  4974.7  471.72  4980.8  470.33
  4992.6  464.87  4993.1  464.07  4998.1  464.07  4998.6  464.87  5006.1  467.66
  5019.1  469.22  5037.4  469.74  5046.9  465.55  5052.2  465.34  5058.3  469.21
  5137.5  472.80  5444.1  483.27  5486.8  483.09  5564.6  486.04  5600.2  485.87
#Mann=6,-1,0
  4024.7     0.1       0  4101.1    0.05       0  4884.5     0.1       0
  4992.6    0.07       0  4998.6     0.1       0  5137.5    0.05       0
Bank Sta=4992.6,4998.6
Exp/Cntr=0.3,0.1

Type RM Length L Ch R = 1,26635,537,537,537
BEGIN DESCRIPTION:
BEAR Br 53.0
END DESCRIPTION:
XS GIS Cut Line= 3
      2074775.00     13473875.00      2073975.00     13473875.00
      2073624.99     13474325.01
#Sta/Elev= 30
  4225.8  487.24  4305.8  485.43  4315.8  484.50  4335.8  484.61  4385.8  483.06
  4575.8  479.88  4655.8  477.19  4695.8  477.15  4735.8  475.22  4795.8  474.31
  4855.8  471.80  4891.5  471.84  4935.8  470.19  4955.8  470.46  4965.8  469.69
  4992.8  463.04  4993.3  462.24  4998.3  462.24  4998.8  463.04  5005.8  466.46
  5015.8  468.33  5039.4  469.63  5089.1  469.93  5167.9  471.56  5294.9  476.09
  5360.6  478.56  5395.9  478.93  5431.2  481.03  5481.9  482.82  5595.9  484.89
#Mann=5,-1,0
  4225.8    0.05       0  4891.5     0.1       0  4992.8    0.07       0
  4998.8     0.1       0  5294.9    0.05       0
Bank Sta=4992.8,4998.8
Exp/Cntr=0.3,0.1

Type RM Length L Ch R = 1,26098,190,190,190
BEGIN DESCRIPTION:
Mapping XS 4d42cb4c
END DESCRIPTION:
XS GIS Cut Line= 4
      2073941.50     13473393.99      2073757.49     13473426.97
      2073464.95     13473650.93      2073453.67     13473834.13
#Sta/Elev= 30
  4666.1  470.86  4816.8  469.22  4835.2  469.33  4891.7  467.50  4939.2  467.05
  4953.7  466.67  4968.2  466.59  4974.5  467.03  4989.0  466.86  4995.3  464.29
  5000.5  461.10  5001.0  460.30  5006.0  460.30  5006.5  461.10  5009.8  461.47
  5018.1  463.99  5024.4  466.91  5032.5  467.48  5038.9  468.46  5059.7  469.16
  5082.4  469.42  5137.5  470.86  5217.5  472.82  5220.7  473.71  5235.6  473.37
  5265.6  474.26  5285.6  474.53  5301.4  475.27  5375.8  477.44  5405.0  477.58
#Mann=5,-1,0
  4666.1    0.05       0  4891.7     0.1       0  5000.5    0.07       0
  5006.5     0.1       0  5137.5    0.05       0
Bank Sta=5000.5,5006.5
Exp/Cntr=0.3,0.1

Type RM Length L Ch R = 1,25908,167,167,167
BEGIN DESCRIPTION:
Mapping XS 233b32df
END DESCRIPTION:
XS GIS Cut Line= 4
      2073838.25     13473305.45      2073680.23     13473265.52
      2073400.72     13473465.17      2073358.19     13473717.73
#Sta/Elev= 30
  4673.9  470.95  4836.9  469.47  4861.8  467.78  4877.2  467.33  4918.3  466.79
  4933.1  465.78  4941.6  464.01  4947.8  464.47  4953.9  462.96  4962.6  463.45
  4968.7  462.48  4977.3  462.70  4983.4  465.11  4990.8  461.53  4995.2  461.26
  4995.7  460.46  5000.7  460.46  5001.2  461.26  5012.9  466.61  5031.8  467.64
  5124.2  468.71  5158.4  469.49  5182.6  469.87  5200.5  470.75  5240.5  471.06
  5261.3  472.29  5291.8  472.46  5342.5  474.10  5366.6  474.15  5436.5  476.30
#Mann=7,-1,0
  4673.9    0.05       0  4877.2     0.1       0  4995.2    0.07       0
  5001.2     0.1       0  5031.8    0.07       0  5124.2     0.1       0
  5158.4    0.05       0
Bank Sta=4995.2,5001.2
Exp/Cntr=0.3,0.1

Type RM Length L Ch R = 1,25741,371,371,371
BEGIN DESCRIPTION:
Mapping XS f86193e1
END DESCRIPTION:
XS GIS Cut Line= 4
      2074178.02     13473195.07      2073948.90     13473092.22
      2073288.74     13473254.98      2073136.74     13473827.99
#Sta/Elev= 30
  4279.0  473.25  4426.3  470.87  4554.8  469.29  4604.9  469.82  4732.4  470.85
  4810.2  470.65  4856.8  469.73  4910.9  466.89  4938.7  466.65  4956.4  466.74
  4976.1  465.37  4981.3  464.82  4987.3  462.49  4994.6  461.50  4995.1  460.70
  5000.1  460.70  5000.6  461.50  5007.9  462.44  5017.6  465.49  5040.7  466.14
  5238.2  467.83  5245.2  467.41  5313.5  469.31  5325.6  468.78  5406.7  471.44
  5516.2  473.42  5556.4  473.46  5590.8  474.59  5671.8  476.06  5802.9  476.75
#Mann=10,-1,0
  4279.0    0.05       0  4426.3     0.1       0  4604.9    0.05       0
  4910.9     0.1       0  4938.7    0.16       0  4994.6    0.07       0
  5000.6    0.16       0  5040.7     0.1       0  5238.2    0.05       0
  5590.8     0.1       0
Bank Sta=4994.6,5000.6
Exp/Cntr=0.3,0.1

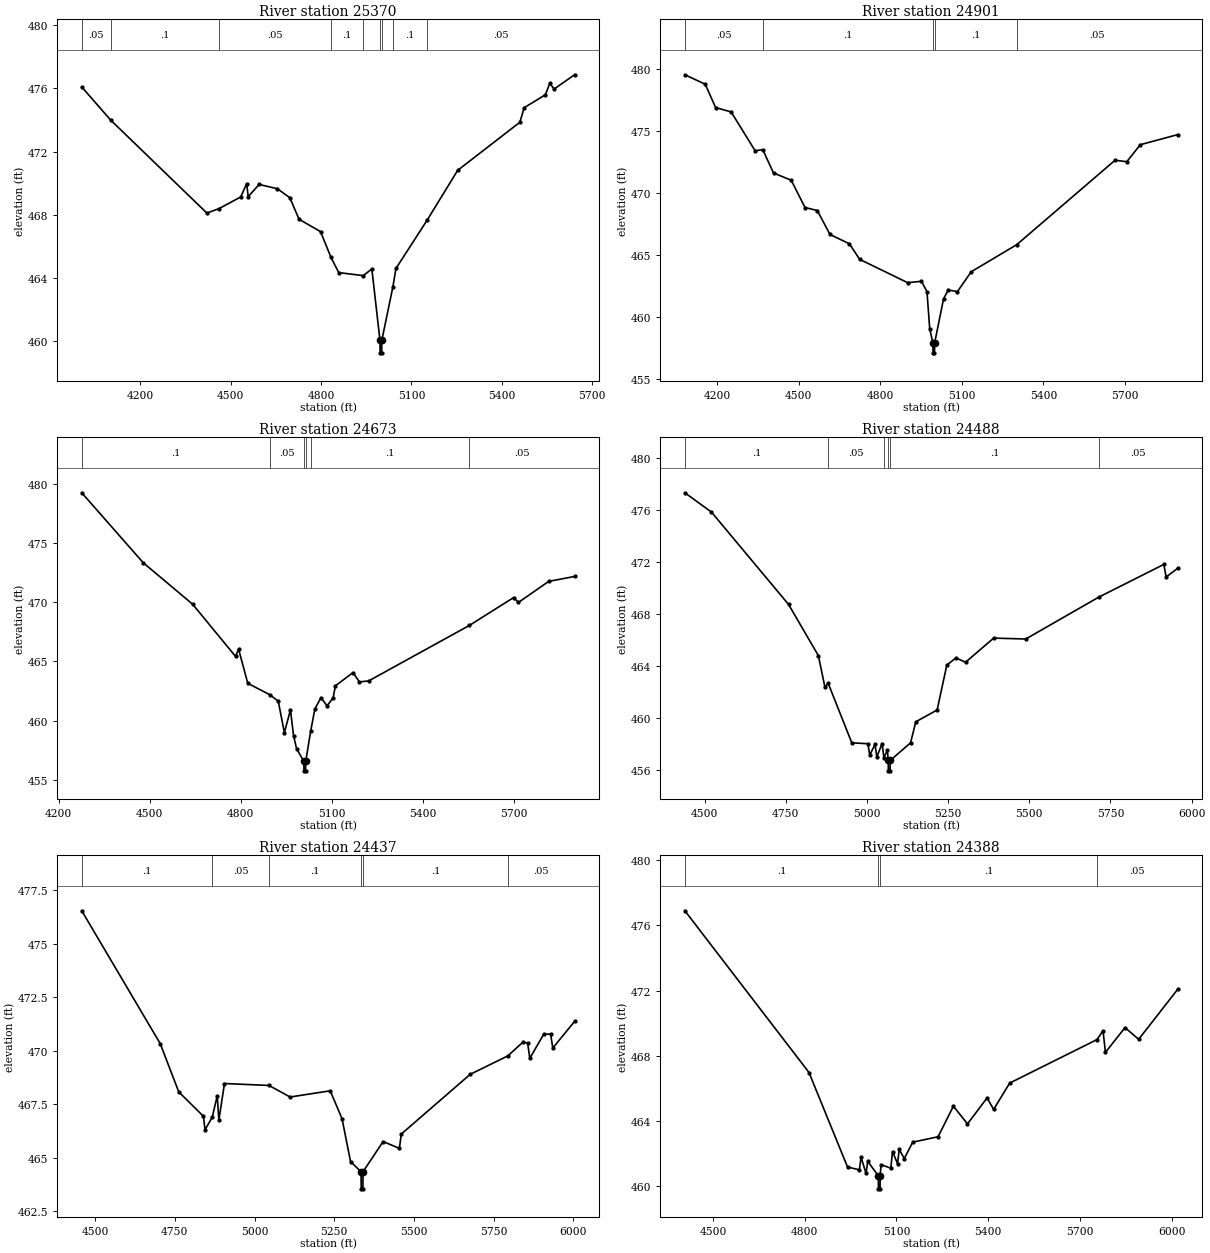
Type RM Length L Ch R = 1,25370,469,469,469
BEGIN DESCRIPTION:
Mapping XS e1c57ca5
END DESCRIPTION:
XS GIS Cut Line= 4
      2074282.60     13473088.46      2073489.26     13472929.58
      2073152.45     13472938.26      2072768.49     13473243.47
#Sta/Elev= 30
  4005.2  476.08  4101.6  473.98  4420.9  468.11  4461.9  468.40  4533.1  469.13
  4552.9  469.97  4558.0  469.15  4594.3  469.92  4654.9  469.65  4696.3  469.08
  4726.8  467.72  4798.2  466.94  4832.7  465.32  4858.6  464.35  4940.1  464.16
  4968.6  464.58  4995.5  460.08  4996.0  459.28  5001.3  459.28  5001.8  460.08
  5038.5  463.45  5048.6  464.61  5152.8  467.68  5253.5  470.81  5460.1  473.85
  5474.6  474.77  5545.0  475.59  5559.4  476.31  5573.9  475.95  5641.7  476.85
#Mann=9,-1,0
  4005.2    0.05       0  4101.6     0.1       0  4461.9    0.05       0
  4832.7     0.1       0  4940.1    0.16       0  4995.5    0.07       0
  5001.8    0.16       0  5038.5     0.1       0  5152.8    0.05       0
Bank Sta=4995.5,5001.8
Exp/Cntr=0.3,0.1

Type RM Length L Ch R = 1,24901,228,228,228
BEGIN DESCRIPTION:
Mapping XS 323e0910
END DESCRIPTION:
XS GIS Cut Line= 4
      2074308.57     13472671.78      2073519.64     13472519.86
      2073220.16     13472465.17      2072673.16     13472906.19
#Sta/Elev= 30
  4082.5  479.52  4157.4  478.76  4195.4  476.88  4252.4  476.53  4340.7  473.40
  4368.7  473.49  4408.1  471.61  4473.1  471.03  4524.0  468.83  4568.9  468.59
  4615.7  466.66  4687.0  465.91  4724.6  464.66  4900.8  462.78  4951.6  462.89
  4972.0  462.06  4982.1  459.04  4993.8  457.93  4994.3  457.13  4999.6  457.13
  5000.1  457.93  5033.0  461.49  5050.2  462.19  5083.8  462.06  5134.6  463.66
  5301.8  465.84  5663.0  472.64  5706.1  472.52  5755.7  473.89  5893.0  474.70
#Mann=5,-1,0
  4082.5    0.05       0  4368.7     0.1       0  4993.8    0.07       0
  5000.1     0.1       0  5301.8    0.05       0
Bank Sta=4993.8,5000.1
Exp/Cntr=0.3,0.1

Type RM Length L Ch R = 1,24673,185,185,185
BEGIN DESCRIPTION:
Mapping XS 727ebb0d
END DESCRIPTION:
XS GIS Cut Line= 4
      2074147.17     13472338.45      2073597.77     13472262.04
      2073273.11     13472294.16      2072641.92     13472687.42
#Sta/Elev= 30
  4275.9  479.27  4478.7  473.35  4641.6  469.84  4782.9  465.43  4793.0  466.04
  4823.3  463.15  4895.1  462.20  4923.8  461.64  4943.9  458.98  4964.0  460.91
  4974.1  458.73  4984.1  457.63  5008.0  456.55  5008.5  455.75  5013.8  455.75
  5014.3  456.55  5030.5  459.09  5044.4  460.98  5064.5  461.94  5084.6  461.25
  5104.7  461.92  5112.1  462.94  5170.1  464.06  5191.3  463.27  5222.0  463.36
  5553.9  468.05  5699.9  470.41  5715.3  469.99  5815.6  471.78  5900.5  472.19
#Mann=6,-1,0
  4275.9     0.1       0  4895.1    0.05       0  5008.0   0.033       0
  5014.3    0.05       0  5030.5     0.1       0  5553.9    0.05       0
Bank Sta=5008,5014.3
Exp/Cntr=0.3,0.1

Type RM Length L Ch R = 1,24488,51,51,51
BEGIN DESCRIPTION:
Mapping XS f493a30e
END DESCRIPTION:
XS GIS Cut Line= 5
      2073938.86     13471984.28      2073416.34     13472084.09
      2073313.05     13472139.65      2073182.84     13472209.96
      2072589.95     13472619.64
#Sta/Elev= 30
  4439.1  477.34  4521.1  475.85  4758.6  468.73  4850.3  464.79  4870.6  462.34
  4880.3  462.67  4953.2  458.07  5002.8  458.00  5008.5  457.12  5024.7  457.95
  5030.4  456.99  5046.6  458.01  5052.1  456.93  5062.9  457.49  5065.4  456.71
  5065.9  455.91  5071.2  455.91  5071.7  456.71  5134.2  458.07  5150.4  459.69
  5216.1  460.60  5245.9  464.06  5273.9  464.61  5303.7  464.28  5390.2  466.14
  5489.0  466.07  5713.5  469.29  5914.4  471.82  5921.5  470.85  5957.0  471.52
#Mann=6,-1,0
  4439.1     0.1       0  4880.3    0.05       0  5052.1     0.1       0
  5065.4   0.033       0  5071.7     0.1       0  5713.5    0.05       0
Bank Sta=5065.4,5071.7
Exp/Cntr=0.3,0.1

Type RM Length L Ch R = 1,24437,49,49,49
BEGIN DESCRIPTION:
Mapping XS efc03c3b
END DESCRIPTION:
XS GIS Cut Line= 5
      2073891.90     13471916.59      2073445.86     13472016.38
      2073248.81     13472107.53      2073129.02     13472173.50
      2072518.43     13472582.24
#Sta/Elev= 30
  4457.9  476.54  4704.2  470.33  4762.1  468.08  4839.5  466.94  4844.6  466.31
  4867.1  466.89  4882.9  467.90  4888.0  466.76  4905.6  468.47  5045.3  468.38
  5111.4  467.84  5237.2  468.13  5274.3  466.83  5301.1  464.82  5334.0  464.35
  5334.5  463.55  5339.8  463.55  5340.3  464.35  5403.2  465.76  5454.2  465.44
  5460.2  466.11  5676.4  468.90  5794.3  469.76  5841.5  470.40  5856.5  470.36
  5863.3  469.65  5907.6  470.79  5928.6  470.77  5935.5  470.13  6003.6  471.37
#Mann=6,-1,0
  4457.9     0.1       0  4867.1    0.05       0  5045.3     0.1       0
  5334.0   0.033       0  5340.3     0.1       0  5794.3    0.05       0
Bank Sta=5334,5340.3
Exp/Cntr=0.3,0.1

Type RM Length L Ch R = 1,24388,409,409,409
BEGIN DESCRIPTION:
Mapping XS 97195d87
END DESCRIPTION:
XS GIS Cut Line= 5
      2073918.01     13471859.28      2073398.98     13471979.06
      2073265.30     13472053.71      2073113.39     13472132.70
      2072465.51     13472520.35
#Sta/Elev= 30
  4408.1  476.90  4814.1  466.96  4940.2  461.15  4978.8  460.98  4984.6  461.75
  5000.6  460.76  5006.3  461.50  5040.8  460.61  5041.3  459.81  5046.6  459.81
  5047.1  460.61  5049.7  461.30  5081.7  461.08  5087.4  462.10  5103.7  461.36
  5109.3  462.23  5125.8  461.67  5153.5  462.68  5236.3  463.01  5286.5  464.89
  5332.5  463.80  5396.7  465.40  5418.1  464.69  5470.6  466.31  5755.8  468.98
  5776.0  469.52  5783.8  468.20  5847.9  469.72  5892.5  469.00  6020.1  472.07
#Mann=4,-1,0
  4408.1     0.1       0  5040.8    0.07       0  5047.1     0.1       0
  5755.8    0.05       0
Bank Sta=5040.8,5047.1
Exp/Cntr=0.3,0.1

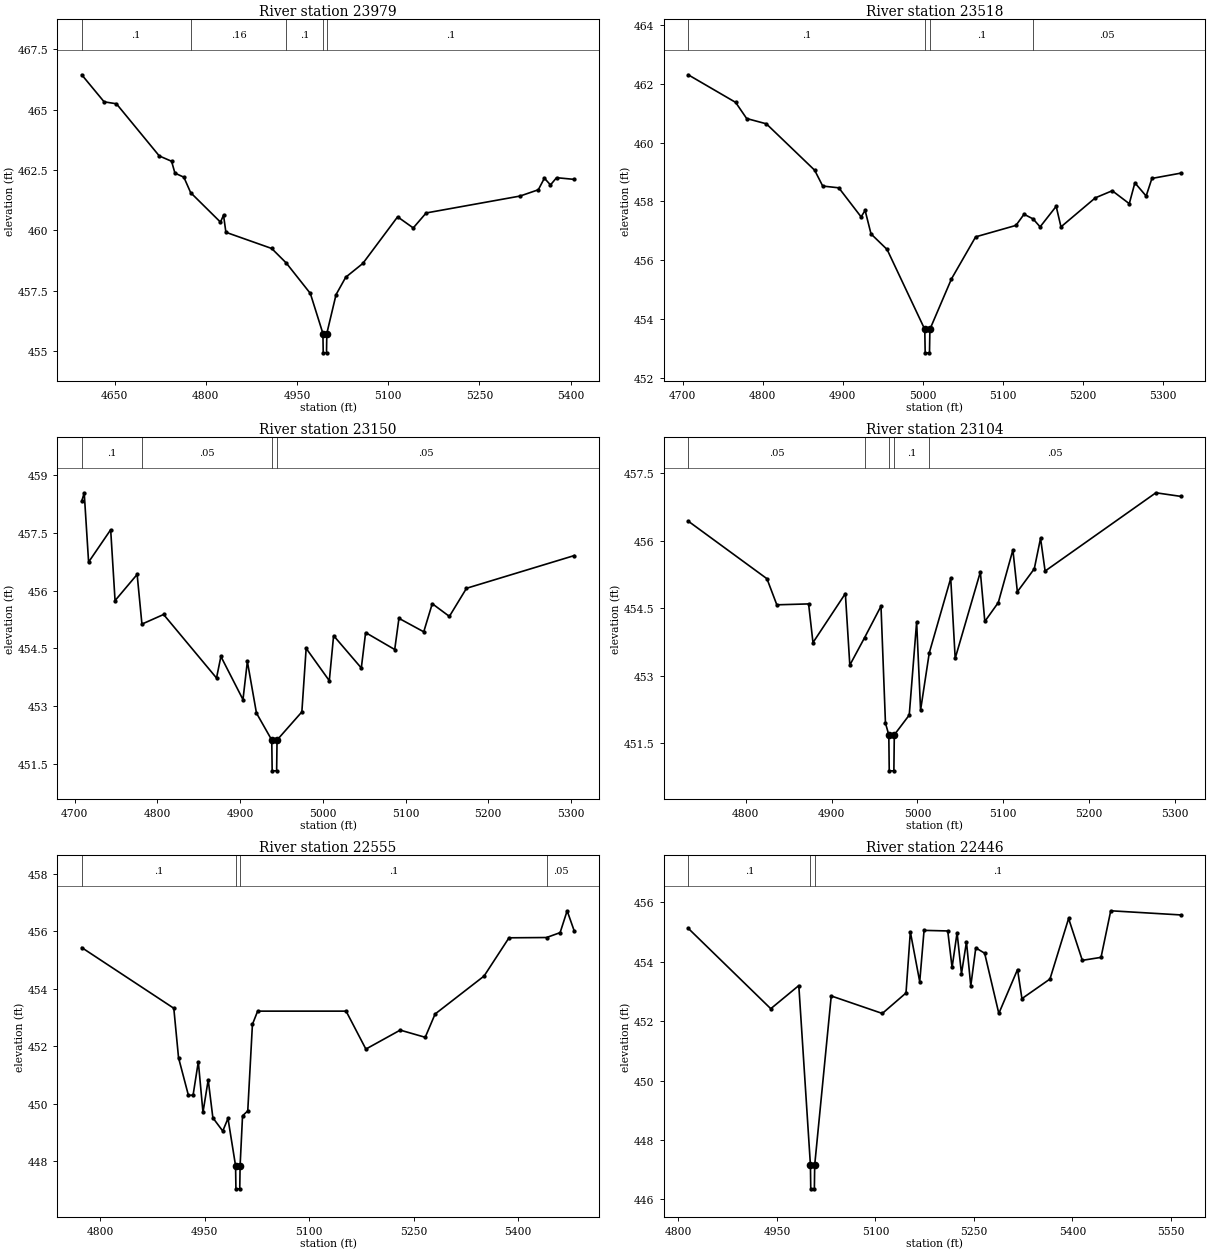
Type RM Length L Ch R = 1,23979,461,461,461
BEGIN DESCRIPTION:
Mapping XS f9f33792
END DESCRIPTION:
XS GIS Cut Line= 4
      2073521.51     13471659.39      2073282.75     13471629.00
      2072898.64     13471761.38      2072894.30     13471924.16
#Sta/Elev= 30
  4596.1  466.44  4632.9  465.32  4653.1  465.24  4723.6  463.08  4743.8  462.86
  4749.3  462.37  4764.0  462.20  4775.2  461.56  4824.2  460.34  4829.2  460.63
  4833.1  459.92  4908.4  459.25  4932.3  458.65  4971.9  457.39  4992.6  455.73
  4993.1  454.93  4998.5  454.93  4999.0  455.73  5014.2  457.34  5030.1  458.06
  5058.2  458.63  5115.4  460.56  5141.1  460.10  5162.3  460.72  5316.7  461.42
  5346.7  461.68  5356.7  462.16  5366.7  461.88  5376.7  462.18  5405.9  462.11
#Mann=5,-1,0
  4596.1     0.1       0  4775.2    0.16       0  4932.3     0.1       0
  4992.6    0.07       0  4999.0     0.1       0
Bank Sta=4992.6,4999
Exp/Cntr=0.3,0.1

Type RM Length L Ch R = 1,23518,368,368,368
BEGIN DESCRIPTION:
Mapping XS 845c8f9e
END DESCRIPTION:
XS GIS Cut Line= 4
      2073425.98     13471253.57      2073358.71     13471223.19
      2072968.08     13471268.76      2072861.78     13471372.90
#Sta/Elev= 30
  4706.8  462.31  4766.1  461.37  4779.9  460.82  4804.5  460.64  4864.9  459.06
  4875.0  458.52  4895.1  458.46  4923.0  457.47  4928.0  457.69  4935.4  456.89
  4955.5  456.36  5002.6  453.64  5003.1  452.84  5008.5  452.84  5009.0  453.64
  5036.0  455.36  5066.2  456.79  5116.6  457.18  5126.7  457.56  5138.1  457.40
  5146.8  457.13  5166.9  457.83  5172.9  457.13  5215.9  458.12  5237.0  458.36
  5258.3  457.92  5265.3  458.63  5279.4  458.18  5286.6  458.78  5322.7  458.96
#Mann=4,-1,0
  4706.8     0.1       0  5002.6    0.07       0  5009.0     0.1       0
  5138.1    0.05       0
Bank Sta=5002.6,5009
Exp/Cntr=0.3,0.1

Type RM Length L Ch R = 1,23150,46,46,46
BEGIN DESCRIPTION:
Mapping XS 757d6db1
END DESCRIPTION:
XS GIS Cut Line= 4
      2073141.69     13470639.44      2073076.46     13470840.91
      2073041.73     13470957.57      2072974.91     13471211.13
#Sta/Elev= 30
  4708.4  458.32  4711.4  458.54  4716.7  456.74  4743.4  457.58  4748.7  455.74
  4775.4  456.42  4781.2  455.13  4807.4  455.38  4871.4  453.73  4876.7  454.29
  4903.4  453.17  4908.7  454.16  4919.7  452.82  4938.2  452.12  4938.7  451.32
  4944.1  451.32  4944.6  452.12  4974.6  452.85  4979.8  454.50  5007.8  453.66
  5013.0  454.83  5046.5  453.99  5051.7  454.91  5086.9  454.47  5092.0  455.28
  5122.0  454.93  5132.3  455.66  5153.0  455.33  5173.7  456.06  5304.1  456.91
#Mann=4,-1,0
  4708.4     0.1       0  4781.2    0.05       0  4938.2    0.04       0
  4944.6    0.05       0
Bank Sta=4938.2,4944.6
Exp/Cntr=0.3,0.1

Type RM Length L Ch R = 1,23104,549,549,549
BEGIN DESCRIPTION:
Mapping XS 03238923
END DESCRIPTION:
XS GIS Cut Line= 5
      2073080.92     13470624.27      2073042.43     13470795.77
      2073019.51     13470888.82      2072997.98     13470967.29
      2072931.21     13471177.57
#Sta/Elev= 30
  4733.0  456.44  4824.7  455.16  4836.2  454.58  4873.2  454.60  4878.3  453.74
  4916.0  454.83  4921.2  453.24  4938.4  453.85  4957.5  454.55  4962.7  451.95
  4966.6  451.69  4967.1  450.89  4972.5  450.89  4973.0  451.69  4990.4  452.13
  4999.0  454.20  5003.6  452.24  5013.7  453.51  5038.7  455.17  5043.9  453.39
  5073.2  455.31  5078.4  454.21  5094.1  454.63  5111.1  455.80  5116.3  454.87
  5136.0  455.38  5143.3  456.06  5148.6  455.33  5277.6  457.07  5306.6  456.99
#Mann=5,-1,0
  4733.0    0.05       0  4938.4     0.1       0  4966.6    0.07       0
  4973.0     0.1       0  5013.7    0.05       0
Bank Sta=4966.6,4973
Exp/Cntr=0.3,0.1

Type RM Length L Ch R = 1,22555,109,109,109
BEGIN DESCRIPTION:
Mapping XS 7d13f706
END DESCRIPTION:
XS GIS Cut Line= 4
      2072959.37     13470318.24      2072909.49     13470313.90
      2072505.85     13470760.95      2072514.52     13470815.18
#Sta/Elev= 30
  4773.4  455.43  4905.6  453.32  4912.4  451.60  4926.6  450.29  4933.3  450.30
  4940.8  451.46  4947.5  449.70  4955.0  450.83  4961.7  449.51  4975.9  449.05
  4983.4  449.49  4994.3  447.84  4994.8  447.04  5000.3  447.04  5000.8  447.84
  5004.3  449.58  5011.8  449.75  5018.5  452.76  5026.0  453.22  5153.0  453.22
  5181.4  451.90  5230.7  452.56  5266.6  452.31  5280.8  453.12  5351.1  454.44
  5386.9  455.77  5440.8  455.78  5460.3  455.95  5470.4  456.71  5480.7  456.00
#Mann=4,-1,0
  4773.4     0.1       0  4994.3    0.07       0  5000.8     0.1       0
  5440.8    0.05       0
Bank Sta=4994.3,5000.8
Exp/Cntr=0.3,0.1

Type RM Length L Ch R = 1,22446,37,37,37
BEGIN DESCRIPTION:
Mapping XS 9a536ea3
END DESCRIPTION:
XS GIS Cut Line= 4
      2072931.20     13470292.20      2072818.35     13470290.03
      2072471.12     13470687.16      2072436.98     13470791.73
#Sta/Elev= 30
  4814.8  455.13  4940.6  452.42  4983.3  453.20  5001.0  447.15  5001.5  446.35
  5007.0  446.35  5007.5  447.15  5032.7  452.85  5110.5  452.26  5146.6  452.95
  5153.2  455.01  5167.5  453.33  5174.1  455.06  5210.2  455.04  5216.8  453.81
  5224.4  454.98  5231.1  453.60  5238.7  454.67  5245.3  453.19  5252.9  454.47
  5266.4  454.29  5288.0  452.26  5316.5  453.74  5323.2  452.76  5365.9  453.42
  5394.3  455.46  5415.2  454.05  5443.7  454.15  5458.5  455.72  5565.2  455.58
#Mann=3,-1,0
  4814.8     0.1       0  5001.0    0.07       0  5007.5     0.1       0
Bank Sta=5001,5007.5
Exp/Cntr=0.3,0.1