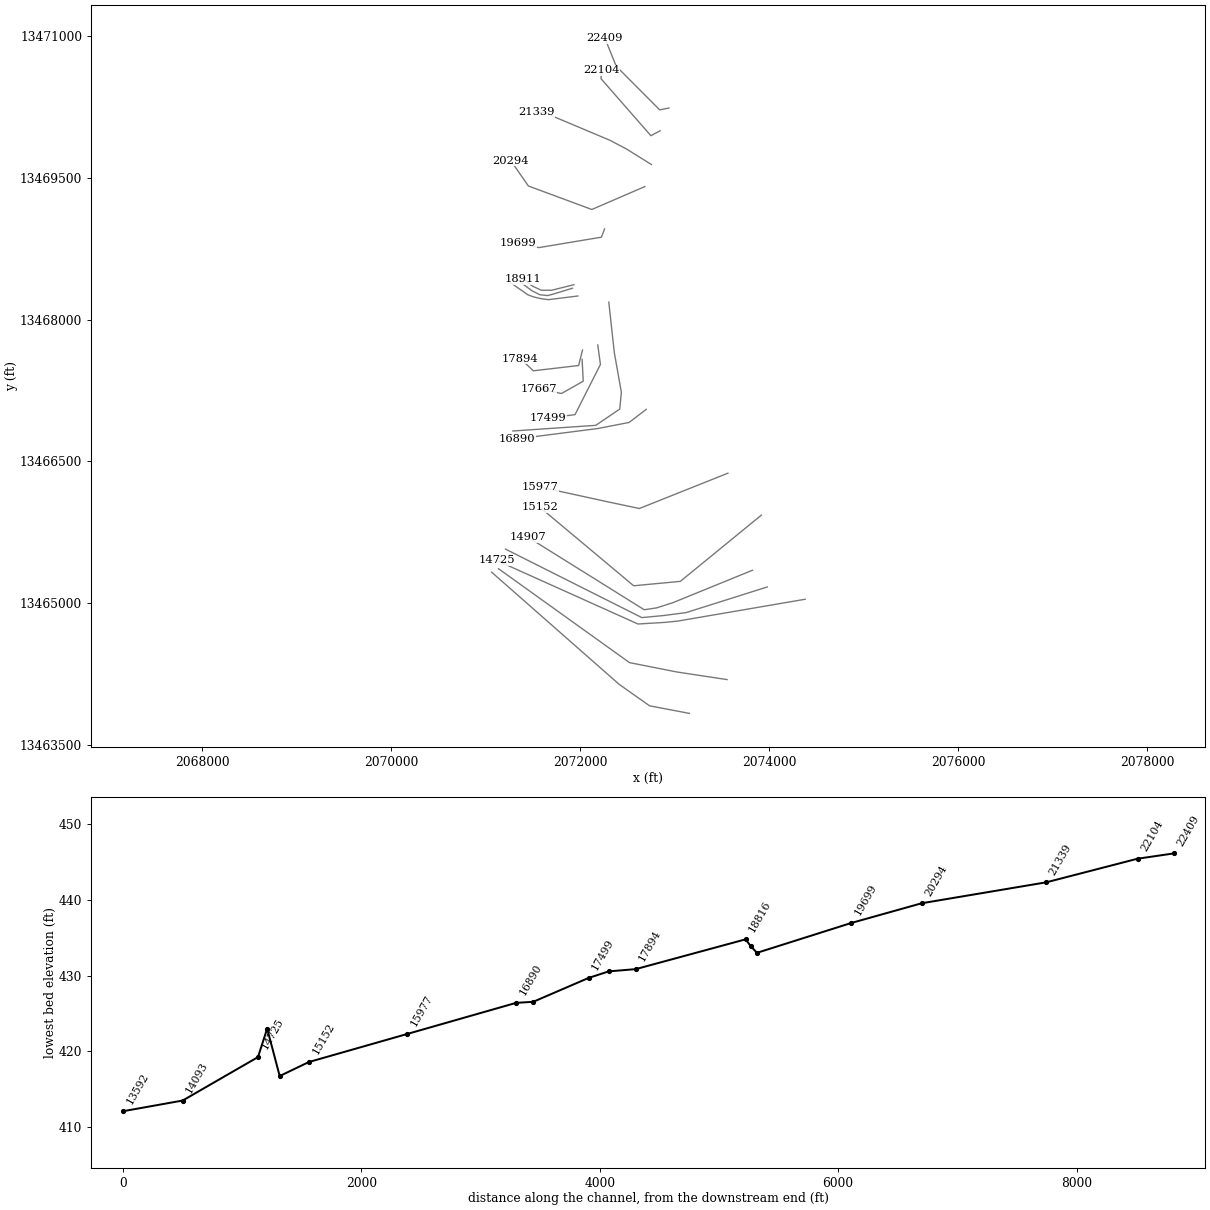
HEC-RAS study BEAR Br.prj: BEAR Br Base Level Engineering

--- BEAR Br.g01 (geometry) --- (continued)

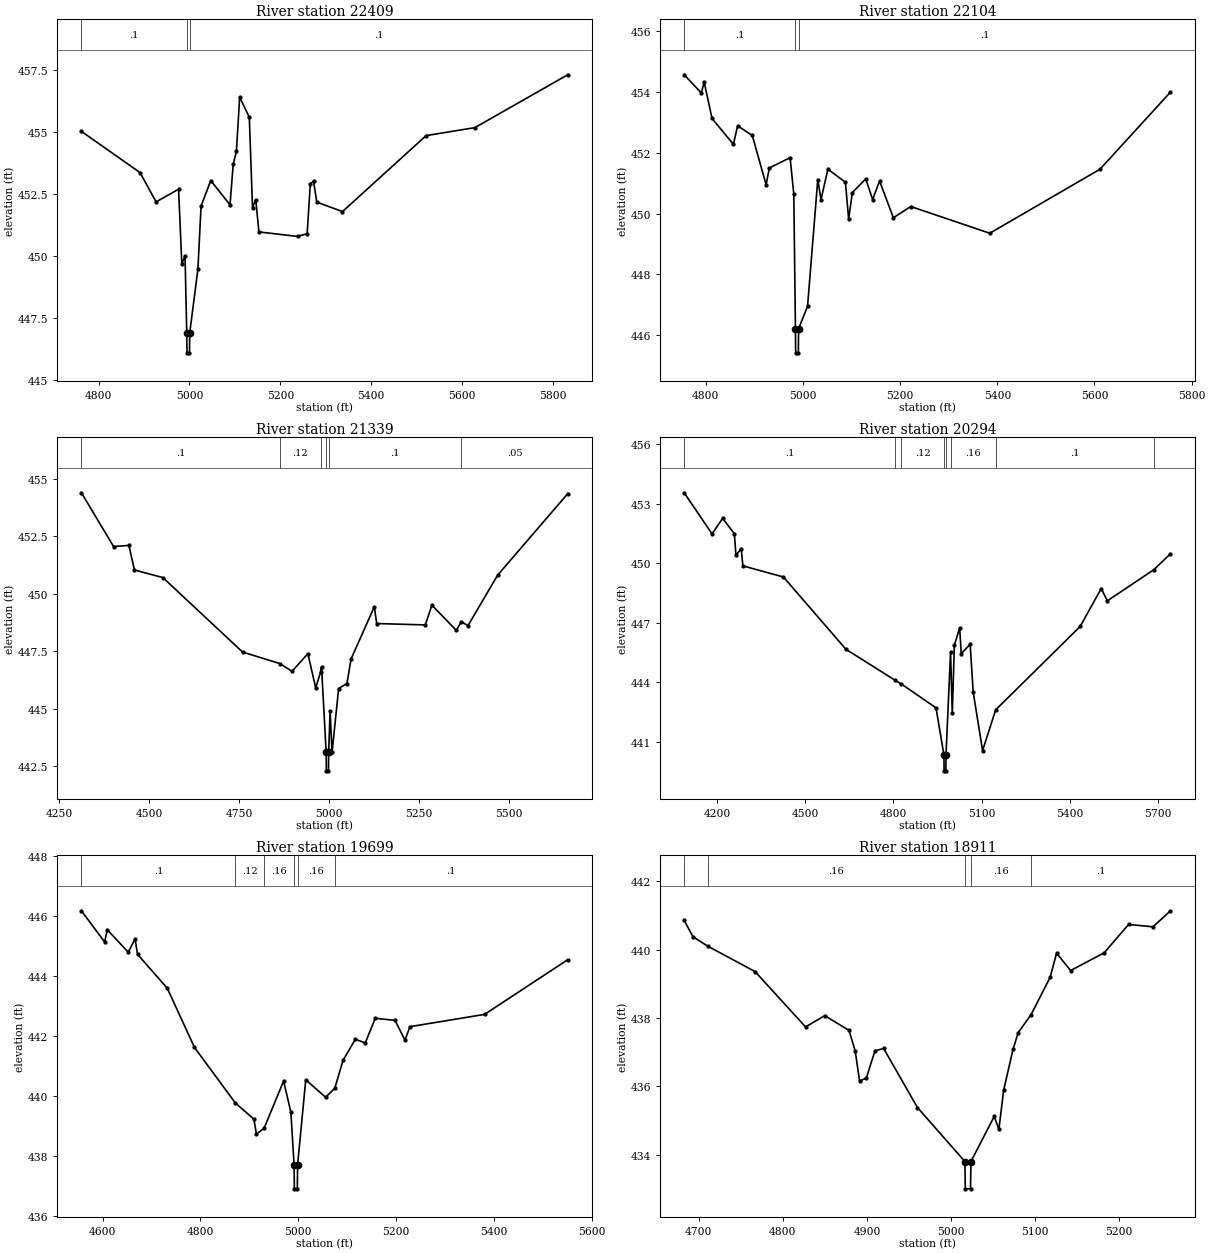
Type RM Length L Ch R = 1,22409,305,305,305
BEGIN DESCRIPTION:
Mapping XS f94e584d
END DESCRIPTION:
XS GIS Cut Line= 4
      2072939.83     13470240.11      2072842.22     13470220.58
      2072382.15     13470682.82      2072262.78     13470977.98
#Sta/Elev= 30
  4762.3  455.03  4891.3  453.37  4926.6  452.19  4976.1  452.70  4983.2  449.69
  4990.3  450.02  4994.1  446.91  4994.6  446.11  5000.1  446.11  5000.6  446.91
  5018.6  449.47  5025.6  452.02  5046.9  453.05  5089.3  452.07  5096.3  453.70
  5103.4  454.23  5110.5  456.41  5131.7  455.60  5138.8  451.96  5145.9  452.28
  5152.9  450.98  5237.8  450.80  5259.0  450.91  5266.0  452.91  5273.1  453.03
  5280.2  452.18  5336.8  451.80  5520.8  454.86  5628.0  455.18  5832.4  457.31
#Mann=3,-1,0
  4762.3     0.1       0  4994.1    0.07       0  5000.6     0.1       0
Bank Sta=4994.1,5000.6
Exp/Cntr=0.3,0.1

Type RM Length L Ch R = 1,22104,765,765,765
BEGIN DESCRIPTION:
Mapping XS 3f834386
END DESCRIPTION:
XS GIS Cut Line= 4
      2072846.52     13469999.21      2072748.90     13469947.15
      2072221.56     13470550.45      2072223.73     13470639.40
#Sta/Elev= 30
  4755.5  454.57  4790.9  453.97  4796.6  454.33  4812.9  453.13  4856.8  452.28
  4865.5  452.89  4895.7  452.57  4924.1  450.95  4930.8  451.50  4973.5  451.84
  4981.1  450.64  4984.5  446.21  4985.0  445.41  4990.5  445.41  4991.0  446.21
  5009.4  446.94  5030.5  451.12  5037.1  450.46  5051.3  451.46  5087.4  451.03
  5094.0  449.81  5101.6  450.69  5129.2  451.14  5143.4  450.46  5157.6  451.07
  5186.1  449.86  5221.9  450.23  5384.5  449.35  5611.4  451.46  5756.4  454.00
#Mann=3,-1,0
  4755.5     0.1       0  4984.5    0.07       0  4991.0     0.1       0
Bank Sta=4984.5,4991
Exp/Cntr=0.3,0.1

Type RM Length L Ch R = 1,21339,1045,1045,1045
BEGIN DESCRIPTION:
Mapping XS b2fef106
END DESCRIPTION:
XS GIS Cut Line= 5
      2072754.54     13469641.86      2072493.47     13469804.78
      2072314.82     13469899.01      2071615.96     13470193.47
      2071533.54     13470193.47
#Sta/Elev= 30
  4312.3  454.40  4401.7  452.06  4444.2  452.11  4459.5  451.04  4538.5  450.71
  4759.7  447.47  4863.1  446.97  4897.1  446.63  4941.2  447.40  4962.9  445.91
  4976.6  446.61  4979.1  446.82  4992.0  443.10  4992.5  442.30  4998.4  442.30
  4998.9  443.10  5002.9  444.89  5008.3  443.10  5026.6  445.88  5049.7  446.10
  5061.2  447.17  5125.7  449.44  5132.3  448.71  5267.3  448.65  5285.6  449.51
  5353.5  448.41  5367.1  448.79  5385.9  448.62  5467.9  450.81  5662.8  454.36
#Mann=6,-1,0
  4312.3     0.1       0  4863.1    0.12       0  4976.6     0.1       0
  4992.0    0.07       0  4998.9     0.1       0  5367.1    0.05       0
Bank Sta=4992,4998.9
Exp/Cntr=0.3,0.1

Type RM Length L Ch R = 1,20294,595,595,595
BEGIN DESCRIPTION:
Mapping XS aa4b103a
END DESCRIPTION:
XS GIS Cut Line= 4
      2072685.07     13469408.44      2072123.90     13469165.90
      2071452.49     13469414.92      2071265.88     13469683.99
#Sta/Elev= 30
  4087.9  453.54  4182.7  451.47  4218.7  452.25  4258.6  451.48  4264.1  450.39
  4282.1  450.73  4287.6  449.86  4425.7  449.30  4638.3  445.66  4806.8  444.09
  4827.3  443.91  4944.9  442.71  4971.9  440.34  4972.4  439.54  4978.4  439.54
  4978.9  440.34  4994.4  445.50  5000.3  442.44  5007.4  445.87  5025.4  446.74
  5030.7  445.44  5061.1  445.91  5071.4  443.51  5103.4  440.56  5147.9  442.61
  5435.5  446.81  5507.1  448.72  5528.0  448.10  5686.5  449.67  5742.8  450.47
#Mann=8,-1,0
  4087.9     0.1       0  4806.8    0.16       0  4827.3    0.12       0
  4971.9    0.07       0  4978.9    0.12       0  4994.4    0.16       0
  5147.9     0.1       0  5686.5    0.05       0
Bank Sta=4971.9,4978.9
Exp/Cntr=0.3,0.1

Type RM Length L Ch R = 1,19699,788,788,788
BEGIN DESCRIPTION:
Mapping XS 6dece85f
END DESCRIPTION:
XS GIS Cut Line= 4
      2072258.45     13468959.74      2072225.90     13468872.93
      2071564.00     13468762.25      2071339.13     13468811.98
#Sta/Elev= 30
  4556.8  446.18  4604.3  445.14  4609.6  445.55  4652.5  444.80  4666.5  445.24
  4671.5  444.73  4732.3  443.60  4787.9  441.63  4871.4  439.78  4909.4  439.24
  4914.5  438.75  4930.0  438.93  4970.1  440.51  4985.0  439.47  4991.5  437.72
  4992.1  436.92  4998.2  436.92  4998.7  437.72  5015.4  440.55  5056.0  439.97
  5074.8  440.27  5091.6  441.20  5116.8  441.90  5137.1  441.78  5157.4  442.60
  5197.9  442.53  5218.2  441.87  5228.3  442.32  5381.0  442.73  5550.9  444.55
#Mann=6,-1,0
  4556.8     0.1       0  4871.4    0.12       0  4930.0    0.16       0
  4991.5    0.07       0  4998.7    0.16       0  5074.8     0.1       0
Bank Sta=4991.5,4998.7
Exp/Cntr=0.3,0.1

Type RM Length L Ch R = 1,18911,54,54,54
BEGIN DESCRIPTION:
Mapping XS a893c445
END DESCRIPTION:
XS GIS Cut Line= 5
      2071935.10     13468369.46      2071698.55     13468310.86
      2071590.05     13468310.86      2071496.73     13468354.27
      2071399.66     13468429.77
#Sta/Elev= 30
  4682.8  440.86  4693.2  440.38  4711.1  440.10  4767.1  439.36  4827.1  437.74
  4849.9  438.07  4878.7  437.64  4886.1  437.04  4891.3  436.16  4899.3  436.24
  4909.6  437.04  4919.9  437.11  4960.1  435.38  5016.5  433.80  5017.0  433.00
  5023.2  433.00  5023.7  433.80  5051.4  435.12  5056.9  434.74  5062.6  435.89
  5073.7  437.08  5079.8  437.57  5095.2  438.10  5117.8  439.19  5125.5  439.90
  5142.2  439.39  5182.1  439.91  5211.1  440.74  5240.1  440.67  5260.9  441.14
#Mann=5,-1,0
  4682.8     0.1       0  4711.1    0.16       0  5016.5    0.07       0
  5023.7    0.16       0  5095.2     0.1       0
Bank Sta=5016.5,5023.7
Exp/Cntr=0.3,0.1

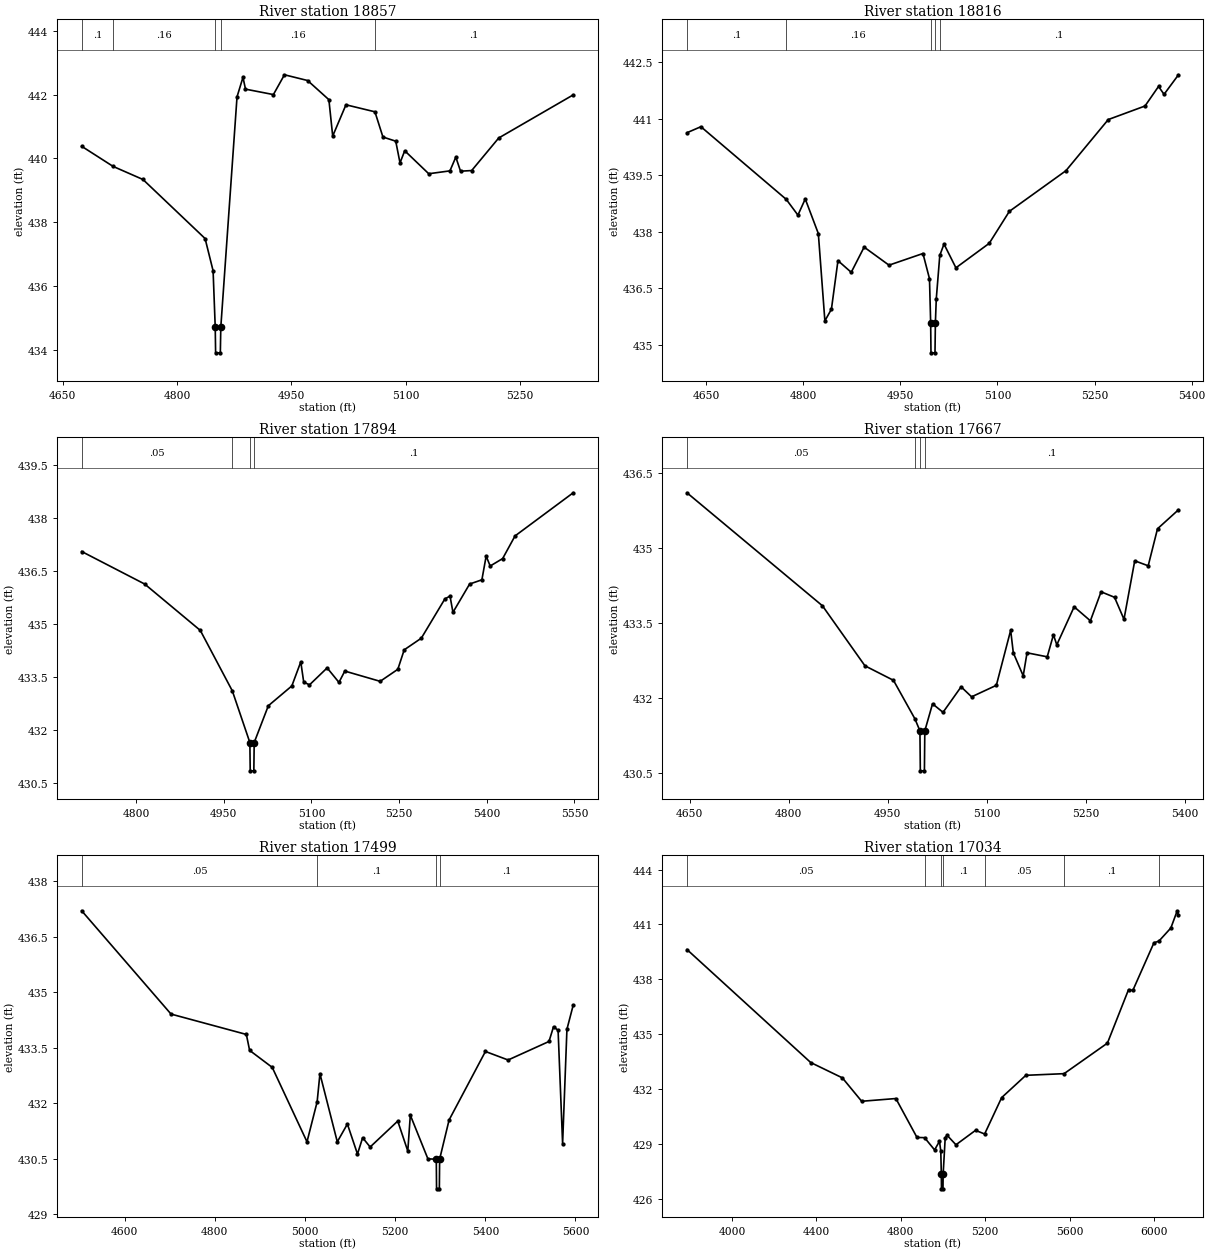
Type RM Length L Ch R = 1,18857,41,41,41
BEGIN DESCRIPTION:
Mapping XS fc3f1530
END DESCRIPTION:
XS GIS Cut Line= 6
      2071919.88     13468332.56      2071713.74     13468269.63
      2071657.32     13468254.44      2071574.86     13468263.12
      2071492.39     13468304.35      2071335.04     13468420.75
#Sta/Elev= 30
  4675.1  440.38  4716.3  439.75  4755.5  439.34  4837.0  437.49  4847.5  436.48
  4850.3  434.71  4850.8  433.91  4857.0  433.91  4857.6  434.71  4878.9  441.93
  4886.7  442.54  4890.0  442.17  4926.6  442.00  4941.1  442.62  4971.5  442.44
  4999.4  441.84  5004.4  440.70  5021.8  441.68  5059.8  441.46  5070.3  440.67
  5087.1  440.54  5092.7  439.86  5098.9  440.24  5130.4  439.52  5158.2  439.61
  5165.9  440.04  5172.1  439.60  5186.7  439.62  5222.2  440.64  5319.9  441.99
#Mann=5,-1,0
  4675.1     0.1       0  4716.3    0.16       0  4850.3    0.07       0
  4857.6    0.16       0  5059.8     0.1       0
Bank Sta=4850.3,4857.6
Exp/Cntr=0.3,0.1

Type RM Length L Ch R = 1,18816,922,922,922
BEGIN DESCRIPTION:
Mapping XS f2c40657
END DESCRIPTION:
XS GIS Cut Line= 6
      2071976.38     13468250.10      2071663.83     13468211.04
      2071585.71     13468221.89      2071503.24     13468241.42
      2071446.82     13468263.12      2071266.72     13468388.97
#Sta/Elev= 30
  4620.8  440.63  4642.3  440.79  4774.0  438.86  4792.1  438.44  4803.4  438.87
  4823.6  437.95  4833.7  435.63  4843.8  435.94  4853.9  437.23  4874.4  436.92
  4894.3  437.59  4932.7  437.11  4985.1  437.42  4995.2  436.75  4997.0  435.58
  4997.5  434.78  5003.7  434.78  5004.3  435.58  5005.7  436.22  5011.1  437.37
  5017.6  437.67  5036.0  437.04  5087.4  437.69  5118.5  438.54  5205.8  439.62
  5271.2  440.98  5327.9  441.34  5348.8  441.86  5357.3  441.65  5379.6  442.17
#Mann=5,-1,0
  4620.8     0.1       0  4774.0    0.16       0  4997.0    0.07       0
  5004.3    0.16       0  5011.1     0.1       0
Bank Sta=4997,5004.3
Exp/Cntr=0.3,0.1

Type RM Length L Ch R = 1,17894,227,227,227
BEGIN DESCRIPTION:
Mapping XS c1247869
END DESCRIPTION:
XS GIS Cut Line= 4
      2072025.51     13467677.74      2071984.27     13467513.87
      2071505.41     13467458.00      2071366.89     13467587.62
#Sta/Elev= 30
  4707.0  437.05  4814.8  436.13  4909.9  434.82  4964.7  433.11  4994.7  431.65
  4995.3  430.85  5001.5  430.85  5002.1  431.65  5026.3  432.69  5066.5  433.25
  5081.8  433.93  5086.8  433.36  5096.7  433.28  5126.9  433.76  5147.1  433.35
  5157.1  433.67  5217.6  433.38  5247.8  433.72  5258.7  434.27  5288.0  434.60
  5328.3  435.71  5337.1  435.79  5342.1  435.33  5370.6  436.13  5391.6  436.25
  5398.9  436.92  5405.8  436.64  5427.1  436.85  5448.3  437.49  5547.8  438.71
#Mann=4,-1,0
  4707.0    0.05       0  4964.7     0.1       0  4994.7    0.07       0
  5002.1     0.1       0
Bank Sta=4994.7,5002.1
Exp/Cntr=0.3,0.1

Type RM Length L Ch R = 1,17667,168,168,168
BEGIN DESCRIPTION:
Mapping XS be8d93ad
END DESCRIPTION:
XS GIS Cut Line= 4
      2072021.16     13467580.07      2072033.10     13467347.85
      2071803.06     13467217.64      2071559.98     13467266.48
#Sta/Elev= 30
  4645.7  436.11  4851.0  433.85  4915.4  432.65  4958.6  432.36  4991.1  431.59
  4998.7  431.35  4999.3  430.55  5005.5  430.55  5006.1  431.35  5017.8  431.89
  5033.7  431.72  5061.1  432.23  5077.0  432.03  5114.5  432.26  5136.2  433.36
  5140.2  432.91  5155.2  432.45  5161.0  432.91  5191.6  432.83  5201.0  433.27
  5206.1  433.07  5232.4  433.83  5257.0  433.55  5273.2  434.13  5293.6  434.02
  5307.9  433.58  5324.2  434.75  5344.6  434.65  5358.7  435.39  5390.5  435.77
#Mann=4,-1,0
  4645.7    0.05       0  4991.1     0.1       0  4998.7    0.07       0
  5006.1     0.1       0
Bank Sta=4998.7,5006.1
Exp/Cntr=0.3,0.1

Type RM Length L Ch R = 1,17499,465,465,465
BEGIN DESCRIPTION:
Mapping XS d432e299
END DESCRIPTION:
XS GIS Cut Line= 4
      2072186.84     13467731.39      2072215.05     13467525.27
      2071945.95     13466993.59      2071661.71     13466958.87
#Sta/Elev= 30
  4504.6  437.20  4702.8  434.41  4869.9  433.86  4877.1  433.43  4927.3  432.97
  5004.4  430.96  5026.9  432.04  5033.1  432.80  5071.6  430.96  5094.0  431.44
  5116.4  430.63  5127.8  431.07  5144.5  430.82  5205.7  431.52  5228.0  430.71
  5233.6  431.68  5272.6  430.50  5291.2  430.49  5291.8  429.69  5298.0  429.69
  5298.6  430.49  5319.6  431.55  5400.2  433.40  5450.5  433.17  5541.2  433.67
  5551.3  434.07  5561.4  433.97  5571.4  430.91  5581.0  434.00  5594.9  434.65
#Mann=4,-1,0
  4504.6    0.05       0  5026.9     0.1       0  5291.2    0.03       0
  5298.6     0.1       0
Bank Sta=5291.2,5298.6
Exp/Cntr=0.3,0.1

Type RM Length L Ch R = 1,17034,144,144,144
BEGIN DESCRIPTION:
Mapping XS 86b4adbc
END DESCRIPTION:
XS GIS Cut Line= 6
      2072303.54     13468185.13      2072361.90     13467651.38
      2072436.56     13467229.51      2072419.20     13467052.42
      2072165.72     13466880.55      2071288.99     13466820.65
#Sta/Elev= 30
  3786.6  439.63  4372.9  433.45  4523.0  432.61  4614.4  431.33  4776.5  431.48
  4876.6  429.35  4912.4  429.34  4959.9  428.67  4983.2  429.14  4989.3  428.61
  4991.9  427.34  4992.6  426.54  4999.7  426.54  5000.5  427.34  5010.3  429.34
  5019.2  429.47  5061.2  428.95  5154.0  429.74  5197.1  429.54  5277.7  431.53
  5392.4  432.75  5573.6  432.84  5778.9  434.51  5879.1  437.44  5899.2  437.39
  5999.4  440.00  6022.9  440.09  6079.6  440.81  6109.7  441.75  6115.7  441.50
#Mann=7,-1,0
  3786.6    0.05       0  4912.4     0.1       0  4991.9    0.07       0
  5000.5     0.1       0  5197.1    0.05       0  5573.6     0.1       0
  6022.9    0.05       0
Bank Sta=4991.9,5000.5
Exp/Cntr=0.3,0.1

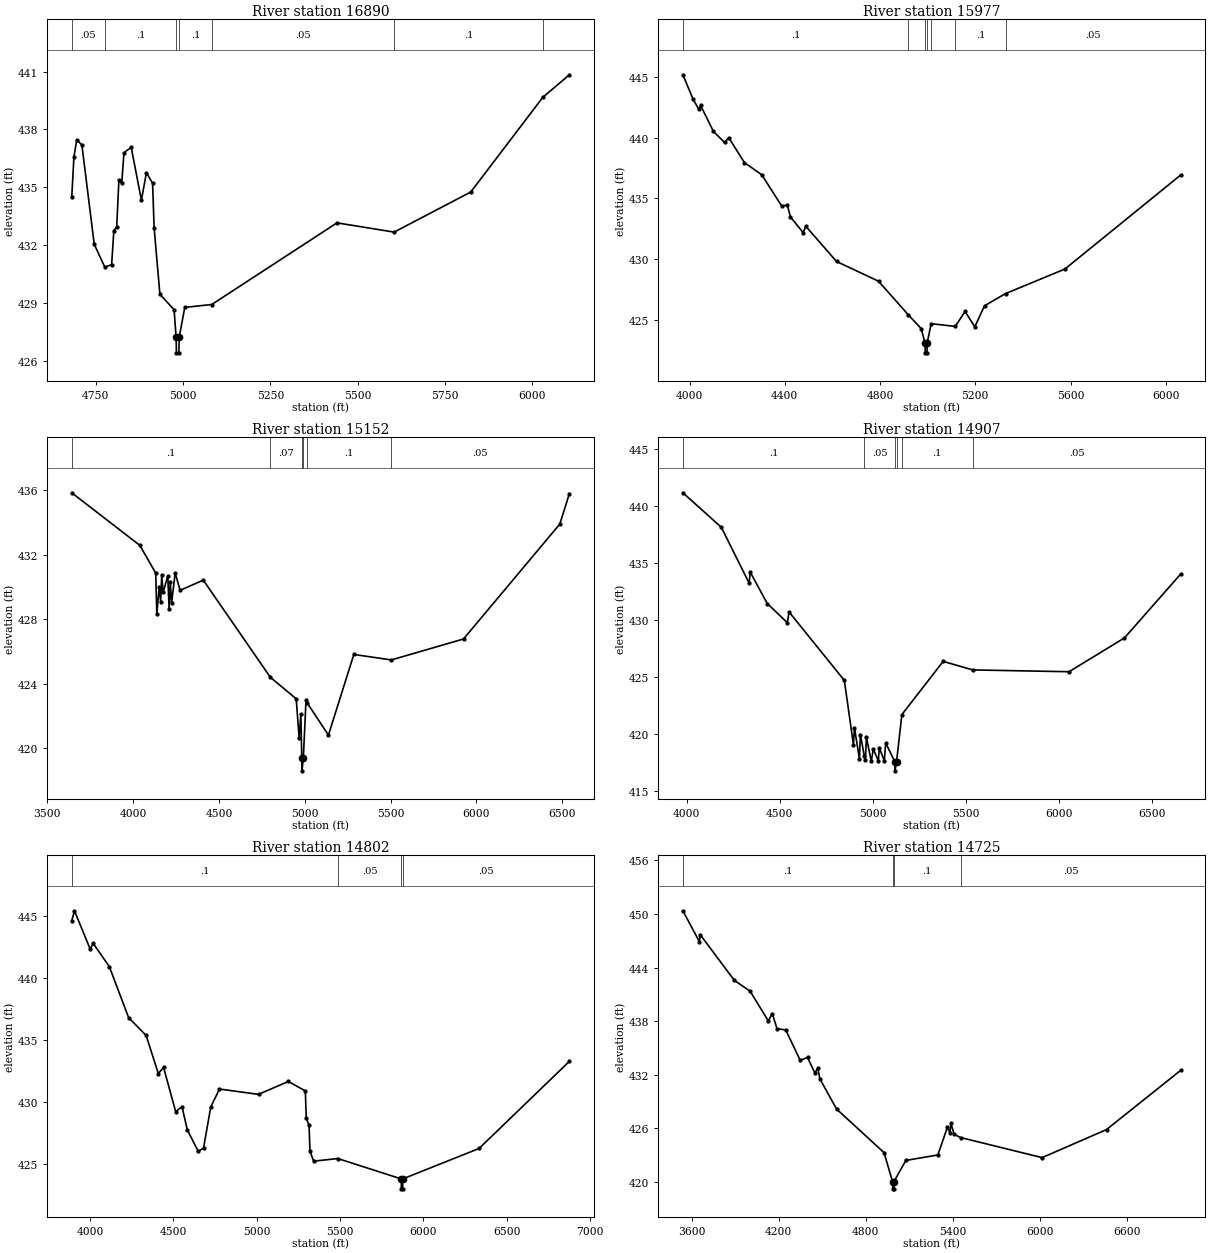
Type RM Length L Ch R = 1,16890,913,913,913
BEGIN DESCRIPTION:
Mapping XS 8b04a475
END DESCRIPTION:
XS GIS Cut Line= 4
      2072700.01     13467050.01      2072518.63     13466911.22
      2072187.03     13466846.98      2071334.82     13466737.24
#Sta/Elev= 30
  4681.2  434.48  4687.5  436.58  4695.7  437.47  4710.3  437.19  4745.6  432.04
  4775.9  430.85  4795.5  430.98  4801.8  432.75  4810.0  432.94  4816.3  435.38
  4824.5  435.21  4830.8  436.80  4851.6  437.07  4880.7  434.33  4895.2  435.76
  4912.8  435.20  4917.2  432.89  4933.7  429.44  4974.4  428.64  4980.2  427.20
  4981.0  426.40  4988.1  426.40  4988.9  427.20  5005.0  428.76  5082.3  428.91
  5441.0  433.15  5604.6  432.67  5824.1  434.75  6030.6  439.67  6106.6  440.84
#Mann=7,-1,0
  4681.2    0.05       0  4775.9     0.1       0  4980.2    0.07       0
  4988.9     0.1       0  5082.3    0.05       0  5604.6     0.1       0
  6030.6    0.05       0
Bank Sta=4980.2,4988.9
Exp/Cntr=0.3,0.1

Type RM Length L Ch R = 1,15977,825,825,825
BEGIN DESCRIPTION:
Mapping XS f8a3c205
END DESCRIPTION:
XS GIS Cut Line= 4
      2073564.19     13466374.13      2072627.03     13465999.93
      2072299.18     13466069.47      2071570.67     13466228.42
#Sta/Elev= 30
  3972.0  445.16  4014.8  443.15  4039.1  442.32  4046.5  442.64  4100.3  440.50
  4146.9  439.60  4164.9  439.98  4230.4  437.94  4303.1  436.94  4386.7  434.38
  4410.9  434.44  4423.4  433.48  4477.2  432.18  4488.0  432.71  4617.2  429.81
  4793.5  428.19  4917.9  425.44  4972.5  424.30  4989.0  423.10  4989.8  422.30
  4997.0  422.30  4997.8  423.10  5014.7  424.70  5115.9  424.47  5157.0  425.70
  5197.9  424.44  5238.7  426.17  5326.9  427.17  5576.4  429.19  6061.9  436.91
#Mann=7,-1,0
  3972.0     0.1       0  4917.9    0.12       0  4989.0    0.07       0
  4997.8    0.12       0  5014.7    0.07       0  5115.9     0.1       0
  5326.9    0.05       0
Bank Sta=4989,4997.8
Exp/Cntr=0.3,0.1

Type RM Length L Ch R = 1,15152,245,245,245
BEGIN DESCRIPTION:
Mapping XS a89fd50c
END DESCRIPTION:
XS GIS Cut Line= 4
      2073918.14     13465929.96      2073060.38     13465228.58
      2072567.00     13465181.94      2071574.34     13466013.30
#Sta/Elev= 30
  3642.8  435.85  4039.3  432.59  4131.9  430.87  4138.3  428.36  4152.7  430.01
  4160.6  429.10  4167.0  430.76  4174.9  429.68  4202.3  430.68  4210.1  428.61
  4216.6  430.32  4224.5  429.03  4245.3  430.88  4274.0  429.80  4409.0  430.43
  4799.9  424.40  4950.2  423.07  4967.2  420.63  4977.2  422.12  4982.6  419.40
  4983.5  418.60  4991.8  419.40  5007.3  423.00  5013.5  422.82  5137.9  420.82
  5285.9  425.82  5504.3  425.48  5924.7  426.78  6485.5  433.91  6541.2  435.80
#Mann=6,-1,0
  3642.8     0.1       0  4799.9    0.07       0  4982.6    0.07       0
  4991.8    0.07       0  5013.5     0.1       0  5504.3    0.05       0
Bank Sta=4982.6,4991.8
Exp/Cntr=0.3,0.1

Type RM Length L Ch R = 1,14907,105,105,105
BEGIN DESCRIPTION:
Mapping XS 71eb256e
END DESCRIPTION:
XS GIS Cut Line= 5
      2073824.32     13465346.60      2072981.39     13465002.88
      2072811.25     13464948.20      2072678.44     13464928.23
      2071449.68     13465695.38
#Sta/Elev= 30
  3979.4  441.16  4185.8  438.13  4335.0  433.23  4340.8  434.20  4432.2  431.44
  4540.2  429.75  4549.3  430.70  4846.2  424.69  4895.2  419.02  4900.4  420.55
  4927.3  417.78  4932.5  419.94  4953.6  418.02  4959.3  417.69  4964.6  419.68
  4991.0  417.58  5001.9  418.67  5028.8  417.61  5034.0  418.78  5060.9  417.62
  5068.4  419.20  5117.3  417.55  5118.2  416.75  5126.5  417.55  5155.2  421.69
  5376.9  426.36  5535.3  425.61  6052.7  425.45  6350.3  428.42  6651.3  434.01
#Mann=6,-1,0
  3979.4     0.1       0  4953.6    0.05       0  5117.3   0.033       0
  5126.5    0.05       0  5155.2     0.1       0  5535.3    0.05       0
Bank Sta=5117.3,5126.5
Exp/Cntr=0.3,0.1

Type RM Length L Ch R = 1,14802,77,77,77
BEGIN DESCRIPTION:
Mapping XS 6feb2be1
END DESCRIPTION:
XS GIS Cut Line= 5
      2073980.62     13465169.53      2073121.15     13464897.85
      2072879.83     13464866.60      2072653.27     13464844.90
      2071210.46     13465570.23
#Sta/Elev= 30
  3889.7  444.60  3906.1  445.41  4000.5  442.32  4018.5  442.78  4115.5  440.91
  4231.2  436.80  4336.1  435.37  4409.5  432.30  4441.0  432.79  4513.8  429.22
  4551.4  429.64  4583.7  427.75  4648.4  426.05  4680.7  426.27  4724.1  429.60
  4776.6  431.05  5011.0  430.62  5190.0  431.66  5291.9  430.90  5297.5  428.71
  5314.2  428.13  5319.8  426.05  5342.1  425.24  5486.8  425.45  5867.7  423.81
  5868.5  423.01  5876.0  423.01  5876.9  423.81  6334.6  426.26  6876.9  433.28
#Mann=4,-1,0
  3889.7     0.1       0  5486.8    0.05       0  5867.7    0.07       0
  5876.9    0.05       0
Bank Sta=5867.7,5876.9
Exp/Cntr=0.3,0.1

Type RM Length L Ch R = 1,14725,632,632,632
BEGIN DESCRIPTION:
Mapping XS c576d7af
END DESCRIPTION:
XS GIS Cut Line= 5
      2074381.70     13465039.33      2073035.21     13464808.44
      2072901.53     13464794.55      2072612.47     13464777.19
      2071116.93     13465450.38
#Sta/Elev= 30
  3539.8  450.35  3653.7  446.89  3658.7  447.69  3893.7  442.58  4003.2  441.35
  4128.8  438.03  4155.4  438.86  4188.8  437.17  4248.8  437.02  4348.1  433.63
  4398.9  433.94  4449.6  432.21  4469.9  432.76  4483.8  431.56  4598.8  428.18
  4926.3  423.30  4985.0  420.05  4985.9  419.25  4993.4  419.25  4994.2  420.05
  5076.9  422.43  5297.3  423.04  5363.3  426.15  5381.0  425.48  5386.5  426.60
  5409.6  425.35  5453.5  424.99  6015.7  422.74  6459.8  425.88  6970.0  432.49
#Mann=4,-1,0
  3539.8     0.1       0  4985.0    0.07       0  4994.2     0.1       0
  5453.5    0.05       0
Bank Sta=4985,4994.2
Exp/Cntr=0.3,0.1

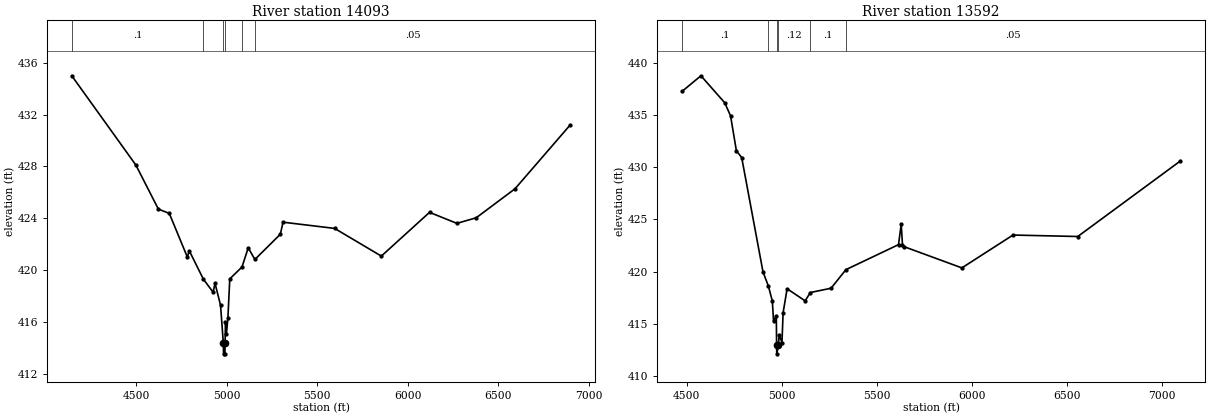
Type RM Length L Ch R = 1,14093,501,501,501
BEGIN DESCRIPTION:
Mapping XS 741801ac
END DESCRIPTION:
XS GIS Cut Line= 4
      2073555.23     13464188.63      2073022.68     13464269.40
      2072522.68     13464368.36      2071136.87     13465362.24
#Sta/Elev= 30
  4143.5  435.00  4497.7  428.10  4621.8  424.70  4682.1  424.37  4781.7  421.00
  4792.6  421.48  4870.7  419.28  4924.4  418.28  4934.6  418.97  4965.2  417.28
  4980.8  414.32  4981.7  413.52  4989.4  413.52  4990.3  414.32  4992.5  415.99
  4997.6  415.05  5006.0  416.30  5016.2  419.31  5083.8  420.23  5118.1  421.71
  5154.9  420.81  5295.6  422.76  5310.3  423.69  5595.3  423.21  5853.5  421.07
  6119.6  424.45  6270.7  423.60  6377.5  424.03  6591.8  426.27  6897.2  431.21
#Mann=6,-1,0
  4143.5     0.1       0  4870.7    0.12       0  4980.8    0.07       0
  4990.3    0.12       0  5083.8     0.1       0  5154.9    0.05       0
Bank Sta=4980.8,4990.3
Exp/Cntr=0.3,0.1

Type RM Length L Ch R = 1,13592,444,444,444
BEGIN DESCRIPTION:
Mapping XS 4adb3e10
END DESCRIPTION:
XS GIS Cut Line= 4
      2073155.97     13463830.99      2072735.36     13463910.85
      2072414.18     13464137.63      2071063.92     13465325.81
#Sta/Elev= 30
  4475.7  437.27  4575.5  438.77  4700.6  436.18  4731.2  434.92  4761.7  431.58
  4789.6  430.93  4901.5  419.97  4929.9  418.60  4950.7  417.17  4956.9  415.23
  4971.6  415.76  4973.0  412.91  4973.9  412.11  4982.6  412.91  4986.4  413.95
  5001.2  413.19  5007.3  416.06  5028.3  418.35  5123.1  417.19  5150.4  417.99
  5259.3  418.40  5337.2  420.18  5613.7  422.58  5627.9  424.53  5634.6  422.56
  5642.2  422.39  5946.7  420.35  6215.3  423.50  6555.8  423.36  7095.6  430.61
#Mann=6,-1,0
  4475.7     0.1       0  4929.9    0.12       0  4973.0    0.07       0
  4982.6    0.12       0  5150.4     0.1       0  5337.2    0.05       0
Bank Sta=4973,4982.6
Exp/Cntr=0.3,0.1