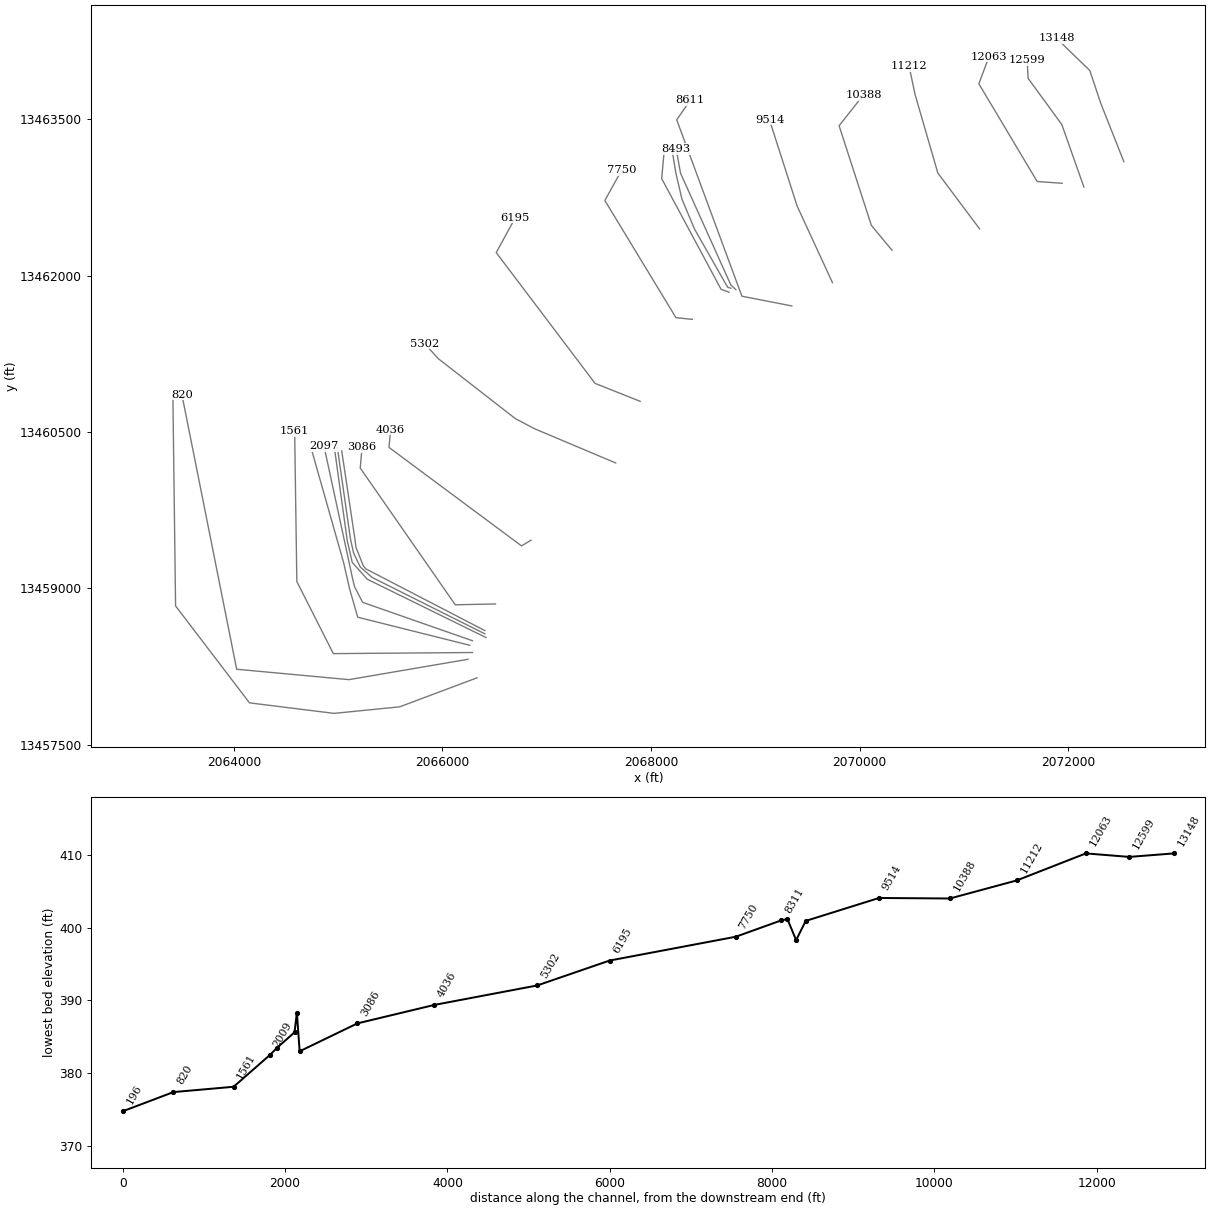
HEC-RAS study BEAR Br.prj: BEAR Br Base Level Engineering

--- BEAR Br.g01 (geometry) --- (continued)

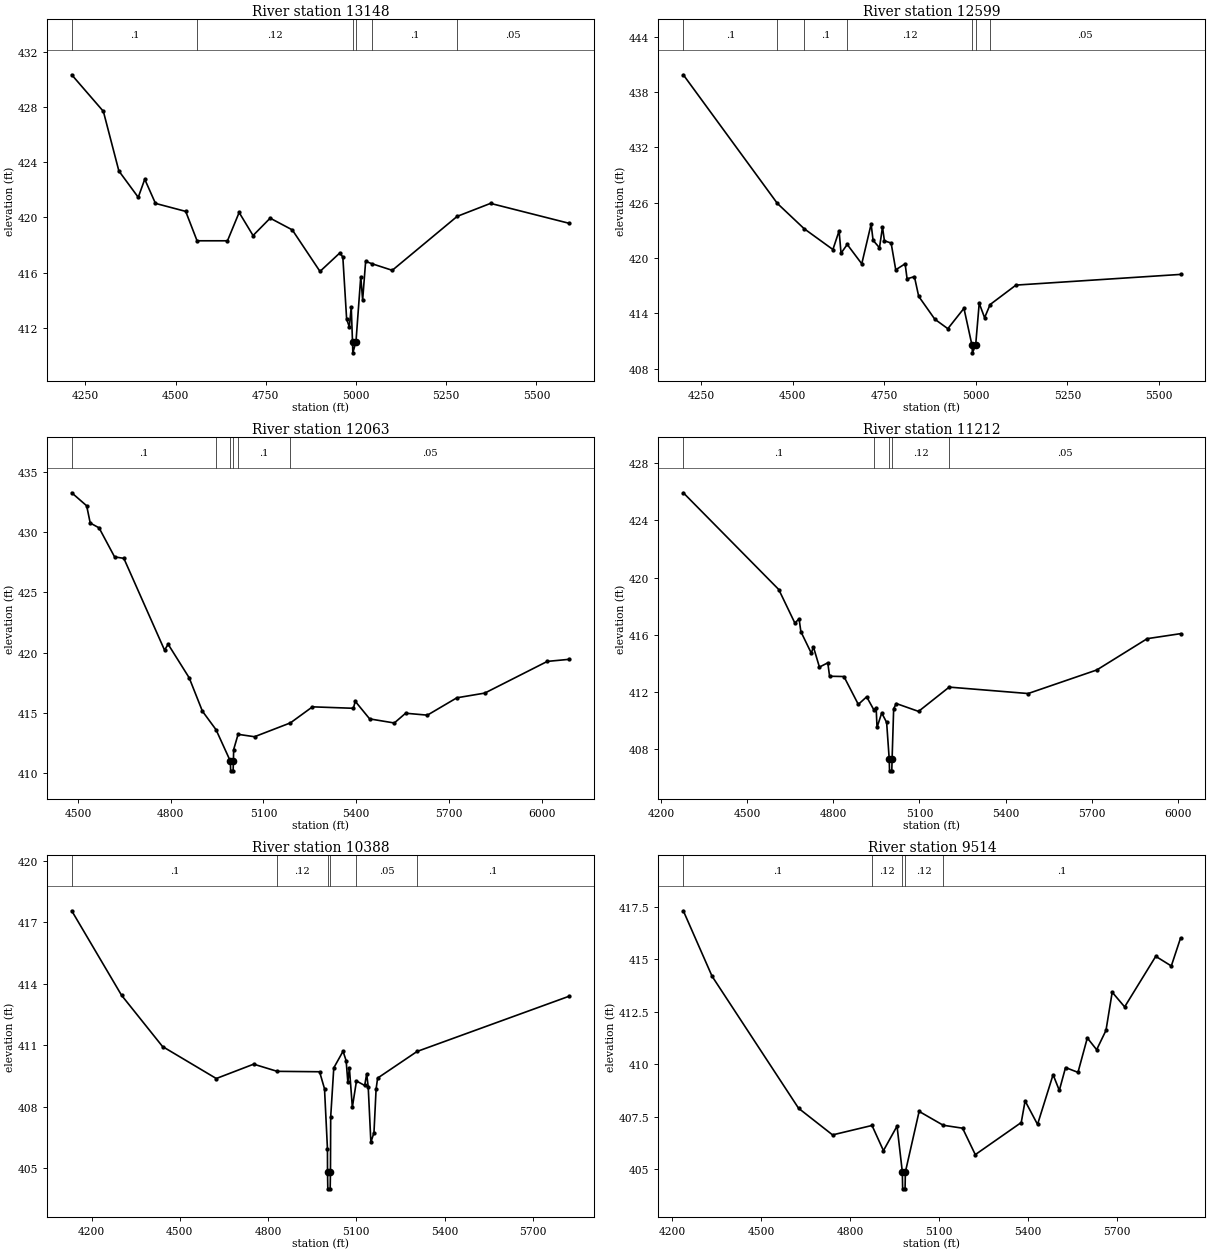
Type RM Length L Ch R = 1,13148,549,549,549
BEGIN DESCRIPTION:
Mapping XS 3a4c25dc
END DESCRIPTION:
XS GIS Cut Line= 4
      2072535.01     13463093.47      2072312.77     13463656.01
      2072208.61     13463968.51      2071889.60     13464277.12
#Sta/Elev= 30
  4211.9  430.34  4299.6  427.69  4342.6  423.37  4396.3  421.46  4414.3  422.77
  4444.0  421.02  4527.8  420.44  4559.3  418.31  4643.6  418.31  4675.9  420.36
  4714.5  418.69  4761.9  419.95  4823.2  419.10  4900.0  416.09  4955.0  417.43
  4963.3  417.13  4973.8  412.65  4981.3  412.06  4986.6  413.51  4990.1  410.99
  4991.0  410.19  4999.7  410.99  5013.0  415.71  5018.2  414.02  5026.5  416.82
  5043.7  416.65  5100.3  416.17  5280.2  420.08  5372.6  421.02  5590.0  419.58
#Mann=6,-1,0
  4211.9     0.1       0  4559.3    0.12       0  4990.1    0.07       0
  4999.7    0.12       0  5043.7     0.1       0  5280.2    0.05       0
Bank Sta=4990.1,4999.7
Exp/Cntr=0.3,0.1

Type RM Length L Ch R = 1,12599,536,536,536
BEGIN DESCRIPTION:
Mapping XS b5624ad7
END DESCRIPTION:
XS GIS Cut Line= 4
      2072151.89     13462849.70      2071940.04     13463450.36
      2071616.91     13463892.88      2071607.62     13464065.87
#Sta/Elev= 30
  4200.8  439.88  4457.7  425.92  4530.8  423.18  4609.4  420.92  4626.3  422.94
  4631.6  420.52  4648.5  421.47  4688.2  419.37  4713.8  423.68  4719.1  421.92
  4736.6  421.11  4744.8  423.35  4750.1  421.87  4768.4  421.62  4781.0  418.72
  4806.6  419.37  4812.0  417.74  4832.0  417.98  4843.7  415.84  4887.7  413.36
  4923.3  412.33  4967.3  414.54  4989.4  410.51  4990.4  409.71  4999.2  410.51
  5009.0  415.09  5023.7  413.52  5038.8  414.95  5109.4  417.06  5558.9  418.22
#Mann=7,-1,0
  4200.8     0.1       0  4457.7    0.12       0  4530.8     0.1       0
  4648.5    0.12       0  4989.4    0.07       0  4999.2    0.12       0
  5038.8    0.05       0
Bank Sta=4989.4,4999.2
Exp/Cntr=0.3,0.1

Type RM Length L Ch R = 1,12063,851,851,851
BEGIN DESCRIPTION:
Mapping XS 52ce9252
END DESCRIPTION:
XS GIS Cut Line= 4
      2071943.30     13462885.93      2071703.72     13462903.29
      2071144.69     13463840.79      2071241.70     13464100.64
#Sta/Elev= 30
  4479.4  433.26  4527.8  432.18  4539.3  430.75  4567.9  430.35  4618.1  427.94
  4648.1  427.82  4779.7  420.21  4791.5  420.69  4859.5  417.91  4902.3  415.14
  4946.5  413.60  4992.8  410.99  4993.8  410.19  5001.7  410.19  5002.6  410.99
  5003.5  411.96  5017.8  413.22  5070.9  413.02  5187.2  414.17  5258.5  415.50
  5390.9  415.38  5396.9  415.96  5443.5  414.50  5523.3  414.16  5559.9  414.97
  5630.3  414.81  5725.7  416.25  5816.0  416.64  6018.4  419.27  6088.5  419.44
#Mann=6,-1,0
  4479.4     0.1       0  4946.5    0.12       0  4992.8    0.07       0
  5002.6    0.12       0  5017.8     0.1       0  5187.2    0.05       0
Bank Sta=4992.8,5002.6
Exp/Cntr=0.3,0.1

Type RM Length L Ch R = 1,11212,824,824,824
BEGIN DESCRIPTION:
Mapping XS ce33431e
END DESCRIPTION:
XS GIS Cut Line= 4
      2071152.25     13462447.83      2070751.22     13462984.27
      2070532.47     13463739.48      2070475.21     13464010.17
#Sta/Elev= 30
  4277.0  425.94  4609.6  419.17  4665.8  416.82  4680.4  417.12  4686.7  416.22
  4722.9  414.72  4730.4  415.15  4751.3  413.74  4780.5  414.04  4786.7  413.10
  4836.7  413.08  4886.8  411.13  4915.9  411.66  4941.2  410.74  4949.0  410.90
  4952.0  409.52  4968.4  410.53  4985.5  409.87  4994.6  407.28  4995.6  406.48
  5003.5  406.48  5004.5  407.28  5010.0  410.83  5019.1  411.19  5096.7  410.64
  5203.5  412.34  5478.5  411.89  5717.9  413.54  5893.5  415.73  6009.7  416.08
#Mann=5,-1,0
  4277.0     0.1       0  4941.2    0.12       0  4994.6    0.07       0
  5004.5    0.12       0  5203.5    0.05       0
Bank Sta=4994.6,5004.5
Exp/Cntr=0.3,0.1

Type RM Length L Ch R = 1,10388,874,874,874
BEGIN DESCRIPTION:
Mapping XS a3d55d56
END DESCRIPTION:
XS GIS Cut Line= 4
      2070311.37     13462243.56      2070113.44     13462483.15
      2069804.41     13463438.02      2070037.05     13463733.15
#Sta/Elev= 30
  4132.5  417.56  4301.9  413.44  4441.2  410.94  4623.9  409.38  4751.0  410.08
  4830.9  409.73  4975.0  409.71  4991.8  408.88  5001.8  405.95  5002.0  404.80
  5003.0  404.00  5011.0  404.00  5012.0  404.80  5012.8  407.51  5023.3  409.90
  5054.8  410.71  5065.3  410.25  5071.1  409.20  5076.3  409.90  5086.4  407.98
  5100.4  409.26  5128.4  409.04  5135.1  409.61  5140.3  408.98  5149.4  406.27
  5159.9  406.74  5167.1  408.86  5172.3  409.40  5306.5  410.70  5822.7  413.39
#Mann=6,-1,0
  4132.5     0.1       0  4830.9    0.12       0  5002.0    0.07       0
  5012.0    0.12       0  5100.4    0.05       0  5306.5     0.1       0
Bank Sta=5002,5012
Exp/Cntr=0.3,0.1

Type RM Length L Ch R = 1,9514,903,903,903
BEGIN DESCRIPTION:
Mapping XS 82e8c997
END DESCRIPTION:
XS GIS Cut Line= 3
      2069740.80     13461932.20      2069402.27     13462666.56
      2069136.65     13463494.66
#Sta/Elev= 30
  4237.0  417.32  4334.1  414.20  4626.0  407.91  4740.8  406.64  4873.9  407.09
  4912.5  405.89  4958.4  407.06  4976.3  404.87  4977.3  404.07  4985.5  404.07
  4986.5  404.87  5032.9  407.76  5114.2  407.10  5179.6  406.96  5222.5  405.70
  5377.6  407.23  5390.6  408.26  5432.6  407.14  5485.1  409.51  5506.1  408.76
  5527.1  409.85  5569.1  409.62  5600.6  411.26  5632.1  410.70  5663.6  411.62
  5684.6  413.44  5726.6  412.74  5831.6  415.15  5884.1  414.69  5915.3  416.02
#Mann=5,-1,0
  4237.0     0.1       0  4873.9    0.12       0  4976.3    0.07       0
  4986.5    0.12       0  5114.2     0.1       0
Bank Sta=4976.3,4986.5
Exp/Cntr=0.3,0.1

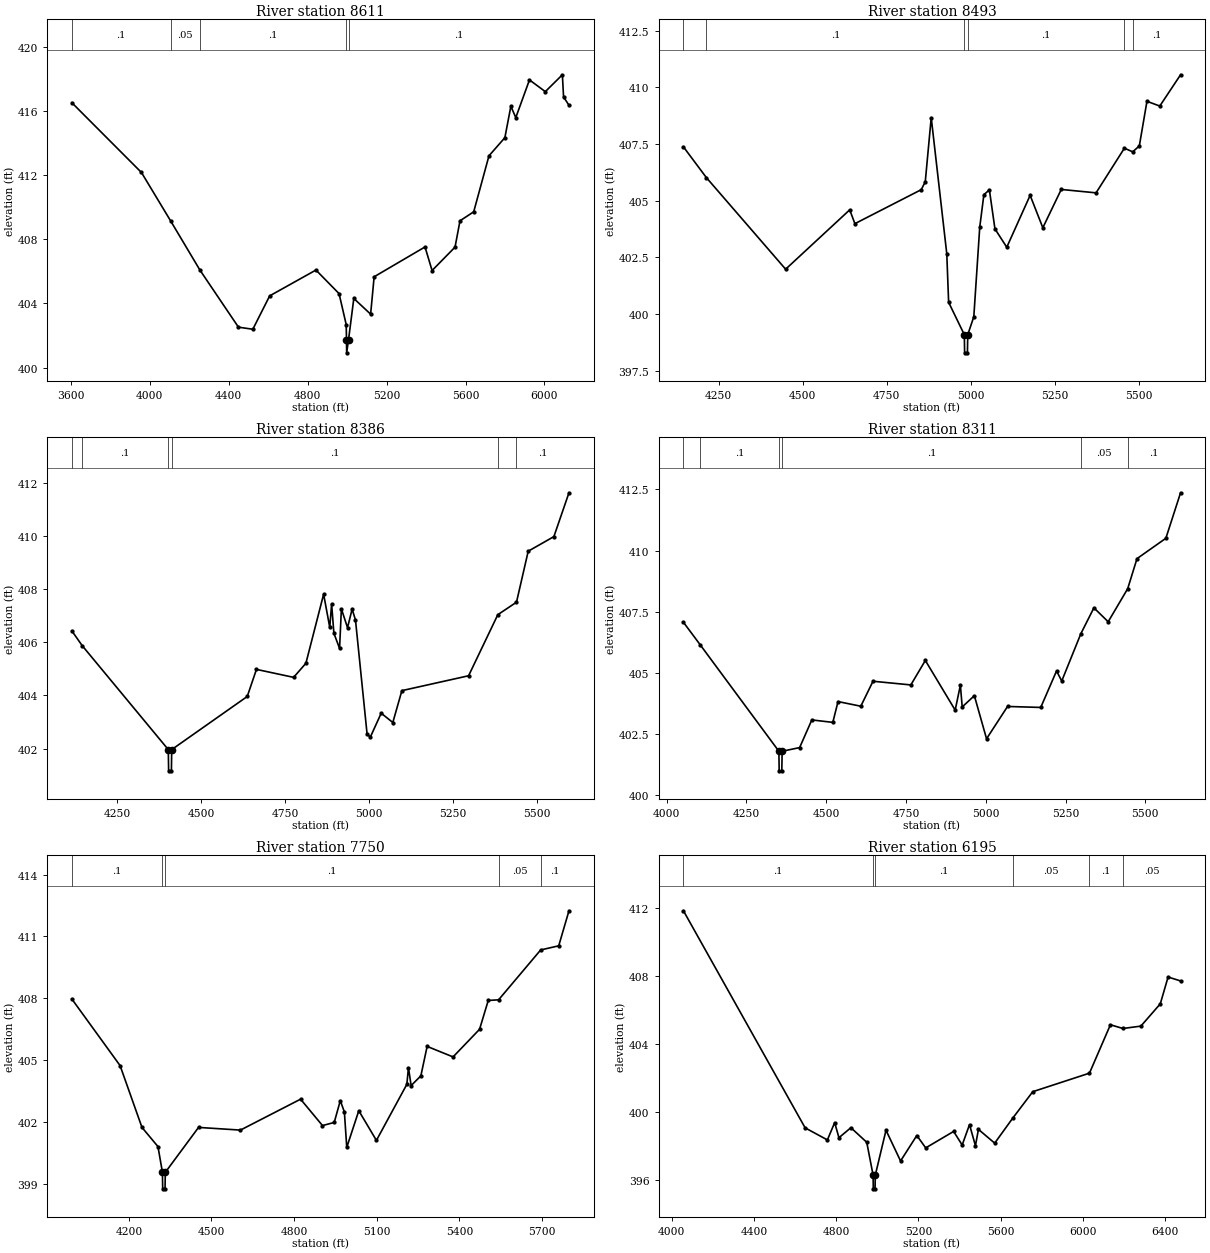
Type RM Length L Ch R = 1,8611,118,118,118
BEGIN DESCRIPTION:
Mapping XS 93852d11
END DESCRIPTION:
XS GIS Cut Line= 4
      2069351.26     13461708.85      2068872.12     13461802.60
      2068247.12     13463495.31      2068376.35     13463681.40
#Sta/Elev= 30
  3604.8  416.51  3957.6  412.16  4105.1  409.15  4253.8  406.08  4449.1  402.52
  4522.0  402.39  4607.3  404.47  4841.8  406.08  4959.0  404.61  4995.2  402.68
  4996.6  401.72  4997.5  400.92  5006.8  401.72  5033.7  404.31  5118.9  403.33
  5136.7  405.66  5394.5  407.52  5430.3  406.05  5546.7  407.51  5571.8  409.15
  5641.3  409.71  5718.6  413.20  5799.2  414.33  5829.6  416.29  5854.5  415.58
  5923.8  417.93  6004.1  417.20  6090.6  418.25  6096.6  416.87  6124.0  416.35
#Mann=5,-1,0
  3604.8     0.1       0  4105.1    0.05       0  4253.8     0.1       0
  4996.6    0.07       0  5006.8     0.1       0
Bank Sta=4996.6,5006.8
Exp/Cntr=0.3,0.1

Type RM Length L Ch R = 1,8493,107,107,107
BEGIN DESCRIPTION:
Mapping XS f87c0072
END DESCRIPTION:
XS GIS Cut Line= 4
      2068814.84     13461865.08      2068766.22     13461910.24
      2068283.58     13462983.15      2068241.91     13463215.82
#Sta/Elev= 30
  4145.2  407.37  4213.6  406.01  4449.3  401.97  4640.0  404.59  4655.4  403.98
  4852.8  405.48  4864.8  405.83  4882.5  408.66  4928.8  402.65  4934.3  400.51
  4981.0  399.08  4981.9  398.28  4990.2  398.28  4991.2  399.08  5009.2  399.87
  5026.9  403.83  5039.2  405.26  5055.6  405.47  5072.1  403.75  5107.3  402.94
  5176.8  405.23  5214.6  403.80  5269.4  405.49  5373.0  405.34  5457.3  407.31
  5482.0  407.15  5501.7  407.41  5524.4  409.38  5562.6  409.17  5624.4  410.55
#Mann=6,-1,0
  4145.2    0.05       0  4213.6     0.1       0  4981.0    0.07       0
  4991.2     0.1       0  5457.3    0.05       0  5482.0     0.1       0
Bank Sta=4981,4991.2
Exp/Cntr=0.3,0.1

Type RM Length L Ch R = 1,8386,75,75,75
BEGIN DESCRIPTION:
Mapping XS 9cda5506
END DESCRIPTION:
XS GIS Cut Line= 6
      2068766.17     13461879.00      2068734.97     13461889.40
      2068418.99     13462444.96      2068297.47     13462733.15
      2068238.44     13462986.63      2068200.24     13463219.27
#Sta/Elev= 30
  4115.3  406.43  4146.4  405.87  4402.6  401.96  4403.6  401.16  4411.9  401.16
  4412.8  401.96  4637.8  403.96  4665.2  404.98  4775.9  404.68  4812.5  405.21
  4865.3  407.81  4883.6  406.56  4889.1  407.44  4895.9  406.34  4912.8  405.77
  4918.2  407.26  4936.5  406.55  4950.2  407.25  4960.2  406.84  4994.8  402.54
  5004.4  402.43  5036.8  403.33  5071.4  402.98  5098.4  404.18  5297.1  404.74
  5384.2  407.04  5439.8  407.51  5474.7  409.43  5551.2  409.98  5596.1  411.63
#Mann=6,-1,0
  4115.3    0.05       0  4146.4     0.1       0  4402.6    0.07       0
  4412.8     0.1       0  5384.2    0.05       0  5439.8     0.1       0
Bank Sta=4402.6,4412.8
Exp/Cntr=0.3,0.1

Type RM Length L Ch R = 1,8311,561,561,561
BEGIN DESCRIPTION:
Mapping XS e4f0ddbd
END DESCRIPTION:
XS GIS Cut Line= 4
      2068748.87     13461840.79      2068672.47     13461868.57
      2068103.02     13462931.07      2068127.24     13463200.91
#Sta/Elev= 30
  4052.6  407.07  4105.1  406.15  4351.7  401.80  4352.6  401.00  4360.9  401.00
  4361.9  401.80  4416.7  401.95  4454.9  403.08  4520.7  402.98  4537.0  403.83
  4608.4  403.64  4646.6  404.66  4765.2  404.51  4810.6  405.51  4904.1  403.48
  4920.4  404.50  4926.1  403.61  4964.2  404.07  5002.4  402.31  5068.2  403.63
  5172.2  403.59  5221.7  405.08  5238.0  404.67  5297.8  406.60  5338.8  407.66
  5383.5  407.09  5444.6  408.44  5473.8  409.67  5564.2  410.50  5610.3  412.36
#Mann=6,-1,0
  4052.6    0.05       0  4105.1     0.1       0  4351.7    0.07       0
  4361.9     0.1       0  5297.8    0.05       0  5444.6     0.1       0
Bank Sta=4351.7,4361.9
Exp/Cntr=0.3,0.1

Type RM Length L Ch R = 1,7750,1555,1555,1555
BEGIN DESCRIPTION:
Mapping XS 43b4f0b9
END DESCRIPTION:
XS GIS Cut Line= 4
      2068396.47     13461580.37      2068240.17     13461596.00
      2067557.88     13462721.00      2067718.62     13463011.37
#Sta/Elev= 30
  3993.1  407.96  4168.2  404.73  4247.7  401.73  4305.8  400.80  4322.0  399.55
  4322.9  398.75  4331.5  398.75  4332.4  399.55  4453.1  401.73  4605.1  401.60
  4823.5  403.10  4903.0  401.82  4945.6  401.97  4967.7  403.03  4982.5  402.48
  4991.1  400.76  5034.8  402.54  5098.8  401.10  5209.3  403.82  5215.1  404.63
  5224.8  403.76  5260.1  404.23  5282.9  405.66  5377.0  405.15  5473.2  406.49
  5504.8  407.89  5542.3  407.92  5695.1  410.34  5760.6  410.54  5797.8  412.24
#Mann=5,-1,0
  3993.1     0.1       0  4322.0    0.07       0  4332.4     0.1       0
  5542.3    0.05       0  5695.1     0.1       0
Bank Sta=4322,4332.4
Exp/Cntr=0.3,0.1

Type RM Length L Ch R = 1,6195,893,893,893
BEGIN DESCRIPTION:
Mapping XS 313a8aae
END DESCRIPTION:
XS GIS Cut Line= 4
      2067896.39     13460793.93      2067464.13     13460965.79
      2066516.22     13462221.00      2066698.50     13462554.32
#Sta/Elev= 30
  4057.0  411.85  4649.0  399.07  4757.2  398.36  4792.6  399.38  4813.4  398.49
  4871.6  399.08  4948.7  398.22  4979.6  396.28  4980.5  395.48  4989.2  395.48
  4990.1  396.28  5042.3  398.93  5113.1  397.12  5192.2  398.62  5235.5  397.89
  5371.2  398.86  5412.8  398.06  5448.5  399.26  5477.3  398.02  5491.9  398.98
  5571.0  398.17  5658.6  399.64  5756.2  401.20  6031.9  402.29  6133.8  405.14
  6194.7  404.92  6282.0  405.06  6376.4  406.37  6414.3  407.95  6475.0  407.72
#Mann=6,-1,0
  4057.0     0.1       0  4979.6    0.07       0  4990.1     0.1       0
  5658.6    0.05       0  6031.9     0.1       0  6194.7    0.05       0
Bank Sta=4979.6,4990.1
Exp/Cntr=0.3,0.1

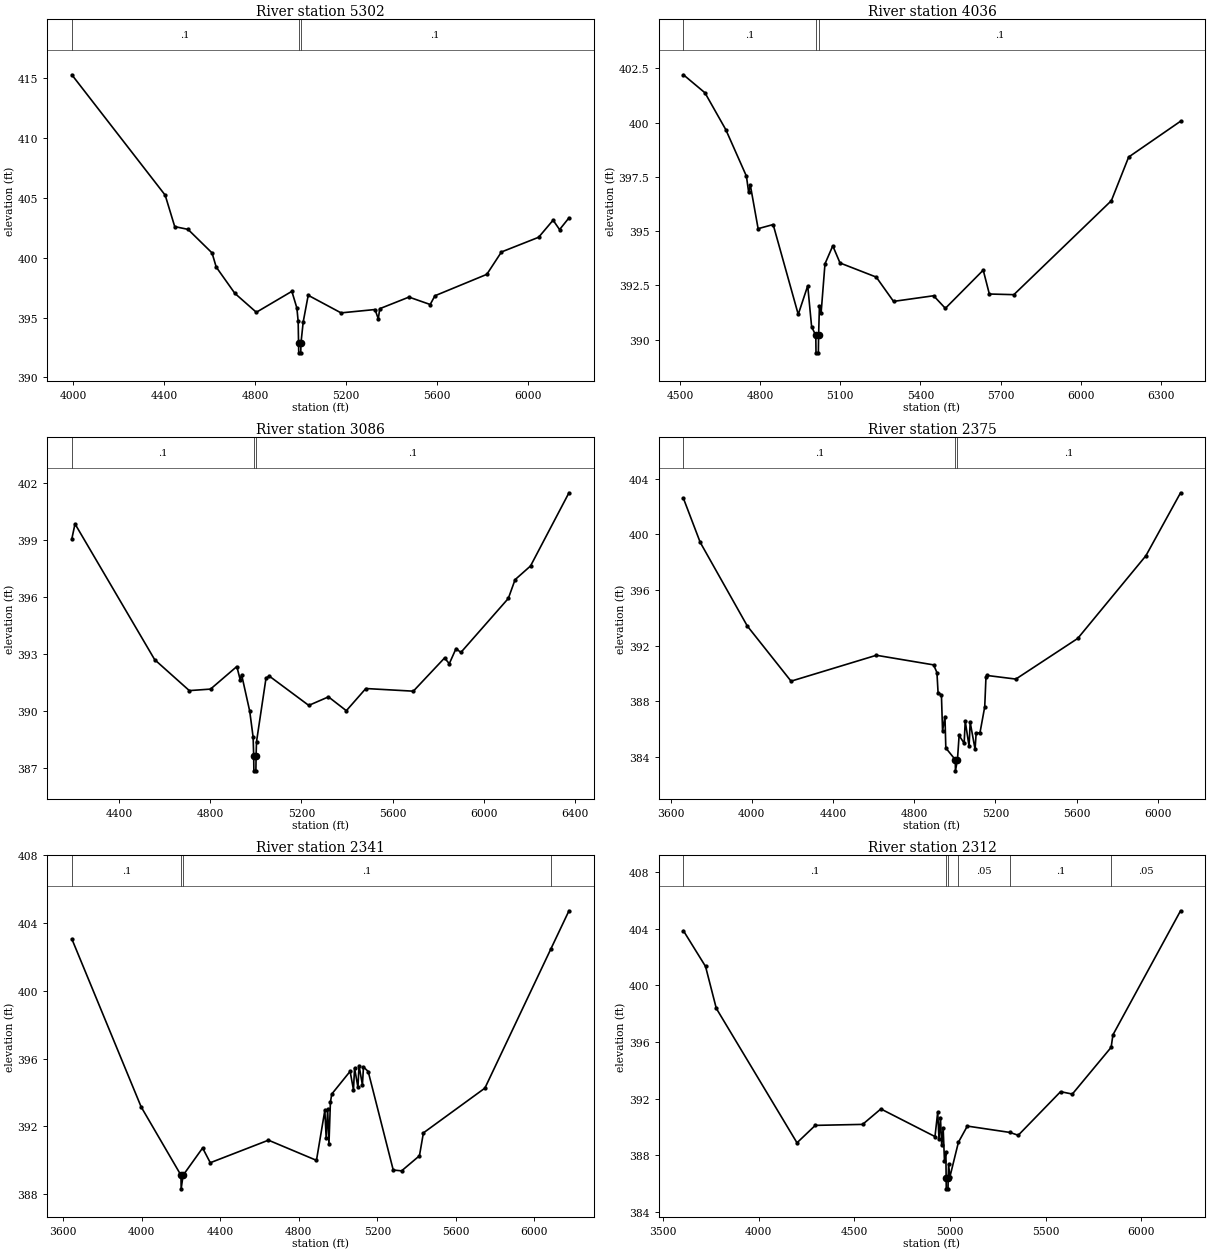
Type RM Length L Ch R = 1,5302,1266,1266,1266
BEGIN DESCRIPTION:
Mapping XS f1239fa7
END DESCRIPTION:
XS GIS Cut Line= 5
      2067661.91     13460202.26      2066885.98     13460529.66
      2066699.37     13460627.87      2065959.49     13461204.06
      2065829.28     13461347.30
#Sta/Elev= 30
  3994.9  415.30  4405.0  405.24  4447.0  402.61  4505.3  402.38  4611.0  400.41
  4629.3  399.23  4711.3  397.03  4805.6  395.45  4961.7  397.20  4983.8  395.80
  4989.4  394.69  4991.1  392.86  4992.0  392.06  5000.8  392.06  5001.6  392.86
  5011.5  394.64  5033.5  396.87  5177.8  395.40  5327.0  395.68  5341.5  394.90
  5347.9  395.75  5476.3  396.72  5569.5  396.10  5590.3  396.83  5818.3  398.62
  5882.6  400.49  6046.1  401.72  6109.6  403.15  6138.0  402.36  6179.3  403.34
#Mann=3,-1,0
  3994.9     0.1       0  4991.1    0.07       0  5001.6     0.1       0
Bank Sta=4991.1,5001.6
Exp/Cntr=0.3,0.1

Type RM Length L Ch R = 1,4036,950,950,950
BEGIN DESCRIPTION:
Mapping XS b5602d89
END DESCRIPTION:
XS GIS Cut Line= 4
      2066849.96     13459461.01      2066758.84     13459406.33
      2065488.00     13460351.64      2065503.47     13460521.81
#Sta/Elev= 30
  4512.8  402.20  4593.4  401.37  4671.5  399.67  4748.6  397.53  4757.0  396.78
  4763.2  397.12  4792.4  395.11  4848.7  395.30  4942.6  391.16  4978.1  392.48
  4992.7  390.59  5008.3  390.19  5009.1  389.39  5017.9  389.39  5018.8  390.19
  5021.9  391.53  5028.1  391.21  5042.7  393.49  5071.9  394.32  5099.0  393.53
  5234.6  392.88  5299.3  391.76  5449.4  392.02  5493.3  391.44  5635.1  393.20
  5658.0  392.10  5749.8  392.07  6114.8  396.40  6179.5  398.41  6373.8  400.06
#Mann=3,-1,0
  4512.8     0.1       0  5008.3    0.07       0  5018.8     0.1       0
Bank Sta=5008.3,5018.8
Exp/Cntr=0.3,0.1

Type RM Length L Ch R = 1,3086,711,711,711
BEGIN DESCRIPTION:
Mapping XS e8a61706
END DESCRIPTION:
XS GIS Cut Line= 4
      2066508.88     13458849.04      2066123.42     13458841.23
      2065211.96     13460153.73      2065230.10     13460353.23
#Sta/Elev= 30
  4191.2  399.08  4205.1  399.87  4555.2  392.71  4707.3  391.08  4800.5  391.16
  4916.0  392.35  4930.8  391.65  4936.9  391.92  4972.7  389.99  4987.6  388.62
  4990.0  387.65  4990.9  386.85  4999.7  386.85  5000.6  387.65  5002.4  388.38
  5044.3  391.75  5059.2  391.84  5232.0  390.30  5318.5  390.75  5397.0  390.02
  5482.6  391.19  5691.3  391.05  5828.4  392.80  5849.3  392.50  5879.0  393.30
  5900.0  393.09  6108.6  395.94  6138.3  396.93  6206.1  397.65  6375.0  401.51
#Mann=3,-1,0
  4191.2     0.1       0  4990.0    0.07       0  5000.6     0.1       0
Bank Sta=4990,5000.6
Exp/Cntr=0.3,0.1

Type RM Length L Ch R = 1,2375,34,34,34
BEGIN DESCRIPTION:
Mapping XS 7e62a8cc
END DESCRIPTION:
XS GIS Cut Line= 6
      2066406.93     13458593.75      2065265.38     13459186.13
      2065240.64     13459217.38      2065171.63     13459391.86
      2065158.61     13459488.22      2065034.58     13460317.66
#Sta/Elev= 30
  3662.8  402.59  3745.5  399.43  3977.6  393.42  4193.1  389.46  4613.5  391.32
  4895.4  390.63  4911.9  390.08  4917.5  388.63  4934.0  388.48  4939.6  385.89
  4951.4  386.92  4955.7  384.66  5002.3  383.82  5003.1  383.02  5013.0  383.82
  5021.2  385.56  5046.0  385.00  5051.3  386.59  5070.3  384.78  5075.7  386.51
  5099.8  384.57  5105.2  385.74  5123.9  385.75  5147.4  387.62  5153.5  389.75
  5158.8  389.87  5300.7  389.61  5605.7  392.53  5941.6  398.47  6112.3  402.99
#Mann=3,-1,0
  3662.8     0.1       0  5002.3    0.07       0  5013.0     0.1       0
Bank Sta=5002.3,5013
Exp/Cntr=0.3,0.1

Type RM Length L Ch R = 1,2341,29,29,29
BEGIN DESCRIPTION:
Mapping XS ed4efae6
END DESCRIPTION:
XS GIS Cut Line= 6
      2066406.99     13458562.48      2065327.55     13459102.85
      2065211.99     13459204.36      2065148.19     13459338.48
      2065118.24     13459473.89      2064992.92     13460348.90
#Sta/Elev= 30
  3643.8  403.06  3997.0  393.15  4199.8  389.12  4200.6  388.32  4210.5  389.12
  4309.9  390.73  4349.0  389.86  4645.2  391.19  4889.8  390.00  4932.5  392.95
  4939.2  391.32  4946.8  393.01  4953.4  390.96  4960.8  393.42  4967.7  393.91
  5061.2  395.25  5078.3  394.16  5083.9  395.44  5101.0  394.31  5106.6  395.59
  5123.8  394.45  5129.3  395.51  5153.3  395.24  5280.8  389.43  5323.4  389.38
  5414.3  390.27  5434.5  391.62  5747.7  394.26  6083.7  402.47  6175.9  404.72
#Mann=4,-1,0
  3643.8     0.1       0  4199.8    0.07       0  4210.5     0.1       0
  6083.7    0.05       0
Bank Sta=4199.8,4210.5
Exp/Cntr=0.3,0.1

Type RM Length L Ch R = 1,2312,215,215,215
BEGIN DESCRIPTION:
Mapping XS 19f7cbe0
END DESCRIPTION:
XS GIS Cut Line= 5
      2066418.68     13458526.46      2065278.40     13459087.18
      2065135.17     13459248.63      2065086.99     13459460.87
      2064964.70     13460345.00
#Sta/Elev= 30
  3607.4  403.85  3722.9  401.33  3779.1  398.37  4200.6  388.88  4296.1  390.11
  4543.3  390.18  4638.7  391.27  4921.4  389.32  4935.6  391.05  4942.3  389.15
  4949.9  390.66  4956.5  388.70  4964.1  389.93  4970.8  387.62  4978.3  388.22
  4979.6  386.43  4980.4  385.63  4989.5  385.63  4990.3  386.43  4992.5  387.36
  4999.2  386.47  5043.8  388.92  5090.3  390.06  5313.7  389.61  5356.1  389.41
  5577.4  392.49  5638.8  392.32  5841.5  395.62  5850.8  396.50  6204.1  405.26
#Mann=6,-1,0
  3607.4     0.1       0  4979.6    0.07       0  4990.3     0.1       0
  5043.8    0.05       0  5313.7     0.1       0  5841.5    0.05       0
Bank Sta=4979.6,4990.3
Exp/Cntr=0.3,0.1

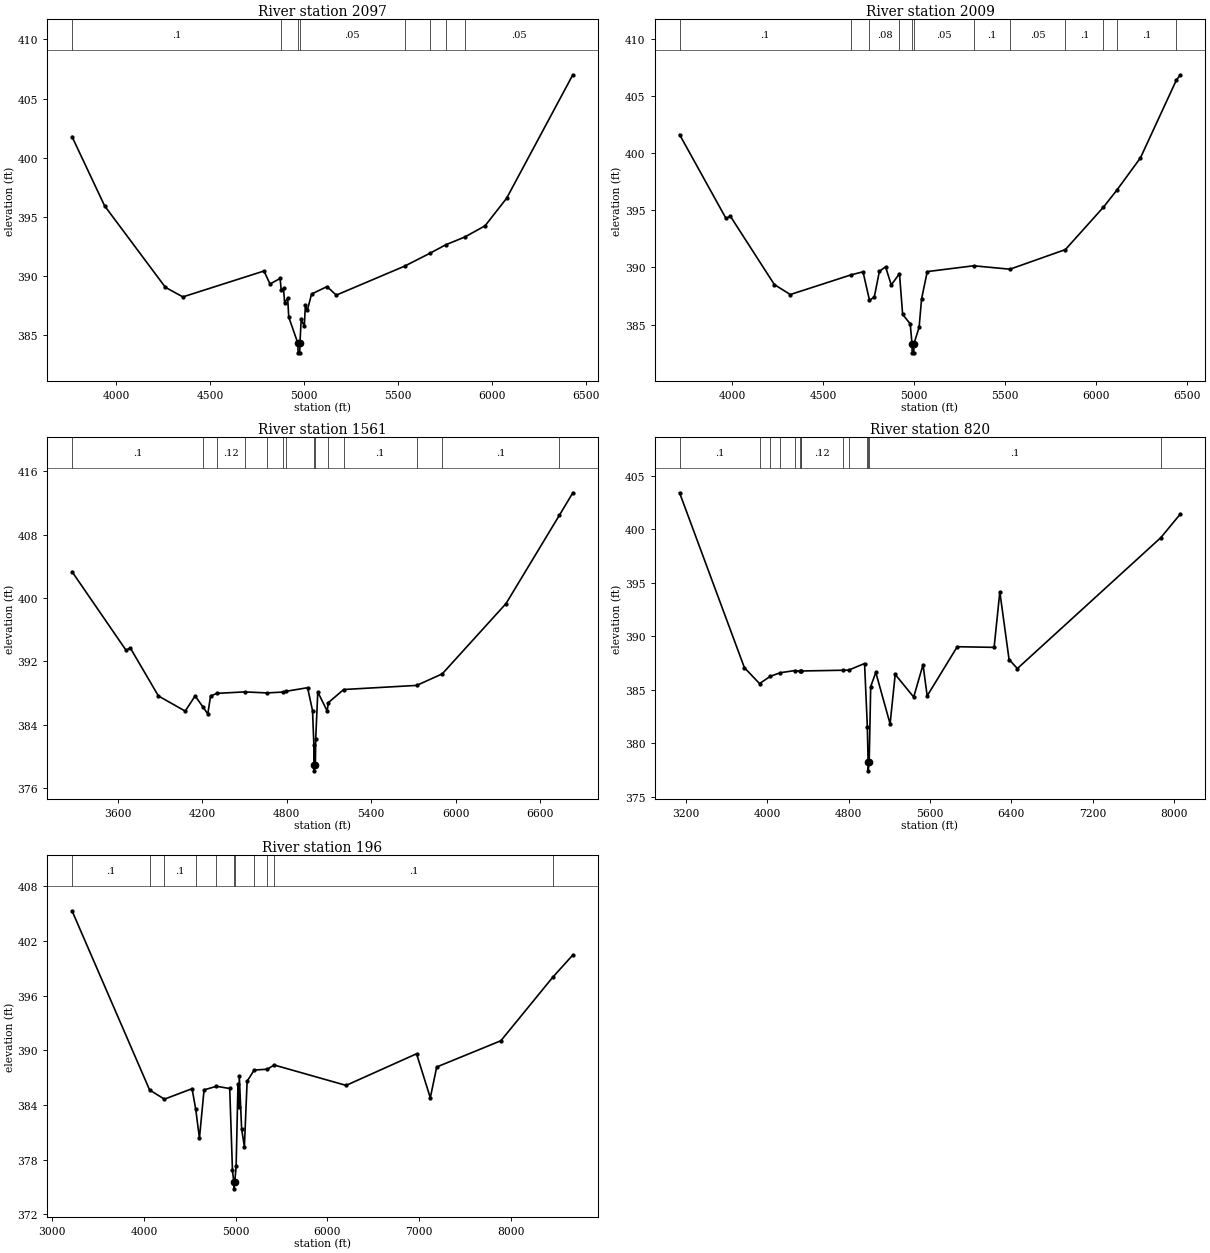
Type RM Length L Ch R = 1,2097,88,88,88
BEGIN DESCRIPTION:
Mapping XS 8cb00993
END DESCRIPTION:
XS GIS Cut Line= 5
      2066288.53     13458496.06      2065235.43     13458864.52
      2065157.30     13459014.26      2065139.08     13459091.08
      2064865.12     13460361.23
#Sta/Elev= 30
  3765.8  401.78  3939.0  395.93  4262.2  389.04  4355.3  388.23  4786.6  390.42
  4818.4  389.32  4872.2  389.79  4878.3  388.78  4890.5  388.95  4896.1  387.75
  4912.5  388.12  4918.2  386.52  4966.9  384.30  4967.7  383.50  4976.8  383.50
  4977.6  384.30  4984.4  386.34  5000.9  385.74  5006.5  387.51  5017.3  387.11
  5039.4  388.47  5121.6  389.10  5170.8  388.38  5534.3  390.83  5666.6  391.90
  5753.6  392.64  5853.8  393.29  5962.0  394.24  6076.6  396.57  6428.7  407.01
#Mann=8,-1,0
  3765.8     0.1       0  4878.3    0.05       0  4966.9    0.04       0
  4977.6    0.05       0  5534.3     0.1       0  5666.6    0.05       0
  5753.6    0.08       0  5853.8    0.05       0
Bank Sta=4966.9,4977.6
Exp/Cntr=0.3,0.1

Type RM Length L Ch R = 1,2009,448,448,448
BEGIN DESCRIPTION:
Mapping XS 1abcee1d
END DESCRIPTION:
XS GIS Cut Line= 5
      2066262.49     13458452.66      2065187.95     13458721.98
      2065112.00     13458986.74      2065053.40     13459242.81
      2064752.01     13460306.02
#Sta/Elev= 30
  3712.6  401.65  3967.7  394.30  3991.5  394.50  4233.5  388.50  4321.0  387.63
  4653.8  389.35  4720.3  389.62  4755.9  387.13  4782.2  387.40  4810.1  389.66
  4844.2  390.06  4875.5  388.47  4920.6  389.46  4938.0  385.89  4979.6  385.06
  4989.4  383.32  4990.2  382.52  4999.3  382.52  5000.1  383.32  5028.5  384.76
  5042.0  387.25  5073.2  389.64  5327.7  390.15  5527.5  389.85  5832.0  391.57
  6041.1  395.29  6113.8  396.76  6244.3  399.61  6442.1  406.44  6463.6  406.89
#Mann=12,-1,0
  3712.6     0.1       0  4653.8    0.05       0  4755.9    0.08       0
  4920.6    0.05       0  4989.4    0.04       0  5000.1    0.05       0
  5327.7     0.1       0  5527.5    0.05       0  5832.0     0.1       0
  6041.1    0.05       0  6113.8     0.1       0  6442.1    0.08       0
Bank Sta=4989.4,5000.1
Exp/Cntr=0.3,0.1

Type RM Length L Ch R = 1,1561,741,741,741
BEGIN DESCRIPTION:
Mapping XS d92562b7
END DESCRIPTION:
XS GIS Cut Line= 4
      2066288.47     13458383.23      2064954.15     13458372.48
      2064604.07     13459064.46      2064583.24     13460508.95
#Sta/Elev= 30
  3275.8  403.33  3659.3  393.39  3689.3  393.69  3889.3  387.61  4079.3  385.70
  4149.3  387.62  4205.3  386.22  4239.3  385.34  4259.3  387.61  4303.6  387.94
  4500.1  388.13  4659.7  388.00  4773.9  388.11  4797.2  388.21  4947.6  388.66
  4982.8  385.76  4992.2  381.46  4992.4  378.95  4993.2  378.15  5003.1  378.95
  5005.2  382.16  5020.1  388.12  5086.9  385.71  5095.0  386.77  5203.9  388.43
  5722.0  388.95  5903.6  390.41  6356.3  399.30  6734.8  410.46  6830.3  413.30
#Mann=14,-1,0
  3275.8     0.1       0  4205.3    0.05       0  4303.6    0.12       0
  4500.1    0.07       0  4659.7    0.12       0  4773.9    0.07       0
  4797.2    0.12       0  4992.4    0.07       0  5003.1    0.12       0
  5095.0    0.07       0  5203.9     0.1       0  5722.0    0.05       0
  5903.6     0.1       0  6734.8    0.05       0
Bank Sta=4992.4,5003.1
Exp/Cntr=0.3,0.1

Type RM Length L Ch R = 1,820,624,624,624
BEGIN DESCRIPTION:
Mapping XS 23fc4d09
END DESCRIPTION:
XS GIS Cut Line= 4
      2066245.09     13458318.13      2065103.59     13458122.81
      2064027.20     13458222.64      2063502.02     13460857.20
#Sta/Elev= 30
  3136.1  403.43  3773.8  387.07  3922.6  385.58  4028.5  386.26  4127.7  386.60
  4270.0  386.80  4321.3  386.73  4326.1  386.74  4333.7  386.76  4742.4  386.83
  4798.1  386.84  4955.6  387.46  4983.0  381.55  4990.4  378.22  4991.2  377.42
  5001.2  378.22  5015.9  385.30  5066.1  386.63  5206.7  381.81  5256.9  386.44
  5438.8  384.32  5530.6  387.35  5571.3  384.43  5867.1  389.03  6229.8  388.97
  6285.9  394.16  6376.9  387.83  6458.5  386.99  7870.0  399.24  8061.6  401.45
#Mann=14,-1,0
  3136.1     0.1       0  3922.6    0.05       0  4028.5    0.07       0
  4127.7    0.12       0  4270.0    0.07       0  4321.3    0.12       0
  4326.1    0.07       0  4333.7    0.12       0  4742.4    0.07       0
  4798.1    0.12       0  4983.0     0.1       0  4990.4    0.07       0
  5001.2     0.1       0  7870.0    0.05       0
Bank Sta=4990.4,5001.2
Exp/Cntr=0.3,0.1

Type RM Length L Ch R = 1,196,0,0,0
BEGIN DESCRIPTION:
BEAR Br 1.0
END DESCRIPTION:
XS GIS Cut Line= 6
      2066331.86     13458140.16      2065590.87     13457862.06
      2064961.53     13457799.13      2064150.00     13457900.00
      2063441.26     13458830.28      2063415.22     13460870.07
#Sta/Elev= 30
  3215.2  405.30  4061.8  385.64  4223.1  384.63  4525.0  385.78  4564.8  383.53
  4605.5  380.34  4655.7  385.65  4791.1  386.04  4935.8  385.80  4965.8  376.81
  4980.4  375.59  4981.2  374.79  4991.2  375.59  5005.8  377.25  5025.8  386.28
  5035.1  383.74  5040.1  387.19  5065.8  381.37  5095.8  379.41  5125.8  386.60
  5202.6  387.82  5347.9  387.92  5419.7  388.38  6205.5  386.14  6974.3  389.61
  7124.3  384.78  7194.3  388.16  7894.4  391.04  8459.7  398.00  8679.5  400.45
#Mann=11,-1,0
  3215.2     0.1       0  4061.8    0.05       0  4223.1     0.1       0
  4564.8    0.12       0  4791.1     0.1       0  4980.4    0.07       0
  4991.2     0.1       0  5202.6     0.1       0  5347.9    0.12       0
  5419.7     0.1       0  8459.7    0.05       0
Bank Sta=4980.4,4991.2
Exp/Cntr=0.3,0.1

Chan Stop Cuts=-1