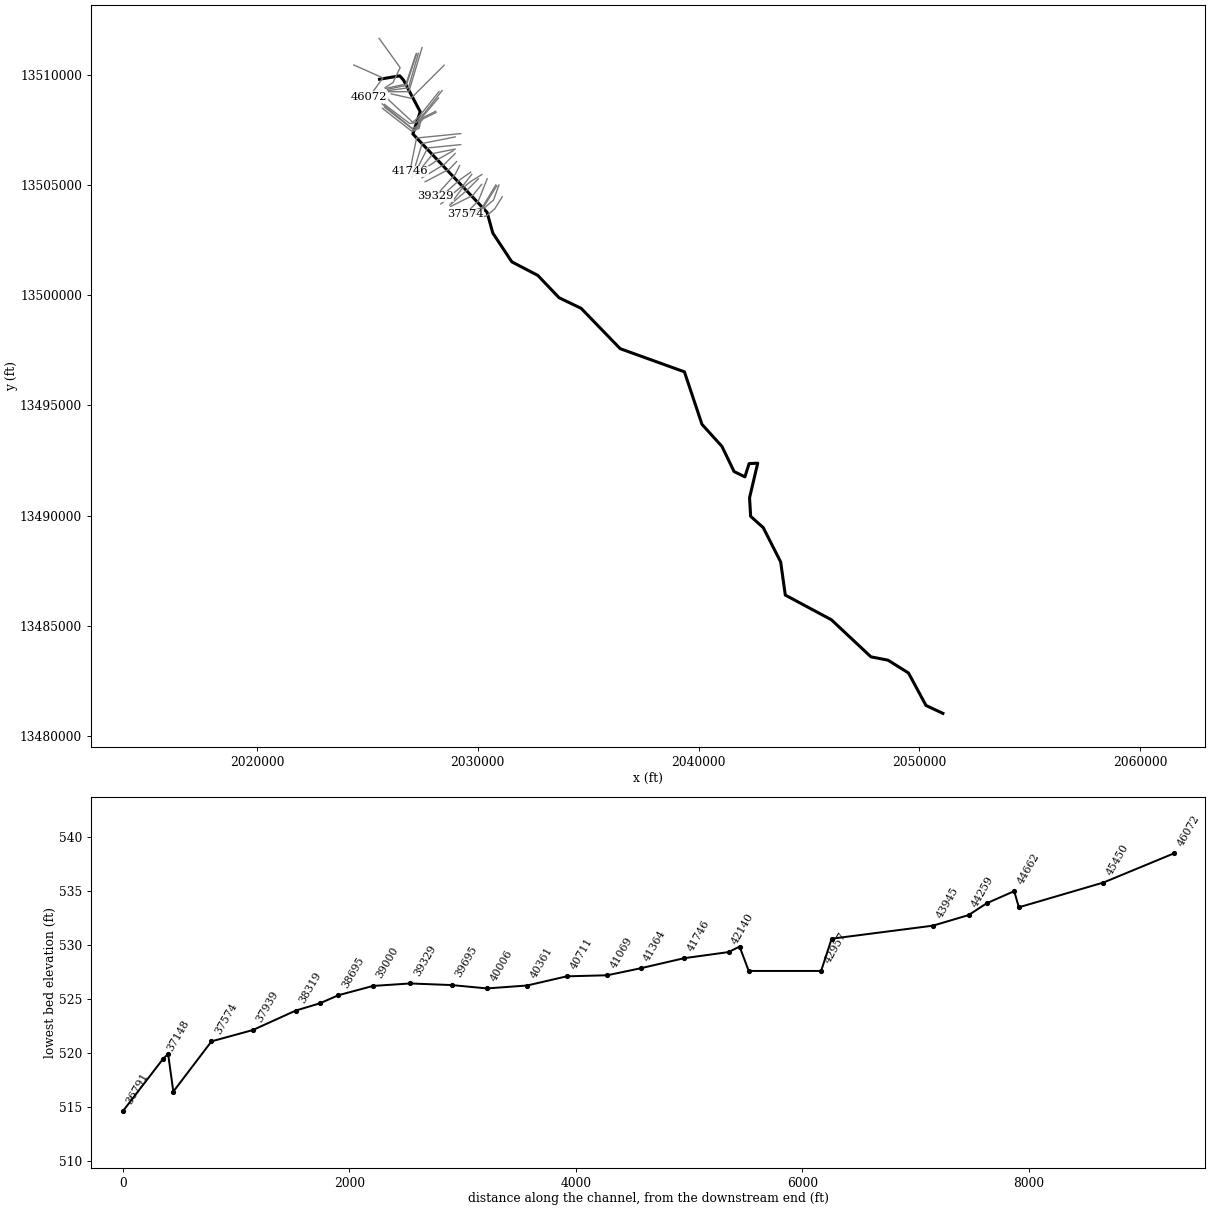
--- CHILTIPIN CREEK.prj (project) ---

Proj Title=CHILTIPIN CREEK Base Level Engineering
Current Plan=p01
Default Exp/Contr=0.3,0.1
English Units
Geom File=g01
Flow File=f01
Plan File=p01
Y Axis Title=Elevation
X Axis Title(PF)=Main Channel Distance
X Axis Title(XS)=Station
BEGIN DESCRIPTION:
CHILTIPIN CREEK
END DESCRIPTION:
DSS Export Rating Curves= 0
DSS Export Rating Curve Sorted= 0
DSS Export Volume Flow Curves= 0
DXF OffsetX= 0
DXF OffsetY= 0
DXF ScaleX= 1
DXF ScaleY= 10

--- CHILTIPIN CREEK.p01 (plan) ---

Plan Title=Multiple Run
Short Identifier=Multiple
Geom File=g01
Flow File=f01
Subcritical Flow
K Sum by GR= 0
Std Step Tol= 0.01
Critical Tol= 0.01
Num of Std Step Trials= 20
Max Error Tol= 0.3
Flow Tol Ratio= 0.001
Split Flow NTrial= 30
Split Flow Tol= 0.02
Split Flow Ratio= 0.02
Log Output Level= 0
Friction Slope Method= 1
Unsteady Friction Slope Method= 2
Unsteady Bridges Friction Slope Method= 1
Parabolic Critical Depth
Global Vel Dist=  1 , 1 , 1
Global Log Level= 0
CheckData=True
Encroach Param= -1, 0, 0, 0
BEGIN DESCRIPTION:
Multiple Run
END DESCRIPTION:

--- CHILTIPIN CREEK.f01 (steady flow) ---

Flow Title=Multiple
Program Version=5.05
Number of Profiles= 7
Profile Names=10-year,25-year,50-year,1pct_min,100-year,1pct_plu,500-year
River Rch & RM=CHILTIPIN CREEK,Reach-1         ,46072
     180     246     300     183     364     727     546
River Rch & RM=CHILTIPIN CREEK,Reach-1         ,45450
     273     381     472     291     581    1159     894
River Rch & RM=CHILTIPIN CREEK,Reach-1         ,43050
     308     433     537     332     663    1323    1026
River Rch & RM=CHILTIPIN CREEK,Reach-1         ,41746
     334     470     584     362     722    1441    1121
River Rch & RM=CHILTIPIN CREEK,Reach-1         ,40361
     408     577     721     448     894    1784    1396
River Rch & RM=CHILTIPIN CREEK,Reach-1         ,35822
     459     654     820     511    1020    2035    1605
River Rch & RM=CHILTIPIN CREEK,Reach-1         ,35530
     604     870    1099     690    1376    2746    2193
River Rch & RM=CHILTIPIN CREEK,Reach-1         ,31839
     637     919    1161     729    1455    2904    2323
River Rch & RM=CHILTIPIN CREEK,Reach-1         ,30368
     717    1038    1315     828    1652    3295    2647
River Rch & RM=CHILTIPIN CREEK,Reach-1         ,24846
     781    1133    1437     906    1807    3606    2902
River Rch & RM=CHILTIPIN CREEK,Reach-1         ,19946
     802    1162    1473     927    1850    3691    2965
River Rch & RM=CHILTIPIN CREEK,Reach-1         ,10181
     871    1267    1611    1017    2028    4047    3268
River Rch & RM=CHILTIPIN CREEK,Reach-1         ,9163
    1489    2205    2836    1809    3609    7200    5936
Boundary for River Rch & Prof#=CHILTIPIN CREEK,Reach-1         , 1
Up Type= 0
Dn Type= 3
Dn Slope=0.00222
Boundary for River Rch & Prof#=CHILTIPIN CREEK,Reach-1         , 2
Up Type= 0
Dn Type= 3
Dn Slope=0.00222
Boundary for River Rch & Prof#=CHILTIPIN CREEK,Reach-1         , 3
Up Type= 0
Dn Type= 3
Dn Slope=0.00222
Boundary for River Rch & Prof#=CHILTIPIN CREEK,Reach-1         , 4
Up Type= 0
Dn Type= 3
Dn Slope=0.00222
Boundary for River Rch & Prof#=CHILTIPIN CREEK,Reach-1         , 5
Up Type= 0
Dn Type= 3
Dn Slope=0.00222
Boundary for River Rch & Prof#=CHILTIPIN CREEK,Reach-1         , 6
Up Type= 0
Dn Type= 3
Dn Slope=0.00222
Boundary for River Rch & Prof#=CHILTIPIN CREEK,Reach-1         , 7
Up Type= 0
Dn Type= 3
Dn Slope=0.00222
DSS Import GetInterval= 0
DSS Import GetPeak= 0
DSS Import FillOption= 0

--- CHILTIPIN CREEK.g01 (geometry) ---

Geom Title=Existing Conditions
Program Version=5.05

River Reach=CHILTIPIN CREEK ,Reach-1
Reach XY= 30
      2025547.85     13509787.87       2026460.8     13509944.54
       2026630.8     13509754.54      2027390.18     13508315.15
      2027059.18     13507309.24      2030418.91     13503756.43
       2030680.8     13502814.54      2031541.31     13501511.11
       2032720.8     13500894.54       2033680.8     13499884.54
       2034680.8     13499404.54       2036450.8     13497574.54
       2039360.8     13496524.54      2040155.49     13494144.82
       2041060.8     13493144.54       2041610.8     13492004.54
       2042100.8     13491764.54       2042290.8     13492364.54
       2042680.8     13492384.54       2042310.8     13490814.54
       2042360.8     13489974.54      2042932.33     13489462.19
       2043720.8     13487904.54       2043930.8     13486404.54
       2046020.8     13485284.54       2047810.8     13483604.54
       2048580.8     13483454.54       2049510.8     13482874.54
      2050305.33     13481400.15       2051070.8     13481042.07

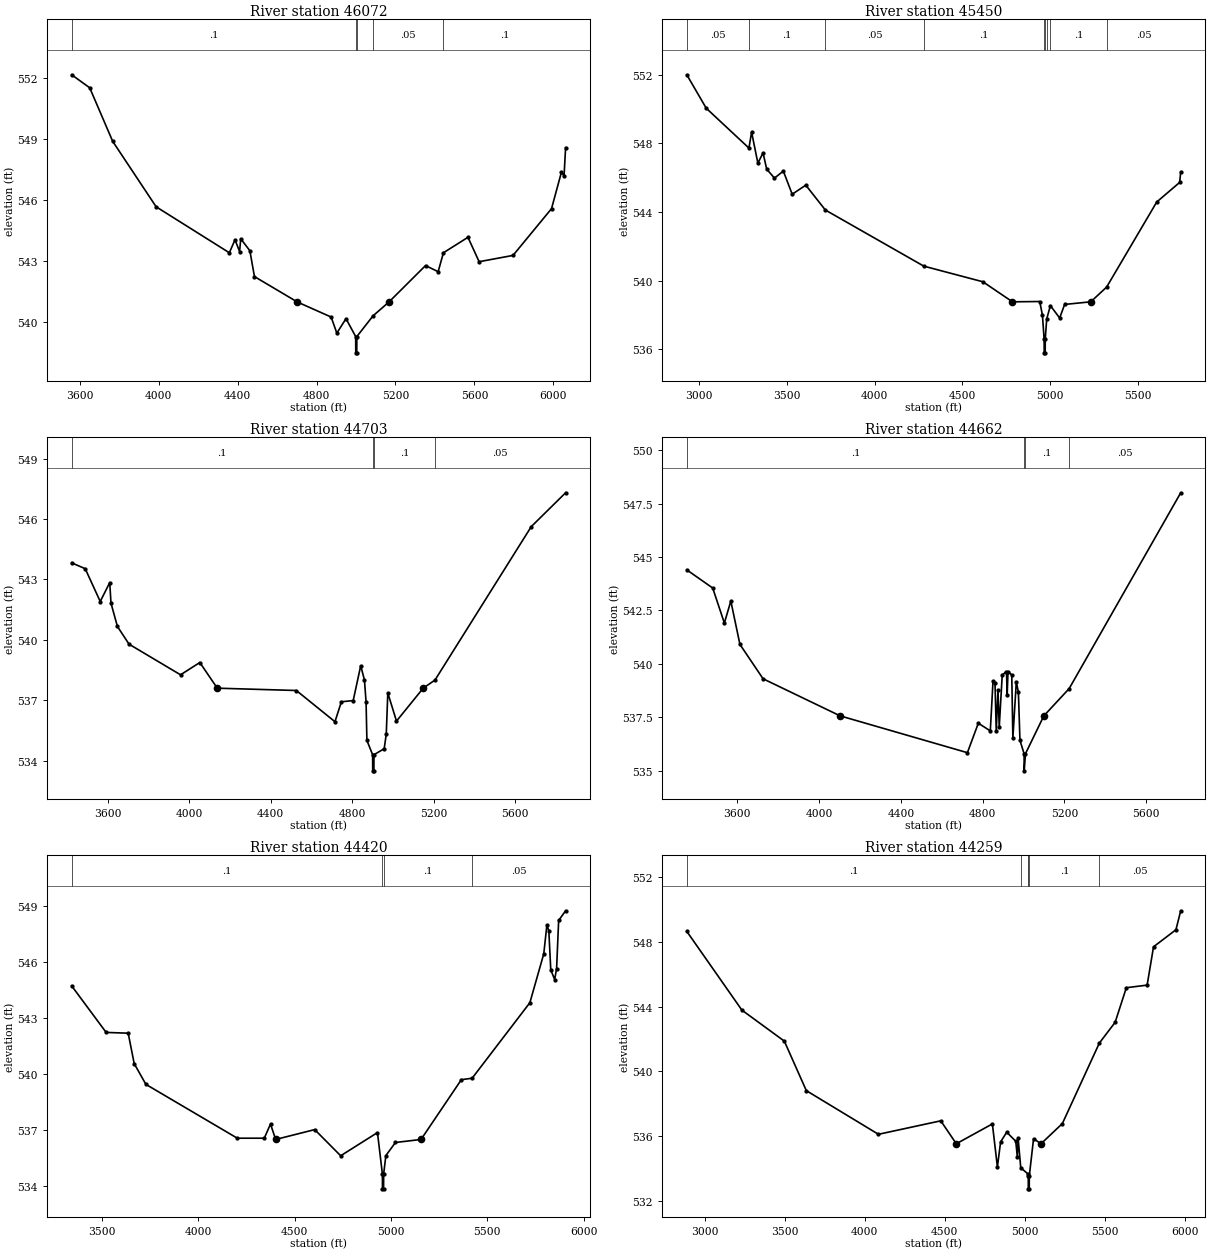
Type RM Length L Ch R = 1 ,46072   ,622,622,622
BEGIN DESCRIPTION:
CHILTIPIN CREEK 111.0
END DESCRIPTION:
XS GIS Cut Line= 3
      2024382.08     13510435.15        2025700.       13509850.
        2025081.     13508988.63
#Sta/Elev= 30
  3559.2  552.16  3650.6  551.52  3766.9  548.89  3987.2  545.67  4358.1  543.41
  4386.8  544.05  4410.1  543.47  4415.8   544.1  4462.1  543.51  4485.3  542.24
 4702.79540.9885  4873.9  540.25  4902.7  539.46  4949.2  540.17  4998.2  539.29
  4998.7  538.49  5003.7  538.49  5004.2  539.29  5086.3  540.31 5166.73540.9884
  5352.1  542.78  5416.2  542.48  5442.8  543.41  5567.2  544.17  5623.7  542.97
  5795.5  543.28  5990.7  545.58    6041  547.38  6054.1  547.19  6061.9  548.58
#Mann= 5 ,-1 , 0
  3559.2      .1       0  4998.2     .07       0  5004.2      .1       0
  5086.3     .05       0  5442.8      .1       0
Bank Sta=4702.79,5166.73
XS Rating Curve= 0 ,0
Exp/Cntr=0.3,0.1

Type RM Length L Ch R = 1 ,45450   ,747,747,747
BEGIN DESCRIPTION:
CHILTIPIN CREEK 110.0
END DESCRIPTION:
XS GIS Cut Line= 4
      2025527.93     13511643.46      2026481.04     13510315.36
      2026158.12     13509638.28      2025800.08     13509409.96
#Sta/Elev= 30
  2932.3  551.99    3043  550.04  3285.8  547.72  3300.9  548.65  3336.6  546.84
    3366  547.44  3386.9  546.49  3431.1  545.97  3481.4  546.38  3531.8  545.03
  3609.1  545.56  3720.5  544.11  4280.7  540.84  4616.6  539.93 4784.65538.7629
  4939.8  538.78  4955.2  537.99  4964.8  536.59  4965.3  535.79  4970.8  535.79
  4971.3  536.59  4979.5  537.76  5000.4  538.54  5053.3  537.82  5081.5  538.61
 5230.16538.7629  5320.3  539.62  5605.5  544.58  5735.9  545.72  5741.8  546.34
#Mann= 9 ,-1 , 0
  2932.3     .05       0  3285.8      .1       0  3720.5     .05       0
  4280.7      .1       0  4964.8     .07       0  4971.3      .1       0
  4979.5     .12       0  5000.4      .1       0  5320.3     .05       0
Bank Sta=4784.65,5230.16
XS Rating Curve= 0 ,0
Exp/Cntr=0.3,0.1

Type RM Length L Ch R = 1 ,44703   ,41,41,41
BEGIN DESCRIPTION:
CHILTIPIN CREEK 109.0
END DESCRIPTION:
XS GIS Cut Line= 6
      2027199.06     13510927.93        2026739.     13509552.09
       2026717.3     13509504.34      2026682.57     13509526.04
      2026578.41     13509534.72      2025819.43     13509374.25
#Sta/Elev= 30
    3424  543.82  3490.4  543.53  3564.2   541.9  3610.9  542.84  3616.9  541.82
  3648.5  540.66  3705.7  539.78  3958.3  538.26  4053.1  538.87 4138.64537.5956
  4526.8  537.48  4716.3  535.93  4747.9  536.92  4805.8  536.98  4842.7  538.71
  4861.1     538    4869  536.91  4873.1     535  4901.2  534.29  4901.7  533.49
  4907.3  533.49  4907.8  534.29    4958  534.59  4968.1  535.31  4975.7  537.36
  5018.3  535.96 5149.48537.5955  5207.4     538  5679.9  545.62  5848.4   547.3
#Mann= 4 ,-1 , 0
    3424      .1       0  4901.2     .07       0  4907.8      .1       0
  5207.4     .05       0
Bank Sta=4138.64,5149.48
XS Rating Curve= 0 ,0
Exp/Cntr=0.3,0.1

Type RM Length L Ch R = 1 ,44662   ,242,242,242
BEGIN DESCRIPTION:
CHILTIPIN CREEK 108.0
END DESCRIPTION:
XS GIS Cut Line= 6
      2027229.46      13510949.7      2026765.04      13509521.7
      2026725.98     13509469.62      2026673.89     13509491.32
      2026600.11      13509478.3      2025898.47     13509331.04
#Sta/Elev= 30
  3353.4   544.4  3480.1  543.55  3537.1  541.91  3568.7  542.94  3613.2  540.91
  3726.4   539.3  4103.5537.5627  4725.4  535.84  4778.8  537.22  4837.4  536.86
  4850.7   539.2  4860.3  539.11  4866.5  536.86  4874.9  538.78  4881.1  537.04
  4895.7  539.48  4916.5  539.64  4919.9  538.56  4923.9  539.64  4942.3  539.48
  4947.7  536.52  4964.5  539.16  4974.8  538.66  4982.3  536.42  5002.6  535.79
  5003.1  534.99  5009.2  535.79    5099537.5627  5222.9  538.84  5768.4  548.01
#Mann= 4 ,-1 , 0
  3353.4      .1       0  5002.6     .07       0  5009.2      .1       0
  5222.9     .05       0
Bank Sta=4103.5,5099
XS Rating Curve= 0 ,0
Exp/Cntr=0.3,0.1

Type RM Length L Ch R = 1 ,44420   ,161,161,161
BEGIN DESCRIPTION:
CHILTIPIN CREEK 107.0
END DESCRIPTION:
XS GIS Cut Line= 5
      2027307.56     13510966.98       2026869.2     13509443.58
       2026825.8     13509382.81      2026656.53     13509374.13
      2025928.71     13509274.49
#Sta/Elev= 30
  3342.6  544.73  3521.6  542.24    3636   542.2  3667.2  540.57    3728  539.46
  4202.4  536.58  4342.4  536.58  4374.8  537.34 4401.41536.5126  4604.2  537.04
    4739  535.64    4930  536.88  4955.5  534.67    4956  533.87  4961.7  533.87
  4962.2  534.67  4973.6  535.65  5023.3  536.35 5156.13536.5126  5365.3  539.71
  5421.4  539.79  5721.1  543.83  5793.3  546.45  5809.4  547.98  5819.5  547.69
  5829.6  545.59  5849.8  545.07  5859.9  545.66  5870.5  548.23  5906.6  548.75
#Mann= 4 ,-1 , 0
  3342.6      .1       0  4955.5     .07       0  4962.2      .1       0
  5421.4     .05       0
Bank Sta=4401.41,5156.13
XS Rating Curve= 0 ,0
Exp/Cntr=0.3,0.1

Type RM Length L Ch R = 1 ,44259   ,314,314,314
BEGIN DESCRIPTION:
CHILTIPIN CREEK 106.0
END DESCRIPTION:
XS GIS Cut Line= 3
      2027474.99     13511224.96        2026875.       13509225.
      2025875.02       13509225.
#Sta/Elev= 30
  2886.7  548.63  3231.2  543.78  3496.5  541.87    3634  538.82  4084.7  536.13
  4474.5  536.96 4571.71535.5471  4797.2  536.77  4828.6  534.12  4848.6  535.66
  4886.9  536.26  4943.4   535.7    4953  534.76  4958.2  535.88  4974.6  534.07
  5018.1   533.7  5021.4  533.57  5021.9  532.77  5027.6  532.77  5028.1  533.57
  5054.7  535.86 5101.25535.5471  5234.7  536.79    5466  541.75  5564.7  543.03
  5634.7  545.16  5764.7  545.32  5804.7  547.68  5944.7  548.73  5974.7   549.9
#Mann= 6 ,-1 , 0
  2886.7      .1       0  4974.6     .05       0  5018.1      .1       0
  5021.4     .03       0  5028.1      .1       0    5466     .05       0
Bank Sta=4571.71,5101.25
XS Rating Curve= 0 ,0
Exp/Cntr=0.3,0.1

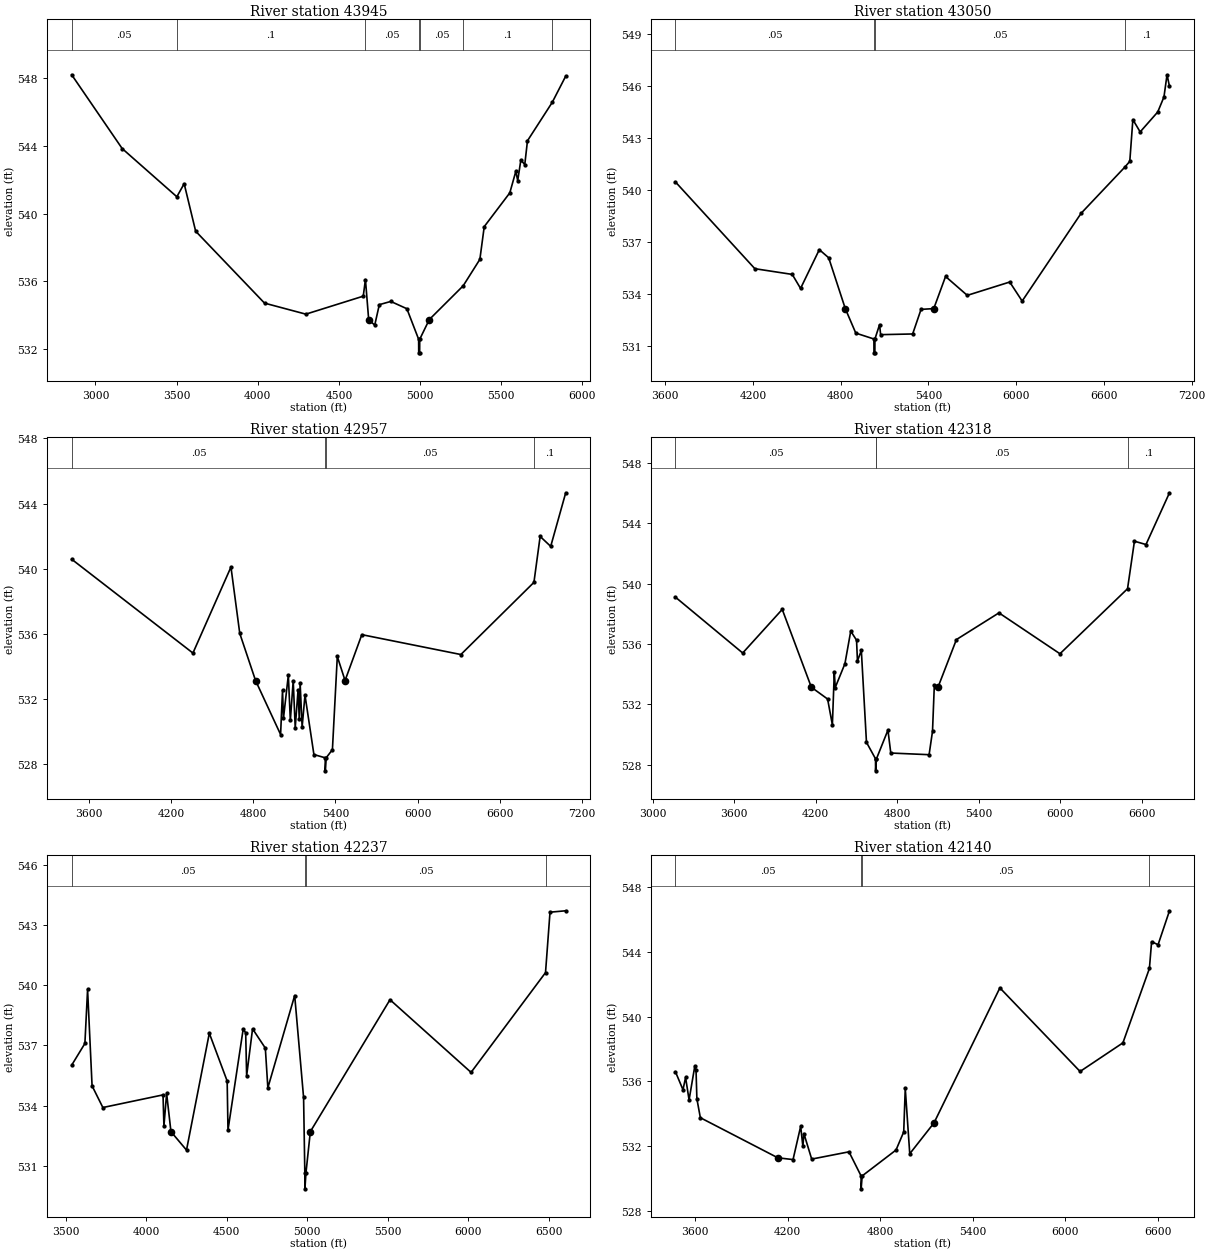
Type RM Length L Ch R = 1 ,43945   ,895,895,895
BEGIN DESCRIPTION:
CHILTIPIN CREEK 105.0
END DESCRIPTION:
XS GIS Cut Line= 3
      2028474.98     13510424.98        2026975.       13508925.
      2026075.05     13509124.99
#Sta/Elev= 30
  2853.5  548.18  3164.6  543.83  3501.3  540.99  3546.4  541.76  3617.1  538.96
  4041.4  534.72    4296  534.07  4649.5  535.13    4663  536.11 4682.94533.7528
  4720.2  533.42  4748.5  534.63  4819.2  534.82  4918.2  534.39  4990.7  532.59
  4991.2  531.79  4996.9  531.79  4997.4  532.59 5056.43533.7527    5265  535.74
  5367.9   537.3  5394.8  539.23  5552.3  541.22  5589.4  542.49    5601  541.94
  5620.2  543.15  5644.5  542.89  5661.1  544.29  5813.4  546.55  5896.7   548.1
#Mann= 7 ,-1 , 0
  2853.5     .05       0  3501.3      .1       0    4663     .05       0
  4990.7    .035       0  4997.4     .05       0    5265      .1       0
  5813.4     .05       0
Bank Sta=4682.94,5056.43
XS Rating Curve= 0 ,0
Exp/Cntr=0.3,0.1

Type RM Length L Ch R = 1 ,43050   ,93,93,93
BEGIN DESCRIPTION:
CHILTIPIN CREEK 104.0
END DESCRIPTION:
XS GIS Cut Line= 6
      2028240.72     13509230.89      2027546.29     13508354.17
      2027394.38     13508171.88      2027216.43      13507980.9
      2027047.16     13507842.02      2025918.65     13508892.39
#Sta/Elev= 30
  3670.6  540.45  4213.4  535.44    4469  535.11  4525.9   534.3  4654.1  536.54
  4718.2  536.07 4831.63533.1355  4903.4  531.72  5027.3  531.38  5027.8  530.58
  5033.8  530.58  5034.3  531.38    5066  532.21  5073.3  531.63  5292.2  531.67
  5349.6  533.09 5436.49533.1354  5517.1  534.99  5665.6   533.9  5955.8  534.67
  6040.8  533.57  6443.9  538.64  6741.9   541.3  6776.6  541.64  6797.6  544.05
  6847.5  543.34  6967.6  544.49  7010.2  545.36  7031.2  546.64    7048  545.97
#Mann= 4 ,-1 , 0
  3670.6     .05       0  5027.3    .035       0  5034.3     .05       0
  6741.9      .1       0
Bank Sta=4831.63,5436.49
XS Rating Curve= 0 ,0
Exp/Cntr=0.3,0.1

Type RM Length L Ch R = 1 ,42957   ,639,639,639
BEGIN DESCRIPTION:
CHILTIPIN CREEK 103.0
END DESCRIPTION:
XS GIS Cut Line= 6
      2028383.93     13509278.61      2027576.67     13508245.66
      2027381.36     13508063.37      2027216.43     13507833.34
      2026916.95     13507781.25      2025766.81     13508649.28
#Sta/Elev= 30
  3475.4  540.58  4360.4  534.82    4638   540.1  4702.2  536.03 4817.52533.1343
  5000.3  529.82  5014.4  532.54  5021.3  530.82  5056.8  533.46  5071.5  530.69
  5092.4  533.12  5107.1  530.24    5128  532.56  5136.6  530.76  5142.8     533
  5157.5  530.28  5178.4  532.24  5243.5  528.59  5325.9  528.39  5326.4  527.59
    5333  528.39  5378.6  528.89  5414.3  534.61 5470.86 533.134  5593.2  535.95
  6316.2  534.73  6849.5  539.16  6894.8  541.98  6971.9  541.37  7081.5  544.66
#Mann= 4 ,-1 , 0
  3475.4     .05       0  5325.9    .035       0    5333     .05       0
  6849.5      .1       0
Bank Sta=4817.52,5470.86
XS Rating Curve= 0 ,0
Exp/Cntr=0.3,0.1

Type RM Length L Ch R = 1 ,42318   ,81,81,81
BEGIN DESCRIPTION:
CHILTIPIN CREEK 102.0
END DESCRIPTION:
XS GIS Cut Line= 6
      2028218.47     13508939.44      2027319.15     13507883.87
      2027315.68     13507713.73      2027142.07      13507592.2
      2027003.18     13507578.31      2025667.57     13508671.05
#Sta/Elev= 30
  3168.5   539.1  3663.3   535.4  3954.3  538.29 4168.55533.1308  4288.1  532.35
  4323.2  530.64  4337.5  534.15  4344.1  533.11  4415.5  534.69  4458.3  536.85
  4501.1  536.25  4507.7  534.87  4536.3  535.57  4574.1  529.48  4640.6  528.39
  4641.1  527.59  4647.7  528.39  4732.1  530.29    4753  528.77  5034.9  528.66
    5060  530.21  5073.5  533.29 5100.34533.1307  5235.9  536.29    5549  538.06
  5997.8  535.35  6495.1  539.66  6545.9  542.81  6630.8  542.59  6803.8  546.02
#Mann= 4 ,-1 , 0
  3168.5     .05       0  4640.6     .03       0  4647.7     .05       0
  6495.1      .1       0
Bank Sta=4168.55,5100.34
XS Rating Curve= 0 ,0
Exp/Cntr=0.3,0.1

Type RM Length L Ch R = 1 ,42237   ,97,97,97
BEGIN DESCRIPTION:
CHILTIPIN CREEK 101.0
END DESCRIPTION:
XS GIS Cut Line= 6
      2028086.52     13508335.26      2027499.71     13508040.12
      2027357.35     13507887.34      2027294.85     13507613.04
      2027089.99     13507494.98      2025768.53     13508525.04
#Sta/Elev= 30
  3537.5  536.01  3619.6  537.09  3636.3  539.78  3664.2  534.98  3731.2   533.9
    4105  534.53  4110.6  532.98  4127.4   534.6 4154.26 532.699  4250.9  531.78
  4392.6   537.6  4503.5  535.22  4508.6  532.78  4603.1  537.81  4618.6  537.62
  4624.5  535.48  4661.3  537.82  4740.6  536.86  4756.3  534.88    4923  539.48
  4978.3   534.4    4986  530.65  4986.6  529.85  4993.1  530.65 5020.25532.6992
  5515.2  539.27  6018.8  535.65  6481.4  540.62  6509.3  543.63  6606.9   543.7
#Mann= 4 ,-1 , 0
  3537.5     .05       0    4986     .03       0  4993.1     .05       0
  6481.4      .1       0
Bank Sta=4154.26,5020.25
XS Rating Curve= 0 ,0
Exp/Cntr=0.3,0.1

Type RM Length L Ch R = 1 ,42140   ,394,394,394
BEGIN DESCRIPTION:
CHILTIPIN CREEK 100.0
END DESCRIPTION:
XS GIS Cut Line= 6
      2028107.32     13508279.69      2027524.02     13507994.98
      2027402.49     13507849.15      2027343.46     13507564.42
      2027024.02     13507418.59      2025683.74      13508467.2
#Sta/Elev= 30
  3472.6  536.58  3521.4  535.47  3538.3  536.23  3560.9  534.84  3597.6  536.91
  3605.9  536.72  3611.5  534.91    3634  533.74 4136.38531.2593  4234.8  531.15
  4284.3  533.21  4298.6  531.96  4305.1  532.76  4355.7  531.18  4597.4  531.63
  4675.8  530.14  4676.3  529.34  4682.9  530.14  4902.2  531.74  4952.2  532.86
  4962.2  535.55  4991.3  531.51  5148.6  533.42  5575.5  541.77  6095.4   536.6
    6373  538.37  6544.7  542.97    6559  544.63  6600.9  544.44  6674.9  546.54
#Mann= 4 ,-1 , 0
  3472.6     .05       0  4675.8     .03       0  4682.9     .05       0
  6544.7      .1       0
Bank Sta=4136.38,5148.6
XS Rating Curve= 0 ,0
Exp/Cntr=0.3,0.1

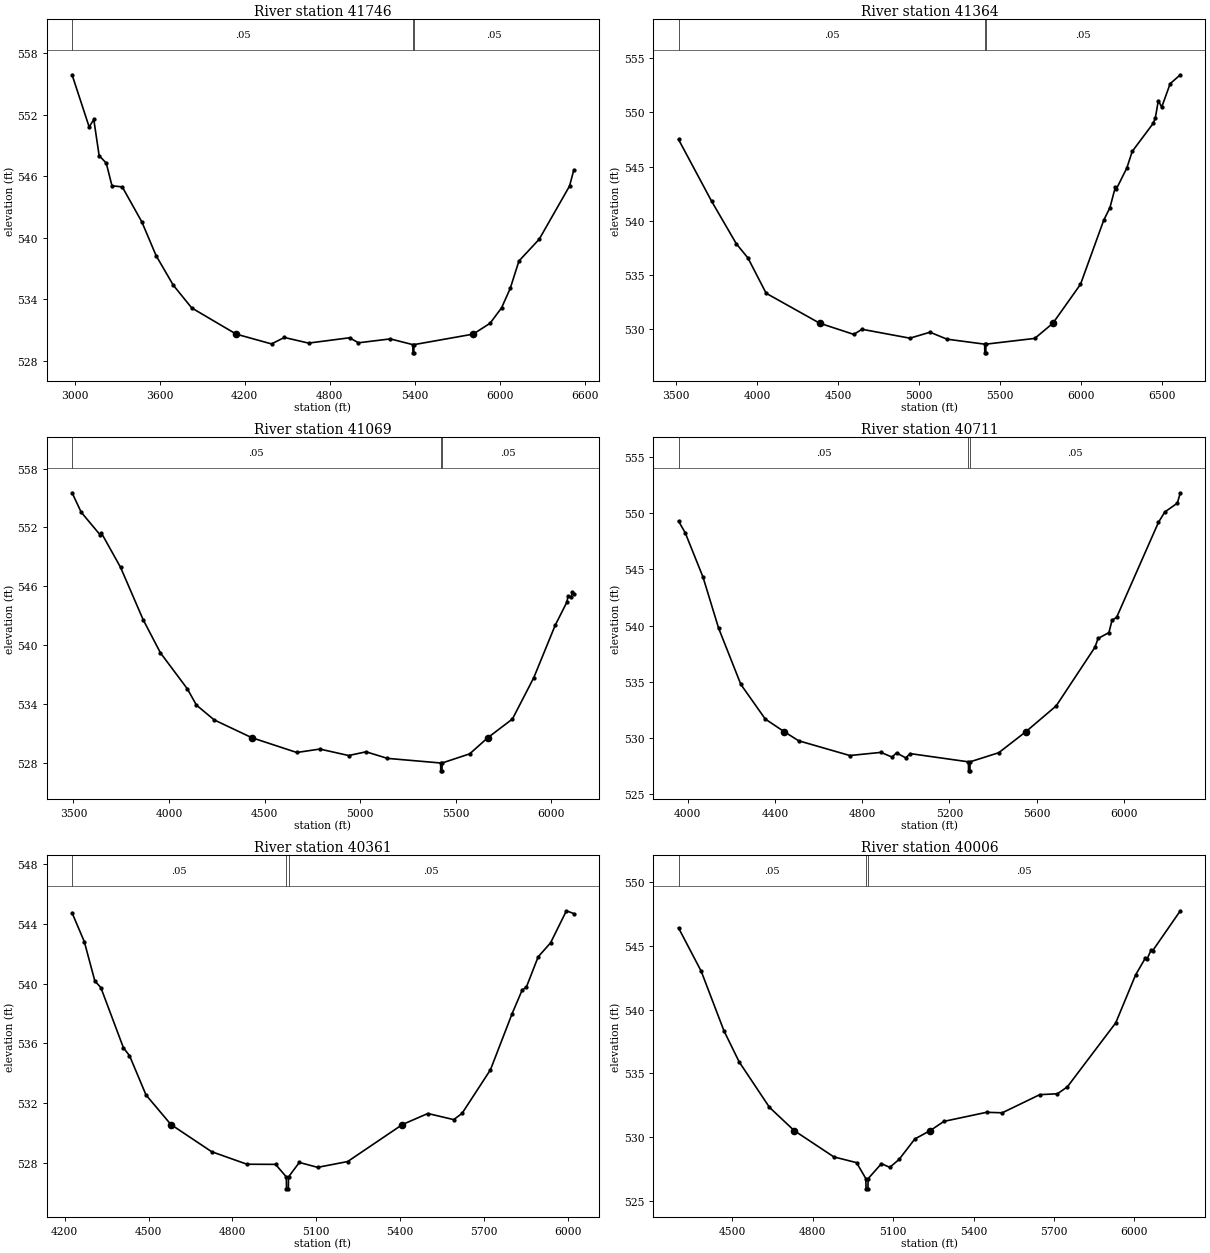
Type RM Length L Ch R = 1 ,41746   ,382,382,382
BEGIN DESCRIPTION:
CHILTIPIN CREEK 99.0
END DESCRIPTION:
XS GIS Cut Line= 3
      2029224.96       13507325.        2027225.       13507125.
      2026925.01     13505625.04
#Sta/Elev= 30
  2982.7   555.9  3103.3  550.81  3135.9  551.54  3173.6  548.02  3223.9  547.28
  3264.1  545.07  3336.9  544.96  3475.1  541.54  3575.6  538.25  3696.2  535.38
  3826.8  533.15 4140.34530.5967  4389.6  529.64  4480.1  530.27  4650.9  529.72
  4939.9  530.24  5002.8  529.75  5227.2  530.13  5386.6  529.57  5387.2  528.77
  5393.5  528.77  5394.1  529.57 5811.91530.5967  5930.9  531.65  6012.4  533.16
  6073.6  535.06  6134.8  537.73  6277.6  539.85  6491.7  545.04  6522.3  546.63
#Mann= 3 ,-1 , 0
  2982.7     .05       0  5386.6    .035       0  5394.1     .05       0
Bank Sta=4140.34,5811.91
XS Rating Curve= 0 ,0
Exp/Cntr=0.3,0.1

Type RM Length L Ch R = 1 ,41364   ,295,295,295
BEGIN DESCRIPTION:
CHILTIPIN CREEK 98.0
END DESCRIPTION:
XS GIS Cut Line= 3
        2028975.       13507175.        2027475.       13506875.
      2027024.99     13505374.95
#Sta/Elev= 30
  3515.8   547.5  3719.8  541.81  3872.7  537.88  3944.1  536.58  4056.3  533.33
 4386.38530.5718  4596.8  529.54  4647.8  530.01  4943.5  529.19  5067.3  529.74
  5171.7   529.1  5404.6  528.64  5405.2  527.84  5411.5  527.84  5412.1  528.64
  5713.7  529.17 5825.61530.5717  5995.6  534.15  6139.1  540.06  6177.4  541.22
  6210.5   543.1  6215.7   542.9  6281.8  544.88  6314.9   546.4  6444.5  548.99
  6457.6   549.5  6475.8  551.08  6496.7  550.48  6548.9  552.64  6611.6  553.46
#Mann= 3 ,-1 , 0
  3515.8     .05       0  5404.6    .035       0  5412.1     .05       0
Bank Sta=4386.38,5825.61
XS Rating Curve= 0 ,0
Exp/Cntr=0.3,0.1

Type RM Length L Ch R = 1 ,41069   ,358,358,358
BEGIN DESCRIPTION:
CHILTIPIN CREEK 97.0
END DESCRIPTION:
XS GIS Cut Line= 3
      2029224.97       13506825.        2027725.       13506675.
      2027224.99     13505674.98
#Sta/Elev= 30
  3492.6  555.53  3540.3  553.55  3640.8  551.21  3645.8  551.44  3746.3  547.93
  3864.4   542.6  3954.9  539.22  4095.6  535.55  4143.3  533.89  4236.3  532.38
 4433.43530.5651  4668.4  529.06    4789  529.41  4939.7  528.75  5030.8  529.13
  5142.6  528.46  5421.2  527.99  5421.7  527.19  5428.1  527.19  5428.7  527.99
    5573  528.92 5667.72 530.565  5796.6  532.47  5908.5  536.69  6020.3  542.02
  6081.7  544.39  6087.3  544.98  6104.1  544.86  6109.7  545.43  6118.1  545.26
#Mann= 3 ,-1 , 0
  3492.6     .05       0  5421.2    .035       0  5428.7     .05       0
Bank Sta=4433.43,5667.72
XS Rating Curve= 0 ,0
Exp/Cntr=0.3,0.1

Type RM Length L Ch R = 1 ,40711   ,350,350,350
BEGIN DESCRIPTION:
CHILTIPIN CREEK 96.0
END DESCRIPTION:
XS GIS Cut Line= 3
      2028975.02       13506625.        2027975.       13506425.
      2027174.97     13505424.96
#Sta/Elev= 30
  3957.9  549.27  3988.5  548.24  4070.1   544.3  4141.5  539.77  4243.5  534.77
  4355.6  531.69 4443.12530.5594  4508.6  529.76  4743.2  528.45  4885.9  528.73
  4936.9  528.31  4957.3  528.69  4999.3  528.24  5020.1  528.62  5286.9  527.89
  5287.5  527.09  5293.9  527.09  5294.4  527.89  5425.9   528.7 5549.81530.5594
  5689.3  532.86    5867  538.07  5881.4  538.85    5931  539.37  5945.4  540.47
  5966.2  540.72  6158.3  549.17  6187.1  550.08  6244.7  550.87  6258.4  551.79
#Mann= 3 ,-1 , 0
  3957.9     .05       0  5286.9    .035       0  5294.4     .05       0
Bank Sta=4443.12,5549.81
XS Rating Curve= 0 ,0
Exp/Cntr=0.3,0.1

Type RM Length L Ch R = 1 ,40361   ,355,355,355
BEGIN DESCRIPTION:
CHILTIPIN CREEK 95.0
END DESCRIPTION:
XS GIS Cut Line= 4
      2028889.76     13506550.65        2028225.       13506175.
      2028178.86     13506133.13      2027379.67     13505583.86
#Sta/Elev= 30
  4226.2  544.74    4270  542.81  4307.6  540.18  4329.2  539.73  4410.1  535.69
  4431.7  535.17  4490.9  532.53 4579.91530.5522  4725.6  528.73  4851.9  527.89
  4954.4  527.88  4992.9  527.04  4993.5  526.24  5000.1  526.24  5000.8  527.04
  5039.4  528.01  5104.9  527.68  5212.4  528.07 5408.46530.5522  5499.3  531.29
    5592  530.88  5621.8   531.3  5723.3  534.22    5801  537.99  5836.9  539.57
  5851.8  539.76    5894  541.79  5938.4  542.73  5995.2  544.88  6021.8  544.69
#Mann= 3 ,-1 , 0
  4226.2     .05       0  4992.9    .035       0  5000.8     .05       0
Bank Sta=4579.91,5408.46
XS Rating Curve= 0 ,0
Exp/Cntr=0.3,0.1

Type RM Length L Ch R = 1 ,40006   ,311,311,311
BEGIN DESCRIPTION:
CHILTIPIN CREEK 94.0
END DESCRIPTION:
XS GIS Cut Line= 3
      2028974.98     13506424.98        2028475.       13505925.
      2027474.97     13505324.98
#Sta/Elev= 30
  4298.7  546.39  4383.5  542.99  4468.4  538.33  4524.9  535.91  4638.1  532.35
 4730.08530.5338  4878.5  528.47  4963.3  528.02    4998  526.77  4998.7  525.97
  5005.7  525.97  5006.5  526.77  5056.3  527.94  5087.4  527.65  5122.4  528.28
  5180.7  529.87  5238.7530.5338  5289.5  531.25  5448.9  531.96  5507.2  531.92
  5647.2  533.34  5713.3  533.41  5750.2  533.95  5930.9  538.96  6004.8   542.7
  6041.7  544.04  6047.6  543.95  6063.1  544.66  6068.9  544.61    6172  547.73
#Mann= 3 ,-1 , 0
  4298.7     .05       0    4998    .035       0  5006.5     .05       0
Bank Sta=4730.08,5238.7
XS Rating Curve= 0 ,0
Exp/Cntr=0.3,0.1

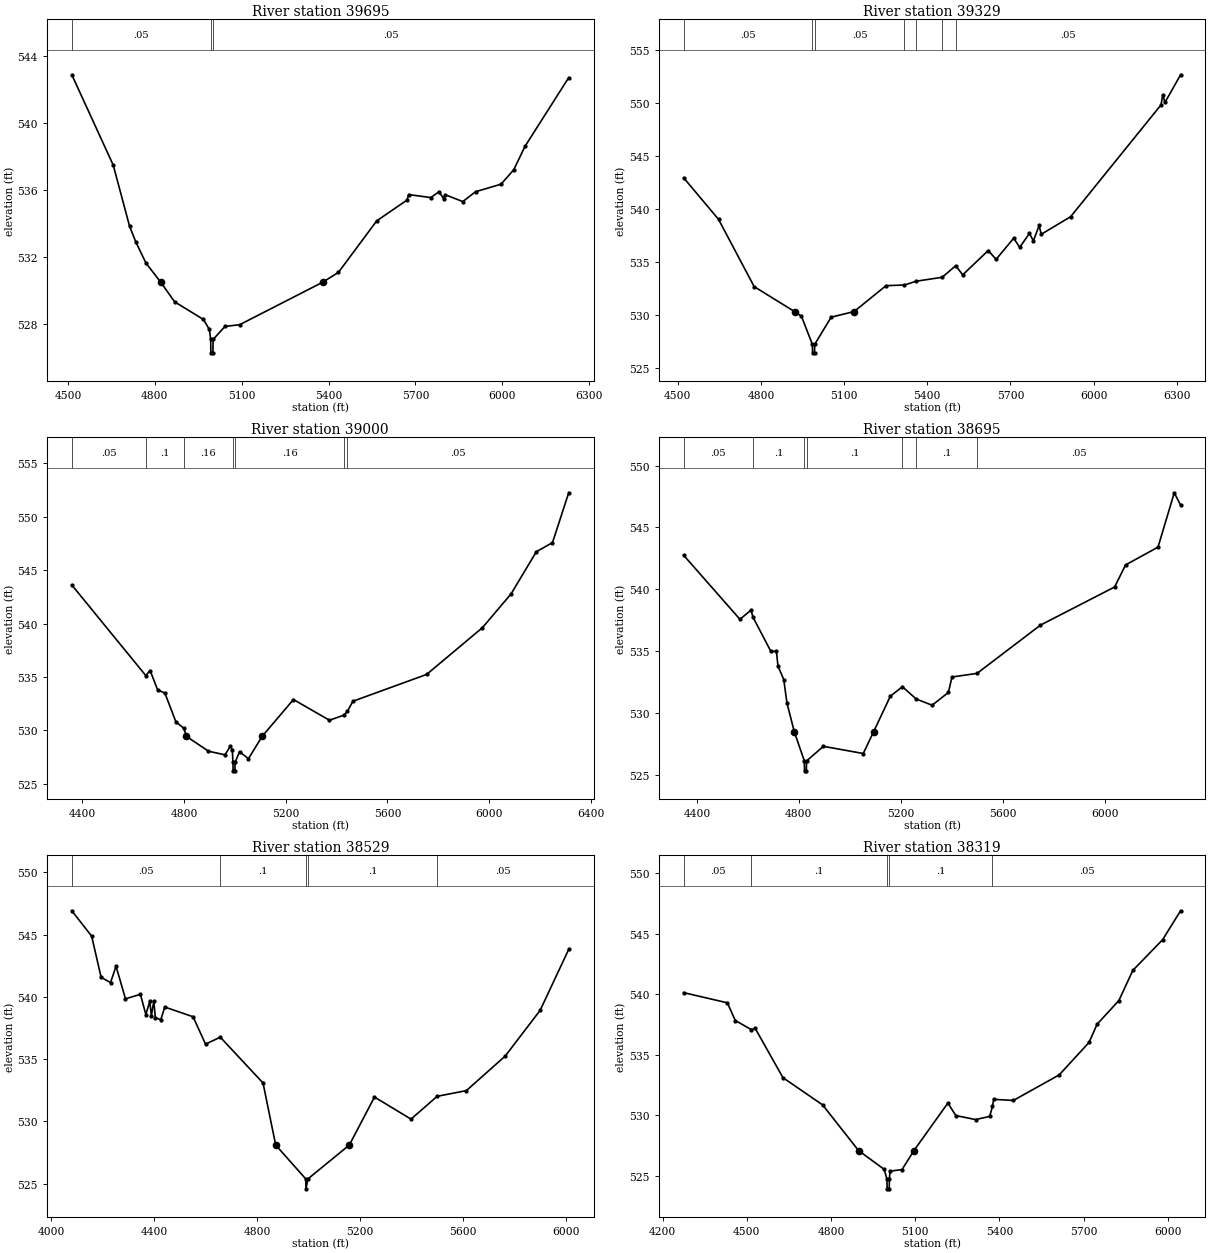
Type RM Length L Ch R = 1 ,39695   ,366,366,366
BEGIN DESCRIPTION:
CHILTIPIN CREEK 93.0
END DESCRIPTION:
XS GIS Cut Line= 3
      2029042.58     13506059.35        2028725.       13505725.
      2027614.58     13505140.49
#Sta/Elev= 30
  4513.2   542.9  4656.2   537.5  4712.4  533.86  4733.9  532.92  4769.1  531.65
 4820.26530.5019  4868.2  529.33  4967.3  528.28  4988.2  527.68  4992.7  527.08
  4993.4  526.28  5000.4  526.28  5001.2  527.08  5042.1  527.86  5092.7  527.96
 5379.66 530.502    5434  531.09  5566.2  534.17  5670.7  535.41  5676.4  535.74
  5753.2  535.56  5780.9  535.91  5797.3   535.5  5802.9  535.73  5863.4  535.32
  5907.4  535.91  5995.6  536.36  6039.6  537.23  6078.1  538.62  6229.2  542.73
#Mann= 3 ,-1 , 0
  4513.2     .05       0  4992.7    .035       0  5001.2     .05       0
Bank Sta=4820.26,5379.66
XS Rating Curve= 0 ,0
Exp/Cntr=0.3,0.1

Type RM Length L Ch R = 1 ,39329   ,329,329,329
BEGIN DESCRIPTION:
CHILTIPIN CREEK 92.0
END DESCRIPTION:
XS GIS Cut Line= 3
      2029174.98     13505874.96        2028975.       13505475.
      2028075.02     13504475.03
#Sta/Elev= 30
  4521.2  542.92  4646.9  539.01  4775.5  532.67 4921.04530.3204    4946  529.88
  4985.4  527.23  4986.2  526.43  4993.2  526.43  4993.9  527.23  5053.2  529.79
 5135.95530.3204  5251.3  532.76  5317.4  532.82  5360.4  533.18  5453.9  533.55
  5502.5  534.64  5527.8  533.78  5619.8  536.07  5648.2  535.24  5711.7  537.23
  5733.4  536.37  5768.5  537.68  5782.7  536.98  5803.6  538.43  5811.1   537.6
  5917.2  539.26  6243.1  549.79  6249.8  550.76  6257.3  550.02  6313.7  552.63
#Mann= 7 ,-1 , 0
  4521.2     .05       0  4985.4    .035       0  4993.9     .05       0
  5317.4      .1       0  5360.4     .05       0  5453.9      .1       0
  5502.5     .05       0
Bank Sta=4921.04,5135.95
XS Rating Curve= 0 ,0
Exp/Cntr=0.3,0.1

Type RM Length L Ch R = 1 ,39000   ,305,305,305
BEGIN DESCRIPTION:
CHILTIPIN CREEK 91.0
END DESCRIPTION:
XS GIS Cut Line= 3
      2029675.04     13505575.03        2029175.       13505225.
      2028175.03     13504325.02
#Sta/Elev= 30
    4358  543.61  4648.9  535.13  4666.3  535.59  4695.9  533.77  4724.2  533.49
  4767.4   530.8    4799  530.18 4809.03529.4321  4895.6  528.04    4961   527.7
  4982.2  528.52  4989.7  528.17  4992.1     527  4992.9   526.2    5000   526.2
  5000.8     527  5018.1  527.99  5053.2  527.34  5107.1 529.432  5230.3  532.88
    5372  530.94  5429.1  531.42  5442.9  531.79  5464.3  532.72  5754.3  535.23
    5974  539.61  6086.9  542.78  6186.3  546.73  6249.8  547.58  6313.7  552.25
#Mann= 7 ,-1 , 0
    4358     .05       0  4648.9      .1       0    4799     .16       0
  4992.1     .07       0  5000.8     .16       0  5429.1      .1       0
  5442.9     .05       0
Bank Sta=4809.03,5107.1
XS Rating Curve= 0 ,0
Exp/Cntr=0.3,0.1

Type RM Length L Ch R = 1 ,38695   ,166,166,166
BEGIN DESCRIPTION:
CHILTIPIN CREEK 90.0
END DESCRIPTION:
XS GIS Cut Line= 3
      2029725.03     13505475.04        2029375.       13505025.
      2028322.35     13504132.83
#Sta/Elev= 30
  4348.3  542.75  4569.1  537.58  4612.6  538.32  4620.3  537.75  4690.4  534.99
  4712.1     535  4718.4   533.8  4741.1  532.71  4753.7  530.81 4782.48528.4926
  4821.8  526.14  4822.6  525.34  4829.7  525.34  4830.5  526.14  4896.7  527.32
    5053  526.74 5093.61528.4927  5159.6  531.38  5206.9  532.13    5261  531.14
  5323.3  530.64    5387  531.67  5401.3  532.92  5499.5  533.21  5748.4  537.11
  6039.5  540.19  6082.3  541.97  6209.8  543.41  6273.5   547.8  6298.3  546.81
#Mann= 7 ,-1 , 0
  4348.3     .05       0  4620.3      .1       0  4821.8     .07       0
  4830.5      .1       0  5206.9     .16       0    5261      .1       0
  5499.5     .05       0
Bank Sta=4782.48,5093.61
XS Rating Curve= 0 ,0
Exp/Cntr=0.3,0.1

Type RM Length L Ch R = 1 ,38529   ,210,210,210
BEGIN DESCRIPTION:
CHILTIPIN CREEK 89.0
END DESCRIPTION:
XS GIS Cut Line= 4
      2030186.96     13505469.65      2029673.02     13505153.65
      2029259.83     13504802.95      2028795.45     13504168.76
#Sta/Elev= 30
    4080  546.91  4157.1  544.87  4193.8  541.57  4230.5  541.14  4251.8  542.46
  4288.5  539.84  4346.5   540.2  4367.8  538.58  4383.2  539.65  4389.1  538.47
  4398.6  539.66  4404.5  538.33  4425.8  538.16  4441.2  539.18  4551.3   538.4
  4599.7   536.2    4657  536.76  4823.2  533.08 4872.35528.0972  4989.1  525.38
  4989.9  524.58  4997.8  525.38 5158.57528.0968  5256.3  531.95  5398.3  530.18
    5500  532.01  5613.7  532.47  5764.3  535.24  5900.1  538.91  6011.3  543.81
#Mann= 5 ,-1 , 0
    4080     .05       0    4657      .1       0  4989.1     .07       0
  4997.8      .1       0    5500     .05       0
Bank Sta=4872.35,5158.57
XS Rating Curve= 0 ,0
Exp/Cntr=0.3,0.1

Type RM Length L Ch R = 1 ,38319   ,380,380,380
BEGIN DESCRIPTION:
CHILTIPIN CREEK 88.0
END DESCRIPTION:
XS GIS Cut Line= 3
      2030025.01     13505275.01        2029525.       13504775.
      2028725.03     13504075.02
#Sta/Elev= 30
  4275.4  540.12    4431  539.28  4459.3  537.82    4517  537.06    4530  537.18
    4629   533.1  4770.4  530.85 4898.55527.0759  4989.6  525.53  4999.5  524.72
  5000.3  523.92  5007.5  523.92  5008.3  524.72  5010.5  525.38  5053.2  525.51
  5095.6527.0761  5216.5     531    5245  529.97  5315.2  529.64  5365.5   529.9
  5375.4  530.72  5379.7  531.31    5450  531.22  5613.2  533.33  5719.5  536.01
    5748  537.51  5825.8  539.47  5875.2  541.95  5981.5  544.49  6045.5  546.88
#Mann= 5 ,-1 , 0
  4275.4     .05       0    4517      .1       0  4999.5     .07       0
  5008.3      .1       0  5375.4     .05       0
Bank Sta=4898.55,5095.6
XS Rating Curve= 0 ,0
Exp/Cntr=0.3,0.1

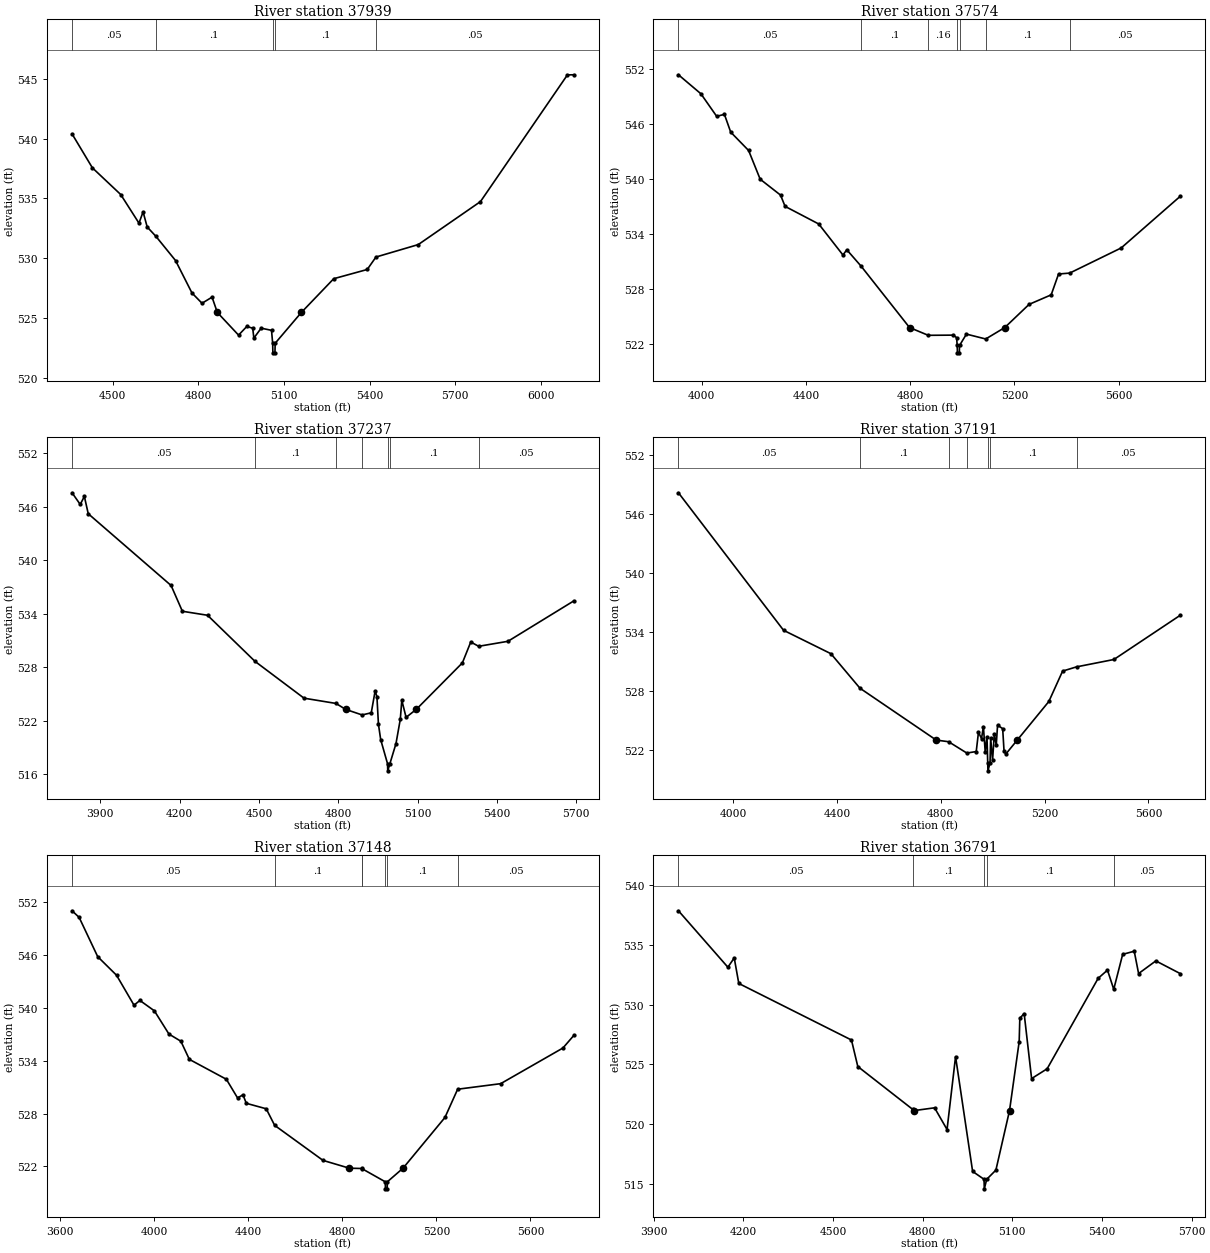
Type RM Length L Ch R = 1 ,37939   ,365,365,365
BEGIN DESCRIPTION:
CHILTIPIN CREEK 87.0
END DESCRIPTION:
XS GIS Cut Line= 3
        2030175.       13505025.        2029775.       13504525.
      2028775.04     13504025.02
#Sta/Elev= 30
    4357  540.39  4428.2  537.56  4527.5  535.33  4591.5  532.94  4605.9  533.88
  4620.3  532.62  4650.8  531.84  4719.6  529.82  4777.2  527.11  4812.4  526.25
  4847.6  526.76 4866.06525.4842  4940.5  523.59  4969.3  524.31  4990.1  524.17
  4994.1  523.34  5019.7  524.17    5056  523.99    5060  522.91  5060.8  522.11
    5068  522.11  5068.8  522.91 5160.66 525.484    5274   528.3  5391.4  529.07
    5422  530.11  5570.3  531.15  5788.3  534.74    6093  545.32  6115.3  545.33
#Mann= 5 ,-1 , 0
    4357     .05       0  4650.8      .1       0    5060     .07       0
  5068.8      .1       0    5422     .05       0
Bank Sta=4866.06,5160.66
XS Rating Curve= 0 ,0
Exp/Cntr=0.3,0.1

Type RM Length L Ch R = 1 ,37574   ,337,337,337
BEGIN DESCRIPTION:
CHILTIPIN CREEK 86.0
END DESCRIPTION:
XS GIS Cut Line= 3
        2030425.     13505275.01        2030025.       13504275.
      2029424.98     13503674.98
#Sta/Elev= 30
  3910.9  551.36  3997.1  549.29  4057.7  546.83  4087.3  547.05  4111.5  545.11
  4180.2  543.11  4224.6  539.98  4302.7  538.25  4320.2  537.02  4449.4   535.1
  4542.3  531.72  4557.1  532.29  4612.4  530.49  4797.8523.8178  4869.6  522.97
  4966.4  522.99  4978.5  522.71  4980.8  521.86  4981.6  521.06  4988.9  521.06
  4989.7  521.86  5016.2   523.1  5090.2  522.57 5163.46523.8179  5256.6  526.34
  5341.5  527.38  5369.8  529.65  5412.5  529.75  5610.2  532.49  5836.5  538.11
#Mann= 7 ,-1 , 0
  3910.9     .05       0  4612.4      .1       0  4869.6     .16       0
  4980.8     .07       0  4989.7     .16       0  5090.2      .1       0
  5412.5     .05       0
Bank Sta=4797.8,5163.46
XS Rating Curve= 0 ,0
Exp/Cntr=0.3,0.1

Type RM Length L Ch R = 1 ,37237   ,46,46,46
BEGIN DESCRIPTION:
CHILTIPIN CREEK 85.0
END DESCRIPTION:
XS GIS Cut Line= 4
      2030815.41     13504997.44      2030211.22     13503993.93
        2030114.     13503941.84      2029528.55     13503747.85
#Sta/Elev= 30
  3792.9  547.59  3823.8  546.28  3839.4  547.18  3854.1  545.24  4167.6  537.19
  4210.3   534.3  4305.5  533.85  4485.1  528.68  4670.6  524.55  4791.6  523.96
 4827.79523.2973  4890.4  522.67    4925  522.91  4939.7  525.37  4946.4  524.73
  4952.2  521.62  4960.7   519.9  4986.6   517.2  4987.4   516.4  4995.5   517.2
  5018.6  519.46  5034.9  522.19  5040.6  524.31  5056.8   522.4 5095.55523.2972
  5269.8  528.51  5301.5  530.85  5331.4  530.37  5442.2  530.93  5691.3  535.46
#Mann= 7 ,-1 , 0
  3792.9     .05       0  4485.1      .1       0  4791.6     .16       0
  4890.4      .1       0  4986.6     .07       0  4995.5      .1       0
  5331.4     .05       0
Bank Sta=4827.79,5095.55
XS Rating Curve= 0 ,0
Exp/Cntr=0.3,0.1

Type RM Length L Ch R = 1 ,37191   ,43,43,43
BEGIN DESCRIPTION:
CHILTIPIN CREEK 84.0
END DESCRIPTION:
XS GIS Cut Line= 5
      2030860.94     13504958.57      2030248.98      13503977.7
      2030192.56     13503925.62      2030118.77     13503903.92
      2029519.93     13503730.34
#Sta/Elev= 30
    3789  548.15    4194  534.17  4376.5  531.79  4488.5  528.28 4782.26523.0077
    4830  522.84  4900.1  521.69  4936.5  521.84  4945.1   523.8  4956.9  523.16
  4964.1  524.38  4971.1  521.82  4977.9  523.34  4980.8  520.68  4981.6  519.88
  4989.7  520.68  4992.1  523.22  4999.4  520.94  5006.2  523.65  5013.6  522.48
  5018.7  524.52  5038.4  524.17  5043.6  521.91  5050.6  521.59 5094.58523.0076
  5216.3  526.93  5269.3  530.02  5322.9  530.45    5467   531.2  5722.3  535.69
#Mann= 7 ,-1 , 0
    3789     .05       0  4488.5      .1       0    4830     .16       0
  4900.1      .1       0  4980.8     .07       0  4989.7      .1       0
  5322.9     .05       0
Bank Sta=4782.26,5094.58
XS Rating Curve= 0 ,0
Exp/Cntr=0.3,0.1

Type RM Length L Ch R = 1 ,37148   ,357,357,357
BEGIN DESCRIPTION:
CHILTIPIN CREEK 83.0
END DESCRIPTION:
XS GIS Cut Line= 4
      2030956.44     13504993.31      2030713.39     13504311.91
      2030149.15     13503834.47      2029489.75     13503704.33
#Sta/Elev= 30
  3649.9  551.03    3680  550.28    3759  545.82  3839.2  543.71  3913.5  540.31
  3938.5  540.85  4000.1  539.67  4062.2  537.03  4112.8  536.22  4148.9  534.16
  4306.4   531.9  4353.9  529.79  4377.1  530.13  4391.3  529.17    4476  528.55
  4511.8  526.67  4717.6  522.69 4829.87521.8022  4882.1  521.77  4883.5  521.75
  4982.5  520.26  4983.3  519.46  4990.6  519.46  4991.4  520.26 5058.09521.8024
  5236.4  527.56  5290.5  530.77  5473.5   531.4  5738.5  535.45  5784.6  536.87
#Mann= 7 ,-1 , 0
  3649.9     .05       0  4511.8      .1       0  4882.1     .16       0
  4883.5      .1       0  4982.5     .07       0  4991.4      .1       0
  5290.5     .05       0
Bank Sta=4829.87,5058.09
XS Rating Curve= 0 ,0
Exp/Cntr=0.3,0.1

Type RM Length L Ch R = 1 ,36791   ,122,122,122
BEGIN DESCRIPTION:
CHILTIPIN CREEK 82.0
END DESCRIPTION:
XS GIS Cut Line= 5
      2031108.34     13504459.45      2030765.47      13503912.6
      2030387.87     13503587.08      2030275.02     13503565.38
       2029871.4     13503682.56
#Sta/Elev= 30
  3982.4  537.88  4147.9  533.15  4169.1  533.93  4184.4  531.79  4561.5  527.05
  4582.7  524.83  4766.9  521.23 4771.61521.1376  4839.7  521.37  4881.4  519.55
  4909.9  525.66    4967  516.04  5005.2  515.38  5006.1  514.58  5014.2  515.38
  5044.9  516.15 5090.52521.1373  5122.8  526.91    5125  528.87  5139.5  529.27
  5164.4  523.82  5216.4  524.64  5387.1  532.22  5418.4  532.91  5439.3   531.3
  5469.2  534.23  5507.9  534.49  5522.5  532.62  5580.2  533.68  5661.6  532.62
#Mann= 5 ,-1 , 0
  3982.4     .05       0  4766.9      .1       0  5005.2     .07       0
  5014.2      .1       0  5439.3     .05       0
Bank Sta=4771.61,5090.52
XS Rating Curve= 0 ,0
Exp/Cntr=0.3,0.1