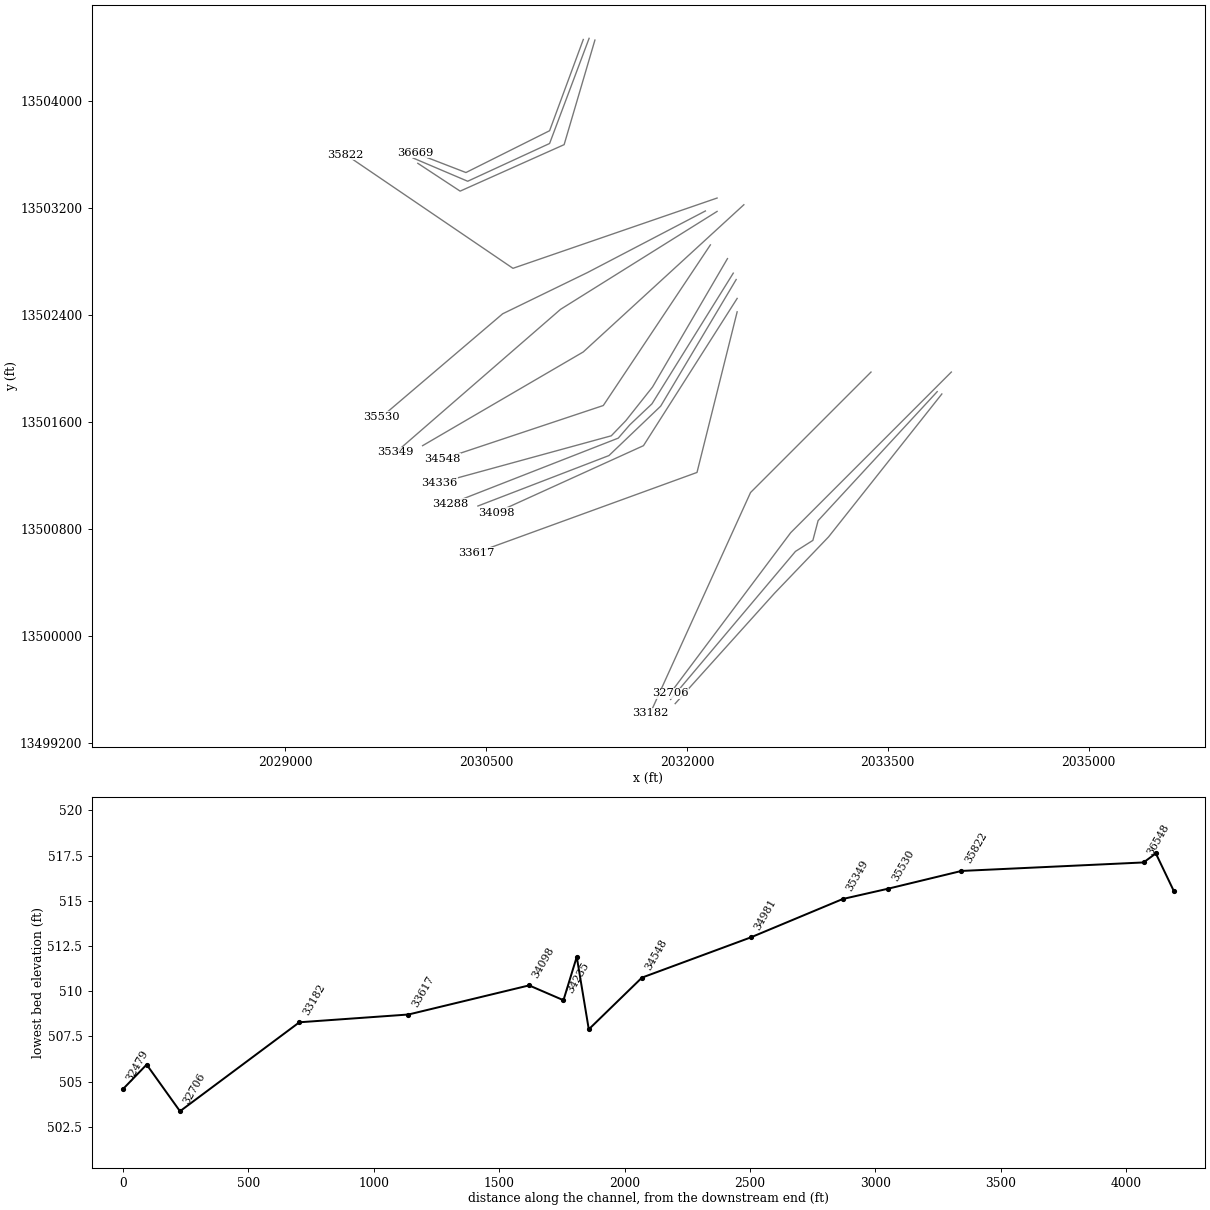
HEC-RAS study CHILTIPIN CREEK.prj: CHILTIPIN CREEK Base Level Engineering

--- CHILTIPIN CREEK.g01 (geometry) --- (continued)

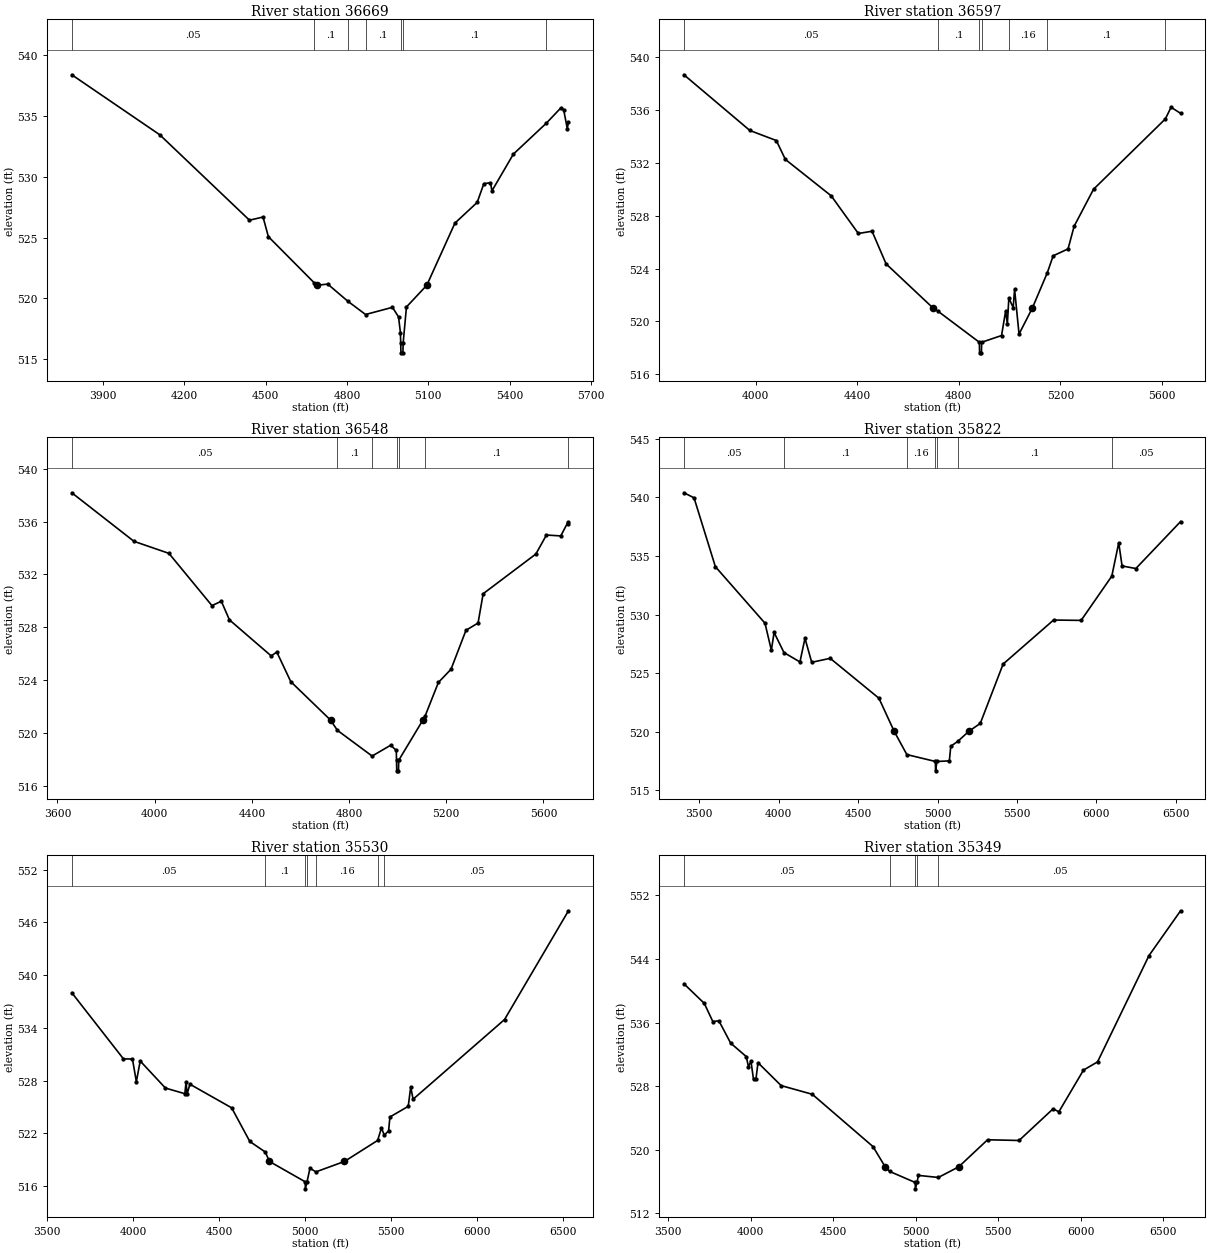
Type RM Length L Ch R = 1 ,36669   ,72,72,72
BEGIN DESCRIPTION:
CHILTIPIN CREEK 81.0
END DESCRIPTION:
XS GIS Cut Line= 4
      2031225.56     13504459.52      2030973.81     13503778.05
      2030348.81     13503465.55      2029968.46      13503612.5
#Sta/Elev= 30
  3784.3  538.38  4108.9  533.45    4440  526.43  4490.1  526.69  4509.7  525.08
  4678.7  521.29 4689.98521.0835  4728.8  521.18  4803.1  519.77  4868.5  518.68
  4967.8  519.27  4990.2  518.48  4997.1   517.2  4998.2  516.33    4999  515.53
  5006.3  515.53  5007.2  516.33  5019.4   519.3 5094.43521.0836  5198.3  526.19
  5280.4  527.89    5305  529.43  5329.5  529.51  5334.9  528.84    5414  531.86
    5536  534.41  5588.9  535.65  5599.6  535.51    5613  533.95  5617.3   534.5
#Mann= 7 ,-1 , 0
  3784.3     .05       0  4678.7      .1       0  4803.1     .16       0
  4868.5      .1       0  4998.2     .07       0  5007.2      .1       0
    5536     .05       0
Bank Sta=4689.98,5094.43
XS Rating Curve= 0 ,0
Exp/Cntr=0.3,0.1

Type RM Length L Ch R = 1 ,36597   ,49,49,49
BEGIN DESCRIPTION:
CHILTIPIN CREEK 80.0
END DESCRIPTION:
XS GIS Cut Line= 4
      2031268.94     13504468.14      2030973.81     13503682.56
      2030361.83     13503400.45      2029953.88     13503574.04
#Sta/Elev= 30
  3717.3  538.68    3977  534.46  4081.2   533.7  4116.8  532.27  4297.5  529.51
  4404.3  526.66  4458.3  526.83  4513.5  524.36 4698.57521.0147  4718.9  520.76
    4881  518.42  4881.9  517.62  4889.2  517.62    4890  518.42  4968.4  518.93
  4984.6  520.79  4991.3   519.8  4997.2  521.77  5014.3  521.05  5019.8  522.43
  5037.3  519.04 5089.81 521.015  5148.6  523.68  5171.8  524.97  5230.4  525.49
  5254.4  527.21  5330.8  530.01  5613.9  535.34  5636.1  536.22  5673.7  535.76
#Mann= 7 ,-1 , 0
  3717.3     .05       0  4718.9      .1       0    4881     .07       0
    4890      .1       0  4997.2     .16       0  5148.6      .1       0
  5613.9     .05       0
Bank Sta=4698.57,5089.81
XS Rating Curve= 0 ,0
Exp/Cntr=0.3,0.1

Type RM Length L Ch R = 1 ,36548   ,726,726,726
BEGIN DESCRIPTION:
CHILTIPIN CREEK 79.0
END DESCRIPTION:
XS GIS Cut Line= 4
      2031312.35     13504455.14      2031082.31     13503673.88
       2030305.4     13503326.66       2029989.3     13503534.51
#Sta/Elev= 30
  3659.1  538.19  3914.9  534.51  4058.7   533.6  4235.8  529.64  4274.4  529.97
  4307.7  528.56  4479.5  525.83  4502.7  526.12  4560.1  523.88 4723.76520.9667
    4752  520.19  4894.9  518.24  4971.1  519.06  4994.3  518.67  4995.3  517.92
  4996.1  517.12  5003.4  517.12  5004.3  517.92 5103.79 520.967  5113.7  521.31
  5167.7  523.82  5219.6  524.82  5281.1  527.77  5330.8  528.32  5351.8  530.54
  5568.7  533.55  5612.2  534.99  5671.2  534.92  5701.3  535.98  5702.8   535.8
#Mann= 7 ,-1 , 0
  3659.1     .05       0    4752      .1       0  4894.9     .16       0
  4995.3     .07       0  5004.3     .16       0  5113.7      .1       0
  5701.3     .05       0
Bank Sta=4723.76,5103.79
XS Rating Curve= 0 ,0
Exp/Cntr=0.3,0.1

Type RM Length L Ch R = 1 ,35822   ,292,292,292
BEGIN DESCRIPTION:
CHILTIPIN CREEK 78.0
END DESCRIPTION:
XS GIS Cut Line= 3
      2032225.01       13503275.        2030700.       13502750.
      2029449.98     13503600.01
#Sta/Elev= 30
  3404.5   540.4    3468  539.97  3602.2  534.09  3914.4  529.26  3954.5  526.95
  3971.6  528.47  4033.9  526.75  4134.3  525.95    4166  527.97  4208.3  525.92
  4324.6  526.26  4631.3  522.85 4726.94520.0297  4806.8  518.04  4986.5  517.45
  4987.5  516.65  4996.4  517.45  5074.3   517.5  5083.2  518.75  5126.6  519.16
 5197.25520.0296  5268.8   520.7  5412.5  525.77  5729.8  529.53  5903.3   529.5
  6096.3  533.28  6139.9  536.13  6160.9  534.15  6247.6  533.93    6529  537.94
#Mann= 7 ,-1 , 0
  3404.5     .05       0  4033.9      .1       0  4806.8     .16       0
  4986.5     .07       0  4996.4     .16       0  5126.6      .1       0
  6096.3     .05       0
Bank Sta=4726.94,5197.25
XS Rating Curve= 0 ,0
Exp/Cntr=0.3,0.1

Type RM Length L Ch R = 1 ,35530   ,181,181,181
BEGIN DESCRIPTION:
CHILTIPIN CREEK 77.0
END DESCRIPTION:
XS GIS Cut Line= 4
      2032137.65     13503178.38      2031256.62     13502718.33
      2030622.94     13502410.17      2029717.25     13501638.81
#Sta/Elev= 30
  3642.4  537.99  3942.8  530.46  3995.1  530.45  4017.7  527.87  4040.2  530.22
  4186.9  527.14  4299.7   526.5    4307  527.86  4312.6  526.44  4329.1  527.58
    4572  524.89  4677.6  521.06  4767.5  519.86  4791.7518.7889  4999.8  516.47
  5000.6  515.67  5010.4  516.47  5027.3  518.02  5061.8   517.6 5228.04518.7888
  5420.9  521.18    5443   522.6  5459.7  521.78  5484.7  522.28  5492.4  523.85
  5598.9  525.06  5613.2  527.26  5627.2  525.87  6158.9  534.94  6530.6  547.32
#Mann= 7 ,-1 , 0
  3642.4     .05       0  4767.5      .1       0  4999.8     .07       0
  5010.4      .1       0  5061.8     .16       0  5420.9      .1       0
  5459.7     .05       0
Bank Sta=4791.7,5228.04
XS Rating Curve= 0 ,0
Exp/Cntr=0.3,0.1

Type RM Length L Ch R = 1 ,35349   ,368,368,368
BEGIN DESCRIPTION:
CHILTIPIN CREEK 76.0
END DESCRIPTION:
XS GIS Cut Line= 3
      2032225.02     13503175.01      2031055.66     13502443.59
      2029825.01     13501375.01
#Sta/Elev= 30
  3595.9  540.88  3719.1  538.42    3771  536.13  3807.6  536.23    3879  533.42
  3973.4  531.73  3986.8  530.46  4002.1  531.14  4017.4  528.85  4032.3  528.93
  4044.6  530.96  4184.9  528.08  4373.5  526.99  4741.4  520.41 4815.32517.8667
  4842.1  517.29  4997.2   515.9  4998.1   515.1  5007.8   515.9  5016.8  516.79
  5137.3  516.53  5260.7517.8666  5435.6  521.27  5626.4  521.18  5832.5  525.16
  5867.6  524.79  6016.7  530.03  6101.8  531.06  6413.7  544.43    6605  550.06
#Mann= 5 ,-1 , 0
  3595.9     .05       0  4842.1      .1       0  4997.2     .07       0
  5007.8      .1       0  5137.3     .05       0
Bank Sta=4815.32,5260.7
XS Rating Curve= 0 ,0
Exp/Cntr=0.3,0.1

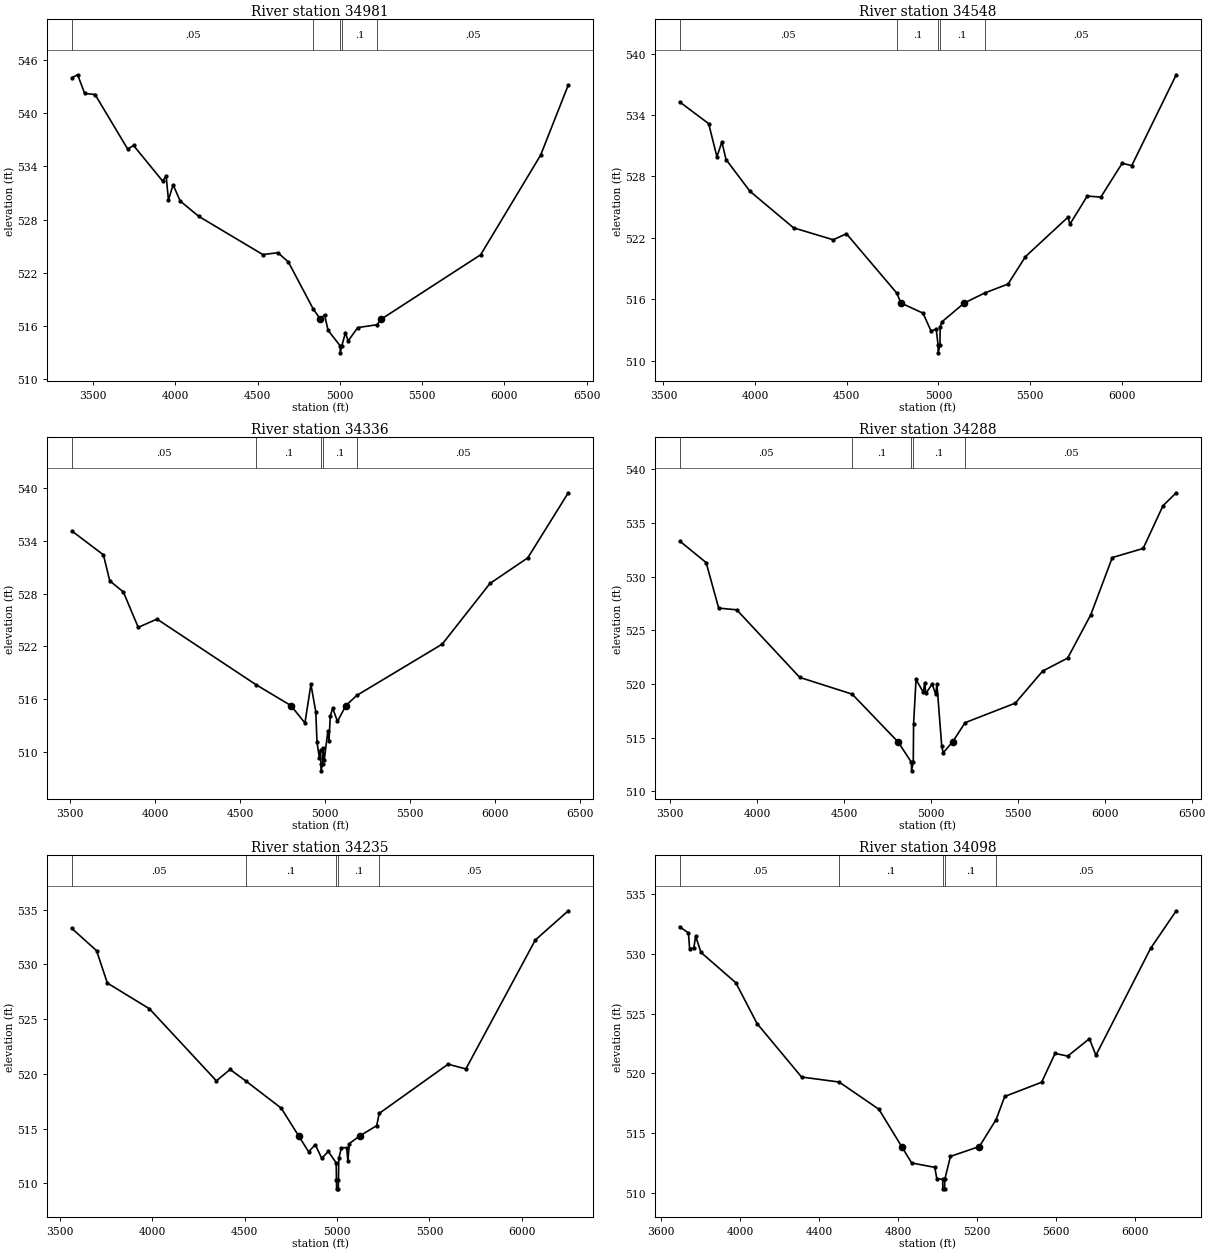
Type RM Length L Ch R = 1 ,34981   ,433,433,433
BEGIN DESCRIPTION:
CHILTIPIN CREEK 75.0
END DESCRIPTION:
XS GIS Cut Line= 3
      2032425.01     13503225.01        2031225.       13502125.
      2030025.03     13501425.02
#Sta/Elev= 30
  3371.4  544.02  3406.9  544.35  3449.4  542.25  3512.9  542.12  3710.9  535.97
  3746.6  536.37  3923.6  532.35  3944.6  532.94  3958.7  530.22  3987.1  531.94
  4029.7  530.11  4143.1  528.37  4532.2  524.06  4624.1  524.27  4687.6  523.22
    4837  517.97 4882.16516.7576  4907.1  517.27  4928.7  515.51  5001.9  513.77
  5002.7  512.97  5012.5  513.77  5034.4  515.25  5050.2   514.3  5108.9  515.82
  5225.6  516.14 5250.83516.7579    5856  524.04  6220.3  535.28  6388.5   543.2
#Mann= 5 ,-1 , 0
  3371.4     .05       0    4837      .1       0  5001.9     .07       0
  5012.5      .1       0  5225.6     .05       0
Bank Sta=4882.16,5250.83
XS Rating Curve= 0 ,0
Exp/Cntr=0.3,0.1

Type RM Length L Ch R = 1 ,34548   ,212,212,212
BEGIN DESCRIPTION:
CHILTIPIN CREEK 74.0
END DESCRIPTION:
XS GIS Cut Line= 3
        2032175.     13502924.99        2031375.       13501725.
      2030175.02     13501325.01
#Sta/Elev= 30
  3589.2  535.29  3746.9  533.17    3792  529.93    3819  531.38  3841.6  529.66
  3972.3  526.55  4209.6  522.98    4426  521.81  4498.1   522.4  4773.3  516.58
  4794.8515.6265  4915.7  514.63  4959.3  512.89  4987.8  513.06  4997.5  511.55
  4998.4  510.75  5008.2  511.55  5008.9  513.29  5017.9  513.77 5140.75515.6263
  5251.3   516.6  5379.3  517.48  5474.1  520.16    5706  524.02  5716.6  523.34
  5811.4  526.09  5885.2  525.98  6001.2  529.29  6053.9  529.07  6296.3  537.95
#Mann= 5 ,-1 , 0
  3589.2     .05       0  4773.3      .1       0  4997.5     .07       0
  5008.2      .1       0  5251.3     .05       0
Bank Sta=4794.8,5140.75
XS Rating Curve= 0 ,0
Exp/Cntr=0.3,0.1

Type RM Length L Ch R = 1 ,34336   ,48,48,48
BEGIN DESCRIPTION:
CHILTIPIN CREEK 73.0
END DESCRIPTION:
XS GIS Cut Line= 5
      2032302.63      13502822.5      2031742.73     13501863.29
      2031543.08     13501611.56      2031434.57     13501498.71
      2030149.91     13501147.16
#Sta/Elev= 30
  3510.6  535.11  3696.5   532.4  3733.8  529.45    3814  528.18  3901.4  524.17
  4011.6  525.11  4594.5  517.66 4799.34515.2976  4881.9  513.32  4917.2   517.7
  4945.9  514.56  4952.8  511.15  4966.9  509.33  4974.2  510.31  4975.7  508.69
  4976.6  507.89  4986.4  508.69  4988.3  510.44  4995.2  509.08  5016.6  512.36
  5023.5  511.29  5030.8  514.07  5044.9     515  5073.2  513.51 5123.07515.2978
  5186.3  516.44  5689.6  522.27  5970.2  529.15  6192.7  532.06    6431  539.44
#Mann= 5 ,-1 , 0
  3510.6     .05       0  4594.5      .1       0  4975.7     .07       0
  4986.4      .1       0  5186.3     .05       0
Bank Sta=4799.34,5123.07
XS Rating Curve= 0 ,0
Exp/Cntr=0.3,0.1

Type RM Length L Ch R = 1 ,34288   ,53,53,53
BEGIN DESCRIPTION:
CHILTIPIN CREEK 72.0
END DESCRIPTION:
XS GIS Cut Line= 5
      2032346.01     13502713.96      2031738.39     13501737.43
      2031573.46     13501581.18      2031486.65     13501481.35
      2030232.35     13500990.91
#Sta/Elev= 30
    3555  533.32  3706.9  531.31    3779  527.07  3882.9  526.91  4245.3  520.61
  4547.1  519.05 4810.79514.5988  4887.8   512.7  4888.6   511.9  4898.5   512.7
  4900.4  516.31  4914.5  520.42  4956.6  519.21  4964.2   520.1  4970.9  519.11
  5006.8  519.99  5027.9  519.04  5034.5  520.01  5062.1  514.24  5070.1  513.58
 5125.03514.5989  5196.7  516.39  5485.4  518.21  5642.9   521.2  5786.7  522.41
  5919.8  526.45  6043.5  531.78  6221.2  532.63  6335.1  536.61  6411.4  537.82
#Mann= 5 ,-1 , 0
    3555     .05       0  4547.1      .1       0  4887.8     .07       0
  4898.5      .1       0  5196.7     .05       0
Bank Sta=4810.79,5125.03
XS Rating Curve= 0 ,0
Exp/Cntr=0.3,0.1

Type RM Length L Ch R = 1 ,34235   ,137,137,137
BEGIN DESCRIPTION:
CHILTIPIN CREEK 71.0
END DESCRIPTION:
XS GIS Cut Line= 4
      2032367.71     13502666.22      2031803.49     13501720.06
      2031417.21     13501351.14      2030438.11     13500974.23
#Sta/Elev= 30
  3565.8  533.28  3699.6  531.25    3758  528.29  3985.7  525.94  4347.7  519.36
  4421.7   520.4  4507.5  519.34  4698.2  516.87 4792.58514.3322  4846.6  512.88
  4882.2  513.54  4917.4  512.28  4952.9  512.92  4995.4  511.87    4997   510.3
  4997.8   509.5  5006.8   509.5  5007.7   510.3  5009.6  512.28  5023.7  513.24
    5052  513.27  5058.9  512.05  5066.2  513.63 5123.19514.3318  5214.6  515.27
  5228.3  516.39  5600.4  520.88  5696.8  520.45  6072.4  532.22  6250.7  534.89
#Mann= 5 ,-1 , 0
  3565.8     .05       0  4507.5      .1       0    4997     .07       0
  5007.7      .1       0  5228.3     .05       0
Bank Sta=4792.58,5123.19
XS Rating Curve= 0 ,0
Exp/Cntr=0.3,0.1

Type RM Length L Ch R = 1 ,34098   ,481,481,481
BEGIN DESCRIPTION:
CHILTIPIN CREEK 70.0
END DESCRIPTION:
XS GIS Cut Line= 3
      2032375.02     13502525.04        2031675.       13501425.
      2030574.99     13500924.99
#Sta/Elev= 30
    3695  532.28  3739.1  531.76    3745  530.42  3766.2  530.52  3775.5  531.48
  3802.6  530.13  3978.7  527.59  4086.2  524.17  4311.4  519.69  4501.4  519.27
  4702.6  516.99  4817.8513.8652  4868.5  512.49  4985.3  512.12  4995.9  511.17
  5025.4  511.12  5026.2  510.32  5035.2  510.32  5036.1  511.12  5064.8  513.04
 5211.07513.8656    5296  516.13  5339.4  518.06  5526.1  519.25  5594.2  521.67
    5658  521.44  5767.8   522.9  5800.8  521.51  6077.6  530.47  6207.2  533.62
#Mann= 5 ,-1 , 0
    3695     .05       0  4501.4      .1       0  5025.4     .07       0
  5036.1      .1       0    5296     .05       0
Bank Sta=4817.8,5211.07
XS Rating Curve= 0 ,0
Exp/Cntr=0.3,0.1

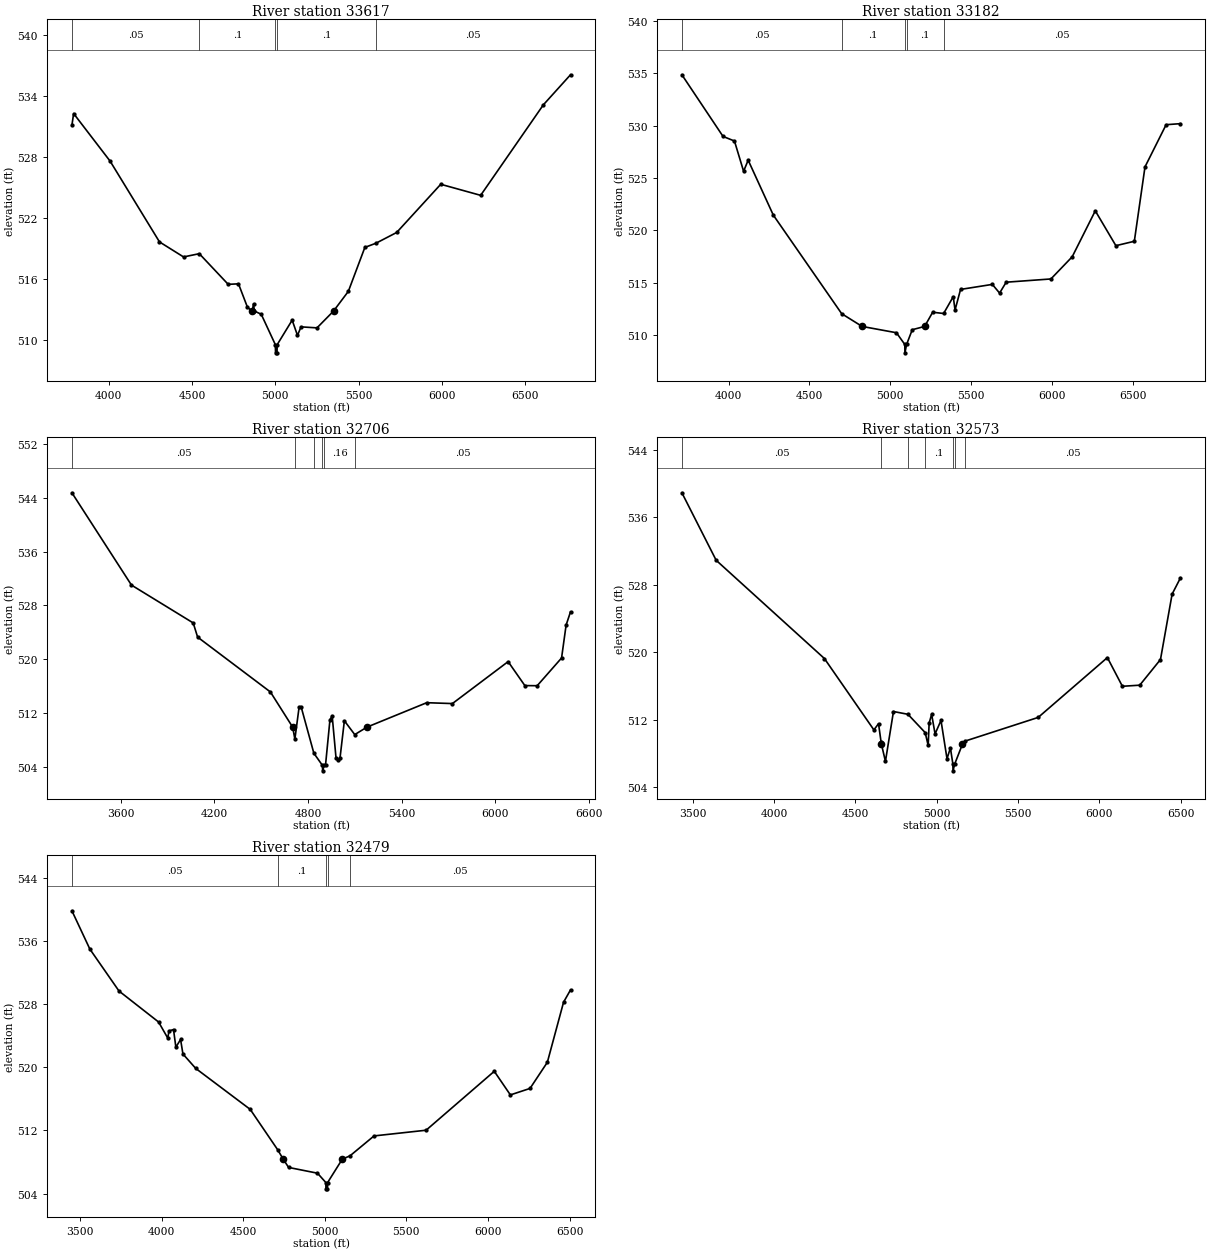
Type RM Length L Ch R = 1 ,33617   ,435,435,435
BEGIN DESCRIPTION:
CHILTIPIN CREEK 69.0
END DESCRIPTION:
XS GIS Cut Line= 3
      2032374.99     13502424.97        2032075.       13501225.
        2030425.       13500625.
#Sta/Elev= 30
    3779  531.13  3789.3  532.29  4008.3   527.6  4304.7  519.64    4449  518.16
  4543.6  518.48    4717  515.46  4778.8  515.51  4832.9  513.19 4861.21512.8212
    4869  513.53  4874.2  512.83  4915.4  512.51  5000.2  509.51  5001.1  508.71
  5010.1  508.71  5010.9  509.51    5101  511.93  5132.9  510.43  5154.2  511.27
    5250  511.17 5349.13512.8211  5438.2  514.77  5537.3   519.1  5603.7  519.51
  5728.2  520.57  5992.8  525.32  6232.3  524.23  6608.7  533.15  6771.6  536.11
#Mann= 5 ,-1 , 0
    3779     .05       0  4543.6      .1       0  5000.2     .07       0
  5010.9      .1       0  5603.7     .05       0
Bank Sta=4861.21,5349.13
XS Rating Curve= 0 ,0
Exp/Cntr=0.3,0.1

Type RM Length L Ch R = 1 ,33182   ,476,476,476
BEGIN DESCRIPTION:
CHILTIPIN CREEK 68.0
END DESCRIPTION:
XS GIS Cut Line= 3
        2033375.       13501975.        2032475.       13501075.
      2031725.02     13499425.04
#Sta/Elev= 30
  3710.6  534.85  3965.2  528.96  4035.9  528.52  4092.4  525.63  4120.7  526.69
  4276.3  521.44  4699.4  512.02 4825.87510.8028  5038.3   510.2    5090  509.08
  5090.7  508.28  5100.9  509.08  5136.1  510.49 5212.55510.8027  5262.4  512.16
  5330.2  512.04  5389.8  513.65  5400.8  512.37  5434.9  514.34  5631.5  514.82
  5676.5  513.99  5717.2  515.03    5994  515.34  6125.8  517.46  6268.6  521.85
    6396  518.52  6510.2  518.94  6576.2  526.05  6706.9  530.08  6795.8  530.18
#Mann= 5 ,-1 , 0
  3710.6     .05       0  4699.4      .1       0    5090     .07       0
  5100.9      .1       0  5330.2     .05       0
Bank Sta=4825.87,5212.55
XS Rating Curve= 0 ,0
Exp/Cntr=0.3,0.1

Type RM Length L Ch R = 1 ,32706   ,133,133,133
BEGIN DESCRIPTION:
CHILTIPIN CREEK 67.0
END DESCRIPTION:
XS GIS Cut Line= 3
        2033975.       13501975.        2032775.       13500775.
      2031874.97     13499574.97
#Sta/Elev= 30
  3286.2  544.78    3668  531.03    4064  525.39  4092.3  523.28    4559  515.11
 4701.74509.8723  4715.9  508.09  4742.8  512.81    4757  512.81  4837.7  505.98
    4893  504.16  4893.7  503.36  4903.9  504.16  4912.5  504.23  4940.8  510.96
    4955  511.56  4979.7  505.29  4990.5  504.97  5005.1  505.22  5033.3  510.82
  5099.8  508.76 5178.15509.8719  5561.4  513.51    5726  513.38  6083.3  519.63
  6190.5  516.06  6269.7  516.04    6426  520.17  6455.1  525.07  6483.3  527.04
#Mann= 6 ,-1 , 0
  3286.2     .05       0  4715.9      .1       0  4837.7     .16       0
    4893     .07       0  4903.9     .16       0  5099.8     .05       0
Bank Sta=4701.74,5178.15
XS Rating Curve= 0 ,0
Exp/Cntr=0.3,0.1

Type RM Length L Ch R = 1 ,32573   ,94,94,94
BEGIN DESCRIPTION:
CHILTIPIN CREEK 66.0
END DESCRIPTION:
XS GIS Cut Line= 5
      2033869.46     13501828.57      2032979.71     13500865.03
      2032940.65     13500717.46      2032810.44       13500635.
      2031878.02     13499529.11
#Sta/Elev= 30
  3433.6  538.89  3644.3  530.89  4309.6  519.25  4613.9  510.79  4642.3  511.53
    4658  509.35 4660.06509.1103  4684.8  507.06  4734.1  512.97  4823.2  512.64
  4929.1  510.47  4947.5  508.95  4953.4  511.59  4968.7  512.64  4989.8  510.32
  5026.3  511.91  5063.3  507.37  5084.1  508.66  5099.4  506.74  5100.2  505.94
  5110.4  506.74 5158.33509.1108  5176.9  509.48  5623.7  512.27    6049  519.36
  6141.3  515.96  6247.9  516.09  6375.4  519.13  6446.9  526.88  6498.4  528.81
#Mann= 7 ,-1 , 0
  3433.6     .05       0    4658      .1       0  4823.2     .05       0
  4929.1      .1       0  5099.4     .07       0  5110.4      .1       0
  5176.9     .05       0
Bank Sta=4660.06,5158.33
XS Rating Curve= 0 ,0
Exp/Cntr=0.3,0.1

Type RM Length L Ch R = 1 ,32479   ,221,221,221
BEGIN DESCRIPTION:
CHILTIPIN CREEK 65.0
END DESCRIPTION:
XS GIS Cut Line= 4
      2033904.17     13501811.18      2033057.83      13500743.5
      2032654.19      13500322.5      2031912.02     13499497.87
#Sta/Elev= 30
  3450.9  539.79  3560.9  534.94  3739.5  529.63    3982  525.71  4038.3  523.67
  4045.8  524.58  4073.5  524.76  4087.9  522.52  4116.8   523.5  4131.2  521.66
  4209.8  519.83  4543.4  514.65    4711  509.56  4745.7508.3495  4778.6   507.3
  4955.7  506.57  5006.8  505.39  5007.6  504.59    5017  504.59  5017.8  505.39
 5107.71508.3494    5155  508.77  5302.3  511.29  5621.1  512.01  6038.9  519.47
  6137.6  516.48  6257.9   517.3  6364.1  520.61  6463.5  528.22    6506  529.77
#Mann= 5 ,-1 , 0
  3450.9     .05       0    4711      .1       0  5006.8     .07       0
  5017.8      .1       0    5155     .05       0
Bank Sta=4745.7,5107.71
XS Rating Curve= 0 ,0
Exp/Cntr=0.3,0.1