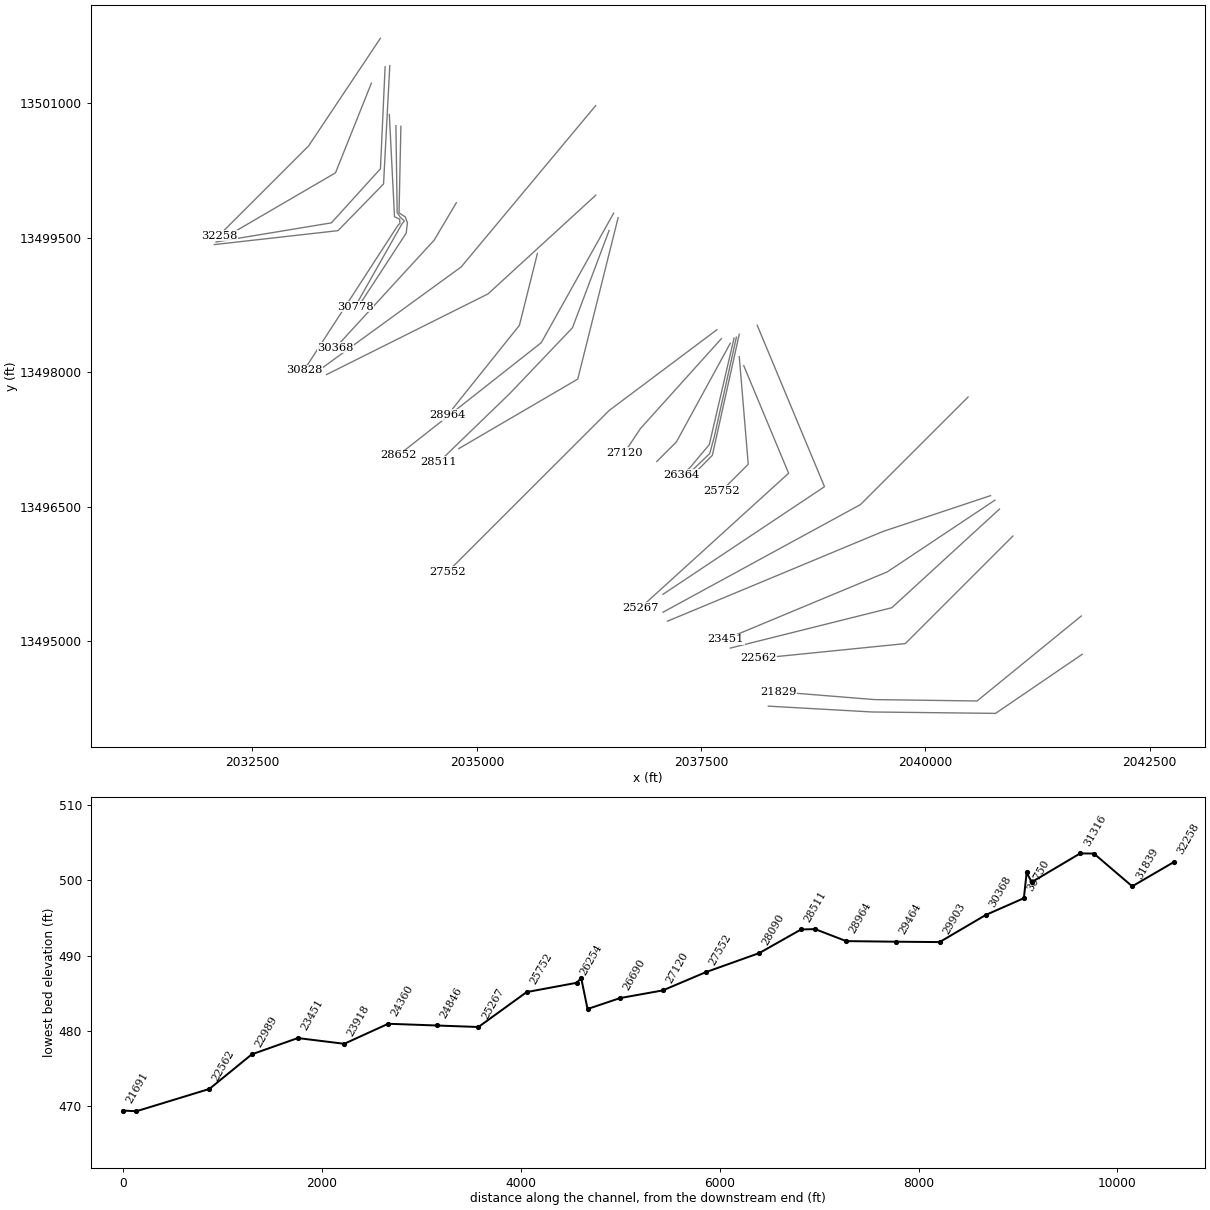
HEC-RAS study CHILTIPIN CREEK.prj: CHILTIPIN CREEK Base Level Engineering

--- CHILTIPIN CREEK.g01 (geometry) --- (continued)

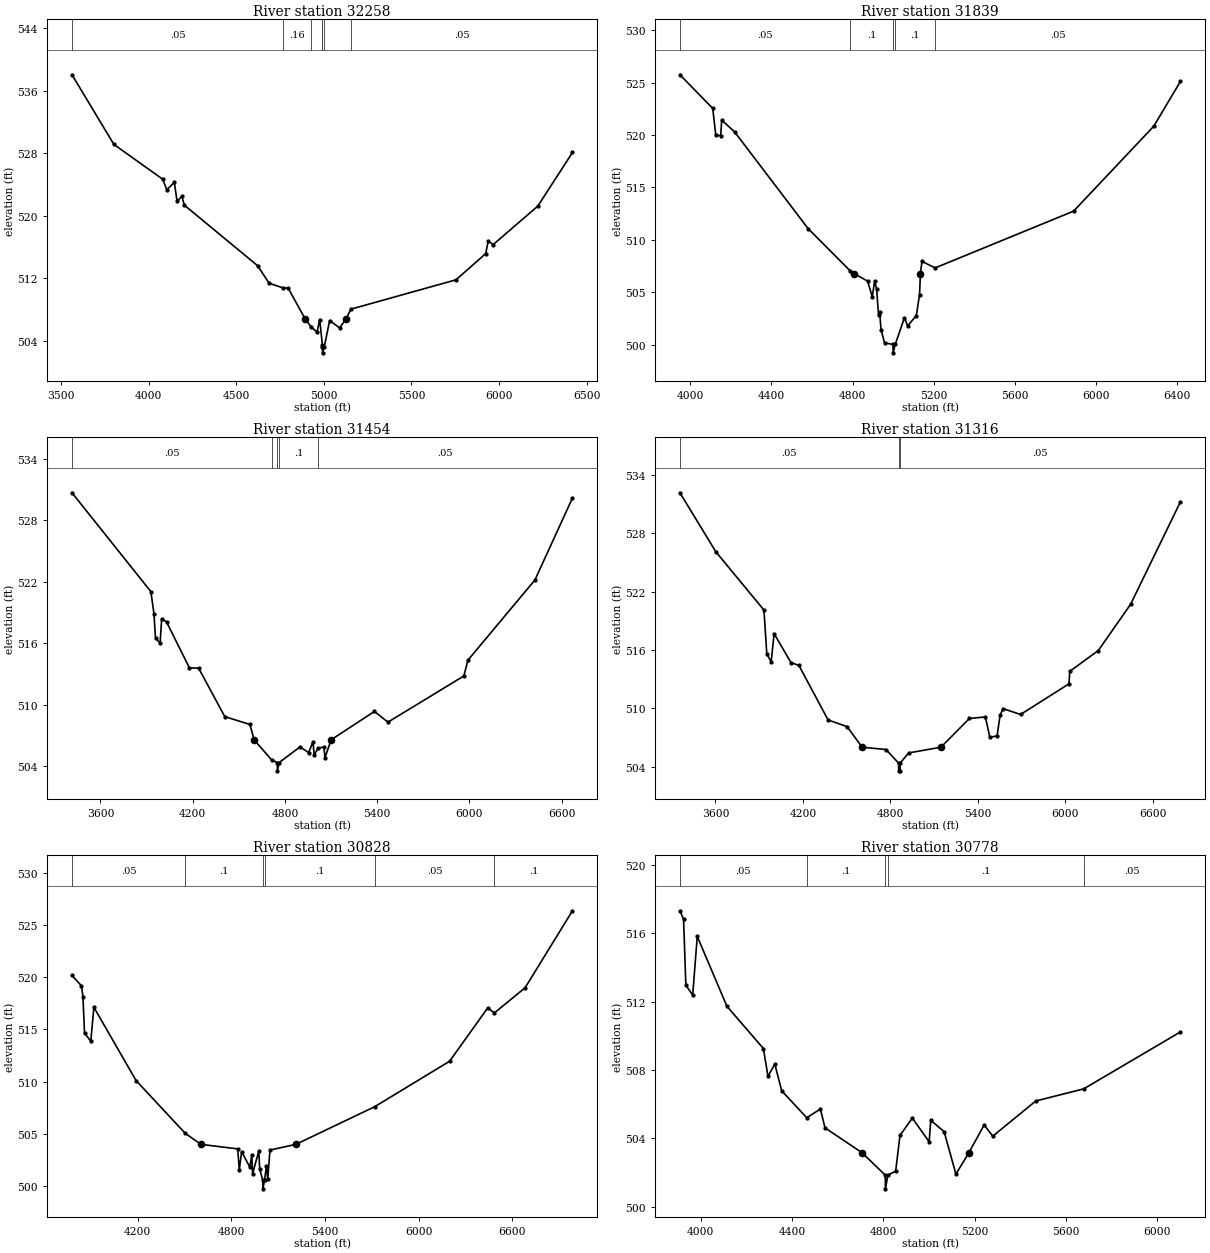
Type RM Length L Ch R = 1 ,32258   ,419,419,419
BEGIN DESCRIPTION:
CHILTIPIN CREEK 64.0
END DESCRIPTION:
XS GIS Cut Line= 3
      2033925.03     13501725.04        2033125.       13500525.
      2032124.99     13499524.99
#Sta/Elev= 30
  3562.6  538.03  3801.5  529.12  4080.9  524.65  4103.5  523.31    4147  524.25
  4162.1  521.82  4189.1  522.47  4204.1  521.33  4621.8  513.59  4687.9  511.34
  4767.5  510.74    4796  510.73 4893.51506.7602  4927.4  505.76  4961.3  505.07
  4976.3  506.69  4991.6  503.46  4991.9  503.23  4992.7  502.43  5002.9  503.23
  5033.2  506.57  5089.7  505.62 5126.46  506.76  5154.4  508.02  5754.4  511.78
  5924.1  515.14  5938.3  516.74  5966.5  516.29  6221.1  521.21  6419.1  528.08
#Mann= 7 ,-1 , 0
  3562.6     .05       0  4767.5     .16       0  4927.4      .1       0
  4991.6     .16       0  4991.9     .07       0  5002.9     .16       0
  5154.4     .05       0
Bank Sta=4893.51,5126.46
XS Rating Curve= 0 ,0
Exp/Cntr=0.3,0.1

Type RM Length L Ch R = 1 ,31839   ,385,385,385
BEGIN DESCRIPTION:
CHILTIPIN CREEK 63.0
END DESCRIPTION:
XS GIS Cut Line= 3
      2033825.01     13501225.02        2033425.       13500225.
      2032224.99       13499525.
#Sta/Elev= 30
  3948.8  525.76  4110.4  522.55  4125.2  520.04  4149.4  519.93  4154.8  521.43
  4218.1  520.31  4580.2  511.08  4787.1  507.05 4807.15506.7738  4873.7  506.06
  4896.6  504.57  4908.7  506.06  4918.1   505.3  4927.6  502.82    4933  503.13
  4939.7  501.42  4957.2  500.17  4998.8  500.01  4999.5  499.21  5009.9  500.01
  5055.2  502.57  5070.9  501.78  5113.9  502.77  5129.6  504.77 5134.02506.7743
  5141.6  507.94  5206.6  507.32  5888.8  512.74    6284  520.85  6415.1  525.12
#Mann= 5 ,-1 , 0
  3948.8     .05       0  4787.1      .1       0  4998.8     .07       0
  5009.9      .1       0  5206.6     .05       0
Bank Sta=4807.15,5134.02
XS Rating Curve= 0 ,0
Exp/Cntr=0.3,0.1

Type RM Length L Ch R = 1 ,31454   ,138,138,138
BEGIN DESCRIPTION:
CHILTIPIN CREEK 62.0
END DESCRIPTION:
XS GIS Cut Line= 4
      2033977.97     13501407.52      2033925.89     13500270.41
      2033379.01     13499667.11      2032094.28     13499454.44
#Sta/Elev= 30
    3415  530.67  3928.1  521.03  3948.1  518.87  3958.1  516.47  3988.1  516.02
  3998.1  518.39  4029.7  518.08  4178.3  513.61  4238.4  513.57  4408.6  508.85
  4572.2  508.08    4599506.5908  4714.5  504.61  4750.4  504.36  4751.2  503.56
  4761.5  504.36  4897.9  505.89    4954  505.34  4982.4   506.4  4989.8  505.11
  5015.2  505.76  5053.3  505.89  5060.1  504.85 5100.71506.5911  5381.8  509.35
  5470.2  508.31  5963.4  512.81  5989.9  514.35  6425.8  522.17  6669.8  530.16
#Mann= 5 ,-1 , 0
    3415     .05       0  4714.5      .1       0  4750.4     .07       0
  4761.5      .1       0  5015.2     .05       0
Bank Sta=4599,5100.71
XS Rating Curve= 0 ,0
Exp/Cntr=0.3,0.1

Type RM Length L Ch R = 1 ,31316   ,488,488,488
BEGIN DESCRIPTION:
CHILTIPIN CREEK 61.0
END DESCRIPTION:
XS GIS Cut Line= 4
      2034030.05     13501420.55      2033960.61     13500101.14
       2033452.8     13499580.31      2032074.98       13499425.
#Sta/Elev= 30
    3356  532.15  3601.9   526.1  3932.6   520.1  3952.4  515.58  3982.4  514.79
  4002.4  517.68  4117.8  514.71  4172.7  514.41    4373  508.81  4503.4  508.12
 4606.72506.0087  4770.3  505.77  4856.8  504.38  4857.5  503.58  4867.2  503.58
  4867.9  504.38  4925.9  505.42 5147.53506.0088  5343.1  508.96  5452.8  509.12
    5483  507.02  5533.3  507.18  5553.4  509.28  5573.5  509.97  5694.3  509.37
  6026.4  512.52  6031.9   513.8  6227.6  515.94    6449  520.68  6791.2  531.21
#Mann= 3 ,-1 , 0
    3356     .05       0  4856.8     .04       0  4867.9     .05       0
Bank Sta=4606.72,5147.53
XS Rating Curve= 0 ,0
Exp/Cntr=0.3,0.1

Type RM Length L Ch R = 1 ,30828   ,50,50,50
BEGIN DESCRIPTION:
CHILTIPIN CREEK 60.0
END DESCRIPTION:
XS GIS Cut Line= 6
        2034025.     13500875.05      2034082.76     13499735.39
      2034140.06     13499707.61      2034143.53     13499664.21
      2034117.49      13499634.7      2033074.99     13498024.98
#Sta/Elev= 30
  3779.1  520.17  3839.2  519.18  3849.2  518.15  3859.3  514.67  3899.3  513.87
  3919.3  517.12  4189.7  510.11  4504.4  505.07 4604.91504.0117  4840.5  503.58
  4850.5  501.58  4865.6  503.31  4917.9  501.84  4930.4  502.96    4936  501.22
  4975.6  503.37  4981.1  501.67    5001  500.56  5001.7  499.76  5012.2  500.56
  5024.5  501.93  5032.9  500.71  5047.1  503.47 5212.86504.0118  5718.6  507.62
  6197.5  511.96  6442.2  517.07  6484.2  516.58  6680.9  518.98  6984.6  526.35
#Mann= 6 ,-1 , 0
  3779.1     .05       0  4504.4      .1       0    5001     .07       0
  5012.2      .1       0  5718.6     .05       0  6484.2      .1       0
Bank Sta=4604.91,5212.86
XS Rating Curve= 0 ,0
Exp/Cntr=0.3,0.1

Type RM Length L Ch R = 1 ,30778   ,28,28,28
BEGIN DESCRIPTION:
CHILTIPIN CREEK 59.0
END DESCRIPTION:
XS GIS Cut Line= 6
      2034098.39     13500751.03      2034112.28     13499782.27
        2034147.     13499730.18      2034192.14     13499688.52
      2034164.36     13499653.79      2033643.55     13498733.69
#Sta/Elev= 30
  3908.2  517.32  3924.2  516.82  3934.2  512.96  3964.2  512.39  3984.2  515.82
  4114.3  511.73  4274.3  509.26  4294.3  507.63  4324.3  508.35  4354.3  506.79
  4464.3  505.21  4524.3  505.72  4544.3  504.62 4707.16503.1605  4808.7  501.85
  4809.4  501.05  4819.9  501.85  4854.3  502.08  4873.2  504.18  4927.5  505.19
  5001.1   503.8  5008.3  505.06  5066.6   504.4  5118.5  501.91 5175.12503.1605
  5242.5  504.79    5280  504.13  5468.7  506.19    5679   506.9  6102.9  510.23
#Mann= 5 ,-1 , 0
  3908.2     .05       0  4464.3      .1       0  4808.7     .07       0
  4819.9      .1       0    5679     .05       0
Bank Sta=4707.16,5175.12
XS Rating Curve= 0 ,0
Exp/Cntr=0.3,0.1

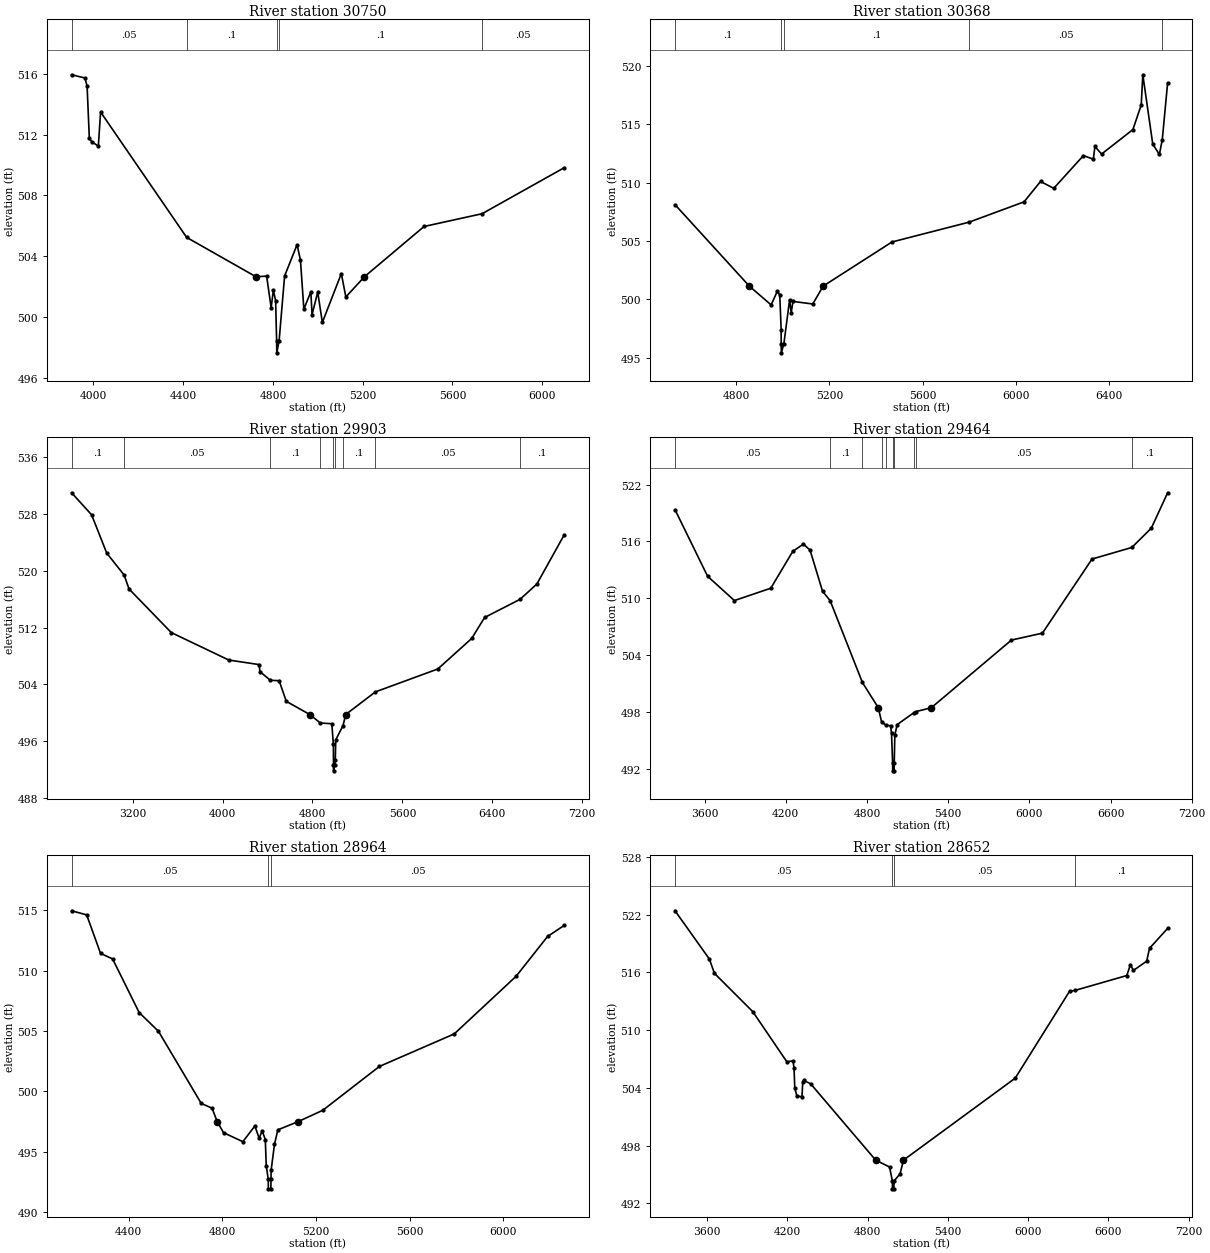
Type RM Length L Ch R = 1 ,30750   ,382,382,382
BEGIN DESCRIPTION:
CHILTIPIN CREEK 58.0
END DESCRIPTION:
XS GIS Cut Line= 6
      2034153.94     13500744.03      2034133.11     13499778.79
      2034202.99     13499733.33      2034226.86     13499667.68
      2034212.97      13499553.1      2033688.64      13498747.5
#Sta/Elev= 30
  3902.9  515.94  3961.9  515.73  3971.9  515.21  3981.9  511.76  3991.9  511.54
    4022  511.24    4032  513.49  4415.7  505.23 4724.27502.6431  4772.1  502.68
  4792.1   500.6  4802.1  501.76  4812.1  501.06  4816.5  498.43  4817.2  497.63
  4827.7  498.43  4852.1  502.69  4907.6  504.75  4922.7  503.74  4937.9  500.51
  4969.1  501.65  4974.4  500.14  4999.7  501.63  5020.3  499.63  5104.9  502.85
    5125  501.31 5208.05502.6432  5473.6  505.95  5732.1  506.79  6098.2  509.82
#Mann= 5 ,-1 , 0
  3902.9     .05       0  4415.7      .1       0  4816.5     .07       0
  4827.7      .1       0  5732.1     .05       0
Bank Sta=4724.27,5208.05
XS Rating Curve= 0 ,0
Exp/Cntr=0.3,0.1

Type RM Length L Ch R = 1 ,30368   ,465,465,465
BEGIN DESCRIPTION:
CHILTIPIN CREEK 57.0
END DESCRIPTION:
XS GIS Cut Line= 3
      2034771.77     13499891.72        2034525.       13499475.
      2033424.99     13498274.99
#Sta/Elev= 30
  4538.4  508.12 4857.04501.1318  4950.6  499.52  4977.8  500.73  4987.6  500.35
  4993.5  497.38  4993.7  496.21  4994.3  495.41  5005.3  496.21  5029.8  499.97
  5036.6  498.83    5044  499.82  5129.1   499.6 5173.53501.1319  5468.8  504.92
  5799.5  506.62  6034.9  508.36  6105.8  510.11  6162.2  509.52  6289.6  512.33
  6332.1  512.02  6338.9  513.11  6367.3  512.46  6501.7  514.56  6537.4  516.67
  6544.2  519.26  6586.8  513.32  6615.1  512.43  6627.6  513.68  6650.6  518.57
#Mann= 5 ,-1 , 0
  4538.4      .1       0  4993.7     .07       0  5005.3      .1       0
  5799.5     .05       0  6627.6      .1       0
Bank Sta=4857.04,5173.53
XS Rating Curve= 0 ,0
Exp/Cntr=0.3,0.1

Type RM Length L Ch R = 1 ,29903   ,439,439,439
BEGIN DESCRIPTION:
CHILTIPIN CREEK 56.0
END DESCRIPTION:
XS GIS Cut Line= 3
        2036325.     13500974.99        2034825.       13499175.
      2033174.99     13497974.99
#Sta/Elev= 30
  2656.8     531  2834.5   527.9  2969.2   522.5  3124.2   519.4  3167.7  517.44
  3543.9  511.29  4055.5  507.42  4324.9  506.78  4332.7  505.79  4425.5  504.56
  4503.3  504.51    4567   501.6 4776.55499.7335  4870.8  498.54  4971.9  498.44
  4986.2  495.52  4986.9   492.6  4987.5   491.8  4998.6   492.6    5003  493.31
  5007.2  496.17  5072.1  498.18 5095.23499.7334  5359.8  502.93  5915.3  506.16
  6216.7  510.46  6331.8  513.42    6647  515.98  6796.3  518.13  7040.1  525.07
#Mann= 9 ,-1 , 0
  2656.8      .1       0  3124.2     .05       0  4425.5      .1       0
  4870.8     .16       0  4986.9     .07       0  4998.6     .16       0
  5072.1      .1       0  5359.8     .05       0    6647      .1       0
Bank Sta=4776.55,5095.23
XS Rating Curve= 0 ,0
Exp/Cntr=0.3,0.1

Type RM Length L Ch R = 1 ,29464   ,500,500,500
BEGIN DESCRIPTION:
CHILTIPIN CREEK 55.0
END DESCRIPTION:
XS GIS Cut Line= 3
      2036324.99     13499974.99        2035125.       13498875.
      2033325.03     13497975.01
#Sta/Elev= 30
  3381.6  519.35  3622.4  512.34  3820.3  509.78  4089.2  511.08  4251.9  514.96
  4330.3  515.73  4379.6  515.09  4471.5  510.77    4528  509.77  4766.2  501.16
 4883.78498.4969  4908.5  496.98  4943.8  496.64    4974   496.6  4981.4  495.84
  4989.7  492.65  4990.3  491.85  5000.9  491.85  5001.5  492.65  5006.1  495.63
  5023.4  496.72  5146.5  497.97  5161.8  498.09 5275.77498.4965  5867.6  505.62
  6096.8  506.35  6462.9  514.15  6757.2  515.37  6901.7  517.41  7021.9  521.13
#Mann= 10 ,-1 , 0
  3381.6     .05       0    4528      .1       0  4766.2     .05       0
  4908.5      .1       0  4943.8     .16       0  4989.7     .07       0
  5001.5     .16       0  5146.5      .1       0  5161.8     .05       0
  6757.2      .1       0
Bank Sta=4883.78,5275.77
XS Rating Curve= 0 ,0
Exp/Cntr=0.3,0.1

Type RM Length L Ch R = 1 ,28964   ,312,312,312
BEGIN DESCRIPTION:
CHILTIPIN CREEK 54.0
END DESCRIPTION:
XS GIS Cut Line= 3
      2035674.99     13499324.95        2035475.       13498525.
        2034675.       13497525.
#Sta/Elev= 30
  4155.8  514.97  4220.2  514.63  4279.4  511.44    4331  510.98  4444.4  506.54
  4526.8  504.99  4709.8  499.01  4756.2  498.61 4777.76497.5087  4805.1  496.58
  4887.6  495.84  4939.1  497.14  4957.2  496.12  4970.1  496.74  4983.6  496.01
  4987.6  493.85  4996.1  492.73  4996.7  491.93  5007.3  491.93  5007.9  492.73
  5008.4  493.46  5022.8  495.62  5037.2  496.82  5125.1497.5085  5229.3  498.44
    5471  502.07  5791.2  504.77  6055.3  509.54  6189.8  512.84    6261  513.76
#Mann= 3 ,-1 , 0
  4155.8     .05       0  4996.1     .03       0  5007.9     .05       0
Bank Sta=4777.76,5125.1
XS Rating Curve= 0 ,0
Exp/Cntr=0.3,0.1

Type RM Length L Ch R = 1 ,28652   ,141,141,141
BEGIN DESCRIPTION:
CHILTIPIN CREEK 53.0
END DESCRIPTION:
XS GIS Cut Line= 3
      2036524.99     13499774.99      2035718.13     13498330.96
      2034125.02     13497075.02
#Sta/Elev= 30
  3359.9  522.41  3616.9  517.39  3654.6  515.91  3941.3  511.93  4196.1  506.72
  4241.9  506.82  4249.7  506.07  4255.4  503.96  4271.4  503.16  4309.1  503.09
  4314.8  504.61  4322.1  504.79  4374.2  504.43 4860.14496.5025  4963.6  495.79
  4985.1  494.32  4985.6  493.52  4996.3  493.52  4996.9  494.32  5042.5  495.08
 5067.82496.5025  5903.5  505.02  6309.2  514.04  6351.2  514.14  6737.1  515.68
  6764.5  516.81    6787  516.21  6886.4  517.18  6907.2  518.51  7042.7  520.58
#Mann= 4 ,-1 , 0
  3359.9     .05       0  4985.1     .03       0  4996.9     .05       0
  6351.2      .1       0
Bank Sta=4860.14,5067.82
XS Rating Curve= 0 ,0
Exp/Cntr=0.3,0.1

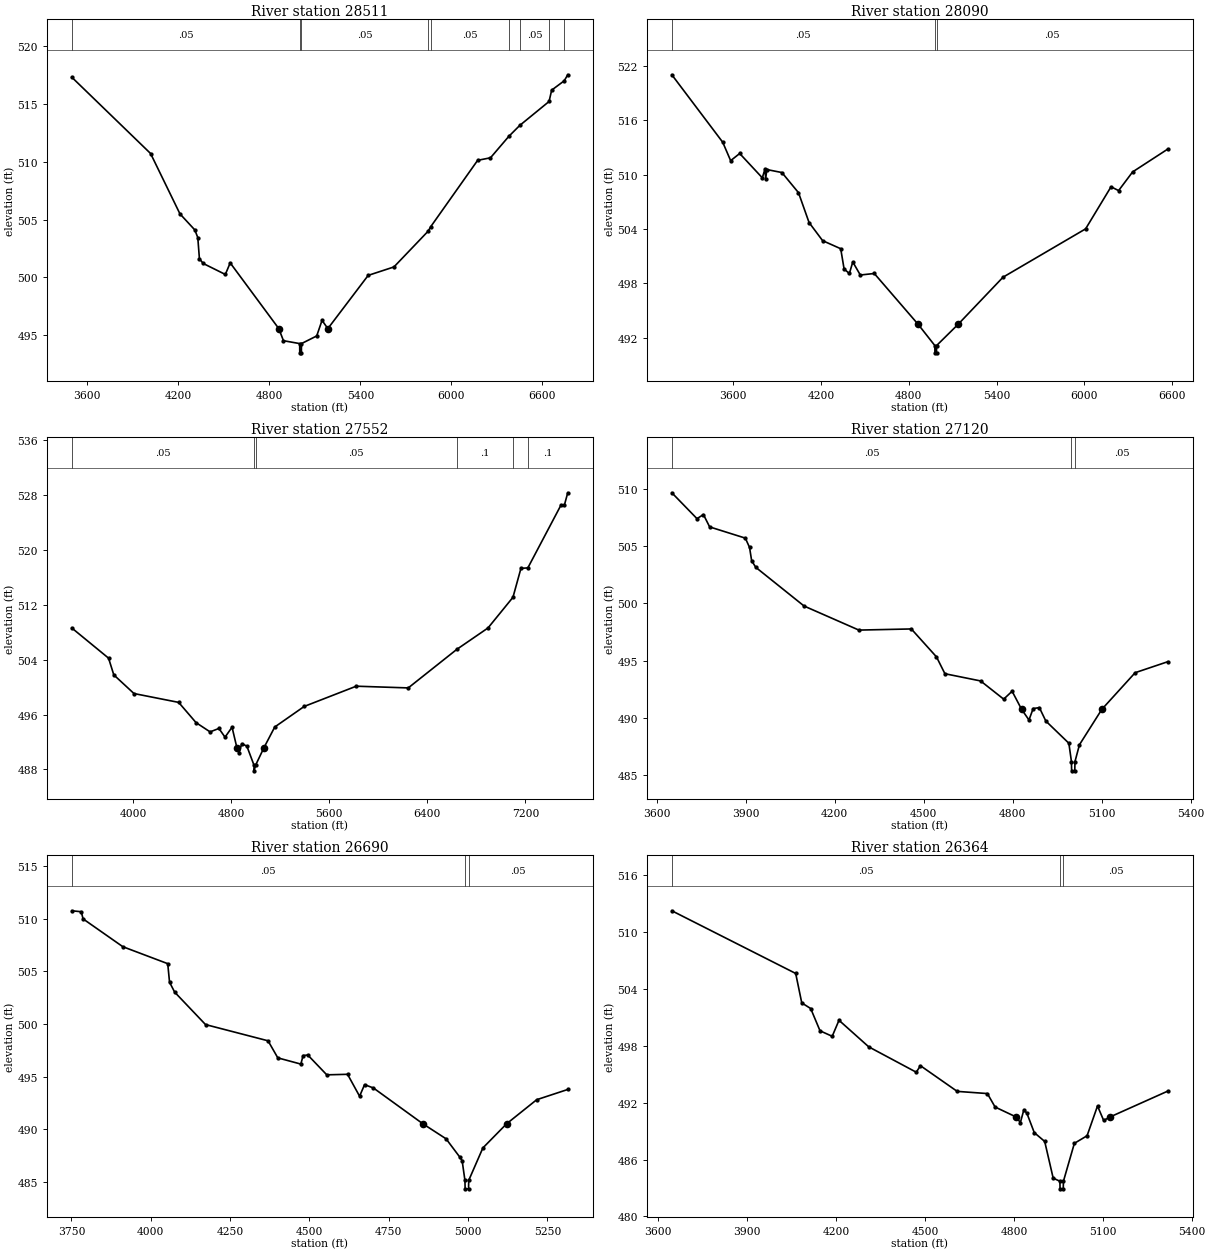
Type RM Length L Ch R = 1 ,28511   ,421,421,421
BEGIN DESCRIPTION:
CHILTIPIN CREEK 52.0
END DESCRIPTION:
XS GIS Cut Line= 4
      2036474.25     13499582.52      2036066.27     13498497.48
      2035367.49     13497763.97      2034578.75     13497001.24
#Sta/Elev= 30
  3497.6  517.32  4017.1  510.72  4210.7   505.5  4308.7  504.11  4328.3  503.45
    4339  501.62  4363.9  501.21  4509.9  500.26  4541.9  501.26 4862.35495.5749
    4893  494.53    5000  494.28  5000.5  493.48  5011.2  493.48  5011.8  494.28
  5112.2  494.94  5147.4  496.29 5185.59495.5751  5451.6  500.18  5621.4  500.91
  5847.3  504.01  5864.4   504.4  6173.1  510.13  6257.8  510.35  6378.4   512.2
  6450.8  513.15    6644  515.22    6661   516.2  6743.9  517.01  6767.1  517.53
#Mann= 9 ,-1 , 0
  3497.6     .05       0    5000     .04       0  5011.8     .05       0
  5847.3     .08       0  5864.4     .05       0  6378.4     .08       0
  6450.8     .05       0    6644     .08       0  6743.9     .05       0
Bank Sta=4862.35,5185.59
XS Rating Curve= 0 ,0
Exp/Cntr=0.3,0.1

Type RM Length L Ch R = 1 ,28090   ,538,538,538
BEGIN DESCRIPTION:
CHILTIPIN CREEK 51.0
END DESCRIPTION:
XS GIS Cut Line= 3
      2036574.99     13499724.97        2036125.       13497925.
      2034799.98     13497149.99
#Sta/Elev= 30
  3180.6     521  3528.5  513.56  3582.6  511.53  3644.4  512.32    3799  509.64
  3817.1  510.59  3822.2  509.56    3830  510.55    3933  510.22  4046.4     508
  4118.6  504.71  4211.3  502.71    4335  501.82  4358.2  499.58  4394.3  499.09
  4417.5  500.36    4469  498.92  4564.4  499.09 4864.47493.4804  4978.5  491.14
  4979.1  490.34  4989.8  490.34  4990.3  491.14 5137.35493.4805  5444.6  498.68
  6009.1  504.01  6182.9  508.65  6234.6  508.23  6330.5  510.29    6571  512.81
#Mann= 3 ,-1 , 0
  3180.6     .05       0  4978.5     .03       0  4990.3     .05       0
Bank Sta=4864.47,5137.35
XS Rating Curve= 0 ,0
Exp/Cntr=0.3,0.1

Type RM Length L Ch R = 1 ,27552   ,432,432,432
BEGIN DESCRIPTION:
CHILTIPIN CREEK 50.0
END DESCRIPTION:
XS GIS Cut Line= 3
      2037675.04     13498475.03        2036475.       13497575.
      2034675.02     13495775.02
#Sta/Elev= 30
  3499.3  508.63  3799.3  504.23  3842.1  501.79  4006.6  499.07  4371.2  497.78
  4512.9  494.83  4627.5  493.48  4699.3  493.98  4749.3  492.71  4806.6  494.16
  4845.8491.2004  4862.9  490.38  4885.8  491.76  4927.5   491.4  4986.2   488.6
  4986.7   487.8    4998   488.6  5067.6491.2002  5154.9  494.19  5395.3  497.19
  5819.6  500.14  6243.9  499.89  6640.7  505.52  6894.4  508.63    7098   513.1
  7163.1  517.32  7219.5  517.39  7488.4   526.5  7516.6  526.49  7544.9  528.34
#Mann= 6 ,-1 , 0
  3499.3     .05       0  4986.2     .03       0    4998     .05       0
  6640.7      .1       0    7098     .08       0  7219.5      .1       0
Bank Sta=4845.8,5067.6
XS Rating Curve= 0 ,0
Exp/Cntr=0.3,0.1

Type RM Length L Ch R = 1 ,27120   ,430,430,430
BEGIN DESCRIPTION:
CHILTIPIN CREEK 49.0
END DESCRIPTION:
XS GIS Cut Line= 3
      2037724.97     13498374.97        2036825.       13497375.
      2036643.95     13497103.43
#Sta/Elev= 30
  3651.7  509.66  3736.5   507.4  3758.2  507.76  3779.1  506.68  3899.4   505.7
  3913.6  504.89  3920.7  503.73  3934.6  503.15  4097.5  499.77  4282.1  497.67
  4458.9  497.77  4543.7  495.33  4572.1  493.86  4692.4  493.23  4770.2  491.64
  4798.6  492.33 4830.45490.7576  4855.4  489.82  4869.6  490.82  4890.5   490.9
  4912.2  489.73  4989.9  487.79  4998.6  486.18  4999.2  485.38  5009.9  485.38
  5010.4  486.18  5025.6  487.66 5101.27490.7575  5213.3  493.95  5323.4  494.91
#Mann= 3 ,-1 , 0
  3651.7     .05       0  4998.6     .03       0  5010.4     .05       0
Bank Sta=4830.45,5101.27
XS Rating Curve= 0 ,0
Exp/Cntr=0.3,0.1

Type RM Length L Ch R = 1 ,26690   ,326,326,326
BEGIN DESCRIPTION:
CHILTIPIN CREEK 48.0
END DESCRIPTION:
XS GIS Cut Line= 3
      2037825.01     13498325.03        2037225.       13497225.
      2037005.82     13497005.82
#Sta/Elev= 30
  3750.9  510.75  3780.8  510.66  3786.5  509.98  3911.8  507.34  4053.3  505.73
    4059  503.97  4075.1  503.03  4172.4  499.95  4369.4  498.41  4400.2  496.79
  4472.8   496.2  4479.9  497.01  4494.7  497.06  4554.5  495.18    4620  495.23
  4657.9  493.15  4673.6  494.25  4701.6  493.93 4857.55490.5304  4930.4  489.11
    4974  487.36  4981.1  487.03  4989.9  485.16  4990.5  484.36  5001.3  484.36
  5001.8  485.16  5046.4  488.24 5121.08490.5303  5216.1  492.82  5313.9  493.79
#Mann= 3 ,-1 , 0
  3750.9     .05       0  4989.9     .03       0  5001.8     .05       0
Bank Sta=4857.55,5121.08
XS Rating Curve= 0 ,0
Exp/Cntr=0.3,0.1

Type RM Length L Ch R = 1 ,26364   ,64,64,64
BEGIN DESCRIPTION:
CHILTIPIN CREEK 47.0
END DESCRIPTION:
XS GIS Cut Line= 4
      2037867.06     13498382.04      2037591.01     13497194.53
      2037377.47     13496939.32      2037285.17     13496860.21
#Sta/Elev= 30
  3645.8  512.24  4063.7  505.63  4084.2  502.52  4114.3  501.93  4145.8  499.58
  4186.9     499  4209.8  500.69  4310.1  497.89  4470.6  495.21  4484.6   495.9
  4608.7  493.19  4710.5  492.96  4736.5  491.54 4807.69490.4875  4821.8   489.9
  4833.7  491.26    4844  490.87  4868.7  488.84  4903.9  487.91  4932.5  484.04
  4955.2  483.71  4955.7  482.91  4966.5  482.91  4967.1  483.71    5004  487.71
  5046.9  488.51  5082.1  491.65  5102.9  490.12 5124.06490.4875  5319.3  493.22
#Mann= 3 ,-1 , 0
  3645.8     .05       0  4955.2     .03       0  4967.1     .05       0
Bank Sta=4807.69,5124.06
XS Rating Curve= 0 ,0
Exp/Cntr=0.3,0.1

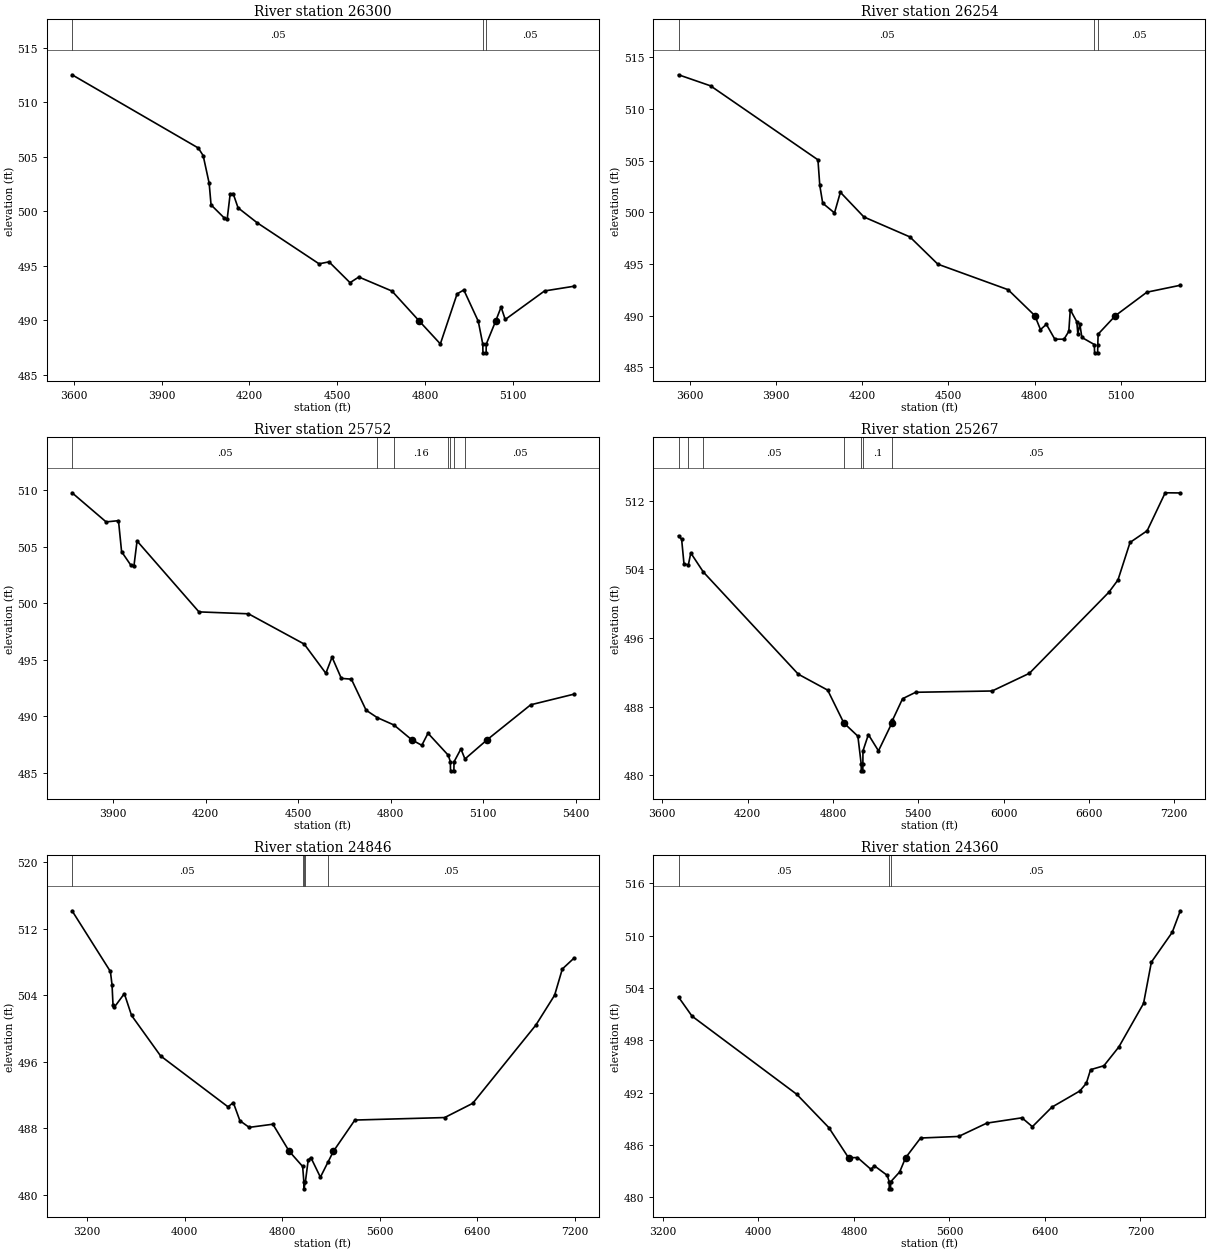
Type RM Length L Ch R = 1 ,26300   ,46,46,46
BEGIN DESCRIPTION:
CHILTIPIN CREEK 46.0
END DESCRIPTION:
XS GIS Cut Line= 5
       2037893.1     13498392.46       2037648.3     13497288.28
      2037596.22     13497095.57      2037439.97     13496944.53
      2037316.72     13496831.74
#Sta/Elev= 30
  3594.1  512.54  4025.5  505.82  4042.2  505.12  4062.7  502.58  4069.1   500.6
  4112.7  499.44  4124.1  499.27  4134.4  501.59  4144.6  501.64  4161.4  500.33
  4226.6  498.96  4438.3  495.19  4472.4  495.37  4544.1  493.46  4574.2  493.98
  4687.5  492.69 4781.46 489.916  4852.8  487.84    4910  492.43    4933  492.79
  4982.4  489.92  4997.8  487.82  4998.4  487.02  5009.2  487.02  5009.7  487.82
 5041.57489.9156  5060.4  491.22  5074.5  490.08  5208.9   492.7  5309.1  493.13
#Mann= 3 ,-1 , 0
  3594.1     .05       0  4997.8     .03       0  5009.7     .05       0
Bank Sta=4781.46,5041.57
XS Rating Curve= 0 ,0
Exp/Cntr=0.3,0.1

Type RM Length L Ch R = 1 ,26254   ,502,502,502
BEGIN DESCRIPTION:
CHILTIPIN CREEK 45.0
END DESCRIPTION:
XS GIS Cut Line= 3
      2037924.99     13498424.97        2037625.       13497075.
       2037369.6     13496815.78
#Sta/Elev= 30
  3560.3   513.3  3671.7  512.23  4045.6  505.07    4052   502.6  4062.2  500.87
  4103.2  499.93  4123.7  501.93  4205.6  499.54  4365.7  497.61    4463  494.97
  4707.6   492.5 4800.53489.9927  4820.3  488.64  4840.8  489.15  4870.2  487.71
  4902.2  487.71  4918.9  488.47    4924  490.56  4946.7   489.4  4950.3  488.24
  4957.3  489.17  4964.4  487.88  5007.9  487.19  5008.5  486.39  5019.3  486.39
  5019.8  487.19    5021   488.2 5081.27489.9924  5190.7  492.26  5307.1  492.93
#Mann= 3 ,-1 , 0
  3560.3     .05       0  5007.9     .03       0  5019.8     .05       0
Bank Sta=4800.53,5081.27
XS Rating Curve= 0 ,0
Exp/Cntr=0.3,0.1

Type RM Length L Ch R = 1 ,25752   ,485,485,485
BEGIN DESCRIPTION:
CHILTIPIN CREEK 44.0
END DESCRIPTION:
XS GIS Cut Line= 3
        2037925.       13498175.        2038025.       13496975.
      2037726.08     13496676.08
#Sta/Elev= 30
  3766.9  509.79  3877.3  507.21  3917.4  507.32  3927.5  504.57  3957.6  503.37
  3967.6  503.33  3977.6  505.52  4178.3  499.24  4338.9  499.07  4519.5  496.39
  4589.7   493.8  4609.8  495.23  4639.9  493.35  4672.5  493.28  4720.2  490.53
    4756  489.88  4810.6  489.22 4868.16487.9132  4900.8  487.42  4920.9  488.49
  4986.7  486.54  4993.4  485.96  4993.9  485.16  5004.8  485.16  5005.3  485.96
  5027.6   487.1  5040.7  486.21 5112.61487.9132  5253.9  491.01  5393.8  491.95
#Mann= 7 ,-1 , 0
  3766.9     .05       0    4756      .1       0  4810.6     .16       0
  4986.7      .1       0  4993.4     .07       0  5005.3      .1       0
  5040.7     .05       0
Bank Sta=4868.16,5112.61
XS Rating Curve= 0 ,0
Exp/Cntr=0.3,0.1

Type RM Length L Ch R = 1 ,25267   ,421,421,421
BEGIN DESCRIPTION:
CHILTIPIN CREEK 43.0
END DESCRIPTION:
XS GIS Cut Line= 3
      2037974.98     13498075.04        2038475.       13496875.
      2036825.04     13495375.03
#Sta/Elev= 30
  3713.8  507.92  3735.5  507.53  3752.3  504.63  3782.9  504.54    3800  505.92
  3888.4   503.7  4556.1  491.79    4763  489.93  4875.4  486.14 4878.85486.0702
  4975.4  484.56  4998.7  481.32  4999.2  480.52  5010.1  480.52  5010.6  481.32
  5011.1  482.84  5049.3  484.75  5120.3  482.85 5213.95486.0699  5218.4   486.4
  5289.9  488.93  5381.8  489.68  5919.7  489.83  6181.8  491.89  6741.3  501.35
  6804.9  502.77    6890  507.15  7010.3  508.51  7137.3  512.94  7243.7  512.92
#Mann= 7 ,-1 , 0
  3713.8     .05       0  3782.9     .08       0  3888.4     .05       0
  4875.4      .1       0  4998.7     .07       0  5010.6      .1       0
  5218.4     .05       0
Bank Sta=4878.85,5213.95
XS Rating Curve= 0 ,0
Exp/Cntr=0.3,0.1

Type RM Length L Ch R = 1 ,24846   ,486,486,486
BEGIN DESCRIPTION:
CHILTIPIN CREEK 42.0
END DESCRIPTION:
XS GIS Cut Line= 3
      2038124.99     13498525.01        2038875.       13496725.
      2037075.04     13495525.03
#Sta/Elev= 30
  3077.3  514.15  3391.5  506.85    3405  505.24  3413.1  502.77  3423.4  502.55
  3505.8  504.19  3564.8  501.57  3803.1   496.7  4355.6  490.58    4399  491.09
  4453.1  488.91    4529  488.11  4723.4  488.49 4856.56485.2481  4967.4  483.41
  4977.5  481.52    4978  480.72  4989.4  481.52  5012.7  484.15  5034.8  484.48
  5112.9  482.12  5177.4     484  5220.2 485.248  5395.4  488.99  6131.5  489.29
  6361.4     491  6879.7  500.42  7032.9     504    7096  507.15  7190.6  508.44
#Mann= 5 ,-1 , 0
  3077.3     .05       0  4967.4      .1       0  4977.5     .07       0
  4989.4      .1       0  5177.4     .05       0
Bank Sta=4856.56,5220.2
XS Rating Curve= 0 ,0
Exp/Cntr=0.3,0.1

Type RM Length L Ch R = 1 ,24360   ,442,442,442
BEGIN DESCRIPTION:
CHILTIPIN CREEK 41.0
END DESCRIPTION:
XS GIS Cut Line= 3
      2040474.98     13497724.98        2039275.       13496525.
      2037075.02     13495325.01
#Sta/Elev= 30
  3330.6  502.95  3443.7  500.76  4320.5   491.8  4589.2  487.98 4754.66484.5143
  4829.6  484.54  4942.8  483.18  4971.1  483.59  5079.4  482.49  5095.1  481.75
  5095.6  480.95  5106.7  480.95  5107.2  481.75  5182.8  482.89  5232.4484.5142
    5358  486.78  5676.9  486.96  5912.8  488.49  6207.1   489.1  6294.4  488.08
  6457.7  490.32  6692.1  492.18  6746.2  493.06  6781.8  494.62  6893.4  495.07
  7018.7  497.23  7225.6  502.22  7291.1  506.96  7465.8  510.38  7533.6  512.85
#Mann= 3 ,-1 , 0
  3330.6     .05       0  5095.1     .03       0  5107.2     .05       0
Bank Sta=4754.66,5232.4
XS Rating Curve= 0 ,0
Exp/Cntr=0.3,0.1

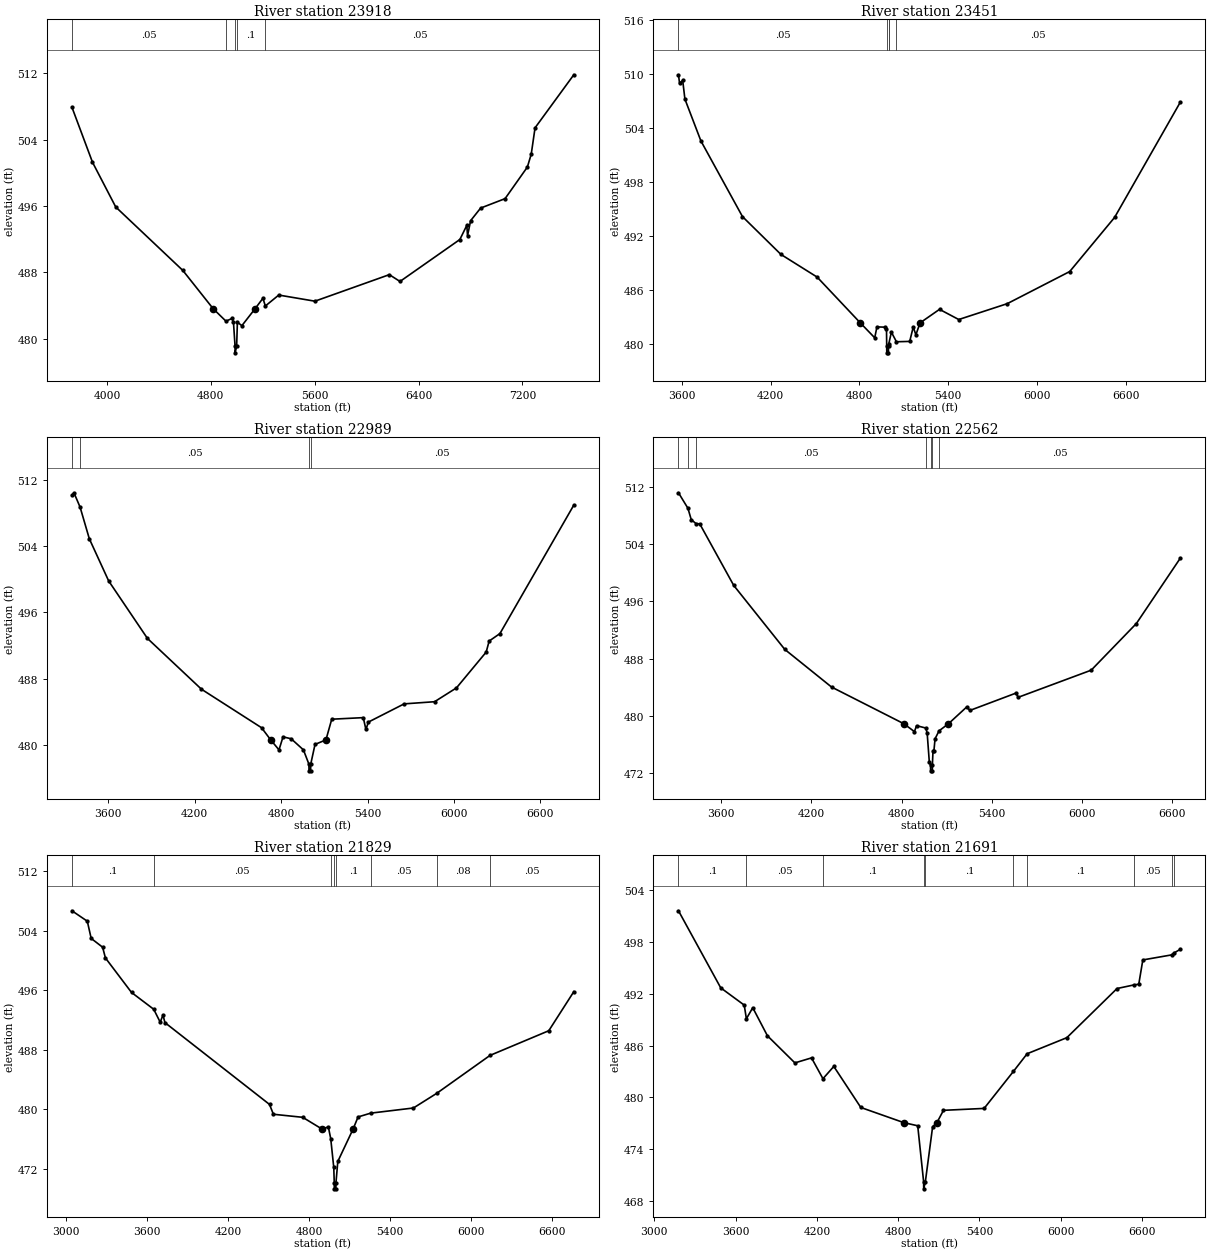
Type RM Length L Ch R = 1 ,23918   ,467,467,467
BEGIN DESCRIPTION:
CHILTIPIN CREEK 40.0
END DESCRIPTION:
XS GIS Cut Line= 3
      2040725.04     13496625.01        2039525.       13496225.
      2037125.04     13495225.02
#Sta/Elev= 30
  3730.5  507.91  3888.7  501.28  4067.8  495.88  4584.4  488.23 4817.43 483.626
  4916.5  482.11  4963.8  482.44  4974.4  481.98  4986.7  479.09  4987.2  478.29
  4998.9  479.09  5004.7  481.98  5039.3  481.57  5141.5 483.626  5201.3  484.87
    5220  483.94  5323.2  485.26  5601.6  484.52  6174.7  487.72    6257   486.9
  6717.9  491.96  6771.6  493.67    6777  492.41  6800.8  494.23  6877.7  495.75
  7066.2  496.89  7237.9   500.7  7267.7  502.26    7297  505.43  7595.4  511.83
#Mann= 5 ,-1 , 0
  3730.5     .05       0  4916.5      .1       0  4986.7     .07       0
  4998.9      .1       0    5220     .05       0
Bank Sta=4817.43,5141.5
XS Rating Curve= 0 ,0
Exp/Cntr=0.3,0.1

Type RM Length L Ch R = 1 ,23451   ,462,462,462
BEGIN DESCRIPTION:
CHILTIPIN CREEK 39.0
END DESCRIPTION:
XS GIS Cut Line= 3
      2040774.97     13496574.98        2039575.       13495775.
      2037774.99       13495025.
#Sta/Elev= 30
  3576.8  509.93  3584.3  508.97  3605.3  509.31  3620.3  507.23  3728.5  502.58
  4009.4  494.18  4269.3  489.98  4514.2  487.46 4806.05482.3758  4903.3  480.72
  4918.3  481.93  4975.4   481.9  4982.9  481.72  4984.3  479.85  4984.8  479.05
    4996  479.05  4996.5  479.85  4998.5  480.06    5016  481.35    5050  480.28
  5139.8  480.32  5163.6  481.92  5181.5  481.05 5209.76482.3759  5341.3  483.88
  5471.3  482.75    5799  484.51  6221.5  488.08  6524.8  494.09    6969  506.89
#Mann= 5 ,-1 , 0
  3576.8     .05       0  4984.3     .07       0  4996.5     .05       0
  4998.5      .1       0    5050     .05       0
Bank Sta=4806.05,5209.76
XS Rating Curve= 0 ,0
Exp/Cntr=0.3,0.1

Type RM Length L Ch R = 1 ,22989   ,427,427,427
BEGIN DESCRIPTION:
CHILTIPIN CREEK 38.0
END DESCRIPTION:
XS GIS Cut Line= 3
      2040825.04     13496475.03        2039625.       13495375.
      2037825.03     13494925.01
#Sta/Elev= 30
  3348.2  510.16  3362.1  510.44  3404.9   508.7  3468.8  504.89  3603.2   499.8
  3872.1  492.87    4247  486.74  4664.4  482.09 4727.73480.6247  4785.3  479.42
  4813.3  480.99  4869.8  480.76  4954.9  479.42  4993.1  477.69  4993.6  476.89
    5005  476.89  5005.5  477.69  5035.4  480.08 5111.12480.6245  5151.4  483.12
  5370.4  483.31  5388.4  481.89  5406.5  482.78  5653.9  484.97  5865.2  485.23
  6017.2   486.9  6223.4  491.22    6244  492.55  6318.7  493.45  6831.5  508.95
#Mann= 4 ,-1 , 0
  3348.2     .08       0  3404.9     .05       0  4993.1     .03       0
  5005.5     .05       0
Bank Sta=4727.73,5111.12
XS Rating Curve= 0 ,0
Exp/Cntr=0.3,0.1

Type RM Length L Ch R = 1 ,22562   ,733,733,733
BEGIN DESCRIPTION:
CHILTIPIN CREEK 37.0
END DESCRIPTION:
XS GIS Cut Line= 3
      2040975.03     13496175.03        2039775.       13494975.
      2038141.57     13494810.44
#Sta/Elev= 30
  3315.4  511.21  3378.3  509.04  3400.3  507.45  3432.5  506.89  3456.9  506.86
  3683.1  498.24  4022.5  489.29  4333.7  484.02 4814.65478.8857  4885.2  477.78
  4899.4  478.61  4961.2  478.28  4970.1  477.53  4984.2  473.53  4992.2  473.09
  4992.7  472.29  5004.1  472.29  5004.6  473.09    5009  475.13    5015  475.13
  5022.5  476.78  5049.1  477.89 5111.83478.8855  5233.6  481.24  5253.7  480.74
  5560.7  483.17  5575.3  482.58  6061.4  486.38  6361.8  492.91  6654.2  502.06
#Mann= 7 ,-1 , 0
  3315.4      .1       0  3378.3     .08       0  3432.5     .05       0
  4961.2      .1       0  4992.2     .07       0  5004.6      .1       0
  5049.1     .05       0
Bank Sta=4814.65,5111.83
XS Rating Curve= 0 ,0
Exp/Cntr=0.3,0.1

Type RM Length L Ch R = 1 ,21829   ,138,138,138
BEGIN DESCRIPTION:
CHILTIPIN CREEK 36.0
END DESCRIPTION:
XS GIS Cut Line= 4
      2041736.81     13495283.04      2040575.39     13494335.15
      2039429.55     13494350.78      2038360.32     13494437.38
#Sta/Elev= 30
  3044.7  506.65  3158.5  505.25  3187.2  502.94  3271.9  501.76  3292.7  500.32
  3485.9  495.69  3650.6  493.43  3698.4   491.7  3719.2  492.65  3733.6  491.64
  4508.3  480.66    4537  479.34  4754.2  478.93 4895.93477.3693  4944.3  477.63
  4961.8  476.07  4984.3   472.2    4988  470.13  4988.5  469.33    5000  469.33
  5000.5  470.13  5014.3  473.01  5127.9477.3692  5164.3  478.98    5258  479.49
  5574.3  480.18  5746.4  482.14    6142  487.24  6577.2  490.55  6762.5  495.79
#Mann= 8 ,-1 , 0
  3044.7      .1       0  3650.6     .05       0  4961.8      .1       0
    4988     .07       0  5000.5      .1       0    5258     .05       0
  5746.4     .08       0    6142     .05       0
Bank Sta=4895.93,5127.9
XS Rating Curve= 0 ,0
Exp/Cntr=0.3,0.1

Type RM Length L Ch R = 1 ,21691   ,889,889,889
BEGIN DESCRIPTION:
CHILTIPIN CREEK 35.0
END DESCRIPTION:
XS GIS Cut Line= 4
      2041747.24     13494855.97      2040781.29     13494196.94
      2039403.68     13494212.56      2038248.77     13494277.59
#Sta/Elev= 30
  3178.9  501.61  3490.7  492.69  3664.2  490.69  3680.1  489.11  3727.1  490.39
  3835.3  487.14  4038.1     484  4160.8  484.58  4245.2  482.17  4325.3  483.59
  4524.6  478.84 4841.61477.0859  4944.6  476.72  4988.3  470.22  4988.8  469.42
  5000.8  470.22  5054.6  476.61  5086.3477.0856  5134.6  478.51  5434.6  478.73
  5650.7  483.01  5752.2  485.06  6045.1  486.92  6415.7  492.61  6538.3  493.02
    6576  493.11    6606  495.92  6817.6   496.5  6837.3  496.74  6882.7  497.15
#Mann= 10 ,-1 , 0
  3178.9      .1       0  3680.1     .05       0  4245.2      .1       0
  4988.3     .07       0  5000.8      .1       0  5650.7     .05       0
  5752.2      .1       0  6538.3     .05       0  6817.6     .08       0
  6837.3     .05       0
Bank Sta=4841.61,5086.3
XS Rating Curve= 0 ,0
Exp/Cntr=0.3,0.1