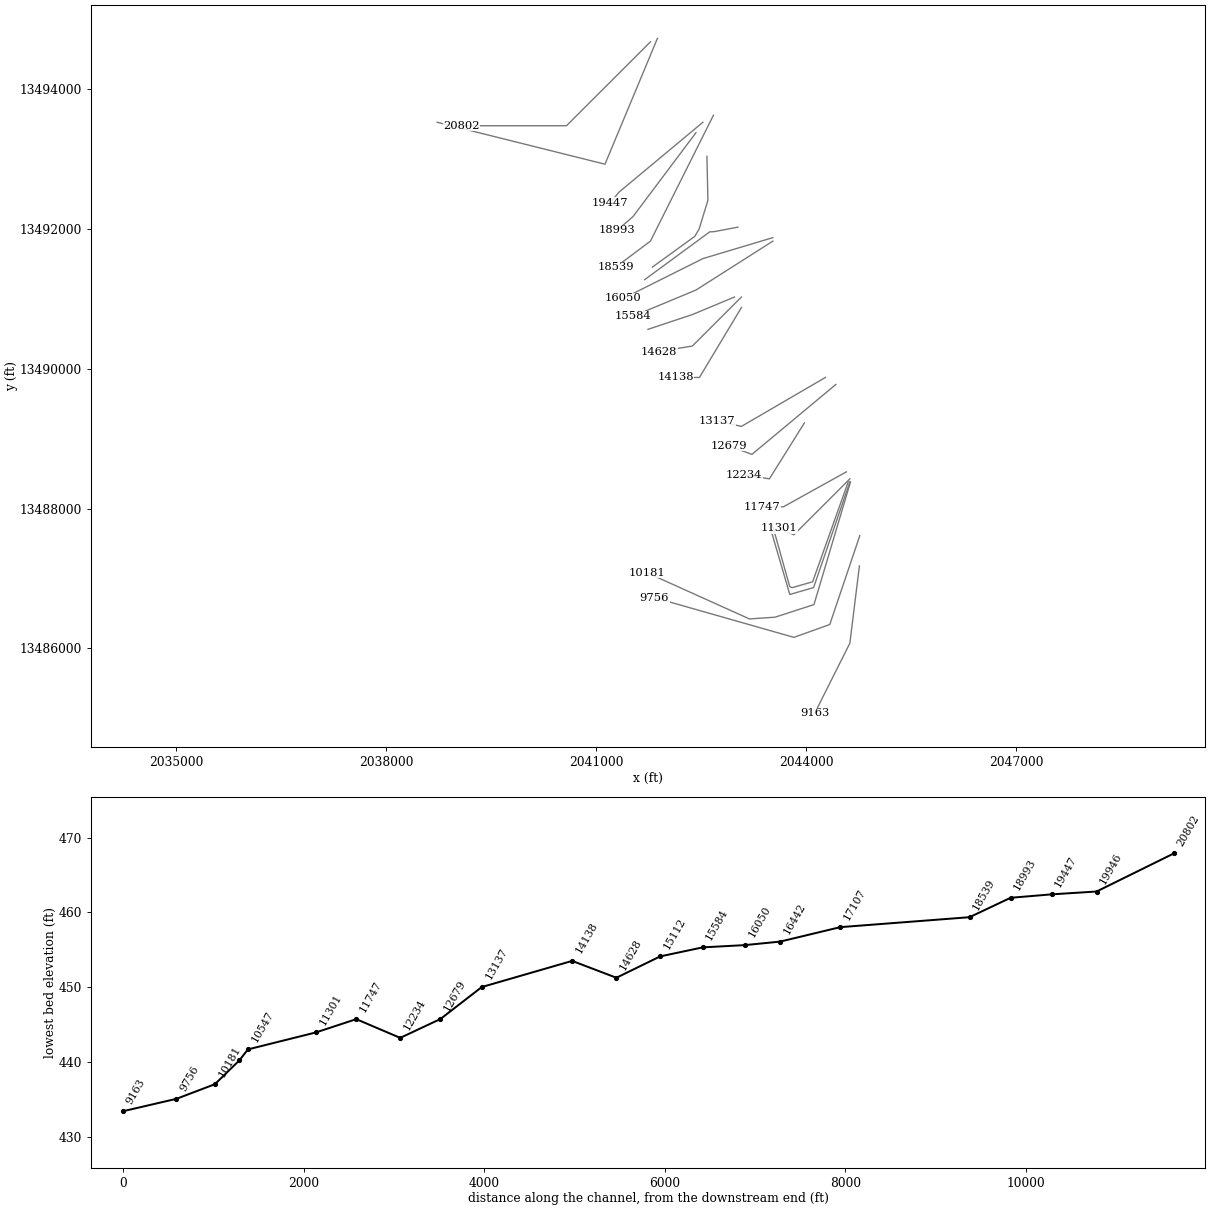
HEC-RAS study CHILTIPIN CREEK.prj: CHILTIPIN CREEK Base Level Engineering

--- CHILTIPIN CREEK.g01 (geometry) --- (continued)

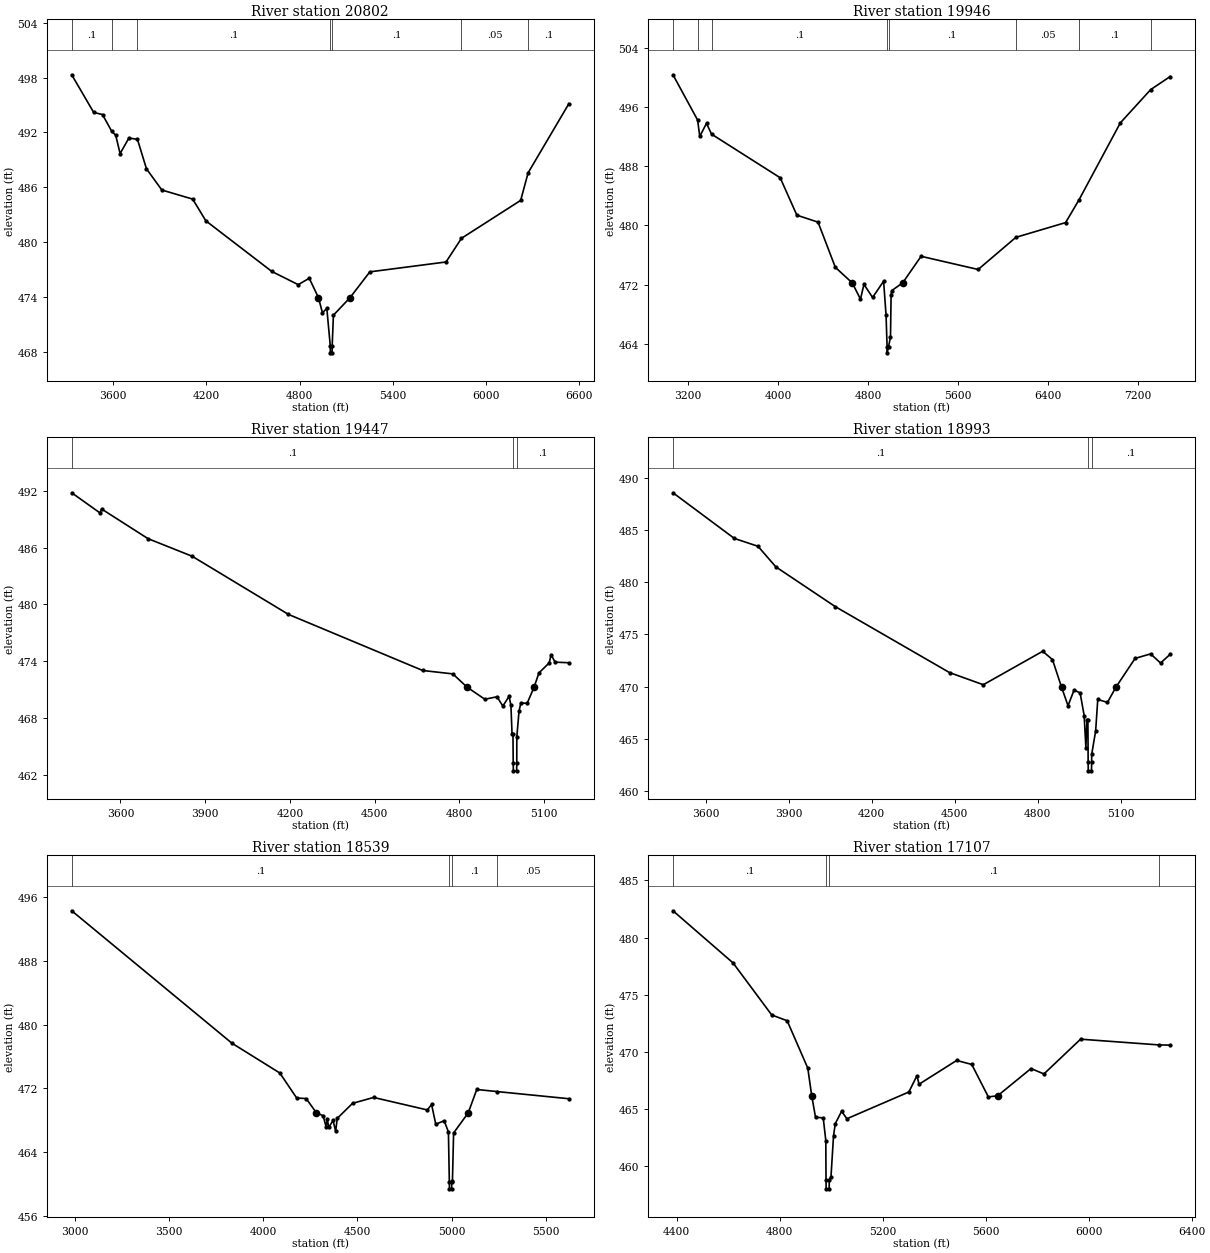
Type RM Length L Ch R = 1 ,20802   ,856,856,856
BEGIN DESCRIPTION:
CHILTIPIN CREEK 34.0
END DESCRIPTION:
XS GIS Cut Line= 3
        2041775.       13494675.        2040575.       13493475.
      2039074.96       13493475.
#Sta/Elev= 30
    3335   498.3  3476.4  494.18    3533  493.95  3592.2  492.12  3617.8  491.69
  3646.1  489.68  3702.7  491.38  3757.6  491.24  3815.8  488.01  3914.8  485.69
  4112.8   484.7  4197.7  482.32  4621.9  476.78  4791.6  475.34  4862.4  476.04
 4921.84473.9129  4947.2  472.26  4975.5  472.74  4997.5  468.68    4998  467.88
  5009.5  467.88    5010  468.68  5017.9     472 5124.61473.9129  5252.1  476.74
  5742.1  477.82  5841.4  480.41  6222.1  484.56  6269.8  487.57  6532.1  495.14
#Mann= 7 ,-1 , 0
    3335      .1       0  3592.2     .08       0  3757.6      .1       0
  4997.5     .07       0    5010      .1       0  5841.4     .05       0
  6269.8      .1       0
Bank Sta=4921.84,5124.61
XS Rating Curve= 0 ,0
Exp/Cntr=0.3,0.1

Type RM Length L Ch R = 1 ,19946   ,499,499,499
BEGIN DESCRIPTION:
CHILTIPIN CREEK 33.0
END DESCRIPTION:
XS GIS Cut Line= 3
      2041874.99     13494724.98        2041125.       13492925.
      2038725.04     13493524.99
#Sta/Elev= 30
  3065.1  500.32  3284.3  494.21  3303.4     492  3363.5  493.77  3408.1  492.31
    4019  486.42  4167.4  481.37  4355.9  480.43  4509.7  474.33 4660.28472.2278
  4733.4  470.04  4764.3  472.03  4841.2  470.26  4939.2  472.46  4960.9  467.92
  4970.3  463.59  4970.8  462.79  4982.9  463.59  5000.5  464.95  5005.9  470.63
  5012.4   471.2 5108.46472.2276  5272.8  475.82  5780.4  474.04  6116.3  478.38
  6558.7  480.37  6678.2  483.45  7045.7  493.83  7315.6  498.32  7488.9  500.08
#Mann= 8 ,-1 , 0
  3065.1      .1       0  3284.3     .08       0  3408.1      .1       0
  4970.3     .07       0  4982.9      .1       0  6116.3     .05       0
  6678.2      .1       0  7315.6     .05       0
Bank Sta=4660.28,5108.46
XS Rating Curve= 0 ,0
Exp/Cntr=0.3,0.1

Type RM Length L Ch R = 1 ,19447   ,454,454,454
BEGIN DESCRIPTION:
CHILTIPIN CREEK 32.0
END DESCRIPTION:
XS GIS Cut Line= 3
      2042525.02     13493525.02        2041325.       13492525.
      2041199.61     13492371.74
#Sta/Elev= 30
  3427.5  491.81  3527.1  489.69  3533.6  490.09  3697.6  486.96  3853.8   485.1
  4194.9  478.95    4670  473.02  4776.8  472.66 4826.92 471.261    4890  469.98
    4933  470.24  4953.8  469.26  4975.9  470.29  4982.4  469.34  4986.3  466.34
  4989.6  466.34  4990.5  463.21    4991  462.41  5002.6  462.41  5003.1  463.21
  5003.2  465.98  5011.1  468.72  5017.6  469.59  5039.8  469.55 5064.42471.2611
  5081.5  472.76  5118.1  473.83  5124.5  474.69  5138.9   473.9  5187.6  473.84
#Mann= 3 ,-1 , 0
  3427.5      .1       0  4990.5     .07       0  5003.1      .1       0
Bank Sta=4826.92,5064.42
XS Rating Curve= 0 ,0
Exp/Cntr=0.3,0.1

Type RM Length L Ch R = 1 ,18993   ,454,454,454
BEGIN DESCRIPTION:
CHILTIPIN CREEK 31.0
END DESCRIPTION:
XS GIS Cut Line= 3
      2042425.02     13493375.02        2041525.       13492175.
      2041300.02     13491980.55
#Sta/Elev= 30
  3481.2  488.56  3703.1  484.19  3788.5  483.44  3853.1  481.47  4067.7  477.67
  4481.2  471.35  4603.1  470.19  4817.7  473.39  4853.1   472.6 4886.11469.9437
  4909.4  468.18  4931.2  469.68  4953.1  469.41  4967.7  467.24  4973.9  464.17
  4978.1  466.86  4981.2  466.86  4982.1  462.75  4982.6  461.95  4994.2  461.95
  4994.7  462.75    4995  463.54  5009.2  465.76  5016.9  468.78    5052   468.5
 5082.26 469.944  5151.8  472.71  5207.8  473.14  5243.9  472.27  5278.6   473.1
#Mann= 3 ,-1 , 0
  3481.2      .1       0  4982.1     .07       0  4994.7      .1       0
Bank Sta=4886.11,5082.26
XS Rating Curve= 0 ,0
Exp/Cntr=0.3,0.1

Type RM Length L Ch R = 1 ,18539   ,1432,1432,1432
BEGIN DESCRIPTION:
CHILTIPIN CREEK 30.0
END DESCRIPTION:
XS GIS Cut Line= 3
        2042675.     13493625.01        2041775.       13491825.
      2041274.89     13491449.92
#Sta/Elev= 30
  2984.2  494.29  3833.9  477.66  4088.3  473.91  4177.7  470.77    4228   470.7
 4282.55468.9048  4317.5  468.55  4334.2  467.14  4339.8  468.11  4348.2  467.08
  4370.6  467.96  4384.5  466.59  4392.9  468.21    4474   470.1  4585.8  470.84
  4870.9  469.27  4893.3  469.96  4915.6  467.48  4960.3  467.91  4982.7   466.5
  4987.6  460.16  4988.1  459.36  4999.7  459.36  5000.2  460.16    5004  460.32
  5010.2  466.38 5087.67468.9047  5133.1  471.84  5240.5  471.58  5621.8  470.68
#Mann= 4 ,-1 , 0
  2984.2      .1       0  4987.6     .07       0  5000.2      .1       0
  5240.5     .05       0
Bank Sta=4282.55,5087.67
XS Rating Curve= 0 ,0
Exp/Cntr=0.3,0.1

Type RM Length L Ch R = 1 ,17107   ,665,665,665
BEGIN DESCRIPTION:
CHILTIPIN CREEK 29.0
END DESCRIPTION:
XS GIS Cut Line= 6
      2042582.12     13493038.19      2042595.57     13492435.76
      2042595.14     13492406.25      2042470.57     13491997.67
      2042408.94     13491893.23      2041802.16     13491453.11
#Sta/Elev= 30
  4386.2  482.35  4619.4  477.79  4769.5  473.24  4829.5  472.73  4909.5  468.59
 4924.75466.1735  4939.5   464.3  4969.5  464.23  4979.5  462.25  4980.3  458.83
  4980.8  458.03  4992.5  458.03    4993  458.83  4999.5  459.06  5009.5  462.68
  5016.4  463.74  5040.8  464.81  5061.4  464.16  5301.9   466.5  5333.2  467.92
  5341.5  467.18  5487.5  469.26  5546.1  468.91  5610.5  466.07 5646.81466.1734
    5776  468.55  5826.3  468.08  5968.5  471.12  6271.7  470.62  6316.3   470.6
#Mann= 4 ,-1 , 0
  4386.2      .1       0  4980.3     .07       0    4993      .1       0
  6271.7     .05       0
Bank Sta=4924.75,5646.81
XS Rating Curve= 0 ,0
Exp/Cntr=0.3,0.1

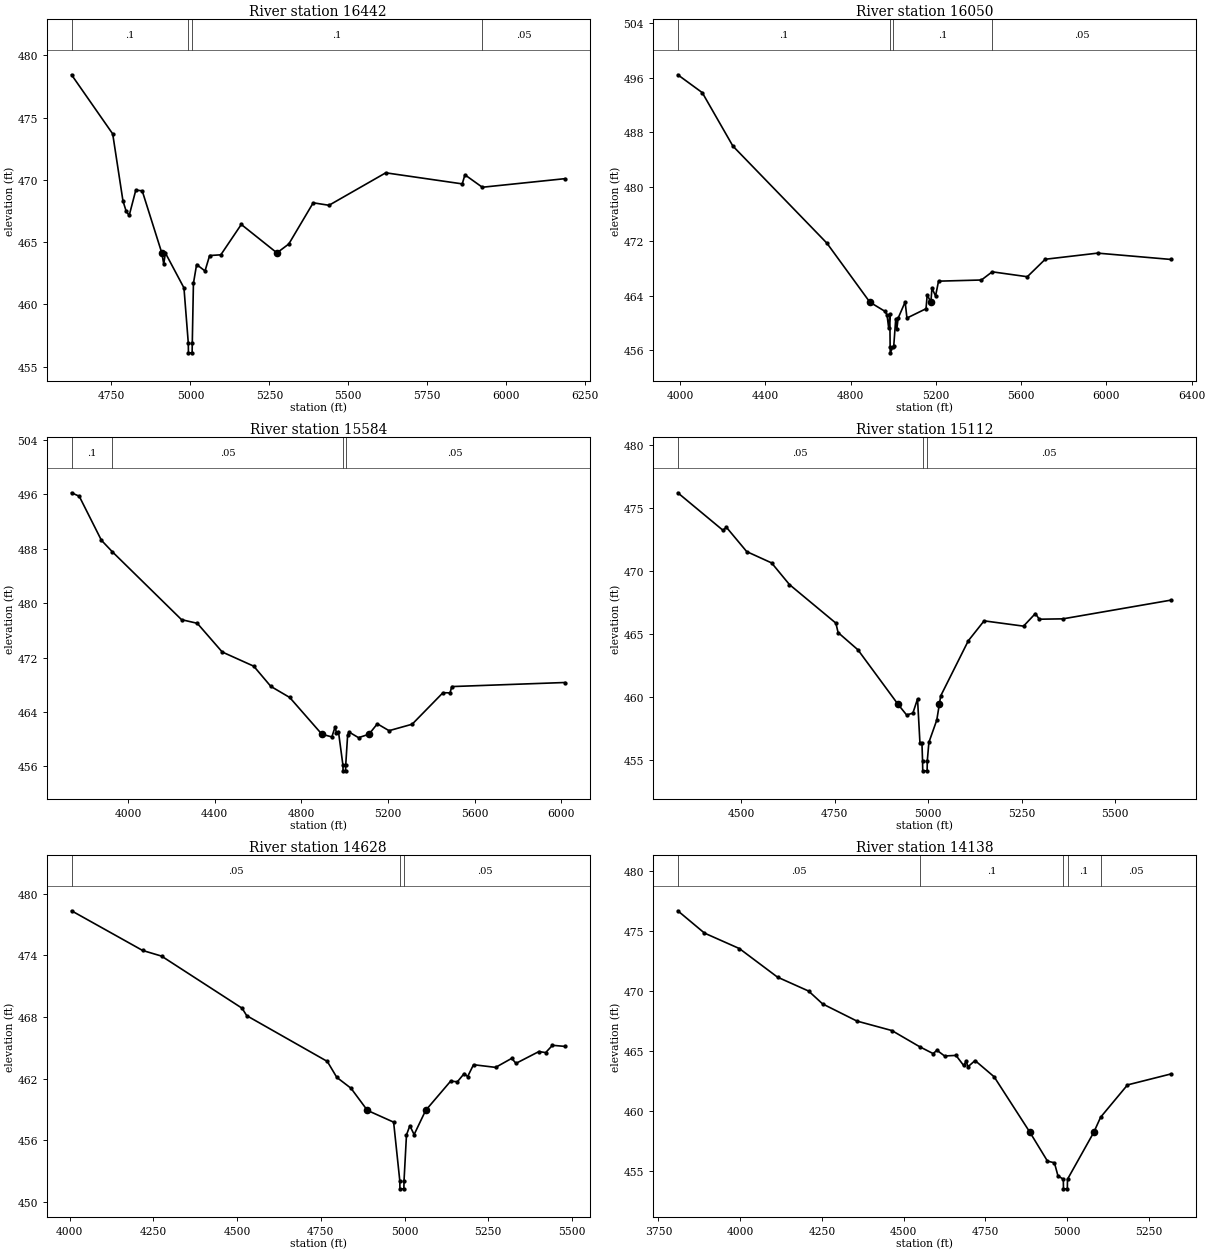
Type RM Length L Ch R = 1 ,16442   ,392,392,392
BEGIN DESCRIPTION:
CHILTIPIN CREEK 28.0
END DESCRIPTION:
XS GIS Cut Line= 4
      2043024.98       13492025.      2042683.05      13491959.9
      2042622.58     13491957.57      2041692.39     13491273.88
#Sta/Elev= 30
  4623.5  478.45  4753.9   473.7  4786.4  468.31  4796.5  467.49  4806.1  467.14
  4827.1  469.18  4847.4  469.12 4909.38464.1324  4915.6  463.23  4920.7  464.13
  4979.6  461.32  4993.3   456.9  4993.8   456.1  5005.5   456.1    5006   456.9
  5009.6  461.68  5019.7   463.2  5046.3  462.68  5060.9  463.92  5096.4  463.98
  5161.2  466.42 5274.11464.1329  5311.7  464.85    5389  468.16    5439  467.96
  5618.8  470.57  5861.1  469.68  5869.5  470.41  5924.6  469.41  6186.5   470.1
#Mann= 4 ,-1 , 0
  4623.5      .1       0  4993.3     .07       0    5006      .1       0
  5924.6     .05       0
Bank Sta=4909.38,5274.11
XS Rating Curve= 0 ,0
Exp/Cntr=0.3,0.1

Type RM Length L Ch R = 1 ,16050   ,466,466,466
BEGIN DESCRIPTION:
CHILTIPIN CREEK 27.0
END DESCRIPTION:
XS GIS Cut Line= 3
      2043525.04     13491875.01        2042525.       13491575.
       2041388.7     13491006.85
#Sta/Elev= 30
  3989.5   496.4  4104.4  493.78  4247.9  485.95    4689  471.71 4890.41463.0579
  4960.5  461.73  4970.9   461.2  4978.8  459.22    4984   461.3  4985.5  456.43
    4986  455.63  4998.2  456.43  5002.3  456.59  5011.8   460.6    5017  459.16
  5023.1  460.72  5055.9  463.09  5064.3  460.73  5153.8   462.1  5159.4  464.13
 5176.54 463.056  5181.7  465.12  5198.5  463.96  5212.5  466.14  5413.7  466.31
  5464.2  467.51  5628.9  466.79  5712.8  469.35  5958.8  470.25    6304  469.32
#Mann= 4 ,-1 , 0
  3989.5      .1       0  4985.5     .07       0  4998.2      .1       0
  5464.2     .05       0
Bank Sta=4890.41,5176.54
XS Rating Curve= 0 ,0
Exp/Cntr=0.3,0.1

Type RM Length L Ch R = 1 ,15584   ,472,472,472
BEGIN DESCRIPTION:
CHILTIPIN CREEK 26.0
END DESCRIPTION:
XS GIS Cut Line= 3
      2043524.99       13491825.        2042425.       13491125.
      2041524.94     13490749.97
#Sta/Elev= 30
  3738.6  496.25  3774.2  495.74  3876.6  489.26    3927  487.57  4246.6  477.58
  4319.4  477.04  4434.5  472.82  4580.2  470.73  4658.9  467.76  4746.1  466.13
 4894.51460.7245  4940.8  460.32  4956.1  461.82    4962  460.89  4971.3  461.11
  4992.1  456.13  4992.6  455.33  5004.3  455.33  5004.8  456.13  5013.6  460.55
  5019.6  461.05  5064.1  460.21 5112.45460.7247  5150.8  462.25  5204.9  461.24
  5311.6  462.19  5454.1  466.83  5486.6   466.8  5494.7  467.73  6017.5  468.33
#Mann= 4 ,-1 , 0
  3738.6      .1       0    3927     .05       0  4992.1     .03       0
  5004.8     .05       0
Bank Sta=4894.51,5112.45
XS Rating Curve= 0 ,0
Exp/Cntr=0.3,0.1

Type RM Length L Ch R = 1 ,15112   ,484,484,484
BEGIN DESCRIPTION:
CHILTIPIN CREEK 25.0
END DESCRIPTION:
XS GIS Cut Line= 3
        2042975.       13491025.        2042375.       13490775.
      2041740.43     13490563.48
#Sta/Elev= 30
  4330.5   476.2  4451.3  473.22  4460.5  473.46  4514.7  471.53  4581.3  470.63
    4629  468.91    4753  465.85    4759   465.1    4812  463.73 4919.23 459.399
    4942  458.56  4958.8   458.7  4971.3  459.83  4977.8   456.3  4983.1   456.3
  4984.7  454.92  4985.2  454.12  4996.9  454.12  4997.4  454.92  5001.6  456.38
  5022.7  458.15 5029.53459.3988  5033.2  460.07    5107  464.45  5149.2  466.03
  5254.6  465.61  5286.2  466.61  5296.7  466.16    5360  466.19  5649.4  467.68
#Mann= 3 ,-1 , 0
  4330.5     .05       0  4984.7     .03       0  4997.4     .05       0
Bank Sta=4919.23,5029.53
XS Rating Curve= 0 ,0
Exp/Cntr=0.3,0.1

Type RM Length L Ch R = 1 ,14628   ,490,490,490
BEGIN DESCRIPTION:
CHILTIPIN CREEK 24.0
END DESCRIPTION:
XS GIS Cut Line= 3
      2043074.99     13491024.99        2042375.       13490325.
      2041898.12     13490245.52
#Sta/Elev= 30
  4005.8  478.33  4217.9  474.47  4274.5  473.92  4514.9  468.85    4529  468.12
  4769.5  463.67  4797.8  462.12  4840.2  461.06 4889.22458.9045  4967.5  457.76
  4985.9  452.07  4986.4  451.27  4998.1  451.27  4998.6  452.07  5005.9  456.52
    5016  457.41  5028.7  456.55 5063.21458.9045  5137.7  461.75  5157.9  461.69
  5178.2  462.49  5188.4  462.19  5206.1  463.35    5272  463.09  5320.2  463.97
  5332.8  463.48  5401.3  464.63  5421.5  464.53  5441.8  465.24  5479.2  465.13
#Mann= 3 ,-1 , 0
  4005.8     .05       0  4985.9     .03       0  4998.6     .05       0
Bank Sta=4889.22,5063.21
XS Rating Curve= 0 ,0
Exp/Cntr=0.3,0.1

Type RM Length L Ch R = 1 ,14138   ,1001,1001,1001
BEGIN DESCRIPTION:
CHILTIPIN CREEK 23.0
END DESCRIPTION:
XS GIS Cut Line= 3
      2043075.02     13490875.04        2042475.       13489875.
      2042131.14       13489875.
#Sta/Elev= 30
  3809.1  476.69  3890.8  474.83  3997.7  473.54  4114.3  471.16  4209.5     470
  4252.3  468.93  4357.3   467.5  4464.2  466.71  4549.4  465.36  4590.5  464.79
  4602.2  465.07  4625.5  464.59  4660.5  464.64  4683.8   463.8  4691.6  464.15
  4697.4   463.7  4718.8  464.21  4777.1  462.86  4886.7 458.231  4940.4  455.83
  4961.7  455.69  4972.4  454.61  4988.9  454.32  4989.4  453.52  5001.2  453.52
  5001.7  454.32 5082.14 458.231  5103.1  459.49  5185.3  462.18  5319.2   463.1
#Mann= 5 ,-1 , 0
  3809.1     .05       0  4549.4      .1       0  4988.9     .07       0
  5001.7      .1       0  5103.1     .05       0
Bank Sta=4886.7,5082.14
XS Rating Curve= 0 ,0
Exp/Cntr=0.3,0.1

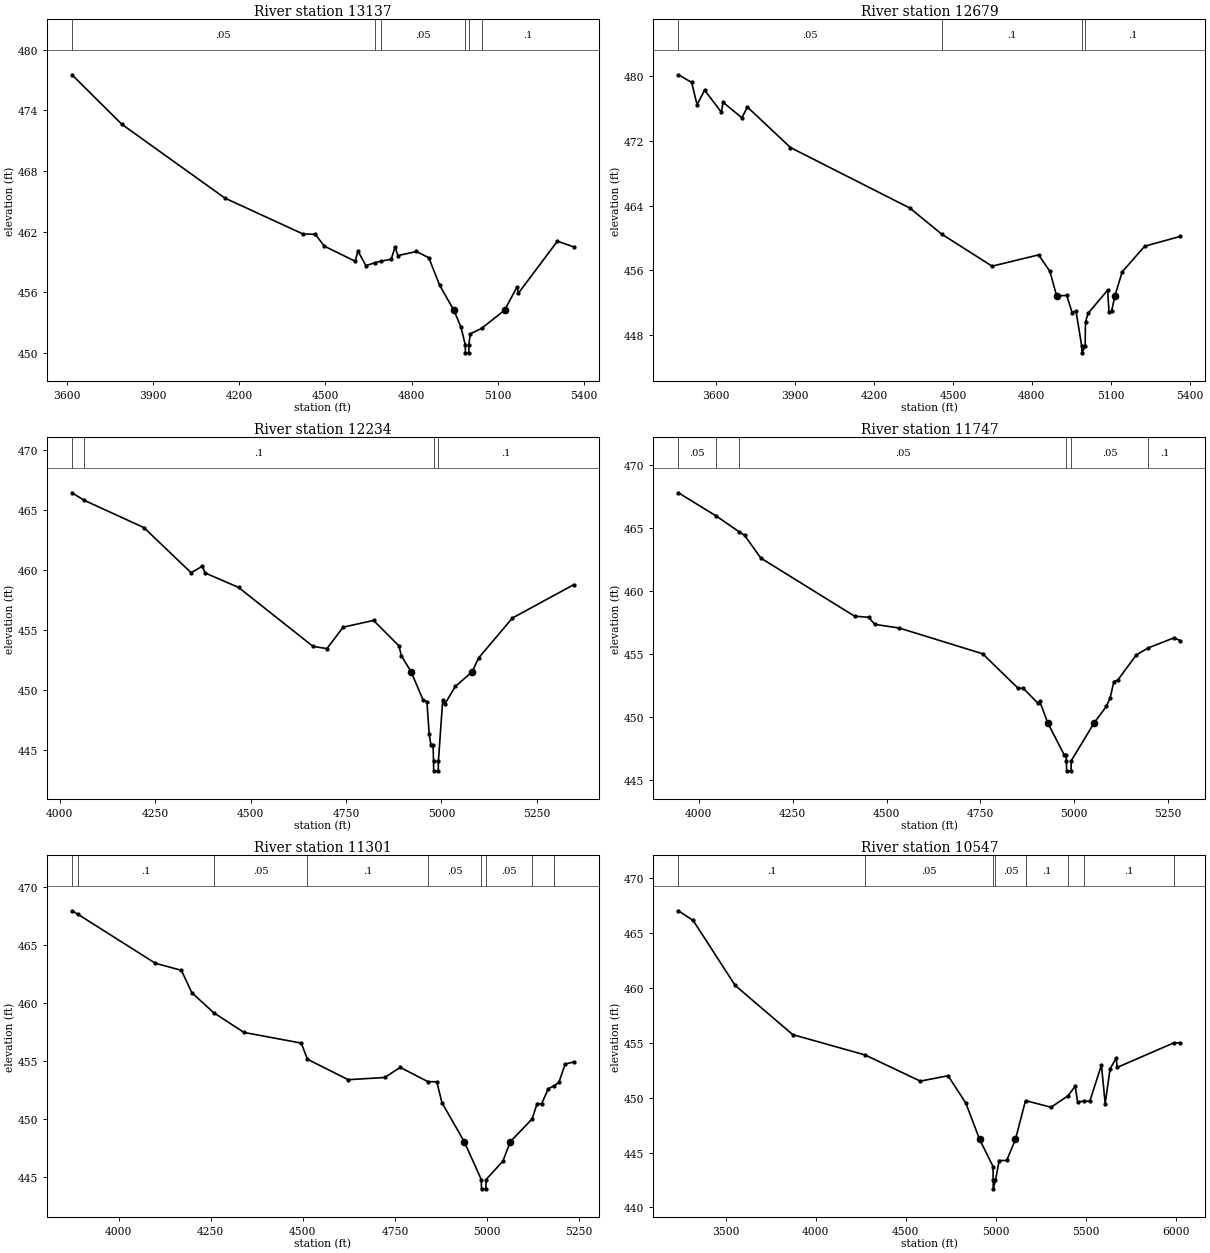
Type RM Length L Ch R = 1 ,13137   ,458,458,458
BEGIN DESCRIPTION:
CHILTIPIN CREEK 22.0
END DESCRIPTION:
XS GIS Cut Line= 3
      2044274.97     13489874.98        2043075.       13489175.
      2042725.44     13489252.68
#Sta/Elev= 30
  3617.5  477.52  3791.5  472.62    4150  465.33  4421.7  461.78  4464.7  461.75
  4496.1  460.58  4603.6  459.08  4613.1   460.1  4640.8  458.65  4671.3  458.93
  4692.5  459.08  4728.9  459.29  4742.5   460.5    4752  459.64  4816.9  460.05
  4859.9  459.43  4897.1  456.74 4946.81454.2487  4971.6   452.6  4986.7  450.83
  4987.2  450.03    4999  450.03  4999.5  450.83  5003.8   451.9  5043.4  452.44
  5123.7454.2487  5166.8  456.54  5171.9  455.93  5307.6  461.07  5364.8   460.5
#Mann= 6 ,-1 , 0
  3617.5     .05       0  4671.3      .1       0  4692.5     .05       0
  4986.7     .03       0  4999.5     .05       0  5043.4      .1       0
Bank Sta=4946.81,5123.7
XS Rating Curve= 0 ,0
Exp/Cntr=0.3,0.1

Type RM Length L Ch R = 1 ,12679   ,445,445,445
BEGIN DESCRIPTION:
CHILTIPIN CREEK 21.0
END DESCRIPTION:
XS GIS Cut Line= 3
      2044425.03     13489775.03        2043225.       13488775.
      2042900.04     13488896.43
#Sta/Elev= 30
  3455.9  480.19  3506.1  479.25  3526.9  476.48  3555.5  478.29  3619.3  475.55
  3625.8  476.78  3697.4  474.86  3718.2   476.2  3882.2  471.18  4336.5  463.68
  4457.2  460.46    4649  456.49    4826  457.89  4868.9  455.84 4894.34452.8285
  4932.7  452.86  4953.6  450.73  4967.9  450.96  4990.1  446.56  4990.6  445.76
  5002.9  446.56  5004.3  449.62  5014.7  450.68  5088.4  453.52  5093.7  450.78
  5103.4   450.9 5116.23452.8283  5143.7  455.78  5229.2  458.96  5364.9  460.18
#Mann= 4 ,-1 , 0
  3455.9     .05       0  4457.2      .1       0  4990.1     .07       0
  5002.9      .1       0
Bank Sta=4894.34,5116.23
XS Rating Curve= 0 ,0
Exp/Cntr=0.3,0.1

Type RM Length L Ch R = 1 ,12234   ,487,487,487
BEGIN DESCRIPTION:
CHILTIPIN CREEK 20.0
END DESCRIPTION:
XS GIS Cut Line= 3
      2043974.98     13489224.97        2043475.       13488425.
      2043108.72     13488486.05
#Sta/Elev= 30
  4032.1  466.46  4064.4  465.83  4220.7  463.55    4344  459.79    4374  460.33
  4380.5  459.77  4468.4  458.56  4663.6  453.63  4700.1  453.45  4742.6  455.24
  4822.2   455.8  4888.8  453.67  4894.7  452.86 4920.35451.5156  4952.5  449.12
  4961.9  449.03  4967.8  446.32  4972.5  445.39    4978  445.39  4979.2  444.04
  4979.7  443.24  4991.5  443.24    4992  444.04  5003.3  449.17  5008.4   448.8
  5036.3  450.29 5080.68451.5153  5097.1  452.66  5185.8     456  5346.8  458.79
#Mann= 4 ,-1 , 0
  4032.1     .05       0  4064.4      .1       0  4979.2     .07       0
    4992      .1       0
Bank Sta=4920.35,5080.68
XS Rating Curve= 0 ,0
Exp/Cntr=0.3,0.1

Type RM Length L Ch R = 1 ,11747   ,446,446,446
BEGIN DESCRIPTION:
CHILTIPIN CREEK 19.0
END DESCRIPTION:
XS GIS Cut Line= 3
      2044574.98     13488524.99        2043675.       13488025.
      2043368.14       13488025.
#Sta/Elev= 30
  3945.8  467.78  4045.4  465.96  4107.4  464.69  4121.9  464.41  4165.4   462.6
  4414.8     458  4452.5  457.91  4468.6  457.35  4533.8  457.06  4755.7  455.02
  4849.5  452.31  4864.4  452.27  4902.1  451.13  4907.8  451.25 4928.79 449.569
  4972.5  447.03  4977.8  447.03  4978.9  446.54  4979.4  445.74  4991.3  445.74
  4991.8  446.54 5053.32 449.569  5085.3  450.85  5095.3  451.51  5105.3  452.82
  5115.3  452.92  5165.3  454.94  5197.3  455.49  5265.3  456.28  5282.2  456.06
#Mann= 6 ,-1 , 0
  3945.8     .05       0  4045.4      .1       0  4107.4     .05       0
  4978.9     .03       0  4991.8     .05       0  5197.3      .1       0
Bank Sta=4928.79,5053.32
XS Rating Curve= 0 ,0
Exp/Cntr=0.3,0.1

Type RM Length L Ch R = 1 ,11301   ,754,754,754
BEGIN DESCRIPTION:
CHILTIPIN CREEK 18.0
END DESCRIPTION:
XS GIS Cut Line= 3
      2044624.99     13488424.99        2043825.       13487625.
      2043613.38     13487716.47
#Sta/Elev= 30
  3873.5  467.97  3889.1  467.68  4099.8  463.44  4170.5  462.83  4198.8   460.9
  4257.8  459.18  4340.2  457.47  4495.7  456.55  4512.4  455.16    4623  453.39
    4722  453.58  4764.4  454.45  4839.6  453.22  4863.4  453.21  4877.6   451.4
 4938.09448.0334  4984.3  444.77  4984.8  443.97  4996.7  443.97  4997.2  444.77
  5042.8  446.36 5062.86448.0331  5122.4  450.01  5135.6  451.33  5147.7  451.29
  5165.8   452.6  5180.2  452.84  5194.7  453.15  5211.8  454.74  5235.4  454.92
#Mann= 9 ,-1 , 0
  3873.5     .05       0  3889.1      .1       0  4257.8     .05       0
  4512.4      .1       0  4839.6     .05       0  4984.3     .03       0
  4997.2     .05       0  5122.4      .1       0  5180.2     .05       0
Bank Sta=4938.09,5062.86
XS Rating Curve= 0 ,0
Exp/Cntr=0.3,0.1

Type RM Length L Ch R = 1 ,10547   ,95,95,95
BEGIN DESCRIPTION:
CHILTIPIN CREEK 17.0
END DESCRIPTION:
XS GIS Cut Line= 5
      2044601.43     13488382.02      2044092.86     13486952.72
      2043797.73      13486868.4      2043765.35     13486884.73
      2043514.92     13487776.65
#Sta/Elev= 30
  3237.9  467.05  3319.7  466.17  3553.2  460.24  3872.7  455.76  4273.8  453.91
    4581  451.52  4735.2  452.01  4834.2   449.5 4910.06446.2105    4985  443.73
  4985.5   442.5    4986   441.7  4998.4   442.5  5018.8  444.28  5060.7  444.29
 5109.21 446.211  5165.1  449.74  5307.2  449.14  5400.1  450.17  5441.2  451.06
  5453.9  449.64    5489  449.68    5522  449.69  5586.6  452.98  5607.4  449.47
  5634.6  452.64  5668.7  453.61  5673.9  452.77  5987.6     455  6024.6  455.02
#Mann= 8 ,-1 , 0
  3237.9      .1       0  4273.8     .05       0  4985.5     .04       0
  4998.4     .05       0  5165.1      .1       0  5400.1     .05       0
    5489      .1       0  5987.6     .05       0
Bank Sta=4910.06,5109.21
XS Rating Curve= 0 ,0
Exp/Cntr=0.3,0.1

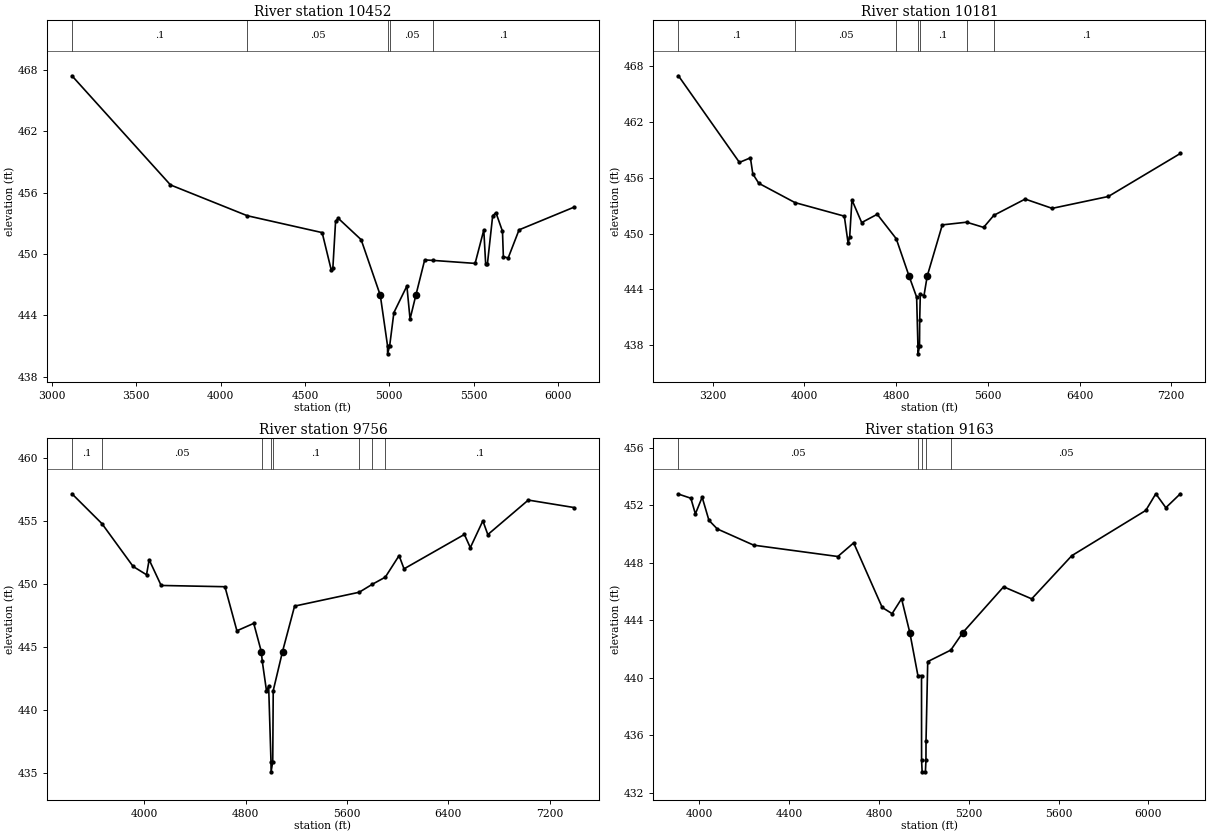
Type RM Length L Ch R = 1 ,10452   ,271,271,271
BEGIN DESCRIPTION:
CHILTIPIN CREEK 16.0
END DESCRIPTION:
XS GIS Cut Line= 4
      2044627.47     13488387.25      2044106.45     13486870.16
      2043766.53     13486771.43      2043481.63     13487746.63
#Sta/Elev= 30
  3119.3  467.41  3703.2  456.74  4158.3  453.73  4601.9  452.08  4655.5  448.44
  4665.4  448.63  4681.4  453.18  4697.1  453.48  4832.9  451.39 4946.46445.9459
  4989.2  441.03  4989.7  440.23  5002.1  441.03  5026.9  444.26  5103.9  446.86
  5122.7  443.63 5156.91445.9461  5209.4  449.41  5261.5  449.36  5508.2  449.07
  5559.6  452.33  5570.7  449.03  5581.1  449.02  5612.4  453.74  5631.8  454.02
  5670.4  452.21  5675.6  449.74  5703.9  449.59  5768.6  452.35  6093.3  454.56
#Mann= 5 ,-1 , 0
  3119.3      .1       0  4158.3     .05       0  4989.2     .03       0
  5002.1     .05       0  5261.5      .1       0
Bank Sta=4946.46,5156.91
XS Rating Curve= 0 ,0
Exp/Cntr=0.3,0.1

Type RM Length L Ch R = 1 ,10181   ,425,425,425
BEGIN DESCRIPTION:
CHILTIPIN CREEK 15.0
END DESCRIPTION:
XS GIS Cut Line= 5
      2044632.67      13488376.8      2044111.84     13486626.82
      2043556.64     13486446.84      2043190.09     13486421.44
      2041731.67     13487079.93
#Sta/Elev= 30
  2901.6     467  3433.6  457.67  3529.5  458.16  3550.4  456.43  3602.5  455.42
  3918.2  453.34  4348.4  451.88  4381.6  448.96  4395.5  449.68  4414.8  453.63
  4499.8  451.19  4635.4  452.08  4801.2  449.45 4912.94445.4298  4979.1  443.16
  4990.5  437.85  4991.3  437.05  5004.3  437.85  5005.8  440.67  5011.1  443.47
  5043.1  443.31 5071.47445.4297    5203  450.94  5414.9  451.23  5563.3  450.67
  5652.4  451.97  5925.5  453.72  6161.2  452.72  6651.1     454  7278.7  458.63
#Mann= 7 ,-1 , 0
  2901.6      .1       0  3918.2     .05       0  4801.2      .1       0
  4990.5     .07       0  5004.3      .1       0  5414.9     .05       0
  5652.4      .1       0
Bank Sta=4912.94,5071.47
XS Rating Curve= 0 ,0
Exp/Cntr=0.3,0.1

Type RM Length L Ch R = 1 ,9756    ,593,593,593
BEGIN DESCRIPTION:
double CHILTIPIN CREEK 14.0
END DESCRIPTION:
XS GIS Cut Line= 4
      2044766.69     13487612.29      2044337.84      13486341.7
      2043825.09     13486158.06      2041829.15     13486726.66
#Sta/Elev= 30
  3428.9  457.18  3665.5  454.81  3911.5  451.41  4017.5  450.75  4038.2  451.94
  4132.8   449.9  4636.3   449.8  4730.7   446.3  4863.6  446.89 4923.12 444.653
  4930.7   443.9  4964.1  441.54  4981.3  441.89  4999.7   435.9  5000.5   435.1
  5013.5   435.9  5017.4  441.55  5090.7444.6528    5186  448.26  5695.6  449.36
  5798.8  449.99  5901.9  450.56  6010.6  452.27  6049.7  451.22  6526.1  453.95
  6572.8   452.9  6671.8  455.03  6710.9  453.94  7030.3  456.68  7389.9  456.09
#Mann= 8 ,-1 , 0
  3428.9      .1       0  3665.5     .05       0  4930.7      .1       0
  4999.7     .07       0  5013.5      .1       0  5695.6     .05       0
  5798.8     .08       0  5901.9      .1       0
Bank Sta=4923.12,5090.7
XS Rating Curve= 0 ,0
Exp/Cntr=0.3,0.1

Type RM Length L Ch R = 1 ,9163    ,559,559,559
BEGIN DESCRIPTION:
CHILTIPIN CREEK 13.0
END DESCRIPTION:
XS GIS Cut Line= 3
      2044761.48     13487179.99        2044625.       13486075.
      2044121.73     13485071.07
#Sta/Elev= 30
  3906.3  452.79  3961.7   452.5  3981.9  451.41  4012.1  452.57  4042.3  450.96
  4079.6  450.36  4241.8  449.23  4616.6  448.44  4687.2  449.39  4814.4  444.89
  4858.5  444.46  4900.6   445.5 4937.44443.1346  4973.5  440.14  4989.5  440.15
  4989.8  434.24  4992.3  433.44  5006.8  433.44  5009.3  434.24  5009.6   435.6
  5017.2  441.12  5119.9  441.92 5173.22443.1347  5355.3  446.33  5480.5  445.49
  5659.3   448.5  5988.8  451.65  6033.5  452.81  6078.2  451.84  6142.7  452.81
#Mann= 5 ,-1 , 0
  3906.3     .05       0  4973.5      .1       0  4989.8     .07       0
  5009.3      .1       0  5119.9     .05       0
Bank Sta=4937.44,5173.22
XS Rating Curve= 0 ,0
Exp/Cntr=0.3,0.1