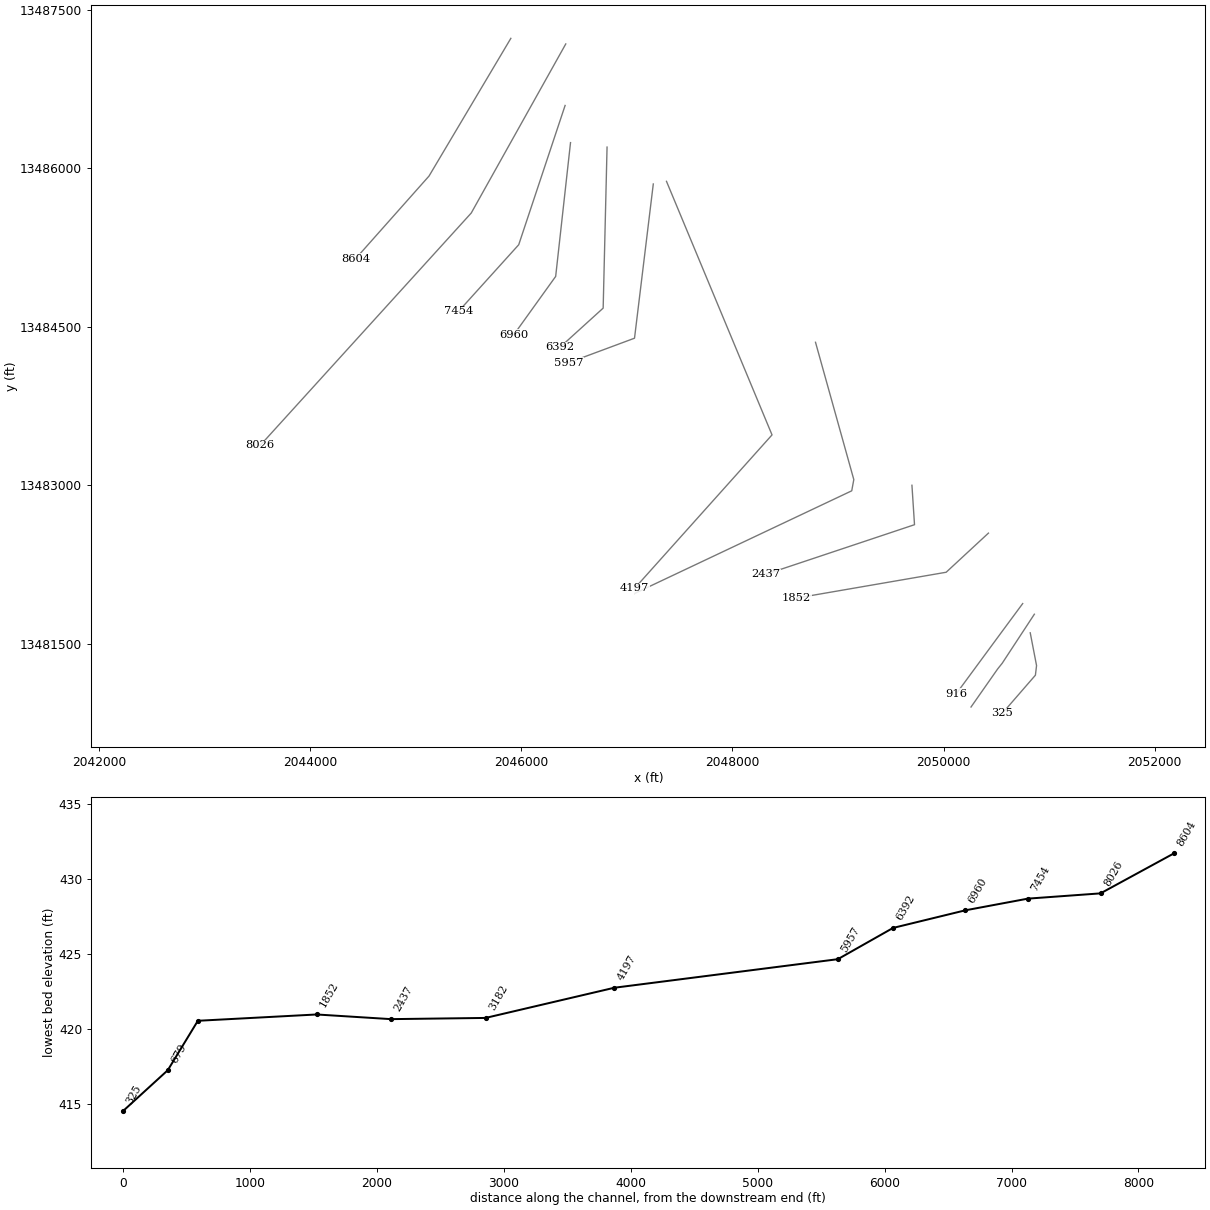
HEC-RAS study CHILTIPIN CREEK.prj: CHILTIPIN CREEK Base Level Engineering

--- CHILTIPIN CREEK.g01 (geometry) --- (continued)

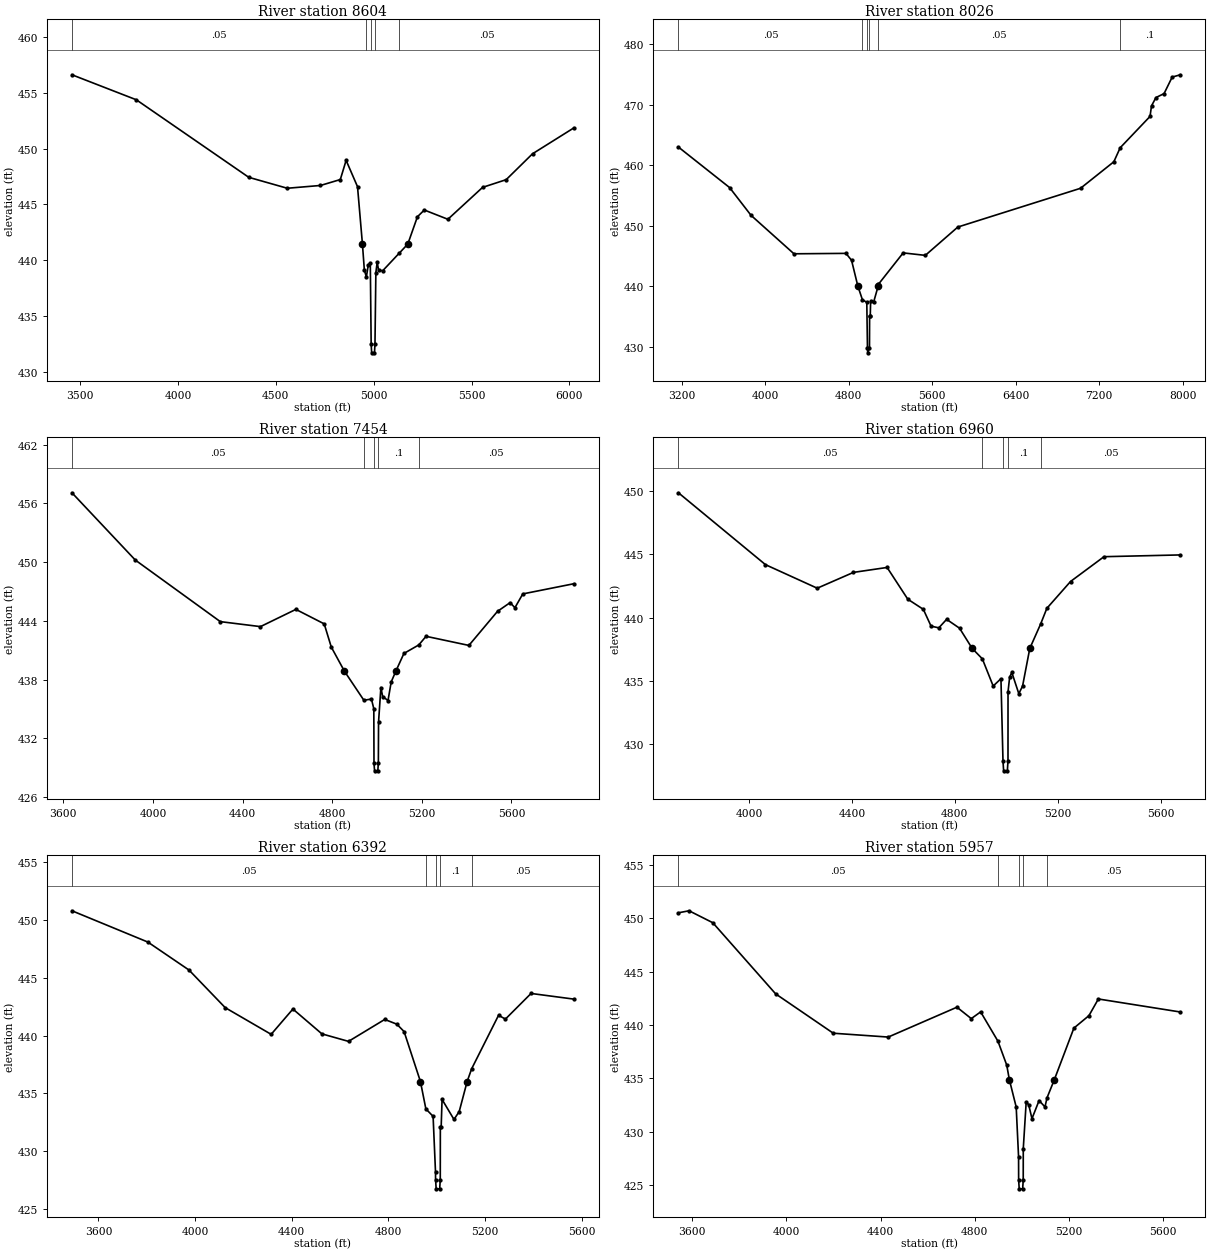
Type RM Length L Ch R = 1 ,8604    ,578,578,578
BEGIN DESCRIPTION:
CHILTIPIN CREEK 12.0
END DESCRIPTION:
XS GIS Cut Line= 3
      2045900.35     13487228.59        2045125.       13485925.
      2044429.41     13485142.66
#Sta/Elev= 30
  3458.7  456.61  3787.4  454.37  4361.9  447.42  4558.6  446.44  4728.1  446.69
  4829.4  447.22  4859.1  448.94  4917.3  446.58 4942.45441.4333  4952.2  439.11
  4962.5  438.49  4972.5  439.59  4982.6  439.71    4987  432.49  4989.5  431.69
    5004  431.69  5006.5  432.49    5011  438.88  5017.7   439.8  5025.2  439.09
  5046.1  439.05  5129.2   440.6 5174.06 441.434  5223.4  443.89  5258.5  444.49
  5378.9  443.66  5556.2  446.52  5676.6  447.21  5811.2  449.53  6022.3  451.85
#Mann= 5 ,-1 , 0
  3458.7     .05       0  4962.5      .1       0    4987     .07       0
  5006.5      .1       0  5129.2     .05       0
Bank Sta=4942.45,5174.06
XS Rating Curve= 0 ,0
Exp/Cntr=0.3,0.1

Type RM Length L Ch R = 1 ,8026    ,572,572,572
BEGIN DESCRIPTION:
CHILTIPIN CREEK 11.0
END DESCRIPTION:
XS GIS Cut Line= 3
      2046420.62     13487175.47        2045525.       13485575.
      2043525.02     13483375.03
#Sta/Elev= 30
  3169.9  463.02    3660  456.33  3865.6  451.74  4276.6  445.39  4774.7  445.46
  4828.1  444.32 4888.31440.0659  4932.2   437.8  4974.2  437.37  4980.5  429.83
    4983  429.03    5000  429.83  5001.1  435.13  5007.3  435.13    5011  437.53
  5039.4  437.39 5083.14 440.067  5084.9  440.34  5322.5  445.54  5534.7  445.13
  5846.2  449.81  7021.3  456.21  7340.3  460.59  7401.3  462.91  7686.9  468.08
  7701.1  469.82  7743.7   471.2  7821.4  471.85  7899.1  474.58  7977.1  474.96
#Mann= 6 ,-1 , 0
  3169.9     .05       0  4932.2      .1       0  4980.5     .07       0
    5000      .1       0  5084.9     .05       0  7401.3      .1       0
Bank Sta=4888.31,5083.14
XS Rating Curve= 0 ,0
Exp/Cntr=0.3,0.1

Type RM Length L Ch R = 1 ,7454    ,494,494,494
BEGIN DESCRIPTION:
CHILTIPIN CREEK 10.0
END DESCRIPTION:
XS GIS Cut Line= 3
      2046414.41     13486593.23        2045975.       13485275.
      2045404.33     13484644.02
#Sta/Elev= 30
  3638.4  457.08  3921.1  450.21  4300.6  443.92  4479.8  443.41  4637.9  445.17
  4764.4  443.69    4796  441.32 4854.55 438.863  4941.4  435.89  4975.2  436.01
  4985.8  435.02  4986.6  429.48  4989.1  428.68  5003.6  428.68  5006.1  429.48
  5006.9  433.65  5017.4  437.19  5025.3  436.27  5049.2  435.86  5063.4  437.76
 5084.17438.8634  5120.2  440.67  5186.6  441.54  5218.9  442.42  5410.2  441.49
  5537.9  444.97  5594.2  445.86  5615.6  445.34  5650.8  446.75  5878.7  447.79
#Mann= 5 ,-1 , 0
  3638.4     .05       0  4941.4      .1       0  4986.6     .07       0
  5006.1      .1       0  5186.6     .05       0
Bank Sta=4854.55,5084.17
XS Rating Curve= 0 ,0
Exp/Cntr=0.3,0.1

Type RM Length L Ch R = 1 ,6960    ,568,568,568
BEGIN DESCRIPTION:
CHILTIPIN CREEK 9.0
END DESCRIPTION:
XS GIS Cut Line= 3
      2046465.73     13486241.54        2046325.       13484975.
      2045929.66     13484424.97
#Sta/Elev= 30
  3725.1  449.87  4063.7  444.19  4264.9  442.33  4405.8  443.58  4536.6  443.97
  4617.1  441.46  4677.5  440.66  4707.6  439.33  4737.8   439.2    4768  439.87
  4818.3  439.17 4867.36437.5748  4906.9  436.75  4949.1   434.6  4979.3  435.18
  4987.2   428.7  4989.7   427.9  5004.2   427.9  5006.7   428.7  5006.8  434.14
    5013  435.28  5021.5  435.68  5048.7     434  5063.3  434.59 5091.48437.5752
  5133.4  439.49  5157.8  440.74  5249.9  442.86    5380  444.82  5676.8  444.96
#Mann= 5 ,-1 , 0
  3725.1     .05       0  4906.9      .1       0  4987.2     .07       0
  5006.7      .1       0  5133.4     .05       0
Bank Sta=4867.36,5091.48
XS Rating Curve= 0 ,0
Exp/Cntr=0.3,0.1

Type RM Length L Ch R = 1 ,6392    ,435,435,435
BEGIN DESCRIPTION:
CHILTIPIN CREEK 8.0
END DESCRIPTION:
XS GIS Cut Line= 3
      2046811.92     13486199.13        2046775.       13484675.
      2046365.59     13484303.97
#Sta/Elev= 30
  3490.4  450.81  3804.6   448.1  3974.7  445.68  4124.7  442.42  4314.8  440.11
  4404.8   442.3  4524.8  440.15  4634.9   439.5  4784.9   441.4  4834.9  440.99
  4864.9  440.35 4932.57436.0239  4955.1  433.65    4985  433.01    4995  428.16
  4995.2  427.53  4997.7  426.73  5012.2  426.73  5014.7  427.53    5015  432.09
  5018.4  432.09  5022.1  434.47  5071.4  432.74    5093  433.42 5125.89436.0241
  5144.6  437.13  5255.9  441.76  5284.3  441.43  5390.4  443.65  5567.5  443.16
#Mann= 5 ,-1 , 0
  3490.4     .05       0  4955.1      .1       0  4995.2     .07       0
  5014.7      .1       0  5144.6     .05       0
Bank Sta=4932.57,5125.89
XS Rating Curve= 0 ,0
Exp/Cntr=0.3,0.1

Type RM Length L Ch R = 1 ,5957    ,1760,1760,1760
BEGIN DESCRIPTION:
CHILTIPIN CREEK 7.0
END DESCRIPTION:
XS GIS Cut Line= 3
        2047250.       13485850.      2047072.12     13484390.36
      2046451.03     13484159.65
#Sta/Elev= 30
  3541.1  450.53  3586.4  450.72  3687.2   449.6  3954.3  442.93  4199.2  439.24
  4432.7  438.88  4724.8  441.68  4785.7  440.61  4825.5  441.24  4899.1  438.49
  4936.4  436.25 4947.39434.9012  4976.6  432.32  4986.7  427.65    4987  425.45
  4989.5  424.65    5004  424.65  5006.5  425.45  5006.7  428.42  5019.1   432.8
  5029.8  432.53  5043.6  431.23  5073.9  432.93  5098.9  432.33  5107.7  433.19
    5139434.9008  5221.8  439.72  5285.8  440.89  5325.8  442.45  5674.1  441.23
#Mann= 5 ,-1 , 0
  3541.1     .05       0  4899.1      .1       0    4987     .07       0
  5006.5      .1       0  5107.7     .05       0
Bank Sta=4947.39,5139
XS Rating Curve= 0 ,0
Exp/Cntr=0.3,0.1

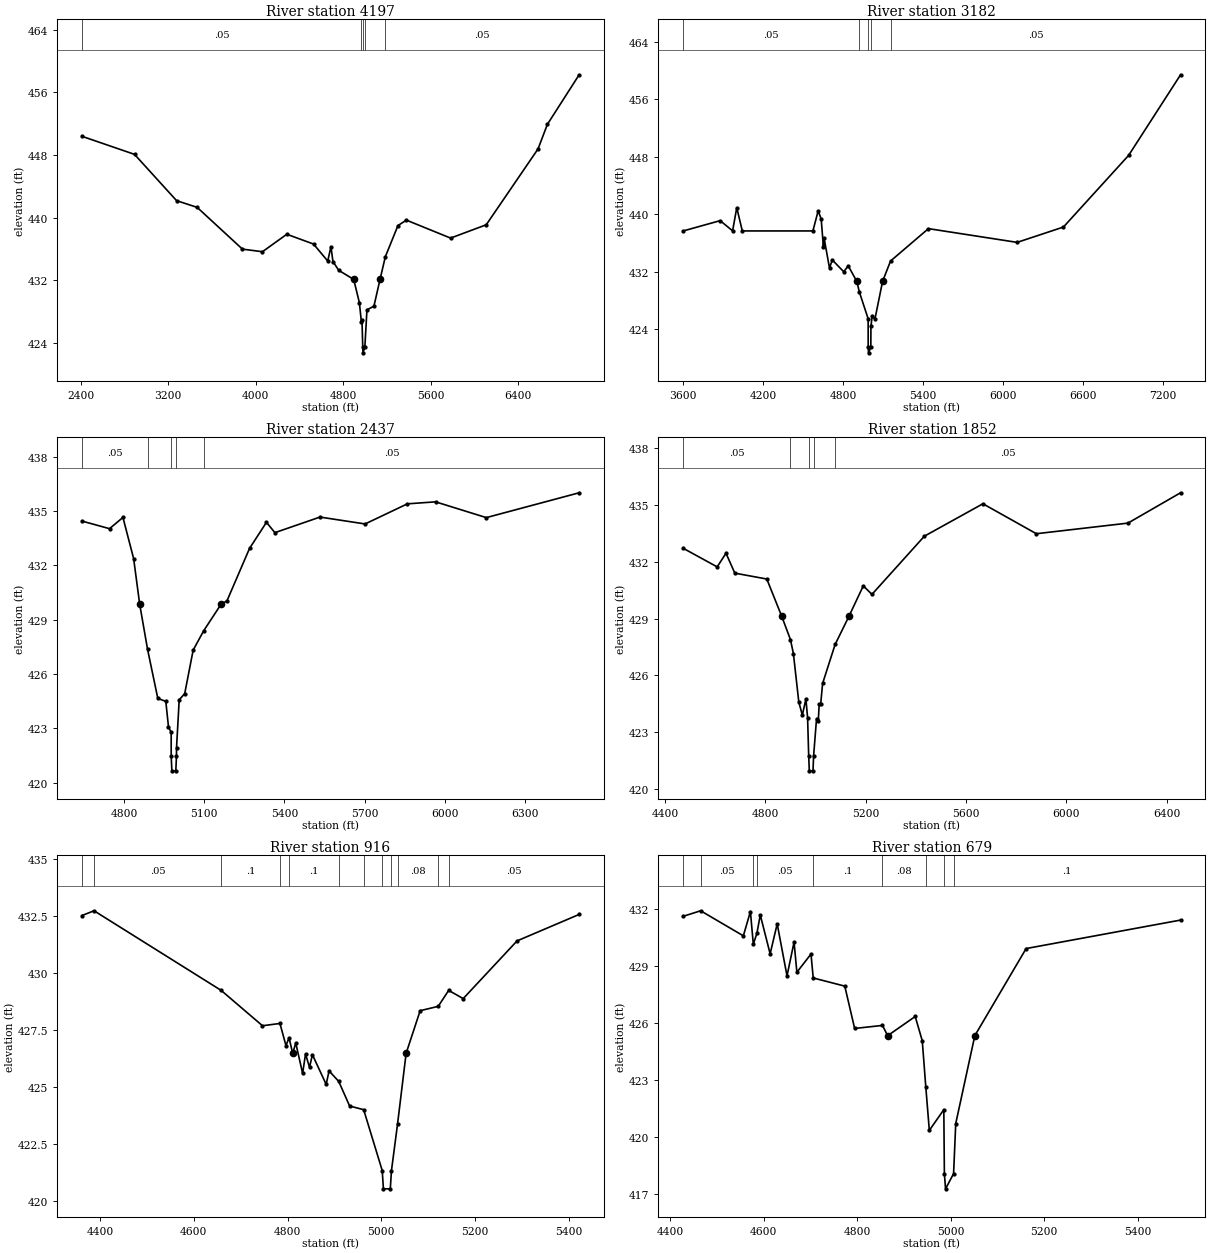
Type RM Length L Ch R = 1 ,4197    ,1015,1015,1015
BEGIN DESCRIPTION:
CHILTIPIN CREEK 6.0
END DESCRIPTION:
XS GIS Cut Line= 3
      2047374.99     13485875.03        2048375.       13483475.
      2047074.98     13482024.98
#Sta/Elev= 30
  2410.3   450.4  2891.9  448.09  3276.5  442.18    3465  441.32  3878.8  435.99
  4061.9  435.66  4284.5  437.89  4528.8  436.64  4658.8  434.47    4688   436.3
  4706.5  434.41  4759.5  433.28 4896.24432.1271    4948  429.17  4966.4  426.71
  4971.9  426.93  4978.9  423.55  4981.4  422.75  4998.5  423.55  5017.4  428.25
    5081   428.7 5137.04432.1271  5185.6  435.02  5300.8     439  5378.5  439.69
  5782.2   437.4  6108.2   439.1  6582.1  448.79  6667.3  451.92  6957.8  458.25
#Mann= 5 ,-1 , 0
  2410.3     .05       0  4966.4      .1       0  4978.9     .07       0
  4998.5      .1       0  5185.6     .05       0
Bank Sta=4896.24,5137.04
XS Rating Curve= 0 ,0
Exp/Cntr=0.3,0.1

Type RM Length L Ch R = 1 ,3182    ,745,745,745
BEGIN DESCRIPTION:
CHILTIPIN CREEK 5.0
END DESCRIPTION:
XS GIS Cut Line= 4
      2048786.94     13484351.64      2049149.78     13483052.19
      2049130.24     13482945.85      2047074.99     13481974.99
#Sta/Elev= 30
  3602.2  437.68  3879.1  439.11  3972.5  437.69  4003.6  440.91  4045.2  437.68
  4574.7  437.68  4614.3  440.47    4637  439.33  4653.6  435.44  4658.8  436.68
  4699.3  432.51    4720  433.65  4805.9  432.01    4840  432.83 4904.29 430.658
  4922.8  429.22  4989.2  425.47  4989.5  421.54    4992  420.74  5009.2  421.54
    5010  424.44  5019.7  425.88    5040  425.42 5097.16430.6574  5157.2   433.5
  5441.3     438  6106.9  436.09  6453.9  438.22    6943  448.18  7332.5  459.38
#Mann= 5 ,-1 , 0
  3602.2     .05       0  4922.8      .1       0  4989.5     .07       0
  5009.2      .1       0  5157.2     .05       0
Bank Sta=4904.29,5097.16
XS Rating Curve= 0 ,0
Exp/Cntr=0.3,0.1

Type RM Length L Ch R = 1 ,2437    ,585,585,585
BEGIN DESCRIPTION:
CHILTIPIN CREEK 4.0
END DESCRIPTION:
XS GIS Cut Line= 3
      2049700.61     13482998.35        2049725.       13482625.
      2048315.58     13482155.19
#Sta/Elev= 30
  4642.3  434.44  4745.9  434.02    4796  434.64  4836.1  432.36 4858.64429.8481
  4888.1  427.36  4926.3  424.66  4956.3  424.49  4966.3  423.09  4976.4  422.78
  4976.5  421.46    4979  420.66  4993.7  420.66  4996.2  421.46  4996.4  421.93
  5006.4  424.58    5027  424.92  5058.6  427.32  5098.1  428.39 5162.81429.8479
  5185.1  430.04  5269.4  432.93  5332.7  434.37  5364.3   433.8  5532.9  434.66
  5701.6  434.28  5859.7  435.39  5965.1   435.5  6154.9  434.63  6502.1     436
#Mann= 5 ,-1 , 0
  4642.3     .05       0  4888.1      .1       0  4976.5     .07       0
  4996.2      .1       0  5098.1     .05       0
Bank Sta=4858.64,5162.81
XS Rating Curve= 0 ,0
Exp/Cntr=0.3,0.1

Type RM Length L Ch R = 1 ,1852    ,936,936,936
BEGIN DESCRIPTION:
CHILTIPIN CREEK 3.0
END DESCRIPTION:
XS GIS Cut Line= 3
      2050425.48     13482545.43        2050025.       13482175.
      2048608.33     13481930.75
#Sta/Elev= 30
  4472.4  432.71  4607.7  431.73  4642.9  432.45    4678   431.4  4805.6  431.09
  4865.2429.1193    4900  427.89  4911.6  427.16  4933.2   424.6  4947.3  423.91
  4961.5  424.76  4968.3  423.76  4972.6  421.77  4975.1  420.97  4989.8  420.97
  4992.3  421.77    5004  423.73  5010.8  423.58  5014.5   424.5  5020.5   424.5
  5028.1  425.58  5078.1  427.64 5133.02429.1193  5190.4  430.73  5224.9  430.28
    5434  433.35  5667.4  435.06  5880.5  433.48  6245.8  434.04  6455.5  435.64
#Mann= 5 ,-1 , 0
  4472.4     .05       0    4900      .1       0  4972.6     .07       0
  4992.3      .1       0  5078.1     .05       0
Bank Sta=4865.2,5133.02
XS Rating Curve= 0 ,0
Exp/Cntr=0.3,0.1

Type RM Length L Ch R = 1 ,916     ,237,237,237
BEGIN DESCRIPTION:
CHILTIPIN CREEK 2.0
END DESCRIPTION:
XS GIS Cut Line= 3
      2050749.98     13481878.53      2050548.48     13481605.99
      2050120.37     13481024.91
#Sta/Elev= 30
  4361.3  432.53  4387.3  432.74  4658.4  429.25  4746.6   427.7  4783.8   427.8
  4796.7  426.83  4803.3  427.17 4810.92426.4927  4817.6  426.94  4832.2  425.61
  4838.4  426.46  4846.9  425.88  4853.1  426.43  4882.4  425.13  4888.6  425.72
  4909.2  425.26  4932.5  424.18  4962.4  424.02    5002  421.35  5004.5  420.55
  5019.2  420.55  5021.7  421.35  5034.6  423.38 5052.96 426.492  5082.9  428.36
  5121.4  428.55  5143.7  429.25  5174.7  428.89  5289.6  431.42    5422  432.58
#Mann= 12 ,-1 , 0
  4361.3     .08       0  4387.3     .05       0  4658.4      .1       0
  4783.8     .08       0  4803.3      .1       0  4909.2     .05       0
  4962.4      .1       0    5002     .07       0  5021.7      .1       0
  5034.6     .08       0  5121.4      .1       0  5143.7     .05       0
Bank Sta=4810.92,5052.96
XS Rating Curve= 0 ,0
Exp/Cntr=0.3,0.1

Type RM Length L Ch R = 1 ,679     ,354,354,354
BEGIN DESCRIPTION:
CHILTIPIN CREEK 112.0
END DESCRIPTION:
XS GIS Cut Line= 4
      2050860.51     13481777.66      2050555.84     13481313.44
      2050512.44     13481259.18       2050260.4     13480899.43
#Sta/Elev= 30
  4427.7  431.62  4464.9  431.91  4556.3  430.59  4571.4  431.87  4577.6  430.15
  4585.3  430.72  4592.5  431.69  4613.6  429.64  4628.7  431.22  4649.7  428.48
  4664.8  430.26  4670.8  428.67    4701  429.63  4705.8  428.37  4773.3  427.94
  4794.4  425.71    4854  425.87 4865.02425.3282    4924  426.34  4939.1  425.06
  4946.6  422.64  4954.2  420.34  4985.2  421.43  4986.4  418.06  4988.9  417.26
  5006.1  418.06  5010.7   420.7 5051.52425.3295  5161.3  429.92  5491.7  431.42
#Mann= 9 ,-1 , 0
  4427.7     .08       0  4464.9     .05       0  4577.6     .08       0
  4585.3     .05       0  4705.8      .1       0    4854     .08       0
  4946.6      .1       0  4986.4     .07       0  5006.1      .1       0
Bank Sta=4865.02,5051.52
XS Rating Curve= 0 ,0
Exp/Cntr=0.3,0.1

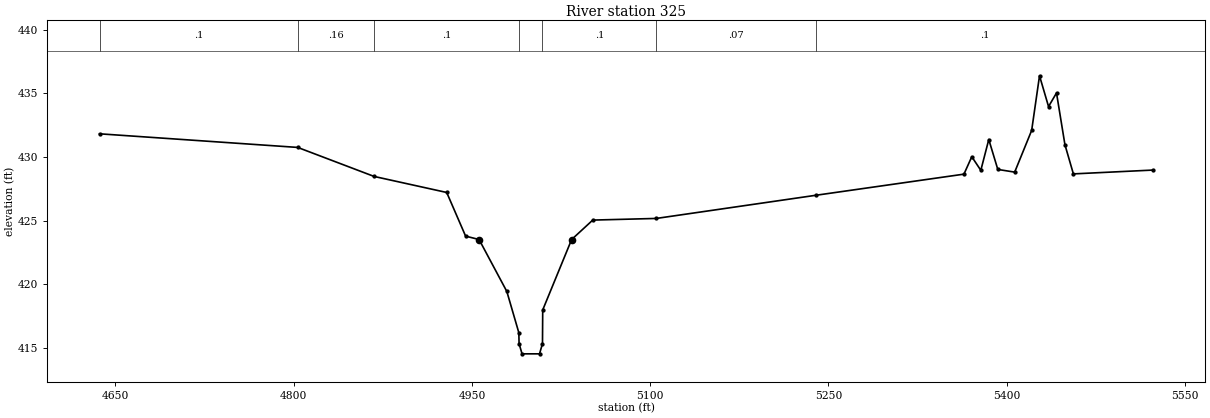
Type RM Length L Ch R = 1 ,325     ,0,0,0
BEGIN DESCRIPTION:
CHILTIPIN CREEK 1.0
END DESCRIPTION:
XS GIS Cut Line= 4
      2050821.42     13481601.87      2050881.36     13481291.74
      2050870.51     13481200.59      2050556.53     13480839.19
#Sta/Elev= 30
  4636.6  431.82  4803.4  430.75  4867.7  428.47  4928.8  427.21  4944.7  423.78
 4956.04423.5127  4979.4  419.43  4989.5  416.19  4989.7  415.33  4992.2  414.53
  5006.9  414.53  5009.4  415.33  5009.6  417.98 5033.92423.5123  5051.7  425.04
  5105.2  425.17  5239.5  426.99  5364.1  428.65  5370.7  430.02  5378.3  428.95
    5385  431.37  5392.6  429.02  5406.8  428.81  5421.1  432.09  5427.7  436.38
  5435.3  433.96    5442  435.03  5449.1  430.96  5456.2  428.67    5523  428.97
#Mann= 7 ,-1 , 0
  4636.6      .1       0  4803.4     .16       0  4867.7      .1       0
  4989.7     .07       0  5009.4      .1       0  5105.2     .07       0
  5239.5      .1       0
Bank Sta=4956.04,5033.92
XS Rating Curve= 0 ,0
Exp/Cntr=0.3,0.1
LCMann Table=0

Chan Stop Cuts=-1
Use User Specified Reach Order=0
Composite Channel Slope=5