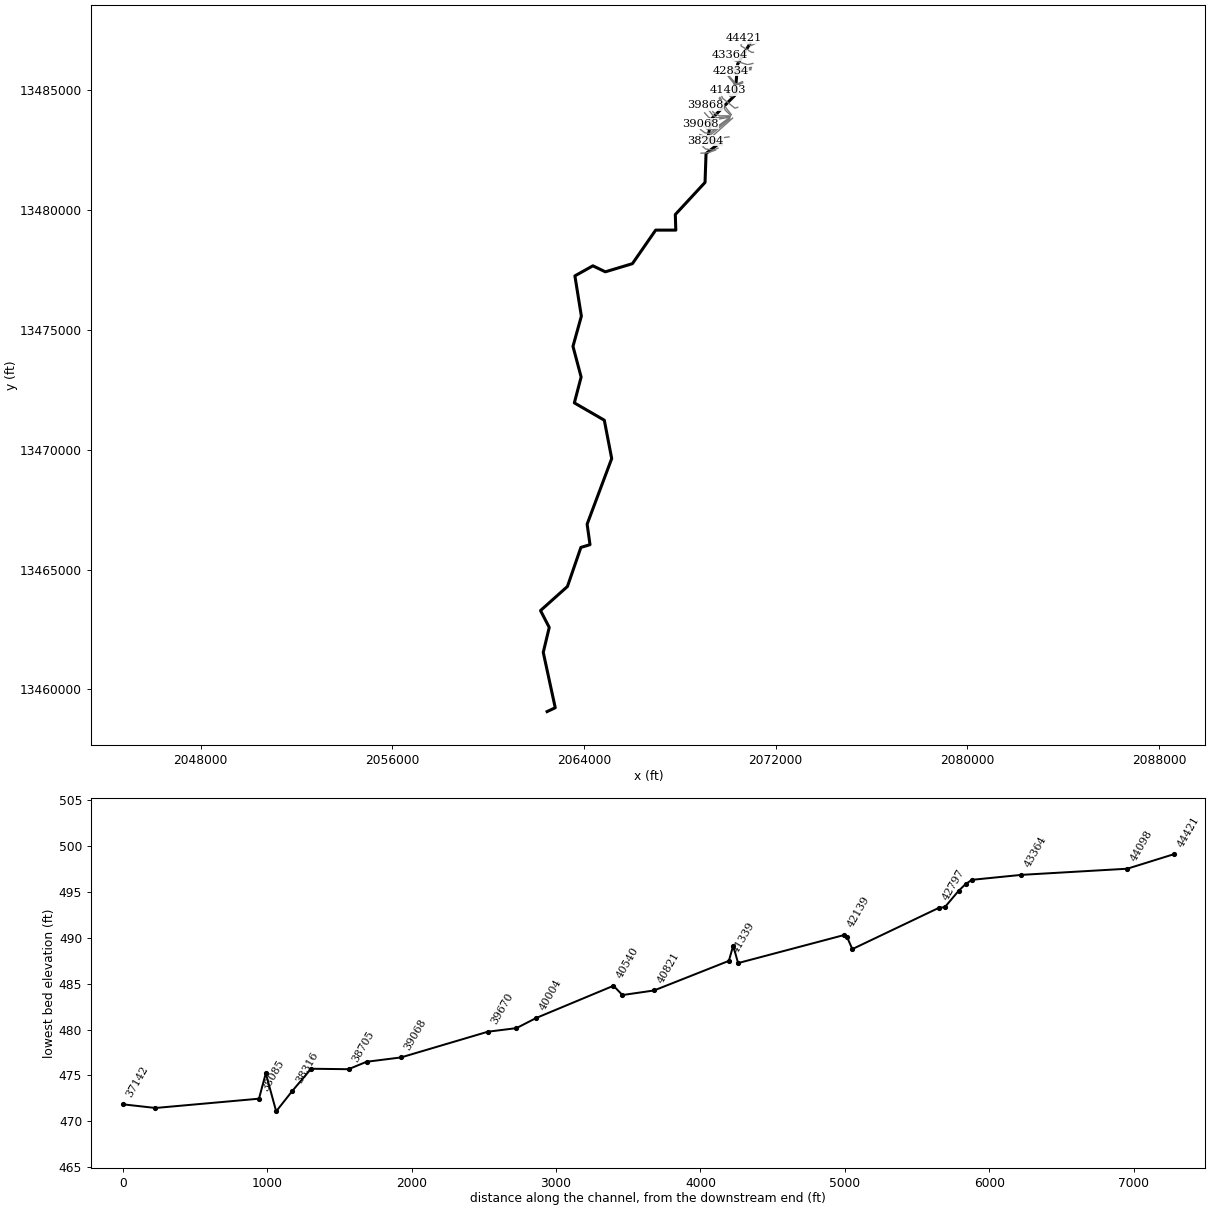
--- DOAK Br.prj (project) ---

Proj Title=DOAK Br Base Level Engineering
Current Plan=p01
Default Exp/Contr=0.3,0.1
English Units
Geom File=g01
Flow File=f01
Plan File=p01
Y Axis Title=Elevation
X Axis Title(PF)=Main Channel Distance
X Axis Title(XS)=Station
BEGIN DESCRIPTION:
DOAK Br
END DESCRIPTION:
DSS Export Rating Curves= 0
DSS Export Rating Curve Sorted= 0
DSS Export Volume Flow Curves= 0
DXF OffsetX= 0
DXF OffsetY= 0
DXF ScaleX= 1
DXF ScaleY= 10

--- DOAK Br.p01 (plan) ---

Plan Title=Multiple Run
Short Identifier=Multiple
Geom File=g01
Flow File=f01
Subcritical Flow
K Sum by GR= 0
Std Step Tol= 0.01
Critical Tol= 0.01
Num of Std Step Trials= 20
Max Error Tol= 0.3
Flow Tol Ratio= 0.001
Split Flow NTrial= 30
Split Flow Tol= 0.02
Split Flow Ratio= 0.02
Log Output Level= 0
Friction Slope Method= 1
Unsteady Friction Slope Method= 2
Unsteady Bridges Friction Slope Method= 1
Parabolic Critical Depth
Global Vel Dist=  1 , 1 , 1
Global Log Level= 0
CheckData=True
Encroach Param= -1, 0, 0, 0
BEGIN DESCRIPTION:
Multiple Run
END DESCRIPTION:

--- DOAK Br.f01 (steady flow) ---

Flow Title=Multiple
Program Version=5.05
Number of Profiles= 7
Profile Names=10-year,25-year,50-year,1pct_min,100-year,1pct_plu,500-year
River Rch & RM=DOAK Br,Reach-1         ,44421
     160     215     259     156     311     621     455
River Rch & RM=DOAK Br,Reach-1         ,38446
     240     330     404     247     492     981     740
River Rch & RM=DOAK Br,Reach-1         ,34139
     393     553     688     425     849    1694    1313
River Rch & RM=DOAK Br,Reach-1         ,26173
     736    1063    1344     844    1685    3362    2689
River Rch & RM=DOAK Br,Reach-1         ,24354
     767    1105    1396     876    1747    3486    2780
River Rch & RM=DOAK Br,Reach-1         ,18949
     798    1151    1454     912    1820    3632    2897
River Rch & RM=DOAK Br,Reach-1         ,16712
     798    1151    1454     912    1820    3632    2897
River Rch & RM=DOAK Br,Reach-1         ,11809
     885    1281    1622    1019    2034    4059    3249
River Rch & RM=DOAK Br,Reach-1         ,9168
     885    1281    1622    1019    2034    4059    3249
Boundary for River Rch & Prof#=DOAK Br,Reach-1         , 1
Up Type= 0
Dn Type= 3
Dn Slope=0.01148
Boundary for River Rch & Prof#=DOAK Br,Reach-1         , 2
Up Type= 0
Dn Type= 3
Dn Slope=0.01148
Boundary for River Rch & Prof#=DOAK Br,Reach-1         , 3
Up Type= 0
Dn Type= 3
Dn Slope=0.01148
Boundary for River Rch & Prof#=DOAK Br,Reach-1         , 4
Up Type= 0
Dn Type= 3
Dn Slope=0.01148
Boundary for River Rch & Prof#=DOAK Br,Reach-1         , 5
Up Type= 0
Dn Type= 3
Dn Slope=0.01148
Boundary for River Rch & Prof#=DOAK Br,Reach-1         , 6
Up Type= 0
Dn Type= 3
Dn Slope=0.01148
Boundary for River Rch & Prof#=DOAK Br,Reach-1         , 7
Up Type= 0
Dn Type= 3
Dn Slope=0.01148
DSS Import GetInterval= 0
DSS Import GetPeak= 0
DSS Import FillOption= 0

--- DOAK Br.g01 (geometry) ---

Geom Title=Existing Conditions

River Reach=DOAK Br,Reach-1
Reach XY= 30
      2070930.80     13486954.54      2070412.88     13486096.61
      2070300.80     13484794.54      2069320.80     13483804.54
      2069180.80     13483074.54      2069533.71     13482704.66
      2069092.74     13482360.91      2069050.80     13481154.54
      2067810.80     13479814.54      2067830.80     13479164.54
      2066990.80     13479164.54      2066020.80     13477764.54
      2064890.80     13477424.54      2064370.80     13477674.54
      2063620.80     13477254.54      2063890.80     13475574.54
      2063540.80     13474314.54      2063880.80     13473034.54
      2063597.77     13471956.16      2064847.77     13471232.72
      2065156.62     13469632.20      2064130.92     13466894.51
      2064251.36     13466039.47      2063870.80     13465924.54
      2063309.74     13464294.82      2062186.48     13463289.62
      2062550.19     13462585.62      2062300.80     13461544.54
      2062800.80     13459234.54      2062460.80     13459074.54

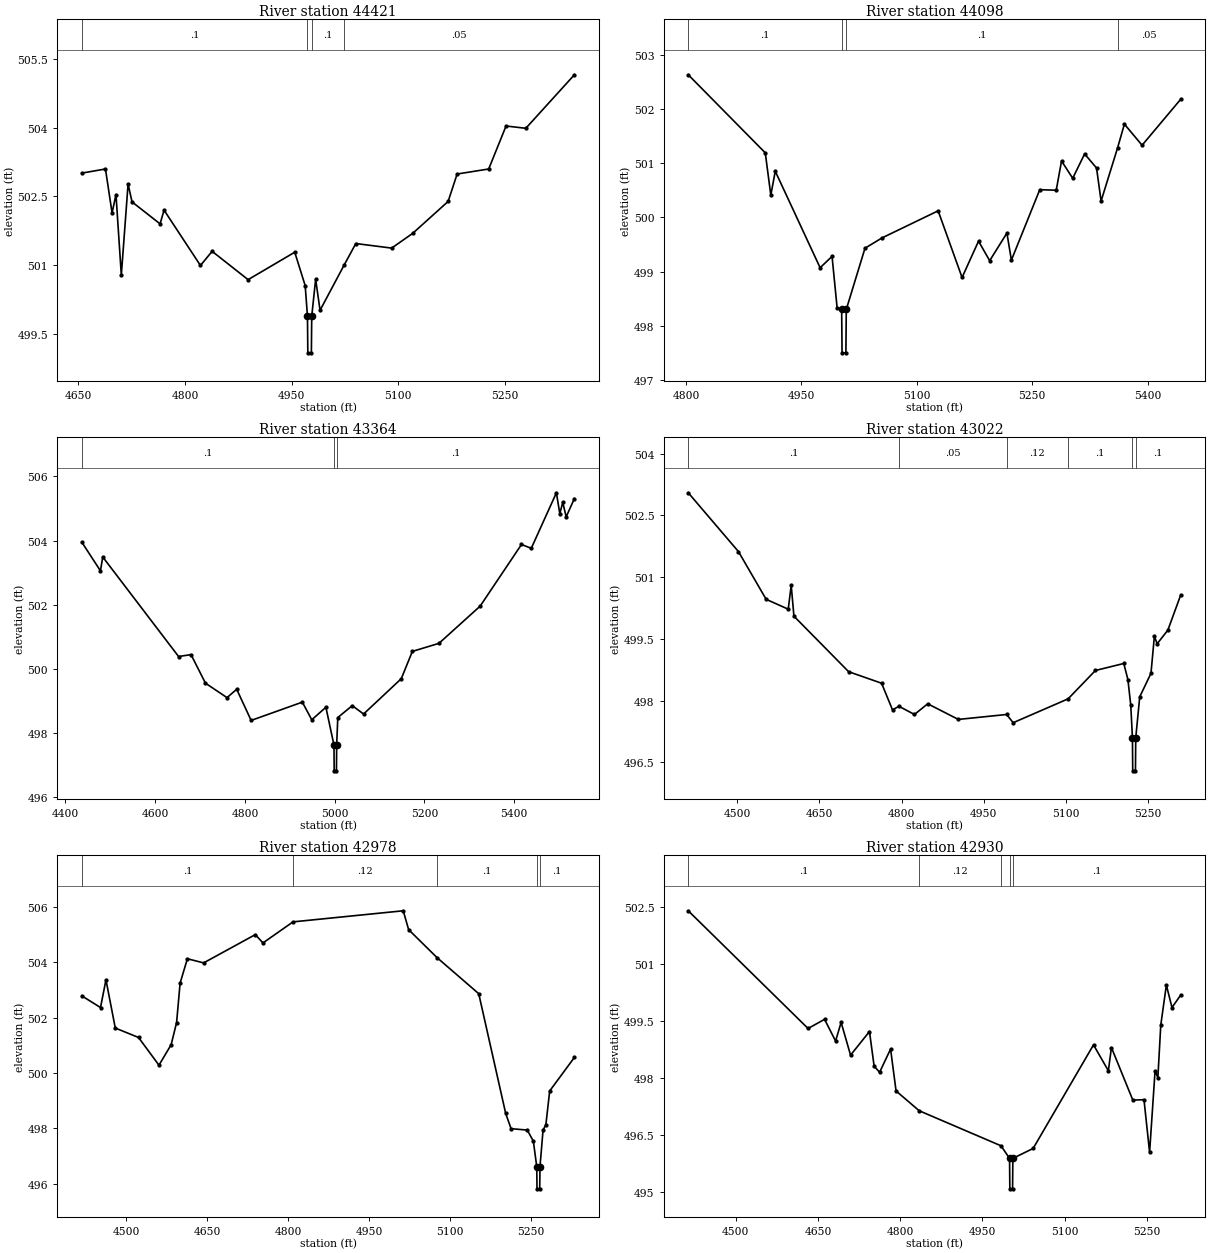
Type RM Length L Ch R = 1,44421,323,323,323
BEGIN DESCRIPTION:
Mapping XS a0e58a20
END DESCRIPTION:
XS GIS Cut Line= 4
      2071184.86     13486970.26      2070960.86     13486860.87
      2070710.86     13487040.55      2070671.91     13487170.39
#Sta/Elev= 30
  4654.9  503.01  4688.1  503.10  4697.4  502.14  4702.9  502.54  4710.4  500.78
  4719.9  502.77  4725.5  502.38  4764.9  501.90  4770.5  502.20  4821.7  500.99
  4838.1  501.30  4888.7  500.68  4954.3  501.28  4969.0  500.55  4972.2  499.88
  4972.7  499.08  4977.7  499.08  4978.2  499.88  4983.7  500.69  4989.9  500.01
  5023.8  501.00  5040.2  501.47  5090.6  501.37  5120.0  501.69  5170.0  502.39
  5182.7  502.99  5227.1  503.10  5251.5  504.04  5279.3  503.99  5347.6  505.16
#Mann=4,-1,0
  4654.9     0.1       0  4972.2    0.07       0  4978.2     0.1       0
  5023.8    0.05       0
Bank Sta=4972.2,4978.2
Exp/Cntr=0.3,0.1

Type RM Length L Ch R = 1,44098,734,734,734
BEGIN DESCRIPTION:
Mapping XS 2d3c3ad2
END DESCRIPTION:
XS GIS Cut Line= 4
      2071070.94     13486582.45      2070999.77     13486580.71
      2070555.33     13486848.07      2070557.06     13486898.39
#Sta/Elev= 30
  4802.9  502.63  4903.0  501.19  4910.2  500.41  4916.0  500.85  4974.3  499.07
  4989.8  499.28  4996.4  498.33  5002.3  498.30  5002.8  497.50  5007.8  497.50
  5008.3  498.30  5032.6  499.43  5054.7  499.62  5127.7  500.12  5158.8  498.89
  5180.2  499.56  5194.7  499.20  5217.1  499.71  5222.9  499.21  5259.8  500.51
  5281.2  500.50  5288.1  501.04  5302.6  500.72  5318.1  501.17  5333.6  500.91
  5339.5  500.30  5360.9  501.28  5369.8  501.72  5392.8  501.33  5443.1  502.18
#Mann=4,-1,0
  4802.9     0.1       0  5002.3    0.07       0  5008.3     0.1       0
  5360.9    0.05       0
Bank Sta=5002.3,5008.3
Exp/Cntr=0.3,0.1

Type RM Length L Ch R = 1,43364,342,342,342
BEGIN DESCRIPTION:
Mapping XS 8a2ab5ef
END DESCRIPTION:
XS GIS Cut Line= 4
      2071047.89     13486120.11      2070822.69     13486066.82
      2070264.08     13486245.12      2070079.57     13486455.61
#Sta/Elev= 30
  4436.5  503.95  4477.9  503.06  4483.1  503.49  4652.1  500.39  4679.8  500.45
  4712.0  499.56  4760.0  499.11  4781.6  499.37  4813.8  498.40  4927.9  498.97
  4948.9  498.42  4980.4  498.81  4998.4  497.63  4998.9  496.83  5003.9  496.83
  5004.4  497.63  5006.9  498.49  5039.1  498.86  5064.4  498.60  5148.4  499.70
  5173.1  500.55  5232.3  500.80  5324.2  501.96  5416.3  503.88  5438.1  503.76
  5494.1  505.49  5501.7  504.84  5508.3  505.19  5515.9  504.74  5534.2  505.31
#Mann=3,-1,0
  4436.5     0.1       0  4998.4    0.07       0  5004.4     0.1       0
Bank Sta=4998.4,5004.4
Exp/Cntr=0.3,0.1

Type RM Length L Ch R = 1,43022,44,44,44
BEGIN DESCRIPTION:
Mapping XS 9d61fe9f
END DESCRIPTION:
XS GIS Cut Line= 6
      2070985.85     13485954.75      2070789.68     13485928.71
      2070481.52     13485917.43      2070326.14     13485912.22
      2070193.33     13485917.43      2070091.94     13485940.43
#Sta/Elev= 30
  4410.9  503.05  4502.5  501.62  4553.0  500.46  4593.3  500.22  4598.7  500.80
  4603.7  500.05  4703.5  498.70  4763.6  498.42  4783.6  497.77  4795.2  497.86
  4823.6  497.66  4847.8  497.92  4903.7  497.54  4991.7  497.66  5003.7  497.46
  5103.9  498.04  5153.8  498.73  5205.5  498.90  5213.0  498.51  5218.2  497.89
  5221.3  497.09  5221.8  496.29  5226.8  496.29  5227.3  497.09  5234.6  498.09
  5255.1  498.66  5261.3  499.56  5266.4  499.38  5285.9  499.71  5309.5  500.57
#Mann=6,-1,0
  4410.9     0.1       0  4795.2    0.05       0  4991.7    0.12       0
  5103.9     0.1       0  5221.3    0.07       0  5227.3     0.1       0
Bank Sta=5221.3,5227.3
Exp/Cntr=0.3,0.1

Type RM Length L Ch R = 1,42978,48,48,48
BEGIN DESCRIPTION:
Mapping XS b6457c07
END DESCRIPTION:
XS GIS Cut Line= 6
      2070969.35     13485907.88      2070787.08     13485885.31
      2070446.80     13485872.29      2070274.93     13485870.55
      2070137.77     13485872.29      2070061.38     13485896.60
#Sta/Elev= 30
  4417.5  502.78  4452.1  502.36  4462.2  503.36  4479.5  501.62  4522.6  501.28
  4560.5  500.28  4583.1  501.02  4593.2  501.82  4599.7  503.24  4613.2  504.12
  4643.3  503.97  4739.2  504.99  4753.4  504.69  4809.1  505.45  5013.5  505.85
  5023.5  505.17  5076.2  504.16  5153.5  502.86  5203.5  498.54  5213.5  497.99
  5243.5  497.94  5254.8  497.54  5261.1  496.62  5261.6  495.82  5266.6  495.82
  5267.1  496.62  5272.8  497.94  5278.0  498.13  5285.1  499.35  5330.9  500.56
#Mann=5,-1,0
  4417.5     0.1       0  4809.1    0.12       0  5076.2     0.1       0
  5261.1    0.07       0  5267.1     0.1       0
Bank Sta=5261.1,5267.1
Exp/Cntr=0.3,0.1

Type RM Length L Ch R = 1,42930,96,96,96
BEGIN DESCRIPTION:
Mapping XS 34ebb734
END DESCRIPTION:
XS GIS Cut Line= 6
      2070962.41     13485859.27      2070636.91     13485827.15
      2070310.52     13485823.68      2070195.93     13485829.76
      2070172.50     13485837.57      2070069.19     13485858.23
#Sta/Elev= 30
  4413.4  502.39  4631.9  499.30  4662.0  499.54  4682.1  498.97  4692.2  499.46
  4709.4  498.60  4743.9  499.22  4752.4  498.31  4762.4  498.15  4782.4  498.76
  4792.4  497.66  4834.6  497.14  4983.8  496.22  4999.4  495.89  4999.9  495.09
  5004.9  495.09  5005.4  495.89  5042.4  496.15  5152.5  498.87  5179.6  498.19
  5185.2  498.80  5224.2  497.42  5244.6  497.43  5254.8  496.05  5264.8  498.19
  5269.9  498.01  5275.2  499.39  5285.4  500.44  5295.6  499.85  5311.7  500.18
#Mann=5,-1,0
  4413.4     0.1       0  4834.6    0.12       0  4983.8     0.1       0
  4999.4    0.07       0  5005.4     0.1       0
Bank Sta=4999.4,5005.4
Exp/Cntr=0.3,0.1

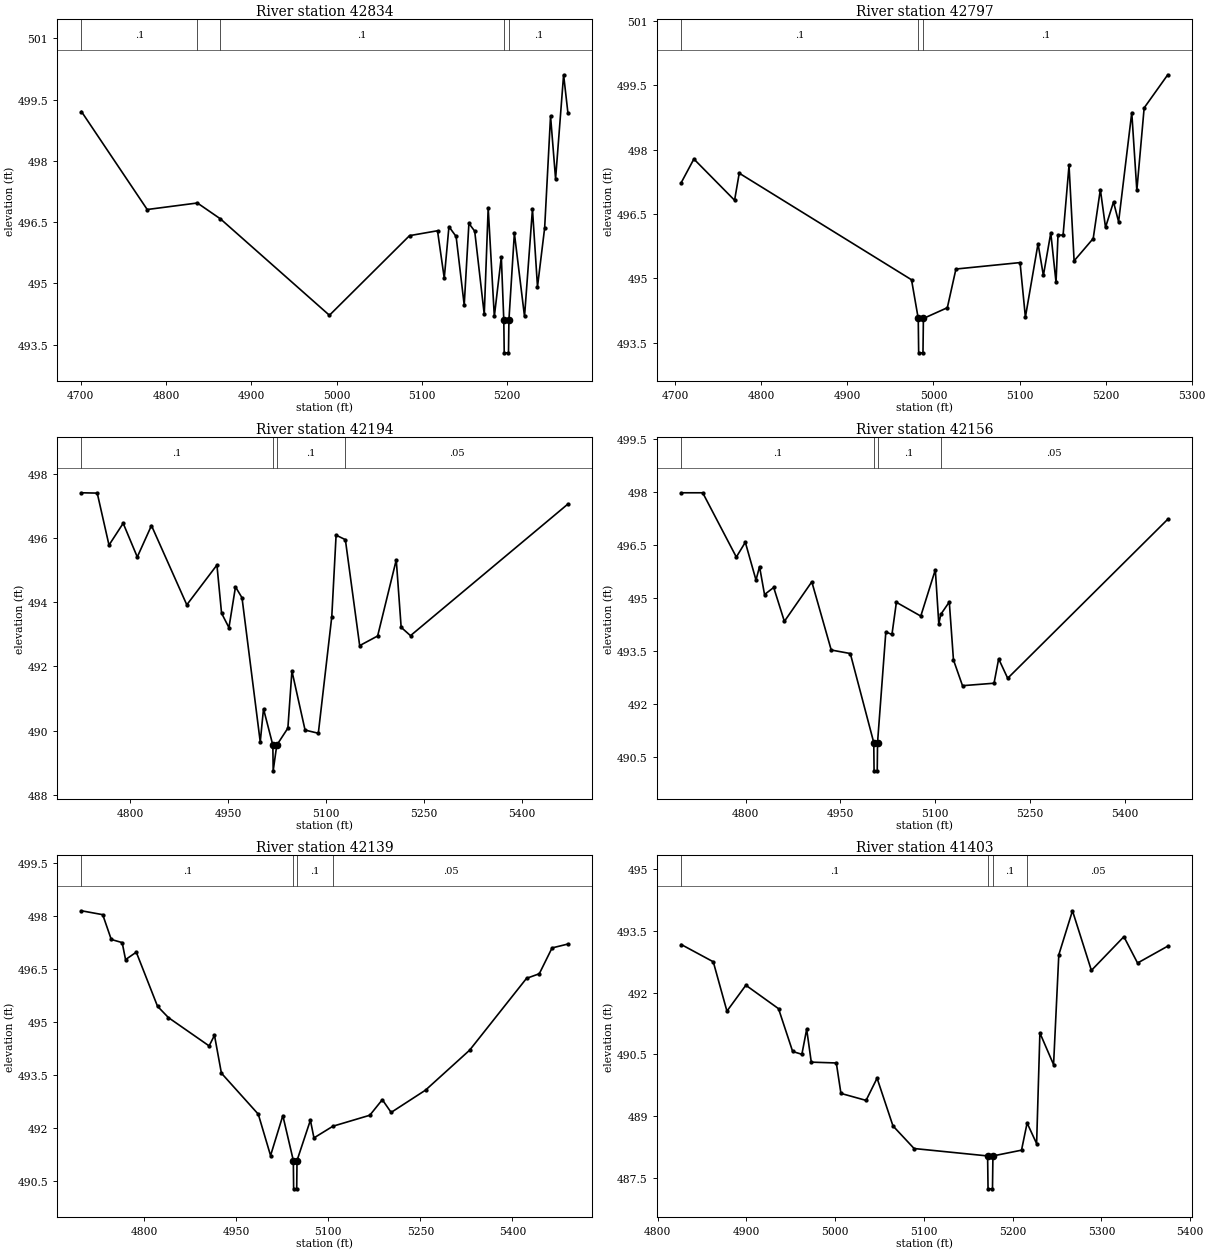
Type RM Length L Ch R = 1,42834,37,37,37
BEGIN DESCRIPTION:
Mapping XS 17d717d5
END DESCRIPTION:
XS GIS Cut Line= 6
      2070641.15     13485823.64      2070513.53     13485784.05
      2070393.74     13485739.78      2070303.12     13485720.51
      2070197.91     13485766.34      2070111.84     13485820.26
#Sta/Elev= 30
  4700.9  499.21  4778.0  496.81  4836.8  496.97  4863.9  496.58  4991.6  494.22
  5085.5  496.17  5118.3  496.29  5126.2  495.13  5131.7  496.39  5140.1  496.15
  5149.6  494.47  5155.1  496.47  5161.9  496.28  5173.1  494.24  5177.7  496.85
  5184.9  494.19  5193.1  495.65  5196.0  494.10  5196.5  493.30  5201.5  493.30
  5202.0  494.10  5208.4  496.23  5220.3  494.19  5229.6  496.82  5235.5  494.92
  5243.9  496.36  5250.8  499.10  5256.7  497.56  5266.1  500.11  5271.2  499.17
#Mann=5,-1,0
  4700.9     0.1       0  4836.8    0.12       0  4863.9     0.1       0
  5196.0    0.07       0  5202.0     0.1       0
Bank Sta=5196,5202
Exp/Cntr=0.3,0.1

Type RM Length L Ch R = 1,42797,603,603,603
BEGIN DESCRIPTION:
Mapping XS 5b7cd5d9
END DESCRIPTION:
XS GIS Cut Line= 6
      2070635.38     13485794.98      2070454.16     13485717.91
      2070330.72     13485687.70      2070283.85     13485683.53
      2070229.16     13485722.59      2070121.91     13485790.66
#Sta/Elev= 30
  4706.9  497.23  4721.6  497.78  4768.9  496.82  4774.3  497.45  4974.5  494.97
  4982.3  494.07  4982.8  493.27  4987.8  493.27  4988.3  494.07  5016.1  494.32
  5026.1  495.22  5100.6  495.37  5106.8  494.10  5121.5  495.81  5127.7  495.07
  5136.3  496.06  5142.4  494.91  5144.7  496.01  5150.6  496.01  5157.5  497.63
  5163.4  495.41  5185.6  495.93  5193.9  497.07  5199.9  496.19  5209.2  496.78
  5215.1  496.32  5230.4  498.86  5236.3  497.05  5244.8  498.97  5272.2  499.74
#Mann=3,-1,0
  4706.9     0.1       0  4982.3    0.07       0  4988.3     0.1       0
Bank Sta=4982.3,4988.3
Exp/Cntr=0.3,0.1

Type RM Length L Ch R = 1,42194,38,38,38
BEGIN DESCRIPTION:
Mapping XS 3ab9debe
END DESCRIPTION:
XS GIS Cut Line= 5
      2070613.96     13485358.62      2070411.88     13485274.59
      2070307.72     13485266.26      2070300.08     13485313.48
      2070053.53     13485594.06
#Sta/Elev= 30
  4725.5  497.41  4749.7  497.40  4767.7  495.78  4789.4  496.46  4811.0  495.41
  4832.7  496.39  4886.8  493.92  4932.9  495.16  4940.0  493.66  4951.3  493.21
  4961.3  494.48  4971.3  494.14  4999.2  489.65  5004.2  490.68  5018.5  489.55
  5019.0  488.75  5024.5  489.55  5041.5  490.08  5047.7  491.86  5067.8  490.02
  5088.1  489.92  5108.7  493.55  5115.3  496.09  5129.5  495.95  5151.4  492.65
  5178.9  492.95  5207.4  495.32  5214.9  493.22  5229.2  492.96  5470.2  497.06
#Mann=4,-1,0
  4725.5     0.1       0  5018.5    0.07       0  5024.5     0.1       0
  5129.5    0.05       0
Bank Sta=5018.5,5024.5
Exp/Cntr=0.3,0.1

Type RM Length L Ch R = 1,42156,17,17,17
BEGIN DESCRIPTION:
Mapping XS e2e68570
END DESCRIPTION:
XS GIS Cut Line= 5
      2070613.25     13485333.61      2070447.99     13485252.37
      2070298.69     13485239.17      2070262.58     13485318.34
      2070038.77     13485585.67
#Sta/Elev= 30
  4698.2  497.99  4732.2  497.99  4785.4  496.17  4799.6  496.59  4816.5  495.52
  4822.1  495.90  4830.0  495.11  4844.5  495.31  4861.4  494.35  4904.8  495.47
  4935.5  493.54  4965.7  493.44  5002.8  490.92  5003.3  490.12  5008.3  490.12
  5008.8  490.92  5021.9  494.05  5031.6  493.98  5038.6  494.89  5077.2  494.50
  5100.2  495.81  5105.7  494.28  5108.9  494.55  5122.3  494.90  5128.9  493.26
  5143.2  492.53  5193.1  492.60  5200.4  493.29  5214.7  492.74  5467.9  497.24
#Mann=4,-1,0
  4698.2     0.1       0  5002.8    0.07       0  5008.8     0.1       0
  5108.9    0.05       0
Bank Sta=5002.8,5008.8
Exp/Cntr=0.3,0.1

Type RM Length L Ch R = 1,42139,736,736,736
BEGIN DESCRIPTION:
Mapping XS b93111a1
END DESCRIPTION:
XS GIS Cut Line= 5
      2070616.77     13485308.63      2070442.44     13485231.54
      2070279.94     13485223.20      2070220.22     13485330.15
      2070020.93     13485576.65
#Sta/Elev= 30
  4697.6  498.15  4732.3  498.04  4746.2  497.34  4764.0  497.25  4769.5  496.77
  4787.0  496.98  4821.6  495.45  4839.4  495.13  4905.7  494.33  4914.4  494.63
  4925.7  493.56  4985.8  492.40  5005.8  491.23  5025.8  492.36  5042.9  491.09
  5043.4  490.29  5048.4  490.29  5048.9  491.09  5070.7  492.23  5076.5  491.73
  5107.4  492.06  5167.5  492.37  5187.9  492.81  5202.3  492.45  5258.3  493.08
  5330.2  494.21  5422.9  496.24  5443.7  496.37  5464.5  497.10  5490.4  497.21
#Mann=4,-1,0
  4697.6     0.1       0  5042.9    0.07       0  5048.9     0.1       0
  5107.4    0.05       0
Bank Sta=5042.9,5048.9
Exp/Cntr=0.3,0.1

Type RM Length L Ch R = 1,41403,34,34,34
BEGIN DESCRIPTION:
Mapping XS 62ca25c5
END DESCRIPTION:
XS GIS Cut Line= 6
      2070423.16     13484917.38      2070325.25     13484857.49
      2070171.61     13484806.97      2070135.67     13484798.12
      2070080.98     13484865.30      2070003.41     13484990.97
#Sta/Elev= 30
  4826.7  493.17  4862.8  492.75  4878.2  491.55  4899.5  492.18  4936.3  491.61
  4952.2  490.57  4962.6  490.50  4968.0  491.11  4973.2  490.31  5001.4  490.29
  5006.6  489.55  5034.9  489.38  5047.3  489.92  5065.2  488.76  5089.0  488.21
  5171.8  488.03  5172.3  487.23  5177.3  487.23  5177.8  488.03  5210.0  488.17
  5216.3  488.83  5227.0  488.33  5230.7  491.02  5246.1  490.25  5252.0  492.92
  5267.4  493.99  5288.7  492.54  5325.3  493.36  5340.7  492.72  5374.7  493.13
#Mann=4,-1,0
  4826.7     0.1       0  5171.8    0.07       0  5177.8     0.1       0
  5216.3    0.05       0
Bank Sta=5171.8,5177.8
Exp/Cntr=0.3,0.1

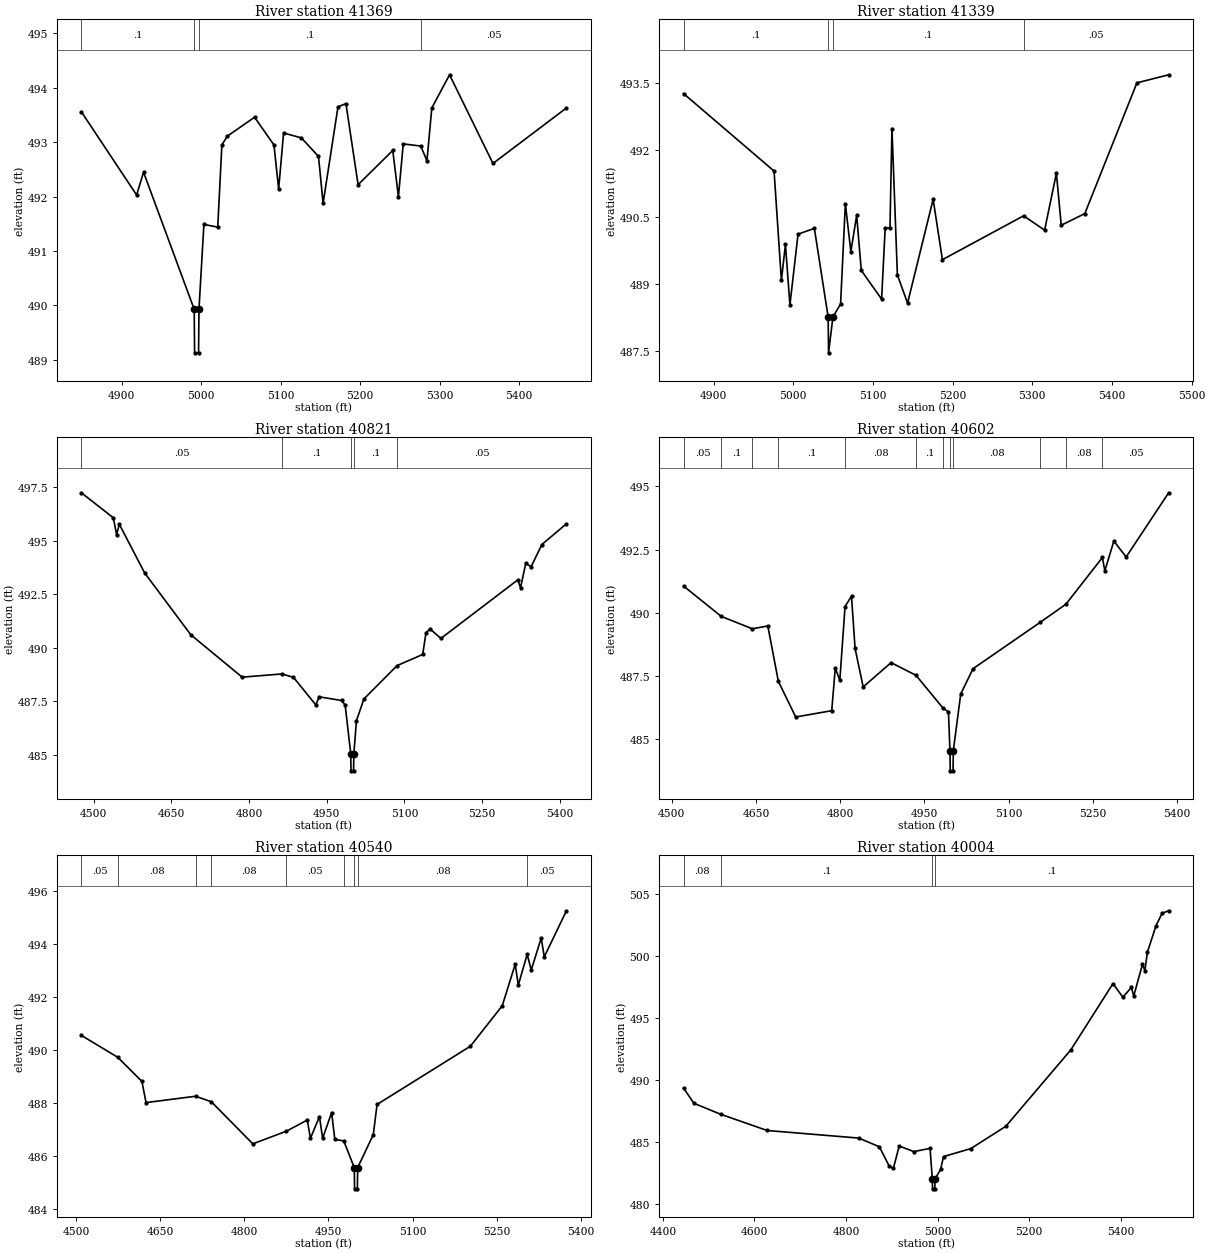
Type RM Length L Ch R = 1,41369,30,30,30
BEGIN DESCRIPTION:
Mapping XS 328795f3
END DESCRIPTION:
XS GIS Cut Line= 6
      2070434.61     13484890.29      2070334.11     13484838.74
      2070215.36     13484797.07      2070160.67     13484756.45
      2070118.48     13484760.09      2069983.26     13484980.97
#Sta/Elev= 30
  4849.4  493.56  4918.9  492.03  4927.6  492.45  4991.3  489.93  4991.8  489.13
  4996.8  489.13  4997.3  489.93  5003.5  491.49  5020.9  491.44  5026.1  492.95
  5032.8  493.11  5067.2  493.46  5091.6  492.95  5097.5  492.14  5103.7  493.17
  5126.1  493.08  5147.6  492.74  5153.4  491.88  5172.1  493.65  5182.1  493.71
  5197.4  492.22  5241.0  492.85  5248.1  492.00  5254.2  492.97  5276.2  492.93
  5284.0  492.66  5290.1  493.63  5312.4  494.24  5367.0  492.61  5459.4  493.63
#Mann=4,-1,0
  4849.4     0.1       0  4991.3    0.07       0  4997.3     0.1       0
  5276.2    0.05       0
Bank Sta=4991.3,4997.3
Exp/Cntr=0.3,0.1

Type RM Length L Ch R = 1,41339,518,518,518
BEGIN DESCRIPTION:
Mapping XS c7939005
END DESCRIPTION:
XS GIS Cut Line= 6
      2070429.46     13484846.05      2070328.90     13484803.84
      2070247.65     13484788.22      2070174.21     13484741.87
      2070104.94     13484737.70      2069959.27     13484945.58
#Sta/Elev= 30
  4862.2  493.26  4975.8  491.53  4985.0  489.09  4990.1  489.89  4995.7  488.54
  5005.9  490.12  5026.4  490.25  5043.7  488.27  5044.2  487.47  5049.7  488.27
  5059.3  488.56  5065.3  490.80  5072.2  489.73  5079.5  490.54  5085.3  489.31
  5110.8  488.67  5115.3  490.26  5121.3  490.26  5123.8  492.48  5130.6  489.21
  5143.4  488.58  5175.5  490.90  5187.1  489.55  5289.0  490.53  5315.4  490.21
  5330.2  491.48  5336.3  490.32  5365.9  490.58  5431.3  493.50  5471.1  493.68
#Mann=4,-1,0
  4862.2     0.1       0  5043.7    0.07       0  5049.7     0.1       0
  5289.0    0.05       0
Bank Sta=5043.7,5049.7
Exp/Cntr=0.3,0.1

Type RM Length L Ch R = 1,40821,219,219,219
BEGIN DESCRIPTION:
Mapping XS 739555f1
END DESCRIPTION:
XS GIS Cut Line= 4
      2070414.16     13484290.14      2070294.35     13484253.67
      2069772.65     13484673.81      2069735.57     13484810.90
#Sta/Elev= 30
  4475.9  497.25  4537.7  496.08  4544.0  495.29  4549.2  495.78  4598.2  493.50
  4687.4  490.61  4786.5  488.63  4863.7  488.78  4885.7  488.62  4928.9  487.33
  4935.3  487.71  4978.5  487.54  4985.5  487.33  4996.3  485.05  4996.8  484.25
  5001.8  484.25  5002.3  485.05  5007.3  486.59  5021.7  487.61  5085.8  489.17
  5135.3  489.69  5141.7  490.71  5149.6  490.88  5170.5  490.44  5319.1  493.18
  5324.3  492.81  5334.4  493.95  5344.7  493.79  5365.5  494.83  5413.0  495.80
#Mann=5,-1,0
  4475.9    0.05       0  4863.7     0.1       0  4996.3    0.07       0
  5002.3     0.1       0  5085.8    0.05       0
Bank Sta=4996.3,5002.3
Exp/Cntr=0.3,0.1

Type RM Length L Ch R = 1,40602,62,62,62
BEGIN DESCRIPTION:
Mapping XS 2bead4e2
END DESCRIPTION:
XS GIS Cut Line= 4
      2070146.19     13483986.19      2069882.54     13484320.39
      2069781.85     13484507.02      2069673.34     13484705.80
#Sta/Elev= 30
  4521.0  491.06  4588.1  489.86  4643.5  489.37  4671.1  489.48  4689.9  487.29
  4720.8  485.88  4785.0  486.13  4791.3  487.82  4799.4  487.33  4808.7  490.25
  4820.2  490.66  4826.6  488.59  4841.0  487.07  4890.7  488.03  4935.1  487.53
  4982.9  486.24  4992.9  486.08  4995.6  484.55  4996.1  483.75  5001.1  483.75
  5001.6  484.55  5014.8  486.79  5036.7  487.79  5156.7  489.63  5202.1  490.34
  5267.2  492.19  5271.5  491.66  5287.6  492.84  5309.5  492.21  5385.2  494.75
#Mann=12,-1,0
  4521.0    0.05       0  4588.1     0.1       0  4643.5    0.08       0
  4689.9     0.1       0  4808.7    0.08       0  4935.1     0.1       0
  4982.9    0.08       0  4995.6    0.07       0  5001.6    0.08       0
  5156.7    0.05       0  5202.1    0.08       0  5267.2    0.05       0
Bank Sta=4995.6,5001.6
Exp/Cntr=0.3,0.1

Type RM Length L Ch R = 1,40540,536,536,536
BEGIN DESCRIPTION:
Mapping XS 3d6bd178
END DESCRIPTION:
XS GIS Cut Line= 5
      2070120.18     13483957.52      2069901.64     13484162.41
      2069776.64     13484385.50      2069714.14     13484506.16
      2069642.94     13484664.18
#Sta/Elev= 30
  4509.6  490.56  4574.6  489.73  4617.5  488.82  4624.9  488.02  4713.3  488.26
  4741.3  488.05  4815.2  486.46  4875.1  486.94  4912.2  487.36  4917.9  486.67
  4933.9  487.49  4939.6  486.67  4955.6  487.64  4961.3  486.63  4977.3  486.57
  4996.0  485.56  4996.5  484.76  5001.5  484.76  5002.0  485.56  5029.9  486.81
  5036.6  487.95  5202.9  490.15  5259.7  491.68  5282.8  493.25  5288.3  492.46
  5304.1  493.62  5311.4  493.03  5329.1  494.24  5334.6  493.53  5374.1  495.27
#Mann=9,-1,0
  4509.6    0.05       0  4574.6    0.08       0  4713.3    0.05       0
  4741.3    0.08       0  4875.1    0.05       0  4977.3    0.08       0
  4996.0    0.07       0  5002.0    0.08       0  5304.1    0.05       0
Bank Sta=4996,5002
Exp/Cntr=0.3,0.1

Type RM Length L Ch R = 1,40004,136,136,136
BEGIN DESCRIPTION:
Mapping XS a94af0b1
END DESCRIPTION:
XS GIS Cut Line= 4
      2070057.62     13483931.49      2069644.26     13483933.89
      2069393.39     13484074.52      2069260.79     13484408.06
#Sta/Elev= 30
  4445.1  489.37  4467.7  488.14  4526.1  487.26  4627.7  485.95  4827.7  485.34
  4872.9  484.64  4894.6  483.07  4903.5  482.90  4916.3  484.70  4948.2  484.25
  4983.7  484.51  4988.6  482.05  4989.1  481.25  4994.1  481.25  4994.6  482.05
  5006.6  482.81  5013.2  483.85  5072.6  484.49  5149.0  486.28  5291.2  492.44
  5383.3  497.78  5404.9  496.69  5423.5  497.47  5428.8  496.79  5447.8  499.34
  5453.1  498.83  5458.7  500.33  5477.4  502.45  5490.9  503.46  5505.0  503.65
#Mann=4,-1,0
  4445.1    0.08       0  4526.1     0.1       0  4988.6    0.07       0
  4994.6     0.1       0
Bank Sta=4988.6,4994.6
Exp/Cntr=0.3,0.1

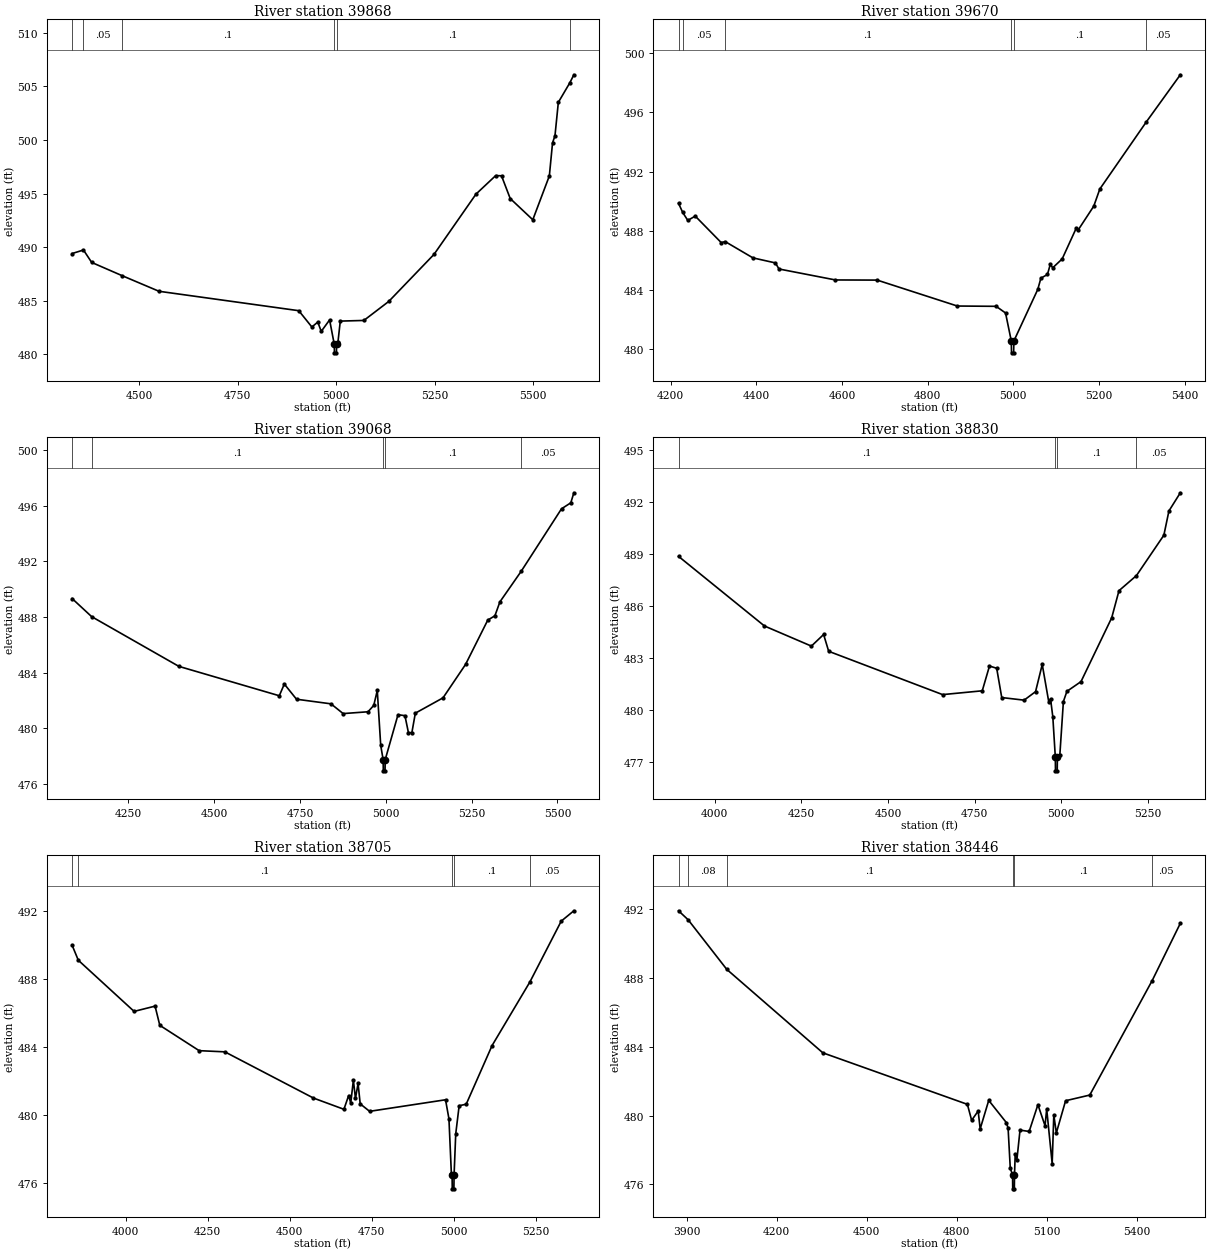
Type RM Length L Ch R = 1,39868,198,198,198
BEGIN DESCRIPTION:
Mapping XS 2ebe48f2
END DESCRIPTION:
XS GIS Cut Line= 4
      2070104.56     13483908.06      2069534.88     13483853.16
      2069360.40     13483969.48      2069069.06     13484365.06
#Sta/Elev= 30
  4330.0  489.41  4358.9  489.74  4379.8  488.58  4457.4  487.34  4550.6  485.89
  4905.3  484.08  4938.5  482.56  4953.5  483.02  4962.3  482.15  4983.5  483.22
  4995.3  480.95  4995.8  480.15  5000.8  480.15  5001.3  480.95  5004.6  481.12
  5010.6  483.11  5070.4  483.17  5133.5  484.94  5248.4  489.33  5354.9  494.95
  5405.0  496.68  5419.7  496.66  5441.8  494.54  5499.1  492.56  5541.1  496.65
  5549.2  499.73  5555.4  500.40  5563.9  503.51  5592.9  505.32  5603.3  506.08
#Mann=6,-1,0
  4330.0    0.08       0  4358.9    0.05       0  4457.4     0.1       0
  4995.3    0.07       0  5001.3     0.1       0  5592.9    0.05       0
Bank Sta=4995.3,5001.3
Exp/Cntr=0.3,0.1

Type RM Length L Ch R = 1,39670,602,602,602
BEGIN DESCRIPTION:
Mapping XS b0a8c275
END DESCRIPTION:
XS GIS Cut Line= 4
      2070086.30     13483876.80      2069411.62     13483763.75
      2069191.13     13483880.07      2069034.25     13484059.07
#Sta/Elev= 30
  4218.5  489.85  4228.2  489.24  4240.1  488.70  4257.5  488.99  4318.2  487.20
  4327.4  487.27  4392.2  486.17  4444.6  485.83  4453.0  485.42  4584.8  484.68
  4682.2  484.67  4869.3  482.92  4959.9  482.90  4981.9  482.45  4995.3  480.56
  4995.8  479.76  5000.8  479.76  5001.3  480.56  5057.1  484.04  5064.4  484.80
  5079.7  485.05  5086.4  485.74  5092.0  485.50  5114.1  486.10  5146.8  488.17
  5151.8  488.07  5187.8  489.66  5202.0  490.82  5310.3  495.34  5389.9  498.53
#Mann=6,-1,0
  4218.5    0.08       0  4228.2    0.05       0  4327.4     0.1       0
  4995.3    0.07       0  5001.3     0.1       0  5310.3    0.05       0
Bank Sta=4995.3,5001.3
Exp/Cntr=0.3,0.1

Type RM Length L Ch R = 1,39068,238,238,238
BEGIN DESCRIPTION:
Mapping XS 17b81d5e
END DESCRIPTION:
XS GIS Cut Line= 4
      2070068.05     13483855.95      2069371.69     13483347.08
      2069144.26     13483377.47      2068846.70     13483598.18
#Sta/Elev= 30
  4085.6  489.33  4142.6  488.03  4396.8  484.46  4689.5  482.35  4704.2  483.19
  4739.7  482.10  4840.1  481.77  4875.6  481.07  4948.1  481.20  4964.9  481.66
  4975.1  482.73  4985.1  478.79  4992.2  477.76  4992.7  476.96  4997.7  476.96
  4998.2  477.76  5035.5  480.99  5055.7  480.92  5065.8  479.71  5075.9  479.70
  5086.0  481.10  5166.7  482.20  5232.4  484.60  5297.1  487.78  5317.9  488.09
  5332.5  489.09  5394.4  491.28  5512.0  495.77  5539.1  496.20  5548.0  496.92
#Mann=5,-1,0
  4085.6    0.05       0  4142.6     0.1       0  4992.2    0.07       0
  4998.2     0.1       0  5394.4    0.05       0
Bank Sta=4992.2,4998.2
Exp/Cntr=0.3,0.1

Type RM Length L Ch R = 1,38830,125,125,125
BEGIN DESCRIPTION:
Mapping XS ae97a079
END DESCRIPTION:
XS GIS Cut Line= 4
      2070055.09     13483811.72      2069238.01     13483191.70
      2069040.09     13483228.16      2068862.34     13483358.58
#Sta/Elev= 30
  3895.8  488.87  4143.7  484.85  4279.0  483.69  4314.3  484.36  4328.9  483.39
  4657.5  480.89  4771.9  481.11  4792.7  482.54  4813.5  482.41  4828.1  480.72
  4892.6  480.57  4925.6  481.06  4944.9  482.63  4963.7  480.47  4968.8  480.65
  4975.4  479.61  4982.6  477.29  4983.1  476.49  4988.1  476.49  4988.6  477.29
  4995.7  477.42  5005.9  480.49  5016.1  481.08  5056.7  481.64  5145.2  485.32
  5166.3  486.89  5216.6  487.76  5295.7  490.09  5310.3  491.49  5343.2  492.54
#Mann=4,-1,0
  3895.8     0.1       0  4982.6    0.07       0  4988.6     0.1       0
  5216.6    0.05       0
Bank Sta=4982.6,4988.6
Exp/Cntr=0.3,0.1

Type RM Length L Ch R = 1,38705,259,259,259
BEGIN DESCRIPTION:
Mapping XS 490fc340
END DESCRIPTION:
XS GIS Cut Line= 4
      2070094.11     13483801.27      2069234.54     13483103.16
      2069086.10     13483063.23      2068833.70     13483152.85
#Sta/Elev= 30
  3837.0  490.02  3856.0  489.13  4026.0  486.12  4089.9  486.43  4104.3  485.30
  4224.2  483.81  4302.5  483.74  4572.6  481.02  4665.3  480.36  4679.7  481.17
  4686.1  480.73  4694.1  482.07  4700.5  481.00  4708.4  481.88  4714.9  480.68
  4743.6  480.24  4974.9  480.92  4985.3  479.80  4992.7  476.56  4994.9  476.48
  4995.4  475.68  5000.4  475.68  5000.9  476.48  5006.0  478.92  5016.4  480.57
  5037.9  480.66  5116.7  484.11  5231.9  487.85  5327.4  491.43  5365.9  492.04
#Mann=5,-1,0
  3837.0    0.08       0  3856.0     0.1       0  4994.9    0.07       0
  5000.9     0.1       0  5231.9    0.05       0
Bank Sta=4994.9,5000.9
Exp/Cntr=0.3,0.1

Type RM Length L Ch R = 1,38446,130,130,130
BEGIN DESCRIPTION:
Mapping XS a156eb51
END DESCRIPTION:
XS GIS Cut Line= 5
      2070200.92     13483837.77      2069396.86     13483119.65
      2069364.74     13483043.27      2069266.00     13483001.81
      2068864.98     13483043.47
#Sta/Elev= 30
  3873.0  491.92  3905.3  491.39  4033.6  488.51  4353.5  483.65  4835.0  480.65
  4849.2  479.72  4870.9  480.26  4877.6  479.22  4906.1  480.88  4965.1  479.58
  4970.6  479.26  4977.8  476.94  4985.5  476.53  4986.0  475.73  4991.4  475.73
  4991.9  476.53  4994.3  477.76  4999.7  477.39  5010.3  479.15  5040.7  479.07
  5069.9  480.63  5093.7  479.40  5099.1  480.38  5117.4  477.20  5122.8  480.03
  5131.3  478.99  5162.1  480.86  5242.6  481.19  5450.6  487.86  5544.2  491.19
#Mann=6,-1,0
  3873.0    0.05       0  3905.3    0.08       0  4033.6     0.1       0
  4985.5    0.07       0  4991.9     0.1       0  5450.6    0.05       0
Bank Sta=4985.5,4991.9
Exp/Cntr=0.3,0.1

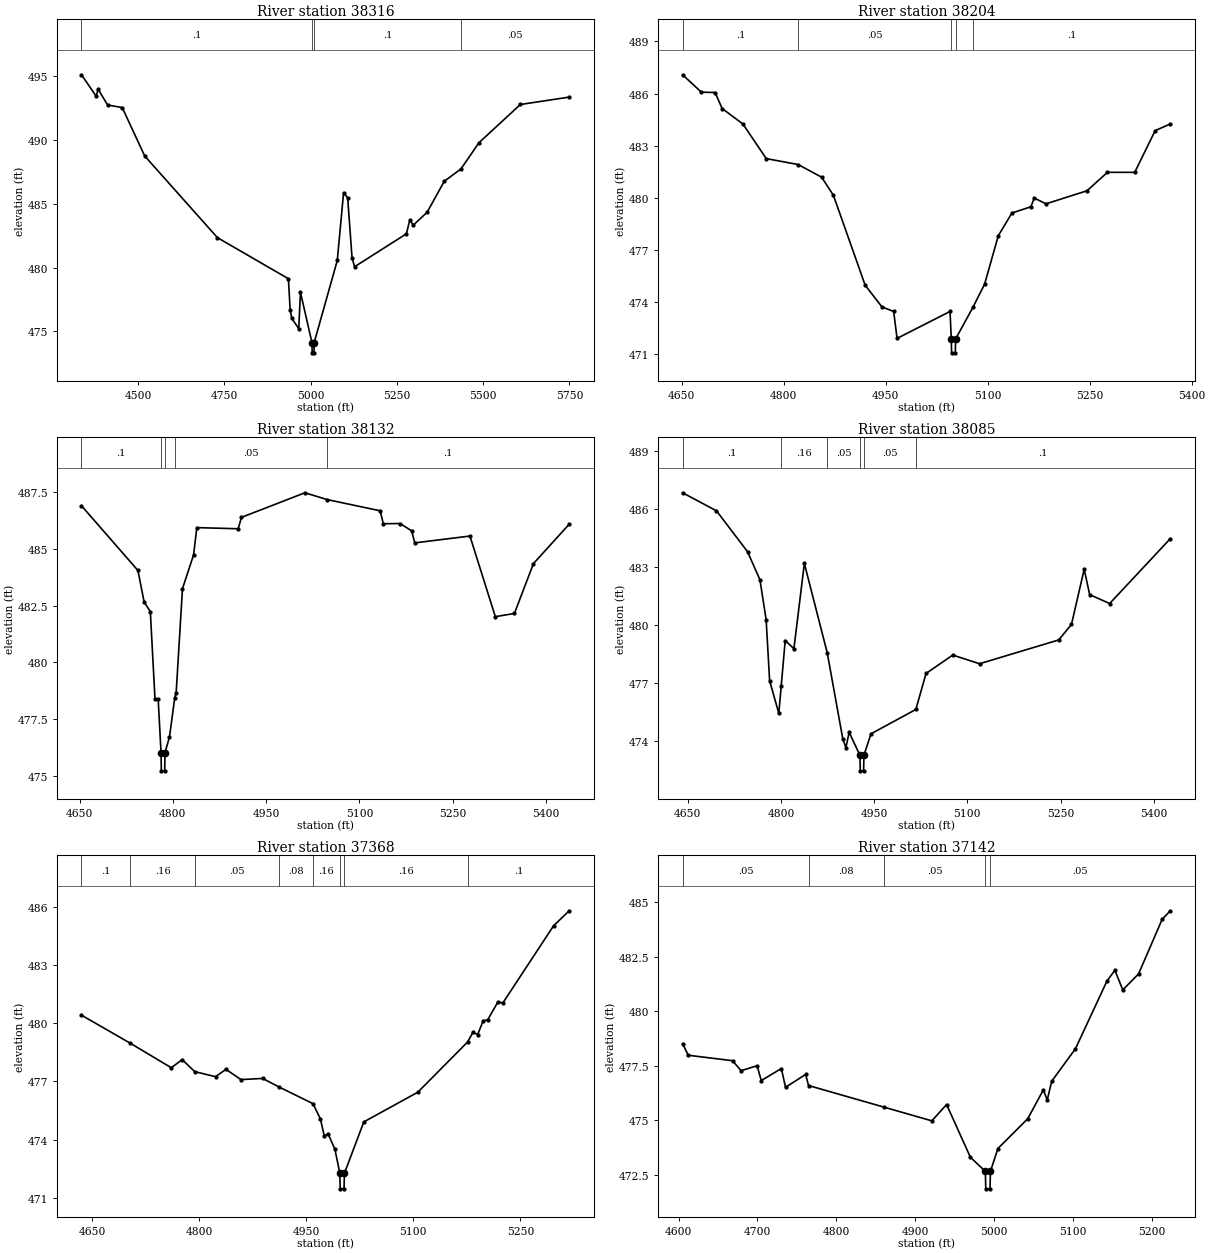
Type RM Length L Ch R = 1,38316,112,112,112
BEGIN DESCRIPTION:
Mapping XS 4a45563a
END DESCRIPTION:
XS GIS Cut Line= 4
      2070049.87     13483056.50      2069442.87     13482968.61
      2069293.56     13482979.03      2068643.61     13483012.22
#Sta/Elev= 30
  4335.6  495.12  4378.4  493.43  4383.5  494.00  4411.3  492.75  4453.7  492.55
  4518.9  488.75  4729.7  482.35  4935.4  479.13  4940.5  476.68  4945.3  476.02
  4965.4  475.22  4970.4  478.06  5003.7  474.12  5004.2  473.32  5009.6  473.32
  5010.1  474.12  5077.1  480.56  5095.4  485.88  5107.2  485.47  5119.9  480.78
  5127.2  480.07  5277.4  482.65  5287.4  483.74  5297.4  483.33  5337.5  484.34
  5387.5  486.78  5435.4  487.73  5487.7  489.79  5607.8  492.79  5749.4  493.37
#Mann=4,-1,0
  4335.6     0.1       0  5003.7    0.07       0  5010.1     0.1       0
  5435.4    0.05       0
Bank Sta=5003.7,5010.1
Exp/Cntr=0.3,0.1

Type RM Length L Ch R = 1,38204,72,72,72
BEGIN DESCRIPTION:
Mapping XS bd8a687e
END DESCRIPTION:
XS GIS Cut Line= 5
      2069762.06     13482853.15      2069623.21     13482826.25
      2069499.08     13482854.90      2069359.32     13482871.39
      2069052.91     13482896.56
#Sta/Elev= 30
  4651.5  487.08  4679.1  486.08  4699.4  486.06  4709.6  485.14  4740.2  484.25
  4774.5  482.26  4821.3  481.92  4855.9  481.19  4873.2  480.15  4919.9  474.98
  4944.6  473.73  4961.8  473.47  4966.8  471.92  5044.7  473.47  5046.5  471.89
  5047.0  471.09  5052.4  471.09  5052.9  471.89  5078.5  473.72  5095.5  475.04
  5115.6  477.82  5135.6  479.13  5163.5  479.49  5168.5  479.99  5185.8  479.66
  5246.0  480.41  5276.1  481.47  5316.2  481.47  5346.3  483.87  5368.5  484.25
#Mann=5,-1,0
  4651.5     0.1       0  4821.3    0.05       0  5046.5   0.033       0
  5052.9    0.05       0  5078.5     0.1       0
Bank Sta=5046.5,5052.9
Exp/Cntr=0.3,0.1

Type RM Length L Ch R = 1,38132,47,47,47
BEGIN DESCRIPTION:
Mapping XS 78ba8e08
END DESCRIPTION:
XS GIS Cut Line= 5
      2069765.60     13482736.84      2069644.91     13482732.50
      2069474.77     13482782.85      2069143.17     13482850.56
      2068998.72     13482880.65
#Sta/Elev= 30
  4653.1  486.88  4743.8  484.04  4753.8  482.66  4763.8  482.23  4771.3  478.39
  4776.4  478.39  4781.0  476.04  4781.5  475.24  4786.9  475.24  4787.4  476.04
  4794.6  476.73  4803.0  478.44  4805.3  478.66  4815.5  483.24  4833.3  484.72
  4838.6  485.92  4905.1  485.87  4910.3  486.37  5012.3  487.45  5048.3  487.15
  5133.3  486.66  5138.4  486.09  5165.4  486.10  5183.9  485.78  5189.0  485.25
  5277.7  485.55  5318.5  482.01  5349.2  482.15  5379.8  484.34  5437.3  486.07
#Mann=5,-1,0
  4653.1     0.1       0  4781.0   0.033       0  4787.4     0.1       0
  4803.0    0.05       0  5048.3     0.1       0
Bank Sta=4781,4787.4
Exp/Cntr=0.3,0.1

Type RM Length L Ch R = 1,38085,717,717,717
BEGIN DESCRIPTION:
Mapping XS d1f02ce9
END DESCRIPTION:
XS GIS Cut Line= 6
      2069779.44     13482704.72      2069638.83     13482701.25
      2069474.77     13482742.05      2069412.27     13482746.39
      2069091.96     13482819.31      2069013.64     13482850.29
#Sta/Elev= 30
  4641.6  486.83  4696.1  485.90  4746.1  483.79  4766.1  482.34  4776.1  480.27
  4781.7  477.12  4796.5  475.44  4800.3  476.83  4806.8  479.20  4820.8  478.78
  4837.6  483.18  4874.4  478.57  4899.4  474.14  4904.5  473.67  4909.7  474.46
  4927.1  473.27  4927.6  472.47  4933.0  472.47  4933.5  473.27  4944.8  474.38
  5017.1  475.64  5033.5  477.50  5076.6  478.45  5119.6  478.00  5247.1  479.23
  5267.6  480.03  5288.1  482.88  5296.9  481.57  5329.1  481.11  5426.7  484.46
#Mann=6,-1,0
  4641.6     0.1       0  4800.3    0.16       0  4874.4    0.05       0
  4927.1   0.033       0  4933.5    0.05       0  5017.1     0.1       0
Bank Sta=4927.1,4933.5
Exp/Cntr=0.3,0.1

Type RM Length L Ch R = 1,37368,226,226,226
BEGIN DESCRIPTION:
Mapping XS 09ba3bde
END DESCRIPTION:
XS GIS Cut Line= 4
      2069590.22     13482586.19      2069394.89     13482500.46
      2069073.71     13482550.37      2068964.12     13482644.77
#Sta/Elev= 30
  4635.3  480.41  4703.8  478.96  4761.1  477.70  4776.3  478.12  4793.9  477.50
  4823.0  477.24  4837.6  477.62  4858.6  477.09  4889.0  477.15  4911.9  476.71
  4959.5  475.85  4969.9  475.06  4975.4  474.17  4980.5  474.31  4990.2  473.50
  4997.1  472.26  4997.6  471.46  5003.0  471.46  5003.5  472.26  5030.7  474.91
  5106.3  476.44  5176.1  479.03  5183.5  479.53  5190.1  479.41  5197.7  480.11
  5204.3  480.18  5218.6  481.10  5225.2  481.03  5296.5  485.02  5318.3  485.79
#Mann=8,-1,0
  4635.3     0.1       0  4703.8    0.16       0  4793.9    0.05       0
  4911.9    0.08       0  4959.5    0.16       0  4997.1    0.07       0
  5003.5    0.16       0  5176.1     0.1       0
Bank Sta=4997.1,5003.5
Exp/Cntr=0.3,0.1

Type RM Length L Ch R = 1,37142,85,85,85
BEGIN DESCRIPTION:
Mapping XS b96f1b0e
END DESCRIPTION:
XS GIS Cut Line= 5
      2069484.73     13482503.18      2069229.05     13482412.22
      2069133.74     13482394.51      2069020.72     13482376.80
      2068884.74     13482376.80
#Sta/Elev= 30
  4605.1  478.52  4612.3  477.99  4668.5  477.74  4679.3  477.28  4699.6  477.51
  4704.9  476.83  4730.4  477.38  4735.7  476.52  4761.2  477.11  4764.9  476.60
  4860.5  475.61  4921.3  474.98  4940.0  475.73  4970.2  473.31  4989.2  472.66
  4989.7  471.86  4995.1  471.86  4995.6  472.66  5005.1  473.71  5043.0  475.08
  5062.7  476.40  5067.7  475.94  5073.4  476.80  5103.5  478.29  5143.5  481.40
  5153.5  481.89  5163.5  480.99  5183.5  481.72  5213.5  484.23  5223.8  484.62
#Mann=5,-1,0
  4605.1    0.05       0  4764.9    0.08       0  4860.5    0.05       0
  4989.2    0.04       0  4995.6    0.05       0
Bank Sta=4989.2,4995.6
Exp/Cntr=0.3,0.1