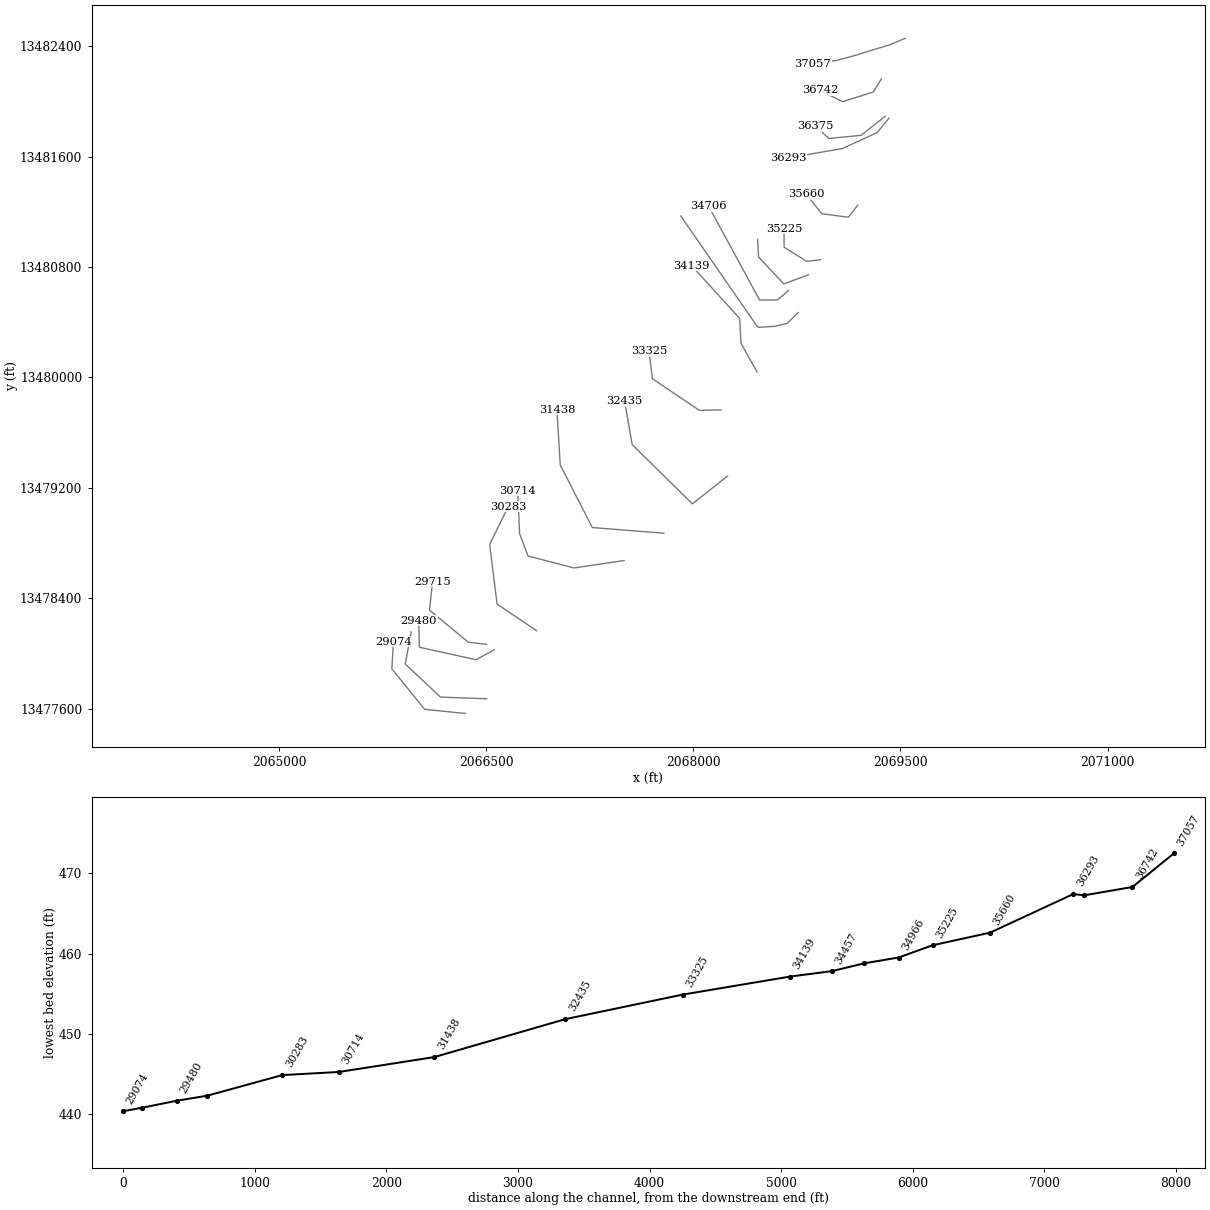
HEC-RAS study DOAK Br.prj: DOAK Br Base Level Engineering

--- DOAK Br.g01 (geometry) --- (continued)

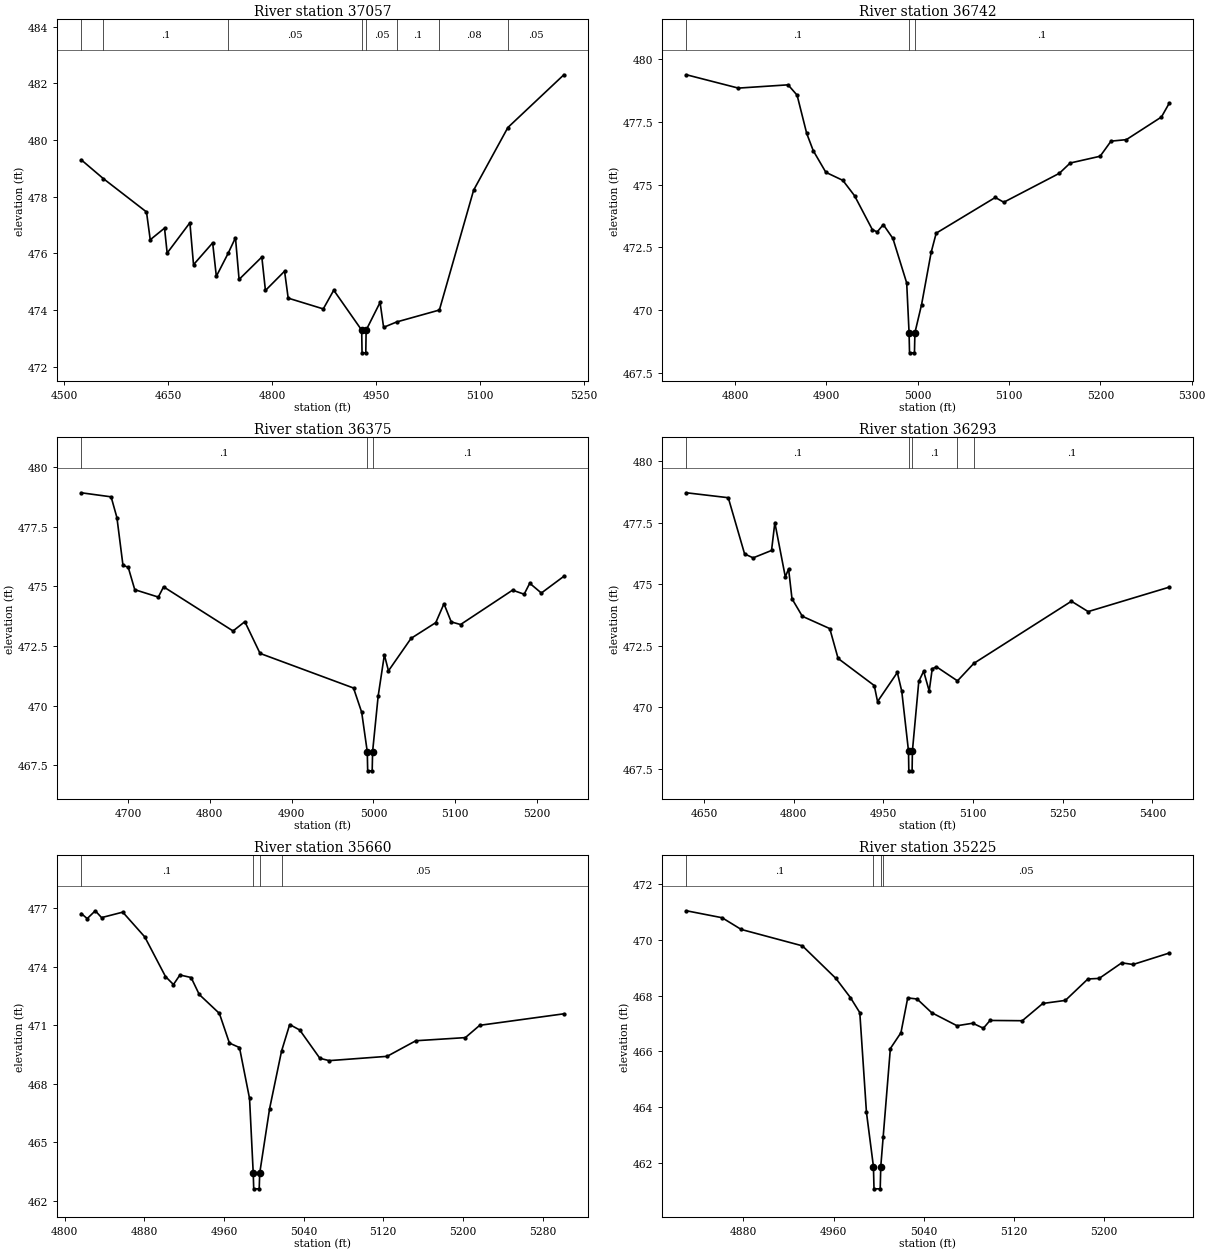
Type RM Length L Ch R = 1,37057,315,315,315
BEGIN DESCRIPTION:
Mapping XS a81ac8e9
END DESCRIPTION:
XS GIS Cut Line= 5
      2069534.59     13482457.59      2069427.19     13482412.02
      2069147.80     13482326.80      2069045.20     13482298.68
      2068866.05     13482274.72
#Sta/Elev= 30
  4525.0  479.30  4556.7  478.64  4619.1  477.46  4624.5  476.48  4645.1  476.89
  4648.9  476.01  4681.7  477.08  4686.9  475.60  4714.5  476.37  4719.8  475.19
  4736.8  476.00  4747.4  476.55  4752.6  475.08  4785.4  475.87  4790.6  474.69
  4818.2  475.37  4823.4  474.42  4874.0  474.04  4889.1  474.70  4929.4  473.29
  4929.9  472.49  4935.3  472.49  4935.8  473.29  4955.9  474.27  4961.0  473.39
  4979.9  473.58  5041.4  474.00  5090.8  478.23  5140.2  480.44  5220.9  482.30
#Mann=8,-1,0
  4525.0    0.05       0  4556.7     0.1       0  4736.8    0.05       0
  4929.4    0.07       0  4935.8    0.05       0  4979.9     0.1       0
  5041.4    0.08       0  5140.2    0.05       0
Bank Sta=4929.4,4935.8
Exp/Cntr=0.3,0.1

Type RM Length L Ch R = 1,36742,367,367,367
BEGIN DESCRIPTION:
Mapping XS 4cf9dd7b
END DESCRIPTION:
XS GIS Cut Line= 4
      2069362.75     13482163.82      2069303.73     13482068.70
      2069081.51     13481998.56      2068917.45     13482080.59
#Sta/Elev= 30
  4746.9  479.37  4803.7  478.84  4858.1  478.97  4868.0  478.56  4878.5  477.04
  4885.7  476.35  4899.5  475.49  4918.1  475.17  4930.9  474.56  4950.4  473.21
  4955.7  473.12  4962.4  473.41  4972.9  472.86  4988.0  471.09  4990.6  469.11
  4991.1  468.31  4996.5  468.31  4997.0  469.11  5004.3  470.23  5014.8  472.31
  5020.3  473.07  5085.0  474.49  5094.3  474.30  5155.1  475.45  5167.0  475.86
  5199.8  476.13  5211.7  476.73  5228.5  476.79  5266.9  477.69  5275.3  478.23
#Mann=3,-1,0
  4746.9     0.1       0  4990.6    0.07       0  4997.0     0.1       0
Bank Sta=4990.6,4997
Exp/Cntr=0.3,0.1

Type RM Length L Ch R = 1,36375,82,82,82
BEGIN DESCRIPTION:
Mapping XS 10dae7a5
END DESCRIPTION:
XS GIS Cut Line= 4
      2069389.15     13481892.31      2069216.23     13481754.81
      2068982.20     13481731.90      2068884.30     13481822.85
#Sta/Elev= 30
  4643.0  478.92  4679.5  478.75  4686.6  477.88  4694.0  475.88  4700.4  475.80
  4708.4  474.86  4737.2  474.55  4743.6  474.98  4828.5  473.13  4842.9  473.52
  4861.5  472.19  4975.7  470.74  4985.7  469.72  4992.5  468.07  4993.0  467.27
  4998.5  467.27  4999.0  468.07  5005.8  470.40  5013.4  472.13  5018.4  471.46
  5046.0  472.82  5076.2  473.48  5086.2  474.27  5095.1  473.51  5106.5  473.40
  5170.0  474.84  5184.2  474.67  5191.0  475.13  5205.2  474.72  5232.7  475.42
#Mann=3,-1,0
  4643.0     0.1       0  4992.5    0.07       0  4999.0     0.1       0
Bank Sta=4992.5,4999
Exp/Cntr=0.3,0.1

Type RM Length L Ch R = 1,36293,633,633,633
BEGIN DESCRIPTION:
Mapping XS f5553aa0
END DESCRIPTION:
XS GIS Cut Line= 4
      2069417.63     13481879.82      2069332.90     13481774.95
      2069080.82     13481658.98      2068691.58     13481591.75
#Sta/Elev= 30
  4620.7  478.71  4690.6  478.51  4717.9  476.23  4732.2  476.07  4763.0  476.37
  4768.5  477.50  4786.0  475.30  4791.5  475.62  4797.2  474.41  4814.5  473.70
  4860.4  473.20  4874.3  471.99  4934.8  470.89  4940.3  470.24  4973.4  471.42
  4980.8  470.66  4992.1  468.23  4992.6  467.43  4998.1  467.43  4998.6  468.23
  5009.3  471.06  5017.4  471.47  5026.7  470.67  5031.8  471.57  5038.9  471.65
  5074.0  471.08  5101.4  471.79  5264.6  474.31  5292.6  473.89  5428.0  474.88
#Mann=5,-1,0
  4620.7     0.1       0  4992.1    0.07       0  4998.6     0.1       0
  5074.0    0.05       0  5101.4     0.1       0
Bank Sta=4992.1,4998.6
Exp/Cntr=0.3,0.1

Type RM Length L Ch R = 1,35660,435,435,435
BEGIN DESCRIPTION:
Mapping XS 602c8471
END DESCRIPTION:
XS GIS Cut Line= 4
      2069191.22     13481247.85      2069123.18     13481161.06
      2068930.82     13481186.76      2068819.48     13481328.51
#Sta/Elev= 30
  4816.7  476.73  4822.7  476.47  4830.8  476.87  4837.1  476.52  4858.4  476.80
  4880.5  475.53  4901.3  473.50  4909.3  473.09  4915.8  473.58  4927.0  473.45
  4935.2  472.58  4955.4  471.61  4965.5  470.09  4975.6  469.86  4985.7  467.25
  4989.4  463.42  4989.9  462.62  4995.4  462.62  4995.9  463.42  5005.8  466.72
  5017.8  469.67  5026.0  471.04  5036.1  470.76  5056.3  469.31  5065.7  469.19
  5123.8  469.41  5152.7  470.21  5202.4  470.37  5216.8  471.00  5301.3  471.59
#Mann=4,-1,0
  4816.7     0.1       0  4989.4    0.07       0  4995.9     0.1       0
  5017.8    0.05       0
Bank Sta=4989.4,4995.9
Exp/Cntr=0.3,0.1

Type RM Length L Ch R = 1,35225,259,259,259
BEGIN DESCRIPTION:
Mapping XS 1351f982
END DESCRIPTION:
XS GIS Cut Line= 4
      2068923.20     13480853.43      2068821.09     13480841.62
      2068658.59     13480943.70      2068657.20     13481077.00
#Sta/Elev= 30
  4829.6  471.05  4861.2  470.80  4878.1  470.38  4932.4  469.79  4962.1  468.62
  4975.0  467.93  4983.3  467.39  4989.2  463.81  4995.4  461.86  4995.9  461.06
  5001.4  461.06  5001.9  461.86  5004.0  462.91  5010.4  466.10  5019.8  466.67
  5025.8  467.92  5034.1  467.88  5047.0  467.39  5069.5  466.92  5083.5  467.01
  5092.9  466.83  5098.8  467.11  5127.4  467.10  5145.6  467.72  5165.6  467.83
  5185.6  468.60  5195.6  468.62  5215.6  469.18  5225.6  469.12  5257.6  469.53
#Mann=4,-1,0
  4829.6     0.1       0  4995.4    0.07       0  5001.9     0.1       0
  5004.0    0.05       0
Bank Sta=4995.4,5001.9
Exp/Cntr=0.3,0.1

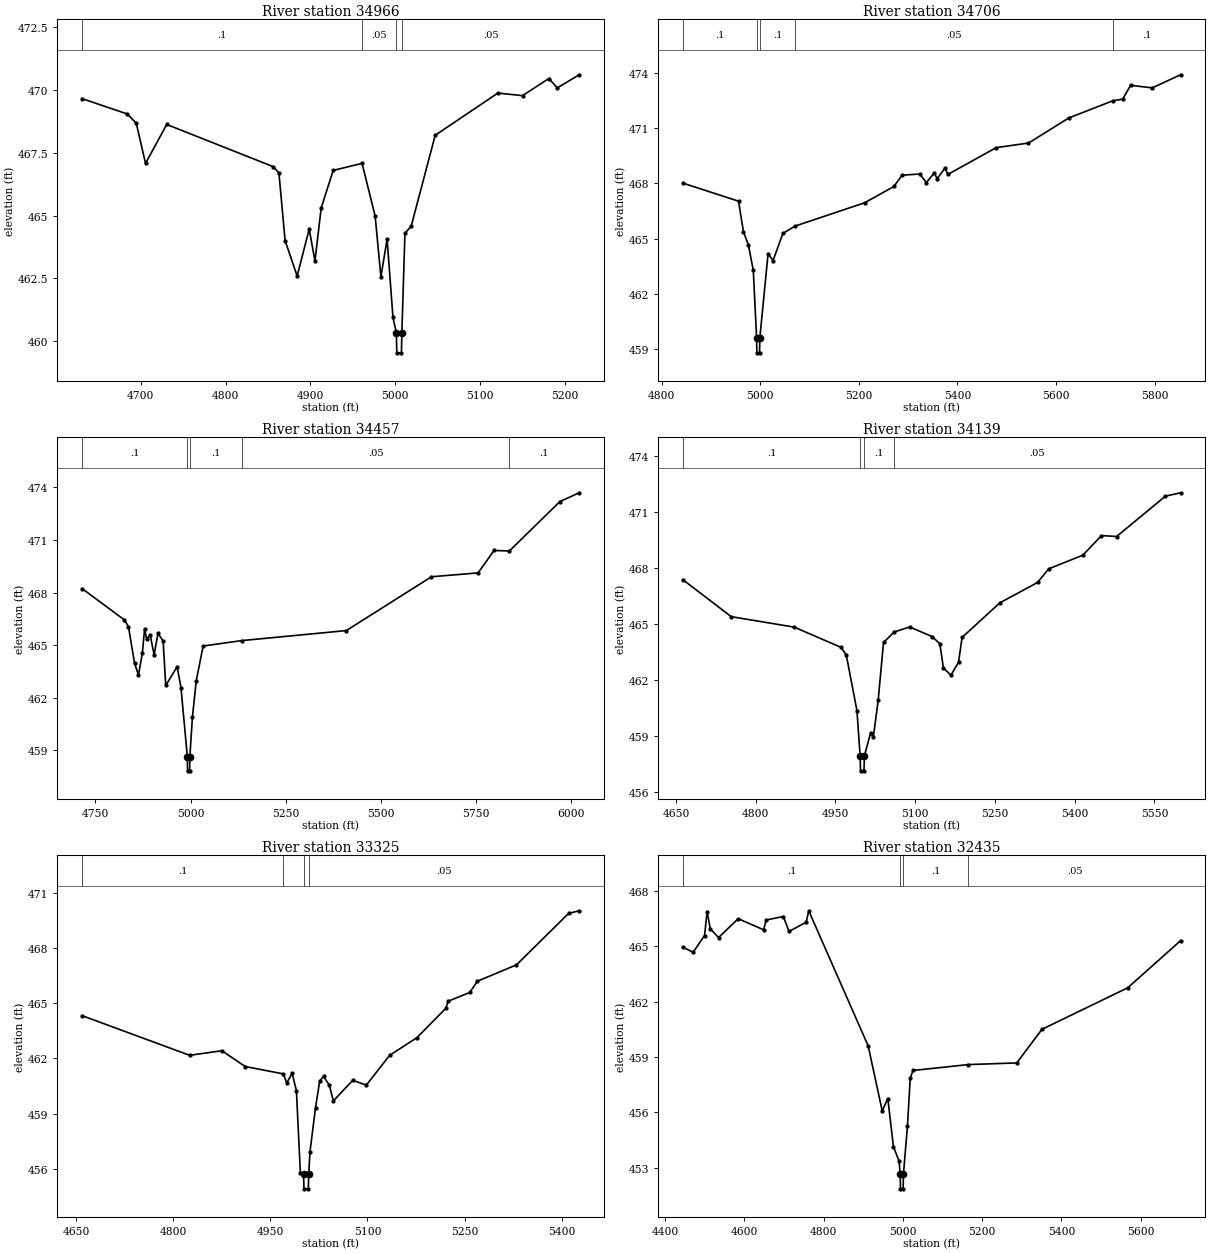
Type RM Length L Ch R = 1,34966,260,260,260
BEGIN DESCRIPTION:
Mapping XS c992bad6
END DESCRIPTION:
XS GIS Cut Line= 4
      2068834.94     13480744.38      2068655.82     13480677.73
      2068473.87     13480872.87      2068466.27     13481000.72
#Sta/Elev= 30
  4630.7  469.66  4684.0  469.05  4694.7  468.68  4705.6  467.08  4730.6  468.63
  4856.0  466.95  4862.8  466.70  4870.1  464.00  4884.3  462.59  4898.5  464.46
  4905.3  463.19  4912.6  465.30  4926.8  466.80  4960.8  467.08  4976.2  464.98
  4983.0  462.56  4990.3  464.06  4997.2  460.94  5001.2  460.33  5001.7  459.53
  5007.2  459.53  5007.7  460.33  5011.3  464.29  5018.7  464.58  5047.0  468.20
  5120.8  469.88  5149.9  469.78  5180.9  470.46  5190.9  470.09  5216.7  470.61
#Mann=4,-1,0
  4630.7     0.1       0  4960.8    0.05       0  5001.2    0.03       0
  5007.7    0.05       0
Bank Sta=5001.2,5007.7
Exp/Cntr=0.3,0.1

Type RM Length L Ch R = 1,34706,249,249,249
BEGIN DESCRIPTION:
Mapping XS a852a9a1
END DESCRIPTION:
XS GIS Cut Line= 4
      2068691.21     13480631.18      2068610.68     13480561.76
      2068480.82     13480561.06      2068112.32     13481240.14
#Sta/Elev= 30
  4843.8  468.00  4955.8  467.03  4965.8  465.38  4975.8  464.66  4985.8  463.28
  4992.5  459.61  4993.0  458.81  4998.5  458.81  4999.0  459.61  5015.8  464.19
  5025.8  463.81  5045.8  465.28  5070.5  465.68  5211.4  466.94  5271.3  467.83
  5287.5  468.44  5323.4  468.50  5336.9  468.04  5353.0  468.56  5358.7  468.25
  5374.9  468.83  5380.6  468.48  5478.5  469.93  5544.1  470.18  5625.9  471.54
  5715.2  472.47  5735.2  472.56  5751.3  473.31  5795.1  473.17  5852.6  473.88
#Mann=5,-1,0
  4843.8     0.1       0  4992.5    0.07       0  4999.0     0.1       0
  5070.5    0.05       0  5715.2     0.1       0
Bank Sta=4992.5,4999
Exp/Cntr=0.3,0.1

Type RM Length L Ch R = 1,34457,318,318,318
BEGIN DESCRIPTION:
Mapping XS c5484221
END DESCRIPTION:
XS GIS Cut Line= 6
      2068760.39     13480470.49      2068680.95     13480392.34
      2068587.20     13480370.21      2068473.92     13480363.70
      2068459.59     13480375.42      2067910.14     13481170.26
#Sta/Elev= 30
  4714.5  468.23  4825.9  466.44  4836.7  466.05  4852.6  463.97  4862.9  463.30
  4873.1  464.54  4879.0  465.93  4884.1  465.36  4893.7  465.58  4904.0  464.44
  4914.2  465.68  4927.7  465.23  4934.5  462.70  4964.5  463.77  4974.5  462.58
  4991.3  458.63  4991.8  457.83  4997.3  457.83  4997.8  458.63  5004.6  460.89
  5014.6  462.96  5032.7  464.95  5134.9  465.26  5408.8  465.83  5632.5  468.90
  5754.9  469.12  5796.8  470.40  5837.1  470.37  5969.8  473.19  6020.5  473.69
#Mann=5,-1,0
  4714.5     0.1       0  4991.3    0.07       0  4997.8     0.1       0
  5134.9    0.05       0  5837.1     0.1       0
Bank Sta=4991.3,4997.8
Exp/Cntr=0.3,0.1

Type RM Length L Ch R = 1,34139,814,814,814
BEGIN DESCRIPTION:
Mapping XS 743eadd3
END DESCRIPTION:
XS GIS Cut Line= 4
      2068462.98     13480039.26      2068345.78     13480247.62
      2068336.67     13480427.31      2067989.51     13480809.50
#Sta/Elev= 30
  4663.9  467.36  4754.1  465.40  4872.6  464.84  4960.4  463.76  4970.4  463.36
  4990.5  460.37  4996.5  457.95  4997.2  457.15  5003.8  457.15  5004.5  457.95
  5016.3  459.19  5021.3  458.94  5030.5  460.94  5040.5  464.02  5060.5  464.58
  5089.7  464.85  5132.2  464.33  5146.4  463.95  5153.2  462.65  5167.4  462.27
  5181.6  462.97  5188.3  464.29  5259.3  466.14  5330.2  467.23  5351.2  467.96
  5415.4  468.69  5450.5  469.74  5478.9  469.69  5570.8  471.85  5599.2  472.03
#Mann=4,-1,0
  4663.9     0.1       0  4996.5    0.07       0  5004.5     0.1       0
  5060.5    0.05       0
Bank Sta=4996.5,5004.5
Exp/Cntr=0.3,0.1

Type RM Length L Ch R = 1,33325,890,890,890
BEGIN DESCRIPTION:
Mapping XS 09dace07
END DESCRIPTION:
XS GIS Cut Line= 4
      2068200.88     13479765.33      2068044.61     13479761.86
      2067704.33     13479991.02      2067680.17     13480191.21
#Sta/Elev= 30
  4658.9  464.33  4825.3  462.17  4875.0  462.42  4911.2  461.56  4970.0  461.16
  4975.3  460.66  4983.5  461.20  4990.2  460.25  4996.3  455.78  5001.2  455.71
  5001.9  454.91  5008.6  454.91  5009.2  455.71  5011.2  456.94  5019.7  459.32
  5026.2  460.78  5032.2  461.02  5041.2  460.54  5047.2  459.69  5077.2  460.81
  5098.2  460.55  5134.2  462.17  5176.4  463.13  5221.1  464.73  5224.5  465.11
  5258.1  465.59  5269.8  466.20  5330.2  467.09  5410.8  469.89  5427.1  470.03
#Mann=4,-1,0
  4658.9     0.1       0  4970.0    0.05       0  5001.2    0.03       0
  5009.2    0.05       0
Bank Sta=5001.2,5009.2
Exp/Cntr=0.3,0.1

Type RM Length L Ch R = 1,32435,997,997,997
BEGIN DESCRIPTION:
Mapping XS cc96b4f0
END DESCRIPTION:
XS GIS Cut Line= 4
      2068248.65     13479286.00      2067994.15     13479084.04
      2067557.95     13479513.73      2067503.69     13479826.26
#Sta/Elev= 30
  4446.1  464.94  4470.9  464.67  4499.7  465.58  4506.1  466.87  4514.2  465.94
  4535.0  465.47  4584.6  466.49  4648.7  465.89  4655.1  466.42  4698.4  466.61
  4712.8  465.80  4756.1  466.30  4762.5  466.92  4912.5  459.60  4947.9  456.08
  4962.0  456.75  4976.2  454.14  4990.3  453.37  4993.3  452.66  4994.0  451.86
  5000.7  451.86  5001.4  452.66  5011.5  455.24  5018.6  457.86  5025.6  458.27
  5165.1  458.59  5287.3  458.68  5350.9  460.50  5567.3  462.75  5700.5  465.30
#Mann=4,-1,0
  4446.1     0.1       0  4993.3    0.07       0  5001.4     0.1       0
  5165.1    0.05       0
Bank Sta=4993.3,5001.4
Exp/Cntr=0.3,0.1

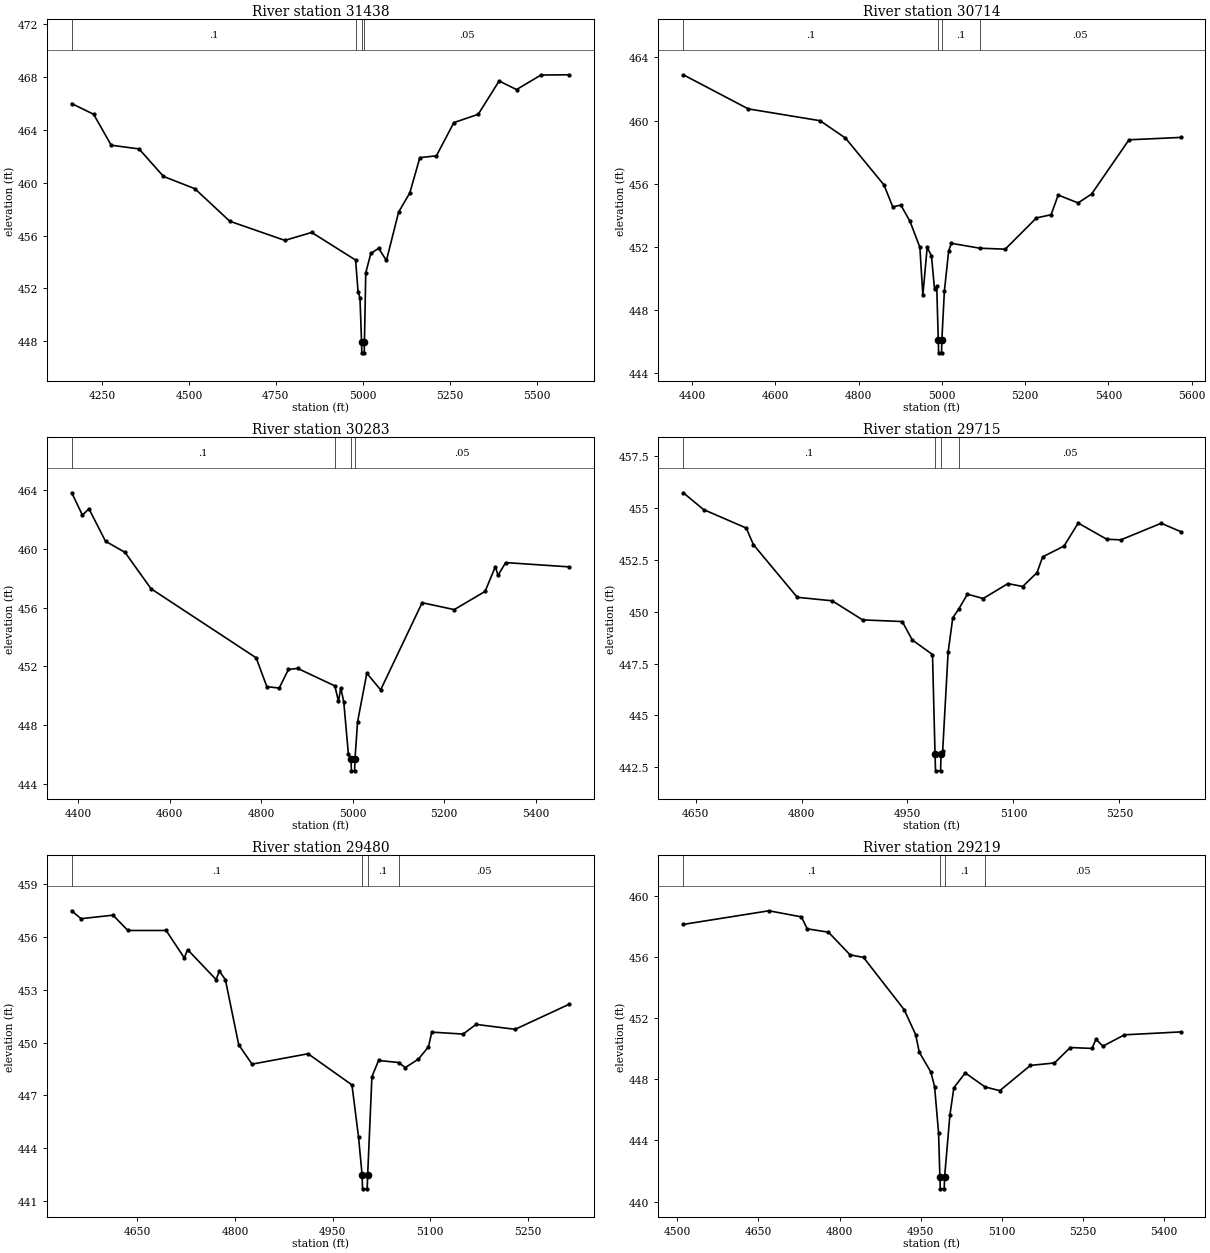
Type RM Length L Ch R = 1,31438,724,724,724
BEGIN DESCRIPTION:
Mapping XS 8405211f
END DESCRIPTION:
XS GIS Cut Line= 4
      2067787.95     13478871.37      2067269.32     13478912.60
      2067037.11     13479366.16      2067013.24     13479765.44
#Sta/Elev= 30
  4163.0  465.99  4226.1  465.18  4276.6  462.84  4356.6  462.56  4426.8  460.48
  4517.1  459.55  4617.4  457.09  4775.8  455.64  4853.1  456.24  4979.3  454.15
  4986.3  451.77  4991.9  451.28  4996.4  447.93  4997.1  447.13  5004.0  447.13
  5004.7  447.93  5008.5  453.18  5023.0  454.65  5045.5  455.04  5067.9  454.12
  5103.0  457.78  5135.3  459.24  5164.0  461.90  5211.7  462.04  5261.8  464.55
  5331.9  465.18  5392.0  467.70  5442.1  467.05  5512.2  468.15  5592.8  468.17
#Mann=4,-1,0
  4163.0     0.1       0  4979.3    0.05       0  4996.4    0.03       0
  5004.7    0.05       0
Bank Sta=4996.4,5004.7
Exp/Cntr=0.3,0.1

Type RM Length L Ch R = 1,30714,431,431,431
BEGIN DESCRIPTION:
Mapping XS 625d73db
END DESCRIPTION:
XS GIS Cut Line= 5
      2067499.91     13478673.53      2067137.11     13478619.72
      2066803.77     13478706.52      2066743.01     13478867.98
      2066729.12     13479178.73
#Sta/Elev= 30
  4378.7  462.90  4534.7  460.74  4707.2  459.99  4768.3  458.89  4860.9  455.92
  4882.0  454.53  4901.4  454.64  4923.3  453.62  4947.1  451.97  4954.3  448.93
  4964.7  451.97  4975.0  451.42  4982.4  449.30  4987.6  449.50  4991.4  446.08
  4992.2  445.28  4999.2  445.28  4999.9  446.08  5006.0  449.18  5016.3  451.74
  5022.9  452.22  5091.4  451.91  5152.2  451.85  5227.2  453.83  5262.4  454.03
  5279.5  455.28  5327.2  454.78  5359.6  455.34  5449.6  458.78  5573.5  458.93
#Mann=4,-1,0
  4378.7     0.1       0  4991.4    0.07       0  4999.9     0.1       0
  5091.4    0.05       0
Bank Sta=4991.4,4999.9
Exp/Cntr=0.3,0.1

Type RM Length L Ch R = 1,30283,568,568,568
BEGIN DESCRIPTION:
Mapping XS a8db9cdc
END DESCRIPTION:
XS GIS Cut Line= 4
      2066866.29     13478164.84      2066579.82     13478357.56
      2066526.00     13478789.86      2066660.72     13479064.49
#Sta/Elev= 30
  4385.7  463.81  4409.1  462.29  4423.4  462.72  4459.6  460.51  4502.1  459.76
  4559.1  457.28  4788.8  452.58  4812.2  450.62  4839.2  450.52  4859.4  451.79
  4879.5  451.86  4960.8  450.67  4968.7  449.62  4973.8  450.53  4980.3  449.58
  4990.4  446.03  4996.2  445.69  4997.0  444.89  5004.0  444.89  5004.8  445.69
  5010.5  448.23  5030.7  451.53  5060.9  450.40  5151.6  456.33  5221.8  455.86
  5289.2  457.10  5311.7  458.79  5317.3  458.19  5334.2  459.06  5472.5  458.77
#Mann=4,-1,0
  4385.7     0.1       0  4960.8    0.05       0  4996.2    0.03       0
  5004.8    0.05       0
Bank Sta=4996.2,5004.8
Exp/Cntr=0.3,0.1

Type RM Length L Ch R = 1,29715,235,235,235
BEGIN DESCRIPTION:
Mapping XS c2557a0f
END DESCRIPTION:
XS GIS Cut Line= 4
      2066503.48     13478065.89      2066371.48     13478081.52
      2066090.23     13478314.16      2066112.80     13478519.01
#Sta/Elev= 30
  4632.6  455.74  4661.3  454.93  4721.7  454.04  4731.8  453.24  4793.9  450.70
  4843.4  450.53  4886.4  449.61  4942.6  449.53  4956.8  448.64  4985.4  447.94
  4989.0  443.13  4989.7  442.33  4996.8  442.33  4997.6  443.13  4999.8  443.29
  5007.5  448.04  5014.1  449.71  5022.3  450.12  5034.9  450.85  5057.1  450.64
  5092.2  451.36  5113.1  451.22  5133.4  451.89  5141.4  452.65  5171.6  453.17
  5191.7  454.28  5232.0  453.50  5252.1  453.47  5309.2  454.27  5336.6  453.87
#Mann=4,-1,0
  4632.6     0.1       0  4989.0    0.07       0  4997.6     0.1       0
  5022.3    0.05       0
Bank Sta=4989,4997.6
Exp/Cntr=0.3,0.1

Type RM Length L Ch R = 1,29480,261,261,261
BEGIN DESCRIPTION:
Mapping XS f2182917
END DESCRIPTION:
XS GIS Cut Line= 4
      2066560.73     13478027.71      2066427.04     13477954.79
      2066017.32     13478045.06      2066012.11     13478237.76
#Sta/Elev= 30
  4549.0  457.50  4563.2  457.05  4612.5  457.25  4635.3  456.38  4694.2  456.38
  4722.1  454.82  4727.2  455.29  4771.0  453.59  4776.1  454.07  4785.3  453.58
  4805.8  449.88  4826.3  448.78  4912.4  449.37  4979.9  447.60  4990.1  444.61
  4995.5  442.49  4996.2  441.69  5003.3  441.69  5004.1  442.49  5010.6  448.06
  5020.8  448.99  5052.0  448.87  5061.8  448.58  5082.2  449.07  5097.5  449.76
  5102.7  450.60  5150.8  450.49  5170.8  451.04  5230.8  450.76  5313.6  452.18
#Mann=4,-1,0
  4549.0     0.1       0  4995.5    0.07       0  5004.1     0.1       0
  5052.0    0.05       0
Bank Sta=4995.5,5004.1
Exp/Cntr=0.3,0.1

Type RM Length L Ch R = 1,29219,145,145,145
BEGIN DESCRIPTION:
Mapping XS 55da26b0
END DESCRIPTION:
XS GIS Cut Line= 4
      2066503.42     13477671.80      2066170.09     13477683.95
      2065914.88     13477923.54      2065958.28     13478156.13
#Sta/Elev= 30
  4510.9  458.12  4669.4  459.01  4729.5  458.61  4740.2  457.83  4779.5  457.61
  4819.5  456.13  4844.4  455.96  4919.7  452.54  4940.8  450.92  4947.6  449.76
  4969.1  448.46  4975.9  447.51  4983.3  444.49  4985.7  441.63  4986.5  440.83
  4993.7  440.83  4994.5  441.63  5004.3  445.67  5011.6  447.44  5032.6  448.41
  5069.4  447.49  5096.6  447.25  5153.2  448.90  5197.8  449.06  5227.0  450.07
  5267.2  450.01  5274.6  450.61  5287.5  450.16  5327.3  450.90  5431.1  451.09
#Mann=4,-1,0
  4510.9     0.1       0  4985.7    0.07       0  4994.5     0.1       0
  5069.4    0.05       0
Bank Sta=4985.7,4994.5
Exp/Cntr=0.3,0.1

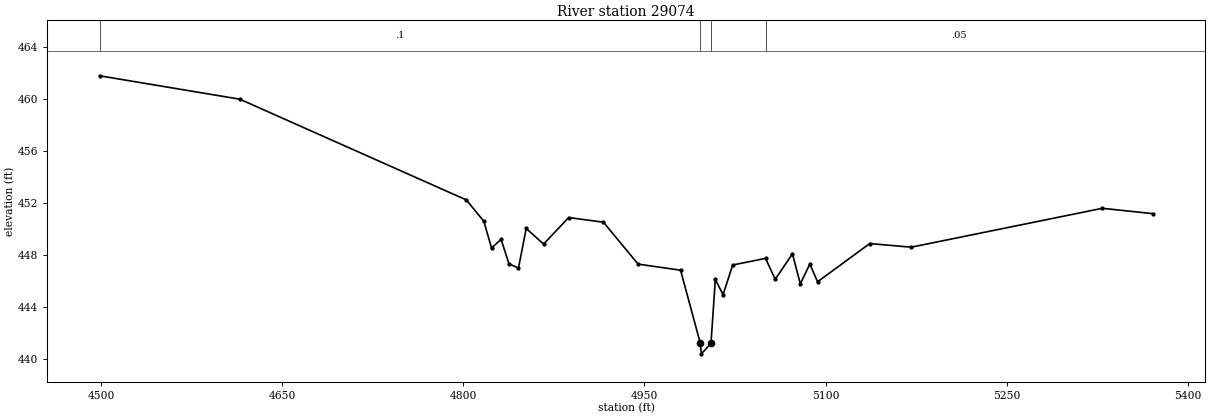
Type RM Length L Ch R = 1,29074,621,621,621
BEGIN DESCRIPTION:
Mapping XS 2a4a214b
END DESCRIPTION:
XS GIS Cut Line= 6
      2066350.65     13477565.90      2066347.18     13477565.90
      2066341.97     13477565.90      2066055.51     13477595.41
      2065817.66     13477888.81      2065829.81     13478086.69
#Sta/Elev= 30
  4498.5  461.77  4614.7  459.97  4802.5  452.22  4816.9  450.58  4823.3  448.53
  4831.2  449.19  4837.7  447.32  4845.6  446.98  4852.0  450.03  4866.4  448.83
  4887.2  450.87  4916.0  450.51  4944.7  447.29  4979.9  446.82  4996.3  441.19
  4997.1  440.39  5005.1  441.19  5008.7  446.11  5015.1  444.94  5023.1  447.22
  5050.3  447.73  5058.3  446.12  5072.6  448.08  5079.1  445.77  5087.0  447.29
  5093.4  445.93  5136.6  448.87  5171.0  448.59  5329.3  451.58  5371.1  451.17
#Mann=4,-1,0
  4498.5     0.1       0  4996.3    0.07       0  5005.1     0.1       0
  5050.3    0.05       0
Bank Sta=4996.3,5005.1
Exp/Cntr=0.3,0.1