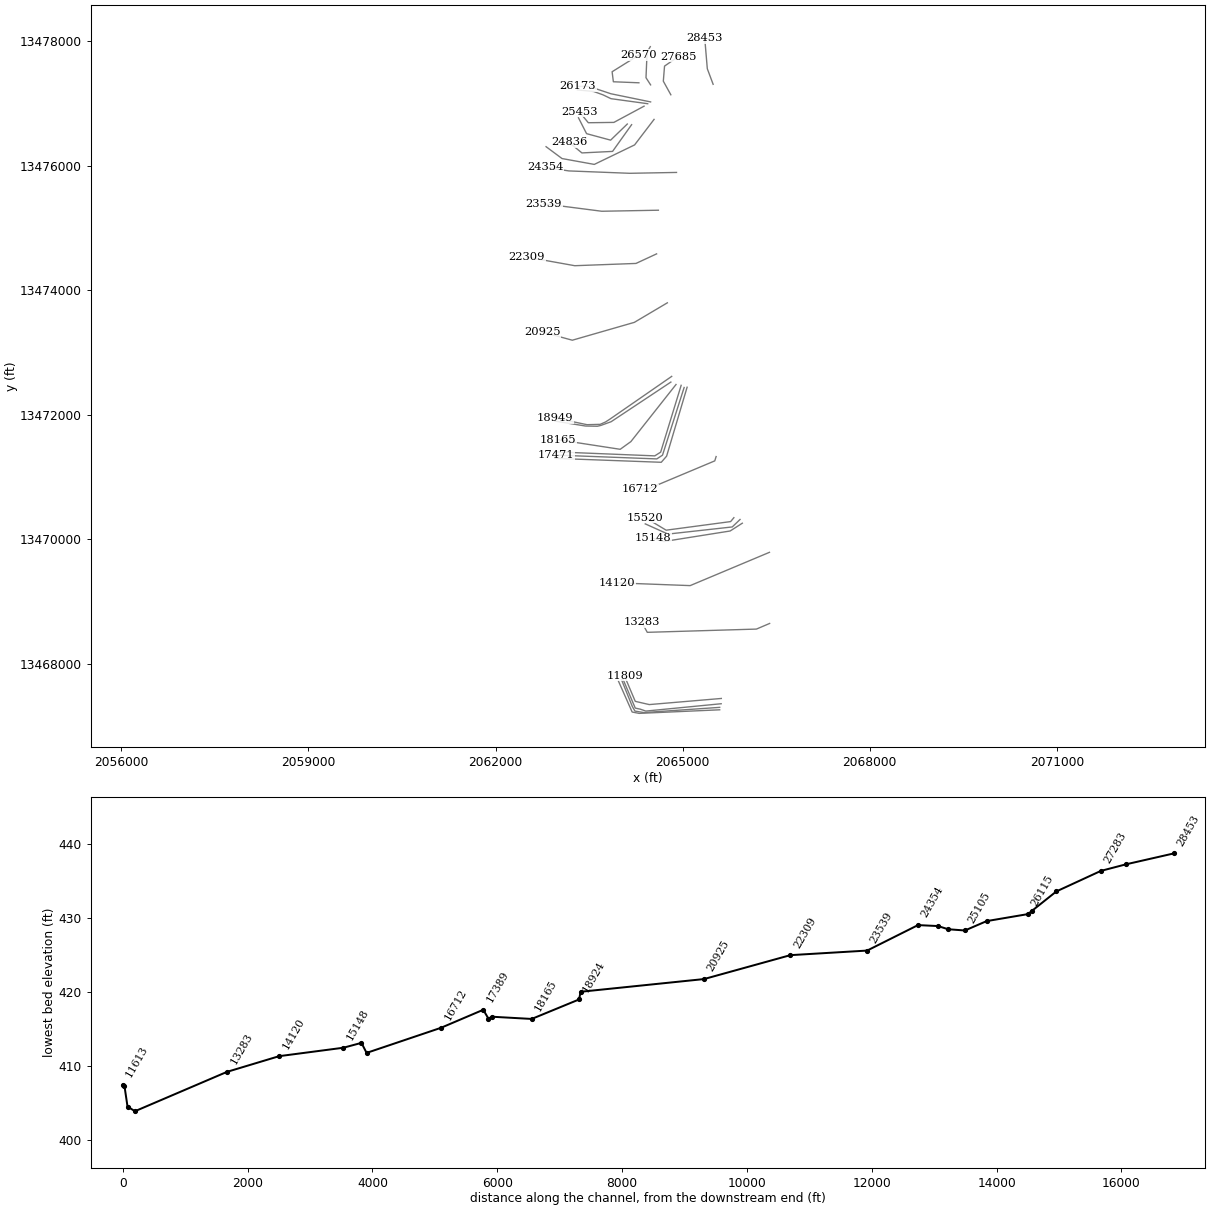
HEC-RAS study DOAK Br.prj: DOAK Br Base Level Engineering

--- DOAK Br.g01 (geometry) --- (continued)

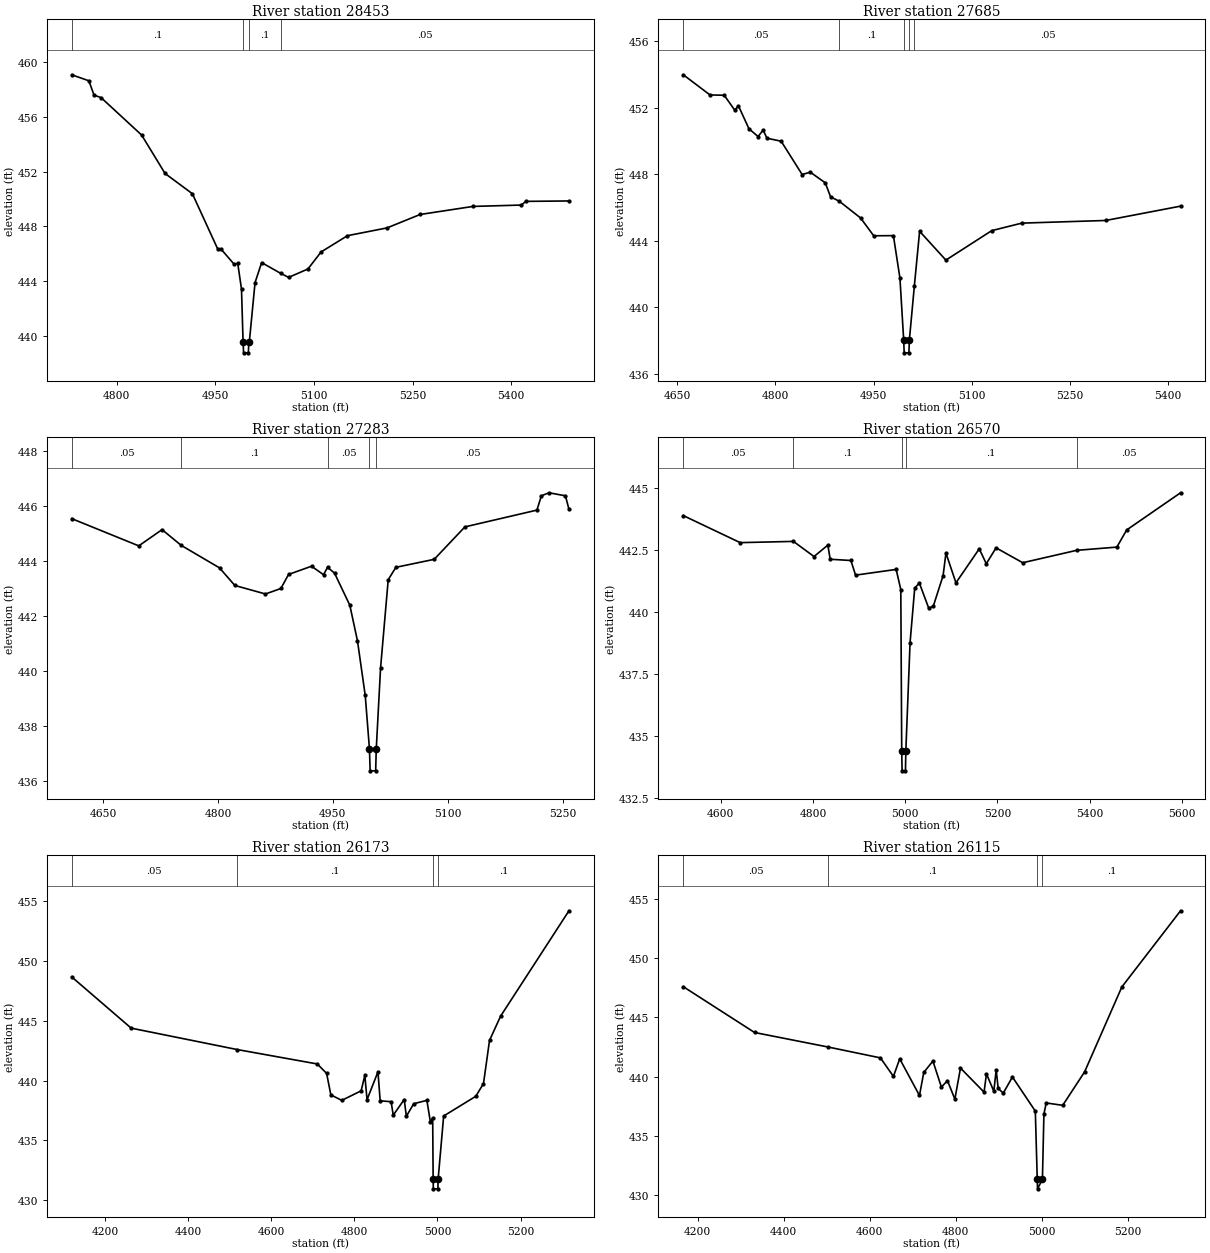
Type RM Length L Ch R = 1,28453,768,768,768
BEGIN DESCRIPTION:
Mapping XS 28cdd790
END DESCRIPTION:
XS GIS Cut Line= 3
      2065488.27     13477303.22      2065394.97     13477552.74
      2065353.78     13478040.51
#Sta/Elev= 30
  4731.8  459.09  4757.9  458.65  4765.7  457.60  4776.4  457.42  4838.1  454.68
  4873.7  451.87  4915.2  450.39  4953.9  446.33  4959.3  446.31  4978.9  445.22
  4984.2  445.29  4989.9  443.41  4992.3  439.55  4993.1  438.75  5000.3  438.75
  5001.1  439.55  5001.8  439.55  5010.5  443.89  5020.5  445.35  5049.3  444.57
  5061.5  444.27  5090.8  444.88  5110.9  446.13  5151.0  447.32  5211.2  447.89
  5261.4  448.87  5341.7  449.46  5415.4  449.56  5422.0  449.83  5487.7  449.86
#Mann=4,-1,0
  4731.8     0.1       0  4992.3    0.07       0  5001.1     0.1       0
  5049.3    0.05       0
Bank Sta=4992.3,5001.1
Exp/Cntr=0.3,0.1

Type RM Length L Ch R = 1,27685,402,402,402
BEGIN DESCRIPTION:
Mapping XS 7d7b0115
END DESCRIPTION:
XS GIS Cut Line= 4
      2064810.08     13477134.89      2064689.62     13477353.01
      2064709.16     13477594.98      2064930.25     13477747.80
#Sta/Elev= 30
  4659.0  453.97  4699.8  452.76  4721.6  452.74  4737.6  451.85  4743.4  452.10
  4759.4  450.73  4773.4  450.26  4781.2  450.65  4786.9  450.16  4808.7  449.98
  4840.8  447.98  4853.3  448.12  4876.2  447.48  4884.3  446.64  4897.8  446.37
  4930.2  445.37  4950.3  444.30  4980.4  444.31  4990.4  441.76  4996.1  438.07
  4996.9  437.27  5004.1  437.27  5004.9  438.07  5012.4  441.26  5020.5  444.57
  5060.7  442.84  5130.9  444.61  5176.8  445.06  5305.2  445.22  5419.7  446.08
#Mann=5,-1,0
  4659.0    0.05       0  4897.8     0.1       0  4996.1    0.07       0
  5004.9     0.1       0  5012.4    0.05       0
Bank Sta=4996.1,5004.9
Exp/Cntr=0.3,0.1

Type RM Length L Ch R = 1,27283,713,713,713
BEGIN DESCRIPTION:
Mapping XS 10099fa4
END DESCRIPTION:
XS GIS Cut Line= 4
      2064485.65     13477293.80      2064411.85     13477408.84
      2064429.21     13477818.99      2064480.64     13477906.85
#Sta/Elev= 30
  4609.2  445.55  4696.7  444.56  4727.1  445.15  4752.0  444.58  4802.1  443.76
  4822.1  443.12  4862.1  442.81  4882.2  443.01  4892.2  443.52  4922.2  443.82
  4937.9  443.51  4943.1  443.78  4952.2  443.57  4972.2  442.40  4982.2  441.10
  4992.3  439.12  4997.8  437.18  4998.7  436.38  5005.9  436.38  5006.7  437.18
  5012.3  440.12  5022.3  443.33  5032.3  443.78  5082.3  444.07  5122.4  445.25
  5216.4  445.86  5222.2  446.38  5232.1  446.49  5253.6  446.38  5258.2  445.89
#Mann=5,-1,0
  4609.2    0.05       0  4752.0     0.1       0  4943.1    0.05       0
  4997.8    0.03       0  5006.7    0.05       0
Bank Sta=4997.8,5006.7
Exp/Cntr=0.3,0.1

Type RM Length L Ch R = 1,26570,397,397,397
BEGIN DESCRIPTION:
Mapping XS 7a290a58
END DESCRIPTION:
XS GIS Cut Line= 4
      2064298.15     13477327.24      2063888.73     13477343.65
      2063868.45     13477504.32      2064298.11     13477772.53
#Sta/Elev= 30
  4518.8  443.89  4642.1  442.80  4757.6  442.85  4802.2  442.24  4832.2  442.70
  4837.3  442.13  4882.2  442.08  4892.3  441.49  4980.3  441.72  4990.4  440.91
  4992.4  434.40  4993.2  433.60  5000.5  433.60  5001.3  434.40  5010.5  438.77
  5020.6  440.97  5030.7  441.17  5050.9  440.16  5060.9  440.24  5082.1  441.47
  5088.3  442.38  5110.0  441.18  5160.5  442.55  5175.8  441.95  5197.0  442.59
  5254.8  441.99  5371.7  442.49  5458.9  442.62  5480.1  443.31  5597.0  444.81
#Mann=5,-1,0
  4518.8    0.05       0  4757.6     0.1       0  4992.4    0.07       0
  5001.3     0.1       0  5371.7    0.05       0
Bank Sta=4992.4,5001.3
Exp/Cntr=0.3,0.1

Type RM Length L Ch R = 1,26173,58,58,58
BEGIN DESCRIPTION:
Mapping XS 3cd9a47e
END DESCRIPTION:
XS GIS Cut Line= 6
      2064485.90     13477020.26      2063848.54     13477151.44
      2063674.93     13477209.60      2063546.46     13477252.13
      2063470.07     13477269.49      2063320.75     13477269.49
#Sta/Elev= 30
  4119.7  448.68  4262.8  444.39  4517.5  442.60  4710.7  441.39  4733.2  440.60
  4743.4  438.80  4769.7  438.34  4816.3  439.14  4825.2  440.43  4830.5  438.40
  4856.8  440.73  4862.1  438.30  4888.4  438.23  4893.6  437.10  4919.9  438.41
  4925.2  437.01  4942.9  438.06  4974.5  438.34  4983.2  436.49  4988.5  436.88
  4989.6  431.73  4990.1  430.93  5001.0  430.93  5001.6  431.73  5014.9  437.03
  5092.2  438.68  5110.8  439.75  5125.3  443.36  5151.9  445.39  5316.5  454.22
#Mann=4,-1,0
  4119.7    0.05       0  4517.5     0.1       0  4989.6    0.07       0
  5001.6     0.1       0
Bank Sta=4989.6,5001.6
Exp/Cntr=0.3,0.1

Type RM Length L Ch R = 1,26115,662,662,662
BEGIN DESCRIPTION:
Mapping XS 2fd3eb8a
END DESCRIPTION:
XS GIS Cut Line= 5
      2064439.03     13476991.62      2063850.28     13477072.44
      2063721.81     13477134.08      2063572.50     13477187.89
      2063312.99     13477213.07
#Sta/Elev= 30
  4166.5  447.57  4332.1  443.71  4502.5  442.49  4624.8  441.57  4655.1  440.01
  4669.7  441.49  4715.6  438.40  4725.7  440.35  4746.9  441.30  4766.6  439.11
  4780.8  439.65  4797.9  438.09  4811.0  440.71  4865.8  438.68  4871.4  440.22
  4888.5  438.76  4894.0  440.56  4898.7  438.99  4910.5  438.60  4931.8  439.96
  4985.0  437.08  4989.5  431.33  4990.1  430.53  5001.5  431.33  5005.0  436.83
  5010.3  437.77  5048.7  437.57  5099.6  440.39  5186.2  447.55  5322.7  453.97
#Mann=4,-1,0
  4166.5    0.05       0  4502.5     0.1       0  4989.5    0.07       0
  5001.5     0.1       0
Bank Sta=4989.5,5001.5
Exp/Cntr=0.3,0.1

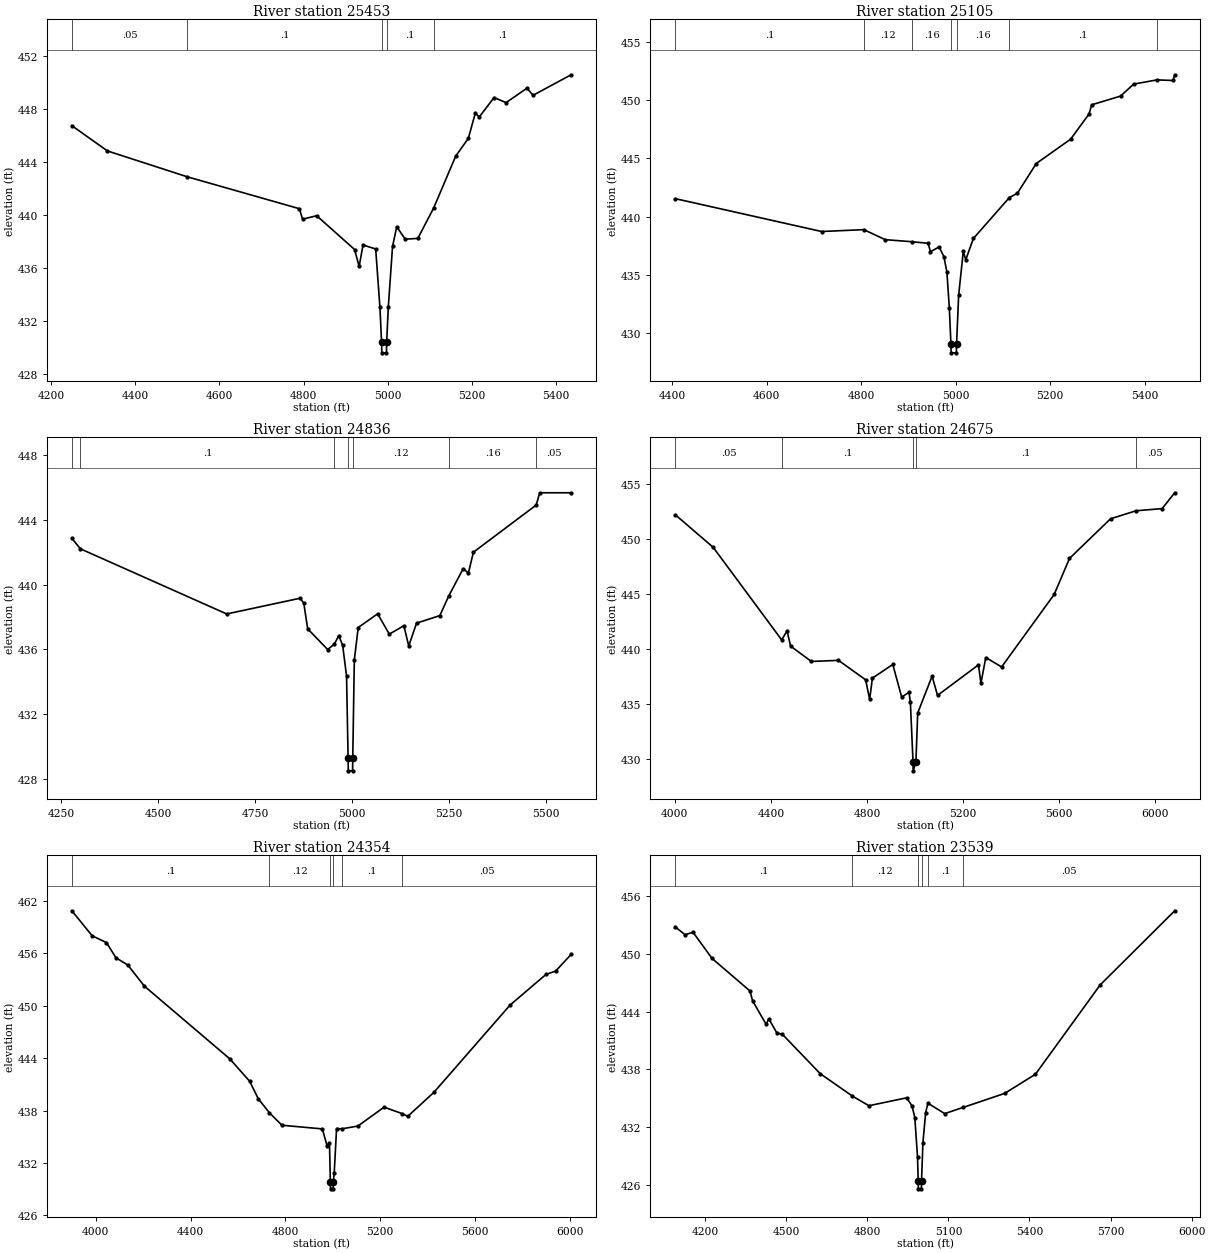
Type RM Length L Ch R = 1,25453,348,348,348
BEGIN DESCRIPTION:
Mapping XS 5a45f9da
END DESCRIPTION:
XS GIS Cut Line= 4
      2064380.87     13476952.04      2063896.50     13476691.63
      2063486.78     13476686.42      2063343.41     13476860.88
#Sta/Elev= 30
  4249.8  446.73  4334.4  444.82  4523.8  442.87  4790.1  440.46  4797.7  439.67
  4831.2  439.93  4921.2  437.38  4932.0  436.10  4941.2  437.72  4971.3  437.42
  4981.3  433.04  4985.3  430.38  4985.8  429.58  4996.8  429.58  4997.3  430.38
  5001.3  433.05  5011.3  437.61  5021.3  439.10  5041.3  438.16  5071.3  438.22
  5108.9  440.51  5161.3  444.43  5191.3  445.77  5207.9  447.69  5217.1  447.38
  5252.3  448.85  5281.0  448.47  5330.5  449.56  5344.9  449.02  5435.3  450.57
#Mann=5,-1,0
  4249.8    0.05       0  4523.8     0.1       0  4985.3    0.07       0
  4997.3     0.1       0  5108.9     0.1       0
Bank Sta=4985.3,4997.3
Exp/Cntr=0.3,0.1

Type RM Length L Ch R = 1,25105,269,269,269
BEGIN DESCRIPTION:
Mapping XS bb66897c
END DESCRIPTION:
XS GIS Cut Line= 4
      2064111.77     13476665.57      2063844.42     13476406.91
      2063459.00     13476511.07      2063329.41     13476765.08
#Sta/Elev= 30
  4406.8  441.55  4716.1  438.73  4805.4  438.89  4850.7  438.03  4908.1  437.85
  4941.4  437.72  4946.5  436.99  4964.7  437.41  4975.0  436.55  4981.2  435.24
  4986.4  432.13  4989.7  429.11  4990.2  428.31  5001.2  428.31  5001.7  429.11
  5006.1  433.26  5015.9  437.03  5021.1  436.30  5037.2  438.13  5113.5  441.65
  5130.4  442.02  5170.3  444.57  5243.0  446.66  5281.9  448.82  5287.5  449.61
  5348.6  450.36  5376.4  451.39  5425.7  451.75  5459.7  451.70  5463.2  452.19
#Mann=7,-1,0
  4406.8     0.1       0  4805.4    0.12       0  4908.1    0.16       0
  4989.7    0.07       0  5001.7    0.16       0  5113.5     0.1       0
  5425.7    0.05       0
Bank Sta=4989.7,5001.7
Exp/Cntr=0.3,0.1

Type RM Length L Ch R = 1,24836,161,161,161
BEGIN DESCRIPTION:
Mapping XS d7955f11
END DESCRIPTION:
XS GIS Cut Line= 4
      2064181.25     13476655.20      2063875.67     13476226.35
      2063384.35     13476202.04      2063177.33     13476371.11
#Sta/Elev= 30
  4278.3  442.87  4300.5  442.22  4677.2  438.19  4865.6  439.16  4875.6  438.87
  4885.7  437.27  4937.1  435.99  4954.3  436.32  4965.8  436.85  4975.8  436.24
  4985.8  434.35  4989.8  429.28  4990.3  428.48  5001.3  428.48  5001.8  429.28
  5005.8  435.34  5015.8  437.35  5065.9  438.20  5095.9  436.94  5133.4  437.46
  5146.0  436.21  5166.0  437.62  5226.1  438.09  5249.1  439.31  5286.1  440.99
  5299.6  440.72  5312.4  442.01  5474.2  444.93  5483.2  445.69  5564.1  445.69
#Mann=7,-1,0
  4278.3    0.05       0  4300.5     0.1       0  4954.3    0.12       0
  4989.8    0.07       0  5001.8    0.12       0  5249.1    0.16       0
  5474.2    0.05       0
Bank Sta=4989.8,5001.8
Exp/Cntr=0.3,0.1

Type RM Length L Ch R = 1,24675,321,321,321
BEGIN DESCRIPTION:
Mapping XS 1e3566a8
END DESCRIPTION:
XS GIS Cut Line= 5
      2064541.34     13476740.04      2064228.82     13476330.30
      2063582.99     13476017.80      2063065.63     13476111.55
      2062809.34     13476302.03
#Sta/Elev= 30
  4002.7  452.22  4160.0  449.26  4445.1  440.83  4467.4  441.67  4481.9  440.27
  4568.4  438.87  4681.4  438.97  4794.3  437.20  4811.1  435.42  4822.5  437.35
  4907.3  438.60  4944.4  435.62  4975.0  436.07  4980.6  435.14  4991.6  429.71
  4992.1  428.91  5003.6  429.71  5011.1  434.18  5070.9  437.53  5093.5  435.78
  5263.9  438.56  5274.1  436.88  5294.4  439.23  5360.2  438.37  5579.0  444.97
  5642.7  448.25  5813.5  451.86  5919.2  452.59  6028.4  452.79  6080.6  454.23
#Mann=5,-1,0
  4002.7    0.05       0  4445.1     0.1       0  4991.6    0.07       0
  5003.6     0.1       0  5919.2    0.05       0
Bank Sta=4991.6,5003.6
Exp/Cntr=0.3,0.1

Type RM Length L Ch R = 1,24354,815,815,815
BEGIN DESCRIPTION:
Mapping XS f5f7b85f
END DESCRIPTION:
XS GIS Cut Line= 4
      2064901.10     13475888.89      2064151.13     13475875.00
      2063175.44     13475913.20      2062800.47     13475968.75
#Sta/Elev= 30
  3899.3  460.87  3985.4  458.00  4045.4  457.23  4085.4  455.49  4135.4  454.66
  4205.5  452.24  4565.5  443.92  4649.4  441.35  4685.6  439.35  4732.7  437.74
  4785.6  436.32  4955.8  435.90  4975.8  433.95  4985.8  434.34  4989.7  429.84
  4990.2  429.04  5001.4  429.04  5001.9  429.84  5005.8  430.82  5015.8  435.94
  5038.5  435.91  5105.9  436.23  5216.0  438.39  5291.4  437.66  5316.0  437.34
  5426.1  440.08  5747.6  450.08  5899.2  453.59  5939.7  453.97  6004.9  455.87
#Mann=6,-1,0
  3899.3     0.1       0  4732.7    0.12       0  4989.7    0.07       0
  5001.9    0.12       0  5038.5     0.1       0  5291.4    0.05       0
Bank Sta=4989.7,5001.9
Exp/Cntr=0.3,0.1

Type RM Length L Ch R = 1,23539,1230,1230,1230
BEGIN DESCRIPTION:
Mapping XS 9b801564
END DESCRIPTION:
XS GIS Cut Line= 3
      2064610.53     13475282.73      2063702.55     13475266.04
      2062771.21     13475386.22
#Sta/Elev= 30
  4090.1  452.77  4125.6  451.98  4155.6  452.22  4225.7  449.51  4365.7  446.14
  4375.7  445.11  4425.7  442.67  4435.7  443.24  4465.7  441.76  4485.7  441.64
  4625.7  437.55  4744.3  435.23  4805.8  434.22  4945.8  435.04  4965.8  434.18
  4975.8  432.97  4985.8  428.91  4988.4  426.39  4988.9  425.59  5000.1  425.59
  5000.6  426.39  5005.8  430.40  5015.9  433.49  5024.2  434.48  5086.5  433.40
  5154.2  434.04  5308.3  435.50  5422.1  437.49  5661.2  446.75  5937.3  454.46
#Mann=6,-1,0
  4090.1     0.1       0  4744.3    0.12       0  4988.4    0.07       0
  5000.6    0.12       0  5024.2     0.1       0  5154.2    0.05       0
Bank Sta=4988.4,5000.6
Exp/Cntr=0.3,0.1

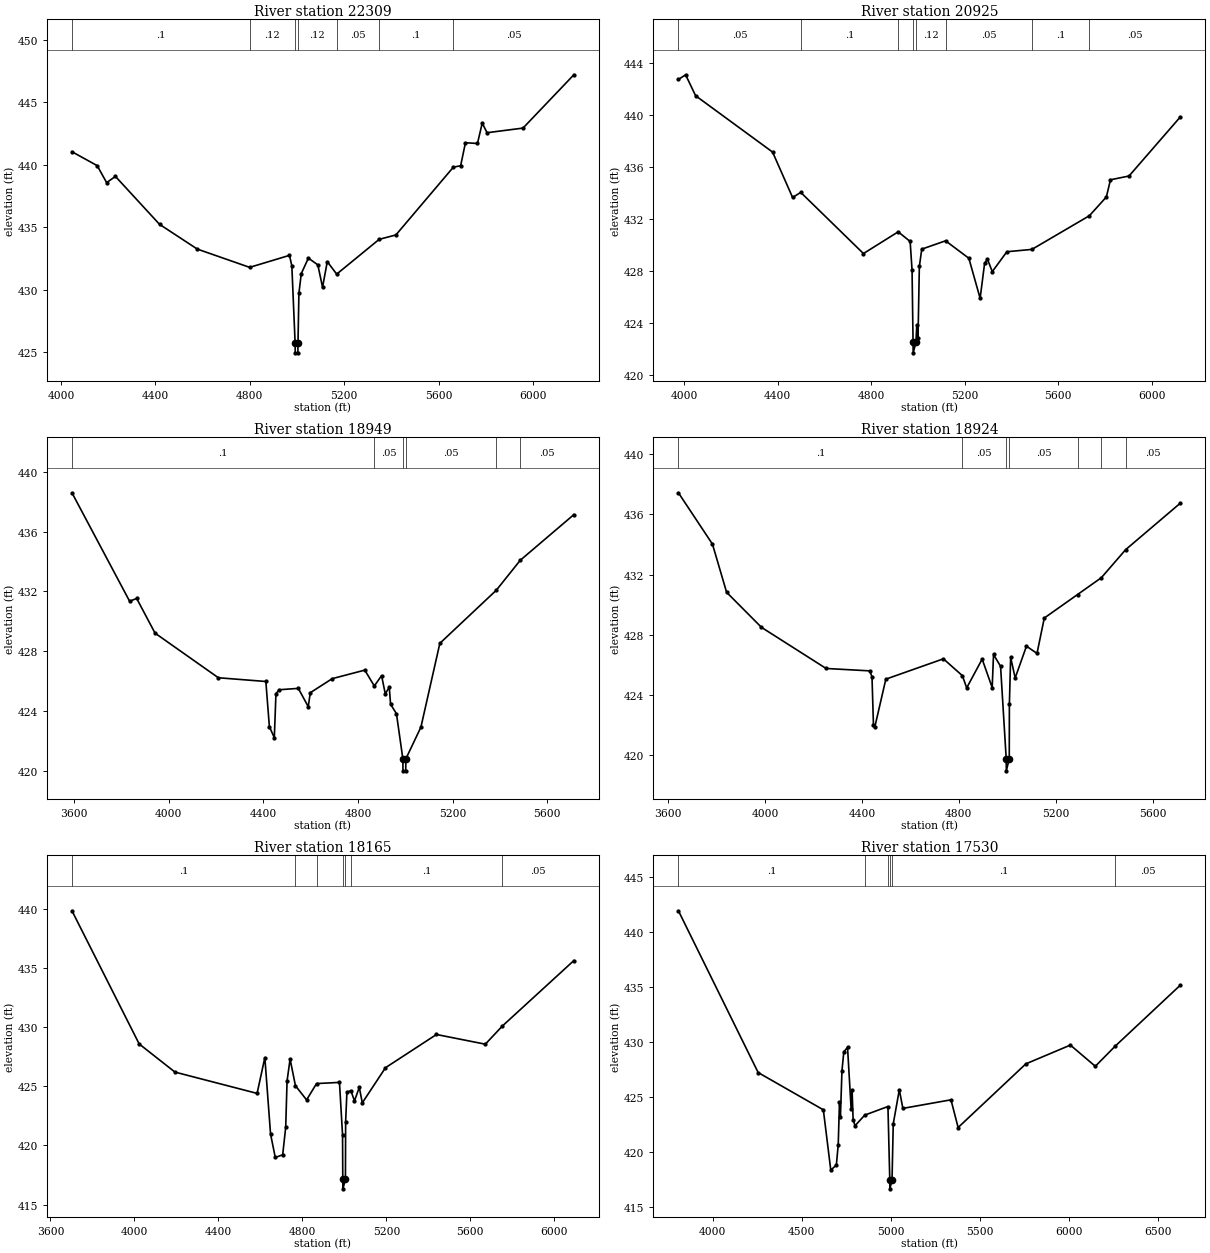
Type RM Length L Ch R = 1,22309,1384,1384,1384
BEGIN DESCRIPTION:
Mapping XS 4a4b06ea
END DESCRIPTION:
XS GIS Cut Line= 4
      2064581.98     13474582.44      2064251.26     13474428.80
      2063269.49     13474392.34      2062503.11     13474530.25
#Sta/Elev= 30
  4046.9  441.04  4153.8  439.93  4193.8  438.57  4231.0  439.07  4417.8  435.24
  4577.9  433.26  4799.6  431.80  4968.2  432.76  4978.2  431.93  4992.1  425.77
  4992.6  424.97  5003.8  424.97  5004.3  425.77  5008.2  429.73  5018.2  431.30
  5048.3  432.54  5088.3  432.00  5108.3  430.21  5128.3  432.26  5168.2  431.26
  5348.2  434.04  5418.9  434.39  5662.5  439.81  5693.2  439.92  5713.5  441.76
  5764.4  441.70  5784.7  443.33  5805.0  442.56  5957.4  442.93  6172.7  447.19
#Mann=7,-1,0
  4046.9     0.1       0  4799.6    0.12       0  4992.1    0.07       0
  5004.3    0.12       0  5168.2    0.05       0  5348.2     0.1       0
  5662.5    0.05       0
Bank Sta=4992.1,5004.3
Exp/Cntr=0.3,0.1

Type RM Length L Ch R = 1,20925,1976,1976,1976
BEGIN DESCRIPTION:
Mapping XS 77159b3e
END DESCRIPTION:
XS GIS Cut Line= 4
      2064754.25     13473797.00      2064225.22     13473483.49
      2063230.43     13473197.03      2062749.54     13473328.12
#Sta/Elev= 30
  3974.6  442.74  4005.4  443.10  4048.2  441.49  4377.7  437.16  4463.4  433.67
  4498.3  434.06  4766.7  429.36  4915.4  431.03  4966.6  430.29  4974.8  428.09
  4979.1  422.53  4979.6  421.73  4991.4  422.53  4995.1  423.89  5000.3  422.88
  5006.0  428.37  5016.4  429.70  5118.2  430.34  5217.9  429.00  5266.2  425.92
  5285.3  428.60  5297.4  428.94  5318.2  427.97  5380.7  429.50  5487.9  429.68
  5734.1  432.27  5806.6  433.71  5824.2  435.03  5903.6  435.32  6123.2  439.86
#Mann=8,-1,0
  3974.6    0.05       0  4498.3     0.1       0  4915.4    0.12       0
  4979.1    0.07       0  4991.4    0.12       0  5118.2    0.05       0
  5487.9     0.1       0  5734.1    0.05       0
Bank Sta=4979.1,4991.4
Exp/Cntr=0.3,0.1

Type RM Length L Ch R = 1,18949,25,25,25
BEGIN DESCRIPTION:
Double Mapping XS 4591be85
END DESCRIPTION:
XS GIS Cut Line= 6
      2064823.73     13472616.47      2063833.21     13471930.56
      2063762.68     13471884.99      2063676.96     13471847.01
      2063466.45     13471841.58      2062949.98     13471950.00
#Sta/Elev= 30
  3591.0  438.59  3834.8  431.34  3864.5  431.53  3942.2  429.21  4209.8  426.23
  4410.4  425.98  4425.3  422.96  4446.2  422.23  4453.1  425.17  4467.2  425.43
  4547.6  425.52  4589.5  424.30  4598.3  425.23  4690.8  426.17  4828.6  426.74
  4868.7  425.68  4899.5  426.37  4915.0  425.16  4932.0  425.59  4937.5  424.46
  4962.3  423.83  4989.4  420.81  4989.9  420.01  5001.5  420.01  5002.0  420.81
  5065.7  422.93  5145.7  428.53  5384.4  432.08  5485.5  434.08  5712.0  437.13
#Mann=6,-1,0
  3591.0     0.1       0  4868.7    0.05       0  4989.4    0.04       0
  5002.0    0.05       0  5384.4    0.08       0  5485.5    0.05       0
Bank Sta=4989.4,5002
Exp/Cntr=0.3,0.1

Type RM Length L Ch R = 1,18924,759,759,759
BEGIN DESCRIPTION:
Double Mapping XS c12221b0
END DESCRIPTION:
XS GIS Cut Line= 6
      2064810.71     13472525.32      2063852.74     13471889.33
      2063687.81     13471829.65      2063632.47     13471816.63
      2063442.58     13471819.88      2062949.99     13471900.00
#Sta/Elev= 30
  3642.4  437.44  3782.9  434.03  3841.3  430.83  3985.3  428.50  4252.0  425.77
  4432.5  425.61  4441.5  425.21  4447.5  422.01  4453.5  421.91  4498.6  425.06
  4736.2  426.41  4814.6  425.29  4832.4  424.48  4896.2  426.39  4937.6  424.50
  4943.1  426.70  4972.2  425.91  4995.5  419.77  4996.0  418.97  5008.1  419.77
  5008.6  423.39  5013.8  426.51  5032.5  425.14  5079.1  427.25  5122.6  426.77
  5152.7  429.12  5289.9  430.68  5388.3  431.80  5488.4  433.66  5714.2  436.75
#Mann=7,-1,0
  3642.4     0.1       0  4814.6    0.05       0  4995.5    0.04       0
  5008.1    0.05       0  5289.9     0.1       0  5388.3    0.08       0
  5488.4    0.05       0
Bank Sta=4995.5,5008.1
Exp/Cntr=0.3,0.1

Type RM Length L Ch R = 1,18165,635,635,635
BEGIN DESCRIPTION:
Double Mapping XS 8ba2682b
END DESCRIPTION:
XS GIS Cut Line= 4
      2064893.17     13472486.27      2064169.58     13471570.32
      2063998.14     13471446.62      2062998.21     13471600.55
#Sta/Elev= 30
  3702.5  439.84  4022.7  428.58  4193.2  426.20  4584.3  424.40  4621.2  427.43
  4648.4  420.96  4670.9  418.98  4706.2  419.21  4720.6  421.55  4727.0  425.45
  4741.4  427.30  4766.9  425.05  4820.0  423.85  4867.4  425.23  4976.6  425.33
  4991.3  420.88  4992.4  417.13  4992.9  416.33  5005.0  417.13  5006.0  422.02
  5012.1  424.50  5030.9  424.63  5048.1  423.77  5071.0  424.91  5085.3  423.60
  5195.7  426.57  5438.5  429.38  5671.2  428.56  5752.7  430.10  6092.9  435.63
#Mann=7,-1,0
  3702.5     0.1       0  4766.9    0.05       0  4867.4    0.16       0
  4992.4    0.07       0  5005.0    0.16       0  5030.9     0.1       0
  5752.7    0.05       0
Bank Sta=4992.4,5005
Exp/Cntr=0.3,0.1

Type RM Length L Ch R = 1,17530,59,59,59
BEGIN DESCRIPTION:
Double Mapping XS 0334a8e9
END DESCRIPTION:
XS GIS Cut Line= 4
      2064975.61     13472473.23      2064647.01     13471401.05
      2064552.61     13471341.37      2062968.00     13471405.43
#Sta/Elev= 30
  3808.1  441.93  4256.0  427.21  4622.1  423.82  4663.9  418.33  4695.3  418.80
  4705.7  420.66  4712.8  424.55  4718.0  423.15  4726.7  427.38  4737.1  429.10
  4758.0  429.50  4778.3  423.87  4783.5  425.64  4789.4  422.93  4799.9  422.37
  4854.9  423.34  4984.9  424.12  4995.3  417.43  4995.8  416.63  5007.9  417.43
  5014.7  422.54  5048.8  425.64  5068.8  423.95  5339.0  424.73  5379.1  422.21
  5759.4  428.00  6009.6  429.71  6149.7  427.78  6259.8  429.59  6627.1  435.16
#Mann=6,-1,0
  3808.1     0.1       0  4854.9    0.05       0  4984.9     0.1       0
  4995.3    0.07       0  5007.9     0.1       0  6259.8    0.05       0
Bank Sta=4995.3,5007.9
Exp/Cntr=0.3,0.1

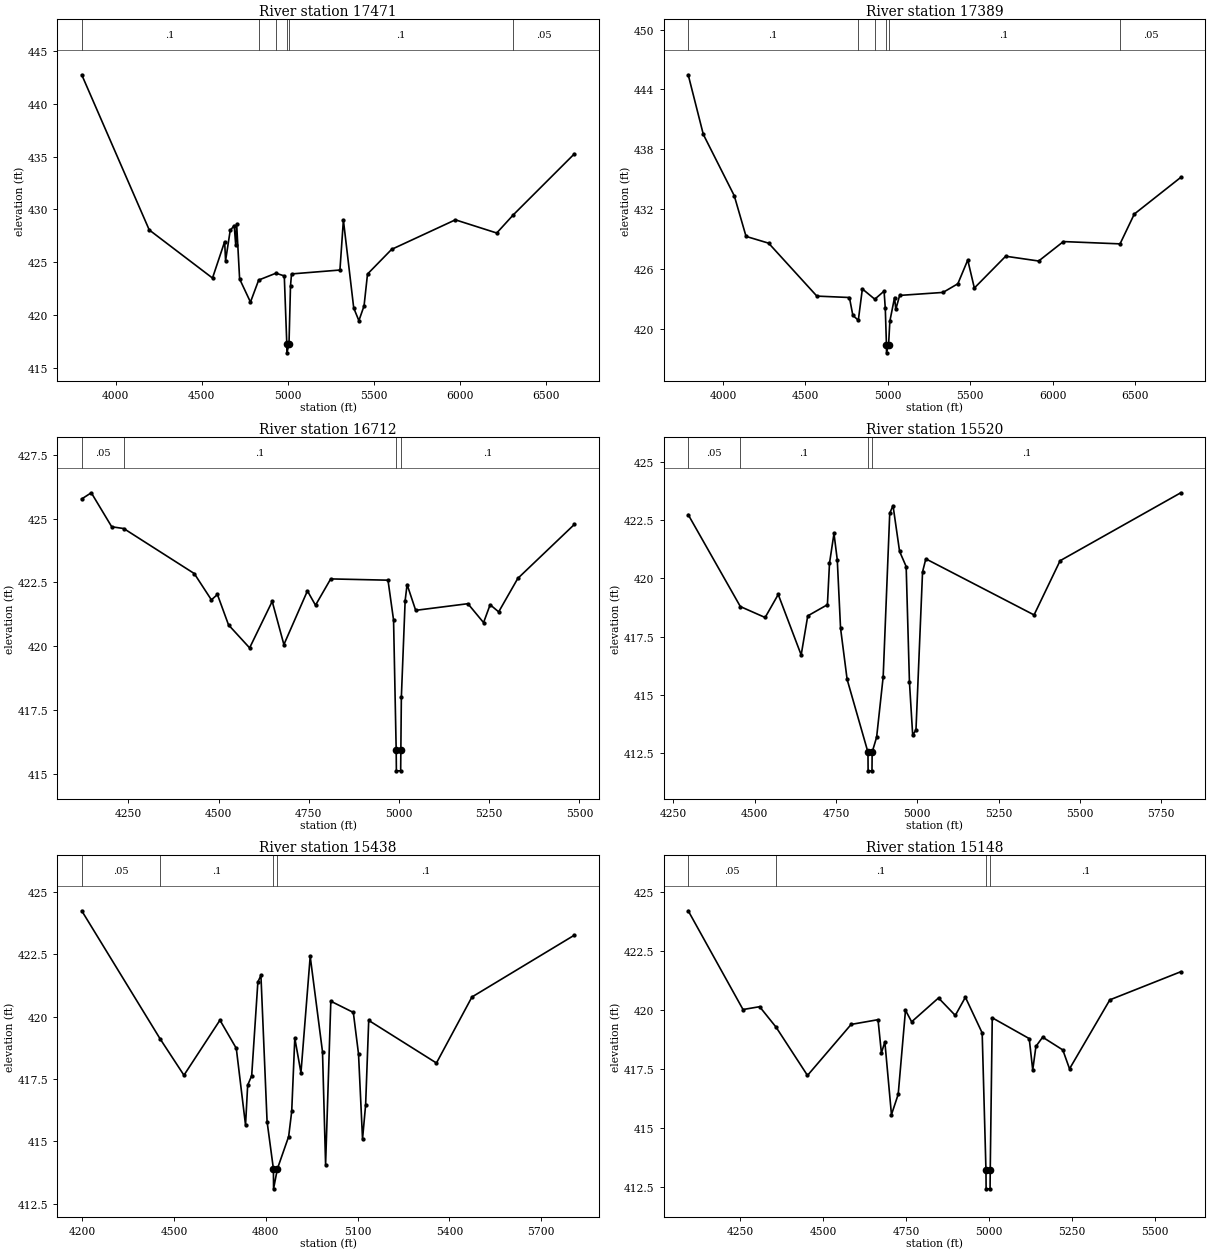
Type RM Length L Ch R = 1,17471,82,82,82
BEGIN DESCRIPTION:
Double Mapping XS a02d2ae7
END DESCRIPTION:
XS GIS Cut Line= 4
      2065023.35     13472438.49      2064676.31     13471352.22
      2064585.16     13471292.54      2062974.72     13471353.43
#Sta/Elev= 30
  3803.8  442.75  4195.9  428.04  4563.3  423.48  4633.9  426.93  4639.2  425.13
  4666.1  427.99  4689.3  428.46  4698.3  426.58  4703.5  428.61  4720.8  423.39
  4783.8  421.20  4831.5  423.29  4931.9  423.94  4980.2  423.68  4994.9  417.19
  4995.4  416.39  5007.5  417.19  5016.3  422.74  5022.3  423.87  5303.4  424.24
  5323.5  428.97  5383.5  420.64  5413.5  419.44  5443.5  420.84  5463.6  423.86
  5603.7  426.20  5973.9  429.00  6214.1  427.75  6310.8  429.48  6664.7  435.25
#Mann=6,-1,0
  3803.8     0.1       0  4831.5    0.05       0  4931.9     0.1       0
  4994.9    0.07       0  5007.5     0.1       0  6310.8    0.05       0
Bank Sta=4994.9,5007.5
Exp/Cntr=0.3,0.1

Type RM Length L Ch R = 1,17389,677,677,677
BEGIN DESCRIPTION:
Double Mapping XS 1f58a865
END DESCRIPTION:
XS GIS Cut Line= 4
      2065071.11     13472442.88      2064742.50     13471337.03
      2064656.78     13471238.29      2062953.05     13471301.34
#Sta/Elev= 30
  3788.7  445.46  3880.4  439.48  4068.2  433.33  4139.8  429.25  4276.8  428.57
  4569.5  423.26  4767.1  423.12  4788.0  421.32  4821.1  420.84  4845.6  423.98
  4921.0  422.95  4977.4  423.76  4984.8  422.02  4991.8  418.37  4992.3  417.57
  5004.7  418.37  5012.5  420.75  5041.0  423.12  5048.6  421.94  5072.0  423.33
  5335.1  423.63  5425.1  424.50  5485.2  426.88  5525.2  424.07  5715.3  427.26
  5915.5  426.78  6065.6  428.73  6409.4  428.50  6495.9  431.49  6778.0  435.17
#Mann=6,-1,0
  3788.7     0.1       0  4821.1    0.05       0  4921.0     0.1       0
  4991.8    0.07       0  5004.7     0.1       0  6409.4    0.05       0
Bank Sta=4991.8,5004.7
Exp/Cntr=0.3,0.1

Type RM Length L Ch R = 1,16712,1192,1192,1192
BEGIN DESCRIPTION:
Mapping XS 5412eec7
END DESCRIPTION:
XS GIS Cut Line= 4
      2065536.26     13471330.28      2065514.57     13471260.86
      2064455.54     13470815.98      2064312.36     13470805.14
#Sta/Elev= 30
  4120.8  425.77  4147.3  426.01  4203.9  424.68  4237.3  424.61  4432.6  422.85
  4480.1  421.82  4496.8  422.03  4527.6  420.84  4586.0  419.94  4648.6  421.76
  4681.0  420.07  4746.2  422.17  4768.6  421.61  4810.7  422.64  4969.5  422.59
  4984.9  421.03  4992.2  415.93  4992.7  415.13  5004.6  415.13  5005.1  415.93
  5006.5  418.01  5017.0  421.79  5022.4  422.42  5046.2  421.41  5190.9  421.67
  5234.3  420.93  5252.5  421.63  5276.2  421.35  5329.2  422.66  5485.8  424.77
#Mann=4,-1,0
  4120.8    0.05       0  4237.3     0.1       0  4992.2    0.07       0
  5005.1     0.1       0
Bank Sta=4992.2,5005.1
Exp/Cntr=0.3,0.1

Type RM Length L Ch R = 1,15520,82,82,82
BEGIN DESCRIPTION:
Mapping XS 810d4dfb
END DESCRIPTION:
XS GIS Cut Line= 4
      2065820.91     13470349.41      2065768.83     13470286.91
      2064734.98     13470148.89      2064399.99     13470350.00
#Sta/Elev= 30
  4295.4  422.74  4455.8  418.79  4532.0  418.32  4572.3  419.31  4642.9  416.71
  4663.1  418.39  4723.6  418.87  4730.0  420.65  4743.8  421.93  4753.9  420.80
  4764.0  417.86  4784.2  415.66  4848.3  412.53  4848.8  411.73  4860.7  411.73
  4861.2  412.53  4875.0  413.18  4895.1  415.77  4915.3  422.80  4925.4  423.13
  4945.6  421.16  4965.8  420.51  4975.9  415.55  4985.9  413.26  4996.0  413.49
  5016.2  420.28  5026.3  420.84  5359.2  418.43  5439.3  420.76  5810.5  423.68
#Mann=4,-1,0
  4295.4    0.05       0  4455.8     0.1       0  4848.3    0.07       0
  4861.2     0.1       0
Bank Sta=4848.3,4861.2
Exp/Cntr=0.3,0.1

Type RM Length L Ch R = 1,15438,290,290,290
BEGIN DESCRIPTION:
Mapping XS c1545bb4
END DESCRIPTION:
XS GIS Cut Line= 4
      2065919.87     13470320.76      2065794.87     13470200.97
      2064763.62     13470086.39      2064399.96     13470250.02
#Sta/Elev= 30
  4198.4  424.25  4454.5  419.11  4532.4  417.65  4650.0  419.86  4703.4  418.73
  4733.6  415.65  4740.6  417.25  4753.7  417.63  4773.9  421.39  4783.9  421.66
  4804.0  415.79  4824.7  413.89  4825.2  413.09  4837.6  413.89  4874.5  415.19
  4884.5  416.20  4894.6  419.14  4914.7  417.75  4944.9  422.42  4985.1  418.59
  4995.2  414.06  5012.3  420.62  5085.8  420.17  5102.8  418.50  5115.9  415.09
  5126.0  416.46  5136.1  419.85  5357.4  418.14  5473.4  420.79  5807.9  423.27
#Mann=4,-1,0
  4198.4    0.05       0  4454.5     0.1       0  4824.7    0.07       0
  4837.6     0.1       0
Bank Sta=4824.7,4837.6
Exp/Cntr=0.3,0.1

Type RM Length L Ch R = 1,15148,1028,1028,1028
BEGIN DESCRIPTION:
Mapping XS e24629b3
END DESCRIPTION:
XS GIS Cut Line= 4
      2065956.35     13470260.88      2065761.02     13470135.87
      2064695.91     13469966.60      2064529.63     13470018.56
#Sta/Elev= 30
  4092.6  424.20  4257.8  420.02  4307.9  420.14  4357.6  419.27  4452.1  417.23
  4583.7  419.39  4664.7  419.59  4674.9  418.18  4685.3  418.65  4705.2  415.57
  4725.5  416.43  4747.5  419.99  4766.0  419.50  4847.0  420.51  4897.6  419.77
  4928.0  420.54  4978.6  419.03  4990.0  413.23  4990.5  412.43  5002.4  412.43
  5002.9  413.23  5009.0  419.67  5120.4  418.79  5131.0  417.46  5140.6  418.46
  5160.9  418.85  5221.6  418.31  5241.9  417.51  5363.4  420.43  5577.2  421.62
#Mann=4,-1,0
  4092.6    0.05       0  4357.6     0.1       0  4990.0    0.07       0
  5002.9     0.1       0
Bank Sta=4990,5002.9
Exp/Cntr=0.3,0.1

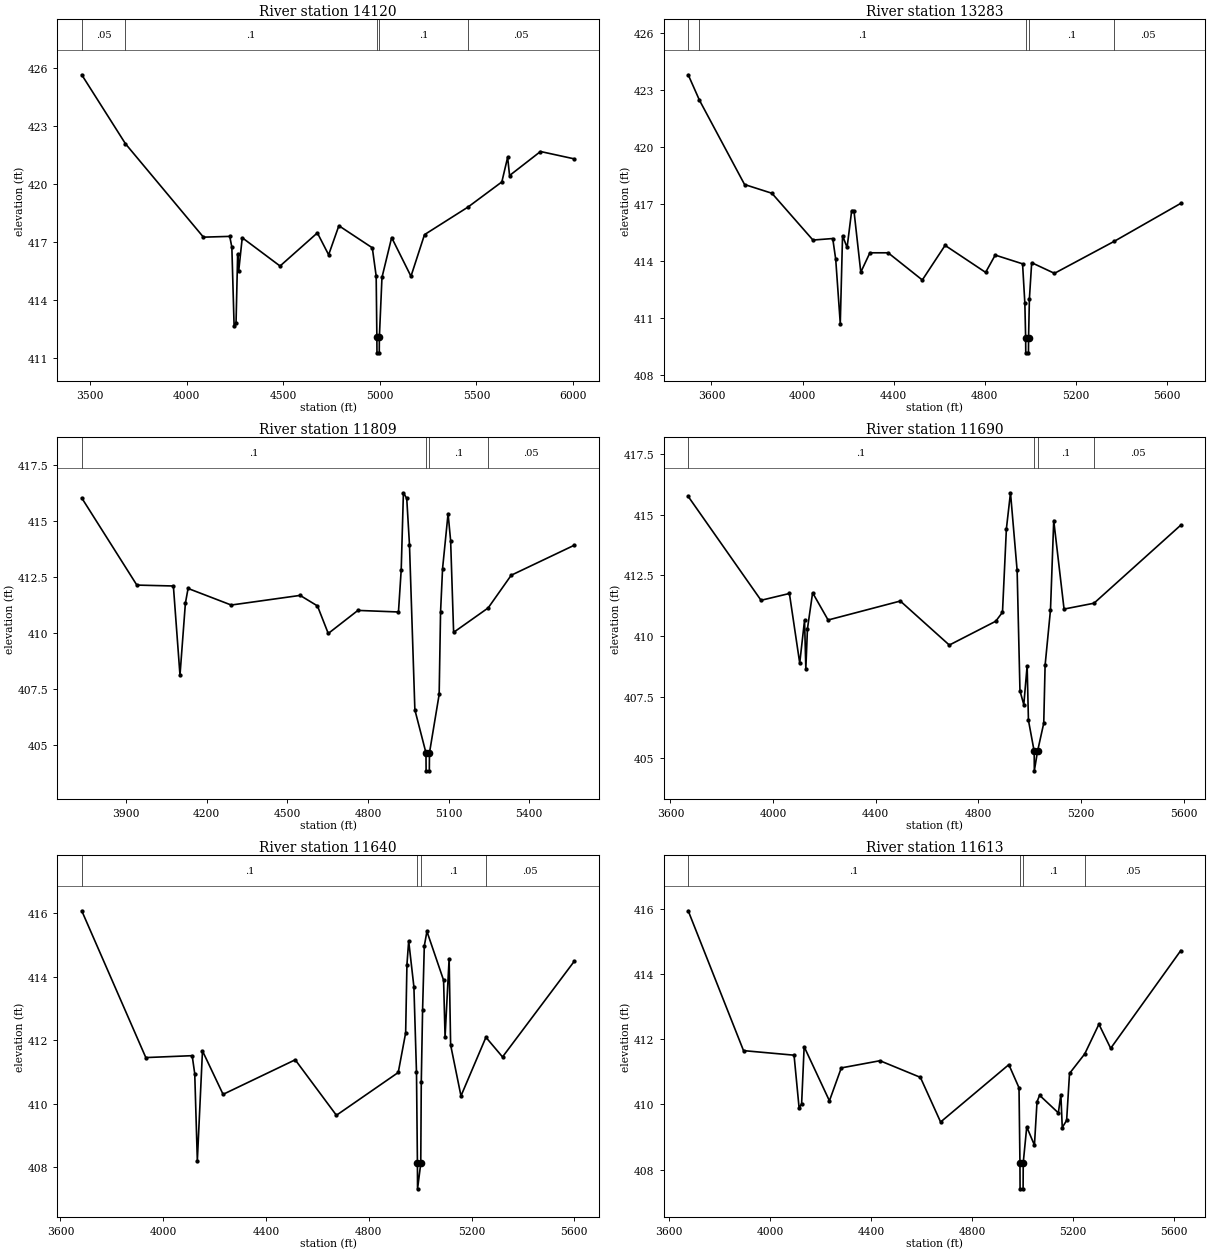
Type RM Length L Ch R = 1,14120,837,837,837
BEGIN DESCRIPTION:
Mapping XS 17549d13
END DESCRIPTION:
XS GIS Cut Line= 3
      2066391.43     13469793.78      2065119.93     13469259.57
      2063950.03     13469303.72
#Sta/Elev= 30
  3456.6  425.64  3683.0  422.08  4086.6  417.26  4222.8  417.30  4233.7  416.74
  4245.4  412.66  4255.4  412.85  4263.7  416.37  4269.2  415.52  4287.5  417.23
  4483.2  415.77  4676.4  417.48  4734.7  416.35  4787.7  417.85  4960.8  416.71
  4980.8  415.25  4984.4  412.09  4984.9  411.29  4996.8  411.29  4997.3  412.09
  5010.8  415.18  5060.9  417.24  5160.9  415.24  5231.0  417.39  5455.7  418.81
  5631.3  420.11  5661.3  421.38  5671.3  420.44  5831.4  421.68  6006.5  421.30
#Mann=5,-1,0
  3456.6    0.05       0  3683.0     0.1       0  4984.4    0.07       0
  4997.3     0.1       0  5455.7    0.05       0
Bank Sta=4984.4,4997.3
Exp/Cntr=0.3,0.1

Type RM Length L Ch R = 1,13283,1474,1474,1474
BEGIN DESCRIPTION:
Mapping XS 4a640f26
END DESCRIPTION:
XS GIS Cut Line= 4
      2066394.10     13468652.35      2066182.31     13468562.08
      2064432.31     13468510.00      2064345.50     13468669.74
#Sta/Elev= 30
  3497.7  423.78  3547.2  422.44  3745.2  418.01  3865.3  417.55  4045.4  415.09
  4132.3  415.17  4145.4  414.08  4165.4  410.70  4175.4  415.32  4195.4  414.70
  4215.5  416.64  4225.5  416.63  4255.5  413.40  4295.5  414.42  4375.5  414.42
  4525.6  412.99  4625.6  414.81  4803.6  413.39  4845.7  414.30  4965.8  413.84
  4975.8  411.78  4979.3  409.96  4979.8  409.16  4991.7  409.16  4992.2  409.96
  4995.8  412.00  5005.8  413.90  5105.8  413.34  5369.3  415.03  5660.5  417.02
#Mann=5,-1,0
  3497.7    0.05       0  3547.2     0.1       0  4979.3    0.07       0
  4992.2     0.1       0  5369.3    0.05       0
Bank Sta=4979.3,4992.2
Exp/Cntr=0.3,0.1

Type RM Length L Ch R = 1,11809,119,119,119
BEGIN DESCRIPTION:
double Mapping XS 27c4fb58
END DESCRIPTION:
XS GIS Cut Line= 4
      2065619.48     13467448.96      2064464.19     13467350.70
      2064239.58     13467402.78      2064066.19     13467811.38
#Sta/Elev= 30
  3734.4  416.01  3939.6  412.12  4075.6  412.08  4100.2  408.10  4120.3  411.31
  4130.3  411.97  4290.9  411.23  4547.5  411.66  4612.0  411.19  4652.2  409.96
  4762.6  410.99  4913.6  410.92  4923.8  412.80  4932.0  416.24  4944.4  415.99
  4954.6  413.92  4974.7  406.55  5016.0  404.63  5016.5  403.83  5028.5  403.83
  5029.0  404.63  5065.1  407.24  5070.3  410.92  5077.8  412.86  5098.3  415.31
  5107.8  414.10  5118.9  410.01  5247.5  411.10  5333.4  412.56  5568.3  413.90
#Mann=4,-1,0
  3734.4     0.1       0  5016.0    0.07       0  5029.0     0.1       0
  5247.5    0.05       0
Bank Sta=5016,5029
Exp/Cntr=0.3,0.1

Type RM Length L Ch R = 1,11690,50,50,50
BEGIN DESCRIPTION:
double Mapping XS 646bf249
END DESCRIPTION:
XS GIS Cut Line= 5
      2065617.31     13467364.32      2064408.85     13467246.53
      2064320.96     13467276.91      2064239.58     13467294.28
      2064033.40     13467780.68
#Sta/Elev= 30
  3669.4  415.75  3953.1  411.48  4063.6  411.76  4103.8  408.90  4122.6  410.66
  4127.6  408.67  4133.9  410.31  4154.0  411.79  4214.3  410.67  4495.6  411.45
  4686.5  409.64  4867.4  410.62  4893.6  410.99  4908.8  414.42  4924.8  415.90
  4950.6  412.71  4961.7  407.76  4976.6  407.19  4989.6  408.79  4994.7  406.55
  5017.1  405.27  5017.6  404.47  5030.1  405.27  5054.3  406.43  5059.6  408.81
  5080.6  411.09  5093.2  414.76  5133.4  411.12  5250.0  411.36  5588.1  414.57
#Mann=4,-1,0
  3669.4     0.1       0  5017.1    0.07       0  5030.1     0.1       0
  5250.0    0.05       0
Bank Sta=5017.1,5030.1
Exp/Cntr=0.3,0.1

Type RM Length L Ch R = 1,11640,27,27,27
BEGIN DESCRIPTION:
double Mapping XS ba6be1b6
END DESCRIPTION:
XS GIS Cut Line= 5
      2065593.81     13467306.05      2064377.38     13467222.66
      2064234.15     13467246.53      2064192.92     13467319.23
      2064017.45     13467754.10
#Sta/Elev= 30
  3682.8  416.08  3932.2  411.45  4112.6  411.51  4122.6  410.94  4132.7  408.20
  4152.7  411.66  4232.9  410.29  4513.6  411.38  4673.9  409.63  4914.6  410.98
  4943.4  412.23  4948.4  414.38  4955.2  415.13  4975.5  413.68  4985.6  410.98
  4989.2  408.11  4989.7  407.31  5002.2  408.11  5004.2  410.67  5009.3  412.95
  5016.0  414.97  5026.2  415.43  5091.0  413.89  5096.8  412.10  5112.6  414.57
  5118.4  411.85  5158.7  410.24  5255.8  412.09  5320.4  411.47  5599.8  414.49
#Mann=4,-1,0
  3682.8     0.1       0  4989.2    0.07       0  5002.2     0.1       0
  5255.8    0.05       0
Bank Sta=4989.2,5002.2
Exp/Cntr=0.3,0.1

Type RM Length L Ch R = 1,11613,471,471,471
BEGIN DESCRIPTION:
double Mapping XS 5295d769
END DESCRIPTION:
XS GIS Cut Line= 4
      2065593.84     13467266.99      2064302.51     13467209.64
      2064189.66     13467231.34      2063969.65     13467728.51
#Sta/Elev= 30
  3675.1  415.94  3894.2  411.65  4094.4  411.51  4114.4  409.89  4124.4  410.02
  4134.4  411.77  4234.5  410.11  4281.5  411.12  4434.7  411.34  4594.8  410.83
  4674.9  409.46  4945.2  411.22  4985.5  410.51  4989.2  408.21  4989.7  407.41
  5001.7  407.41  5002.2  408.21  5016.1  409.31  5046.6  408.75  5056.8  410.08
  5067.0  410.28  5141.3  409.74  5151.3  410.30  5156.8  409.29  5174.1  409.51
  5185.6  410.95  5245.9  411.55  5302.0  412.46  5348.6  411.72  5626.3  414.72
#Mann=4,-1,0
  3675.1     0.1       0  4989.2    0.07       0  5002.2     0.1       0
  5245.9    0.05       0
Bank Sta=4989.2,5002.2
Exp/Cntr=0.3,0.1