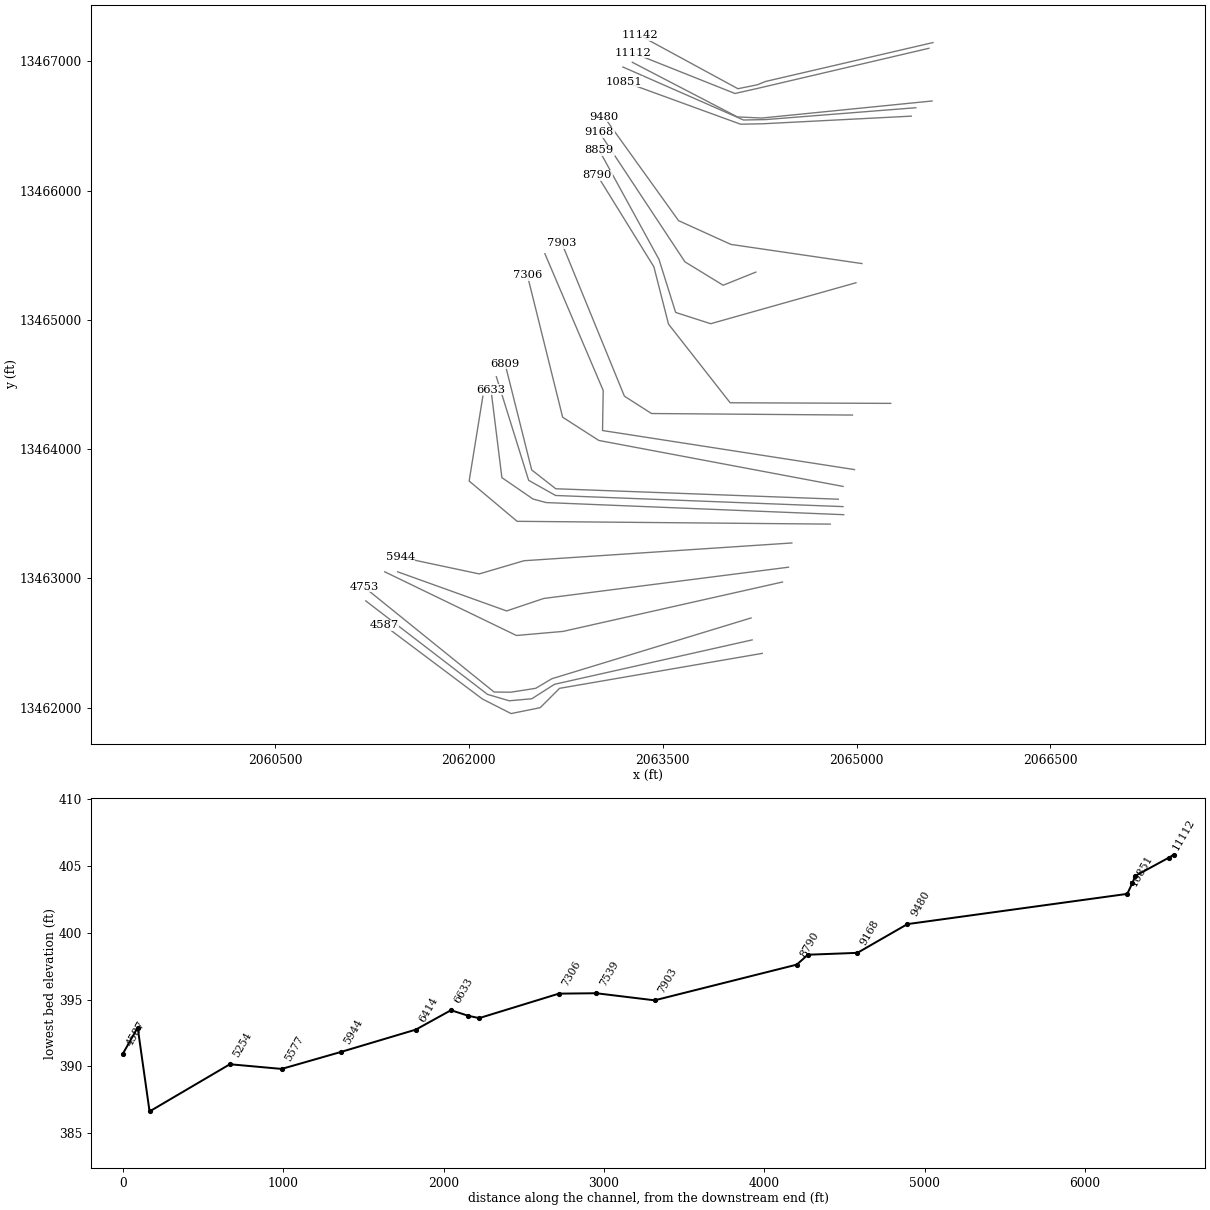
HEC-RAS study DOAK Br.prj: DOAK Br Base Level Engineering

--- DOAK Br.g01 (geometry) --- (continued)

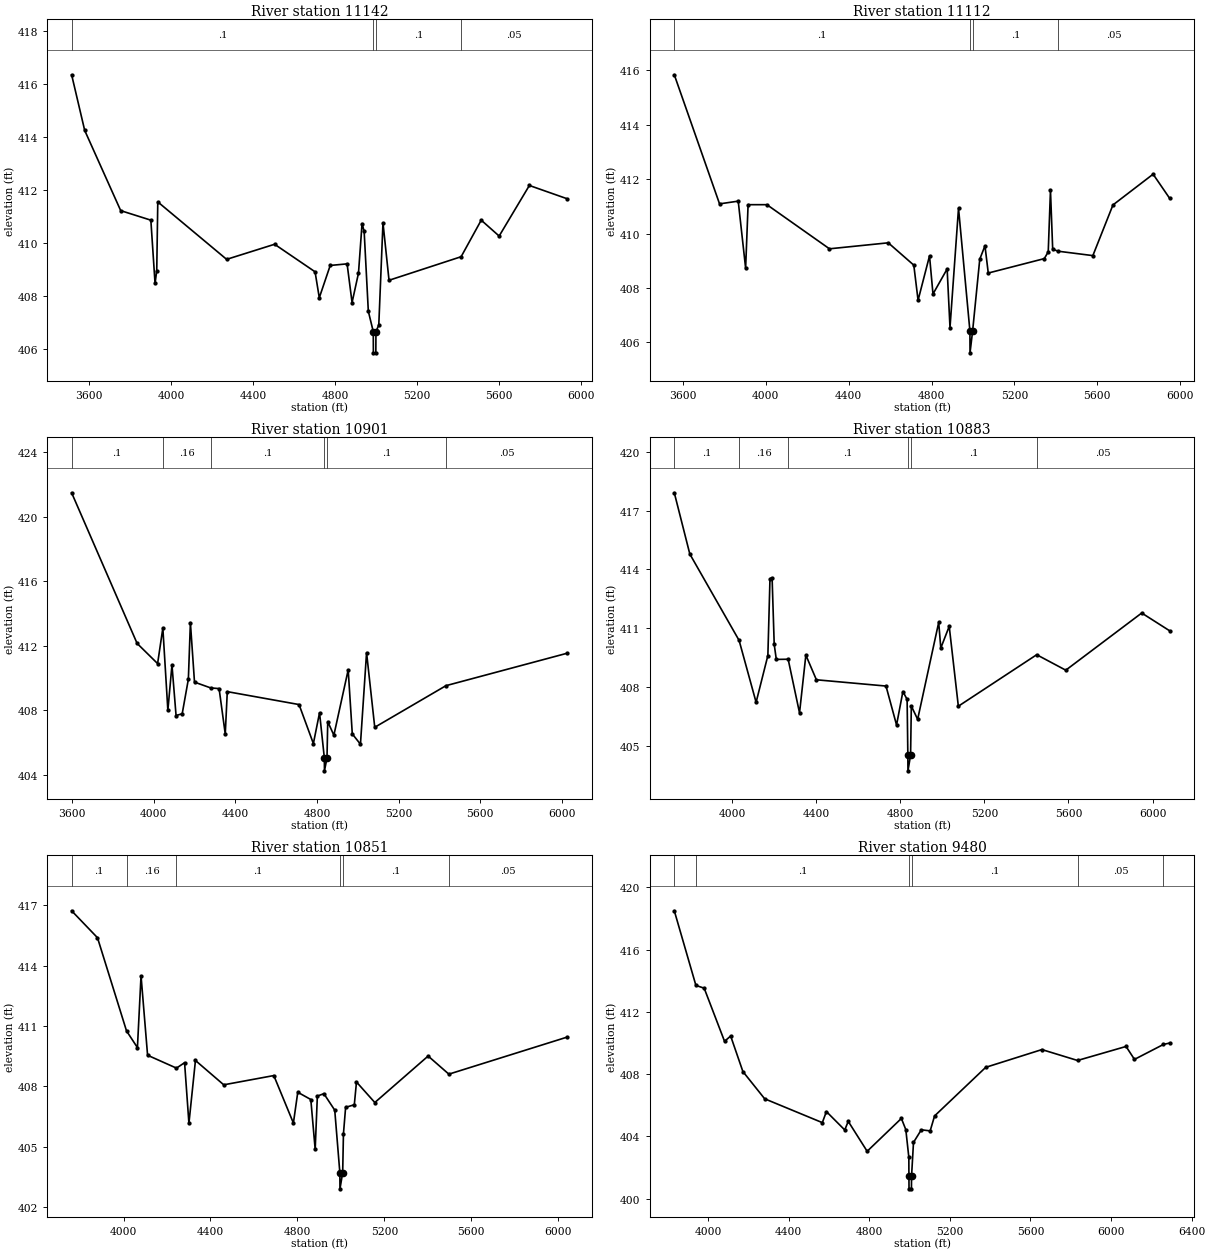
Type RM Length L Ch R = 1,11142,30,30,30
BEGIN DESCRIPTION:
double Mapping XS 64ea674c
END DESCRIPTION:
XS GIS Cut Line= 5
      2065591.24     13467144.59      2064297.09     13466843.97
      2064231.98     13466817.93      2064082.24     13466787.55
      2063323.03     13467200.14
#Sta/Elev= 30
  3514.5  416.34  3578.2  414.24  3753.8  411.21  3900.8  410.85  3921.3  408.46
  3929.5  408.94  3934.6  411.54  4270.3  409.37  4504.2  409.94  4701.5  408.90
  4722.1  407.92  4775.4  409.14  4857.7  409.20  4881.9  407.74  4913.2  408.85
  4930.6  410.72  4940.8  410.43  4961.2  407.41  4985.3  406.64  4985.8  405.84
  4997.8  405.84  4998.3  406.64  5012.2  406.89  5032.6  410.75  5062.1  408.58
  5413.7  409.47  5511.7  410.85  5599.1  410.25  5746.4  412.16  5930.1  411.66
#Mann=4,-1,0
  3514.5     0.1       0  4985.3    0.07       0  4998.3     0.1       0
  5413.7    0.05       0
Bank Sta=4985.3,4998.3
Exp/Cntr=0.3,0.1

Type RM Length L Ch R = 1,11112,211,211,211
BEGIN DESCRIPTION:
double Mapping XS 259a2a8a
END DESCRIPTION:
XS GIS Cut Line= 4
      2065560.02     13467100.33      2064233.07     13466789.72
      2064059.46     13466750.66      2063270.62     13467064.90
#Sta/Elev= 30
  3559.1  415.83  3777.4  411.09  3867.5  411.19  3903.2  408.73  3915.1  411.06
  4005.9  411.06  4307.6  409.44  4591.3  409.66  4714.5  408.84  4735.1  407.55
  4790.3  409.18  4807.0  407.78  4875.3  408.70  4889.1  406.55  4930.2  410.93
  4985.2  406.42  4985.7  405.62  4998.2  406.42  5032.7  409.06  5057.8  409.55
  5073.7  408.55  5344.1  409.08  5363.0  409.33  5373.8  411.59  5384.5  409.42
  5412.4  409.35  5578.3  409.19  5675.2  411.05  5868.9  412.18  5949.0  411.29
#Mann=4,-1,0
  3559.1     0.1       0  4985.2    0.07       0  4998.2     0.1       0
  5412.4    0.05       0
Bank Sta=4985.2,4998.2
Exp/Cntr=0.3,0.1

Type RM Length L Ch R = 1,10901,18,18,18
BEGIN DESCRIPTION:
Double Mapping XS 897f5654
END DESCRIPTION:
XS GIS Cut Line= 4
      2065584.51     13466692.63      2064267.79     13466560.77
      2064077.90     13466569.45      2063265.40     13466991.99
#Sta/Elev= 30
  3597.2  421.48  3918.3  412.14  4018.8  410.89  4044.5  413.09  4069.1  407.99
  4089.2  410.80  4109.3  407.67  4139.4  407.78  4169.6  409.92  4179.6  413.43
  4199.7  409.74  4279.4  409.38  4320.3  409.34  4350.5  406.52  4360.5  409.15
  4712.3  408.35  4782.6  405.93  4812.8  407.84  4836.4  405.04  4836.9  404.24
  4849.4  405.04  4853.0  407.29  4883.1  406.45  4953.3  410.50  4973.4  406.53
  5013.4  405.89  5043.4  411.57  5083.5  406.94  5432.7  409.52  6026.4  411.53
#Mann=6,-1,0
  3597.2     0.1       0  4044.5    0.16       0  4279.4     0.1       0
  4836.4    0.07       0  4849.4     0.1       0  5432.7    0.05       0
Bank Sta=4836.4,4849.4
Exp/Cntr=0.3,0.1

Type RM Length L Ch R = 1,10883,32,32,32
BEGIN DESCRIPTION:
Double Mapping XS 3fb00cab
END DESCRIPTION:
XS GIS Cut Line= 4
      2065458.63     13466640.55      2064297.09     13466548.83
      2064125.65     13466545.58      2063192.55     13466955.51
#Sta/Elev= 30
  3725.5  417.91  3799.4  414.78  4033.7  410.37  4114.5  407.21  4170.5  409.60
  4180.5  413.52  4190.6  413.56  4200.6  410.17  4210.6  409.40  4266.9  409.41
  4321.0  406.67  4351.1  409.62  4401.2  408.36  4732.2  408.04  4782.4  406.05
  4812.5  407.76  4832.6  407.36  4836.1  404.51  4836.6  403.71  4849.1  404.51
  4852.6  407.02  4882.7  406.34  4982.8  411.29  4992.8  409.98  5032.8  411.09
  5076.2  407.01  5448.8  409.64  5587.1  408.85  5948.2  411.77  6081.3  410.86
#Mann=6,-1,0
  3725.5     0.1       0  4033.7    0.16       0  4266.9     0.1       0
  4836.1    0.07       0  4849.1     0.1       0  5448.8    0.05       0
Bank Sta=4836.1,4849.1
Exp/Cntr=0.3,0.1

Type RM Length L Ch R = 1,10851,1371,1371,1371
BEGIN DESCRIPTION:
Double Mapping XS 587843a5
END DESCRIPTION:
XS GIS Cut Line= 4
      2065423.89     13466575.44      2064272.13     13466516.28
      2064102.86     13466513.03      2063204.24     13466840.46
#Sta/Elev= 30
  3761.2  416.72  3880.2  415.38  4013.7  410.75  4063.9  409.92  4080.5  413.49
  4110.6  409.54  4243.5  408.90  4280.8  409.17  4300.8  406.16  4330.8  409.28
  4461.0  408.07  4691.3  408.53  4781.4  406.17  4801.5  407.70  4861.5  407.34
  4881.6  404.86  4891.6  407.51  4921.6  407.63  4971.6  406.81  4995.1  403.70
  4995.6  402.90  5008.1  403.70  5011.6  405.63  5021.6  406.95  5061.6  407.08
  5071.6  408.21  5156.0  407.19  5401.2  409.50  5496.6  408.60  6040.2  410.44
#Mann=6,-1,0
  3761.2     0.1       0  4013.7    0.16       0  4243.5     0.1       0
  4995.1    0.07       0  5008.1     0.1       0  5496.6    0.05       0
Bank Sta=4995.1,5008.1
Exp/Cntr=0.3,0.1

Type RM Length L Ch R = 1,9480,312,312,312
BEGIN DESCRIPTION:
Double  stream Mapping XS e00dd5e4
END DESCRIPTION:
XS GIS Cut Line= 4
      2065041.71     13465434.83      2064028.20     13465583.01
      2063623.20     13465766.74      2063046.69     13466570.08
#Sta/Elev= 30
  3833.0  418.49  3940.2  413.70  3981.3  413.52  4082.3  410.11  4112.6  410.45
  4173.3  408.17  4281.4  406.42  4567.4  404.89  4587.6  405.60  4678.6  404.42
  4696.0  404.97  4789.8  403.05  4959.6  405.16  4981.6  404.44  4996.6  402.66
  4997.0  401.44  4997.5  400.64  5009.5  400.64  5010.0  401.44  5019.7  403.62
  5058.5  404.43  5102.4  404.36  5124.3  405.32  5378.0  408.44  5656.8  409.58
  5833.5  408.88  6074.2  409.78  6116.0  408.95  6259.8  409.91  6290.8  410.00
#Mann=6,-1,0
  3833.0    0.05       0  3940.2     0.1       0  4997.0    0.07       0
  5010.0     0.1       0  5833.5    0.05       0  6259.8    0.08       0
Bank Sta=4997,5010
Exp/Cntr=0.3,0.1

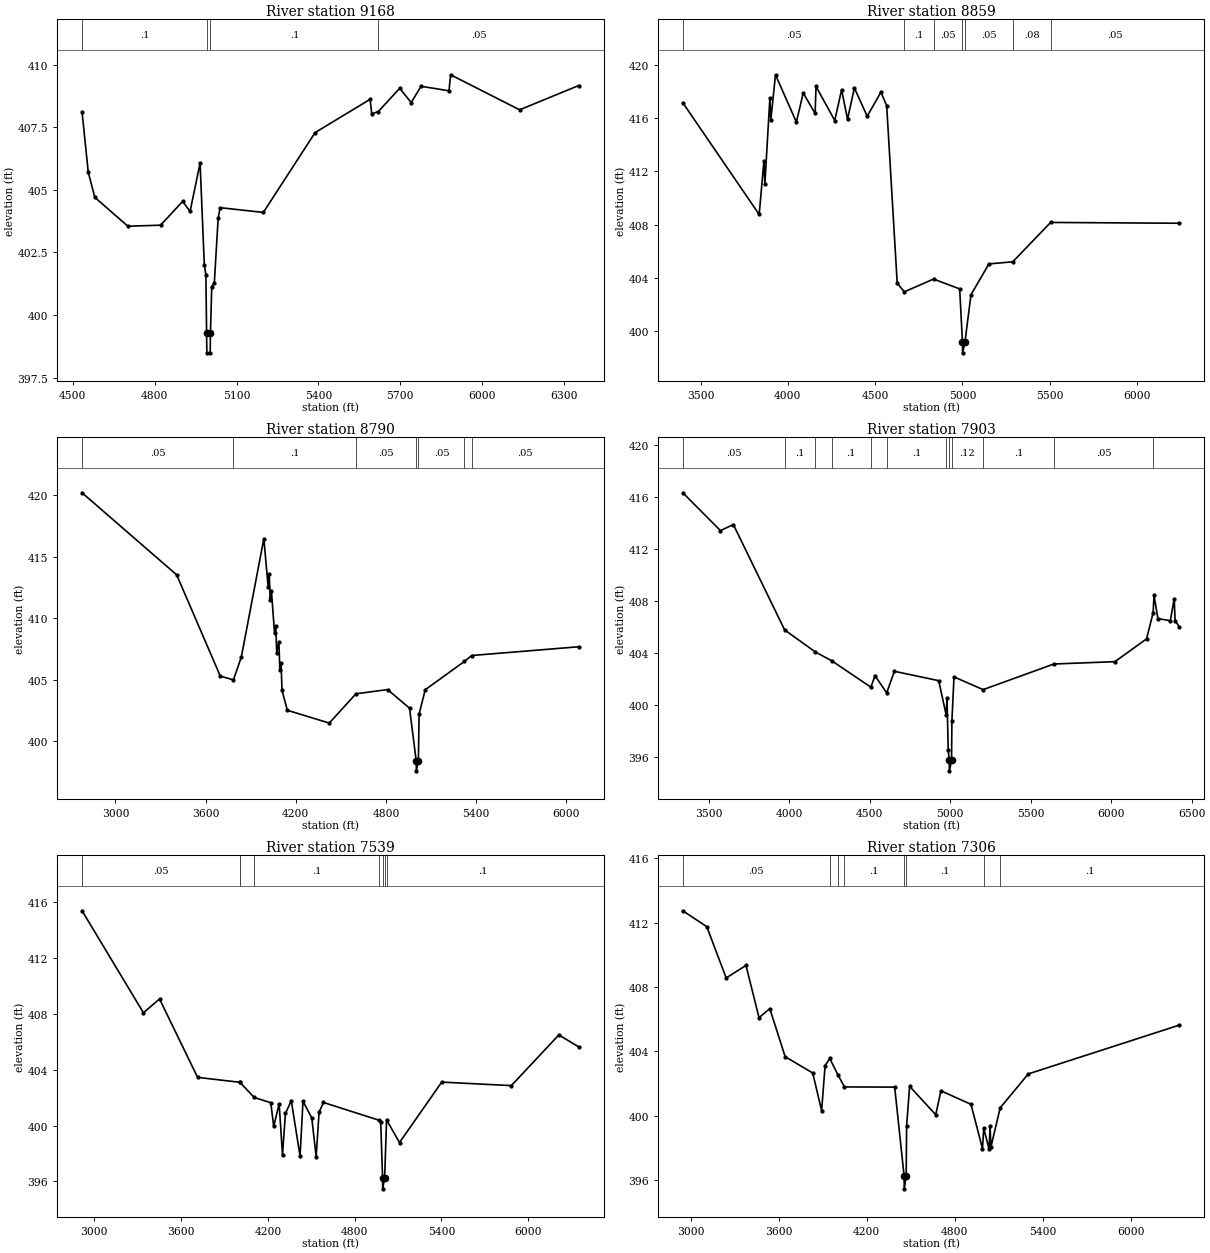
Type RM Length L Ch R = 1,9168,309,309,309
BEGIN DESCRIPTION:
Mapping XS a635cc63
END DESCRIPTION:
XS GIS Cut Line= 4
      2064220.68     13465368.70      2063968.09     13465267.15
      2063672.52     13465448.14      2063010.31     13466450.17
#Sta/Elev= 30
  4534.0  408.11  4556.8  405.70  4581.0  404.70  4701.8  403.55  4821.6  403.59
  4902.6  404.54  4929.8  404.14  4966.5  406.07  4982.0  402.01  4987.8  401.60
  4990.3  399.29  4991.3  398.49  5003.5  398.49  5004.5  399.29  5009.2  401.14
  5018.7  401.28  5032.7  403.87  5040.0  404.29  5198.3  404.10  5388.0  407.29
  5589.6  408.62  5595.6  408.04  5619.5  408.13  5698.0  409.06  5740.1  408.49
  5776.2  409.14  5878.6  408.96  5884.6  409.60  6137.4  408.20  6353.9  409.17
#Mann=4,-1,0
  4534.0     0.1       0  4990.3    0.07       0  5004.5     0.1       0
  5619.5    0.05       0
Bank Sta=4990.3,5004.5
Exp/Cntr=0.3,0.1

Type RM Length L Ch R = 1,8859,69,69,69
BEGIN DESCRIPTION:
Mapping XS 9d55d323
END DESCRIPTION:
XS GIS Cut Line= 5
      2064995.62     13465286.35      2063871.53     13464969.52
      2063600.54     13465056.75      2063472.00     13465466.37
      2063010.19     13466309.73
#Sta/Elev= 30
  3398.9  417.16  3835.9  408.76  3863.3  412.81  3868.5  411.04  3897.3  417.54
  3902.5  415.86  3929.4  419.27  4048.9  415.71  4088.1  417.90  4156.2  416.36
  4161.4  418.39  4268.6  415.83  4307.8  418.14  4341.8  415.93  4381.0  418.28
  4454.3  416.15  4532.7  417.96  4565.9  416.95  4626.2  403.59  4666.8  402.94
  4834.4  403.90  4983.8  403.16  4999.7  399.15  5000.7  398.35  5013.9  399.15
  5048.6  402.72  5151.1  405.04  5287.8  405.20  5504.5  408.16  6242.3  408.10
#Mann=7,-1,0
  3398.9    0.05       0  4666.8     0.1       0  4834.4    0.05       0
  4999.7    0.04       0  5013.9    0.05       0  5287.8    0.08       0
  5504.5    0.05       0
Bank Sta=4999.7,5013.9
Exp/Cntr=0.3,0.1

Type RM Length L Ch R = 1,8790,887,887,887
BEGIN DESCRIPTION:
Mapping XS 304196e8
END DESCRIPTION:
XS GIS Cut Line= 5
      2065264.72     13464353.20      2064022.24     13464357.86
      2063545.20     13464966.69      2063432.35     13465409.40
      2062994.57     13466117.01
#Sta/Elev= 30
  2778.0  420.20  3407.7  413.53  3697.7  405.31  3785.2  405.00  3837.7  406.84
  3987.7  416.47  4016.6  412.53  4023.7  413.57  4030.0  411.47  4038.1  412.24
  4058.9  408.80  4067.0  409.38  4073.4  407.17  4087.8  408.09  4094.2  405.81
  4102.3  406.39  4108.7  404.14  4143.9  402.53  4423.2  401.49  4600.5  403.87
  4811.3  404.21  4957.3  402.70  5001.8  398.41  5002.8  397.61  5016.0  398.41
  5020.9  402.23  5061.8  404.20  5322.4  406.50  5370.9  406.98  6082.9  407.69
#Mann=7,-1,0
  2778.0    0.05       0  3785.2     0.1       0  4600.5    0.05       0
  5001.8    0.04       0  5016.0    0.05       0  5322.4    0.08       0
  5370.9    0.05       0
Bank Sta=5001.8,5016
Exp/Cntr=0.3,0.1

Type RM Length L Ch R = 1,7903,364,364,364
BEGIN DESCRIPTION:
Mapping XS 2c1b322b
END DESCRIPTION:
XS GIS Cut Line= 4
      2064968.54     13464262.82      2063413.84     13464274.70
      2063204.20     13464408.81      2062719.28     13465594.36
#Sta/Elev= 30
  3340.0  416.31  3573.6  413.40  3653.6  413.87  3972.2  405.77  4162.3  404.08
  4263.3  403.41  4507.9  401.37  4533.6  402.25  4606.2  400.93  4653.6  402.59
  4929.0  401.87  4975.8  399.22  4980.6  400.53  4988.3  396.55  4994.7  395.74
  4995.7  394.94  5008.9  395.74  5011.0  398.75  5024.0  402.16  5204.8  401.18
  5644.2  403.15  6023.2  403.33  6219.9  405.08  6260.9  407.09  6266.3  408.43
  6290.3  406.64  6367.8  406.48  6391.8  408.17  6397.2  406.49  6424.5  405.98
#Mann=12,-1,0
  3340.0    0.05       0  3972.2     0.1       0  4162.3    0.05       0
  4263.3     0.1       0  4507.9    0.05       0  4606.2     0.1       0
  4975.8    0.12       0  4994.7    0.07       0  5008.9    0.12       0
  5204.8     0.1       0  5644.2    0.05       0  6260.9     0.1       0
Bank Sta=4994.7,5008.9
Exp/Cntr=0.3,0.1

Type RM Length L Ch R = 1,7539,233,233,233
BEGIN DESCRIPTION:
Mapping XS e87ce57f
END DESCRIPTION:
XS GIS Cut Line= 4
      2064984.20     13463840.94      2063034.93     13464143.19
      2063040.14     13464453.09      2062588.93     13465511.42
#Sta/Elev= 30
  2915.7  415.40  3339.9  408.09  3451.2  409.08  3714.3  403.46  4004.4  403.11
  4005.6  403.12  4105.6  402.02  4220.3  401.64  4240.5  399.94  4278.0  401.57
  4301.3  397.90  4321.5  400.87  4362.0  401.79  4422.7  397.81  4442.9  401.75
  4503.6  400.55  4534.0  397.77  4554.2  400.97  4584.6  401.66  4968.1  400.39
  4980.1  400.25  4993.0  396.27  4994.0  395.47  5007.2  396.27  5020.7  400.41
  5110.1  398.79  5402.0  403.12  5883.4  402.87  6211.3  406.50  6348.7  405.65
#Mann=8,-1,0
  2915.7    0.05       0  4004.4     0.1       0  4005.6    0.05       0
  4105.6     0.1       0  4968.1    0.16       0  4993.0    0.07       0
  5007.2    0.16       0  5020.7     0.1       0
Bank Sta=4993,5007.2
Exp/Cntr=0.3,0.1

Type RM Length L Ch R = 1,7306,497,497,497
BEGIN DESCRIPTION:
Mapping XS 410ef7c0
END DESCRIPTION:
XS GIS Cut Line= 4
      2064895.59     13463710.74      2063006.29     13464066.37
      2062726.34     13464246.05      2062452.92     13465346.15
#Sta/Elev= 30
  2945.0  412.74  3108.4  411.75  3240.7  408.56  3375.8  409.34  3464.6  406.09
  3538.3  406.65  3643.2  403.66  3830.9  402.65  3891.9  400.31  3915.7  403.11
  3947.3  403.55  4003.4  402.53  4047.9  401.78  4390.5  401.77  4454.7  396.24
  4455.7  395.44  4468.9  396.24  4471.9  399.37  4492.3  401.82  4670.6  400.05
  4706.0  401.54  4910.9  400.70  4989.5  397.94  4997.9  399.20  5035.1  397.90
  5041.1  399.35  5047.2  398.05  5110.3  400.48  5302.1  402.59  6333.7  405.63
#Mann=8,-1,0
  2945.0    0.05       0  3947.3    0.08       0  4003.4    0.05       0
  4047.9     0.1       0  4454.7    0.07       0  4468.9     0.1       0
  4997.9    0.12       0  5110.3     0.1       0
Bank Sta=4454.7,4468.9
Exp/Cntr=0.3,0.1

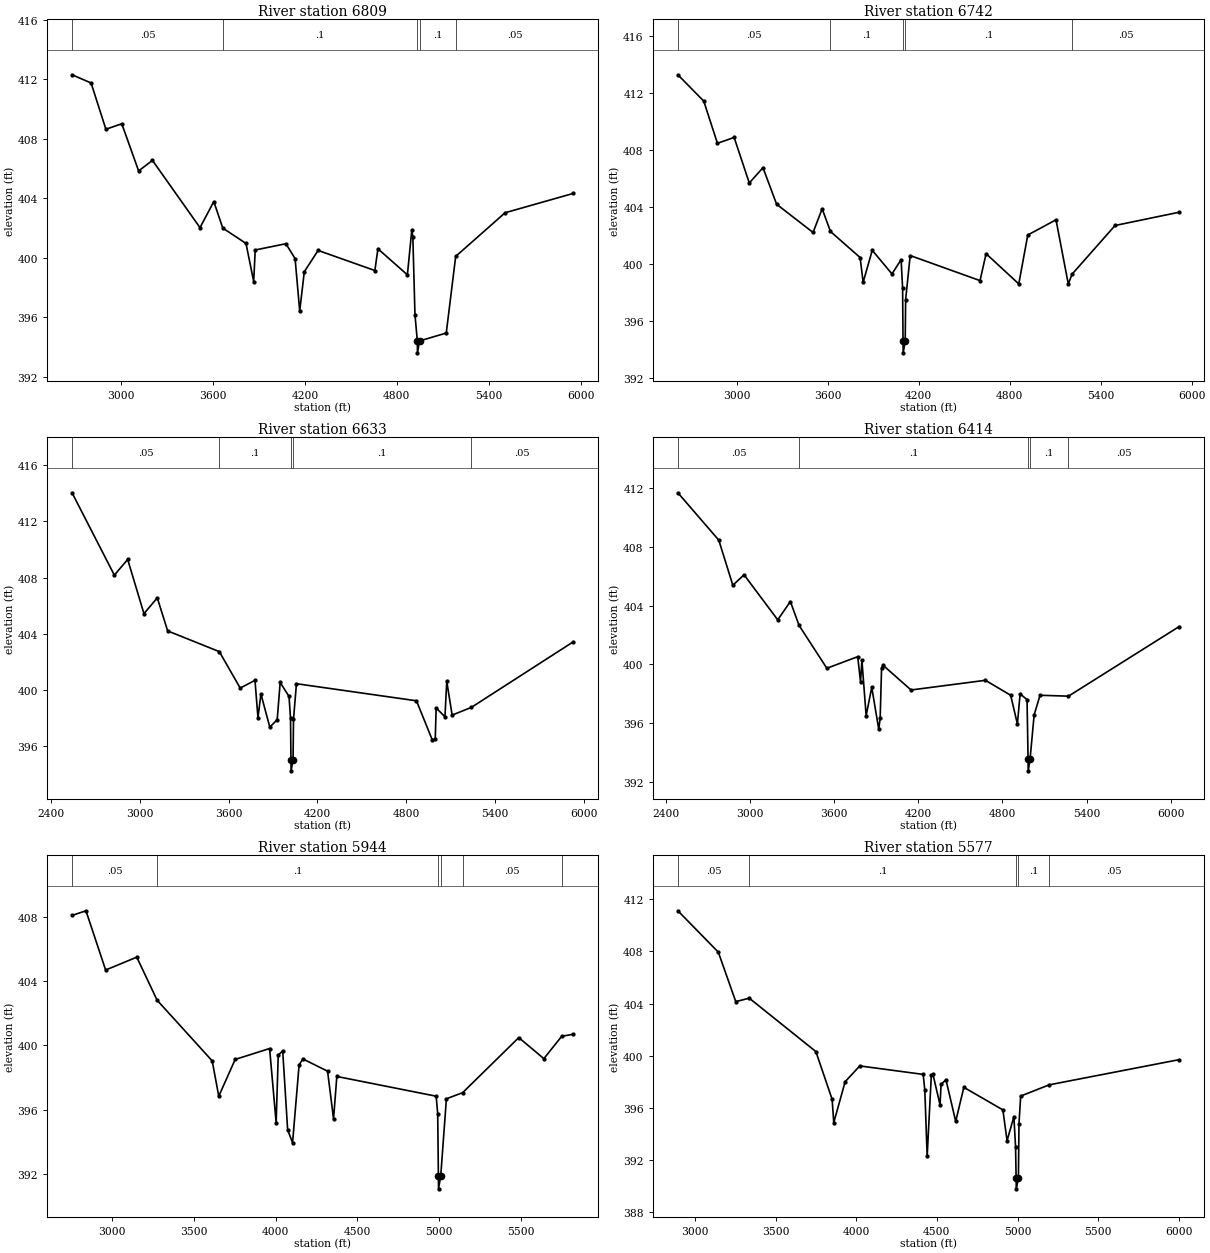
Type RM Length L Ch R = 1,6809,67,67,67
BEGIN DESCRIPTION:
Mapping XS b587e5f6
END DESCRIPTION:
XS GIS Cut Line= 4
      2064859.14     13463611.77      2062672.95     13463692.67
      2062486.76     13463838.50      2062281.06     13464658.61
#Sta/Elev= 30
  2681.0  412.29  2805.2  411.74  2901.9  408.63  3005.4  409.00  3115.4  405.83
  3205.5  406.54  3515.7  402.02  3605.8  403.77  3664.4  401.99  3815.9  400.96
  3866.0  398.40  3876.0  400.52  4076.1  400.94  4136.1  399.94  4166.2  396.42
  4196.2  399.06  4286.2  400.49  4656.5  399.14  4676.5  400.60  4868.7  398.85
  4897.3  401.85  4904.2  401.42  4918.1  396.17  4933.5  394.41  4934.5  393.61
  4947.8  394.41  5122.2  394.94  5183.8  400.09  5505.9  403.02  5950.7  404.32
#Mann=5,-1,0
  2681.0    0.05       0  3664.4     0.1       0  4933.5    0.07       0
  4947.8     0.1       0  5183.8    0.05       0
Bank Sta=4933.5,4947.8
Exp/Cntr=0.3,0.1

Type RM Length L Ch R = 1,6742,109,109,109
BEGIN DESCRIPTION:
Mapping XS 9678e796
END DESCRIPTION:
XS GIS Cut Line= 4
      2064895.58     13463554.48      2062671.65     13463640.59
      2062463.32     13463757.77      2062213.34     13464559.69
#Sta/Elev= 30
  2612.9  413.30  2783.6  411.45  2873.7  408.49  2983.8  408.90  3083.8  405.70
  3173.9  406.78  3264.0  404.21  3504.1  402.23  3564.2  403.89  3618.9  402.30
  3814.4  400.47  3834.4  398.73  3894.4  400.98  4024.5  399.32  4084.6  400.32
  4094.6  398.33  4097.4  394.58  4098.4  393.78  4111.7  394.58  4114.6  397.52
  4144.6  400.61  4605.0  398.85  4645.0  400.74  4860.5  398.62  4919.8  402.05
  5106.0  403.12  5187.0  398.61  5211.7  399.30  5495.4  402.72  5917.5  403.65
#Mann=5,-1,0
  2612.9    0.05       0  3618.9     0.1       0  4097.4    0.07       0
  4111.7     0.1       0  5211.7    0.05       0
Bank Sta=4097.4,4111.7
Exp/Cntr=0.3,0.1

Type RM Length L Ch R = 1,6633,219,219,219
BEGIN DESCRIPTION:
Mapping XS 87154401
END DESCRIPTION:
XS GIS Cut Line= 5
      2064900.81     13463491.98      2062597.43     13463585.90
      2062497.17     13463613.24      2062256.29     13463778.61
      2062171.72     13464460.38
#Sta/Elev= 30
  2542.1  414.05  2828.1  408.17  2918.2  409.29  3028.3  405.42  3118.4  406.55
  3188.4  404.19  3537.8  402.71  3678.9  400.11  3778.9  400.66  3799.0  397.99
  3819.0  399.69  3879.0  397.32  3929.1  397.85  3949.1  400.51  4009.1  399.51
  4019.1  397.95  4022.0  395.00  4023.0  394.20  4036.3  395.00  4039.2  397.88
  4059.2  400.42  4870.6  399.20  4976.5  396.43  4997.5  396.44  5003.6  398.69
  5063.1  398.06  5075.3  400.59  5111.6  398.18  5241.8  398.73  5930.5  403.41
#Mann=5,-1,0
  2542.1    0.05       0  3537.8     0.1       0  4022.0    0.07       0
  4036.3     0.1       0  5241.8    0.05       0
Bank Sta=4022,4036.3
Exp/Cntr=0.3,0.1

Type RM Length L Ch R = 1,6414,470,470,470
BEGIN DESCRIPTION:
Mapping XS 6f589524
END DESCRIPTION:
XS GIS Cut Line= 4
      2064796.67     13463419.07      2062374.13     13463440.72
      2062002.97     13463752.51      2062109.18     13464408.69
#Sta/Elev= 30
  2487.4  411.70  2779.1  408.47  2879.1  405.40  2959.1  406.11  3199.1  403.04
  3289.1  404.29  3351.1  402.66  3549.1  399.74  3769.1  400.53  3789.1  398.82
  3799.1  400.27  3829.1  396.51  3869.1  398.44  3919.1  395.58  3929.1  396.35
  3939.1  399.74  3949.1  399.95  4149.1  398.26  4679.2  398.92  4859.2  397.90
  4907.1  395.94  4926.5  398.00  4975.9  397.60  4983.1  393.55  4984.1  392.75
  4997.4  393.55  5026.4  396.56  5068.3  397.90  5271.3  397.84  6059.5  402.58
#Mann=5,-1,0
  2487.4    0.05       0  3351.1     0.1       0  4983.1    0.07       0
  4997.4     0.1       0  5271.3    0.05       0
Bank Sta=4983.1,4997.4
Exp/Cntr=0.3,0.1

Type RM Length L Ch R = 1,5944,367,367,367
BEGIN DESCRIPTION:
Mapping XS 1749a99f
END DESCRIPTION:
XS GIS Cut Line= 4
      2064499.81     13463273.23      2062427.29     13463135.81
      2062081.16     13463033.81      2061469.31     13463163.70
#Sta/Elev= 30
  2755.5  408.10  2840.5  408.39  2960.8  404.70  3151.2  405.50  3275.4  402.82
  3612.2  399.04  3652.3  396.84  3752.5  399.13  3963.0  399.81  4003.0  395.19
  4015.8  399.40  4043.1  399.66  4073.2  394.75  4103.3  393.94  4143.3  398.79
  4166.5  399.16  4317.3  398.40  4353.8  395.43  4373.9  398.07  4980.9  396.84
  4990.4  395.76  4994.6  391.87  4995.6  391.07  5008.9  391.87  5043.5  396.68
  5142.8  397.06  5485.9  400.49  5639.3  399.18  5748.2  400.57  5818.9  400.70
#Mann=6,-1,0
  2755.5    0.05       0  3275.4     0.1       0  4994.6    0.07       0
  5008.9     0.1       0  5142.8    0.05       0  5748.2     0.1       0
Bank Sta=4994.6,5008.9
Exp/Cntr=0.3,0.1

Type RM Length L Ch R = 1,5577,323,323,323
BEGIN DESCRIPTION:
Mapping XS c4398a56
END DESCRIPTION:
XS GIS Cut Line= 4
      2064473.71     13463085.73      2062580.29     13462843.93
      2062292.75     13462747.36      2061449.97     13463050.01
#Sta/Elev= 30
  2894.2  411.12  3144.9  407.95  3253.0  404.16  3337.0  404.42  3749.8  400.33
  3850.6  396.67  3860.7  394.89  3931.3  398.02  4022.0  399.23  4415.2  398.58
  4425.2  397.37  4439.8  392.31  4465.6  398.51  4475.6  398.59  4519.6  396.25
  4526.1  397.81  4556.3  398.17  4616.8  394.98  4667.2  397.59  4909.2  395.86
  4935.2  393.50  4977.5  395.34  4987.9  393.03  4991.3  390.61  4992.3  389.81
  5005.6  390.61  5009.0  394.77  5019.6  396.92  5196.3  397.78  6001.8  399.71
#Mann=5,-1,0
  2894.2    0.05       0  3337.0     0.1       0  4991.3    0.07       0
  5005.6     0.1       0  5196.3    0.05       0
Bank Sta=4991.3,5005.6
Exp/Cntr=0.3,0.1

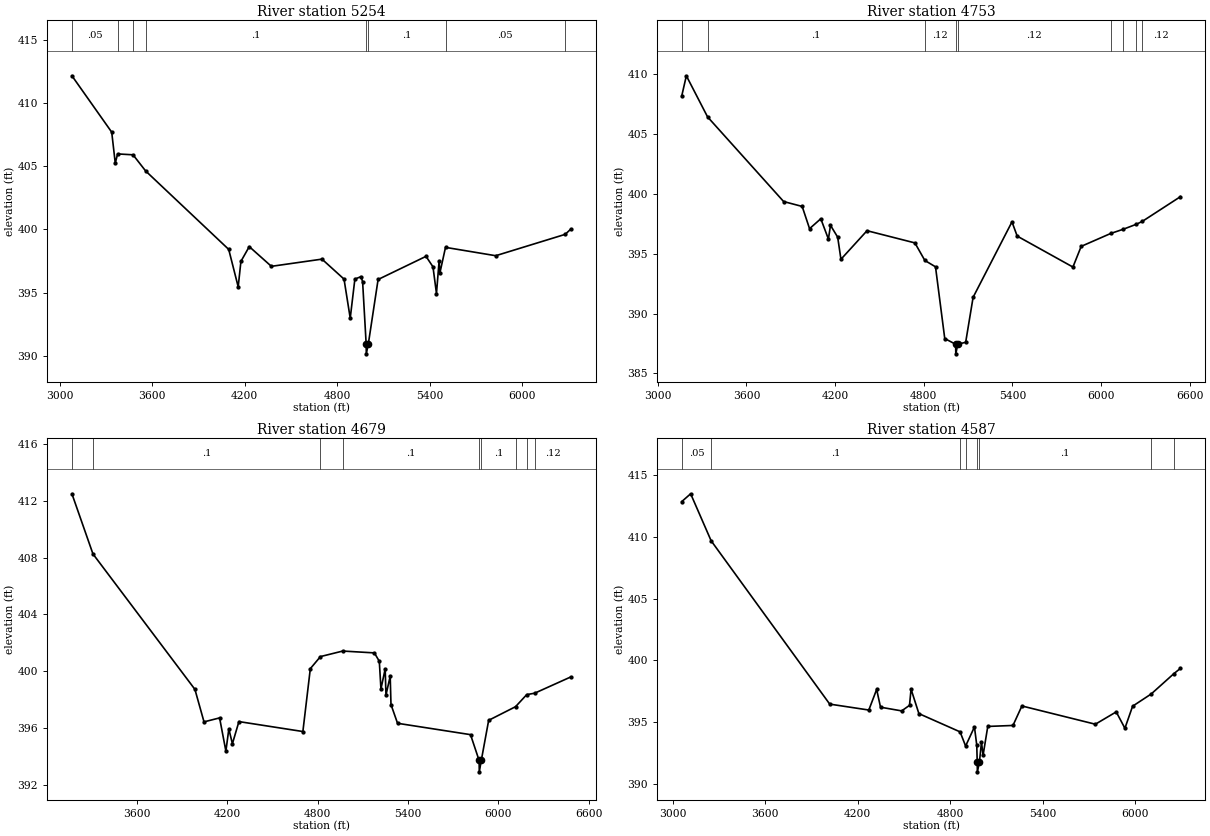
Type RM Length L Ch R = 1,5254,501,501,501
BEGIN DESCRIPTION:
Mapping XS 22599b6d
END DESCRIPTION:
XS GIS Cut Line= 4
      2064426.83     13462971.14      2062728.94     13462588.94
      2062368.70     13462557.47      2061350.01     13463049.99
#Sta/Elev= 30
  3079.6  412.15  3337.7  407.69  3360.7  405.24  3375.9  405.97  3475.9  405.90
  3557.8  404.62  4096.3  398.42  4157.8  395.46  4175.4  397.47  4229.5  398.64
  4373.0  397.08  4701.0  397.65  4844.0  396.07  4884.2  392.98  4914.3  396.07
  4954.4  396.27  4964.5  395.86  4987.4  390.96  4988.4  390.16  5001.8  390.96
  5064.9  396.04  5375.6  397.87  5420.8  397.04  5443.4  394.93  5460.5  397.50
  5466.0  396.58  5502.0  398.58  5827.5  397.92  6278.2  399.61  6313.1  400.01
#Mann=8,-1,0
  3079.6    0.05       0  3375.9    0.08       0  3475.9    0.05       0
  3557.8     0.1       0  4987.4    0.07       0  5001.8     0.1       0
  5502.0    0.05       0  6278.2    0.12       0
Bank Sta=4987.4,5001.8
Exp/Cntr=0.3,0.1

Type RM Length L Ch R = 1,4753,74,74,74
BEGIN DESCRIPTION:
Mapping XS d7cffdb8
END DESCRIPTION:
XS GIS Cut Line= 6
      2064184.49     13462693.28      2062642.57     13462222.83
      2062517.57     13462148.62      2062324.86     13462118.67
      2062195.96     13462119.97      2061188.62     13462933.63
#Sta/Elev= 30
  3162.1  408.22  3192.9  409.89  3336.6  406.45  3851.6  399.37  3977.1  398.96
  4027.1  397.10  4103.2  397.93  4154.8  396.23  4168.8  397.38  4217.5  396.39
  4239.6  394.54  4416.2  396.93  4740.3  395.91  4807.7  394.44  4879.8  393.91
  4942.4  387.91  5016.2  387.43  5017.2  386.63  5030.6  387.43  5084.1  387.60
  5134.4  391.36  5397.6  397.67  5432.8  396.48  5810.2  393.89  5866.2  395.62
  6066.2  396.70  6150.4  397.05  6239.7  397.47  6280.0  397.71  6538.4  399.78
#Mann=9,-1,0
  3162.1    0.05       0  3336.6     0.1       0  4807.7    0.12       0
  5016.2    0.07       0  5030.6    0.12       0  6066.2    0.05       0
  6150.4     0.1       0  6239.7    0.05       0  6280.0    0.12       0
Bank Sta=5016.2,5030.6
Exp/Cntr=0.3,0.1

Type RM Length L Ch R = 1,4679,92,92,92
BEGIN DESCRIPTION:
Mapping XS aab5bf28
END DESCRIPTION:
XS GIS Cut Line= 6
      2064192.51     13462523.23      2062663.41     13462179.87
      2062487.62     13462067.89      2062313.15     13462052.26
      2062145.18     13462101.74      2061202.93     13462825.31
#Sta/Elev= 30
  3166.5  412.49  3306.4  408.25  3983.9  398.71  4044.3  396.42  4147.9  396.70
  4189.7  394.36  4209.3  395.92  4233.0  394.88  4276.3  396.44  4701.3  395.74
  4750.8  400.17  4818.1  401.02  4966.1  401.41  5176.4  401.28  5209.2  400.69
  5220.1  398.74  5248.2  400.15  5253.5  398.31  5281.6  399.64  5286.8  397.64
  5330.4  396.32  5815.4  395.52  5872.5  393.70  5873.6  392.90  5886.9  393.70
  5935.9  396.53  6114.5  397.49  6188.8  398.34  6241.5  398.44  6480.4  399.58
#Mann=9,-1,0
  3166.5    0.05       0  3306.4     0.1       0  4818.1    0.12       0
  4966.1     0.1       0  5872.5    0.07       0  5886.9     0.1       0
  6114.5    0.07       0  6188.8     0.1       0  6241.5    0.12       0
Bank Sta=5872.5,5886.9
Exp/Cntr=0.3,0.1

Type RM Length L Ch R = 1,4587,499,499,499
BEGIN DESCRIPTION:
Mapping XS 0a3ca907
END DESCRIPTION:
XS GIS Cut Line= 6
      2064270.60     13462419.06      2062702.47     13462148.62
      2062552.73     13461998.88      2062327.47     13461953.30
      2062104.81     13462066.58      2061343.52     13462637.83
#Sta/Elev= 30
  3059.5  412.87  3116.9  413.50  3249.8  409.69  4019.1  396.45  4272.7  395.97
  4323.5  397.64  4348.6  396.20  4485.8  395.90  4536.6  396.35  4546.7  397.66
  4597.5  395.68  4864.7  394.20  4900.6  393.05  4957.9  394.60  4972.9  393.12
  4975.9  391.76  4976.9  390.96  4990.3  391.76  5003.5  393.38  5013.7  392.29
  5044.3  394.64  5207.8  394.72  5265.7  396.30  5742.2  394.82  5877.6  395.82
  5933.9  394.49  5983.8  396.28  6104.3  397.27  6251.6  398.92  6294.4  399.35
#Mann=8,-1,0
  3059.5    0.05       0  3249.8     0.1       0  4864.7    0.12       0
  4900.6     0.1       0  4975.9    0.07       0  4990.3     0.1       0
  6104.3    0.07       0  6251.6    0.12       0
Bank Sta=4975.9,4990.3
Exp/Cntr=0.3,0.1