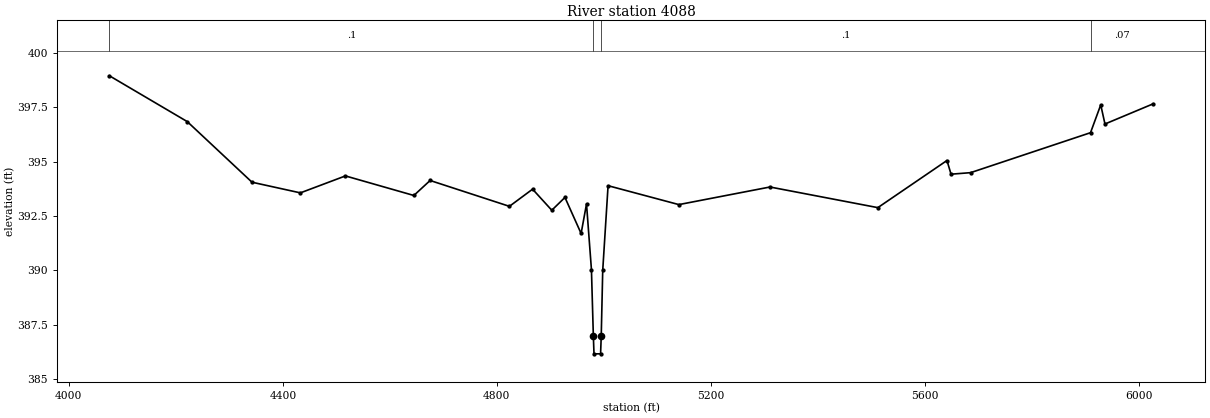
HEC-RAS study DOAK Br.prj: DOAK Br Base Level Engineering

--- DOAK Br.g01 (geometry) --- (continued)

Type RM Length L Ch R = 1,4088,0,0,0
BEGIN DESCRIPTION:
Mapping XS b16e2492
END DESCRIPTION:
XS GIS Cut Line= 4
      2063195.04     13461506.86      2063111.69     13461437.41
      2061672.20     13461624.37      2061449.63     13461945.62
#Sta/Elev= 30
  4075.9  398.95  4221.4  396.84  4342.4  394.05  4432.8  393.56  4517.0  394.34
  4644.9  393.44  4675.3  394.13  4823.5  392.94  4866.8  393.73  4902.7  392.76
  4927.3  393.35  4957.5  391.69  4967.6  393.05  4976.8  390.03  4980.4  386.95
  4981.6  386.15  4993.9  386.15  4995.1  386.95  4997.9  389.99  5007.9  393.89
  5140.2  393.02  5310.5  393.83  5512.1  392.88  5641.3  395.05  5648.9  394.42
  5685.4  394.49  5909.6  396.33  5928.7  397.61  5936.6  396.73  6026.8  397.66
#Mann=4,-1,0
  4075.9     0.1       0  4980.4    0.07       0  4995.1     0.1       0
  5909.6    0.07       0
Bank Sta=4980.4,4995.1
Exp/Cntr=0.3,0.1

Chan Stop Cuts=-1