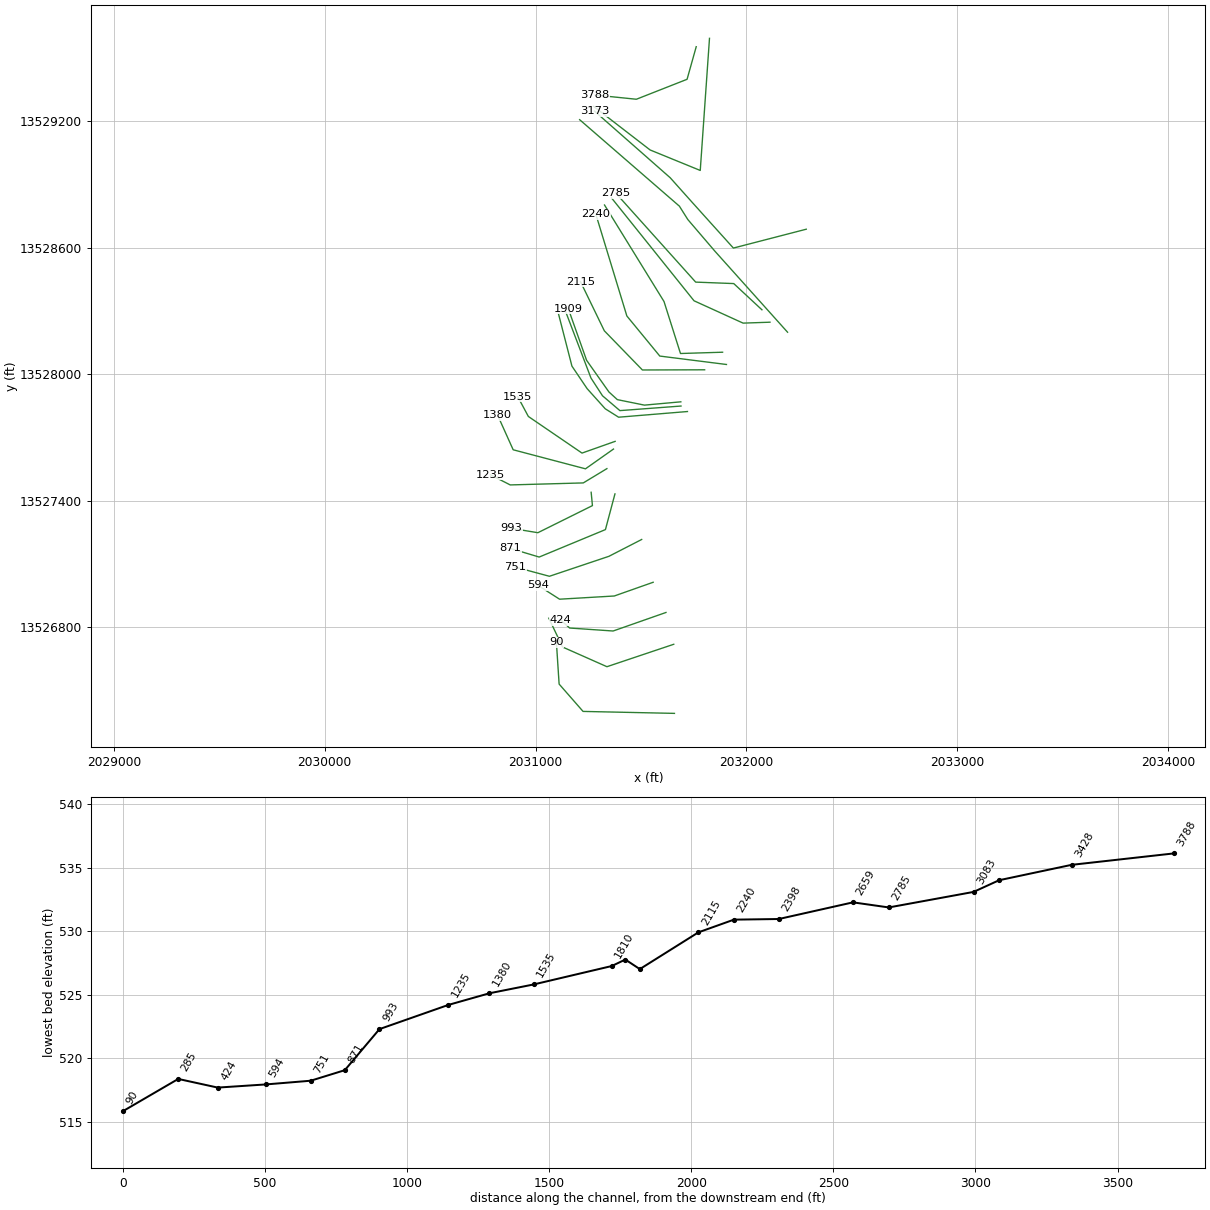
HEC-RAS study EAST FORK ELLIS Br.prj: EAST FORK ELLIS Br Base Level Engineering

--- EAST FORK ELLIS Br.g01 (geometry) --- (continued)

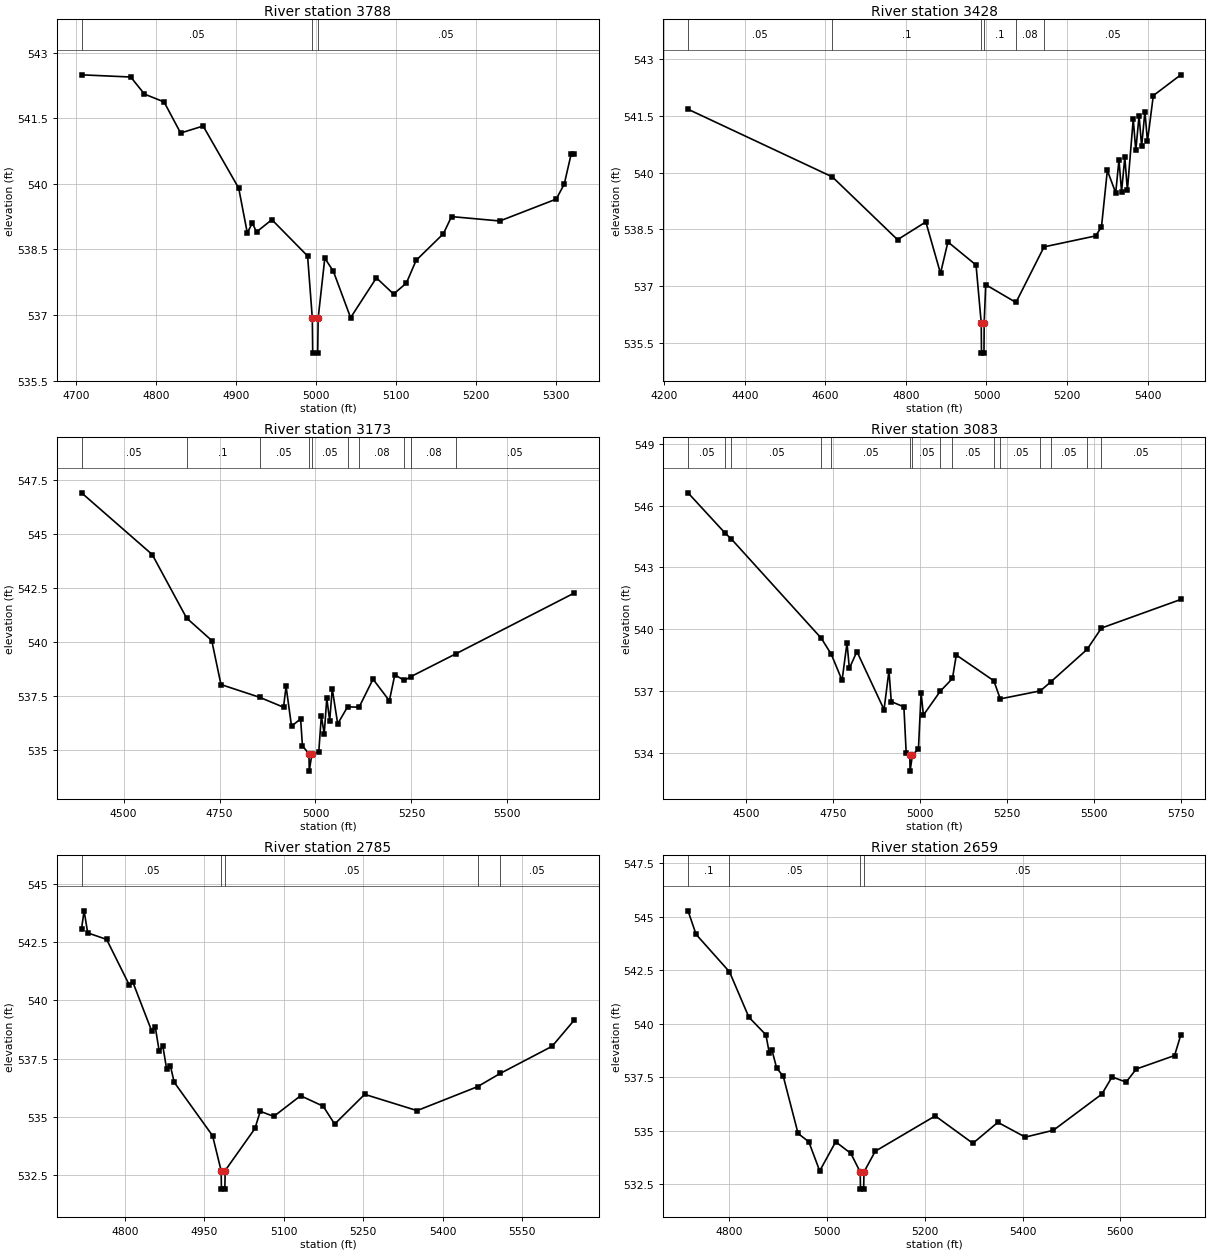
Type RM Length L Ch R = 1,3788,360,360,360
BEGIN DESCRIPTION:
Mapping XS bd652c91
END DESCRIPTION:
XS GIS Cut Line= 4
      2031761.63     13529554.11      2031718.23     13529399.60
      2031477.78     13529304.98      2031282.49     13529324.95
#Sta/Elev= 30
  4707.3  542.49  4768.7  542.44  4785.8  542.05  4810.3  541.87  4831.0  541.16
  4859.1  541.32  4903.5  539.90  4914.2  538.88  4920.5  539.10  4925.8  538.90
  4944.9  539.18  4989.5  538.35  4995.4  536.93  4995.9  536.13  5002.1  536.13
  5002.7  536.93  5011.0  538.30  5021.7  538.00  5043.2  536.94  5075.4  537.85
  5096.9  537.48  5112.8  537.73  5125.0  538.25  5159.1  538.86  5169.2  539.25
  5229.5  539.15  5299.9  539.65  5309.9  539.99  5318.7  540.69  5322.5  540.69
#Mann=3,-1,0
  4707.3    0.05       0  4995.4    0.03       0  5002.7    0.05       0
Bank Sta=4995.4,5002.7
Exp/Cntr=0.3,0.1

Type RM Length L Ch R = 1,3428,255,255,255
BEGIN DESCRIPTION:
Mapping XS 59328ed9
END DESCRIPTION:
XS GIS Cut Line= 4
      2031824.55     13529593.84      2031780.73     13528967.31
      2031542.88     13529064.53      2031275.23     13529271.09
#Sta/Elev= 30
  4259.2  541.68  4617.5  539.89  4779.3  538.23  4849.5  538.70  4885.9  537.34
  4904.3  538.17  4974.1  537.56  4987.0  536.03  4987.6  535.23  4993.8  535.23
  4994.3  536.03  4998.1  537.04  5073.2  536.57  5142.9  538.04  5271.0  538.33
  5285.5  538.57  5300.0  540.06  5320.8  539.47  5328.9  540.34  5335.3  539.50
  5343.4  540.41  5349.8  539.54  5364.3  541.42  5370.6  540.59  5378.8  541.51
  5385.1  540.70  5393.3  541.62  5399.6  540.83  5414.1  542.04  5482.3  542.59
#Mann=6,-1,0
  4259.2    0.05       0  4617.5     0.1       0  4987.0    0.07       0
  4994.3     0.1       0  5073.2    0.08       0  5142.9    0.05       0
Bank Sta=4987,4994.3
Exp/Cntr=0.3,0.1

Type RM Length L Ch R = 1,3173,90,90,90
BEGIN DESCRIPTION:
Mapping XS 137a962f
END DESCRIPTION:
XS GIS Cut Line= 6
      2032283.35     13528688.67      2031937.85     13528599.25
      2031794.62     13528758.11      2031732.99     13528826.68
      2031638.37     13528932.59      2031278.89     13529249.01
#Sta/Elev= 30
  4390.5  546.91  4574.7  544.05  4664.2  541.11  4729.7  540.07  4753.7  538.03
  4854.4  537.44  4916.7  536.98  4923.4  537.94  4937.6  536.10  4961.3  536.44
  4966.0  535.19  4983.1  534.82  4983.7  534.02  4990.8  534.82  5008.6  534.92
  5015.3  536.57  5022.8  535.75  5029.5  537.40  5037.0  536.35  5043.7  537.83
  5057.9  536.21  5083.7  537.00  5113.6  536.98  5149.9  538.28  5192.5  537.28
  5206.7  538.48  5231.7  538.22  5247.8  538.39  5366.4  539.46  5674.4  542.27
#Mann=10,-1,0
  4390.5    0.05       0  4664.2     0.1       0  4854.4    0.05       0
  4983.1    0.07       0  4990.8    0.05       0  5083.7    0.05       0
  5113.6    0.08       0  5231.7    0.05       0  5247.8    0.08       0
  5366.4    0.05       0
Bank Sta=4983.1,4990.8
Exp/Cntr=0.3,0.1

Type RM Length L Ch R = 1,3083,298,298,298
BEGIN DESCRIPTION:
Mapping XS 4222492d
END DESCRIPTION:
XS GIS Cut Line= 5
      2032194.77     13528200.17      2031850.17     13528584.50
      2031721.70     13528734.67      2031681.77     13528798.04
      2031208.69     13529208.13
#Sta/Elev= 30
  4334.0  546.62  4440.1  544.67  4458.8  544.37  4716.4  539.56  4745.3  538.78
  4776.3  537.51  4790.5  539.33  4797.2  538.09  4818.9  538.91  4896.8  536.09
  4911.0  537.98  4917.6  536.48  4953.8  536.22  4960.4  533.99  4970.8  533.90
  4971.5  533.10  4978.5  533.90  4995.6  534.17  5003.2  536.91  5009.8  535.82
  5058.2  536.98  5093.2  537.60  5104.3  538.74  5212.0  537.49  5230.5  536.61
  5345.8  537.00  5375.8  537.44  5479.5  539.01  5521.0  540.05  5748.8  541.44
#Mann=15,-1,0
  4334.0    0.05       0  4440.1     0.1       0  4458.8    0.05       0
  4716.4    0.08       0  4745.3    0.05       0  4970.8    0.04       0
  4978.5    0.05       0  5058.2     0.1       0  5093.2    0.05       0
  5212.0     0.1       0  5230.5    0.05       0  5345.8     0.1       0
  5375.8    0.05       0  5479.5     0.1       0  5521.0    0.05       0
Bank Sta=4970.8,4978.5
Exp/Cntr=0.3,0.1

Type RM Length L Ch R = 1,2785,126,126,126
BEGIN DESCRIPTION:
Mapping XS 75b9aacc
END DESCRIPTION:
XS GIS Cut Line= 4
      2032073.23     13528306.51      2031939.58     13528430.85
      2031759.03     13528437.80      2031380.57     13528859.42
#Sta/Elev= 30
  4718.6  543.09  4723.4  543.86  4730.2  542.91  4765.9  542.63  4808.4  540.68
  4815.2  540.80  4850.9  538.69  4857.7  538.86  4865.1  537.82  4871.9  538.05
  4879.2  537.04  4886.1  537.20  4893.4  536.48  4965.8  534.18  4981.9  532.68
  4982.6  531.88  4989.0  531.88  4989.6  532.68  5045.8  534.49  5055.8  535.23
  5081.3  535.01  5131.9  535.90  5174.5  535.45  5196.2  534.68  5252.8  535.96
  5351.7  535.26  5465.8  536.29  5508.6  536.86  5606.6  538.03  5648.4  539.16
#Mann=5,-1,0
  4718.6    0.05       0  4981.9    0.03       0  4989.6    0.05       0
  5465.8     0.1       0  5508.6    0.05       0
Bank Sta=4981.9,4989.6
Exp/Cntr=0.3,0.1

Type RM Length L Ch R = 1,2659,261,261,261
BEGIN DESCRIPTION:
Mapping XS 88f210ab
END DESCRIPTION:
XS GIS Cut Line= 4
      2032111.50     13528247.69      2031983.85     13528243.35
      2031751.21     13528349.25      2031359.84     13528837.15
#Sta/Elev= 30
  4715.1  545.28  4731.6  544.18  4800.0  542.43  4839.7  540.31  4874.5  539.49
  4881.5  538.64  4887.0  538.77  4896.5  537.94  4910.1  537.55  4940.4  534.88
  4962.4  534.49  4984.7  533.13  5017.4  534.49  5048.4  533.95  5067.6  533.08
  5068.2  532.28  5074.7  532.28  5075.3  533.08  5098.4  534.05  5221.2  535.70
  5298.3  534.42  5349.4  535.40  5405.5  534.71  5463.1  535.03  5562.4  536.72
  5583.2  537.52  5612.0  537.28  5632.8  537.89  5711.2  538.52  5723.9  539.48
#Mann=4,-1,0
  4715.1     0.1       0  4800.0    0.05       0  5067.6    0.03       0
  5075.3    0.05       0
Bank Sta=5067.6,5075.3
Exp/Cntr=0.3,0.1

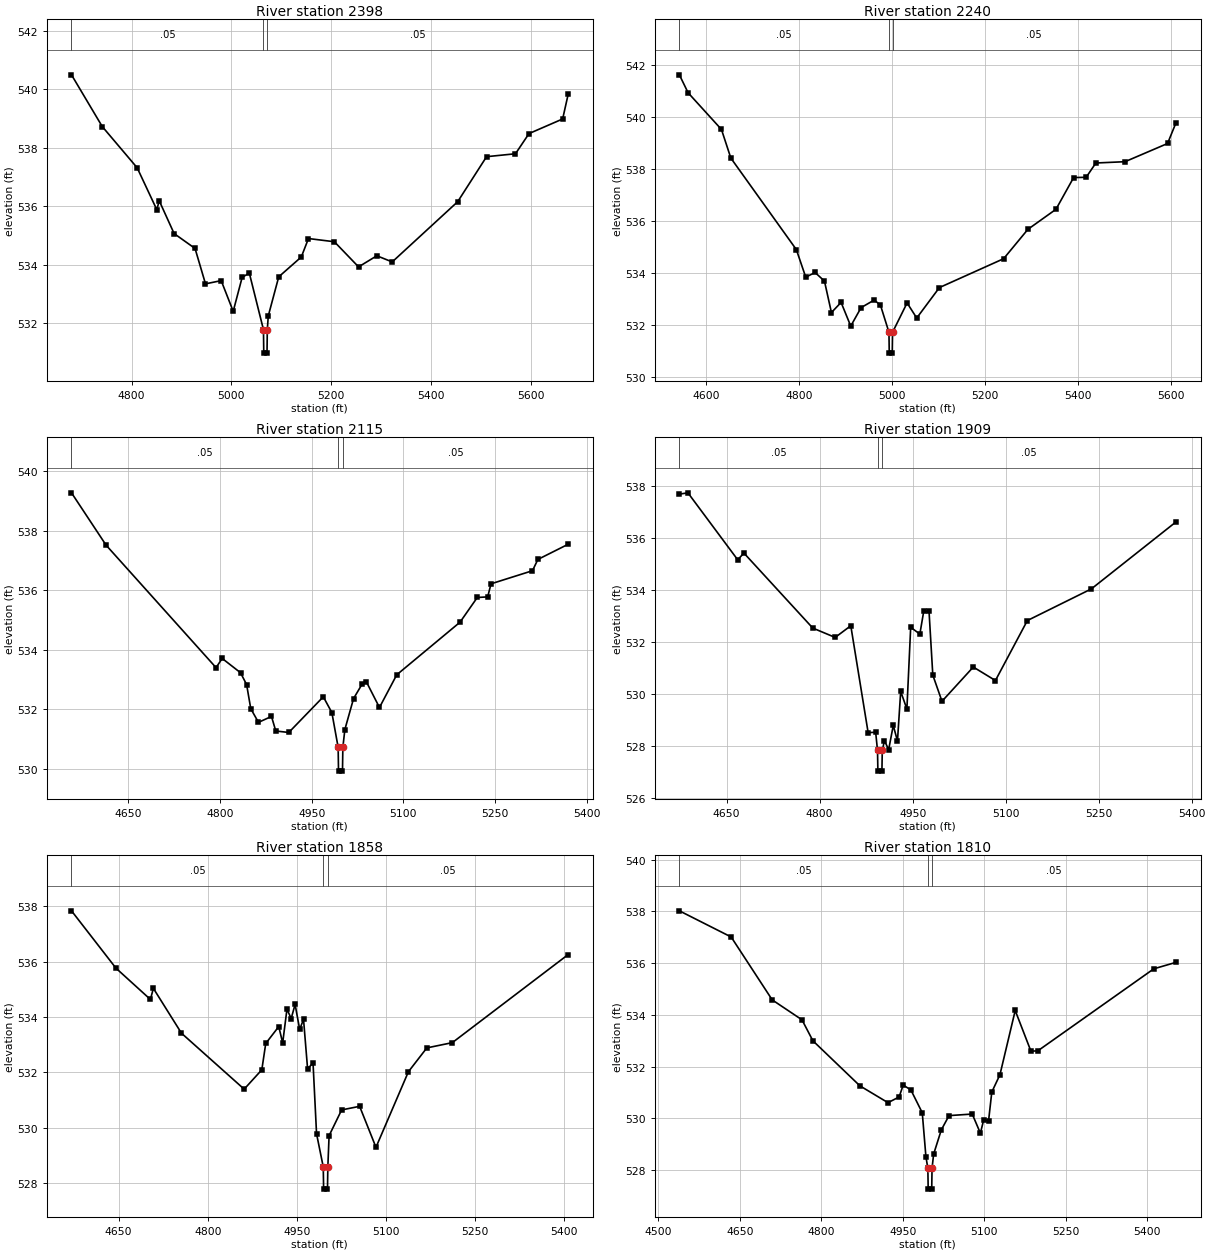
Type RM Length L Ch R = 1,2398,158,158,158
BEGIN DESCRIPTION:
Mapping XS 78e4f282
END DESCRIPTION:
XS GIS Cut Line= 4
      2031886.65     13528105.33      2031686.98     13528099.25
      2031608.85     13528345.78      2031326.73     13528803.44
#Sta/Elev= 30
  4679.3  540.49  4741.0  538.72  4811.0  537.31  4850.3  535.88  4855.3  536.18
  4885.1  535.06  4927.1  534.55  4948.0  533.34  4979.5  533.45  5003.6  532.40
  5021.5  533.56  5035.9  533.71  5064.3  531.77  5064.9  530.97  5071.4  530.97
  5072.0  531.77  5073.9  532.24  5094.9  533.58  5140.2  534.26  5154.5  534.89
  5206.5  534.78  5255.0  533.92  5291.6  534.30  5322.5  534.09  5453.8  536.15
  5511.7  537.69  5569.7  537.79  5596.8  538.48  5664.3  538.98  5675.3  539.82
#Mann=3,-1,0
  4679.3    0.05       0  5064.3    0.03       0  5072.0    0.05       0
Bank Sta=5064.3,5072
Exp/Cntr=0.3,0.1

Type RM Length L Ch R = 1,2240,125,125,125
BEGIN DESCRIPTION:
Mapping XS c9c78cbe
END DESCRIPTION:
XS GIS Cut Line= 4
      2031904.91     13528047.16      2031588.89     13528087.10
      2031432.64     13528277.21      2031285.48     13528760.07
#Sta/Elev= 30
  4542.4  541.62  4561.2  540.93  4633.0  539.52  4653.2  538.42  4794.3  534.90
  4814.5  533.84  4834.6  534.02  4854.8  533.69  4869.8  532.48  4890.6  532.87
  4911.4  531.96  4933.7  532.67  4961.8  532.96  4975.3  532.77  4993.7  531.72
  4994.3  530.92  5000.8  530.92  5001.4  531.72  5032.7  532.85  5053.5  532.27
  5102.3  533.44  5240.6  534.55  5292.9  535.68  5353.3  536.45  5391.3  537.67
  5418.3  537.68  5439.2  538.23  5502.0  538.28  5593.6  538.98  5611.8  539.78
#Mann=3,-1,0
  4542.4    0.05       0  4993.7    0.03       0  5001.4    0.05       0
Bank Sta=4993.7,5001.4
Exp/Cntr=0.3,0.1

Type RM Length L Ch R = 1,2115,206,206,206
BEGIN DESCRIPTION:
Mapping XS 40508798
END DESCRIPTION:
XS GIS Cut Line= 4
      2031801.60     13528022.00      2031506.42     13528021.13
      2031325.87     13528206.89      2031213.02     13528439.54
#Sta/Elev= 30
  4557.0  539.28  4613.6  537.52  4793.6  533.40  4803.6  533.71  4833.6  533.23
  4843.6  532.83  4850.4  532.02  4863.0  531.56  4884.3  531.76  4891.3  531.27
  4912.6  531.22  4969.1  532.42  4983.1  531.89  4993.4  530.72  4994.0  529.92
  5000.5  529.92  5001.1  530.72  5004.4  531.32  5018.6  532.36  5032.7  532.85
  5039.7  532.92  5061.0  532.06  5089.3  533.16  5192.9  534.93  5221.1  535.76
  5238.1  535.78  5243.6  536.22  5311.4  536.66  5320.3  537.04  5369.8  537.55
#Mann=3,-1,0
  4557.0    0.05       0  4993.4    0.03       0  5001.1    0.05       0
Bank Sta=4993.4,5001.1
Exp/Cntr=0.3,0.1

Type RM Length L Ch R = 1,1909,51,51,51
BEGIN DESCRIPTION:
Mapping XS 67f40c12
END DESCRIPTION:
XS GIS Cut Line= 6
      2031688.71     13527870.09      2031515.97     13527854.46
      2031387.50     13527880.50      2031347.57     13527916.96
      2031241.67     13528067.14      2031155.19     13528311.00
#Sta/Elev= 30
  4573.7  537.70  4587.5  537.75  4667.8  535.17  4677.8  535.43  4788.9  532.54
  4825.0  532.18  4850.2  532.63  4878.2  528.51  4890.3  528.53  4893.3  527.83
  4893.9  527.03  4900.4  527.03  4901.0  527.83  4904.5  528.20  4911.3  527.86
  4918.7  528.79  4925.5  528.19  4930.7  530.10  4940.7  529.42  4946.8  532.57
  4961.6  532.31  4967.8  533.18  4976.4  533.19  4982.5  530.73  4997.3  529.72
  5047.8  531.04  5083.5  530.52  5135.0  532.83  5238.3  534.05  5374.8  536.63
#Mann=3,-1,0
  4573.7    0.05       0  4893.3    0.03       0  4901.0    0.05       0
Bank Sta=4893.3,4901
Exp/Cntr=0.3,0.1

Type RM Length L Ch R = 1,1858,48,48,48
BEGIN DESCRIPTION:
Mapping XS d058f7eb
END DESCRIPTION:
XS GIS Cut Line= 5
      2031689.58     13527850.12      2031399.65     13527828.42
      2031317.19     13527898.73      2031262.50     13527982.93
      2031142.71     13528297.16
#Sta/Elev= 30
  4570.8  537.83  4645.6  535.76  4703.6  534.63  4708.6  535.03  4755.9  533.41
  4861.4  531.39  4891.1  532.09  4897.7  533.04  4919.6  533.65  4926.2  533.06
  4933.4  534.28  4940.5  533.94  4947.1  534.45  4954.8  533.55  4961.3  533.91
  4968.1  532.13  4977.3  532.33  4983.2  529.78  4994.5  528.58  4995.1  527.78
  5001.6  527.78  5002.2  528.58  5004.3  529.71  5025.4  530.64  5055.7  530.77
  5083.2  529.29  5137.8  532.02  5168.8  532.88  5211.7  533.07  5406.6  536.25
#Mann=3,-1,0
  4570.8    0.05       0  4994.5    0.03       0  5002.2    0.05       0
Bank Sta=4994.5,5002.2
Exp/Cntr=0.3,0.1

Type RM Length L Ch R = 1,1810,275,275,275
BEGIN DESCRIPTION:
Mapping XS 1905c89c
END DESCRIPTION:
XS GIS Cut Line= 6
      2031719.96     13527824.08      2031393.58     13527797.17
      2031330.21     13527837.10      2031244.27     13527932.59
      2031172.22     13528039.36      2031108.85     13528285.89
#Sta/Elev= 30
  4538.7  538.02  4634.0  537.01  4709.6  534.58  4764.4  533.81  4784.5  533.00
  4871.0  531.26  4922.7  530.61  4943.2  530.83  4950.7  531.29  4964.9  531.10
  4985.8  530.22  4992.5  528.53  4996.1  528.07  4996.7  527.27  5003.2  527.27
  5003.8  528.07  5006.7  528.62  5020.9  529.56  5035.1  530.11  5077.8  530.17
  5092.8  529.43  5098.8  529.94  5107.8  529.90  5113.8  531.02  5128.8  531.69
  5156.9  534.17  5185.8  532.60  5198.4  532.61  5412.0  535.78  5452.9  536.03
#Mann=3,-1,0
  4538.7    0.05       0  4996.1    0.03       0  5003.8    0.05       0
Bank Sta=4996.1,5003.8
Exp/Cntr=0.3,0.1

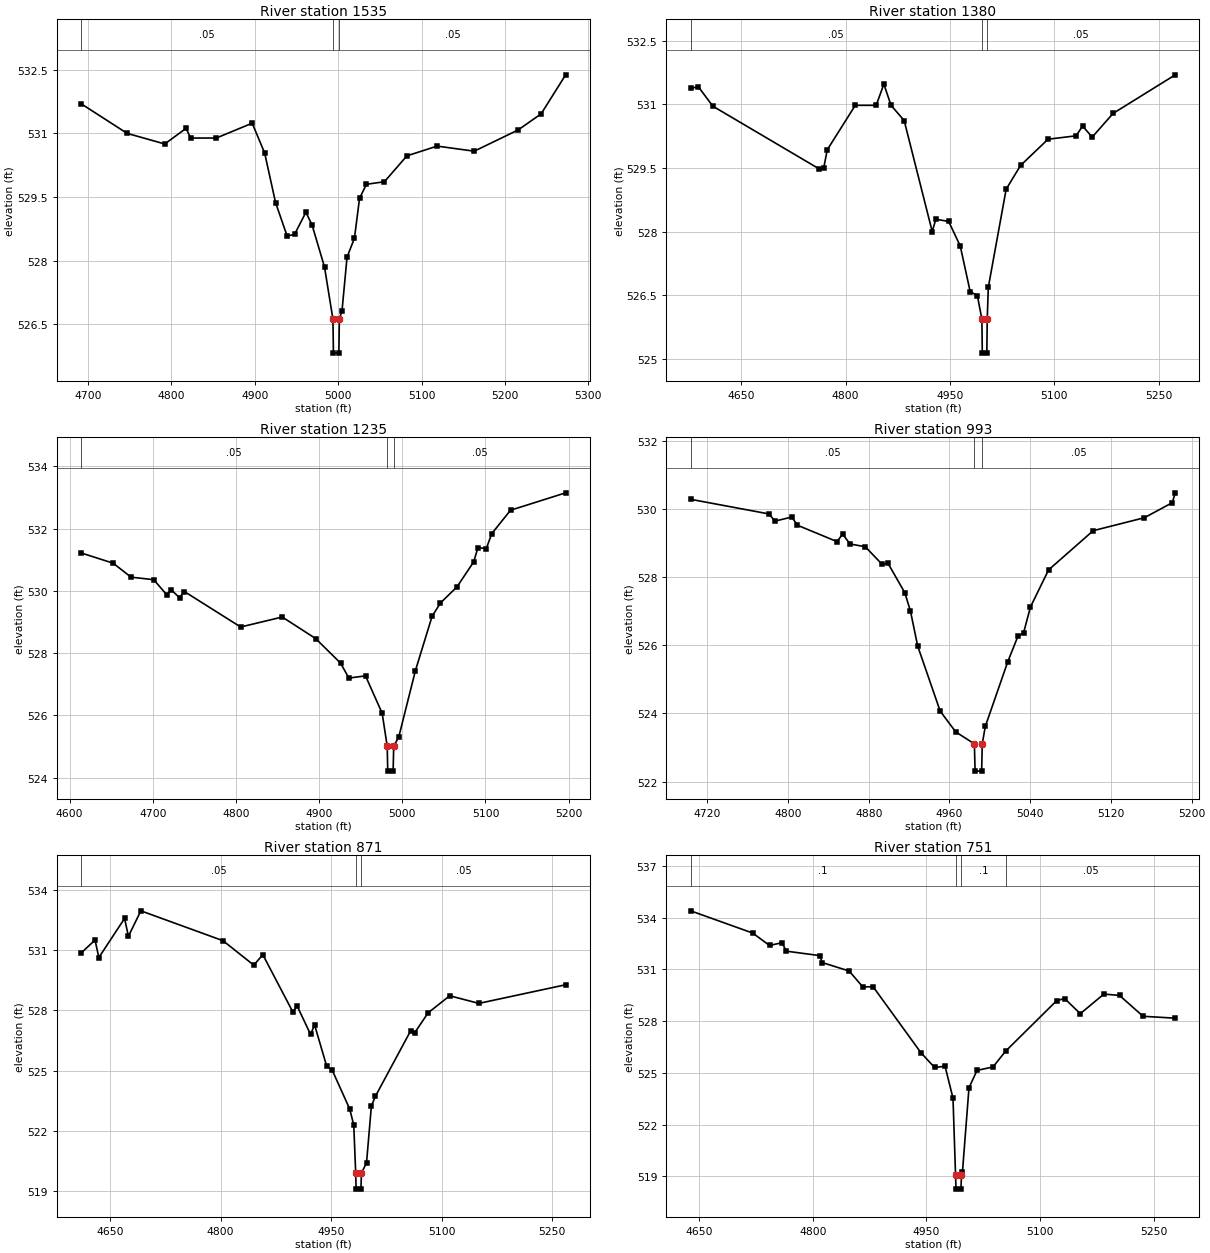
Type RM Length L Ch R = 1,1535,155,155,155
BEGIN DESCRIPTION:
Mapping XS ca513097
END DESCRIPTION:
XS GIS Cut Line= 4
      2031377.11     13527682.60      2031219.96     13527627.03
      2030965.62     13527800.64      2030915.29     13527894.36
#Sta/Elev= 30
  4691.8  531.70  4747.1  531.00  4792.2  530.75  4817.8  531.12  4823.1  530.89
  4854.0  530.89  4897.0  531.24  4911.9  530.54  4925.0  529.37  4938.9  528.58
  4947.8  528.62  4961.4  529.14  4968.8  528.84  4983.7  527.85  4993.8  526.62
  4994.4  525.82  5000.9  525.82  5001.5  526.62  5004.7  526.82  5010.7  528.08
  5019.6  528.53  5025.7  529.47  5034.0  529.80  5055.5  529.86  5082.5  530.47
  5118.7  530.70  5163.2  530.58  5215.8  531.08  5243.4  531.46  5272.8  532.38
#Mann=3,-1,0
  4691.8    0.05       0  4993.8    0.03       0  5001.5    0.05       0
Bank Sta=4993.8,5001.5
Exp/Cntr=0.3,0.1

Type RM Length L Ch R = 1,1380,145,145,145
BEGIN DESCRIPTION:
Mapping XS 13cddf93
END DESCRIPTION:
XS GIS Cut Line= 4
      2031369.25     13527646.12      2031236.46     13527552.38
      2030893.58     13527642.66      2030819.92     13527806.44
#Sta/Elev= 30
  4577.3  531.38  4588.3  531.42  4609.2  530.96  4762.0  529.48  4768.5  529.49
  4773.7  529.93  4814.0  530.98  4844.0  530.98  4855.1  531.48  4865.4  530.98
  4884.3  530.62  4924.6  528.00  4929.8  528.29  4948.2  528.24  4964.9  527.66
  4979.2  526.58  4989.5  526.49  4996.0  525.93  4996.6  525.13  5003.1  525.13
  5003.7  525.93  5005.2  526.68  5030.9  529.00  5051.6  529.56  5091.1  530.18
  5131.4  530.26  5140.8  530.49  5154.6  530.23  5184.7  530.79  5274.0  531.70
#Mann=3,-1,0
  4577.3    0.05       0  4996.0    0.03       0  5003.7    0.05       0
Bank Sta=4996,5003.7
Exp/Cntr=0.3,0.1

Type RM Length L Ch R = 1,1235,242,242,242
BEGIN DESCRIPTION:
Mapping XS d7f2c8b8
END DESCRIPTION:
XS GIS Cut Line= 4
      2031338.02     13527553.25      2031226.04     13527485.54
      2030879.69     13527475.99      2030785.89     13527523.75
#Sta/Elev= 30
  4613.8  531.22  4652.4  530.89  4674.0  530.44  4701.2  530.36  4716.7  529.88
  4722.5  530.03  4732.2  529.78  4738.0  529.98  4805.7  528.84  4855.7  529.16
  4895.8  528.47  4925.8  527.68  4935.8  527.20  4955.8  527.27  4975.8  526.07
  4981.9  525.01  4982.5  524.21  4989.0  524.21  4989.7  525.01  4995.8  525.31
  5015.8  527.44  5035.8  529.18  5045.8  529.61  5065.8  530.13  5085.8  530.93
  5091.0  531.39  5101.0  531.36  5107.6  531.84  5130.1  532.59  5196.4  533.15
#Mann=3,-1,0
  4613.8    0.05       0  4981.9    0.03       0  4989.7    0.05       0
Bank Sta=4981.9,4989.7
Exp/Cntr=0.3,0.1

Type RM Length L Ch R = 1,993,122,122,122
BEGIN DESCRIPTION:
Mapping XS 07ae6376
END DESCRIPTION:
XS GIS Cut Line= 4
      2031263.37     13527441.24      2031269.44     13527377.90
      2031010.76     13527249.43      2030884.81     13527270.13
#Sta/Elev= 30
  4703.6  530.28  4781.4  529.85  4787.0  529.64  4803.8  529.76  4809.4  529.52
  4848.6  529.04  4854.2  529.26  4861.5  528.97  4876.6  528.89  4893.4  528.37
  4899.0  528.41  4915.8  527.54  4921.4  527.00  4928.5  525.98  4950.8  524.07
  4966.2  523.46  4984.7  523.11  4985.4  522.31  4991.9  522.31  4992.5  523.11
  4995.5  523.62  5017.8  525.52  5027.9  526.27  5033.4  526.36  5040.2  527.12
  5058.2  528.21  5102.4  529.36  5153.1  529.74  5180.7  530.18  5183.7  530.47
#Mann=3,-1,0
  4703.6    0.05       0  4984.7    0.03       0  4992.5    0.05       0
Bank Sta=4984.7,4992.5
Exp/Cntr=0.3,0.1

Type RM Length L Ch R = 1,871,120,120,120
BEGIN DESCRIPTION:
Mapping XS 5075e288
END DESCRIPTION:
XS GIS Cut Line= 4
      2031376.21     13527433.44      2031331.08     13527264.18
      2031016.84     13527133.98      2030880.53     13527174.78
#Sta/Elev= 30
  4610.6  530.86  4629.6  531.51  4634.8  530.64  4669.7  532.59  4674.9  531.70
  4691.8  532.97  4803.2  531.48  4845.0  530.26  4857.3  530.78  4898.2  527.91
  4903.6  528.24  4922.1  526.80  4927.5  527.28  4943.9  525.22  4951.4  525.02
  4975.3  523.07  4980.7  522.27  4983.3  519.88  4983.9  519.08  4990.4  519.08
  4991.1  519.88  4998.0  520.39  5004.6  523.23  5010.0  523.71  5057.7  526.97
  5063.1  526.87  5081.6  527.88  5110.9  528.73  5150.4  528.35  5268.2  529.28
#Mann=3,-1,0
  4610.6    0.05       0  4983.3    0.03       0  4991.1    0.05       0
Bank Sta=4983.3,4991.1
Exp/Cntr=0.3,0.1

Type RM Length L Ch R = 1,751,157,157,157
BEGIN DESCRIPTION:
Mapping XS 92dc169a
END DESCRIPTION:
XS GIS Cut Line= 4
      2031502.99     13527217.33      2031347.57     13527137.45
      2031065.45     13527042.83      2030904.00     13527086.23
#Sta/Elev= 30
  4638.8  534.40  4720.7  533.11  4742.9  532.39  4759.4  532.55  4765.0  532.06
  4809.4  531.80  4812.2  531.40  4847.9  530.91  4866.1  529.98  4879.5  530.00
  4942.8  526.16  4960.7  525.31  4974.5  525.38  4985.0  523.53  4988.4  519.05
  4989.0  518.25  4995.5  518.25  4996.2  519.05  4997.5  519.25  5006.1  524.13
  5016.7  525.14  5037.8  525.34  5054.3  526.25  5121.9  529.19  5132.3  529.31
  5153.0  528.43  5184.1  529.57  5204.8  529.49  5235.8  528.28  5278.3  528.17
#Mann=4,-1,0
  4638.8     0.1       0  4988.4    0.07       0  4996.2     0.1       0
  5054.3    0.05       0
Bank Sta=4988.4,4996.2
Exp/Cntr=0.3,0.1

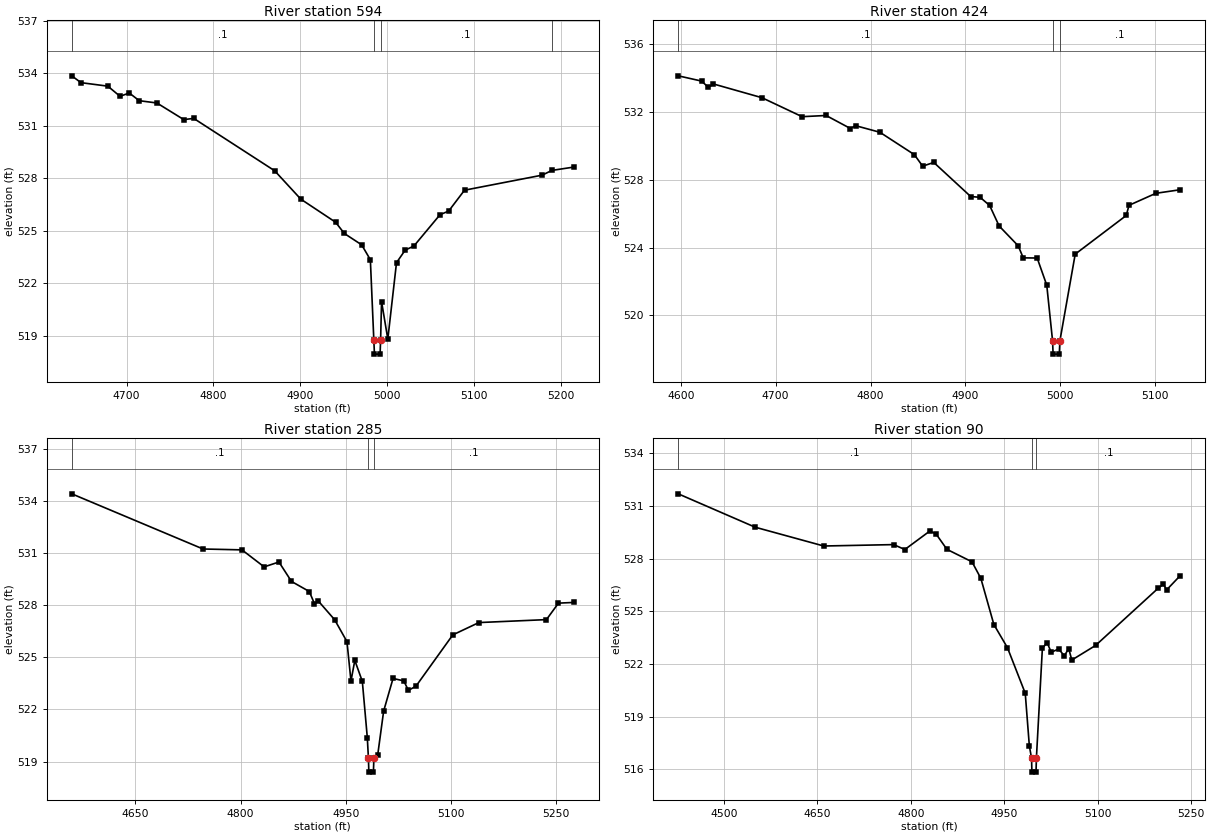
Type RM Length L Ch R = 1,594,170,170,170
BEGIN DESCRIPTION:
Mapping XS 8898d388
END DESCRIPTION:
XS GIS Cut Line= 4
      2031557.43     13527014.40      2031372.96     13526949.30
      2031113.63     13526934.11      2031010.24     13527000.19
#Sta/Elev= 30
  4636.9  533.85  4647.5  533.46  4678.4  533.26  4692.5  532.68  4703.1  532.87
  4714.6  532.43  4734.9  532.30  4765.9  531.35  4777.3  531.42  4870.5  528.43
  4900.6  526.81  4940.7  525.49  4950.7  524.85  4970.7  524.20  4980.7  523.35
  4984.7  518.76  4985.4  517.96  4991.9  517.96  4992.5  518.76  4993.6  520.96
  5000.8  518.82  5010.8  523.18  5020.8  523.90  5030.8  524.13  5060.9  525.92
  5070.9  526.13  5089.1  527.32  5178.6  528.18  5189.7  528.45  5215.0  528.64
#Mann=4,-1,0
  4636.9     0.1       0  4984.7    0.07       0  4992.5     0.1       0
  5189.7    0.05       0
Bank Sta=4984.7,4992.5
Exp/Cntr=0.3,0.1

Type RM Length L Ch R = 1,424,139,139,139
BEGIN DESCRIPTION:
Mapping XS 2fdaa790
END DESCRIPTION:
XS GIS Cut Line= 4
      2031618.21     13526871.18      2031367.53     13526783.28
      2031161.37     13526797.39      2031119.00     13526835.53
#Sta/Elev= 30
  4597.3  534.13  4621.9  533.82  4629.1  533.45  4634.4  533.65  4685.5  532.84
  4727.9  531.72  4753.2  531.79  4778.9  531.02  4784.2  531.19  4809.9  530.80
  4846.2  529.48  4855.0  528.80  4866.7  529.02  4905.6  527.01  4915.6  526.96
  4925.6  526.48  4935.6  525.27  4955.7  524.10  4961.0  523.39  4975.7  523.38
  4985.8  521.78  4991.9  518.51  4992.5  517.71  4999.0  517.71  4999.7  518.51
  5015.8  523.61  5069.6  525.89  5072.5  526.49  5100.9  527.20  5126.6  527.41
#Mann=3,-1,0
  4597.3     0.1       0  4991.9    0.07       0  4999.7     0.1       0
Bank Sta=4991.9,4999.7
Exp/Cntr=0.3,0.1

Type RM Length L Ch R = 1,285,195,195,195
BEGIN DESCRIPTION:
Mapping XS f4b035d9
END DESCRIPTION:
XS GIS Cut Line= 4
      2031655.09     13526720.35      2031338.24     13526614.01
      2031127.73     13526707.33      2031062.63     13526844.04
#Sta/Elev= 30
  4559.2  534.43  4746.4  531.25  4801.9  531.20  4833.5  530.22  4854.6  530.50
  4872.5  529.38  4897.9  528.80  4905.3  528.09  4910.8  528.25  4934.1  527.17
  4951.6  525.91  4957.3  523.64  4962.8  524.83  4973.5  523.62  4980.6  520.38
  4982.2  519.19  4982.8  518.39  4989.3  518.39  4990.0  519.19  4995.4  519.37
  5003.9  521.91  5017.3  523.79  5032.6  523.65  5039.2  523.10  5050.1  523.35
  5102.5  526.30  5139.7  527.01  5236.0  527.18  5253.2  528.13  5275.1  528.17
#Mann=3,-1,0
  4559.2     0.1       0  4982.2    0.07       0  4990.0     0.1       0
Bank Sta=4982.2,4990
Exp/Cntr=0.3,0.1

Type RM Length L Ch R = 1,90,0,0,0
BEGIN DESCRIPTION:
EAST FORK ELLIS Br 1.0
END DESCRIPTION:
XS GIS Cut Line= 4
      2031658.33     13526392.66      2031224.96     13526401.95
      2031111.46     13526531.55      2031098.48     13526730.58
#Sta/Elev= 30
  4427.1  531.69  4550.5  529.79  4660.5  528.72  4772.6  528.80  4790.5  528.52
  4830.5  529.57  4840.5  529.41  4858.0  528.53  4898.2  527.82  4912.4  526.88
  4933.3  524.25  4955.1  522.93  4983.6  520.34  4990.2  517.34  4993.7  516.65
  4994.3  515.85  5000.9  515.85  5001.5  516.65  5011.1  522.90  5018.7  523.22
  5025.3  522.67  5037.1  522.86  5046.3  522.47  5053.3  522.88  5058.3  522.23
  5096.4  523.06  5196.6  526.31  5205.3  526.55  5210.3  526.22  5232.3  527.04
#Mann=3,-1,0
  4427.1     0.1       0  4993.7    0.07       0  5001.5     0.1       0
Bank Sta=4993.7,5001.5
Exp/Cntr=0.3,0.1

Chan Stop Cuts=-1