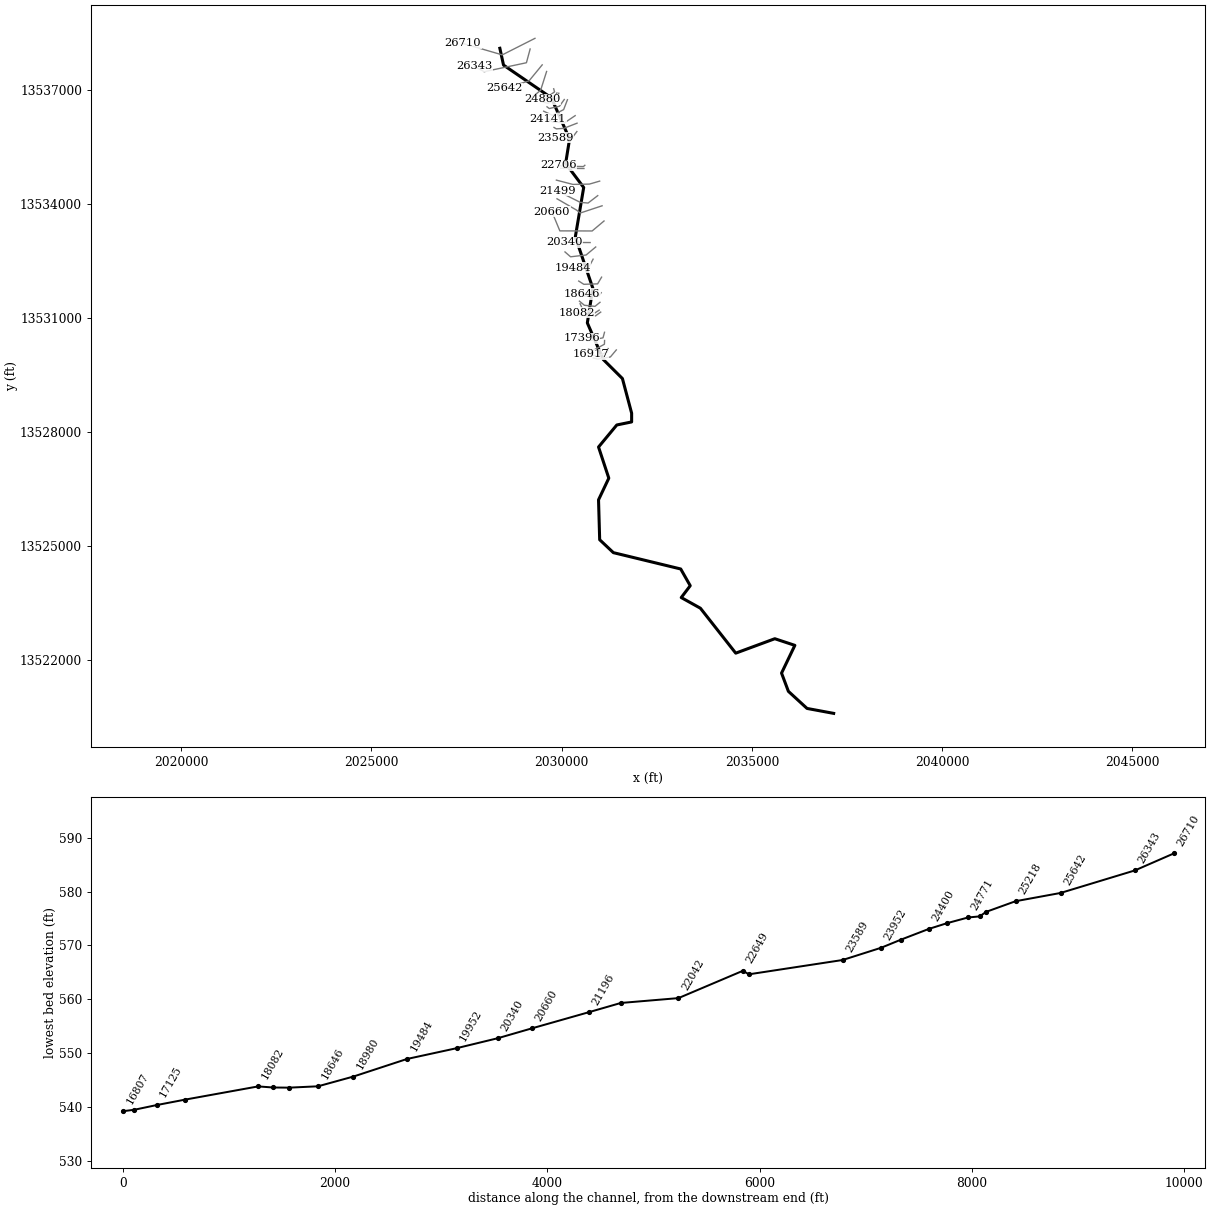
--- ELLIS Br.prj (project) ---

Proj Title=ELLIS Br Base Level Engineering
Current Plan=p01
Default Exp/Contr=0.3,0.1
English Units
Geom File=g01
Flow File=f01
Plan File=p01
Y Axis Title=Elevation
X Axis Title(PF)=Main Channel Distance
X Axis Title(XS)=Station
BEGIN DESCRIPTION:
ELLIS Br
END DESCRIPTION:
DSS Export Rating Curves= 0
DSS Export Rating Curve Sorted= 0
DSS Export Volume Flow Curves= 0
DXF OffsetX= 0
DXF OffsetY= 0
DXF ScaleX= 1
DXF ScaleY= 10

--- ELLIS Br.p01 (plan) ---

Plan Title=Multiple Run
Short Identifier=Multiple
Geom File=g01
Flow File=f01
Subcritical Flow
K Sum by GR= 0
Std Step Tol= 0.01
Critical Tol= 0.01
Num of Std Step Trials= 20
Max Error Tol= 0.3
Flow Tol Ratio= 0.001
Split Flow NTrial= 30
Split Flow Tol= 0.02
Split Flow Ratio= 0.02
Log Output Level= 0
Friction Slope Method= 1
Unsteady Friction Slope Method= 2
Unsteady Bridges Friction Slope Method= 1
Parabolic Critical Depth
Global Vel Dist=  1 , 1 , 1
Global Log Level= 0
CheckData=True
Encroach Param= -1, 0, 0, 0
BEGIN DESCRIPTION:
Multiple Run
END DESCRIPTION:

--- ELLIS Br.f01 (steady flow) ---

Flow Title=Multiple
Number of Profiles=7
Profile Names=10-year,25-year,50-year,1pct_min,100-year,1pct_plu,500-year
River Rch & RM= ELLIS Br,Reach-1,26710
     175     237     287     174     347     692     513
River Rch & RM= ELLIS Br,Reach-1,24941
     287     399     492     303     604    1204     922
River Rch & RM= ELLIS Br,Reach-1,19952
     322     449     555     342     683    1362    1047
River Rch & RM= ELLIS Br,Reach-1,15375
     353     495     614     379     756    1509    1165
River Rch & RM= ELLIS Br,Reach-1,12168
     583     833    1047     654    1305    2603    2057
River Rch & RM= ELLIS Br,Reach-1,3186
     678     974    1228     769    1535    3062    2435
Boundary for River Rch & Prof#=ELLIS Br,Reach-1,1
Up Type=0
Dn Type=3
Dn Slope=0.005
Boundary for River Rch & Prof#=ELLIS Br,Reach-1,2
Up Type=0
Dn Type=3
Dn Slope=0.005
Boundary for River Rch & Prof#=ELLIS Br,Reach-1,3
Up Type=0
Dn Type=3
Dn Slope=0.005
Boundary for River Rch & Prof#=ELLIS Br,Reach-1,4
Up Type=0
Dn Type=3
Dn Slope=0.005
Boundary for River Rch & Prof#=ELLIS Br,Reach-1,5
Up Type=0
Dn Type=3
Dn Slope=0.005
Boundary for River Rch & Prof#=ELLIS Br,Reach-1,6
Up Type=0
Dn Type=3
Dn Slope=0.005
Boundary for River Rch & Prof#=ELLIS Br,Reach-1,7
Up Type=0
Dn Type=3
Dn Slope=0.005

--- ELLIS Br.g01 (geometry) ---

Geom Title=Existing Conditions
Program Version=5.05

River Reach=ELLIS Br        ,Reach-1
Reach XY= 30
      2028377.32     13538088.34      2028473.85     13537645.98
       2029730.1     13536785.56      2030209.57     13535699.22
      2030106.18     13535057.73       2030580.8     13534424.54
       2030360.8     13533124.54       2030820.8     13531774.54
      2030676.49     13530860.33      2031095.24     13529897.83
      2031598.53     13529396.31       2031840.8     13528484.54
       2031840.8     13528254.54       2031450.8     13528174.54
       2030970.8     13527594.54       2031240.8     13526774.54
       2030970.8     13526204.54       2031000.8     13525154.54
       2031360.8     13524814.54       2033130.8     13524384.54
       2033380.8     13523944.54       2033144.6     13523632.71
      2033648.07     13523352.15      2034576.54     13522169.51
      2035603.63     13522549.37       2036130.8     13522374.54
       2035780.8     13521644.54       2035960.8     13521164.54
       2036450.8     13520714.54       2037150.8     13520584.54

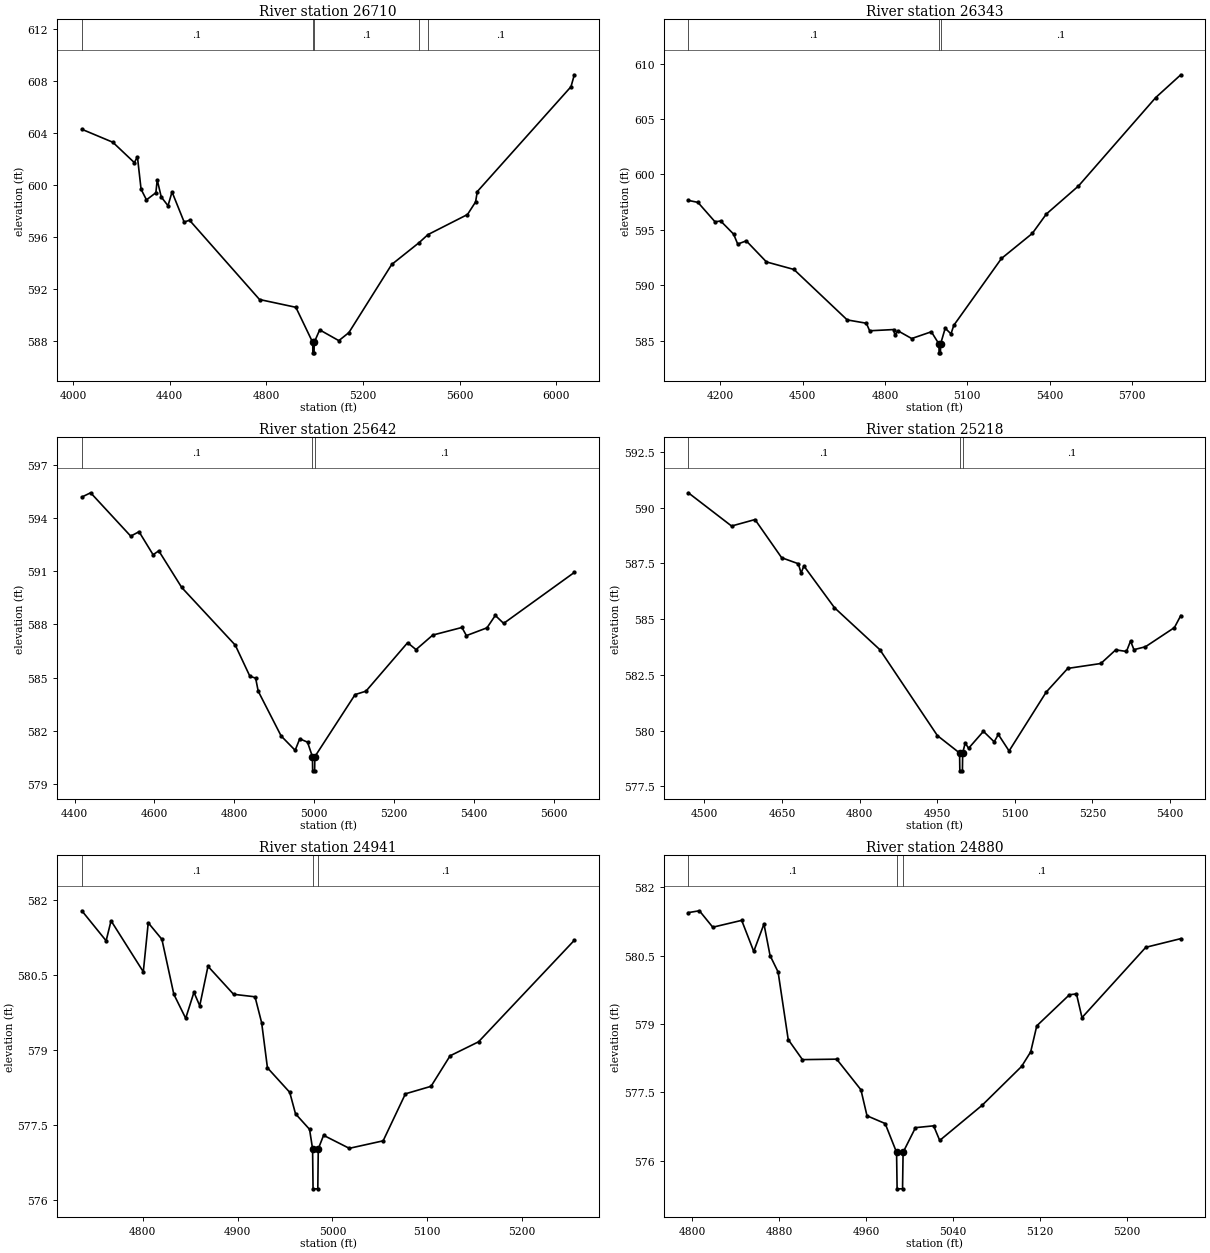
Type RM Length L Ch R = 1 ,26710   ,367,367,367
BEGIN DESCRIPTION:
EAST FORK ELLIS Br 6.0
END DESCRIPTION:
XS GIS Cut Line= 3
      2029300.04     13538350.02       2028440.8     13537914.54
      2027409.58     13538214.66
#Sta/Elev= 30
  4036.7  604.29  4164.8  603.29  4253.9  601.72  4266.6  602.17  4281.7  599.67
    4304  598.85  4342.9   599.4  4348.5  600.39  4365.2  599.07  4393.1   598.4
  4409.8  599.46  4459.9  597.14  4482.2  597.28  4771.7  591.17    4922  590.57
  4991.8  587.86  4992.3  587.06  4997.3  587.06  4997.8  587.86  5020.6  588.83
  5099.8     588  5141.4  588.62  5318.5  593.87  5431.7  595.55  5468.4  596.17
    5632  597.72  5665.5  598.69  5672.6  599.49  6060.2  607.57    6074  608.49
#Mann= 5 ,-1 , 0
  4036.7      .1       0  4991.8     .07       0  4997.8      .1       0
  5431.7     .05       0  5468.4      .1       0
Bank Sta=4991.8,4997.8
XS Rating Curve= 0 ,0
Exp/Cntr=0.3,0.1

Type RM Length L Ch R = 1 ,26343   ,701,701,701
BEGIN DESCRIPTION:
Mapping XS bb3fd42c
END DESCRIPTION:
XS GIS Cut Line= 4
        2029173.     13538068.93      2029075.79     13537707.85
      2027964.68     13537471.74      2027715.24     13537610.31
#Sta/Elev= 30
    4083  597.66  4118.1  597.48  4180.3  595.73    4201   595.8    4248  594.62
  4263.1  593.72  4294.2  594.01  4367.8  592.11    4468  591.43  4662.2  586.88
    4732  586.58    4744   585.9  4831.2  586.01  4836.3  585.48  4846.2  585.91
  4897.3   585.2  4968.9  585.81  4996.6  584.71  4997.1  583.91  5002.1  583.91
  5002.6  584.71  5019.4  586.13  5040.5  585.62  5050.7  586.39  5224.5  592.42
  5336.9  594.68  5388.1  596.43  5505.3  598.96    5787  606.94  5878.2  608.99
#Mann= 3 ,-1 , 0
    4083      .1       0  4996.6     .07       0  5002.6      .1       0
Bank Sta=4996.6,5002.6
XS Rating Curve= 0 ,0
Exp/Cntr=0.3,0.1

Type RM Length L Ch R = 1 ,25642   ,424,424,424
BEGIN DESCRIPTION:
Mapping XS ff4de2fc
END DESCRIPTION:
XS GIS Cut Line= 3
      2029490.15     13537651.57      2029143.72     13537229.99
      2028485.65     13537030.18
#Sta/Elev= 30
  4418.1   595.2  4440.1  595.44  4540.5  592.99  4561.3  593.24  4596.5  591.94
  4610.8  592.16  4668.2  590.09  4802.4  586.83    4839  585.07  4853.3  584.97
  4859.8  584.23  4917.2   581.7  4952.3  580.89  4963.8  581.54  4983.3  581.35
  4995.6  580.53  4996.1  579.73  5001.1  579.73  5001.6  580.53  5102.5  584.04
  5129.6  584.23    5234  586.97    5255  586.58  5296.9   587.4    5370  587.83
  5381.2  587.37  5432.7  587.81  5453.6  588.51  5474.5  588.06  5651.5  590.94
#Mann= 3 ,-1 , 0
  4418.1      .1       0  4995.6     .07       0  5001.6      .1       0
Bank Sta=4995.6,5001.6
XS Rating Curve= 0 ,0
Exp/Cntr=0.3,0.1

Type RM Length L Ch R = 1 ,25218   ,277,277,277
BEGIN DESCRIPTION:
Mapping XS fcf8fd17
END DESCRIPTION:
XS GIS Cut Line= 3
      2029605.85      13537477.9      2029448.72     13536982.56
      2029113.42      13536709.8
#Sta/Elev= 30
    4469  590.66  4552.6  589.17  4597.9  589.46  4649.4  587.75  4681.7  587.48
  4686.9  587.06  4692.4  587.38  4751.5  585.51  4839.2  583.63  4950.4  579.78
  4993.3     579  4993.8   578.2  4998.8   578.2  4999.3     579  5004.2  579.45
  5010.7  579.21  5039.4  579.97  5060.2   579.5  5068.2  579.83    5089  579.09
  5160.8  581.73  5202.4  582.79  5266.4  583.01  5295.1  583.62  5315.9  583.55
  5323.8  584.02  5330.3  583.63  5352.6  583.76  5408.6  584.62  5420.9  585.16
#Mann= 3 ,-1 , 0
    4469      .1       0  4993.3     .07       0  4999.3      .1       0
Bank Sta=4993.3,4999.3
XS Rating Curve= 0 ,0
Exp/Cntr=0.3,0.1

Type RM Length L Ch R = 1 ,24941   ,61,61,61
BEGIN DESCRIPTION:
Mapping XS a7dfa1f2
END DESCRIPTION:
XS GIS Cut Line= 6
      2029792.41     13537022.27      2029815.32     13536941.03
      2029574.35     13536771.58      2029438.24     13536772.28
      2029436.15     13536772.28      2029434.05     13536772.28
#Sta/Elev= 30
  4735.8  581.79  4761.4  581.19  4766.6  581.59  4800.6  580.57  4805.8  581.55
  4820.2  581.22  4832.8  580.12  4845.3  579.64    4854  580.16  4860.1  579.89
  4868.8  580.68  4895.8  580.12  4918.4  580.07  4925.4  579.55  4931.5  578.65
    4955  578.16  4961.1  577.73  4975.9  577.42  4979.1  577.03  4979.6  576.23
  4984.6  576.23  4985.1  577.03  4990.7   577.3  5017.8  577.04  5053.5  577.19
    5077  578.13    5104  578.28  5124.1  578.89  5154.1  579.17  5255.1   581.2
#Mann= 3 ,-1 , 0
  4735.8      .1       0  4979.1     .07       0  4985.1      .1       0
Bank Sta=4979.1,4985.1
XS Rating Curve= 0 ,0
Exp/Cntr=0.3,0.1

Type RM Length L Ch R = 1 ,24880   ,109,109,109
BEGIN DESCRIPTION:
Mapping XS 0fe06da3
END DESCRIPTION:
XS GIS Cut Line= 6
      2029878.53     13536913.97       2029854.9     13536870.89
      2029591.71     13536738.25      2029510.46     13536747.97
      2029508.38     13536748.67       2029483.4      13536745.2
#Sta/Elev= 30
  4796.5  581.44  4806.7  581.48    4819  581.12  4845.6  581.27  4856.7  580.59
  4866.1  581.19  4871.7   580.5  4879.1  580.14  4888.4  578.66  4901.5  578.22
    4933  578.23  4955.3  577.56  4960.9  576.99  4977.6  576.82  4988.1  576.19
  4988.6  575.39  4993.6  575.39  4994.1  576.19  5005.5  576.73  5022.2  576.77
  5027.8  576.45  5066.8  577.22  5103.1  578.07  5111.5  578.39  5117.1  578.96
  5147.1  579.64  5153.6  579.66  5158.7  579.14  5217.4  580.68  5249.6  580.87
#Mann= 3 ,-1 , 0
  4796.5      .1       0  4988.1     .07       0  4994.1      .1       0
Bank Sta=4988.1,4994.1
XS Rating Curve= 0 ,0
Exp/Cntr=0.3,0.1

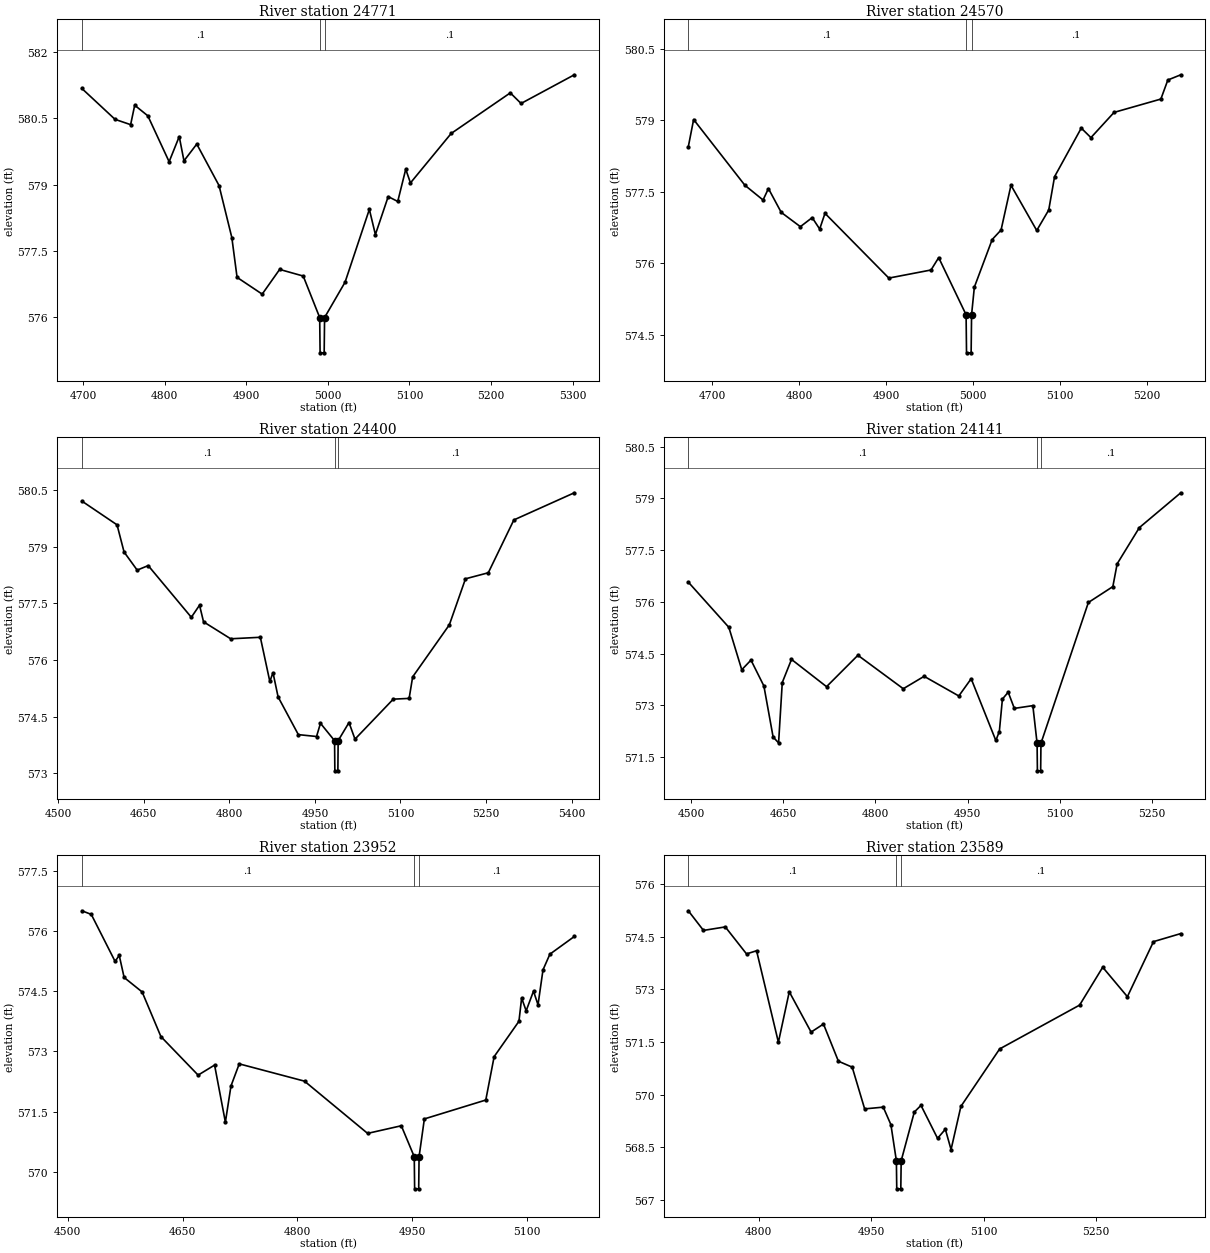
Type RM Length L Ch R = 1 ,24771   ,201,201,201
BEGIN DESCRIPTION:
Mapping XS bd02e12d
END DESCRIPTION:
XS GIS Cut Line= 4
      2029925.73     13536905.57      2029916.02     13536797.97
      2029646.57     13536640.33      2029469.08     13536687.29
#Sta/Elev= 30
  4698.3  581.18    4739  580.48  4758.1  580.36  4763.1   580.8  4779.2  580.56
  4805.3  579.52  4817.7  580.09  4823.5  579.54  4839.2  579.92  4866.5  578.98
  4882.2   577.8  4888.6   576.9  4919.4  576.52  4940.8  577.08  4969.7  576.93
  4989.9  575.99  4990.4  575.19  4995.4  575.19  4995.9  575.99    5021  576.79
  5050.8  578.44  5058.2  577.87  5073.9  578.73  5085.6  578.62  5095.4  579.35
  5101.2  579.04  5151.1  580.16  5223.6  581.08  5236.8  580.84  5302.1  581.49
#Mann= 3 ,-1 , 0
  4698.3      .1       0  4989.9     .07       0  4995.9      .1       0
Bank Sta=4989.9,4995.9
XS Rating Curve= 0 ,0
Exp/Cntr=0.3,0.1

Type RM Length L Ch R = 1 ,24570   ,170,170,170
BEGIN DESCRIPTION:
Mapping XS e072de78
END DESCRIPTION:
XS GIS Cut Line= 4
       2030070.2     13536739.66       2029943.1     13536562.56
      2029676.43     13536502.83      2029616.73     13536547.96
#Sta/Elev= 30
  4672.9  578.45    4679  579.02  4737.9  577.64  4758.8  577.33    4765  577.57
  4779.7  577.07  4801.7  576.77  4815.3  576.96  4823.9  576.72    4830  577.05
  4903.4  575.69  4951.9  575.86  4960.7  576.12  4992.2  574.92  4992.7  574.12
    4998  574.12  4998.5  574.92  5001.7   575.5  5022.2   576.5  5032.4   576.7
  5043.8  577.64  5073.4  576.69  5087.2  577.12  5093.9  577.82  5124.6  578.84
  5135.7  578.64  5162.3  579.17  5216.1  579.45  5224.1  579.85    5239  579.96
#Mann= 3 ,-1 , 0
  4672.9      .1       0  4992.2     .07       0  4998.5      .1       0
Bank Sta=4992.2,4998.5
XS Rating Curve= 0 ,0
Exp/Cntr=0.3,0.1

Type RM Length L Ch R = 1 ,24400   ,259,259,259
BEGIN DESCRIPTION:
Mapping XS 325c481d
END DESCRIPTION:
XS GIS Cut Line= 4
       2030153.5     13536734.05      2030053.52     13536474.36
      2029759.07     13536323.67      2029529.22     13536432.36
#Sta/Elev= 30
  4541.5  580.21  4603.2  579.58  4615.5  578.86  4638.5  578.38  4657.8   578.5
  4733.4  577.13  4747.8  577.45  4754.8  577.01  4802.4  576.56  4854.4   576.6
    4871  575.43  4876.6  575.66  4885.5  575.02    4921  574.02  4952.9  573.97
  4959.8  574.32  4984.5  573.86    4985  573.06  4990.3  573.06  4990.8  573.86
  5009.8  574.34  5020.3   573.9  5087.4  574.96  5115.2  574.98  5121.4  575.55
  5185.7  576.93    5214  578.15    5254  578.31  5298.8  579.71  5404.8  580.43
#Mann= 3 ,-1 , 0
  4541.5      .1       0  4984.5     .07       0  4990.8      .1       0
Bank Sta=4984.5,4990.8
XS Rating Curve= 0 ,0
Exp/Cntr=0.3,0.1

Type RM Length L Ch R = 1 ,24141   ,189,189,189
BEGIN DESCRIPTION:
Mapping XS 496b99e4
END DESCRIPTION:
XS GIS Cut Line= 4
      2030356.92     13536315.27      2030076.43     13536126.44
      2029758.38     13536152.14      2029638.93       13536232.
#Sta/Elev= 30
  4495.7  576.57  4561.6  575.26  4582.6  574.03  4597.6  574.31  4618.6  573.56
  4633.6  572.08  4642.5  571.91  4648.5  573.66  4663.5  574.33  4720.5  573.54
  4771.5  574.45  4845.3  573.48  4879.2  573.84  4935.6  573.27  4955.7  573.77
  4995.8  571.98  5001.5  572.24  5006.5  573.18  5015.9  573.38  5025.9  572.91
    5056  572.99  5062.9   571.9  5063.4   571.1  5068.7   571.1  5069.2   571.9
  5146.3  575.98  5186.1  576.44  5193.1   577.1  5229.2  578.15  5296.6  579.16
#Mann= 3 ,-1 , 0
  4495.7      .1       0  5062.9     .07       0  5069.2      .1       0
Bank Sta=5062.9,5069.2
XS Rating Curve= 0 ,0
Exp/Cntr=0.3,0.1

Type RM Length L Ch R = 1 ,23952   ,363,363,363
BEGIN DESCRIPTION:
Mapping XS 998e201c
END DESCRIPTION:
XS GIS Cut Line= 4
      2030406.43     13536117.37      2030057.68     13535981.31
      2029861.85     13535967.42      2029800.01     13536004.93
#Sta/Elev= 30
  4518.5   576.5  4530.8  576.41  4561.9  575.24  4567.3  575.39  4573.7  574.84
  4597.2  574.48  4621.7  573.37  4670.3  572.41  4691.8  572.66  4705.9  571.24
  4713.2  572.14    4724  572.69  4809.2  572.26  4891.6  570.96  4935.6  571.15
  4952.5  570.38    4953  569.58  4958.3  569.58  4958.8  570.38  4965.7  571.32
  5045.9  571.79  5056.8  572.87  5089.2  573.75  5092.7  574.33  5098.6  574.01
  5108.2   574.5  5114.1  574.16  5120.6  575.03  5129.6  575.42  5161.5  575.86
#Mann= 3 ,-1 , 0
  4518.5      .1       0  4952.5     .07       0  4958.8      .1       0
Bank Sta=4952.5,4958.8
XS Rating Curve= 0 ,0
Exp/Cntr=0.3,0.1

Type RM Length L Ch R = 1 ,23589   ,883,883,883
BEGIN DESCRIPTION:
Mapping XS 8724a25c
END DESCRIPTION:
XS GIS Cut Line= 4
      2030401.75     13535896.78      2030294.02     13535754.94
       2029983.6      13535672.3       2029839.9     13535736.17
#Sta/Elev= 30
  4706.3  575.24  4726.5  574.68  4755.6  574.78  4783.9  574.01  4797.3   574.1
  4826.4  571.49  4840.9  572.93    4870  571.78  4886.5  572.01  4906.4  570.95
  4924.8  570.78  4941.4  569.59  4966.2  569.64  4976.4  569.14  4983.7  568.11
  4984.2  567.31  4989.6  567.31  4990.1  568.11  5007.6   569.5  5016.5  569.69
  5038.6  568.75    5049  569.01  5056.6  568.43  5069.7  569.66  5121.4   571.3
    5228  572.55  5258.8  573.63  5291.7  572.79  5326.5  574.36  5362.9  574.59
#Mann= 3 ,-1 , 0
  4706.3      .1       0  4983.7     .07       0  4990.1      .1       0
Bank Sta=4983.7,4990.1
XS Rating Curve= 0 ,0
Exp/Cntr=0.3,0.1

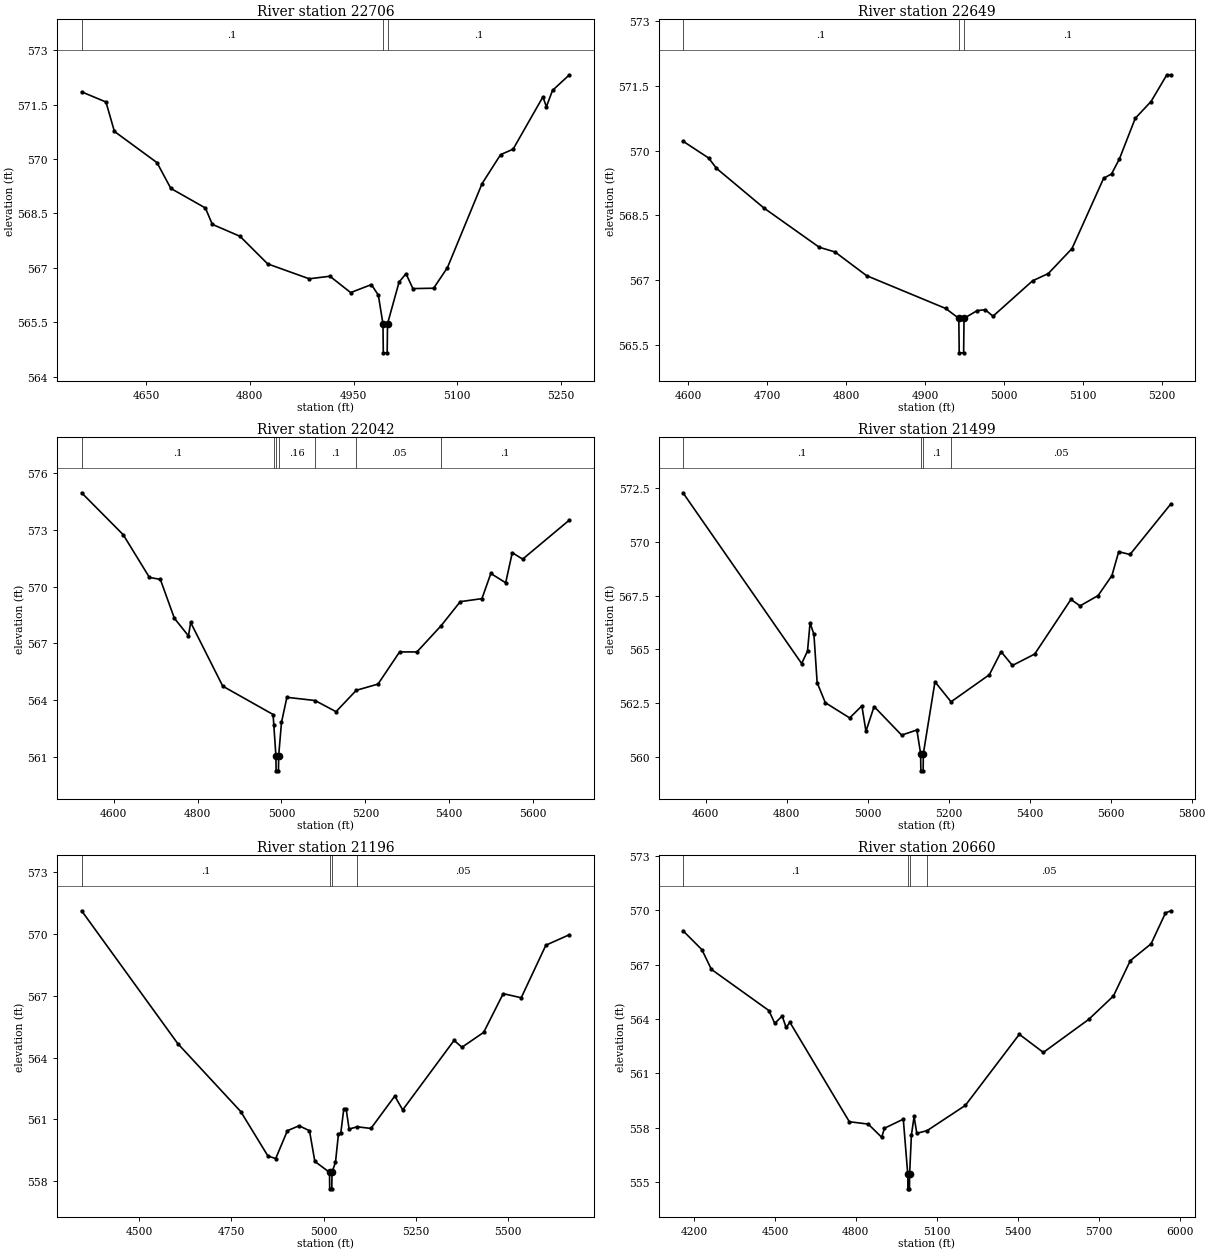
Type RM Length L Ch R = 1 ,22706   ,57,57,57
BEGIN DESCRIPTION:
Mapping XS 2e9377b7
END DESCRIPTION:
XS GIS Cut Line= 4
      2030611.17     13535009.07      2030572.97     13534975.21
      2030016.54     13534986.49      2029921.07     13535008.19
#Sta/Elev= 30
  4556.8  571.85    4592  571.57  4604.2  570.76  4665.8   569.9  4685.8  569.19
  4735.8  568.65  4745.8   568.2  4785.9  567.87  4825.9  567.11  4885.9   566.7
  4915.9  566.77  4945.9  566.32  4975.9  566.54  4985.9  566.25  4992.6  565.46
  4993.1  564.66  4998.7  564.66  4999.2  565.46  5015.9  566.61  5025.9  566.84
  5035.9  566.43  5065.9  566.44  5085.9  567.01  5135.9  569.32  5162.7  570.12
  5180.8  570.27  5223.9  571.71    5229  571.44  5237.8  571.89  5262.3  572.32
#Mann= 3 ,-1 , 0
  4556.8      .1       0  4992.6     .07       0  4999.2      .1       0
Bank Sta=4992.6,4999.2
XS Rating Curve= 0 ,0
Exp/Cntr=0.3,0.1

Type RM Length L Ch R = 1 ,22649   ,607,607,607
BEGIN DESCRIPTION:
Mapping XS f40361aa
END DESCRIPTION:
XS GIS Cut Line= 2
      2030587.39     13534924.36        2029970.     13534928.53
#Sta/Elev= 25
  4593.8  570.22  4626.2  569.83  4636.2  569.59  4696.2  568.67  4766.2  567.76
  4786.2  567.65  4826.2   567.1  4926.2  566.34  4942.9  566.11  4943.4  565.31
    4949  565.31  4949.5  566.11  4966.2  566.29  4976.2  566.31  4986.2  566.16
  5036.2  566.98  5056.2  567.15  5086.2  567.73  5126.2  569.36  5136.2  569.46
  5146.2  569.81  5166.2  570.75  5186.2  571.14  5206.2  571.76  5211.2  571.76
#Mann= 3 ,-1 , 0
  4593.8      .1       0  4942.9     .07       0  4949.5      .1       0
Bank Sta=4942.9,4949.5
XS Rating Curve= 0 ,0
Exp/Cntr=0.3,0.1

Type RM Length L Ch R = 1 ,22042   ,543,543,543
BEGIN DESCRIPTION:
Mapping XS 18abeb39
END DESCRIPTION:
XS GIS Cut Line= 4
      2031000.27     13534592.26      2030731.19     13534514.14
      2030297.16     13534505.46       2029863.1     13534618.32
#Sta/Elev= 30
  4523.7  574.96  4622.9  572.74  4685.4  570.48  4711.3  570.38  4744.8  568.32
  4778.4  567.39  4783.6   568.1  4860.1  564.73  4980.1  563.23  4981.8  562.68
  4986.8  561.05  4987.3  560.25  4992.9  560.25  4993.4  561.05  5000.1  562.81
    5013  564.14  5080.1  563.97  5130.1  563.38  5178.4  564.51  5230.2  564.84
  5281.6  566.54  5322.9  566.54  5380.7  567.93  5426.2   569.2  5477.9  569.36
  5499.1  570.69  5534.5   570.2  5550.2  571.79    5575  571.45  5686.5  573.52
#Mann= 7 ,-1 , 0
  4523.7      .1       0  4981.8     .16       0  4986.8     .07       0
  4993.4     .16       0  5080.1      .1       0  5178.4     .05       0
  5380.7      .1       0
Bank Sta=4986.8,4993.4
XS Rating Curve= 0 ,0
Exp/Cntr=0.3,0.1

Type RM Length L Ch R = 1 ,21499   ,303,303,303
BEGIN DESCRIPTION:
Mapping XS 46f26b3f
END DESCRIPTION:
XS GIS Cut Line= 4
      2030949.97     13534210.35      2030695.96     13534015.22
      2030490.23     13534033.45      2029884.63     13534337.52
#Sta/Elev= 30
    4544  572.28    4837  564.34  4851.5  564.92  4857.8  566.23  4867.3   565.7
  4875.3  563.45  4895.4  562.52  4955.6  561.81  4985.7  562.37  4995.8  561.19
  5015.9  562.34  5083.9  561.01  5121.5  561.25  5130.8  560.15  5131.3  559.35
    5137  559.35  5137.5  560.15  5166.2  563.49  5205.9  562.56  5300.5  563.82
  5329.5  564.89  5357.5  564.25  5412.4  564.78  5501.9  567.32  5524.3  567.02
    5569   567.5  5603.1  568.43  5619.9  569.54  5647.8  569.41  5748.5  571.76
#Mann= 4 ,-1 , 0
    4544      .1       0  5130.8     .07       0  5137.5      .1       0
  5205.9     .05       0
Bank Sta=5130.8,5137.5
XS Rating Curve= 0 ,0
Exp/Cntr=0.3,0.1

Type RM Length L Ch R = 1 ,21196   ,536,536,536
BEGIN DESCRIPTION:
Mapping XS 95def805
END DESCRIPTION:
XS GIS Cut Line= 4
      2031064.49     13533942.95      2030489.89     13533752.37
      2030391.97     13533830.15      2029879.74     13534127.27
#Sta/Elev= 30
  4343.9  571.12  4604.4  564.68  4775.3  561.38  4849.1  559.22  4870.1   559.1
  4901.8  560.45  4933.4  560.69  4961.7  560.45  4976.2  558.96    5016  558.43
  5016.5  557.63  5022.2  557.63  5022.7  558.43  5032.2  558.92  5040.2  560.29
  5046.6  560.34  5054.7  561.51    5061  561.51  5069.1  560.53  5091.1  560.64
  5128.3  560.56  5192.9  562.13  5214.4  561.46  5353.6  564.83  5375.1   564.5
  5433.9  565.22  5486.9   567.1  5535.7   566.9  5602.6  569.45  5666.5  569.96
#Mann= 4 ,-1 , 0
  4343.9      .1       0    5016     .07       0  5022.7      .1       0
  5091.1     .05       0
Bank Sta=5016,5022.7
XS Rating Curve= 0 ,0
Exp/Cntr=0.3,0.1

Type RM Length L Ch R = 1 ,20660   ,320,320,320
BEGIN DESCRIPTION:
Mapping XS 6346a6f2
END DESCRIPTION:
XS GIS Cut Line= 4
      2031115.54     13533543.25      2030803.04     13533280.23
      2029954.09     13533282.83      2029743.84     13533791.58
#Sta/Elev= 30
  4159.3  568.87  4229.2  567.83  4264.6  566.74  4477.6  564.47  4499.6  563.76
    4527  564.17  4541.3  563.54  4555.6  563.82  4775.8  558.34  4845.8  558.21
  4895.8  557.48  4905.8  557.98  4975.8  558.48  4992.4  555.44  4992.9  554.64
  4998.7  554.64  4999.2  555.44  5005.8  557.59  5015.8  558.63  5025.8   557.7
  5064.2  557.85  5205.8  559.24  5405.8  563.16  5494.8  562.16  5662.8  563.98
  5754.5  565.27  5817.1  567.22  5894.2  568.15  5947.5  569.85  5967.2  569.97
#Mann= 4 ,-1 , 0
  4159.3      .1       0  4992.4     .07       0  4999.2      .1       0
  5064.2     .05       0
Bank Sta=4992.4,4999.2
XS Rating Curve= 0 ,0
Exp/Cntr=0.3,0.1

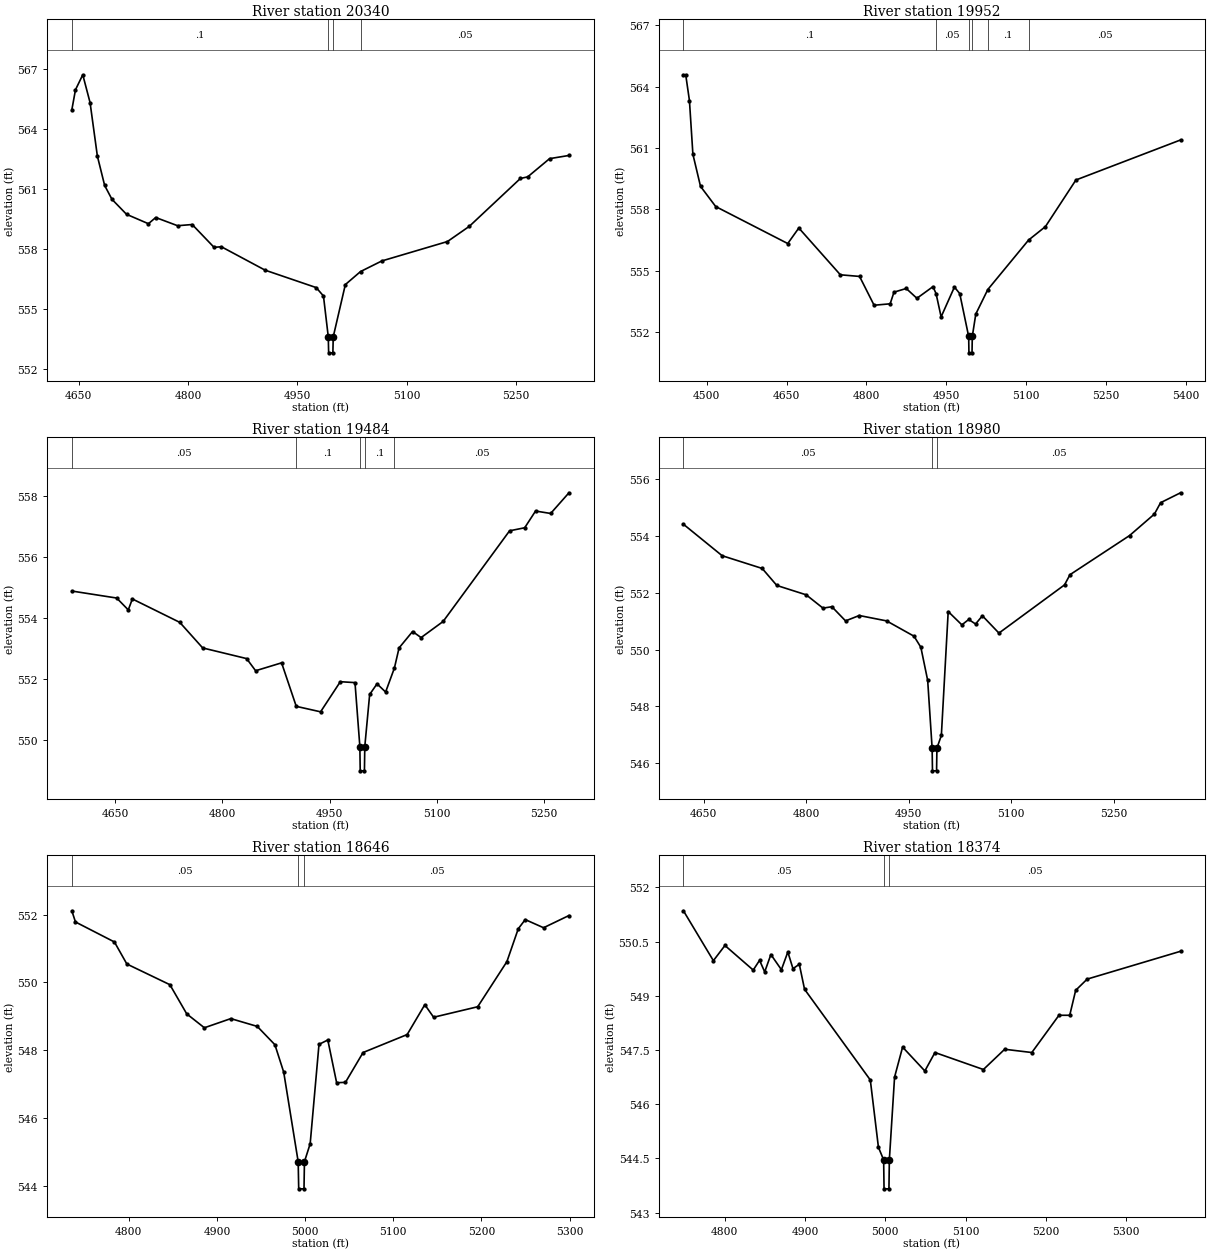
Type RM Length L Ch R = 1 ,20340   ,388,388,388
BEGIN DESCRIPTION:
Mapping XS 1cd1a42b
END DESCRIPTION:
XS GIS Cut Line= 2
      2030749.99     13532975.51       2030068.4     13532978.98
#Sta/Elev= 30
  4640.8  564.96  4645.8  565.96  4655.8  566.71  4665.8  565.32  4675.8  562.65
  4685.8  561.18  4695.8  560.49  4715.8  559.74  4745.8  559.27  4755.8  559.58
  4785.8  559.17  4805.8  559.23  4835.8  558.09  4845.8  558.12  4905.8  556.95
  4975.8  556.08  4985.8  555.66  4992.4  553.62  4992.9  552.82  4998.7  552.82
  4999.2  553.62  5015.8  556.23  5036.6  556.88  5065.8  557.41  5155.8  558.38
  5185.8  559.14  5255.8  561.53  5265.8  561.61  5295.8  562.52  5322.4  562.68
#Mann= 4 ,-1 , 0
  4640.8      .1       0  4992.4     .07       0  4999.2      .1       0
  5036.6     .05       0
Bank Sta=4992.4,4999.2
XS Rating Curve= 0 ,0
Exp/Cntr=0.3,0.1

Type RM Length L Ch R = 1 ,19952   ,468,468,468
BEGIN DESCRIPTION:
Mapping XS 5ccd867f
END DESCRIPTION:
XS GIS Cut Line= 4
      2030896.68     13532858.88      2030644.09     13532647.96
      2030236.15     13532600.51      2030089.27     13532728.38
#Sta/Elev= 30
  4456.2  564.58  4460.5  564.58  4467.5  563.32    4474  560.69  4488.3  559.12
  4516.9  558.13  4652.3  556.32  4673.1  557.08  4751.2  554.79  4787.3  554.71
  4814.6   553.3  4844.8  553.37    4852  553.94    4875  554.12  4895.1  553.64
  4925.3  554.21  4931.1  553.87  4940.6  552.73  4965.6  554.19  4975.6  553.87
  4992.4  551.77  4992.9  550.97  4998.7  550.97  4999.2  551.77  5005.8  552.87
  5028.4  554.07    5105  556.49  5136.7  557.15    5194  559.43  5390.7  561.39
#Mann= 6 ,-1 , 0
  4456.2      .1       0  4931.1     .05       0  4992.4     .03       0
  4999.2     .05       0  5028.4      .1       0    5105     .05       0
Bank Sta=4992.4,4999.2
XS Rating Curve= 0 ,0
Exp/Cntr=0.3,0.1

Type RM Length L Ch R = 1 ,19484   ,504,504,504
BEGIN DESCRIPTION:
Mapping XS 2787203e
END DESCRIPTION:
XS GIS Cut Line= 4
      2030828.16       13532538.      2030712.72     13532322.73
      2030391.54     13532248.95      2030289.99     13532314.91
#Sta/Elev= 30
  4589.6  554.88  4652.3  554.65  4668.5  554.26  4674.2  554.62  4740.5  553.85
  4772.5  553.01  4833.9  552.66  4846.5  552.26  4882.8  552.52  4903.3  551.09
  4937.3  550.91  4964.9   551.9  4985.4  551.87  4992.2  549.77  4992.7  548.97
  4998.6  548.97  4999.1  549.77  5005.9  551.48  5016.2  551.83  5028.2  551.56
  5040.5  552.35    5047  553.01  5065.9  553.55  5077.8  553.35  5108.6  553.88
  5201.5  556.86  5222.6  556.96  5237.8  557.51  5258.9  557.43  5284.5  558.11
#Mann= 5 ,-1 , 0
  4589.6     .05       0  4903.3      .1       0  4992.2     .07       0
  4999.1      .1       0  5040.5     .05       0
Bank Sta=4992.2,4999.1
XS Rating Curve= 0 ,0
Exp/Cntr=0.3,0.1

Type RM Length L Ch R = 1 ,18980   ,334,334,334
BEGIN DESCRIPTION:
Mapping XS 84e76fa5
END DESCRIPTION:
XS GIS Cut Line= 4
      2031051.02     13532064.88      2030946.87     13531888.06
      2030583.89      13531876.6      2030450.42     13531962.32
#Sta/Elev= 30
  4620.6  554.42  4677.2  553.31  4735.8  552.86  4757.2  552.26  4800.1  551.93
  4824.7  551.46  4837.7  551.51  4857.7  551.01  4877.7   551.2  4917.7  551.01
  4957.8  550.47  4967.8  550.08  4977.8  548.91  4984.3  546.52  4984.8  545.72
  4990.8  545.72  4991.3  546.52  4997.8  546.97  5007.8  551.34  5027.8  550.87
  5037.8  551.06  5047.8   550.9  5057.8  551.19    5082  550.58  5177.9  552.28
  5185.9  552.64    5273  554.02  5309.4  554.78  5318.4  555.18  5347.6  555.53
#Mann= 3 ,-1 , 0
  4620.6     .05       0  4984.3     .03       0  4991.3     .05       0
Bank Sta=4984.3,4991.3
XS Rating Curve= 0 ,0
Exp/Cntr=0.3,0.1

Type RM Length L Ch R = 1 ,18646   ,272,272,272
BEGIN DESCRIPTION:
Mapping XS e2ff70ca
END DESCRIPTION:
XS GIS Cut Line= 4
       2031040.7      13531655.7      2030978.21     13531568.74
      2030605.82     13531567.18      2030540.33     13531620.29
#Sta/Elev= 30
  4735.5  552.11  4739.6  551.78  4783.8  551.19  4797.9  550.54  4846.7  549.93
  4865.8  549.07  4885.8  548.66  4915.8  548.93  4945.8   548.7  4965.8  548.16
  4975.8  547.35  4992.2  544.71  4992.8  543.91  4998.8  543.91  4999.3  544.71
  5005.8  545.24  5015.8  548.17  5025.8   548.3  5035.8  547.04  5045.8  547.05
  5065.8  547.93  5115.8  548.46  5135.8  549.34  5145.8  548.97  5195.8  549.28
  5228.9  550.61  5241.8  551.58  5249.7  551.85  5270.5  551.61  5299.3  551.97
#Mann= 3 ,-1 , 0
  4735.5     .05       0  4992.2     .03       0  4999.3     .05       0
Bank Sta=4992.2,4999.3
XS Rating Curve= 0 ,0
Exp/Cntr=0.3,0.1

Type RM Length L Ch R = 1 ,18374   ,154,154,154
BEGIN DESCRIPTION:
Mapping XS 06b83c23
END DESCRIPTION:
XS GIS Cut Line= 4
      2031009.46     13531403.12      2030878.21     13531296.35
      2030598.52     13531324.99      2030469.13     13531433.16
#Sta/Elev= 30
  4748.6  551.35  4785.9  549.97  4800.3  550.39  4835.5  549.71  4843.4  549.98
  4849.8  549.66  4857.5  550.14  4870.6  549.72  4878.6  550.21    4885  549.75
  4892.9  549.87  4899.4  549.18  4981.3  546.67  4991.4  544.81  4997.9  544.46
  4998.4  543.66  5004.5  543.66    5005  544.46  5011.5  546.75  5021.5  547.58
  5049.2  546.92  5061.8  547.43  5122.1  546.96  5148.6  547.52  5182.4  547.43
  5216.2  548.46  5229.6  548.46    5237  549.15  5251.3  549.46  5367.6  550.23
#Mann= 3 ,-1 , 0
  4748.6     .05       0  4997.9     .03       0    5005     .05       0
Bank Sta=4997.9,5005
XS Rating Curve= 0 ,0
Exp/Cntr=0.3,0.1

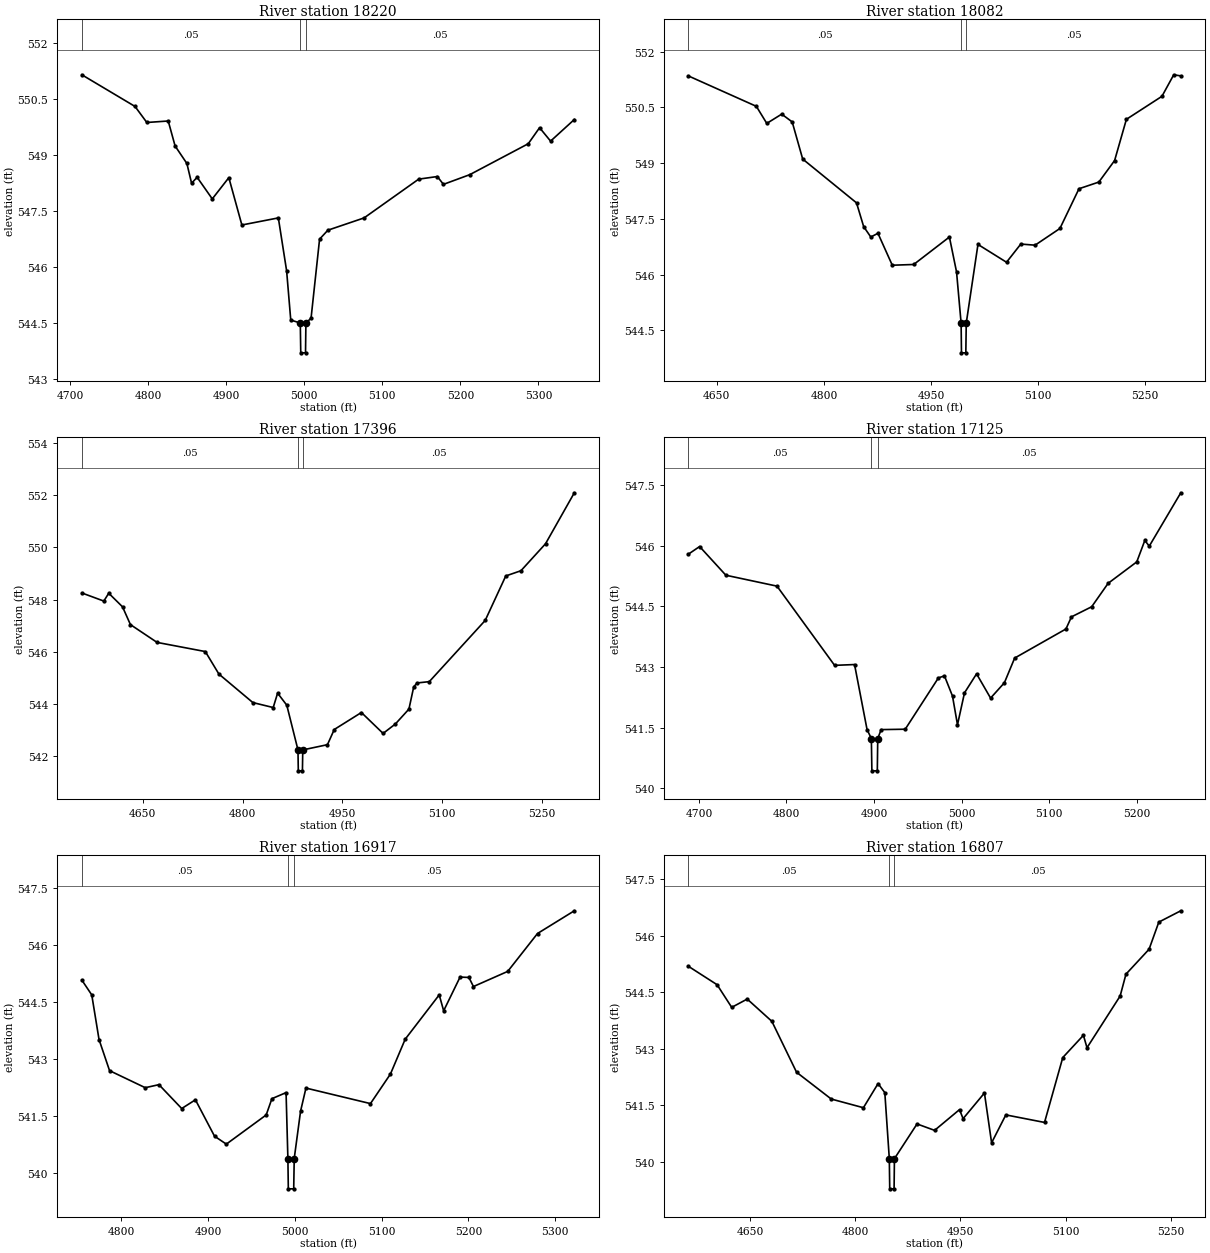
Type RM Length L Ch R = 1 ,18220   ,138,138,138
BEGIN DESCRIPTION:
Mapping XS 58777395
END DESCRIPTION:
XS GIS Cut Line= 4
      2030987.57     13531196.86      2030868.84     13531119.26
        2030548.     13531229.16      2030486.56     13531365.59
#Sta/Elev= 30
  4715.3  551.15  4783.4   550.3  4798.5  549.87  4825.9  549.91  4834.7  549.24
  4849.8  548.77  4855.8  548.24  4862.9   548.4  4882.3  547.82  4903.5  548.39
  4920.2  547.12  4966.9  547.31  4977.5  545.89  4982.8  544.57    4995  544.49
  4995.6  543.69  5001.7  543.69  5002.2  544.49  5008.8  544.62  5019.7  546.74
  5030.3  546.98  5076.7  547.31  5146.6  548.35  5170.5  548.42  5178.3  548.21
    5212  548.47  5286.9   549.3  5301.4  549.73  5315.5  549.37  5345.9  549.95
#Mann= 3 ,-1 , 0
  4715.3     .05       0    4995     .03       0  5002.2     .05       0
Bank Sta=4995,5002.2
XS Rating Curve= 0 ,0
Exp/Cntr=0.3,0.1

Type RM Length L Ch R = 1 ,18082   ,686,686,686
BEGIN DESCRIPTION:
Mapping XS 9982a835
END DESCRIPTION:
XS GIS Cut Line= 4
      2031028.12     13531145.26      2030890.97     13531045.43
      2030540.28     13531055.85      2030390.07       13531134.
#Sta/Elev= 30
  4610.1  551.35  4705.4  550.53    4720  550.07  4740.9  550.32  4755.6  550.11
  4770.3  549.11  4845.7  547.93  4855.7  547.29  4865.7  547.01  4875.7  547.11
  4895.8  546.25  4925.8  546.27  4975.8  547.01  4985.8  546.07  4992.2  544.69
  4992.7  543.89  4998.8  543.89  4999.4  544.69  5015.8  546.81  5055.8  546.33
  5075.8  546.82  5095.8  546.79  5130.6  547.24  5157.3  548.31  5185.1  548.49
  5207.2  549.07  5223.7  550.18  5273.5   550.8    5290  551.38  5299.9  551.35
#Mann= 3 ,-1 , 0
  4610.1     .05       0  4992.2     .03       0  4999.4     .05       0
Bank Sta=4992.2,4999.4
XS Rating Curve= 0 ,0
Exp/Cntr=0.3,0.1

Type RM Length L Ch R = 1 ,17396   ,271,271,271
BEGIN DESCRIPTION:
Mapping XS 9f828fe2
END DESCRIPTION:
XS GIS Cut Line= 4
      2031127.95       13530614.      2031088.89     13530468.18
      2030691.32     13530389.18      2030520.32     13530456.02
#Sta/Elev= 30
  4558.6  548.25  4591.6  547.94    4599  548.24  4619.7  547.72  4631.6  547.04
  4671.6  546.36  4744.1  546.01  4764.5  545.15  4815.5  544.06  4846.1  543.87
  4852.7  544.42  4866.5  543.96  4883.3  542.25  4883.8  541.45    4890  541.45
  4890.5  542.25  4927.6  542.45  4937.8  543.03  4978.6  543.68  5011.2  542.88
  5029.6  543.24    5050  543.81  5057.2  544.66  5062.3  544.81  5080.6  544.86
  5164.6   547.2  5195.5   548.9  5218.3   549.1  5255.2  550.13  5298.5  552.08
#Mann= 3 ,-1 , 0
  4558.6     .05       0  4883.3     .03       0  4890.5     .05       0
Bank Sta=4883.3,4890.5
XS Rating Curve= 0 ,0
Exp/Cntr=0.3,0.1

Type RM Length L Ch R = 1 ,17125   ,208,208,208
BEGIN DESCRIPTION:
Mapping XS 3b571673
END DESCRIPTION:
XS GIS Cut Line= 4
      2031129.69     13530397.89      2031125.35     13530299.77
      2030831.94     13530138.32      2030706.07      13530168.7
#Sta/Elev= 30
  4687.9  545.79  4700.8  545.98  4730.8  545.27  4789.2     545    4855  543.04
  4877.8  543.06  4892.1  541.45    4897  541.23  4897.6  540.43  4903.8  540.43
  4904.3  541.23  4908.2  541.45  4935.7  541.46  4973.6  542.73  4980.5  542.78
  4989.7  542.28  4995.4  541.57  5003.4  542.36  5017.2  542.83  5033.2  542.23
    5049  542.61  5060.7  543.22  5119.3  543.94  5125.6  544.24  5148.7  544.49
  5167.5  545.07  5200.2   545.6  5209.4  546.13  5214.5  545.99  5250.5  547.31
#Mann= 3 ,-1 , 0
  4687.9     .05       0    4897     .03       0  4904.3     .05       0
Bank Sta=4897,4904.3
XS Rating Curve= 0 ,0
Exp/Cntr=0.3,0.1

Type RM Length L Ch R = 1 ,16917   ,110,110,110
BEGIN DESCRIPTION:
Mapping XS 7015235e
END DESCRIPTION:
XS GIS Cut Line= 4
      2031225.18     13530186.07      2031206.08     13530102.73
      2030941.32     13529980.33       2030758.2     13530031.05
#Sta/Elev= 30
  4754.7  545.08  4766.1  544.69  4774.5  543.51  4786.6  542.69  4827.7  542.24
  4843.5  542.32  4869.7  541.69  4885.5  541.92  4907.5  540.96  4921.1  540.75
    4967  541.52  4973.6  541.95  4989.9  542.11    4992  540.37  4992.5  539.57
  4998.7  539.57  4999.3  540.37  5006.6  541.62  5012.8  542.23  5087.1  541.82
  5110.1   542.6  5127.1  543.52  5166.3  544.69  5171.4  544.27  5190.3  545.16
  5200.5  545.15  5205.7  544.91  5245.2  545.31  5279.5  546.31  5321.9  546.91
#Mann= 3 ,-1 , 0
  4754.7     .05       0    4992     .03       0  4999.3     .05       0
Bank Sta=4992,4999.3
XS Rating Curve= 0 ,0
Exp/Cntr=0.3,0.1

Type RM Length L Ch R = 1 ,16807   ,533,533,533
BEGIN DESCRIPTION:
Mapping XS ba78318e
END DESCRIPTION:
XS GIS Cut Line= 4
      2031437.85     13530149.61       2031281.6     13529963.84
      2030951.74     13529908.28      2030831.05      13529937.8
#Sta/Elev= 30
  4562.3  545.19  4603.3   544.7  4624.1   544.1  4646.2  544.32  4681.3  543.73
  4716.5  542.38  4765.9  541.67  4811.7  541.44  4832.6  542.08  4842.2  541.84
  4848.6  540.09  4849.2  539.29  4855.4  539.29  4855.9  540.09  4888.1  541.01
  4913.1  540.84  4948.6  541.39  4953.7  541.15  4984.1  541.83  4994.3  540.51
  5014.6  541.25  5069.7  541.05  5095.7  542.77  5125.1  543.36  5130.2  543.03
  5177.4   544.4  5185.7  544.98  5218.6  545.64  5232.5  546.36  5263.8  546.66
#Mann= 3 ,-1 , 0
  4562.3     .05       0  4848.6     .03       0  4855.9     .05       0
Bank Sta=4848.6,4855.9
XS Rating Curve= 0 ,0
Exp/Cntr=0.3,0.1