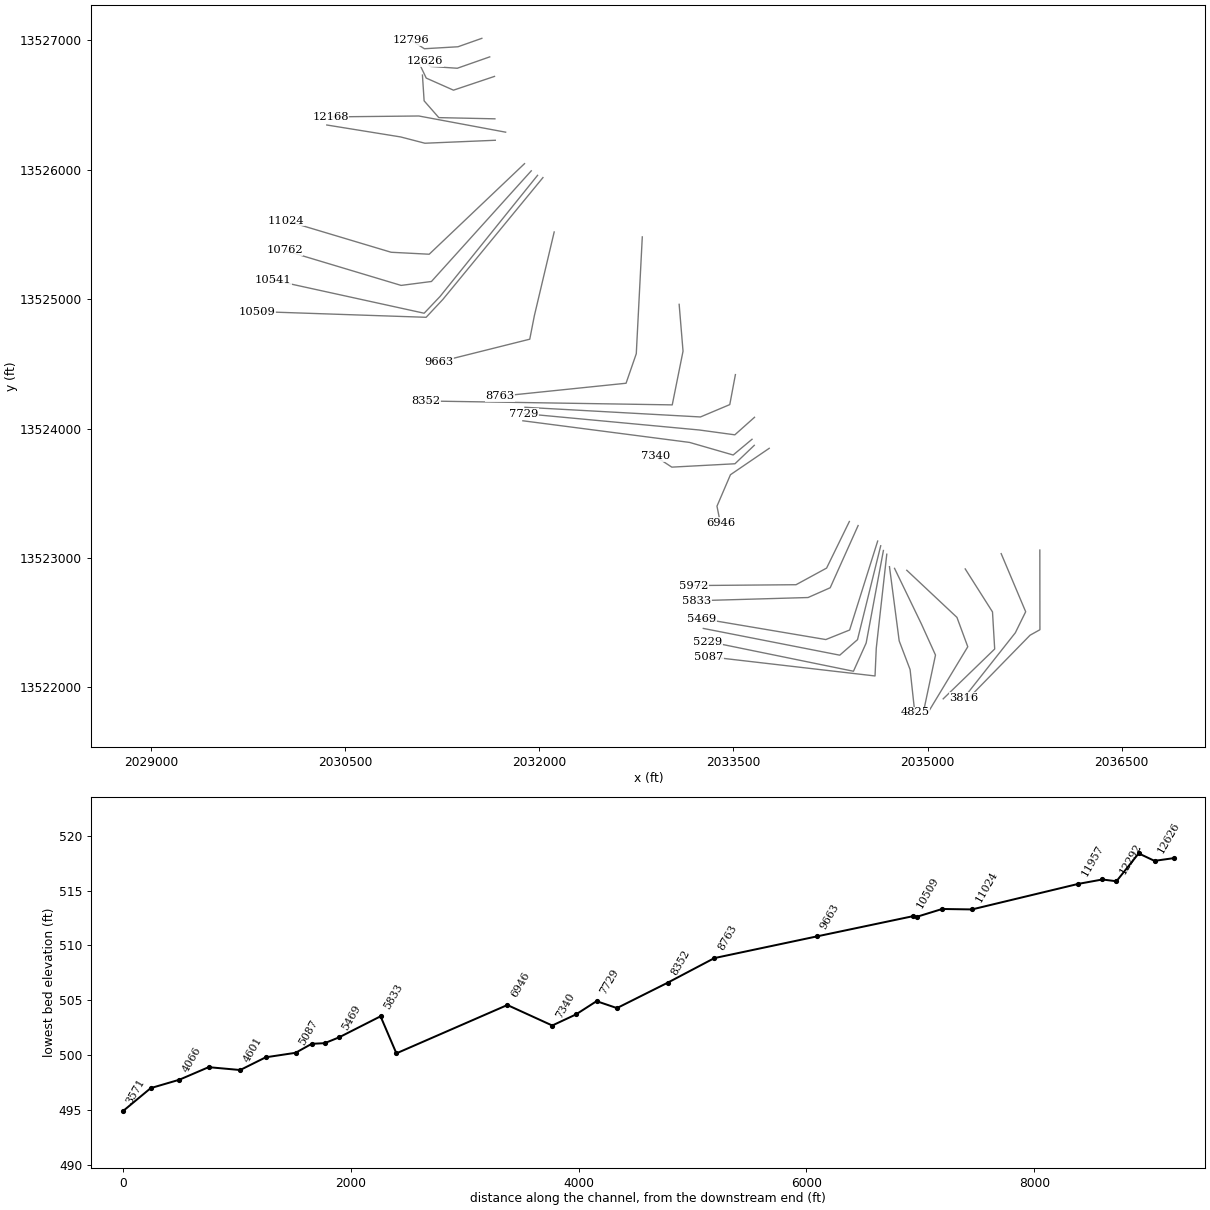
HEC-RAS study ELLIS Br.prj: ELLIS Br Base Level Engineering

--- ELLIS Br.g01 (geometry) --- (continued)

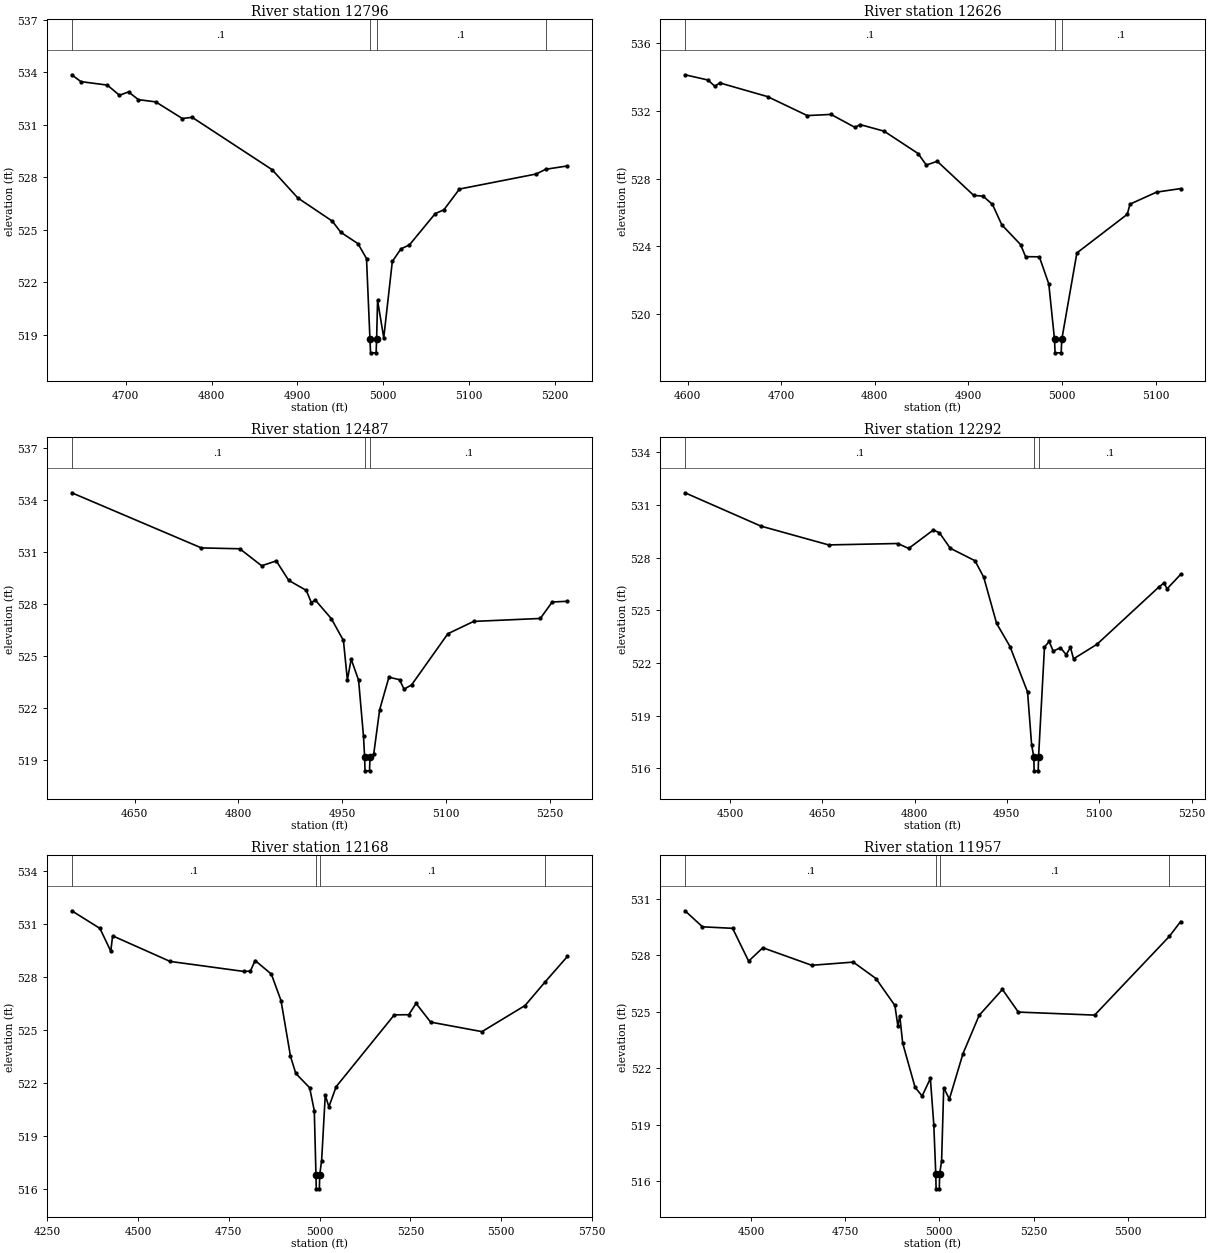
Type RM Length L Ch R = 1 ,12796   ,170,170,170
BEGIN DESCRIPTION:
Mapping XS 8898d388
END DESCRIPTION:
XS GIS Cut Line= 4
      2031557.43      13527014.4      2031372.96      13526949.3
      2031113.63     13526934.11      2031010.24     13527000.19
#Sta/Elev= 30
  4636.9  533.85  4647.5  533.46  4678.4  533.26  4692.5  532.68  4703.1  532.87
  4714.6  532.43  4734.9   532.3  4765.9  531.35  4777.3  531.42  4870.5  528.43
  4900.6  526.81  4940.7  525.49  4950.7  524.85  4970.7   524.2  4980.7  523.35
  4984.7  518.76  4985.4  517.96  4991.9  517.96  4992.5  518.76  4993.6  520.96
  5000.8  518.82  5010.8  523.18  5020.8   523.9  5030.8  524.13  5060.9  525.92
  5070.9  526.13  5089.1  527.32  5178.6  528.18  5189.7  528.45    5215  528.64
#Mann= 4 ,-1 , 0
  4636.9      .1       0  4984.7     .07       0  4992.5      .1       0
  5189.7     .05       0
Bank Sta=4984.7,4992.5
XS Rating Curve= 0 ,0
Exp/Cntr=0.3,0.1

Type RM Length L Ch R = 1 ,12626   ,139,139,139
BEGIN DESCRIPTION:
Mapping XS 2fdaa790
END DESCRIPTION:
XS GIS Cut Line= 4
      2031618.21     13526871.18      2031367.53     13526783.28
      2031161.37     13526797.39        2031119.     13526835.53
#Sta/Elev= 30
  4597.3  534.13  4621.9  533.82  4629.1  533.45  4634.4  533.65  4685.5  532.84
  4727.9  531.72  4753.2  531.79  4778.9  531.02  4784.2  531.19  4809.9   530.8
  4846.2  529.48    4855   528.8  4866.7  529.02  4905.6  527.01  4915.6  526.96
  4925.6  526.48  4935.6  525.27  4955.7   524.1    4961  523.39  4975.7  523.38
  4985.8  521.78  4991.9  518.51  4992.5  517.71    4999  517.71  4999.7  518.51
  5015.8  523.61  5069.6  525.89  5072.5  526.49  5100.9   527.2  5126.6  527.41
#Mann= 3 ,-1 , 0
  4597.3      .1       0  4991.9     .07       0  4999.7      .1       0
Bank Sta=4991.9,4999.7
XS Rating Curve= 0 ,0
Exp/Cntr=0.3,0.1

Type RM Length L Ch R = 1 ,12487   ,195,195,195
BEGIN DESCRIPTION:
Mapping XS f4b035d9
END DESCRIPTION:
XS GIS Cut Line= 4
      2031655.09     13526720.35      2031338.24     13526614.01
      2031127.73     13526707.33      2031062.63     13526844.04
#Sta/Elev= 30
  4559.2  534.43  4746.4  531.25  4801.9   531.2  4833.5  530.22  4854.6   530.5
  4872.5  529.38  4897.9   528.8  4905.3  528.09  4910.8  528.25  4934.1  527.17
  4951.6  525.91  4957.3  523.64  4962.8  524.83  4973.5  523.62  4980.6  520.38
  4982.2  519.19  4982.8  518.39  4989.3  518.39    4990  519.19  4995.4  519.37
  5003.9  521.91  5017.3  523.79  5032.6  523.65  5039.2   523.1  5050.1  523.35
  5102.5   526.3  5139.7  527.01    5236  527.18  5253.2  528.13  5275.1  528.17
#Mann= 3 ,-1 , 0
  4559.2      .1       0  4982.2     .07       0    4990      .1       0
Bank Sta=4982.2,4990
XS Rating Curve= 0 ,0
Exp/Cntr=0.3,0.1

Type RM Length L Ch R = 1 ,12292   ,124,124,124
BEGIN DESCRIPTION:
EAST FORK ELLIS Br 1.0
END DESCRIPTION:
XS GIS Cut Line= 4
      2031658.33     13526392.66      2031224.96     13526401.95
      2031111.46     13526531.55      2031098.48     13526730.58
#Sta/Elev= 30
  4427.1  531.69  4550.5  529.79  4660.5  528.72  4772.6   528.8  4790.5  528.52
  4830.5  529.57  4840.5  529.41    4858  528.53  4898.2  527.82  4912.4  526.88
  4933.3  524.25  4955.1  522.93  4983.6  520.34  4990.2  517.34  4993.7  516.65
  4994.3  515.85  5000.9  515.85  5001.5  516.65  5011.1   522.9  5018.7  523.22
  5025.3  522.67  5037.1  522.86  5046.3  522.47  5053.3  522.88  5058.3  522.23
  5096.4  523.06  5196.6  526.31  5205.3  526.55  5210.3  526.22  5232.3  527.04
#Mann= 3 ,-1 , 0
  4427.1      .1       0  4993.7     .07       0  5001.5      .1       0
Bank Sta=4993.7,5001.5
XS Rating Curve= 0 ,0
Exp/Cntr=0.3,0.1

Type RM Length L Ch R = 1 ,12168   ,211,211,211
BEGIN DESCRIPTION:
ELLIS Br 5.0
END DESCRIPTION:
XS GIS Cut Line= 3
      2031741.23     13526289.48       2031070.8     13526414.54
      2030388.53     13526407.56
#Sta/Elev= 30
    4318  531.77  4395.6  530.77  4425.4  529.48  4430.5  530.35  4588.6   528.9
  4792.3  528.33  4809.6  528.35  4822.8  528.95  4867.4  528.18    4894  526.68
  4920.1  523.52  4934.7  522.55  4972.8  521.74  4985.6  520.44  4990.2  516.81
  4991.1  516.01  4999.6  516.01  5000.5  516.81  5005.8  517.61  5015.8  521.32
  5025.8  520.66  5045.8   521.8  5205.8  525.87  5245.8  525.88  5265.8  526.52
  5305.8  525.46  5447.2  524.92  5565.8   526.4  5620.3  527.72  5682.3  529.18
#Mann= 4 ,-1 , 0
    4318      .1       0  4990.2     .07       0  5000.5      .1       0
  5620.3     .05       0
Bank Sta=4990.2,5000.5
XS Rating Curve= 0 ,0
Exp/Cntr=0.3,0.1

Type RM Length L Ch R = 1 ,11957   ,933,933,933
BEGIN DESCRIPTION:
Mapping XS 75299c99
END DESCRIPTION:
XS GIS Cut Line= 4
      2031661.33     13526226.98      2031117.48     13526204.12
      2030929.98     13526252.73      2030359.62     13526344.98
#Sta/Elev= 30
  4324.8  530.35  4371.2   529.5  4451.2  529.42  4493.7  527.68  4531.3  528.39
  4661.4  527.46  4771.5  527.63  4831.6  526.76    4882  525.33  4889.9  524.25
    4895  524.78  4902.7  523.33  4935.6  520.99  4954.3  520.53  4976.2  521.46
  4985.3  519.01  4990.5  516.41  4991.4  515.61  4999.9  515.61  5000.8  516.41
    5006  517.08  5011.6  520.97  5026.7  520.37  5062.8  522.78  5105.8  524.81
  5167.5  526.18  5209.7  524.98  5412.3  524.82  5610.5  528.99  5640.6  529.78
#Mann= 4 ,-1 , 0
  4324.8      .1       0  4990.5     .07       0  5000.8      .1       0
  5610.5     .05       0
Bank Sta=4990.5,5000.8
XS Rating Curve= 0 ,0
Exp/Cntr=0.3,0.1

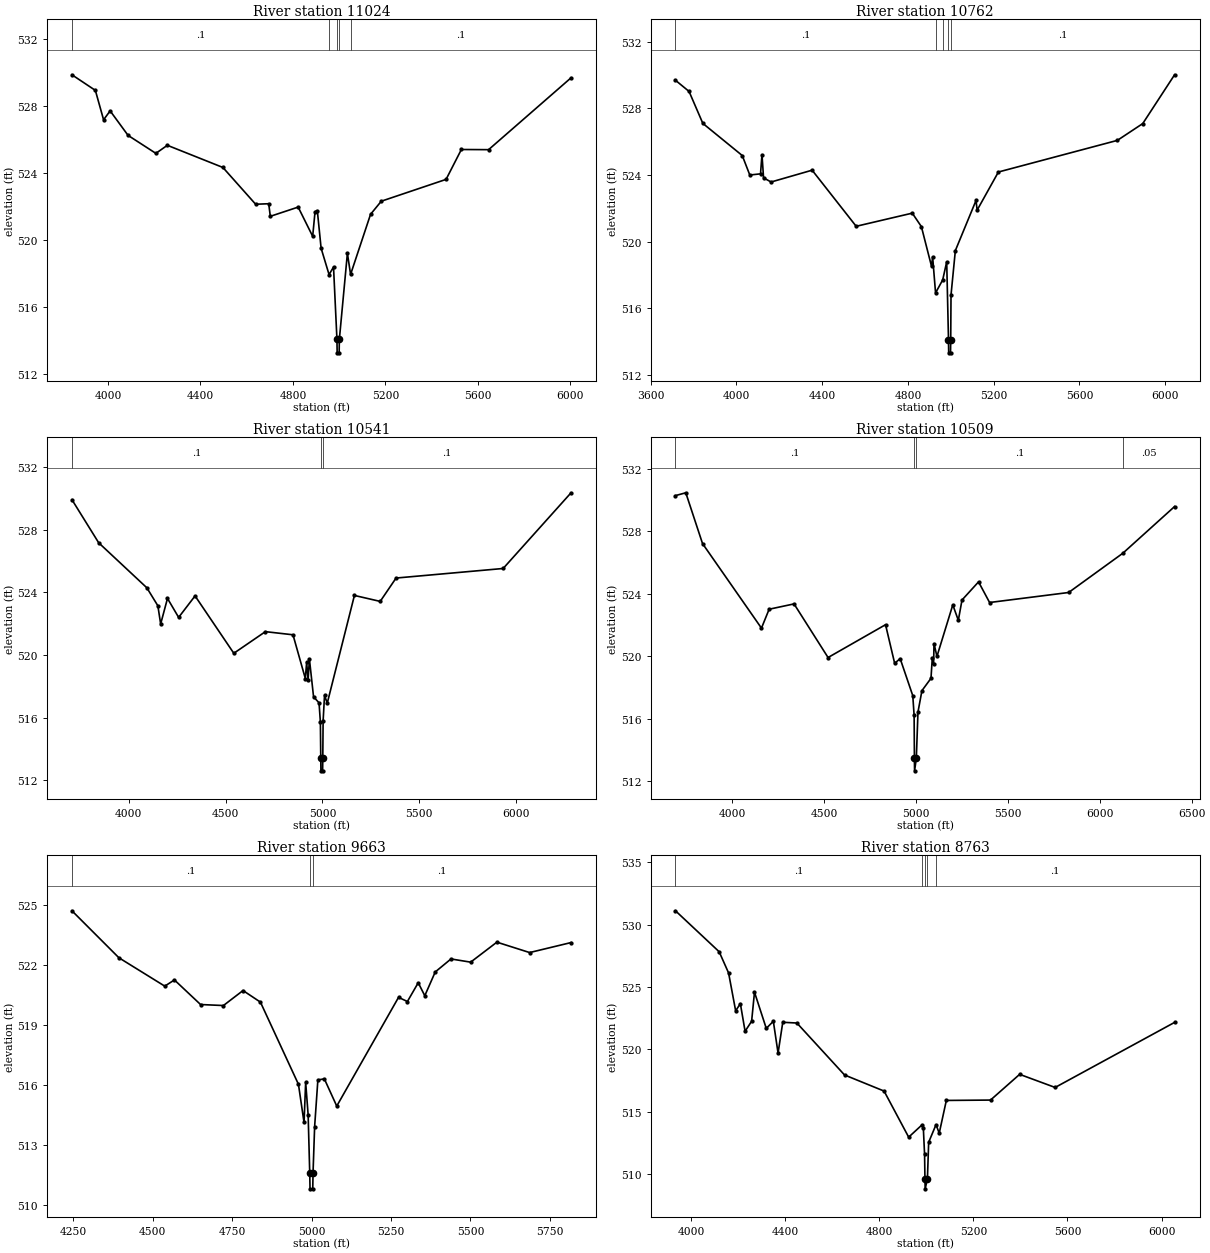
Type RM Length L Ch R = 1 ,11024   ,262,262,262
BEGIN DESCRIPTION:
Mapping XS 38c1cec7
END DESCRIPTION:
XS GIS Cut Line= 4
      2031887.06     13526046.44      2031150.76     13525346.71
       2030856.7      13525361.9      2030043.29     13525605.46
#Sta/Elev= 30
  3844.1  529.84  3945.5  528.91    3981  527.16  4009.4  527.69    4087  526.23
  4207.2  525.16  4256.9  525.64  4497.2  524.32  4638.8  522.13  4695.4  522.16
  4702.3  521.41  4822.8  521.96  4885.6  520.22  4895.7  521.67  4905.7  521.75
  4922.1  519.51  4956.5  517.94  4975.8  518.39  4990.6  514.08  4991.5  513.28
  5000.1  513.28    5001  514.08  5035.8  519.21  5049.6  517.95    5136  521.53
  5182.4  522.31  5462.7  523.61  5528.9  525.39  5646.7  525.38  6003.4  529.66
#Mann= 5 ,-1 , 0
  3844.1      .1       0  4956.5     .12       0  4990.6     .07       0
    5001     .12       0  5049.6      .1       0
Bank Sta=4990.6,5001
XS Rating Curve= 0 ,0
Exp/Cntr=0.3,0.1

Type RM Length L Ch R = 1 ,10762   ,221,221,221
BEGIN DESCRIPTION:
Mapping XS c141a69c
END DESCRIPTION:
XS GIS Cut Line= 4
       2031939.1     13525990.84      2031168.12     13525136.21
      2030933.74     13525105.83      2030032.91     13525376.28
#Sta/Elev= 30
    3716  529.69  3779.4  529.02  3843.7   527.1  4027.5  525.17  4062.7     524
  4112.7  524.07  4119.5  525.22  4126.9  523.83    4162  523.58  4353.4  524.29
  4558.9  520.92  4820.5  521.71    4863   520.9  4910.4  518.51  4915.4  519.09
  4929.1  516.92  4962.4   517.7  4981.1  518.79  4989.4  514.12  4990.3  513.32
  4998.9  513.32  4999.8  514.12  5001.2   516.8  5021.4  519.46  5117.8  522.47
    5123  521.89  5222.1  524.18    5777  526.08  5895.5  527.09  6043.9  530.02
#Mann= 5 ,-1 , 0
    3716      .1       0  4929.1     .12       0  4962.4      .1       0
  4989.4     .07       0  4999.8      .1       0
Bank Sta=4989.4,4999.8
XS Rating Curve= 0 ,0
Exp/Cntr=0.3,0.1

Type RM Length L Ch R = 1 ,10541   ,32,32,32
BEGIN DESCRIPTION:
Mapping XS 52f859f0
END DESCRIPTION:
XS GIS Cut Line= 4
      2031987.74     13525956.15      2031234.31     13525020.11
      2031111.69     13524890.98      2029942.59     13525147.13
#Sta/Elev= 30
  3707.1  529.91  3845.2  527.16  4093.7  524.29  4150.7  523.14  4165.1  521.98
  4200.3  523.61  4257.9   522.4  4342.7  523.77  4542.7  520.11  4705.8  521.49
  4848.2  521.29  4911.9   518.5  4918.8  519.54  4926.1   518.4    4933  519.74
  4954.4  517.33  4982.7  516.95  4989.6  515.72  4991.6  513.41  4992.5  512.61
  5001.1  512.61    5002  513.41  5003.7  515.79    5011  517.42  5025.1  516.93
  5165.3   523.8  5298.4  523.42  5380.3  524.91  5933.1  525.52  6283.6  530.35
#Mann= 3 ,-1 , 0
  3707.1      .1       0  4991.6     .07       0    5002      .1       0
Bank Sta=4991.6,5002
XS Rating Curve= 0 ,0
Exp/Cntr=0.3,0.1

Type RM Length L Ch R = 1 ,10509   ,846,846,846
BEGIN DESCRIPTION:
Mapping XS 646d0eac
END DESCRIPTION:
XS GIS Cut Line= 4
      2032029.43     13525938.82      2031256.01     13524997.32
      2031126.89     13524859.52      2029818.84     13524904.03
#Sta/Elev= 30
    3691  530.28  3747.2  530.46  3838.3  527.21    4159   521.8  4200.7  523.01
  4336.3  523.35  4521.4  519.92  4834.2  522.02  4883.8  519.55  4913.8  519.85
  4982.4  517.48  4989.7  516.22  4991.3  513.47  4992.2  512.67  5001.7  513.47
  5010.7  516.43  5032.2   517.8  5081.5  518.59  5088.8  519.92  5095.7  519.48
    5098  520.81  5113.9  519.99  5200.2  523.29  5230.3   522.3  5250.3   523.6
  5340.3  524.76  5400.4  523.44  5830.6  524.08  6125.3  526.59  6407.1  529.58
#Mann= 4 ,-1 , 0
    3691      .1       0  4991.3     .07       0  5001.7      .1       0
  6125.3     .05       0
Bank Sta=4991.3,5001.7
XS Rating Curve= 0 ,0
Exp/Cntr=0.3,0.1

Type RM Length L Ch R = 1 ,9663    ,900,900,900
BEGIN DESCRIPTION:
Mapping XS fbe877af
END DESCRIPTION:
XS GIS Cut Line= 4
      2032116.22     13525518.68      2031963.04     13524871.81
      2031927.45     13524690.39      2031228.64     13524515.51
#Sta/Elev= 30
  4246.3  524.73    4394  522.38  4538.3  520.96  4568.7  521.27  4650.9  520.04
  4722.8  519.99  4784.5  520.74  4839.2  520.16  4958.8  516.05  4976.4  514.14
  4981.5  516.15  4989.3  514.52  4994.3  511.62  4995.2  510.82  5003.8  510.82
  5004.7  511.62  5009.7  513.93  5019.9  516.27  5040.3  516.32  5079.3  514.96
  5273.7   520.4  5301.5  520.19  5335.6  521.13  5356.2  520.48  5389.1  521.67
  5438.6  522.32  5500.5  522.16    5583  523.16    5686  522.64  5816.3  523.14
#Mann= 3 ,-1 , 0
  4246.3      .1       0  4994.3     .07       0  5004.7      .1       0
Bank Sta=4994.3,5004.7
XS Rating Curve= 0 ,0
Exp/Cntr=0.3,0.1

Type RM Length L Ch R = 1 ,8763    ,411,411,411
BEGIN DESCRIPTION:
Mapping XS 2ba85fd5
END DESCRIPTION:
XS GIS Cut Line= 4
      2032796.77     13525480.49      2032750.37     13524578.41
      2032671.37     13524350.11      2031699.97       13524250.
#Sta/Elev= 30
  3933.9  531.11  4119.6  527.83  4159.7  526.13  4189.7   523.1  4209.8  523.67
  4229.8  521.46  4257.6  522.26  4269.8  524.59  4319.9  521.69  4349.9  522.26
    4370  519.71    4390  522.18    4450  522.12  4652.5  517.96  4820.6  516.67
  4925.1  512.98  4982.8  513.98  4987.4  513.73  4992.7   511.6  4994.3  509.64
  4995.2  508.84  5004.8  509.64  5010.1  512.57  5041.3  513.98    5055   513.3
  5085.2  515.92    5273  515.95  5396.8  518.01  5547.6  516.96  6055.3  522.17
#Mann= 5 ,-1 , 0
  3933.9      .1       0  4982.8     .12       0  4994.3     .07       0
  5004.8     .12       0  5041.3      .1       0
Bank Sta=4994.3,5004.8
XS Rating Curve= 0 ,0
Exp/Cntr=0.3,0.1

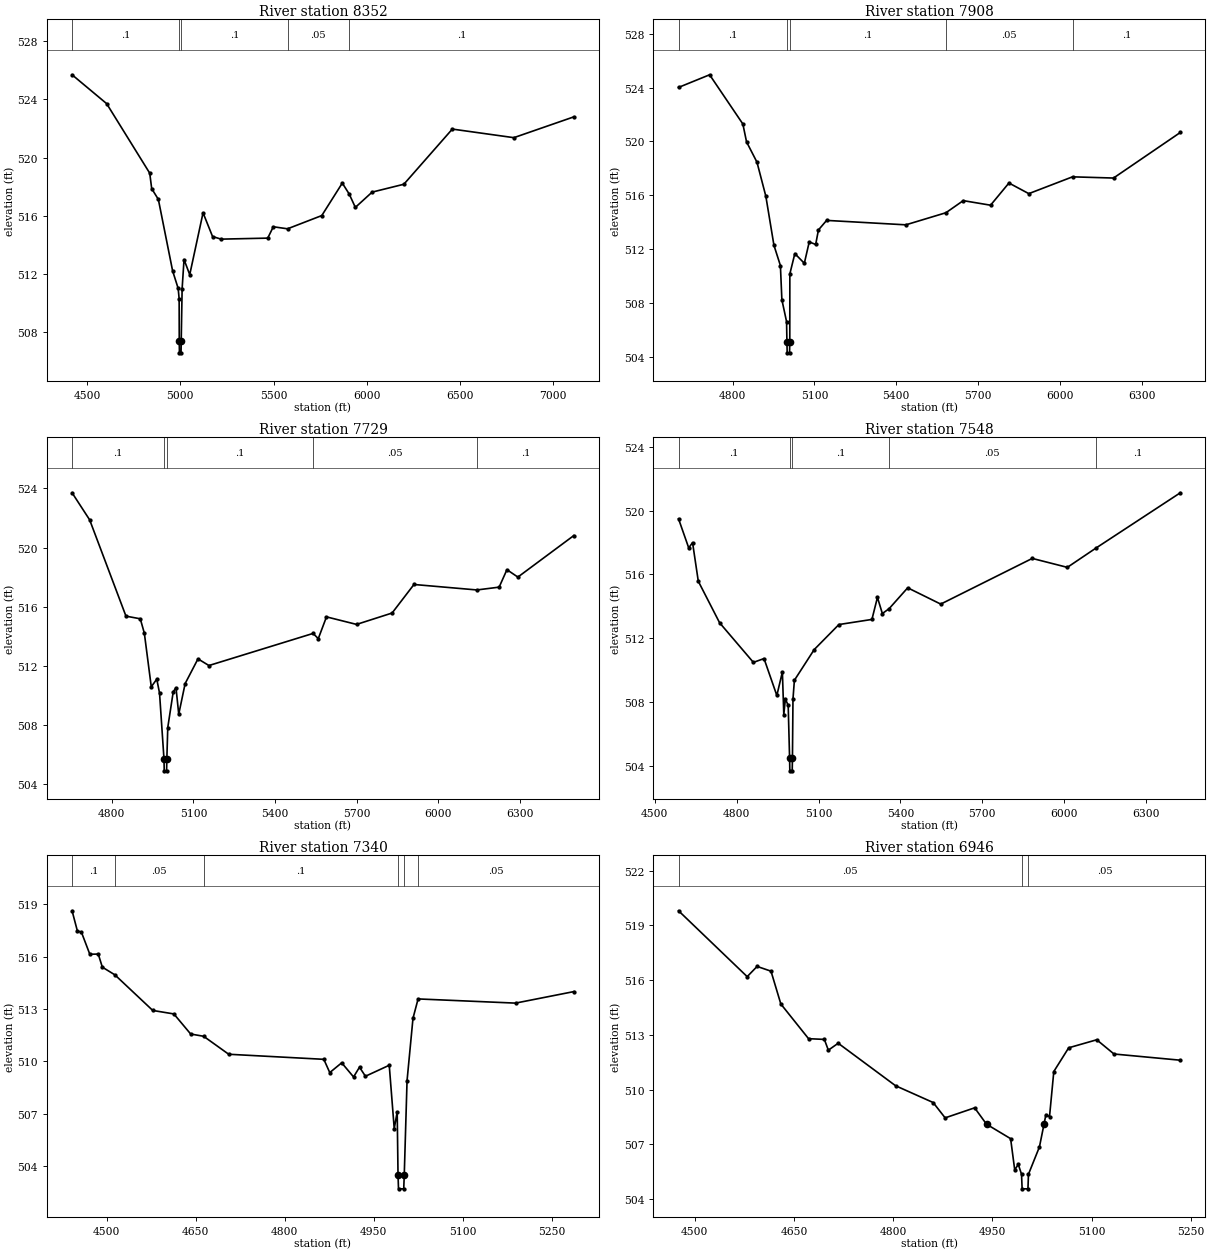
Type RM Length L Ch R = 1 ,8352    ,444,444,444
BEGIN DESCRIPTION:
Mapping XS d3dffc75
END DESCRIPTION:
XS GIS Cut Line= 4
      2033081.49     13524959.64      2033111.49     13524597.91
      2033028.15     13524182.98      2031123.18      13524213.1
#Sta/Elev= 30
  4419.4  525.69  4604.7  523.71    4836  518.93  4846.5  517.87  4882.2  517.13
  4958.7  512.22  4988.6  511.01  4993.7   510.3  4994.3  507.39  4995.2  506.59
  5003.9  506.59  5004.8  507.39  5009.7  510.99  5019.9     513  5050.5  511.96
  5121.9  516.21  5172.9  514.58  5218.7   514.4  5468.8  514.47  5498.8  515.25
  5575.1  515.11  5758.8  516.02  5868.8  518.25  5905.8   517.5  5938.8  516.58
  6028.8  517.63  6198.9  518.17  6458.9  521.96  6788.9  521.37  7110.8   522.8
#Mann= 5 ,-1 , 0
  4419.4      .1       0  4994.3     .07       0  5004.8      .1       0
  5575.1     .05       0  5905.8      .1       0
Bank Sta=4994.3,5004.8
XS Rating Curve= 0 ,0
Exp/Cntr=0.3,0.1

Type RM Length L Ch R = 1 ,7908    ,179,179,179
BEGIN DESCRIPTION:
Mapping XS 70ffaaa9
END DESCRIPTION:
XS GIS Cut Line= 4
        2033516.     13524416.97      2033472.59     13524185.18
      2033246.03      13524089.7      2031890.47     13524164.49
#Sta/Elev= 30
    4602  524.02  4715.9  524.96  4837.8   521.3  4851.3  519.97  4889.5  518.46
    4922  515.93  4951.7  512.28  4975.4  510.77  4980.8  508.23    4998   506.6
  4999.3  505.08  5000.2  504.28  5008.9  504.28  5009.8  505.08    5010  510.15
  5028.3  511.66  5063.1  510.94  5081.1  512.53  5104.7  512.34  5114.8  513.42
  5144.8  514.13  5435.2   513.8  5582.1   514.7  5645.6   515.6  5745.7  515.26
  5813.1  516.91  5885.9  516.12  6046.1  517.37  6196.4  517.28  6441.3  520.67
#Mann= 5 ,-1 , 0
    4602      .1       0  4999.3     .07       0  5009.8      .1       0
  5582.1     .05       0  6046.1      .1       0
Bank Sta=4999.3,5009.8
XS Rating Curve= 0 ,0
Exp/Cntr=0.3,0.1

Type RM Length L Ch R = 1 ,7729    ,181,181,181
BEGIN DESCRIPTION:
Mapping XS 904b8023
END DESCRIPTION:
XS GIS Cut Line= 4
      2033663.59     13524087.12      2033511.65     13523951.67
      2033237.35       13523989.      2031880.15     13524115.87
#Sta/Elev= 30
  4654.3  523.71  4718.9  521.88  4852.3  515.37  4904.9  515.19  4919.8  514.22
  4945.3  510.59  4965.5  511.11  4975.6  510.17    4992  505.71  4992.9  504.91
  5001.6  504.91  5002.5  505.71  5005.9  507.84    5026  510.26  5036.1  510.53
  5046.2  508.74  5069.7  510.81  5116.9  512.48  5157.1  512.03  5539.6   514.2
  5558.9  513.85    5589  515.32  5699.5  514.81    5830  515.58  5910.4  517.51
  6141.5  517.14  6223.3  517.33  6251.9  518.51  6292.1  518.01  6497.8  520.82
#Mann= 5 ,-1 , 0
  4654.3      .1       0    4992     .07       0  5002.5      .1       0
  5539.6     .05       0  6141.5      .1       0
Bank Sta=4992,5002.5
XS Rating Curve= 0 ,0
Exp/Cntr=0.3,0.1

Type RM Length L Ch R = 1 ,7548    ,208,208,208
BEGIN DESCRIPTION:
Mapping XS e673e195
END DESCRIPTION:
XS GIS Cut Line= 4
      2033644.47     13523917.35      2033498.64     13523795.82
      2033161.83     13523893.05      2031874.42     13524060.15
#Sta/Elev= 30
  4586.8  519.48  4624.1  517.66  4638.2  517.99  4659.2  515.57  4737.3  512.97
  4861.1  510.49    4900  510.73    4947  508.42  4967.3  509.89  4972.5  507.22
  4978.2   508.2  4988.6   507.8  4993.7   504.5  4994.6   503.7  5003.3   503.7
  5004.2   504.5  5006.1  508.19  5011.3  509.37  5083.8  511.29  5174.4  512.86
  5295.4  513.18  5315.6  514.56  5333.6  513.55  5358.2  513.85  5426.5  515.16
  5547.5  514.14  5882.9     517  6011.4  516.44  6114.7  517.63  6425.4  521.11
#Mann= 5 ,-1 , 0
  4586.8      .1       0  4993.7     .07       0  5004.2      .1       0
  5358.2     .05       0  6114.7      .1       0
Bank Sta=4993.7,5004.2
XS Rating Curve= 0 ,0
Exp/Cntr=0.3,0.1

Type RM Length L Ch R = 1 ,7340    ,394,394,394
BEGIN DESCRIPTION:
Mapping XS bd9fd184
END DESCRIPTION:
XS GIS Cut Line= 4
      2033661.83     13523870.48      2033512.53     13523728.12
      2033024.68     13523702.07      2032898.96     13523784.74
#Sta/Elev= 30
  4441.7  518.62  4450.6  517.47  4457.5  517.39  4471.6  516.13  4485.8  516.14
  4492.7  515.39  4513.8  514.95  4577.6  512.91  4613.2  512.71  4641.5  511.56
  4663.3  511.43  4705.6   510.4  4865.8  510.11  4875.8  509.35  4895.9  509.91
  4915.9   509.1  4925.9  509.66  4935.9  509.14    4976  509.77  4984.4  506.14
  4989.4   507.1  4990.8  503.49  4991.6  502.69  5000.4  502.69  5001.3  503.49
    5006  508.89    5016  512.46  5024.6  513.57  5188.7  513.33    5287  513.99
#Mann= 6 ,-1 , 0
  4441.7      .1       0  4513.8     .05       0  4663.3      .1       0
  4990.8     .07       0  5001.3      .1       0  5024.6     .05       0
Bank Sta=4990.8,5001.3
XS Rating Curve= 0 ,0
Exp/Cntr=0.3,0.1

Type RM Length L Ch R = 1 ,6946    ,974,974,974
BEGIN DESCRIPTION:
Mapping XS dd2d7d93
END DESCRIPTION:
XS GIS Cut Line= 4
      2033777.25     13523847.49       2033477.8     13523643.51
      2033373.63     13523400.46      2033399.67     13523271.11
#Sta/Elev= 30
  4475.6   519.8  4579.4  516.19  4594.4  516.75  4615.4  516.49  4630.3  514.69
  4672.2  512.79  4696.1  512.75  4702.1  512.16    4717  512.54  4803.8  510.21
  4860.6  509.29  4878.7  508.45  4923.3     509 4941.24508.1032  4977.7  507.31
  4983.9   505.6  4989.3   505.9  4994.2  505.36  4995.1  504.56  5003.9  504.56
  5004.7  505.36  5021.3  506.86 5028.18508.1026  5031.1  508.63  5036.5  508.51
    5043  510.99  5065.5  512.29  5107.9  512.73    5134  511.95  5234.3  511.61
#Mann= 3 ,-1 , 0
  4475.6     .05       0  4994.2     .03       0  5004.7     .05       0
Bank Sta=4941.24,5028.18
XS Rating Curve= 0 ,0
Exp/Cntr=0.3,0.1

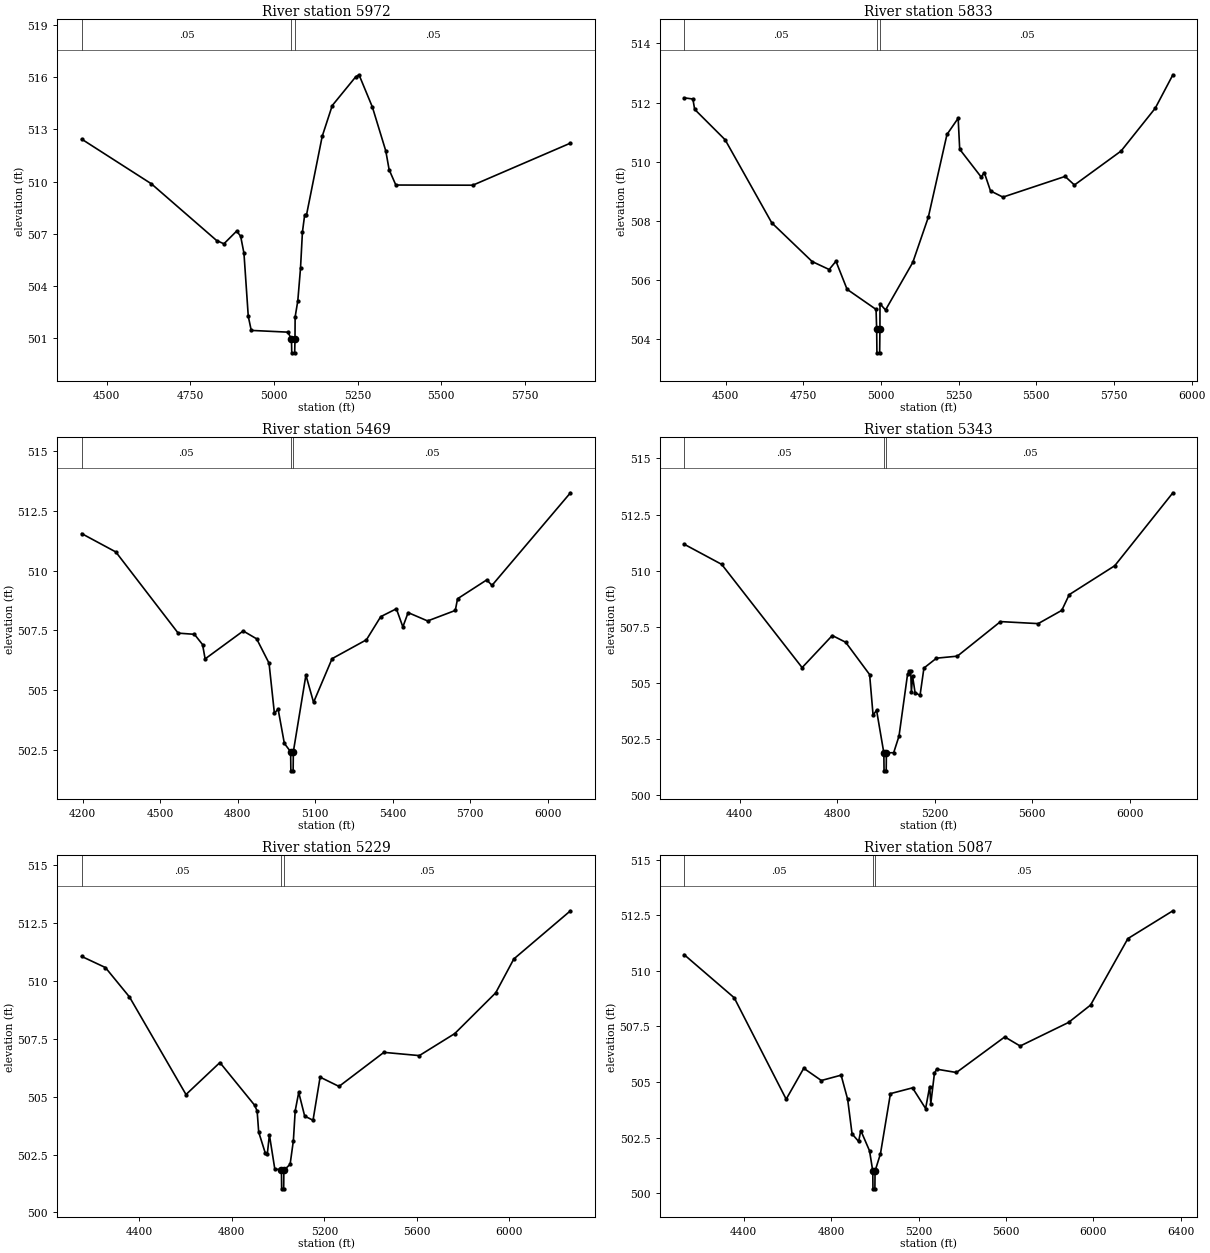
Type RM Length L Ch R = 1 ,5972    ,139,139,139
BEGIN DESCRIPTION:
Mapping XS 9e157b18
END DESCRIPTION:
XS GIS Cut Line= 4
      2034396.31     13523282.15      2034220.46     13522922.29
      2033984.35     13522793.82       2033193.2     13522787.32
#Sta/Elev= 30
  4425.7  512.44    4634  509.87  4828.9  506.61  4850.7  506.42  4888.7  507.15
  4900.7  506.86  4910.6  505.88  4923.5  502.25  4932.4  501.44  5041.6  501.34
  5052.6  500.95  5053.4  500.15  5062.2  500.15  5063.1  500.95  5063.5  502.21
  5071.5  503.14  5079.6  505.02  5085.3  507.09  5091.8  508.05  5097.2  508.05
  5144.4   512.6  5174.4  514.37  5244.4  516.02  5254.4  516.14  5294.4  514.28
  5334.4  511.76  5344.4  510.68  5364.4   509.8  5594.4  509.79  5886.2  512.21
#Mann= 3 ,-1 , 0
  4425.7     .05       0  5052.6     .03       0  5063.1     .05       0
Bank Sta=5052.6,5063.1
XS Rating Curve= 0 ,0
Exp/Cntr=0.3,0.1

Type RM Length L Ch R = 1 ,5833    ,364,364,364
BEGIN DESCRIPTION:
Mapping XS 9ba43b66
END DESCRIPTION:
XS GIS Cut Line= 4
        2034464.     13523250.85      2034248.24     13522770.38
      2034077.23     13522694.86      2033218.32     13522670.18
#Sta/Elev= 30
  4366.7  512.16    4395  512.12  4400.7  511.77  4498.8  510.74  4648.8  507.93
  4778.7  506.62  4833.5  506.35  4855.4  506.63  4891.2  505.68  4984.4     505
  4986.4  504.33  4987.2  503.53    4996  503.53  4996.9  504.33  4997.1  505.19
  5014.9  504.98  5102.6  506.59  5152.6  508.12  5212.6  510.92  5248.6  511.47
  5253.6  510.42  5322.7  509.48  5332.7  509.63  5352.7  509.01  5392.7   508.8
  5592.7   509.5  5622.8  509.21  5772.9  510.36  5882.9  511.81  5939.6  512.94
#Mann= 3 ,-1 , 0
  4366.7     .05       0  4986.4     .03       0  4996.9     .05       0
Bank Sta=4986.4,4996.9
XS Rating Curve= 0 ,0
Exp/Cntr=0.3,0.1

Type RM Length L Ch R = 1 ,5469    ,126,126,126
BEGIN DESCRIPTION:
Mapping XS a13996d5
END DESCRIPTION:
XS GIS Cut Line= 4
      2034615.04     13523131.05      2034398.41     13522443.99
      2034214.39     13522370.21      2033255.63     13522532.11
#Sta/Elev= 30
  4196.4  511.55  4328.6  510.78  4569.7  507.38  4632.6  507.33  4664.1   506.9
    4674   506.3  4821.4  507.47  4873.4  507.14  4921.3  506.12    4942  504.02
  4956.3   504.2  4980.5  502.76  5004.8  502.41  5005.7  501.61  5014.5  501.61
  5015.3  502.41  5063.9  505.62  5093.5  504.48  5165.2  506.31    5298   507.1
  5353.4  508.07  5413.9   508.4    5439  507.64  5459.3  508.24  5534.8  507.89
  5641.8  508.33  5650.6  508.82  5763.5  509.61  5783.8  509.38  6087.4  513.26
#Mann= 3 ,-1 , 0
  4196.4     .05       0  5004.8     .03       0  5015.3     .05       0
Bank Sta=5004.8,5015.3
XS Rating Curve= 0 ,0
Exp/Cntr=0.3,0.1

Type RM Length L Ch R = 1 ,5343    ,114,114,114
BEGIN DESCRIPTION:
Mapping XS 35565d4c
END DESCRIPTION:
XS GIS Cut Line= 4
      2034638.48     13523094.59      2034459.18     13522369.34
      2034322.02     13522249.55      2033268.08     13522456.19
#Sta/Elev= 30
  4172.7  511.18  4326.8  510.28  4656.4  505.68    4780  507.11  4834.9  506.81
    4933  505.37  4947.2  503.56  4961.5  503.78  4991.3  501.88  4992.2  501.08
    5001  501.08  5001.8  501.88  5031.7  501.89  5053.5  502.63  5088.6  505.39
  5096.3  505.51  5101.5  505.55  5104.1   504.6  5109.2  505.29  5119.2  504.57
  5139.6  504.44  5155.6  505.66    5207   506.1  5292.5  506.19  5469.4  507.73
  5623.8  507.64  5720.5  508.23    5751  508.93  5937.7  510.22  6175.9  513.47
#Mann= 3 ,-1 , 0
  4172.7     .05       0  4991.3     .03       0  5001.8     .05       0
Bank Sta=4991.3,5001.8
XS Rating Curve= 0 ,0
Exp/Cntr=0.3,0.1

Type RM Length L Ch R = 1 ,5229    ,142,142,142
BEGIN DESCRIPTION:
Mapping XS 30fad23d
END DESCRIPTION:
XS GIS Cut Line= 4
      2034659.31     13523058.12      2034526.02      13522343.3
      2034427.93     13522125.42      2033305.15     13522355.02
#Sta/Elev= 30
  4151.5  511.05  4254.1  510.57  4358.1   509.3  4602.3  505.09  4748.8  506.47
  4898.7  504.63  4909.7  504.38  4916.4  503.47    4945  502.56  4953.5  502.51
  4962.7  503.35  4985.8  501.89  5014.7  501.82  5015.6  501.02  5024.4  501.02
  5025.2  501.82  5052.2  502.08  5066.3   503.1  5074.2  504.39  5089.4  505.18
  5115.1  504.16  5151.2  503.98  5181.8  505.84  5263.5  505.44  5457.4  506.91
  5610.5  506.77  5763.6  507.72  5940.6  509.48  6018.8  510.94  6263.6  513.02
#Mann= 3 ,-1 , 0
  4151.5     .05       0  5014.7     .03       0  5025.2     .05       0
Bank Sta=5014.7,5025.2
XS Rating Curve= 0 ,0
Exp/Cntr=0.3,0.1

Type RM Length L Ch R = 1 ,5087    ,262,262,262
BEGIN DESCRIPTION:
Mapping XS 073c0e0e
END DESCRIPTION:
XS GIS Cut Line= 4
      2034685.35      13523029.5      2034604.14     13522303.37
      2034594.59     13522088.96      2033310.37     13522237.83
#Sta/Elev= 30
  4126.6  510.73  4356.1  508.79    4594  504.23  4674.5  505.62    4755  505.07
  4845.6  505.31  4875.6  504.22  4895.7  502.67  4925.7  502.33  4935.7  502.82
  4975.7  501.91  4990.5     501  4991.4   500.2  5000.2   500.2    5001     501
  5025.8  501.78  5071.4  504.48  5172.5  504.74  5232.5  503.81  5251.1   504.8
  5256.2  504.03  5272.8  505.39  5282.9  505.58  5373.5  505.43    5595  507.03
  5665.4  506.62  5886.9  507.68  5987.6  508.46  6158.7  511.45  6364.7   512.7
#Mann= 3 ,-1 , 0
  4126.6     .05       0  4990.5     .03       0    5001     .05       0
Bank Sta=4990.5,5001
XS Rating Curve= 0 ,0
Exp/Cntr=0.3,0.1

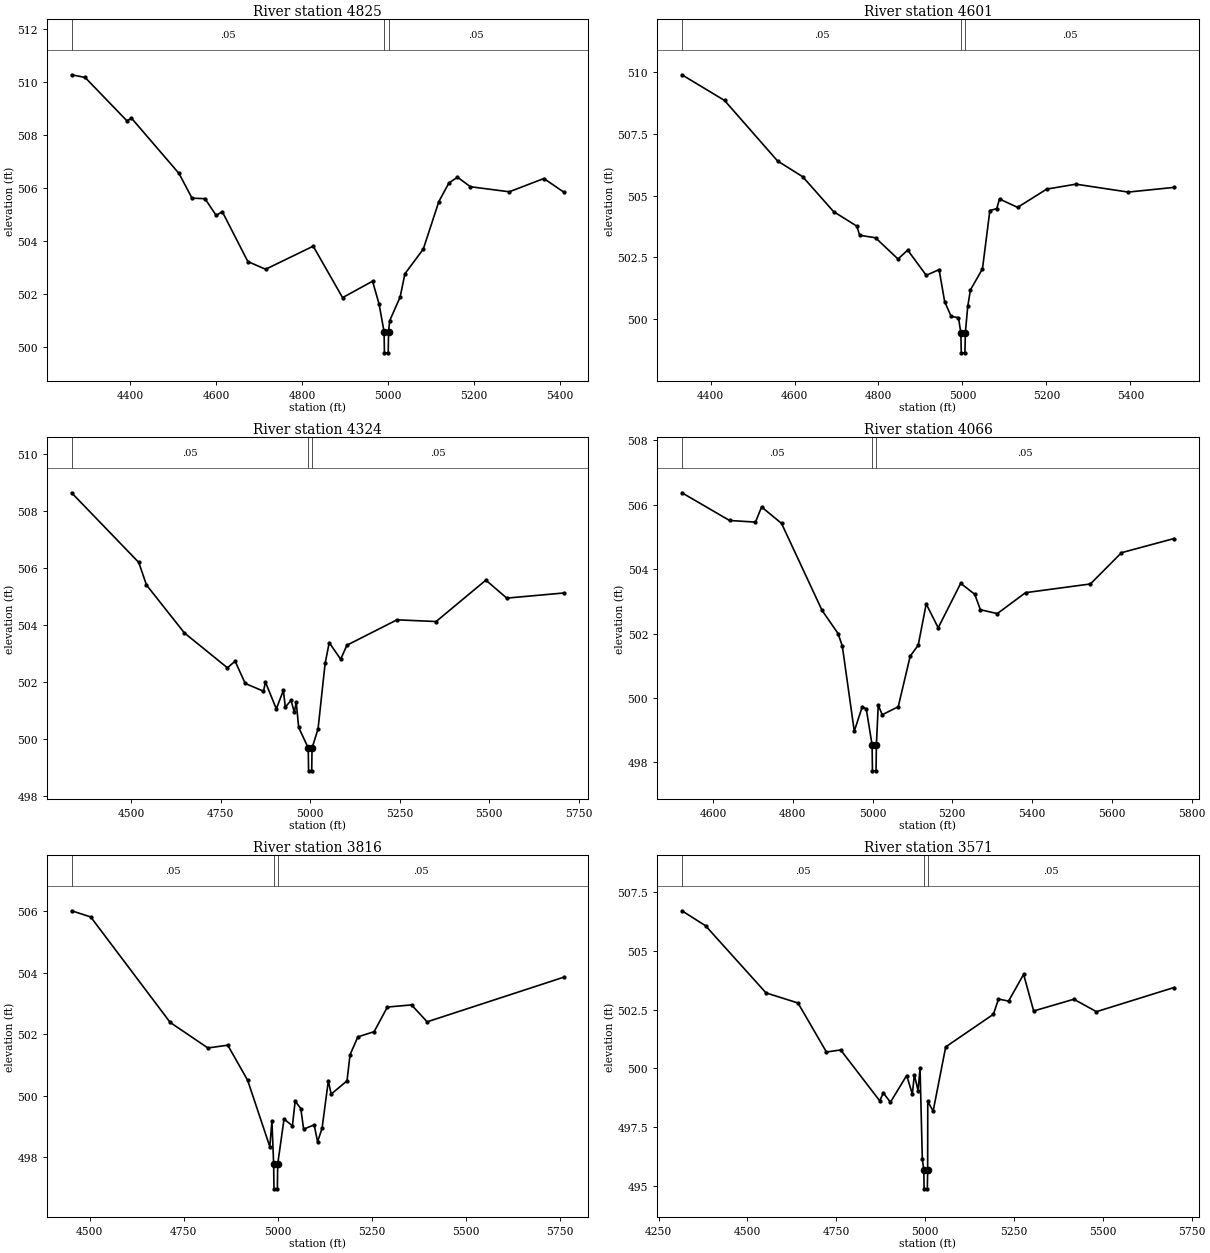
Type RM Length L Ch R = 1 ,4825    ,224,224,224
BEGIN DESCRIPTION:
Mapping XS 0dd28f67
END DESCRIPTION:
XS GIS Cut Line= 4
      2034706.19     13522933.15      2034781.23     13522359.79
      2034865.43     13522138.44       2034901.4     13521809.07
#Sta/Elev= 30
    4263  510.27  4294.4  510.17  4392.2  508.53  4402.3  508.64  4513.3  506.55
  4543.5  505.62  4573.8   505.6  4599.8  504.97  4614.1  505.11  4673.6  503.23
    4715  502.94  4825.9  503.81  4894.3  501.87  4964.1  502.49  4979.3  501.63
  4990.9  500.59  4991.8  499.79  5000.6  499.79  5001.4  500.59    5004     501
  5028.3  501.89  5039.5  502.77  5082.3   503.7  5118.5  505.49  5141.9  506.19
    5162  506.41  5192.2  506.05  5282.7  505.86  5363.2  506.36  5409.4  505.85
#Mann= 3 ,-1 , 0
    4263     .05       0  4990.9     .03       0  5001.4     .05       0
Bank Sta=4990.9,5001.4
XS Rating Curve= 0 ,0
Exp/Cntr=0.3,0.1

Type RM Length L Ch R = 1 ,4601    ,277,277,277
BEGIN DESCRIPTION:
Mapping XS 6b9ad18f
END DESCRIPTION:
XS GIS Cut Line= 4
      2034745.24     13522920.14      2034952.23     13522491.74
      2035061.61     13522250.42       2034972.2     13521828.22
#Sta/Elev= 30
  4331.8  509.89  4433.3  508.85  4559.6   506.4  4619.6  505.76    4693  504.35
  4748.4  503.76  4755.2  503.39  4792.9  503.29  4846.5  502.43  4869.6  502.79
  4913.8  501.77  4944.4     502  4957.7   500.7    4973  500.11  4990.6  500.05
  4996.3  499.43  4997.2  498.63    5006  498.63  5006.9  499.43  5012.6  500.51
  5019.1  501.18  5047.7  502.03  5065.3  504.39  5081.7  504.47  5088.3  504.86
  5131.4  504.52  5200.7  505.26  5270.3  505.46  5394.9  505.14  5504.1  505.33
#Mann= 3 ,-1 , 0
  4331.8     .05       0  4996.3     .03       0  5006.9     .05       0
Bank Sta=4996.3,5006.9
XS Rating Curve= 0 ,0
Exp/Cntr=0.3,0.1

Type RM Length L Ch R = 1 ,4324    ,258,258,258
BEGIN DESCRIPTION:
Mapping XS 8578d986
END DESCRIPTION:
XS GIS Cut Line= 4
      2034839.86     13522905.38      2035227.45     13522541.39
        2035311.     13522314.61      2034999.99     13521799.98
#Sta/Elev= 30
  4333.1  508.63  4520.8  506.19  4542.3   505.4  4648.3  503.72  4768.4   502.5
  4789.9  502.73  4818.2  501.95  4869.2  501.68  4874.6     502    4905  501.06
  4924.8  501.71  4930.1  501.12  4946.2  501.36  4955.3  500.94  4960.6   501.3
  4967.5  500.41  4994.2  499.69  4995.1  498.89  5003.9  498.89  5004.8  499.69
  5021.5  500.35  5041.3  502.65  5052.8  503.38  5084.8   502.8  5102.2  503.29
  5242.1  504.18  5351.4  504.12  5490.4  505.57  5548.7  504.94  5707.8  505.12
#Mann= 3 ,-1 , 0
  4333.1     .05       0  4994.2     .03       0  5004.8     .05       0
Bank Sta=4994.2,5004.8
XS Rating Curve= 0 ,0
Exp/Cntr=0.3,0.1

Type RM Length L Ch R = 1 ,4066    ,250,250,250
BEGIN DESCRIPTION:
Mapping XS 2554007e
END DESCRIPTION:
XS GIS Cut Line= 4
      2035291.24     13522915.82      2035501.97     13522583.71
       2035518.9     13522297.25      2035121.14     13521912.33
#Sta/Elev= 30
  4522.2  506.37  4641.6  505.51  4706.6  505.46  4721.9  505.93  4771.9  505.42
  4873.5  502.72  4913.7     502  4924.3  501.61  4954.3  498.97  4974.3  499.73
  4984.4  499.66    4999  498.54  4999.8  497.74  5008.9  497.74  5009.7  498.54
  5014.4  499.78  5024.4  499.48  5064.5  499.73  5094.5   501.3  5114.6  501.64
  5134.6  502.92  5164.7  502.18  5221.1  503.56  5256.3  503.22  5270.5  502.74
  5312.9  502.62  5383.7  503.27  5546.3  503.54  5624.2  504.51    5756  504.95
#Mann= 3 ,-1 , 0
  4522.2     .05       0    4999     .03       0  5009.7     .05       0
Bank Sta=4999,5009.7
XS Rating Curve= 0 ,0
Exp/Cntr=0.3,0.1

Type RM Length L Ch R = 1 ,3816    ,245,245,245
BEGIN DESCRIPTION:
Mapping XS 7b54dace
END DESCRIPTION:
XS GIS Cut Line= 4
      2035569.03     13523033.86      2035758.27     13522585.09
       2035678.4     13522422.59      2035281.15     13521919.66
#Sta/Elev= 30
  4451.5  506.02  4502.3  505.82  4713.8  502.39  4814.1  501.56  4866.9  501.65
  4919.8  500.51  4978.8  498.35  4984.4  499.18    4989  497.78  4989.8  496.98
  4998.9  496.98  4999.7  497.78  5016.6  499.25  5038.9  499.03  5046.2  499.83
  5061.2  499.59  5068.7  498.92  5096.8  499.06  5105.8  498.51  5117.8  498.95
  5134.4  500.49    5142  500.06  5184.1  500.49  5192.2  501.34    5213  501.92
  5256.3  502.09  5291.5  502.89  5355.7  502.96  5397.3  502.41  5760.5  503.86
#Mann= 3 ,-1 , 0
  4451.5     .05       0    4989     .03       0  4999.7     .05       0
Bank Sta=4989,4999.7
XS Rating Curve= 0 ,0
Exp/Cntr=0.3,0.1

Type RM Length L Ch R = 1 ,3571    ,36,36,36
BEGIN DESCRIPTION:
Mapping XS b1ddd878
END DESCRIPTION:
XS GIS Cut Line= 4
      2035867.65     13523061.59      2035868.34     13522446.21
      2035791.95     13522403.67      2035315.57     13521915.79
#Sta/Elev= 30
  4315.8  506.72  4382.4  506.08  4552.4  503.22  4642.4  502.79  4722.4   500.7
  4762.4  500.79  4872.4  498.62  4882.4  498.96  4902.4  498.56  4948.1   499.7
  4964.1  498.91  4969.8  499.73  4980.1  499.06  4985.8  500.01  4992.2  496.14
  4996.4  495.67  4997.2  494.87  5006.3  494.87  5007.2  495.67  5007.5   498.6
  5022.6  498.18    5058  500.92  5192.3  502.31  5206.5  502.96  5234.8  502.87
  5277.2  504.01  5305.5  502.45  5418.6  502.95  5482.2  502.42  5700.5  503.45
#Mann= 3 ,-1 , 0
  4315.8     .05       0  4996.4     .03       0  5007.2     .05       0
Bank Sta=4996.4,5007.2
XS Rating Curve= 0 ,0
Exp/Cntr=0.3,0.1