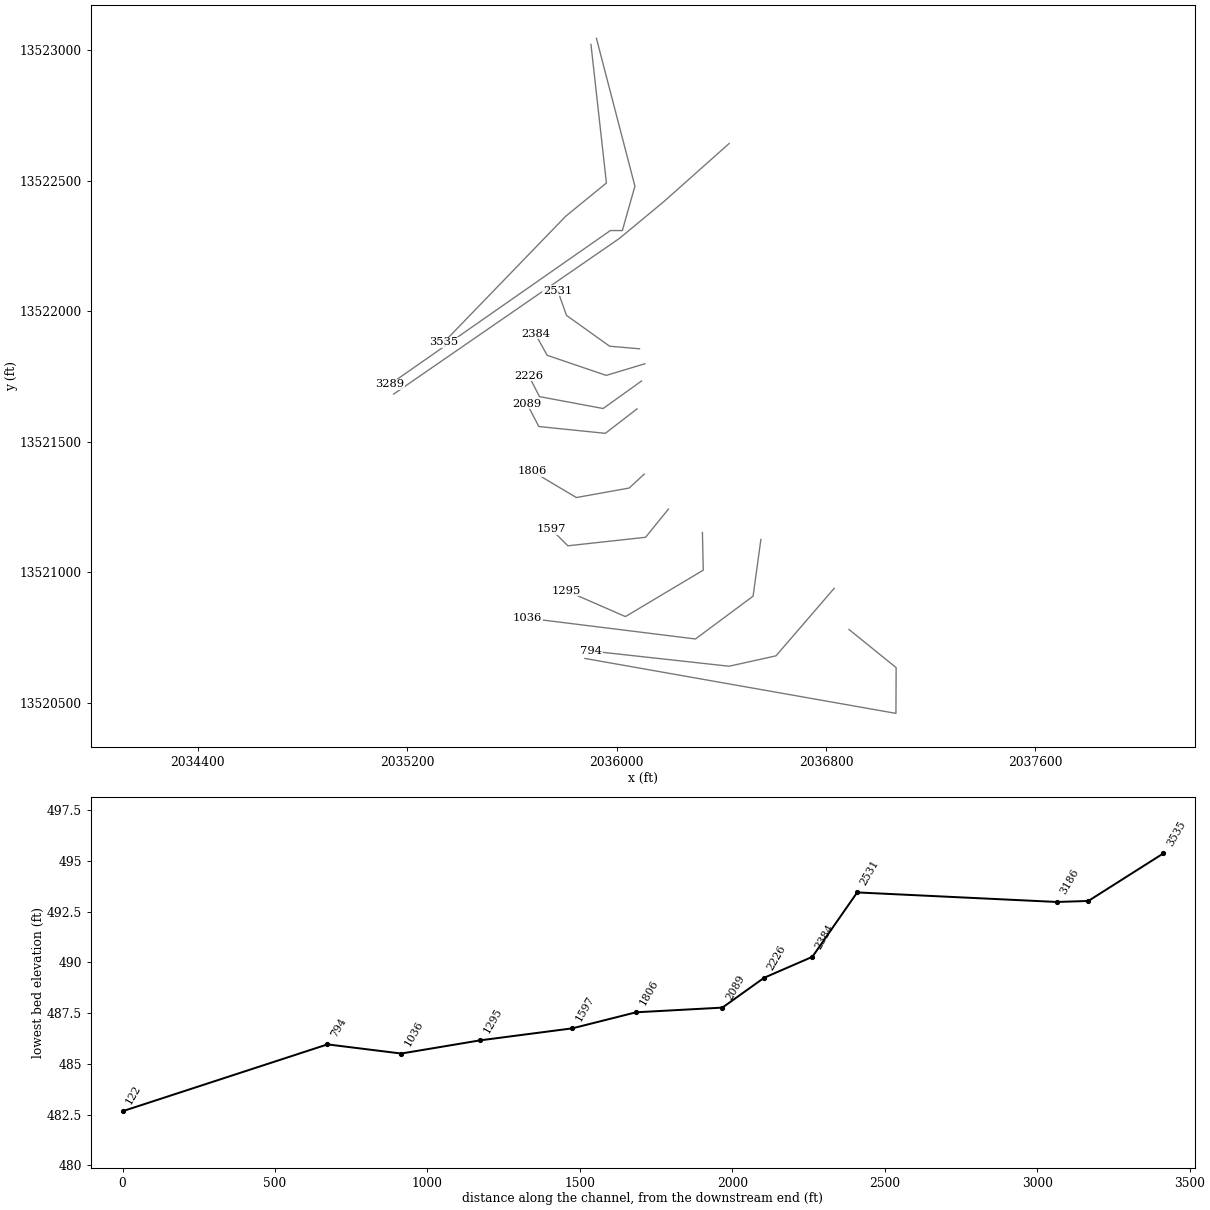
HEC-RAS study ELLIS Br.prj: ELLIS Br Base Level Engineering

--- ELLIS Br.g01 (geometry) --- (continued)

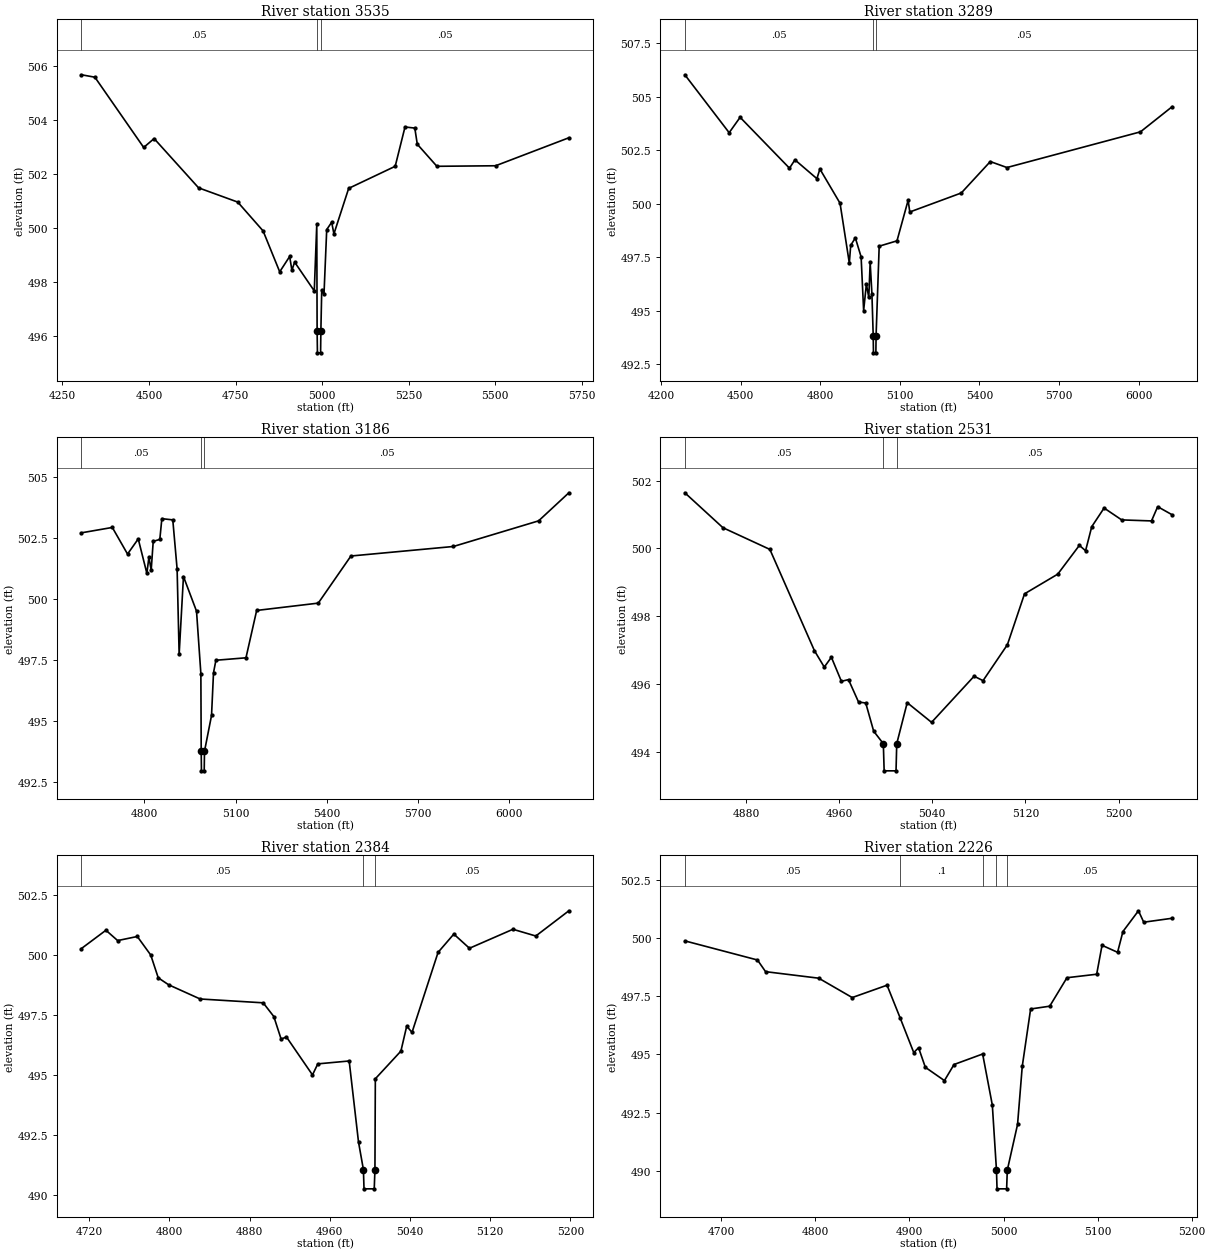
Type RM Length L Ch R = 1 ,3535    ,246,246,246
BEGIN DESCRIPTION:
Mapping XS 06b099b6
END DESCRIPTION:
XS GIS Cut Line= 4
      2035902.37     13523023.45       2035961.4     13522492.18
      2035805.84     13522364.61      2035339.97     13521881.17
#Sta/Elev= 30
  4305.2  505.69  4343.9   505.6  4484.8  502.99  4514.9  503.32  4643.3  501.49
  4756.4  500.96  4829.5  499.89  4877.5  498.37  4906.2  498.94  4912.7  498.43
  4920.6  498.73  4977.3  497.66  4984.5  500.14  4985.5  496.16  4986.4  495.36
  4995.5  495.36  4996.3  496.16  4998.8  497.69  5005.3  497.53  5013.2  499.94
  5027.5  500.21    5034  499.78  5076.6  501.47  5210.9  502.29  5239.2  503.75
  5267.5  503.71  5274.7  503.11  5331.3  502.29  5500.8  502.31  5712.3  503.35
#Mann= 3 ,-1 , 0
  4305.2     .05       0  4985.5     .03       0  4996.3     .05       0
Bank Sta=4985.5,4996.3
XS Rating Curve= 0 ,0
Exp/Cntr=0.3,0.1

Type RM Length L Ch R = 1 ,3289    ,103,103,103
BEGIN DESCRIPTION:
Mapping XS 45410c42
END DESCRIPTION:
XS GIS Cut Line= 5
      2035923.27     13523046.62      2036070.25     13522480.06
      2036022.33     13522309.92       2035976.5     13522309.92
      2035133.84     13521720.06
#Sta/Elev= 30
  4290.2  506.03  4457.2  503.32  4498.5  504.04  4684.5  501.66  4705.1  502.05
  4787.8  501.17  4799.1  501.62    4875  500.02    4910  497.22  4915.2  498.05
  4932.7   498.4  4954.4  497.51  4963.9     495  4974.3  496.24  4983.3  495.61
  4988.5  497.25  4995.1  495.79    5000  493.82  5000.9  493.02    5010  493.02
  5010.8  493.82  5022.5  498.01  5089.6  498.26  5131.6  500.16  5137.8  499.61
  5331.9   500.5  5441.2  501.97  5503.9  501.69    6007  503.36  6126.7  504.54
#Mann= 3 ,-1 , 0
  4290.2     .05       0    5000     .03       0  5010.8     .05       0
Bank Sta=5000,5010.8
XS Rating Curve= 0 ,0
Exp/Cntr=0.3,0.1

Type RM Length L Ch R = 1 ,3186    ,655,655,655
BEGIN DESCRIPTION:
Mapping XS a5a49085
END DESCRIPTION:
XS GIS Cut Line= 4
      2036430.24     13522643.56      2036179.27     13522419.64
      2036010.52     13522279.37      2035148.62     13521682.98
#Sta/Elev= 30
  4593.1  502.72  4694.6  502.94  4744.7  501.85  4779.9  502.47  4808.3  501.06
    4815  501.72  4822.5  501.19  4829.2  502.37  4850.9  502.45  4857.6   503.3
  4893.6  503.25  4907.8  501.24  4914.5  497.74  4928.7  500.93  4971.7  499.51
    4986  496.95  4987.1  493.77  4987.9  492.97    4997  492.97  4997.9  493.77
  5021.1  495.24  5027.6  496.99  5035.5   497.5  5134.4   497.6  5169.6  499.54
  5372.3  499.84  5479.8  501.77    5817  502.16  6097.4  503.21    6197  504.36
#Mann= 3 ,-1 , 0
  4593.1     .05       0  4987.1     .03       0  4997.9     .05       0
Bank Sta=4987.1,4997.9
XS Rating Curve= 0 ,0
Exp/Cntr=0.3,0.1

Type RM Length L Ch R = 1 ,2531    ,147,147,147
BEGIN DESCRIPTION:
Mapping XS f2704457
END DESCRIPTION:
XS GIS Cut Line= 4
      2036087.75     13521856.79       2035973.8     13521866.56
      2035808.87     13521984.83      2035775.29     13522080.17
#Sta/Elev= 30
  4827.6  501.64  4860.3  500.61  4900.6  499.97  4938.9  496.98  4947.3   496.5
  4953.4  496.79    4962  496.08  4968.1  496.13  4976.7  495.47  4982.9  495.44
  4989.7  494.61    4998  494.24  4998.7  493.44  5008.9  493.44  5009.5  494.24
  5018.5  495.45  5039.4  494.87  5075.9  496.23  5083.6   496.1  5104.5  497.16
  5119.2  498.66  5147.7  499.24  5166.3  500.09  5171.6  499.93  5176.9  500.64
  5187.5  501.19  5202.6  500.84  5228.2  500.81  5233.5  501.23    5246  500.99
#Mann= 3 ,-1 , 0
  4827.6     .05       0    4998     .03       0  5009.5     .05       0
Bank Sta=4998,5009.5
XS Rating Curve= 0 ,0
Exp/Cntr=0.3,0.1

Type RM Length L Ch R = 1 ,2384    ,158,158,158
BEGIN DESCRIPTION:
Mapping XS 48382bdd
END DESCRIPTION:
XS GIS Cut Line= 4
      2036108.32     13521799.28      2035960.78      13521754.8
      2035735.09     13521831.84      2035689.76     13521913.87
#Sta/Elev= 30
  4712.2  500.27  4736.6  501.03  4748.3   500.6  4767.9  500.77  4781.3     500
  4788.8  499.05  4799.2  498.76  4830.6  498.17  4893.5  498.01  4904.1  497.44
  4911.4   496.5  4916.7  496.59  4942.7  495.01    4948  495.47  4979.3  495.59
  4988.6  492.22  4993.5  491.07  4994.1  490.27  5004.3  490.27    5005  491.07
  5005.4  494.85  5030.9     496  5036.7  497.04    5042  496.78    5068  500.11
  5083.7  500.87  5099.3  500.28  5142.7  501.07  5165.5  500.79  5198.5  501.84
#Mann= 3 ,-1 , 0
  4712.2     .05       0  4993.5     .03       0    5005     .05       0
Bank Sta=4993.5,5005
XS Rating Curve= 0 ,0
Exp/Cntr=0.3,0.1

Type RM Length L Ch R = 1 ,2226    ,137,137,137
BEGIN DESCRIPTION:
Mapping XS f7d85178
END DESCRIPTION:
XS GIS Cut Line= 4
      2036095.37     13521733.12      2035948.85     13521627.85
      2035705.79     13521673.42      2035664.55     13521753.74
#Sta/Elev= 30
  4661.3  499.87  4738.5  499.05  4747.1  498.55  4803.6  498.27  4839.2  497.44
  4876.2  497.97    4890  496.58  4904.6  495.08  4909.7  495.29  4916.9  494.45
  4937.2  493.88  4947.4  494.57  4977.8  495.02  4988.1  492.83  4992.5  490.04
  4993.1  489.24  5003.3  489.24    5004  490.04  5014.9     492  5019.9  494.49
  5028.8  496.95  5049.1  497.07  5067.4  498.29    5099  498.44  5104.7  499.68
  5121.2  499.38  5126.9  500.27  5143.4  501.16    5149  500.67  5179.3  500.84
#Mann= 5 ,-1 , 0
  4661.3     .05       0    4890      .1       0  4977.8     .05       0
  4992.5     .03       0    5004     .05       0
Bank Sta=4992.5,5004
XS Rating Curve= 0 ,0
Exp/Cntr=0.3,0.1

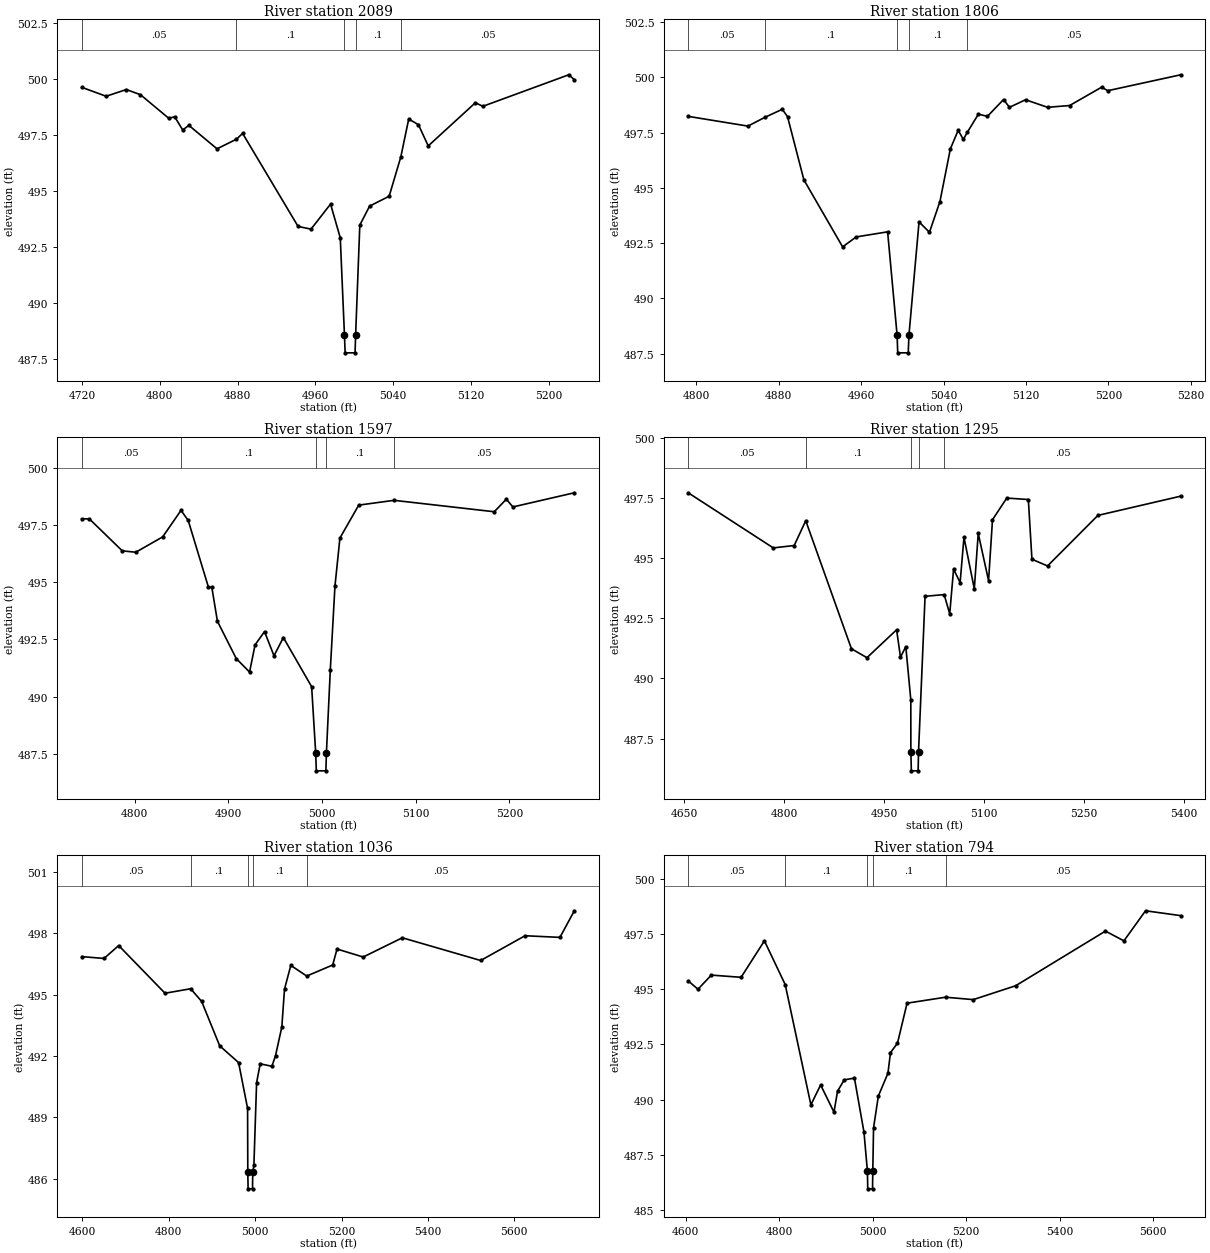
Type RM Length L Ch R = 1 ,2089    ,283,283,283
BEGIN DESCRIPTION:
Mapping XS a9c4fd39
END DESCRIPTION:
XS GIS Cut Line= 4
      2036078.39     13521626.47      2035957.31     13521532.74
       2035703.4     13521558.78      2035657.83     13521646.03
#Sta/Elev= 30
  4719.7  499.64  4744.8  499.24  4765.6  499.54  4780.1  499.31  4809.1  498.26
  4815.4  498.32  4823.6  497.73  4829.9  497.94  4858.9  496.89  4878.9  497.32
  4885.2  497.58  4942.3  493.42  4955.6   493.3  4975.7  494.42  4985.7  492.91
    4990  488.57  4990.7  487.77  5000.9  487.77  5001.5  488.57  5005.8  493.48
  5015.9  494.33    5036  494.77    5048  496.53  5056.1  498.22  5066.1  497.97
  5076.2  497.02  5124.7  498.95  5132.4  498.79  5220.8   500.2  5226.5  499.98
#Mann= 5 ,-1 , 0
  4719.7     .05       0  4878.9      .1       0    4990     .07       0
  5001.5      .1       0    5048     .05       0
Bank Sta=4990,5001.5
XS Rating Curve= 0 ,0
Exp/Cntr=0.3,0.1

Type RM Length L Ch R = 1 ,1806    ,209,209,209
BEGIN DESCRIPTION:
Mapping XS 088769a3
END DESCRIPTION:
XS GIS Cut Line= 4
      2036105.72     13521376.46      2036048.46      13521323.1
      2035846.63     13521286.64      2035679.34      13521386.5
#Sta/Elev= 30
    4792  498.23    4850  497.79  4866.2  498.18  4883.3  498.55  4888.4  498.22
  4904.3  495.36  4941.9  492.33  4955.1  492.78  4985.6  493.01  4994.8  488.34
  4995.4  487.54  5005.6  487.54  5006.3  488.34  5016.1  493.46  5026.2  492.99
  5036.4  494.38  5046.5  496.76  5054.1   497.6  5059.1  497.19    5063  497.51
  5073.7  498.33  5082.5  498.23  5098.1  498.99  5103.9  498.64  5119.5  498.98
  5140.9  498.64  5162.3  498.72  5193.4  499.55  5199.3  499.39  5270.2  500.11
#Mann= 5 ,-1 , 0
    4792     .05       0  4866.2      .1       0  4994.8     .07       0
  5006.3      .1       0    5063     .05       0
Bank Sta=4994.8,5006.3
XS Rating Curve= 0 ,0
Exp/Cntr=0.3,0.1

Type RM Length L Ch R = 1 ,1597    ,302,302,302
BEGIN DESCRIPTION:
Mapping XS 9c7cc612
END DESCRIPTION:
XS GIS Cut Line= 4
      2036198.21     13521242.39      2036110.96      13521134.3
      2035814.08     13521101.75      2035751.55     13521164.28
#Sta/Elev= 30
  4743.3  497.77  4751.4  497.77  4786.6  496.37    4801  496.31  4829.7  496.98
  4849.3  498.14    4857   497.7  4878.6  494.78  4882.2  494.78  4888.2  493.29
  4908.3  491.66  4922.5  491.07  4928.4  492.26  4938.5  492.84  4948.6  491.78
  4958.6  492.58  4988.8  490.43  4993.1  487.55  4993.8  486.75    5004  486.75
  5004.6  487.55  5008.7  491.14  5013.7  494.83    5019  496.93  5039.1  498.37
  5076.8  498.58  5183.8  498.08  5196.7  498.63  5203.7  498.29  5269.3  498.91
#Mann= 5 ,-1 , 0
  4743.3     .05       0  4849.3      .1       0  4993.1     .07       0
  5004.6      .1       0  5076.8     .05       0
Bank Sta=4993.1,5004.6
XS Rating Curve= 0 ,0
Exp/Cntr=0.3,0.1

Type RM Length L Ch R = 1 ,1295    ,259,259,259
BEGIN DESCRIPTION:
Mapping XS 9bed6d5c
END DESCRIPTION:
XS GIS Cut Line= 4
       2036328.1     13521152.68      2036331.35     13521008.36
      2036034.04     13520830.41      2035806.48      13520930.1
#Sta/Elev= 30
  4655.6  497.71  4783.3  495.42  4814.7  495.52    4832  496.55  4900.6  491.23
  4923.9  490.86  4968.4  492.02  4974.2  490.88  4982.2  491.32  4989.7  489.11
  4989.8  486.96  4990.5  486.16  5000.7  486.16  5001.3  486.96  5011.1  493.41
  5039.8  493.48  5048.1  492.68  5053.9  494.54  5063.7  493.98  5069.5  495.86
    5085  493.72  5090.9  496.02  5106.4  494.06  5112.3  496.59  5133.7  497.49
  5166.1  497.43  5171.5  494.95  5194.9  494.67  5270.5  496.77  5394.9  497.57
#Mann= 5 ,-1 , 0
  4655.6     .05       0    4832      .1       0  4989.8     .07       0
  5001.3      .1       0  5039.8     .05       0
Bank Sta=4989.8,5001.3
XS Rating Curve= 0 ,0
Exp/Cntr=0.3,0.1

Type RM Length L Ch R = 1 ,1036    ,242,242,242
BEGIN DESCRIPTION:
Mapping XS 278fd933
END DESCRIPTION:
XS GIS Cut Line= 4
      2036551.42     13521126.14      2036521.64     13520908.67
      2036301.59     13520744.61      2035659.72     13520824.46
#Sta/Elev= 30
  4598.3  496.86  4649.9  496.77  4683.9   497.4  4791.2  495.07  4850.6  495.29
    4876  494.67  4917.8   492.5  4961.6  491.68  4982.4  489.44  4982.9  486.31
  4983.6  485.51  4993.8  485.51  4994.4  486.31    4997  486.66  5003.3   490.7
  5011.6  491.62  5038.7   491.5  5047.1  492.02  5061.7  493.42  5067.9  495.27
  5082.5  496.43  5119.4  495.91  5179.5  496.45  5189.6  497.23  5250.1  496.84
  5340.8  497.78  5522.2  496.67    5625  497.88  5705.8   497.8  5739.1   499.1
#Mann= 5 ,-1 , 0
  4598.3     .05       0  4850.6      .1       0  4982.9     .07       0
  4994.4      .1       0  5119.4     .05       0
Bank Sta=4982.9,4994.4
XS Rating Curve= 0 ,0
Exp/Cntr=0.3,0.1

Type RM Length L Ch R = 1 ,794     ,672,672,672
BEGIN DESCRIPTION:
Mapping XS 5cdaac11
END DESCRIPTION:
XS GIS Cut Line= 4
      2036831.28     13520938.64      2036609.06     13520679.93
      2036429.94     13520640.13      2035904.17     13520698.18
#Sta/Elev= 30
  4605.6  495.37  4626.5  494.99  4655.1  495.63  4718.7  495.53  4768.6  497.18
  4813.1   495.2    4868  489.76  4888.8  490.66  4917.4  489.43    4925  490.38
  4939.3  490.89  4961.1  490.97  4981.5  488.53  4988.9  486.76  4989.6  485.96
  4999.8  485.96  5000.4  486.76    5002  488.72  5012.3  490.16  5032.8  491.19
  5038.2  492.12  5053.2  492.55  5073.7  494.36  5156.1  494.63  5215.3  494.52
  5306.1  495.15  5497.9  497.62  5537.5  497.18  5583.7  498.54  5659.1  498.32
#Mann= 5 ,-1 , 0
  4605.6     .05       0  4813.1      .1       0  4988.9     .07       0
  5000.4      .1       0  5156.1     .05       0
Bank Sta=4988.9,5000.4
XS Rating Curve= 0 ,0
Exp/Cntr=0.3,0.1

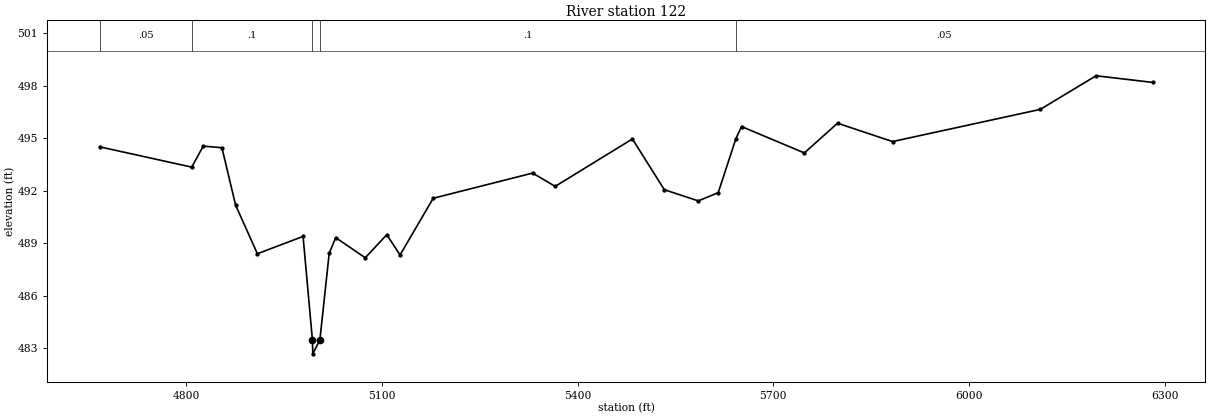
Type RM Length L Ch R = 1 ,122     ,0,0,0
BEGIN DESCRIPTION:
ELLIS Br 1.0
END DESCRIPTION:
XS GIS Cut Line= 4
      2036887.92     13520780.92      2037068.03     13520634.83
      2037067.21     13520459.45       2035879.4     13520669.89
#Sta/Elev= 30
  4667.8   494.5  4808.9  493.34  4826.5  494.54  4855.2  494.45  4876.1  491.17
  4909.5  488.39  4979.5  489.38  4993.8  483.47  4994.4  482.67  5005.3  483.47
  5019.5  488.41  5029.5  489.31  5074.8  488.16  5107.8  489.48  5128.1  488.32
  5178.9  491.56  5331.2     493  5365.8  492.24  5484.1  494.95    5533  492.05
  5585.1  491.41  5615.6  491.88  5642.6  494.96  5651.3  495.66  5747.6  494.15
  5798.4  495.85  5882.7   494.8  6109.1  496.64  6194.5  498.56  6281.4  498.18
#Mann= 5 ,-1 , 0
  4667.8     .05       0  4808.9      .1       0  4993.8     .07       0
  5005.3      .1       0  5642.6     .05       0
Bank Sta=4993.8,5005.3
XS Rating Curve= 0 ,0
Exp/Cntr=0.3,0.1
LCMann Table=0

Chan Stop Cuts=-1
Use User Specified Reach Order=0
Composite Channel Slope=5