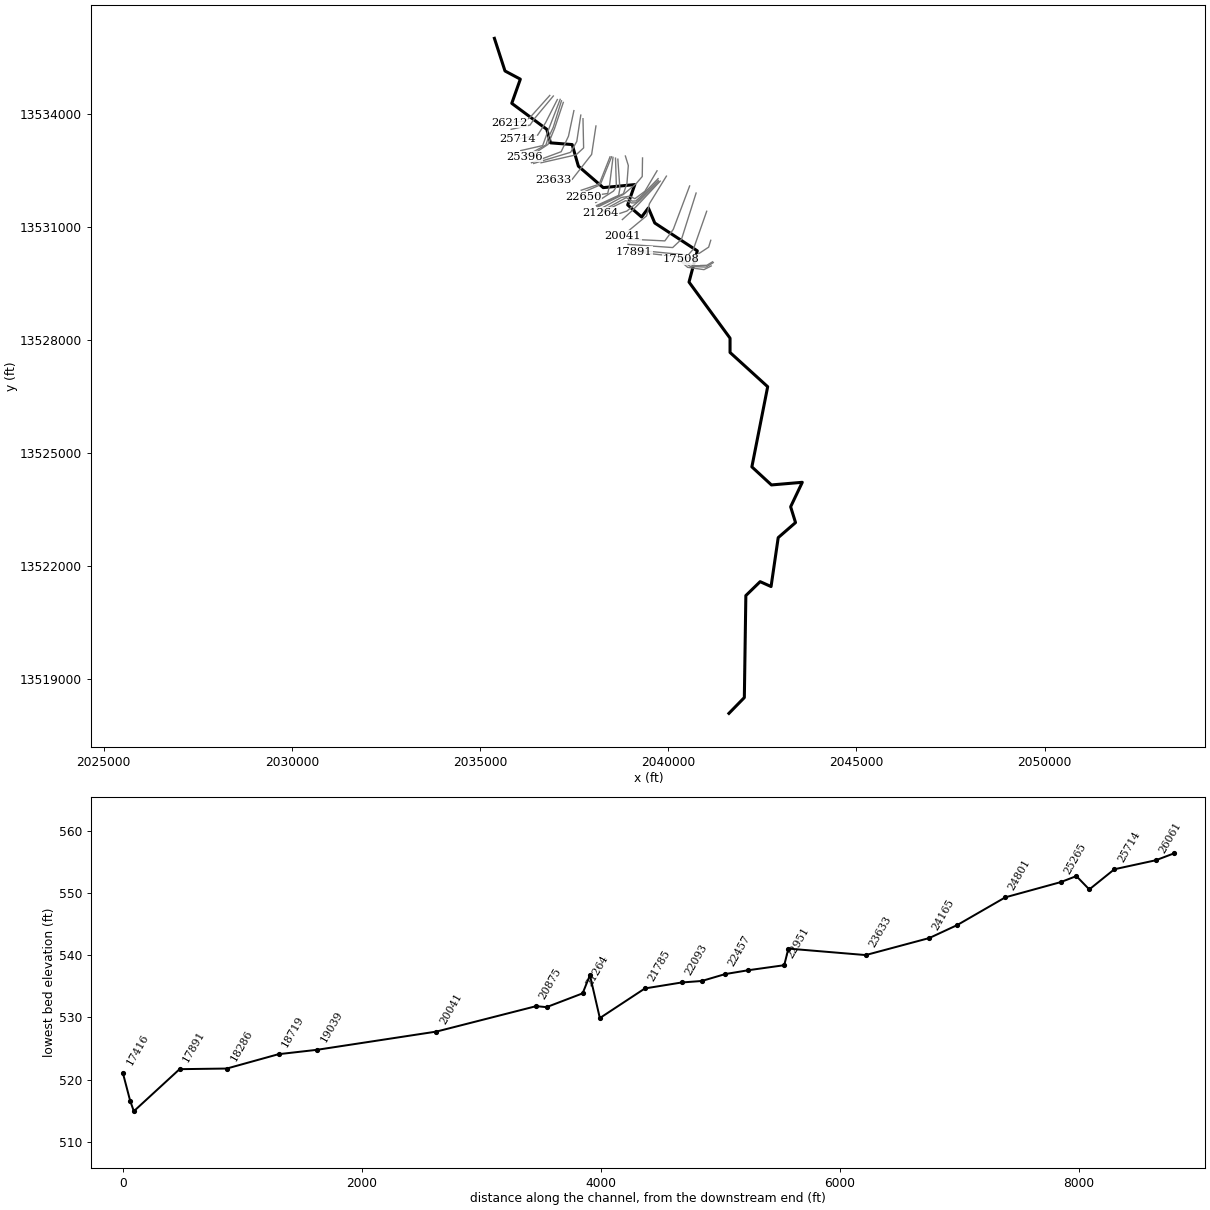
--- ELM Cr.prj (project) ---

Proj Title=ELM Cr Base Level Engineering
Current Plan=p01
Default Exp/Contr=0.3,0.1
English Units
Geom File=g01
Flow File=f01
Plan File=p01
BEGIN DESCRIPTION:
ELM Cr
END DESCRIPTION:

--- ELM Cr.p01 (plan) ---

Plan Title=Multiple Run
Short Identifier=Multiple
Geom File=g01
Flow File=f01
Subcritical Flow
K Sum by GR= 0
Std Step Tol= 0.01
Critical Tol= 0.01
Num of Std Step Trials= 20
Max Error Tol= 0.3
Flow Tol Ratio= 0.001
Split Flow NTrial= 30
Split Flow Tol= 0.02
Split Flow Ratio= 0.02
Log Output Level= 0
Friction Slope Method= 1
Unsteady Friction Slope Method= 2
Unsteady Bridges Friction Slope Method= 1
Parabolic Critical Depth
Global Vel Dist=  1 , 1 , 1
Global Log Level= 0
CheckData=True
Encroach Param= -1, 0, 0, 0
BEGIN DESCRIPTION:
Multiple Run
END DESCRIPTION:

--- ELM Cr.f01 (steady flow) ---

Flow Title=Multiple
Number of Profiles=7
Profile Names=10-year,25-year,50-year,1pct_min,100-year,1pct_plu,500-year
River Rch & RM= ELM Cr,Reach-1,26212
     155     208     250     151     301     600     439
River Rch & RM= ELM Cr,Reach-1,25714
     224     307     374     228     455     908     681
River Rch & RM= ELM Cr,Reach-1,21785
     314     438     540     332     663    1323    1014
River Rch & RM= ELM Cr,Reach-1,18286
     347     484     599     369     737    1470    1130
River Rch & RM= ELM Cr,Reach-1,12908
     541     771     966     602    1201    2397    1887
River Rch & RM= ELM Cr,Reach-1,8649
     695     999    1260     789    1575    3142    2500
Boundary for River Rch & Prof#=ELM Cr,Reach-1,1
Up Type=0
Dn Type=3
Dn Slope=0.005
Boundary for River Rch & Prof#=ELM Cr,Reach-1,2
Up Type=0
Dn Type=3
Dn Slope=0.005
Boundary for River Rch & Prof#=ELM Cr,Reach-1,3
Up Type=0
Dn Type=3
Dn Slope=0.005
Boundary for River Rch & Prof#=ELM Cr,Reach-1,4
Up Type=0
Dn Type=3
Dn Slope=0.005
Boundary for River Rch & Prof#=ELM Cr,Reach-1,5
Up Type=0
Dn Type=3
Dn Slope=0.005
Boundary for River Rch & Prof#=ELM Cr,Reach-1,6
Up Type=0
Dn Type=3
Dn Slope=0.005
Boundary for River Rch & Prof#=ELM Cr,Reach-1,7
Up Type=0
Dn Type=3
Dn Slope=0.005

--- ELM Cr.g01 (geometry) ---

Geom Title=Existing Conditions

River Reach=ELM Cr,Reach-1
Reach XY= 30
      2035379.64     13536011.62      2035660.80     13535144.54
      2036068.53     13534926.90      2035840.80     13534284.54
      2036770.80     13533594.54      2036870.80     13533234.54
      2037445.60     13533189.24      2037610.80     13532614.54
      2038270.80     13532044.54      2039110.49     13532125.22
      2038920.80     13531584.54      2039290.80     13531264.54
      2039470.80     13531504.54      2039640.80     13531104.54
      2040770.86     13530364.55      2040550.80     13529534.54
      2041640.80     13528044.54      2041640.80     13527664.54
      2042640.80     13526754.54      2042220.80     13524624.54
      2042740.80     13524144.54      2043560.80     13524214.54
      2043250.80     13523564.54      2043380.80     13523144.54
      2042920.80     13522744.54      2042730.80     13521444.54
      2042440.80     13521574.54      2042060.80     13521204.54
      2042020.80     13518494.54      2041610.80     13518074.54

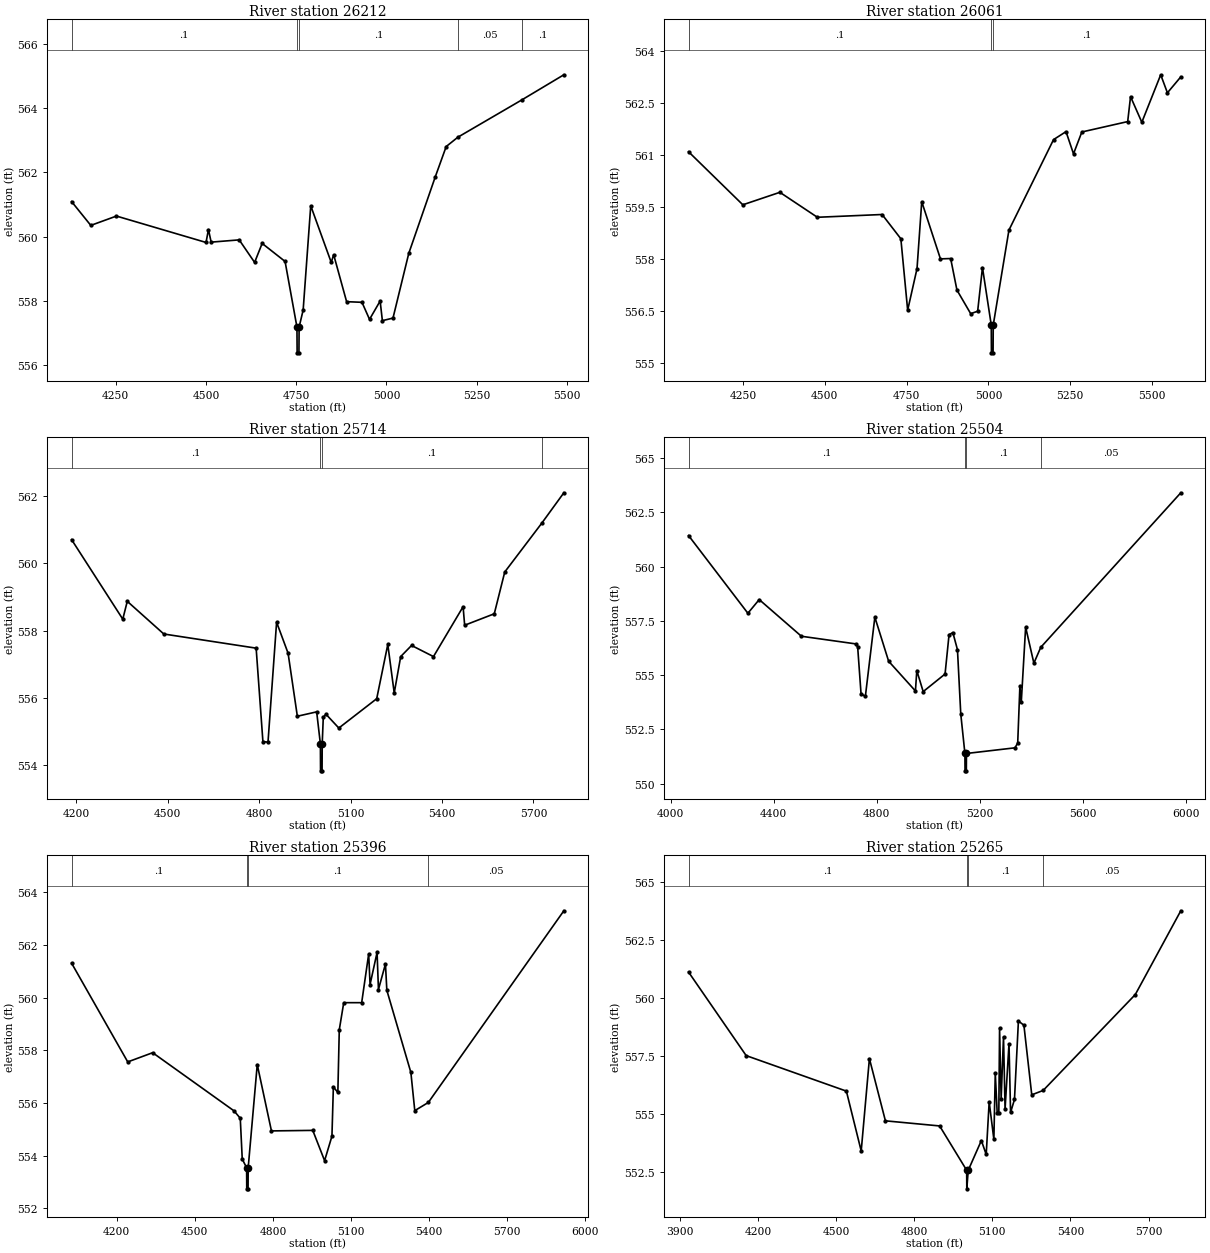
Type RM Length L Ch R = 1,26212,151,151,151
BEGIN DESCRIPTION:
Mapping XS 37848afa
END DESCRIPTION:
XS GIS Cut Line= 4
      2036851.13     13534494.57      2036334.20     13533917.54
      2036191.14     13533814.06      2035780.81     13533770.63
#Sta/Elev= 30
  4127.6  561.09  4180.8  560.35  4251.9  560.64  4500.1  559.82  4506.8  560.22
  4514.3  559.83  4592.0  559.90  4634.7  559.20  4655.6  559.79  4719.1  559.23
  4752.0  557.19  4752.5  556.39  4757.5  556.39  4758.0  557.19  4769.2  557.72
  4790.2  560.96  4847.0  559.20  4853.7  559.44  4889.6  557.98  4932.2  557.96
  4953.1  557.43  4982.5  558.00  4988.7  557.39  5018.1  557.47  5061.8  559.48
  5135.3  561.86  5165.5  562.80  5197.8  563.09  5375.2  564.25  5491.5  565.03
#Mann=5,-1,0
  4127.6     0.1       0  4752.0    0.07       0  4758.0     0.1       0
  5197.8    0.05       0  5375.2     0.1       0
Bank Sta=4752,4758
Exp/Cntr=0.3,0.1

Type RM Length L Ch R = 1,26061,347,347,347
BEGIN DESCRIPTION:
Mapping XS f29ddcf7
END DESCRIPTION:
XS GIS Cut Line= 4
      2036944.90     13534478.96      2036434.65     13533866.85
      2036326.56     13533706.42      2035825.14     13533593.56
#Sta/Elev= 30
  4083.4  561.09  4249.3  559.56  4362.5  559.92  4477.1  559.20  4674.9  559.28
  4732.2  558.58  4753.0  556.52  4781.6  557.72  4796.0  559.65  4853.2  558.00
  4884.4  558.01  4903.6  557.10  4945.6  556.42  4966.9  556.49  4981.6  557.75
  5008.5  556.09  5009.0  555.29  5014.0  555.29  5014.5  556.09  5062.5  558.83
  5198.8  561.44  5236.9  561.67  5259.8  561.03  5285.3  561.66  5425.4  561.96
  5434.1  562.68  5468.6  561.94  5526.3  563.31  5546.8  562.79  5587.7  563.25
#Mann=3,-1,0
  4083.4     0.1       0  5008.5    0.07       0  5014.5     0.1       0
Bank Sta=5008.5,5014.5
Exp/Cntr=0.3,0.1

Type RM Length L Ch R = 1,25714,210,210,210
BEGIN DESCRIPTION:
Mapping XS f507b2a0
END DESCRIPTION:
XS GIS Cut Line= 4
      2037051.70     13534384.82      2036738.47     13533767.89
      2036528.40     13533439.77      2036004.83     13533335.75
#Sta/Elev= 30
  4184.3  560.70  4352.3  558.34  4367.0  558.87  4486.9  557.90  4789.9  557.48
  4812.1  554.71  4828.8  554.69  4857.0  558.25  4894.7  557.33  4925.1  555.46
  4988.5  555.59  5000.7  554.64  5001.2  553.84  5006.2  553.84  5006.7  554.64
  5010.2  555.43  5019.0  555.52  5061.2  555.11  5185.5  555.98  5221.9  557.59
  5243.0  556.15  5264.2  557.23  5299.9  557.56  5371.8  557.23  5469.0  558.71
  5474.1  558.16  5571.3  558.50  5605.7  559.74  5726.5  561.18  5799.6  562.09
#Mann=4,-1,0
  4184.3     0.1       0  5000.7    0.07       0  5006.7     0.1       0
  5726.5    0.05       0
Bank Sta=5000.7,5006.7
Exp/Cntr=0.3,0.1

Type RM Length L Ch R = 1,25504,108,108,108
BEGIN DESCRIPTION:
Mapping XS 128b781b
END DESCRIPTION:
XS GIS Cut Line= 5
      2037127.19     13534389.96      2036860.00     13533696.71
      2036762.78     13533441.51      2036662.08     13533161.99
      2036078.87     13533028.71
#Sta/Elev= 30
  4070.0  561.43  4300.4  557.85  4344.4  558.48  4508.2  556.79  4718.3  556.44
  4726.6  556.31  4739.8  554.14  4756.6  554.02  4793.4  557.67  4846.9  555.64
  4951.0  554.27  4956.3  555.21  4981.1  554.24  5066.0  555.05  5081.5  556.86
  5096.3  556.96  5114.2  556.17  5127.0  553.21  5143.1  551.39  5143.6  550.59
  5148.6  550.59  5149.1  551.39  5337.4  551.65  5348.1  551.87  5356.6  554.50
  5361.9  553.74  5378.9  557.21  5410.9  555.55  5437.6  556.28  5981.4  563.40
#Mann=4,-1,0
  4070.0     0.1       0  5143.1    0.07       0  5149.1     0.1       0
  5437.6    0.05       0
Bank Sta=5143.1,5149.1
Exp/Cntr=0.3,0.1

Type RM Length L Ch R = 1,25396,131,131,131
BEGIN DESCRIPTION:
Mapping XS f8a8f0f9
END DESCRIPTION:
XS GIS Cut Line= 5
      2037161.06     13534350.94      2036941.60     13533642.89
      2036807.91     13533363.38      2036749.05     13533178.78
      2036182.63     13532869.57
#Sta/Elev= 30
  4026.9  561.31  4242.5  557.56  4338.2  557.91  4650.8  555.70  4674.6  555.42
  4682.2  553.87  4699.0  553.54  4699.5  552.74  4704.5  552.74  4705.0  553.54
  4739.8  557.46  4794.3  554.94  4953.0  554.96  4998.4  553.81  5026.6  554.74
  5032.1  556.61  5049.3  556.40  5054.8  558.78  5071.9  559.81  5140.8  559.81
  5167.7  561.66  5173.0  560.50  5199.9  561.72  5205.2  560.31  5232.1  561.28
  5237.4  560.28  5329.7  557.16  5344.7  555.71  5396.7  556.02  5917.1  563.30
#Mann=4,-1,0
  4026.9     0.1       0  4699.0    0.07       0  4705.0     0.1       0
  5396.7    0.05       0
Bank Sta=4699,4705
Exp/Cntr=0.3,0.1

Type RM Length L Ch R = 1,25265,464,464,464
BEGIN DESCRIPTION:
Mapping XS 6df89073
END DESCRIPTION:
XS GIS Cut Line= 4
      2037210.54     13534309.30      2036978.05     13533616.85
      2036804.44     13533193.24      2036219.14     13532807.18
#Sta/Elev= 30
  3934.0  561.11  4155.2  557.51  4539.8  555.98  4596.7  553.40  4628.2  557.38
  4689.6  554.70  4897.7  554.48  5001.5  552.57  5002.0  551.77  5007.5  552.57
  5057.9  553.85  5076.5  553.25  5087.9  555.52  5105.9  553.90  5111.3  556.76
  5118.6  555.05  5124.9  555.05  5127.8  558.68  5133.8  555.65  5142.9  558.32
  5148.9  555.21  5164.0  558.02  5170.0  555.06  5185.0  555.62  5200.1  559.00
  5221.2  558.82  5251.3  555.82  5295.2  556.01  5648.7  560.14  5823.4  563.75
#Mann=4,-1,0
  3934.0     0.1       0  5001.5    0.07       0  5007.5     0.1       0
  5295.2    0.05       0
Bank Sta=5001.5,5007.5
Exp/Cntr=0.3,0.1

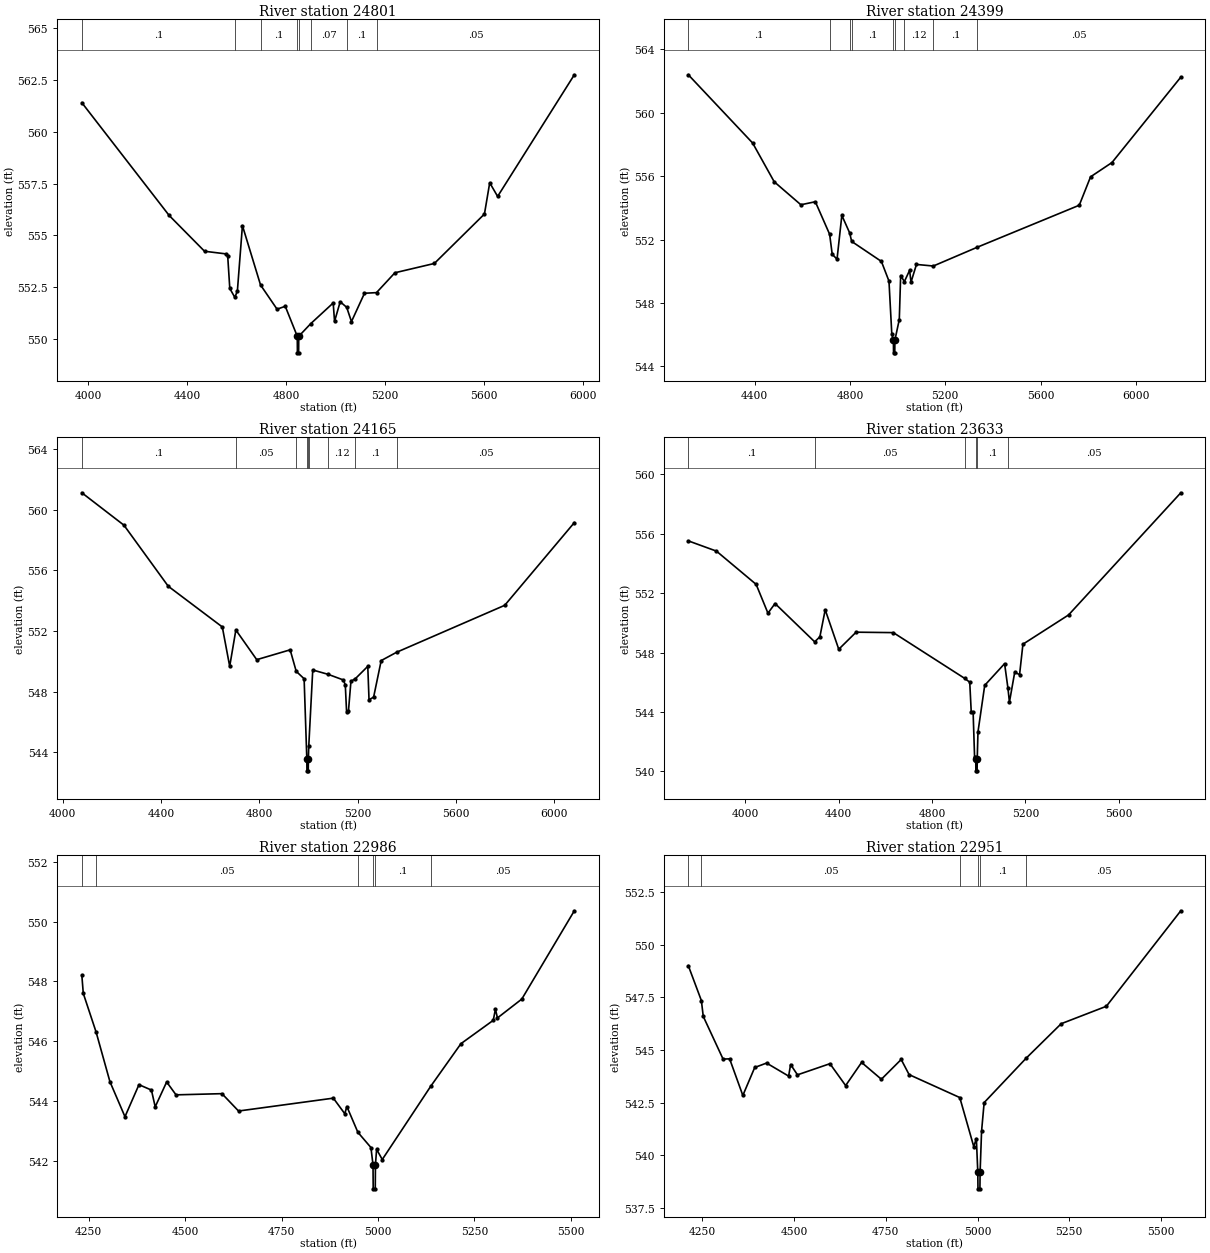
Type RM Length L Ch R = 1,24801,402,402,402
BEGIN DESCRIPTION:
Mapping XS d1ccedd9
END DESCRIPTION:
XS GIS Cut Line= 4
      2037491.78     13534090.48      2037347.85     13533411.99
      2037153.40     13532998.80      2036364.22     13532705.12
#Sta/Elev= 30
  3973.7  561.41  4326.9  555.96  4470.0  554.23  4558.7  554.10  4563.8  553.99
  4572.2  552.43  4592.7  552.00  4602.9  552.31  4623.3  555.47  4696.6  552.60
  4763.4  551.43  4796.6  551.57  4845.2  550.12  4845.7  549.32  4850.7  549.32
  4851.2  550.12  4899.6  550.73  4990.5  551.73  4996.0  550.84  5018.8  551.79
  5045.1  551.52  5064.4  550.83  5117.1  552.20  5165.7  552.23  5240.1  553.19
  5399.7  553.64  5602.4  556.03  5623.7  557.54  5655.7  556.88  5966.0  562.76
#Mann=8,-1,0
  3973.7     0.1       0  4592.7    0.08       0  4696.6     0.1       0
  4845.2    0.07       0  4851.2     0.1       0  4899.6    0.07       0
  5045.1     0.1       0  5165.7    0.05       0
Bank Sta=4845.2,4851.2
Exp/Cntr=0.3,0.1

Type RM Length L Ch R = 1,24399,234,234,234
BEGIN DESCRIPTION:
Mapping XS fda3fd7e
END DESCRIPTION:
XS GIS Cut Line= 4
      2037674.79     13533971.71      2037568.33     13533271.37
      2037405.14     13532983.17      2036422.59     13532686.97
#Sta/Elev= 30
  4122.3  562.38  4392.1  558.08  4482.5  555.64  4594.4  554.19  4655.1  554.38
  4715.1  552.33  4725.9  551.07  4746.1  550.76  4766.3  553.52  4799.0  552.42
  4807.5  551.88  4932.2  550.62  4964.0  549.38  4975.9  546.03  4982.6  545.66
  4983.1  544.86  4988.3  544.86  4988.8  545.66  5007.3  546.96  5013.0  549.73
  5028.6  549.35  5050.6  550.06  5056.4  549.31  5079.3  550.43  5150.0  550.33
  5335.3  551.52  5762.2  554.16  5809.6  555.95  5899.4  556.85  6188.1  562.23
#Mann=9,-1,0
  4122.3     0.1       0  4715.1    0.05       0  4799.0    0.08       0
  4807.5     0.1       0  4982.6    0.07       0  4988.8     0.1       0
  5028.6    0.12       0  5150.0     0.1       0  5335.3    0.05       0
Bank Sta=4982.6,4988.8
Exp/Cntr=0.3,0.1

Type RM Length L Ch R = 1,24165,532,532,532
BEGIN DESCRIPTION:
Mapping XS f8dc9dc2
END DESCRIPTION:
XS GIS Cut Line= 4
      2037733.38     13533876.17      2037750.00     13533100.00
      2037550.00     13532915.75      2036618.93     13532704.56
#Sta/Elev= 30
  4078.3  561.13  4249.5  558.99  4429.6  554.96  4649.6  552.27  4679.6  549.67
  4704.7  552.07  4789.6  550.11  4925.5  550.76  4950.2  549.34  4982.3  548.85
  4993.3  543.57  4993.8  542.77  4999.1  542.77  4999.6  543.57  5001.2  544.40
  5017.4  549.43  5080.2  549.14  5142.0  548.77  5149.8  548.44  5155.0  546.67
  5162.5  546.69  5172.7  548.68  5191.0  548.86  5241.2  549.67  5246.3  547.46
  5265.0  547.64  5295.8  550.05  5358.5  550.60  5798.2  553.70  6081.3  559.16
#Mann=9,-1,0
  4078.3     0.1       0  4704.7    0.05       0  4950.2     0.1       0
  4993.3    0.07       0  4999.6     0.1       0  5001.2    0.07       0
  5080.2    0.12       0  5191.0     0.1       0  5358.5    0.05       0
Bank Sta=4993.3,4999.6
Exp/Cntr=0.3,0.1

Type RM Length L Ch R = 1,23633,647,647,647
BEGIN DESCRIPTION:
Mapping XS e463f702
END DESCRIPTION:
XS GIS Cut Line= 4
      2038077.60     13533682.35      2037963.02     13532927.19
      2037442.18     13532260.52      2036942.14     13532244.89
#Sta/Elev= 30
  3755.4  555.52  3875.9  554.83  4046.0  552.59  4096.6  550.65  4127.0  551.30
  4296.8  548.72  4319.1  549.06  4341.9  550.88  4400.0  548.22  4474.3  549.37
  4633.8  549.34  4940.3  546.25  4961.2  546.00  4967.6  544.00  4975.7  543.97
  4982.0  540.93  4987.0  540.83  4987.5  540.03  4992.8  540.03  4993.3  540.83
  4996.5  542.65  5025.4  545.79  5110.5  547.25  5124.7  545.62  5131.3  544.66
  5153.9  546.67  5174.7  546.51  5189.1  548.56  5384.6  550.53  5865.5  558.76
#Mann=6,-1,0
  3755.4     0.1       0  4296.8    0.05       0  4940.3     0.1       0
  4987.0    0.07       0  4993.3     0.1       0  5124.7    0.05       0
Bank Sta=4987,4993.3
Exp/Cntr=0.3,0.1

Type RM Length L Ch R = 1,22986,35,35,35
BEGIN DESCRIPTION:
Mapping XS fe0ac62e
END DESCRIPTION:
XS GIS Cut Line= 4
      2038451.68     13532862.72      2038177.69     13532171.48
      2038095.66     13532112.45      2037685.65     13531975.17
#Sta/Elev= 30
  4232.2  548.20  4235.9  547.60  4269.1  546.31  4305.0  544.65  4344.0  543.48
  4380.3  544.55  4412.6  544.37  4422.4  543.81  4452.1  544.64  4476.4  544.21
  4595.5  544.25  4638.5  543.67  4884.3  544.10  4914.0  543.58  4919.4  543.82
  4947.9  542.96  4981.8  542.45  4987.2  541.87  4987.7  541.07  4993.0  541.07
  4993.5  541.87  4996.5  542.39  5011.2  542.05  5137.0  544.50  5215.2  545.92
  5299.0  546.70  5304.6  547.07  5309.9  546.78  5373.0  547.41  5509.2  550.36
#Mann=6,-1,0
  4232.2    0.08       0  4269.1    0.05       0  4947.9     0.1       0
  4987.2    0.07       0  4993.5     0.1       0  5137.0    0.05       0
Bank Sta=4987.2,4993.5
Exp/Cntr=0.3,0.1

Type RM Length L Ch R = 1,22951,301,301,301
BEGIN DESCRIPTION:
Mapping XS 543dcc27
END DESCRIPTION:
XS GIS Cut Line= 4
      2038492.92     13532862.74      2038208.88     13532161.64
      2038141.17     13532095.50      2037689.96     13531901.38
#Sta/Elev= 30
  4211.6  549.01  4247.2  547.35  4252.3  546.60  4306.3  544.57  4324.2  544.58
  4360.2  542.84  4392.6  544.17  4424.9  544.38  4485.0  543.76  4490.4  544.31
  4509.1  543.82  4597.6  544.35  4640.4  543.31  4683.9  544.41  4737.8  543.61
  4791.8  544.55  4813.4  543.83  4951.5  542.74  4989.6  540.41  4996.7  540.79
  5000.6  539.20  5001.1  538.40  5006.4  538.40  5006.9  539.20  5010.9  541.14
  5017.9  542.50  5132.9  544.62  5227.9  546.25  5351.0  547.08  5553.9  551.62
#Mann=6,-1,0
  4211.6     0.1       0  4247.2    0.05       0  4951.5     0.1       0
  5000.6    0.07       0  5006.9     0.1       0  5132.9    0.05       0
Bank Sta=5000.6,5006.9
Exp/Cntr=0.3,0.1

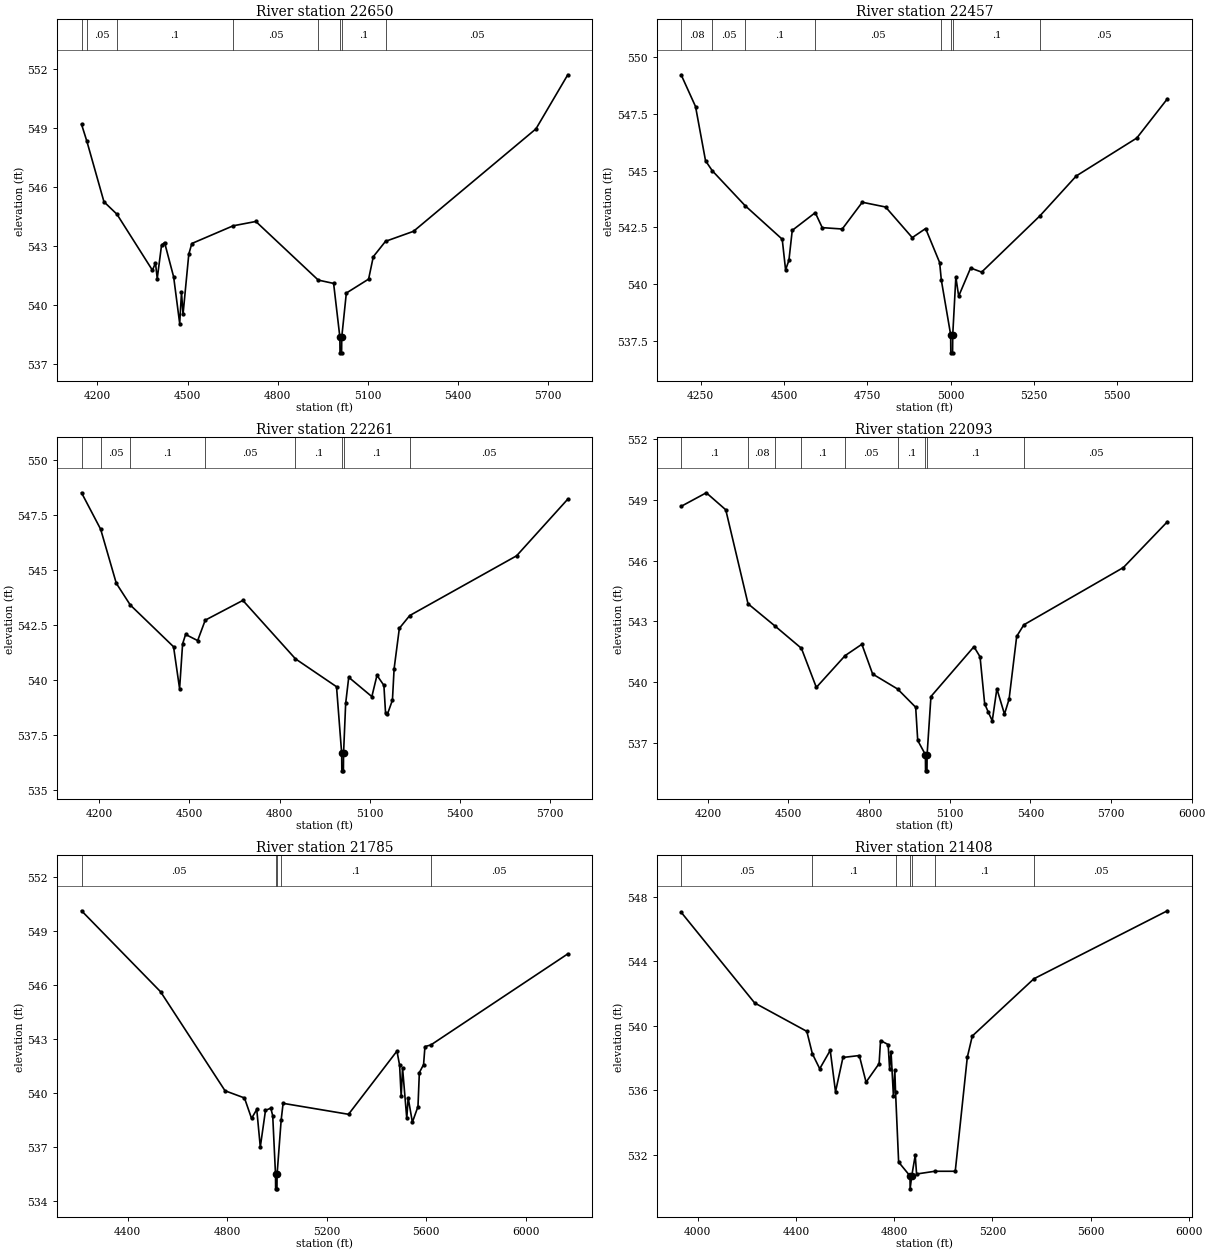
Type RM Length L Ch R = 1,22650,193,193,193
BEGIN DESCRIPTION:
Mapping XS 350ba919
END DESCRIPTION:
XS GIS Cut Line= 4
      2038531.26     13532849.04      2038435.79     13532083.22
      2038389.78     13531888.77      2037750.28     13531798.52
#Sta/Elev= 30
  4147.4  549.21  4165.3  548.34  4222.0  545.27  4265.1  544.64  4383.2  541.79
  4393.3  542.16  4399.2  541.37  4413.5  543.06  4423.6  543.20  4453.8  541.45
  4473.9  539.08  4479.9  540.67  4485.0  539.55  4504.2  542.61  4514.3  543.15
  4651.7  544.05  4727.2  544.27  4934.8  541.29  4985.9  541.12  5006.7  538.39
  5007.2  537.59  5012.5  537.59  5013.0  538.39  5028.2  540.63  5102.3  541.34
  5117.9  542.48  5158.5  543.26  5251.7  543.77  5659.0  548.98  5764.8  551.73
#Mann=8,-1,0
  4147.4     0.1       0  4165.3    0.05       0  4265.1     0.1       0
  4651.7    0.05       0  4934.8     0.1       0  5006.7    0.07       0
  5013.0     0.1       0  5158.5    0.05       0
Bank Sta=5006.7,5013
Exp/Cntr=0.3,0.1

Type RM Length L Ch R = 1,22457,196,196,196
BEGIN DESCRIPTION:
Mapping XS 2d9f6acf
END DESCRIPTION:
XS GIS Cut Line= 4
      2038597.23     13532828.21      2038620.68     13532064.99
      2038543.43     13531953.01      2038073.19     13531650.06
#Sta/Elev= 30
  4191.1  549.23  4234.3  547.83  4264.3  545.44  4284.5  545.00  4383.0  543.46
  4494.4  541.98  4504.5  540.63  4514.5  541.05  4524.5  542.37  4593.5  543.15
  4614.5  542.49  4674.5  542.43  4734.6  543.61  4804.6  543.40  4884.6  542.05
  4924.7  542.45  4966.8  540.95  4971.8  540.18  4999.8  537.77  5000.3  536.97
  5005.6  536.97  5006.1  537.77  5015.4  540.31  5023.9  539.47  5059.7  540.71
  5092.8  540.53  5267.7  543.01  5376.8  544.77  5558.3  546.44  5650.1  548.17
#Mann=8,-1,0
  4191.1    0.08       0  4284.5    0.05       0  4383.0     0.1       0
  4593.5    0.05       0  4971.8     0.1       0  4999.8    0.07       0
  5006.1     0.1       0  5267.7    0.05       0
Bank Sta=4999.8,5006.1
Exp/Cntr=0.3,0.1

Type RM Length L Ch R = 1,22261,168,168,168
BEGIN DESCRIPTION:
Mapping XS df7e0e07
END DESCRIPTION:
XS GIS Cut Line= 4
      2038659.73     13532800.37      2038713.57     13532024.19
      2038681.17     13531838.40      2038089.47     13531567.03
#Sta/Elev= 30
  4141.1  548.52  4204.7  546.86  4256.7  544.40  4303.3  543.41  4447.2  541.51
  4467.3  539.60  4477.3  541.64  4487.3  542.07  4527.4  541.79  4552.6  542.72
  4677.8  543.62  4852.7  540.96  4989.4  539.69  5006.5  536.66  5007.0  535.86
  5012.3  535.86  5012.8  536.66  5019.8  538.93  5030.0  540.12  5106.9  539.24
  5124.0  540.21  5147.0  539.75  5152.5  538.49  5158.5  538.43  5175.4  539.08
  5180.9  540.50  5198.4  542.35  5232.9  542.93  5588.4  545.65  5758.7  548.23
#Mann=8,-1,0
  4141.1    0.08       0  4204.7    0.05       0  4303.3     0.1       0
  4552.6    0.05       0  4852.7     0.1       0  5006.5    0.07       0
  5012.8     0.1       0  5232.9    0.05       0
Bank Sta=5006.5,5012.8
Exp/Cntr=0.3,0.1

Type RM Length L Ch R = 1,22093,308,308,308
BEGIN DESCRIPTION:
Mapping XS 3d020b0b
END DESCRIPTION:
XS GIS Cut Line= 5
      2038859.69     13532884.43      2038937.81     13532631.85
      2038901.35     13532152.69      2038807.60     13531884.46
      2038103.38     13531549.24
#Sta/Elev= 30
  4100.6  548.68  4194.2  549.35  4266.6  548.51  4349.4  543.87  4449.0  542.78
  4548.1  541.67  4603.6  539.74  4710.7  541.31  4773.0  541.87  4813.1  540.40
  4906.0  539.66  4973.2  538.76  4980.8  537.12  5009.4  536.42  5009.9  535.62
  5015.2  535.62  5015.7  536.42  5030.0  539.29  5190.0  541.75  5212.7  541.25
  5229.9  538.93  5243.3  538.52  5258.1  538.09  5275.3  539.67  5303.6  538.42
  5320.7  539.16  5349.0  542.26  5375.6  542.83  5746.1  545.66  5909.6  547.92
#Mann=9,-1,0
  4100.6     0.1       0  4349.4    0.08       0  4449.0    0.05       0
  4548.1     0.1       0  4710.7    0.05       0  4906.0     0.1       0
  5009.4    0.07       0  5015.7     0.1       0  5375.6    0.05       0
Bank Sta=5009.4,5015.7
Exp/Cntr=0.3,0.1

Type RM Length L Ch R = 1,21785,377,377,377
BEGIN DESCRIPTION:
Mapping XS dab22082
END DESCRIPTION:
XS GIS Cut Line= 5
      2039315.41     13532832.42      2039307.60     13532340.19
      2039140.93     13532144.87      2038807.60     13531863.62
      2038118.71     13531525.68
#Sta/Elev= 30
  4215.4  550.14  4532.9  545.63  4791.6  540.12  4869.6  539.72  4898.1  538.58
  4919.0  539.08  4933.2  536.99  4954.1  539.03  4975.4  539.15  4983.1  538.73
  4994.3  535.46  4994.8  534.66  5000.1  534.66  5000.6  535.46  5017.0  538.49
  5024.8  539.42  5287.5  538.81  5482.0  542.33  5492.6  541.54  5498.9  539.81
  5504.5  541.38  5521.4  538.58  5527.0  539.73  5543.9  538.37  5566.4  539.24
  5571.9  541.13  5588.9  541.58  5594.4  542.58  5618.1  542.67  6167.9  547.74
#Mann=5,-1,0
  4215.4    0.05       0  4994.3    0.03       0  5000.6    0.05       0
  5017.0     0.1       0  5618.1    0.05       0
Bank Sta=4994.3,5000.6
Exp/Cntr=0.3,0.1

Type RM Length L Ch R = 1,21408,83,83,83
BEGIN DESCRIPTION:
Mapping XS 119aaedb
END DESCRIPTION:
XS GIS Cut Line= 6
      2039700.84     13532491.24      2039376.76     13531946.06
      2039113.09     13531750.75      2038969.86     13531816.94
      2038752.91     13531782.89      2038199.15     13531481.31
#Sta/Elev= 30
  3932.1  547.05  4231.7  541.42  4444.0  539.66  4466.6  538.27  4496.6  537.34
  4539.4  538.48  4560.9  535.91  4591.2  538.04  4657.8  538.16  4685.3  536.51
  4738.5  537.66  4744.3  539.09  4775.3  538.84  4781.2  537.33  4787.0  538.41
  4796.7  535.67  4802.5  537.24  4805.4  535.91  4818.0  531.55  4864.3  530.69
  4864.8  529.89  4871.4  530.69  4885.6  531.97  4891.1  530.81  4965.3  530.98
  5048.6  530.98  5097.7  538.05  5118.0  539.37  5368.8  542.92  5912.6  547.14
#Mann=7,-1,0
  3932.1    0.05       0  4466.6     0.1       0  4805.4    0.05       0
  4864.3    0.07       0  4871.4    0.05       0  4965.3     0.1       0
  5368.8    0.05       0
Bank Sta=4864.3,4871.4
Exp/Cntr=0.3,0.1

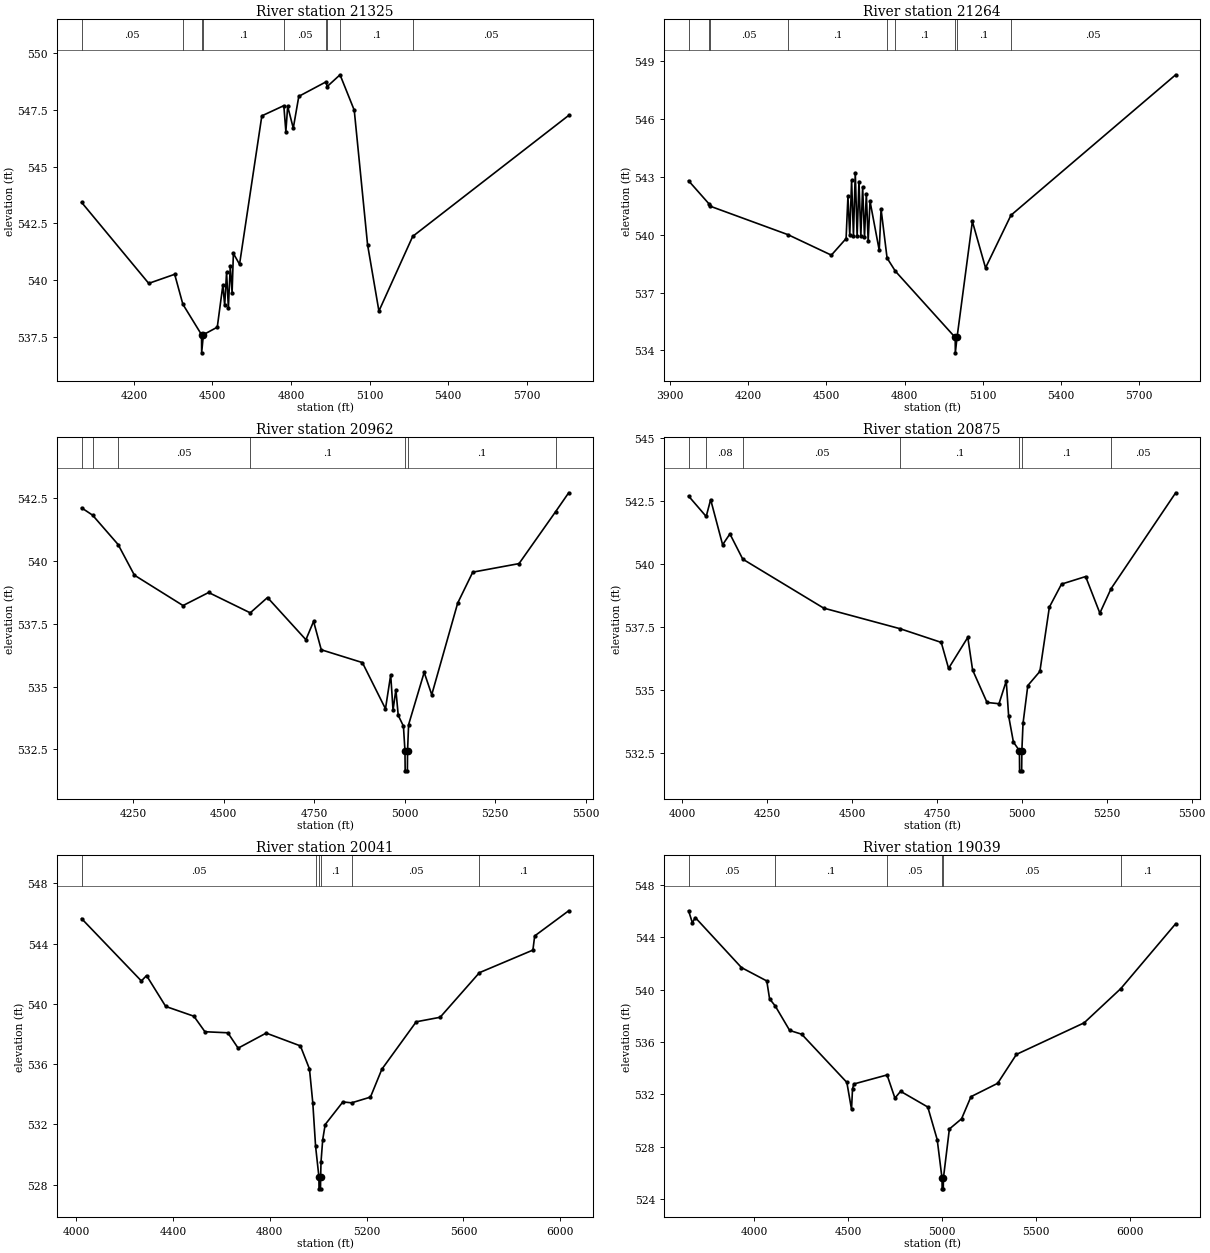
Type RM Length L Ch R = 1,21325,61,61,61
BEGIN DESCRIPTION:
Mapping XS 209bc713
END DESCRIPTION:
XS GIS Cut Line= 6
      2039729.47     13532282.89      2039323.22     13531863.62
      2039139.13     13531691.07      2039039.30     13531686.73
      2038880.88     13531778.96      2038232.04     13531423.50
#Sta/Elev= 30
  4000.6  543.43  4256.9  539.86  4355.9  540.26  4387.2  538.94  4458.4  537.60
  4458.9  536.80  4465.5  537.60  4518.5  537.93  4539.8  539.78  4546.8  538.89
  4554.0  540.35  4560.9  538.79  4568.1  540.61  4575.1  539.45  4580.0  541.18
  4603.5  540.70  4688.6  547.24  4772.5  547.69  4780.3  546.55  4787.2  547.66
  4808.6  546.70  4829.7  548.10  4933.8  548.74  4937.8  548.53  4987.1  549.05
  5041.3  547.49  5092.1  541.57  5135.5  538.64  5264.4  541.93  5859.8  547.26
#Mann=9,-1,0
  4000.6    0.05       0  4387.2     0.1       0  4458.4    0.07       0
  4465.5     0.1       0  4772.5    0.05       0  4933.8     0.1       0
  4937.8    0.05       0  4987.1     0.1       0  5264.4    0.05       0
Bank Sta=4458.4,4465.5
Exp/Cntr=0.3,0.1

Type RM Length L Ch R = 1,21264,302,302,302
BEGIN DESCRIPTION:
Mapping XS 6a2f46cd
END DESCRIPTION:
XS GIS Cut Line= 5
      2039732.05     13532233.39      2039139.85     13531641.74
      2039029.17     13531637.40      2038869.66     13531699.25
      2038194.24     13531369.43
#Sta/Elev= 30
  3970.6  542.80  4050.4  541.58  4053.7  541.48  4352.8  540.00  4518.9  538.94
  4575.5  539.80  4582.6  541.99  4589.6  539.98  4596.7  542.83  4603.8  539.95
  4610.8  543.22  4617.9  539.91  4625.0  542.76  4632.1  539.92  4639.1  542.48
  4646.2  539.87  4653.3  542.13  4660.3  539.66  4667.4  541.74  4702.8  539.19
  4709.8  541.33  4732.9  538.79  4764.6  538.11  4994.5  534.67  4995.0  533.87
  5001.6  534.67  5060.5  540.69  5111.0  538.28  5208.6  541.01  5841.2  548.30
#Mann=9,-1,0
  3970.6    0.05       0  4050.4    0.08       0  4053.7    0.05       0
  4352.8     0.1       0  4732.9    0.05       0  4764.6     0.1       0
  4994.5    0.07       0  5001.6     0.1       0  5208.6    0.05       0
Bank Sta=4994.5,5001.6
Exp/Cntr=0.3,0.1

Type RM Length L Ch R = 1,20962,87,87,87
BEGIN DESCRIPTION:
Mapping XS dad074f6
END DESCRIPTION:
XS GIS Cut Line= 4
      2039746.57     13532199.75      2039251.52     13531711.57
      2038899.96     13531422.51      2038715.04     13531360.00
#Sta/Elev= 30
  4107.4  542.12  4137.7  541.83  4208.3  540.66  4253.3  539.44  4387.7  538.23
  4458.4  538.75  4573.3  537.94  4621.0  538.55  4727.1  536.87  4748.3  537.60
  4769.5  536.47  4883.1  535.96  4946.9  534.12  4961.3  535.47  4967.8  534.07
  4975.6  534.88  4982.1  533.86  4996.5  533.43  5000.7  532.45  5001.3  531.65
  5007.4  531.65  5007.9  532.45  5010.8  533.49  5053.8  535.57  5074.7  534.68
  5146.4  538.33  5188.0  539.56  5315.8  539.90  5417.0  541.97  5453.0  542.72
#Mann=7,-1,0
  4107.4    0.05       0  4137.7    0.08       0  4208.3    0.05       0
  4573.3     0.1       0  5000.7    0.07       0  5007.9     0.1       0
  5417.0    0.05       0
Bank Sta=5000.7,5007.9
Exp/Cntr=0.3,0.1

Type RM Length L Ch R = 1,20875,834,834,834
BEGIN DESCRIPTION:
Mapping XS 9811b3e7
END DESCRIPTION:
XS GIS Cut Line= 4
      2039784.76     13532217.11      2039226.17     13531622.24
      2039050.39     13531442.55      2038779.12     13531195.94
#Sta/Elev= 30
  4019.0  542.70  4070.9  541.89  4084.0  542.56  4119.2  540.77  4140.7  541.20
  4178.5  540.20  4416.6  538.26  4642.3  537.44  4762.9  536.90  4784.4  535.87
  4841.0  537.10  4855.1  535.81  4897.6  534.52  4932.9  534.47  4954.2  535.37
  4961.2  533.99  4975.3  532.95  4993.0  532.61  4993.5  531.81  4999.6  531.81
  5000.2  532.61  5003.6  533.69  5017.7  535.19  5053.2  535.75  5081.2  538.30
  5116.9  539.21  5187.9  539.51  5229.8  538.06  5262.8  539.03  5453.0  542.83
#Mann=7,-1,0
  4019.0    0.05       0  4070.9    0.08       0  4178.5    0.05       0
  4642.3     0.1       0  4993.0    0.07       0  5000.2     0.1       0
  5262.8    0.05       0
Bank Sta=4993,5000.2
Exp/Cntr=0.3,0.1

Type RM Length L Ch R = 1,20041,1002,1002,1002
BEGIN DESCRIPTION:
Mapping XS 5f78a9f7
END DESCRIPTION:
XS GIS Cut Line= 4
      2039949.99     13532349.98      2039499.29     13531619.46
      2039423.77     13531295.24      2038791.16     13530770.95
#Sta/Elev= 30
  4022.2  545.66  4269.3  541.52  4290.6  541.88  4369.8  539.83  4486.3  539.18
  4531.9  538.15  4626.5  538.08  4669.1  537.06  4785.0  538.06  4926.4  537.21
  4963.9  535.68  4977.6  533.44  4989.2  530.54  5002.9  528.52  5003.4  527.72
  5009.5  527.72  5010.1  528.52  5011.6  529.50  5018.6  530.98  5028.9  531.99
  5101.9  533.49  5138.1  533.43  5215.9  533.81  5263.0  535.66  5405.0  538.81
  5503.9  539.11  5666.1  542.07  5887.2  543.57  5894.6  544.51  6035.1  546.18
#Mann=6,-1,0
  4022.2    0.05       0  4989.2     0.1       0  5002.9    0.07       0
  5010.1     0.1       0  5138.1    0.05       0  5666.1     0.1       0
Bank Sta=5002.9,5010.1
Exp/Cntr=0.3,0.1

Type RM Length L Ch R = 1,19039,320,320,320
BEGIN DESCRIPTION:
Mapping XS c18aa806
END DESCRIPTION:
XS GIS Cut Line= 4
      2040567.17     13532088.60      2040132.23     13530934.76
      2039908.27     13530629.20      2038928.28     13530677.10
#Sta/Elev= 30
  3651.2  546.02  3671.3  545.11  3687.1  545.50  3932.9  541.68  4067.5  540.66
  4082.5  539.29  4112.5  538.75  4189.4  536.88  4253.5  536.59  4493.8  532.91
  4518.7  530.85  4524.0  532.43  4531.4  532.79  4707.9  533.48  4749.7  531.71
  4779.9  532.23  4924.6  531.03  4974.8  528.54  5000.5  525.58  5001.0  524.78
  5007.2  524.78  5007.7  525.58  5039.6  529.35  5104.5  530.13  5154.6  531.82
  5296.5  532.84  5396.6  535.05  5757.0  537.46  5952.5  540.08  6244.3  545.03
#Mann=6,-1,0
  3651.2    0.05       0  4112.5     0.1       0  4707.9    0.05       0
  5000.5    0.03       0  5007.7    0.05       0  5952.5     0.1       0
Bank Sta=5000.5,5007.7
Exp/Cntr=0.3,0.1

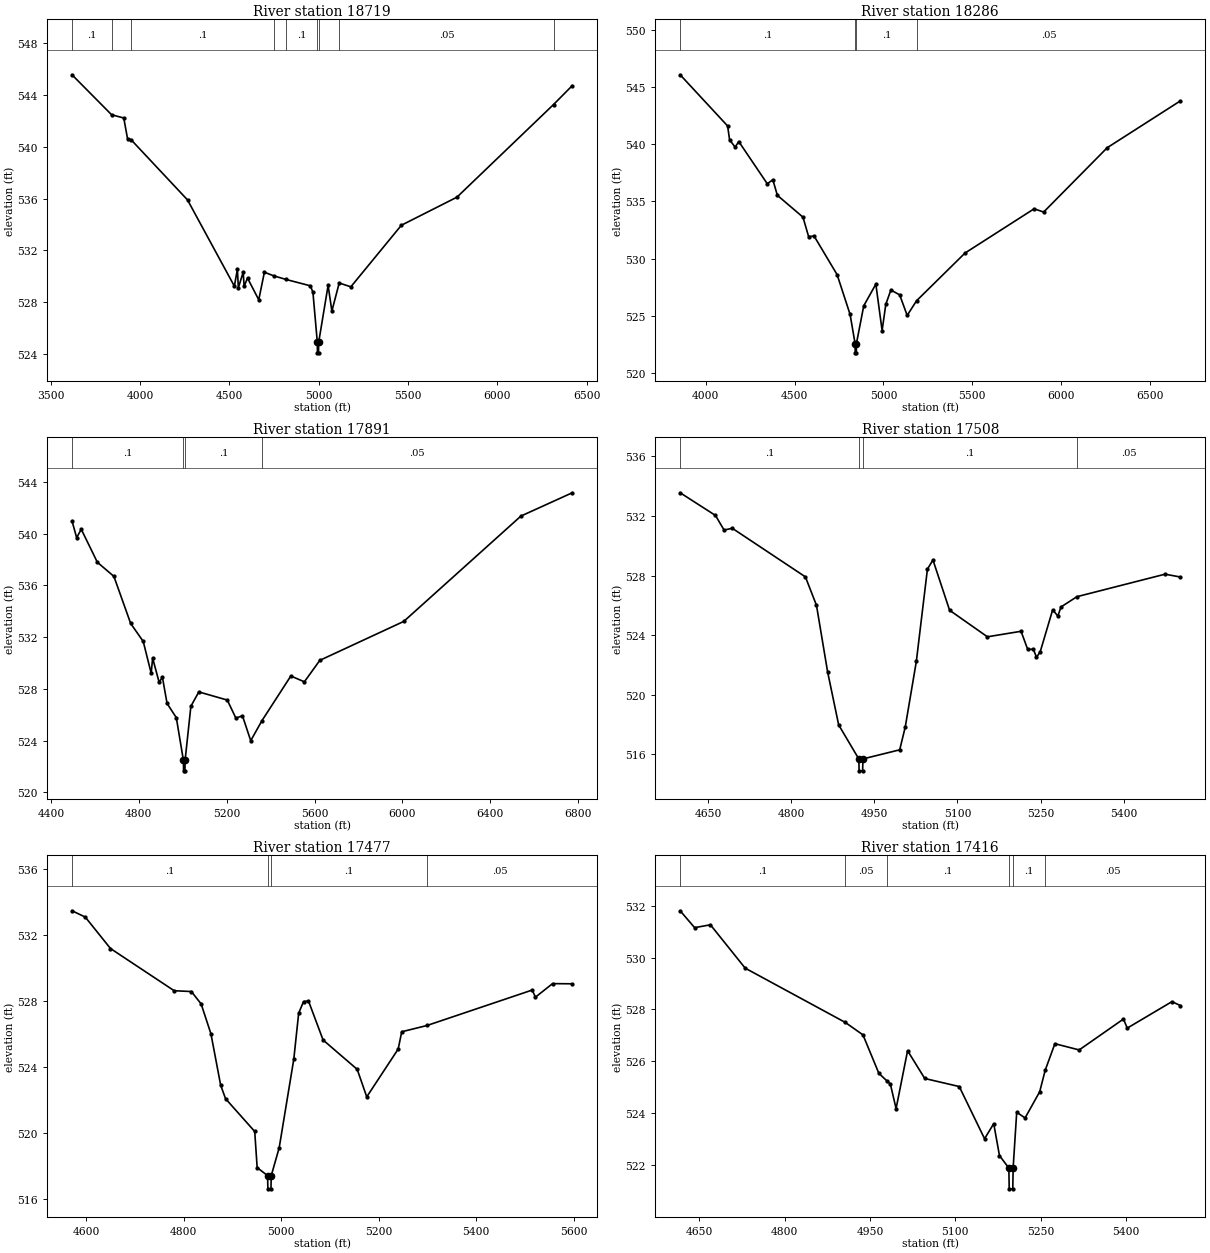
Type RM Length L Ch R = 1,18719,433,433,433
BEGIN DESCRIPTION:
Mapping XS f0113899
END DESCRIPTION:
XS GIS Cut Line= 4
      2040739.05     13531901.12      2040350.98     13530672.60
      2040116.60     13530452.12      2038931.75     13530536.56
#Sta/Elev= 30
  3620.1  545.57  3841.7  542.48  3909.7  542.23  3930.6  540.64  3950.6  540.55
  4266.2  535.90  4528.4  529.23  4545.3  530.54  4550.6  529.11  4577.7  530.31
  4582.9  529.22  4601.8  529.86  4664.7  528.18  4696.2  530.31  4748.8  530.03
  4817.5  529.75  4953.5  529.26  4967.7  528.76  4992.4  524.88  4992.9  524.08
  4999.1  524.08  4999.7  524.88  5052.6  529.29  5073.7  527.31  5114.8  529.48
  5179.7  529.18  5462.4  533.94  5773.2  536.11  6313.5  543.27  6418.1  544.73
#Mann=9,-1,0
  3620.1     0.1       0  3841.7    0.05       0  3950.6     0.1       0
  4748.8    0.05       0  4817.5     0.1       0  4992.4    0.07       0
  4999.7     0.1       0  5114.8    0.05       0  6313.5     0.1       0
Bank Sta=4992.4,4999.7
Exp/Cntr=0.3,0.1

Type RM Length L Ch R = 1,18286,395,395,395
BEGIN DESCRIPTION:
Mapping XS 220061a3
END DESCRIPTION:
XS GIS Cut Line= 4
      2041020.31     13531416.78      2040669.83     13530416.03
      2040525.46     13530250.73      2038999.97     13530400.00
#Sta/Elev= 30
  3857.1  546.06  4123.9  541.59  4135.1  540.37  4166.3  539.74  4186.5  540.23
  4346.9  536.54  4378.2  536.89  4403.6  535.53  4547.7  533.62  4579.2  531.93
  4610.2  531.97  4739.6  528.60  4812.6  525.12  4840.7  522.57  4841.3  521.77
  4847.5  521.77  4848.0  522.57  4889.4  525.88  4957.4  527.77  4992.5  523.72
  5013.4  526.01  5041.9  527.26  5091.4  526.83  5133.5  525.04  5186.3  526.32
  5458.9  530.49  5847.0  534.35  5901.0  534.07  6258.3  539.69  6669.7  543.78
#Mann=4,-1,0
  3857.1     0.1       0  4840.7    0.07       0  4848.0     0.1       0
  5186.3    0.05       0
Bank Sta=4840.7,4848
Exp/Cntr=0.3,0.1

Type RM Length L Ch R = 1,17891,383,383,383
BEGIN DESCRIPTION:
Mapping XS 01d0dc93
END DESCRIPTION:
XS GIS Cut Line= 4
      2041128.33     13530645.29      2041072.33     13530462.97
      2040627.02     13530170.00      2039082.78     13530338.65
#Sta/Elev= 30
  4496.0  540.99  4517.2  539.69  4538.2  540.34  4611.4  537.79  4686.7  536.70
  4763.1  533.06  4820.3  531.67  4856.5  529.21  4863.1  530.38  4892.6  528.52
  4907.7  528.90  4928.8  526.88  4970.9  525.78  5003.3  522.47  5003.9  521.67
  5010.2  521.67  5010.8  522.47  5037.2  526.66  5073.4  527.77  5202.9  527.14
  5241.9  525.75  5272.1  525.92  5309.6  524.00  5360.8  525.55  5492.2  529.00
  5553.8  528.55  5624.2  530.21  6006.4  533.22  6539.6  541.36  6773.2  543.16
#Mann=4,-1,0
  4496.0     0.1       0  5003.3    0.07       0  5010.8     0.1       0
  5360.8    0.05       0
Bank Sta=5003.3,5010.8
Exp/Cntr=0.3,0.1

Type RM Length L Ch R = 1,17508,31,31,31
BEGIN DESCRIPTION:
Mapping XS 26f2bb21
END DESCRIPTION:
XS GIS Cut Line= 4
      2041175.63     13530072.12      2041023.72     13529980.98
      2040669.99     13529969.04      2040340.60     13530140.24
#Sta/Elev= 30
  4599.8  533.55  4663.5  532.03  4679.0  531.05  4693.8  531.17  4825.7  527.91
  4845.7  526.00  4865.7  521.55  4885.7  517.98  4922.0  515.70  4922.6  514.90
  4928.9  514.90  4929.5  515.70  4995.8  516.31  5005.8  517.84  5025.8  522.24
  5045.8  528.43  5055.8  529.04  5085.8  525.67  5154.0  523.89  5214.7  524.26
  5226.7  523.04  5236.8  523.06  5242.5  522.52  5249.2  522.88  5271.7  525.70
  5281.1  525.28  5286.7  525.89  5315.4  526.58  5474.4  528.09  5502.1  527.90
#Mann=4,-1,0
  4599.8     0.1       0  4922.0    0.07       0  4929.5     0.1       0
  5315.4    0.05       0
Bank Sta=4922,4929.5
Exp/Cntr=0.3,0.1

Type RM Length L Ch R = 1,17477,61,61,61
BEGIN DESCRIPTION:
Mapping XS 8766212a
END DESCRIPTION:
XS GIS Cut Line= 5
      2041195.40     13530053.04      2041005.28     13529933.24
      2040587.31     13529951.47      2040362.05     13530092.09
      2040273.60     13530170.13
#Sta/Elev= 30
  4570.6  533.48  4597.8  533.10  4649.6  531.19  4780.3  528.63  4815.6  528.58
  4835.6  527.83  4855.7  526.02  4875.7  522.90  4885.7  522.08  4945.6  520.09
  4950.6  517.90  4972.0  517.41  4972.6  516.61  4978.9  516.61  4979.5  517.41
  4995.8  519.10  5025.8  524.48  5035.8  527.27  5045.8  527.97  5055.9  528.01
  5085.9  525.64  5155.9  523.86  5175.5  522.19  5240.0  525.09  5247.3  526.14
  5299.2  526.52  5515.0  528.67  5521.7  528.24  5556.8  529.06  5597.2  529.05
#Mann=4,-1,0
  4570.6     0.1       0  4972.0    0.07       0  4979.5     0.1       0
  5299.2    0.05       0
Bank Sta=4972,4979.5
Exp/Cntr=0.3,0.1

Type RM Length L Ch R = 1,17416,222,222,222
BEGIN DESCRIPTION:
Mapping XS 2cac13b3
END DESCRIPTION:
XS GIS Cut Line= 4
      2041139.38     13529963.18      2040947.99     13529865.53
      2040513.09     13529926.73      2040343.81     13530075.18
#Sta/Elev= 30
  4616.3  531.80  4641.7  531.15  4669.5  531.26  4730.6  529.59  4906.5  527.50
  4937.6  527.02  4965.5  525.54  4979.1  525.26  4985.7  525.13  4995.8  524.18
  5016.0  526.41  5046.2  525.34  5106.8  525.03  5151.3  523.02  5167.4  523.60
  5177.5  522.37  5194.0  521.89  5194.6  521.09  5200.9  521.09  5201.5  521.89
  5207.8  524.04  5222.5  523.82  5248.2  524.83  5257.9  525.66  5274.9  526.68
  5317.6  526.44  5395.4  527.63  5402.1  527.28  5480.6  528.30  5495.5  528.15
#Mann=6,-1,0
  4616.3     0.1       0  4906.5    0.05       0  4979.1     0.1       0
  5194.0    0.07       0  5201.5     0.1       0  5257.9    0.05       0
Bank Sta=5194,5201.5
Exp/Cntr=0.3,0.1