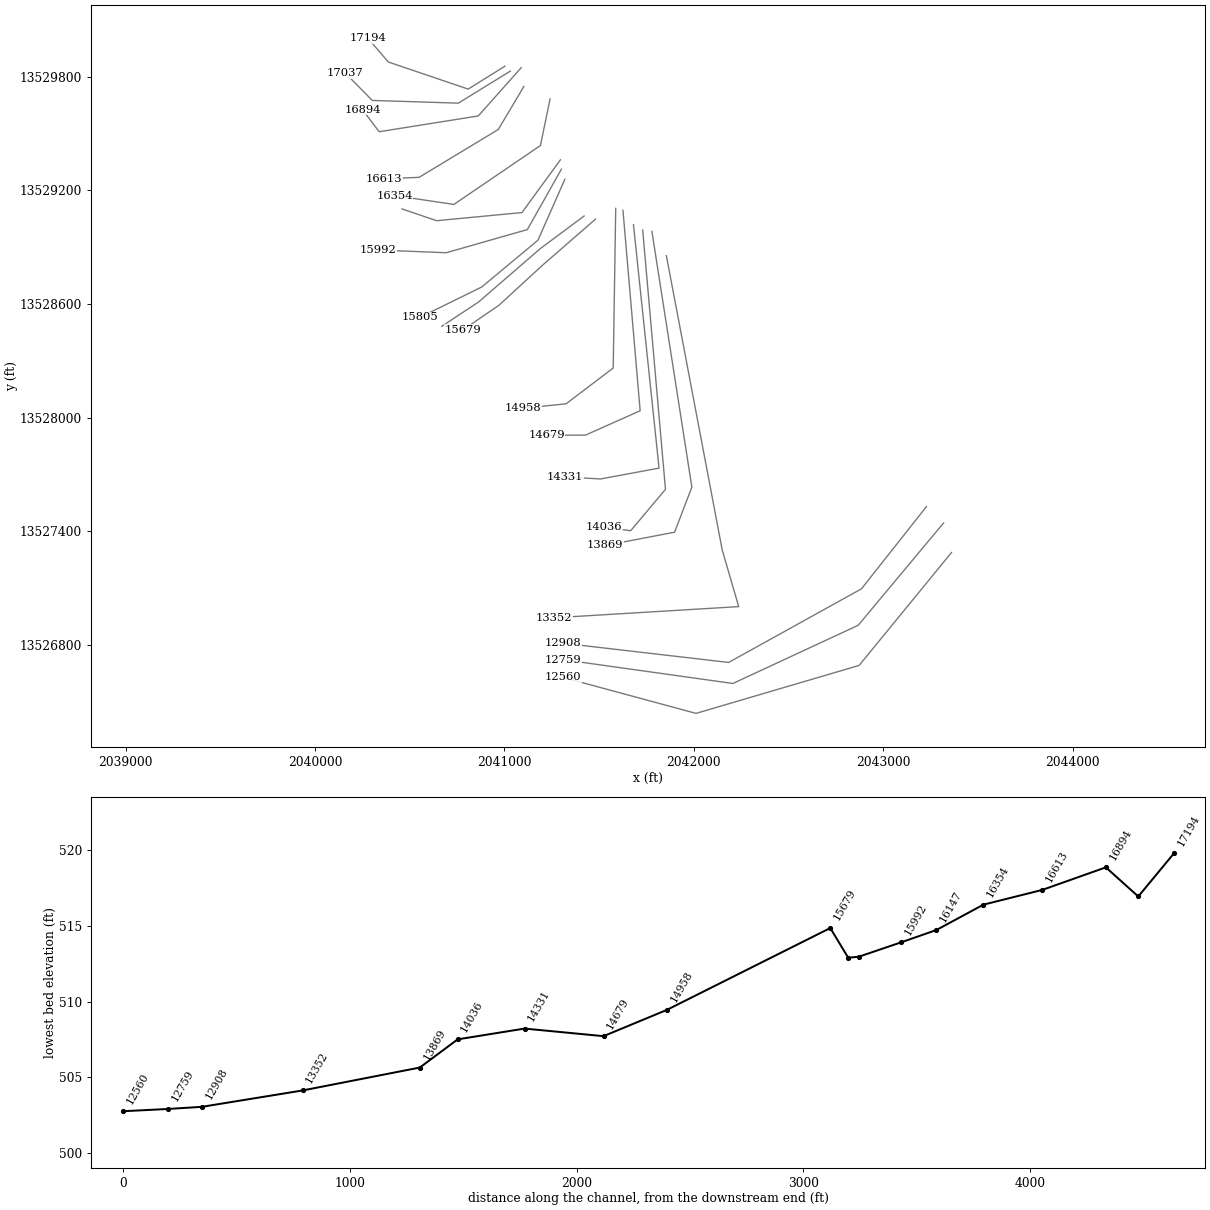
HEC-RAS study ELM Cr.prj: ELM Cr Base Level Engineering

--- ELM Cr.g01 (geometry) --- (continued)

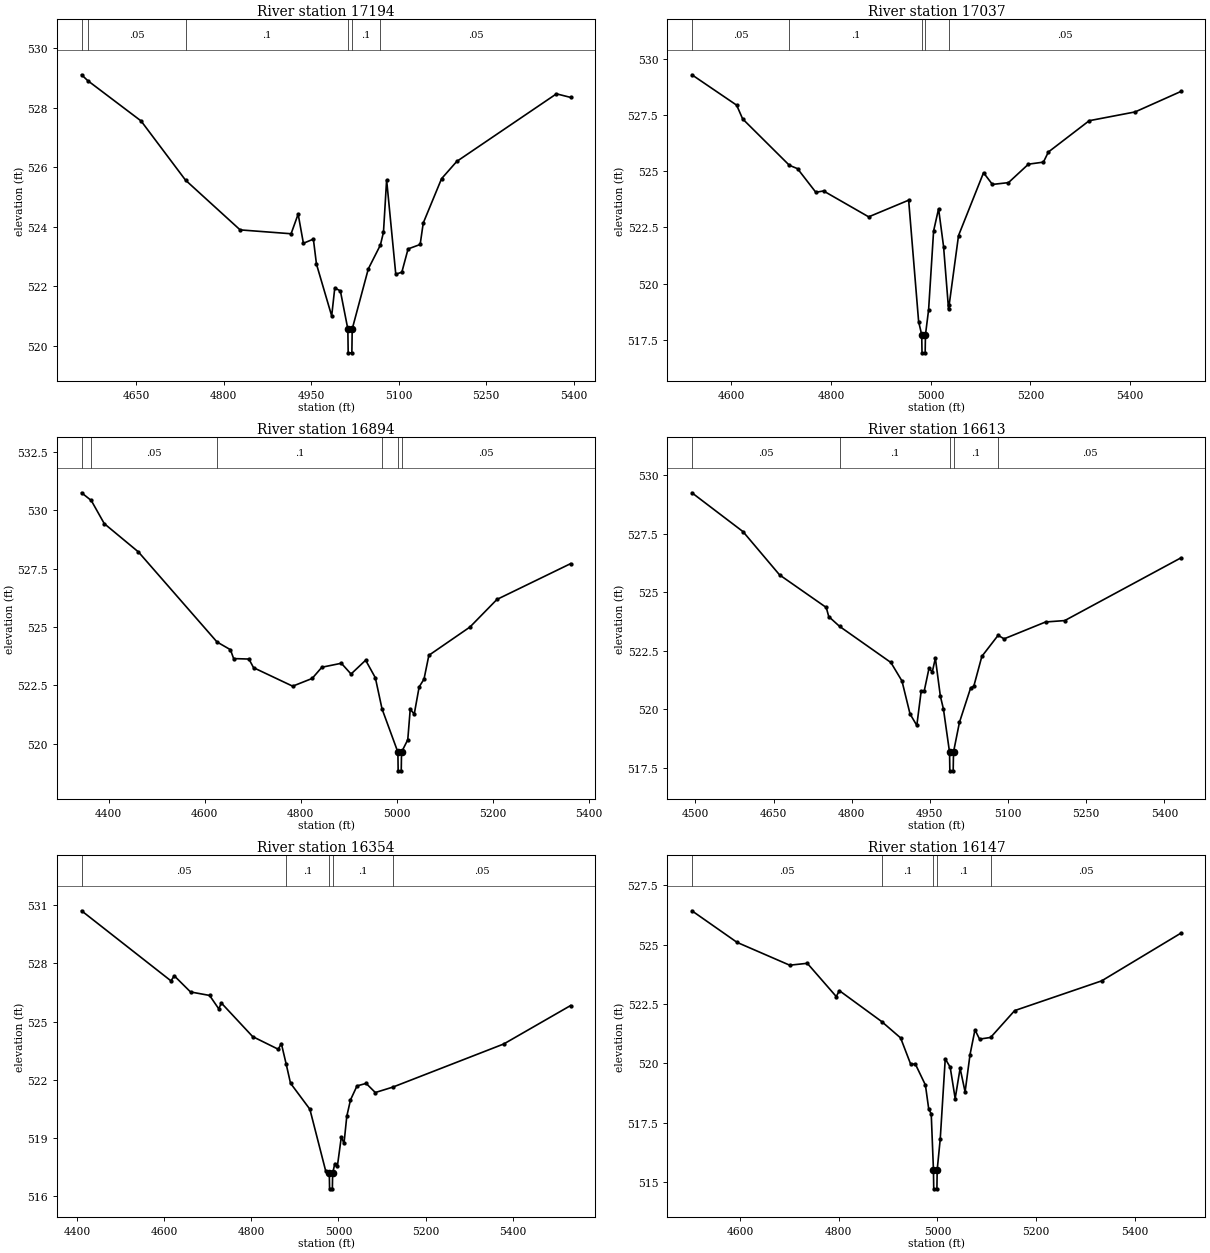
Type RM Length L Ch R = 1,17194,157,157,157
BEGIN DESCRIPTION:
Mapping XS 1250a68d
END DESCRIPTION:
XS GIS Cut Line= 4
      2041002.67     13529856.41      2040808.66     13529735.32
      2040386.79     13529878.55      2040280.02     13530003.54
#Sta/Elev= 30
  4556.0  529.11  4566.8  528.91  4658.0  527.56  4734.3  525.57  4827.9  523.90
  4915.3  523.77  4927.4  524.43  4936.4  523.45  4953.5  523.59  4958.8  522.75
  4984.9  521.01  4990.2  521.95  4999.8  521.85  5012.6  520.57  5013.2  519.77
  5019.5  519.77  5020.1  520.57  5047.7  522.59  5068.4  523.39  5073.7  523.82
  5079.1  525.58  5094.8  522.41  5105.2  522.48  5115.9  523.26  5136.6  523.41
  5141.9  524.13  5173.3  525.62  5199.4  526.20  5370.3  528.47  5394.6  528.35
#Mann=6,-1,0
  4556.0     0.1       0  4566.8    0.05       0  4734.3     0.1       0
  5012.6    0.07       0  5020.1     0.1       0  5068.4    0.05       0
Bank Sta=5012.6,5020.1
Exp/Cntr=0.3,0.1

Type RM Length L Ch R = 1,17037,143,143,143
BEGIN DESCRIPTION:
Mapping XS d245f6bb
END DESCRIPTION:
XS GIS Cut Line= 4
      2041031.36     13529830.40      2040756.58     13529661.10
      2040302.15     13529675.42      2040160.03     13529820.10
#Sta/Elev= 30
  4521.4  529.28  4611.1  527.93  4623.1  527.32  4716.7  525.26  4733.1  525.11
  4769.8  524.06  4785.2  524.12  4875.7  522.97  4955.8  523.71  4975.8  518.32
  4982.0  517.73  4982.6  516.93  4988.9  516.93  4989.5  517.73  4995.8  518.84
  5005.8  522.34  5015.8  523.33  5025.8  521.65  5035.8  518.87  5037.1  519.07
  5055.8  522.14  5105.9  524.93  5123.7  524.41  5155.9  524.49  5195.9  525.31
  5225.9  525.40  5235.9  525.85  5317.7  527.24  5409.7  527.63  5501.6  528.54
#Mann=5,-1,0
  4521.4    0.05       0  4716.7     0.1       0  4982.0    0.07       0
  4989.5     0.1       0  5037.1    0.05       0
Bank Sta=4982,4989.5
Exp/Cntr=0.3,0.1

Type RM Length L Ch R = 1,16894,281,281,281
BEGIN DESCRIPTION:
Mapping XS f5307c55
END DESCRIPTION:
XS GIS Cut Line= 4
      2041088.59     13529848.58      2040862.05     13529593.39
      2040338.61     13529510.06      2040250.09     13529627.22
#Sta/Elev= 30
  4343.6  530.74  4363.8  530.41  4390.9  529.42  4462.0  528.21  4625.6  524.36
  4653.5  524.03  4660.2  523.65  4692.0  523.63  4701.7  523.26  4783.1  522.47
  4823.6  522.80  4843.9  523.28  4884.4  523.45  4904.6  522.99  4935.0  523.58
  4955.2  522.83  4969.1  521.50  5002.1  519.65  5002.7  518.85  5009.1  518.85
  5009.7  519.65  5022.7  520.18  5027.8  521.48  5036.2  521.28  5046.4  522.44
  5056.5  522.77  5066.6  523.79  5152.2  525.00  5208.4  526.18  5361.7  527.71
#Mann=6,-1,0
  4343.6     0.1       0  4363.8    0.05       0  4625.6     0.1       0
  4969.1    0.05       0  5002.1    0.03       0  5009.7    0.05       0
Bank Sta=5002.1,5009.7
Exp/Cntr=0.3,0.1

Type RM Length L Ch R = 1,16613,259,259,259
BEGIN DESCRIPTION:
Mapping XS 535260a0
END DESCRIPTION:
XS GIS Cut Line= 4
      2041102.93     13529749.64      2040967.52     13529521.78
      2040549.55     13529269.17      2040364.65     13529261.36
#Sta/Elev= 30
  4493.4  529.24  4591.5  527.58  4661.7  525.73  4751.2  524.34  4756.0  523.95
  4776.9  523.53  4875.2  521.99  4896.5  521.20  4912.0  519.79  4925.0  519.30
  4933.4  520.77  4939.2  520.77  4948.4  521.74  4954.7  521.59  4960.6  522.17
  4970.2  520.55  4976.1  520.00  4987.8  518.16  4988.4  517.36  4994.8  517.36
  4995.4  518.16  5006.8  519.43  5028.4  520.91  5034.3  520.97  5049.8  522.25
  5081.0  523.15  5092.5  523.00  5172.1  523.72  5208.9  523.78  5431.9  526.46
#Mann=5,-1,0
  4493.4    0.05       0  4776.9     0.1       0  4987.8    0.07       0
  4995.4     0.1       0  5081.0    0.05       0
Bank Sta=4987.8,4995.4
Exp/Cntr=0.3,0.1

Type RM Length L Ch R = 1,16354,207,207,207
BEGIN DESCRIPTION:
Mapping XS fbb36553
END DESCRIPTION:
XS GIS Cut Line= 4
      2041240.96     13529683.27      2041190.17     13529437.14
      2040733.14     13529125.95      2040419.03     13529172.67
#Sta/Elev= 30
  4410.7  530.71  4615.8  527.10  4623.4  527.36  4660.6  526.53  4704.4  526.35
  4725.4  525.66  4731.4  525.96  4803.2  524.23  4861.8  523.58  4869.0  523.87
  4880.0  522.82  4890.0  521.83  4934.4  520.49  4970.7  517.31  4979.0  517.19
  4979.6  516.39  4986.0  516.39  4986.6  517.19  4991.7  517.69  4997.7  517.59
  5006.6  519.07  5012.7  518.73  5019.1  520.13  5027.6  520.97  5042.5  521.69
  5063.5  521.82  5084.5  521.35  5124.8  521.63  5379.1  523.85  5532.5  525.83
#Mann=5,-1,0
  4410.7    0.05       0  4880.0     0.1       0  4979.0    0.07       0
  4986.6     0.1       0  5124.8    0.05       0
Bank Sta=4979,4986.6
Exp/Cntr=0.3,0.1

Type RM Length L Ch R = 1,16147,155,155,155
BEGIN DESCRIPTION:
Mapping XS d32cd816
END DESCRIPTION:
XS GIS Cut Line= 4
      2041295.62     13529361.60      2041092.52     13529082.98
      2040642.00     13529040.01      2040459.16     13529102.25
#Sta/Elev= 30
  4502.8  526.42  4594.3  525.09  4700.9  524.13  4736.5  524.21  4795.2  522.81
  4801.4  523.06  4887.1  521.76  4925.5  521.07  4945.6  519.98  4955.6  519.96
  4975.7  519.09  4982.5  518.07  4987.5  517.88  4992.0  515.52  4992.6  514.72
  4999.0  514.72  4999.6  515.52  5005.8  516.83  5015.9  520.19  5025.9  519.84
  5036.0  518.52  5046.0  519.79  5056.1  518.80  5066.1  520.37  5076.1  521.41
  5085.4  521.02  5107.8  521.09  5156.5  522.22  5332.6  523.47  5493.3  525.48
#Mann=5,-1,0
  4502.8    0.05       0  4887.1     0.1       0  4992.0    0.07       0
  4999.6     0.1       0  5107.8    0.05       0
Bank Sta=4992,4999.6
Exp/Cntr=0.3,0.1

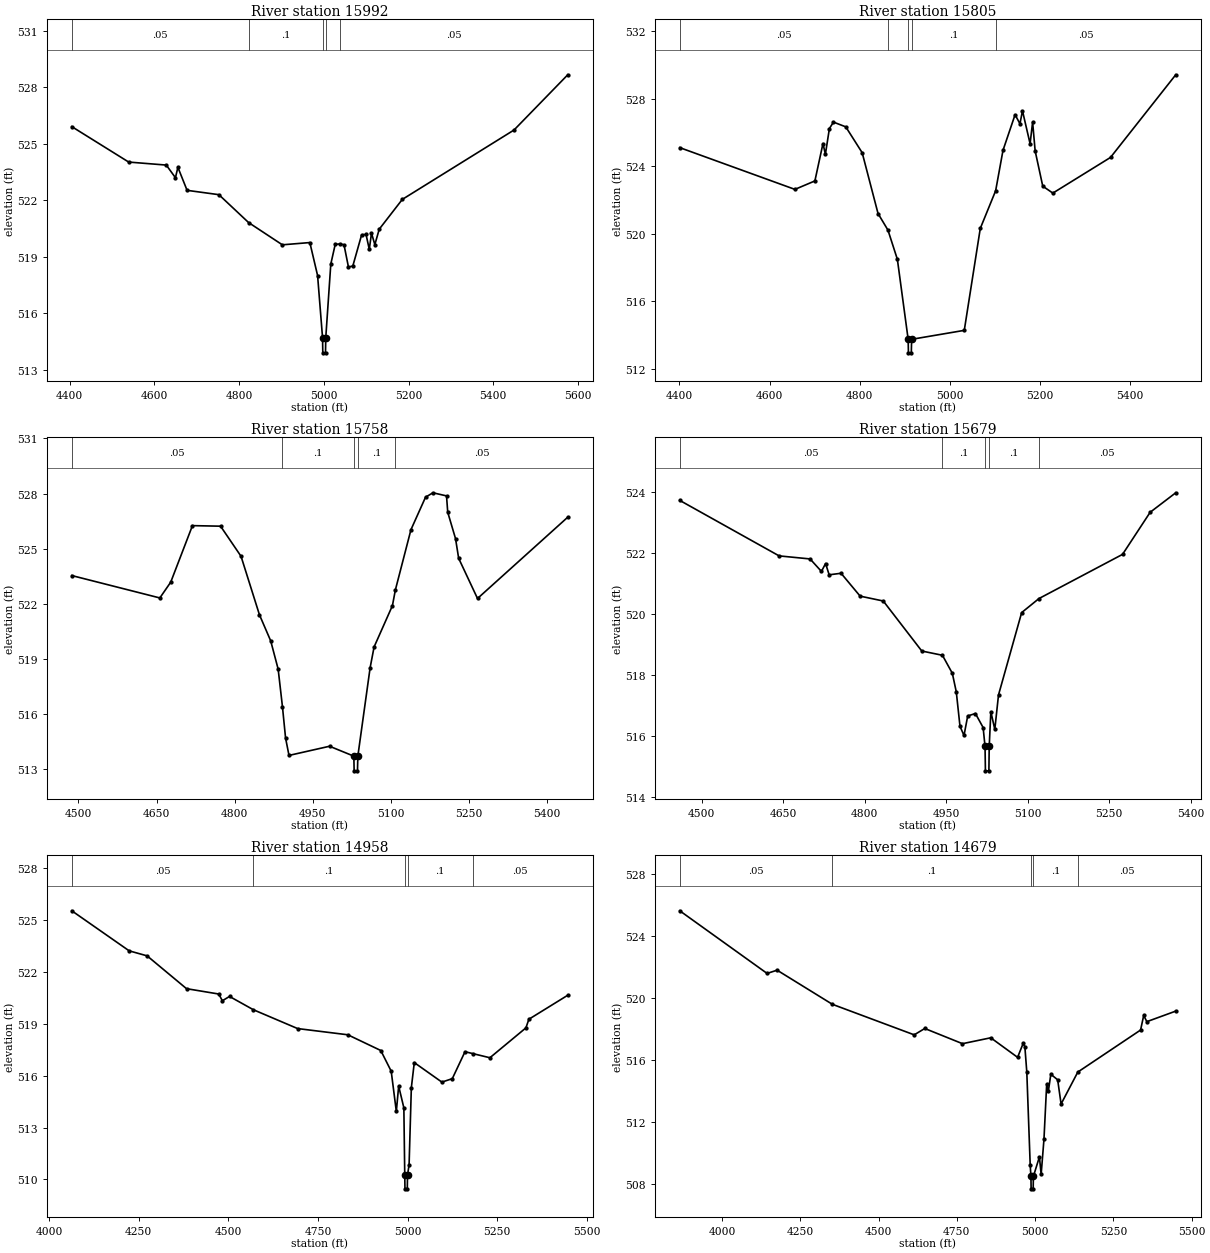
Type RM Length L Ch R = 1,15992,187,187,187
BEGIN DESCRIPTION:
Mapping XS 47ed1407
END DESCRIPTION:
XS GIS Cut Line= 4
      2041300.84     13529312.13      2041121.16     13528993.13
      2040692.78     13528870.74      2040333.41     13528885.06
#Sta/Elev= 30
  4404.7  525.91  4539.1  524.03  4627.9  523.87  4649.5  523.20  4655.3  523.75
  4677.0  522.53  4752.1  522.30  4822.3  520.82  4902.0  519.64  4966.9  519.76
  4985.2  518.01  4996.9  514.71  4997.5  513.91  5003.9  513.91  5004.5  514.71
  5016.4  518.62  5026.8  519.66  5038.5  519.69  5047.6  519.64  5058.0  518.47
  5068.3  518.51  5089.2  520.17  5099.6  520.19  5107.3  519.40  5112.5  520.26
  5120.4  519.65  5130.8  520.47  5185.3  522.05  5449.1  525.73  5576.0  528.66
#Mann=5,-1,0
  4404.7    0.05       0  4822.3     0.1       0  4996.9    0.07       0
  5004.5     0.1       0  5038.5    0.05       0
Bank Sta=4996.9,5004.5
Exp/Cntr=0.3,0.1

Type RM Length L Ch R = 1,15805,47,47,47
BEGIN DESCRIPTION:
Mapping XS 20f0c47e
END DESCRIPTION:
XS GIS Cut Line= 4
      2041319.08     13529258.75      2041177.15     13528937.14
      2040880.28     13528689.75      2040555.17     13528529.80
#Sta/Elev= 30
  4400.7  525.10  4656.2  522.63  4700.5  523.13  4718.4  525.34  4723.8  524.71
  4732.7  526.23  4741.7  526.61  4769.0  526.33  4805.4  524.80  4840.6  521.20
  4862.6  520.22  4883.5  518.49  4907.4  513.76  4908.0  512.96  4914.4  512.96
  4915.1  513.76  5031.9  514.29  5067.4  520.32  5101.5  522.55  5117.8  524.94
  5144.6  527.05  5155.4  526.51  5161.0  527.28  5177.9  525.33  5183.5  526.61
  5189.1  524.91  5206.0  522.82  5228.4  522.41  5356.3  524.52  5501.0  529.41
#Mann=5,-1,0
  4400.7    0.05       0  4862.6     0.1       0  4907.4    0.07       0
  4915.1     0.1       0  5101.5    0.05       0
Bank Sta=4907.4,4915.1
Exp/Cntr=0.3,0.1

Type RM Length L Ch R = 1,15758,79,79,79
BEGIN DESCRIPTION:
Mapping XS 4b0c6c67
END DESCRIPTION:
XS GIS Cut Line= 4
      2041420.67     13529064.77      2041191.47     13528894.17
      2040863.35     13528610.32      2040669.03     13528482.07
#Sta/Elev= 30
  4487.2  523.53  4656.3  522.31  4677.2  523.17  4718.9  526.25  4772.9  526.22
  4812.2  524.58  4847.6  521.39  4869.2  519.97  4883.5  518.43  4891.8  516.37
  4897.7  514.68  4904.3  513.73  4982.2  514.23  5028.8  513.69  5029.4  512.89
  5035.8  512.89  5036.5  513.69  5060.1  518.51  5067.7  519.64  5102.9  521.89
  5108.6  522.75  5138.5  526.03  5166.5  527.80  5180.7  528.04  5206.8  527.87
  5209.1  526.98  5224.1  525.54  5230.1  524.47  5266.3  522.28  5439.6  526.71
#Mann=5,-1,0
  4487.2    0.05       0  4891.8     0.1       0  5028.8    0.07       0
  5036.5     0.1       0  5108.6    0.05       0
Bank Sta=5028.8,5036.5
Exp/Cntr=0.3,0.1

Type RM Length L Ch R = 1,15679,721,721,721
BEGIN DESCRIPTION:
Mapping XS 726ce7c7
END DESCRIPTION:
XS GIS Cut Line= 4
      2041480.55     13529047.83      2041200.59     13528804.33
      2040971.42     13528593.39      2040781.34     13528463.20
#Sta/Elev= 30
  4459.4  523.72  4642.3  521.90  4699.3  521.80  4720.2  521.39  4727.8  521.65
  4734.4  521.28  4756.3  521.33  4791.4  520.58  4834.0  520.42  4904.9  518.78
  4942.9  518.64  4961.1  518.05  4968.4  517.44  4975.2  516.31  4982.6  516.01
  4989.4  516.65  5003.6  516.73  5017.8  516.27  5021.3  515.65  5022.0  514.85
  5028.4  514.85  5029.0  515.65  5032.0  516.79  5039.3  516.21  5046.1  517.34
  5088.7  520.04  5120.5  520.50  5274.4  521.95  5325.2  523.33  5372.3  523.97
#Mann=5,-1,0
  4459.4    0.05       0  4942.9     0.1       0  5021.3    0.07       0
  5029.0     0.1       0  5120.5    0.05       0
Bank Sta=5021.3,5029
Exp/Cntr=0.3,0.1

Type RM Length L Ch R = 1,14958,279,279,279
BEGIN DESCRIPTION:
Mapping XS ea57001d
END DESCRIPTION:
XS GIS Cut Line= 4
      2041587.68     13529105.16      2041574.34     13528261.51
      2041325.59     13528072.56      2041098.82     13528049.23
#Sta/Elev= 30
  4063.1  525.55  4223.3  523.23  4273.3  522.94  4383.3  521.04  4473.3  520.73
  4483.3  520.34  4503.3  520.59  4569.9  519.82  4693.3  518.73  4833.4  518.37
  4925.4  517.46  4954.5  516.26  4968.8  513.93  4975.3  515.40  4989.8  514.14
  4992.3  510.25  4992.9  509.45  4999.4  509.45  5000.0  510.25  5004.4  510.84
  5010.7  515.31  5018.9  516.76  5095.9  515.63  5125.0  515.83  5160.4  517.39
  5182.3  517.28  5229.9  517.04  5330.4  518.77  5338.7  519.27  5447.2  520.66
#Mann=5,-1,0
  4063.1    0.05       0  4569.9     0.1       0  4992.3    0.07       0
  5000.0     0.1       0  5182.3    0.05       0
Bank Sta=4992.3,5000
Exp/Cntr=0.3,0.1

Type RM Length L Ch R = 1,14679,348,348,348
BEGIN DESCRIPTION:
Mapping XS 60f28e4e
END DESCRIPTION:
XS GIS Cut Line= 4
      2041625.88     13529094.76      2041716.70     13528035.82
      2041428.45     13527907.20      2041222.73     13527905.89
#Sta/Elev= 30
  3865.0  525.65  4144.0  521.61  4175.9  521.82  4352.4  519.62  4613.9  517.65
  4647.6  518.06  4768.1  517.08  4858.4  517.46  4944.1  516.20  4961.9  517.10
  4967.3  516.89  4973.5  515.25  4984.4  509.24  4986.7  508.52  4987.3  507.72
  4993.9  507.72  4994.5  508.52  5013.8  509.78  5019.3  508.65  5028.3  510.91
  5037.0  514.47  5042.5  514.03  5050.2  515.11  5072.1  514.75  5083.0  513.19
  5136.4  515.25  5336.9  517.96  5346.9  518.90  5356.9  518.50  5449.2  519.18
#Mann=5,-1,0
  3865.0    0.05       0  4352.4     0.1       0  4986.7    0.07       0
  4994.5     0.1       0  5136.4    0.05       0
Bank Sta=4986.7,4994.5
Exp/Cntr=0.3,0.1

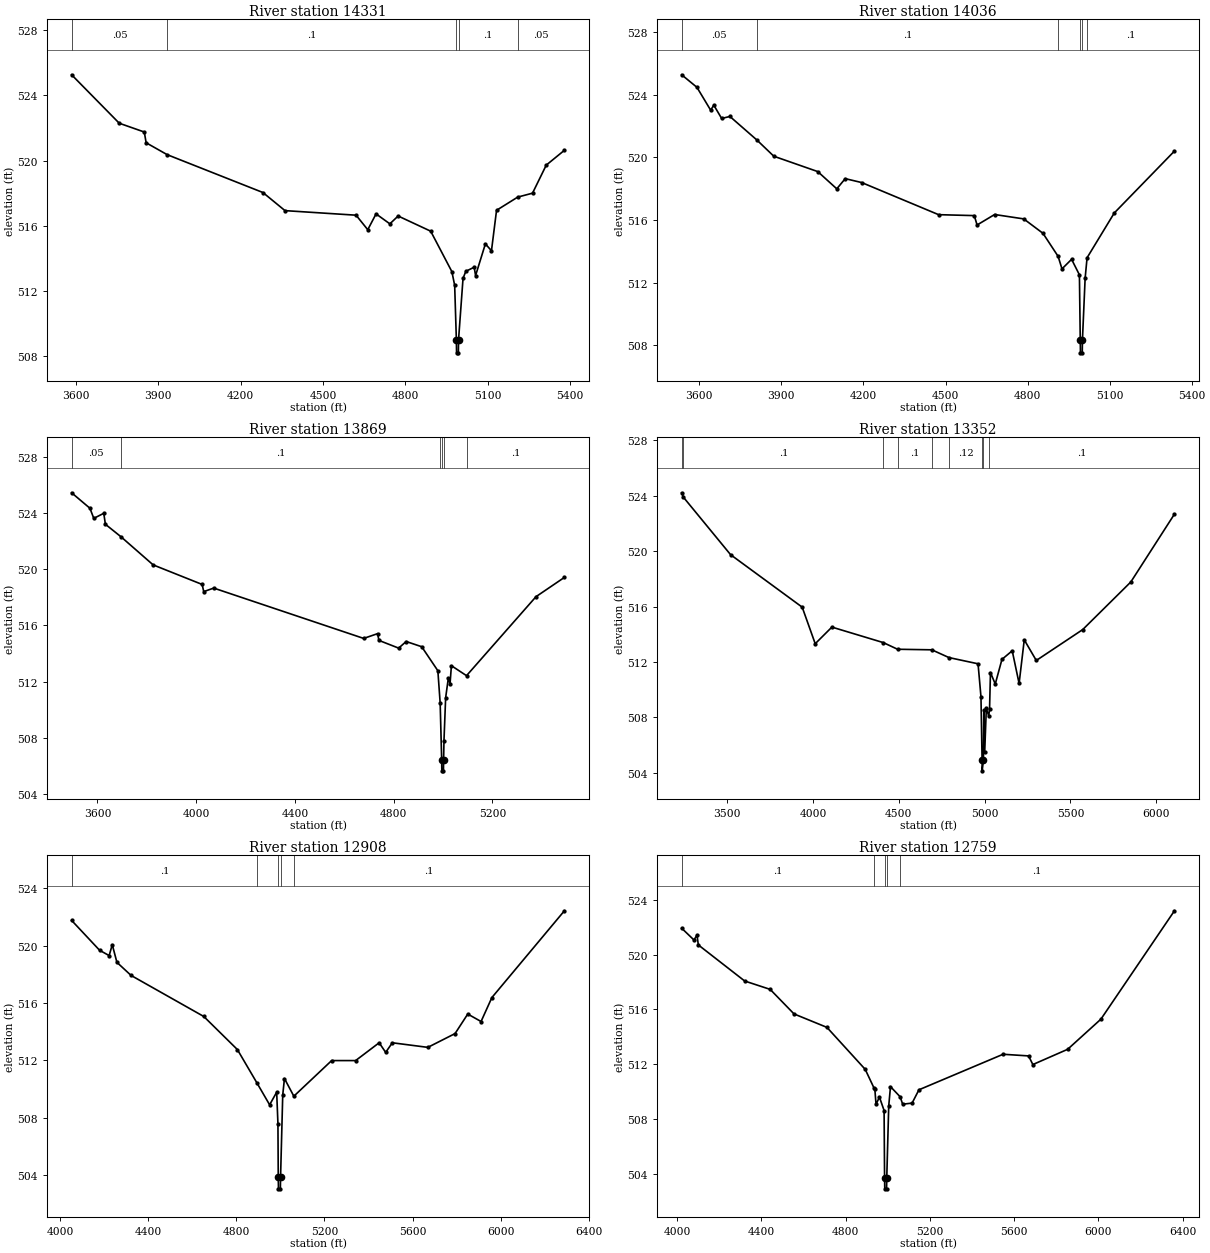
Type RM Length L Ch R = 1,14331,295,295,295
BEGIN DESCRIPTION:
Mapping XS f7c87be7
END DESCRIPTION:
XS GIS Cut Line= 4
      2041681.44     13529018.34      2041816.47     13527732.72
      2041507.88     13527675.42      2041318.93     13527685.78
#Sta/Elev= 30
  3583.9  525.27  3757.4  522.30  3848.7  521.76  3855.5  521.10  3932.3  520.37
  4281.1  518.05  4361.5  516.94  4620.5  516.66  4663.1  515.77  4693.3  516.74
  4743.6  516.13  4773.8  516.61  4892.4  515.68  4969.6  513.20  4979.8  512.36
  4986.0  509.02  4986.7  508.22  4993.3  508.22  4993.9  509.02  5010.3  512.79
  5020.5  513.22  5050.9  513.47  5056.0  512.96  5091.7  514.90  5113.9  514.48
  5132.4  516.96  5209.6  517.77  5263.5  518.01  5313.5  519.73  5379.7  520.64
#Mann=5,-1,0
  3583.9    0.05       0  3932.3     0.1       0  4986.0    0.07       0
  4993.9     0.1       0  5209.6    0.05       0
Bank Sta=4986,4993.9
Exp/Cntr=0.3,0.1

Type RM Length L Ch R = 1,14036,167,167,167
BEGIN DESCRIPTION:
Mapping XS 2f95608f
END DESCRIPTION:
XS GIS Cut Line= 4
      2041730.04     13528990.62      2041850.33     13527620.74
      2041666.74     13527401.99      2041527.36     13527420.22
#Sta/Elev= 30
  3535.6  525.26  3591.4  524.46  3641.6  523.00  3653.1  523.32  3681.8  522.47
  3711.9  522.60  3810.3  521.10  3872.5  520.06  4033.1  519.08  4102.6  517.98
  4133.5  518.63  4193.7  518.38  4474.8  516.33  4605.3  516.27  4615.4  515.67
  4679.5  516.34  4786.0  516.06  4856.3  515.14  4911.6  513.67  4925.8  512.87
  4960.9  513.48  4989.5  512.49  4992.6  508.31  4993.3  507.51  4999.9  507.51
  5000.5  508.31  5010.4  512.27  5017.5  513.58  5117.0  516.44  5336.9  520.39
#Mann=6,-1,0
  3535.6    0.05       0  3810.3     0.1       0  4911.6    0.12       0
  4992.6    0.07       0  5000.5    0.12       0  5017.5     0.1       0
Bank Sta=4992.6,5000.5
Exp/Cntr=0.3,0.1

Type RM Length L Ch R = 1,13869,517,517,517
BEGIN DESCRIPTION:
Mapping XS e1e690fa
END DESCRIPTION:
XS GIS Cut Line= 4
      2041778.65     13528983.68      2041989.65     13527632.46
      2041898.51     13527394.17      2041532.10     13527323.93
#Sta/Elev= 30
  3495.5  525.43  3569.6  524.33  3585.3  523.61  3625.7  523.97  3632.3  523.19
  3695.5  522.30  3825.7  520.30  4024.1  518.91  4030.6  518.40  4071.1  518.65
  4678.3  515.07  4734.9  515.41  4739.9  514.93  4820.0  514.38  4850.4  514.85
  4913.3  514.48  4978.8  512.77  4988.1  510.48  4994.2  506.45  4994.8  505.65
  5001.4  505.65  5002.1  506.45  5003.5  507.78  5010.3  510.85  5021.0  512.22
  5028.2  511.86  5033.6  513.13  5094.9  512.42  5376.3  518.04  5491.3  519.41
#Mann=6,-1,0
  3495.5    0.05       0  3695.5     0.1       0  4988.1    0.12       0
  4994.2    0.07       0  5002.1    0.12       0  5094.9     0.1       0
Bank Sta=4994.2,5002.1
Exp/Cntr=0.3,0.1

Type RM Length L Ch R = 1,13352,444,444,444
BEGIN DESCRIPTION:
Mapping XS 8d3550b4
END DESCRIPTION:
XS GIS Cut Line= 4
      2041855.05     13528855.13      2042150.00     13527300.00
      2042237.05     13527000.95      2041261.25     13526941.98
#Sta/Elev= 30
  3234.4  524.22  3244.5  523.90  3519.5  519.75  3936.8  515.96  4012.7  513.32
  4109.9  514.52  4409.7  513.40  4492.7  512.92  4692.2  512.88  4792.0  512.32
  4961.7  511.87  4978.7  509.49  4985.2  504.94  4985.8  504.14  4993.1  504.94
  4995.2  508.54  5000.4  505.50  5009.9  508.65  5024.0  508.10  5028.7  508.59
  5034.0  511.24  5062.0  510.41  5101.0  512.19  5160.8  512.81  5200.9  510.45
  5231.0  513.60  5301.1  512.11  5571.6  514.34  5852.1  517.78  6106.3  522.68
#Mann=9,-1,0
  3234.4    0.05       0  3244.5     0.1       0  4409.7    0.07       0
  4492.7     0.1       0  4692.2    0.07       0  4792.0    0.12       0
  4985.2    0.07       0  4993.1    0.12       0  5024.0     0.1       0
Bank Sta=4985.2,4993.1
Exp/Cntr=0.3,0.1

Type RM Length L Ch R = 1,12908,149,149,149
BEGIN DESCRIPTION:
Mapping XS e7f08a12
END DESCRIPTION:
XS GIS Cut Line= 4
      2043228.59     13527529.83      2042885.10     13527094.85
      2042183.72     13526705.96      2041309.23     13526807.52
#Sta/Elev= 30
  4052.5  521.75  4179.5  519.67  4222.8  519.30  4237.0  520.06  4258.1  518.83
  4322.2  517.92  4652.4  515.06  4804.7  512.76  4894.9  510.40  4951.2  508.91
  4983.2  509.79  4988.9  507.60  4990.4  503.86  4991.3  503.06  4999.9  503.06
  5000.8  503.86  5010.7  509.60  5018.5  510.74  5061.1  509.51  5232.7  511.99
  5341.5  511.99  5448.3  513.23  5477.9  512.56  5508.1  513.23  5669.2  512.91
  5792.8  513.87  5850.4  515.23  5910.8  514.71  5960.0  516.38  6289.1  522.42
#Mann=5,-1,0
  4052.5     0.1       0  4894.9    0.12       0  4990.4    0.07       0
  5000.8    0.12       0  5061.1     0.1       0
Bank Sta=4990.4,5000.8
Exp/Cntr=0.3,0.1

Type RM Length L Ch R = 1,12759,199,199,199
BEGIN DESCRIPTION:
Mapping XS d0bc0d57
END DESCRIPTION:
XS GIS Cut Line= 4
      2043318.88     13527443.04      2042867.74     13526902.14
      2042206.28     13526594.85      2041309.26     13526720.69
#Sta/Elev= 30
  4021.2  521.92  4079.6  521.06  4093.9  521.42  4100.4  520.70  4320.4  518.07
  4441.4  517.46  4554.7  515.67  4710.9  514.69  4892.6  511.63  4934.0  510.28
  4938.1  510.23  4943.9  509.08  4960.1  509.61  4982.2  508.63  4984.5  503.72
  4985.4  502.92  4994.0  502.92  4994.9  503.72  5004.2  508.96  5012.6  510.37
  5058.5  509.63  5070.4  509.09  5115.2  509.17  5147.6  510.14  5547.1  512.73
  5668.2  512.61  5688.4  511.98  5853.5  513.09  6011.6  515.29  6360.7  523.19
#Mann=5,-1,0
  4021.2     0.1       0  4934.0    0.12       0  4984.5    0.07       0
  4994.9    0.12       0  5058.5     0.1       0
Bank Sta=4984.5,4994.9
Exp/Cntr=0.3,0.1

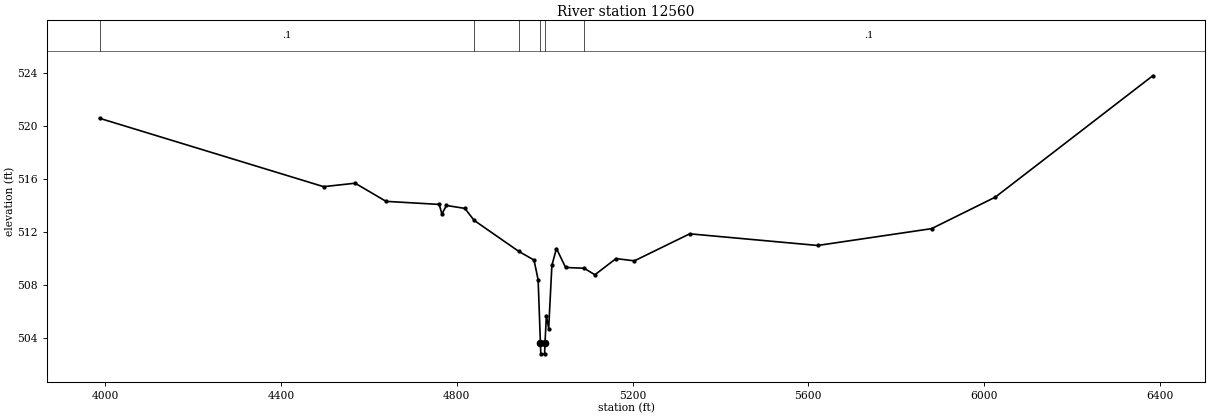
Type RM Length L Ch R = 1,12560,792,792,792
BEGIN DESCRIPTION:
Mapping XS 63ef1253
END DESCRIPTION:
XS GIS Cut Line= 4
      2043360.55     13527286.79      2042872.95     13526690.33
      2042011.84     13526436.86      2041309.21     13526626.85
#Sta/Elev= 30
  3987.6  520.55  4497.1  515.39  4568.9  515.65  4639.2  514.28  4760.1  514.05
  4766.3  513.33  4776.7  513.97  4818.4  513.75  4839.8  512.84  4941.4  510.50
  4975.8  509.85  4985.2  508.36  4990.4  503.57  4991.3  502.77  4999.9  502.77
  5000.8  503.57  5004.0  505.66  5009.2  504.68  5016.5  509.45  5026.9  510.72
  5047.7  509.29  5089.7  509.23  5114.4  508.74  5162.4  509.96  5204.1  509.79
  5330.1  511.83  5621.1  510.95  5880.3  512.22  6025.3  514.60  6383.5  523.76
#Mann=6,-1,0
  3987.6     0.1       0  4839.8    0.07       0  4941.4    0.12       0
  4990.4    0.07       0  5000.8    0.12       0  5089.7     0.1       0
Bank Sta=4990.4,5000.8
Exp/Cntr=0.3,0.1