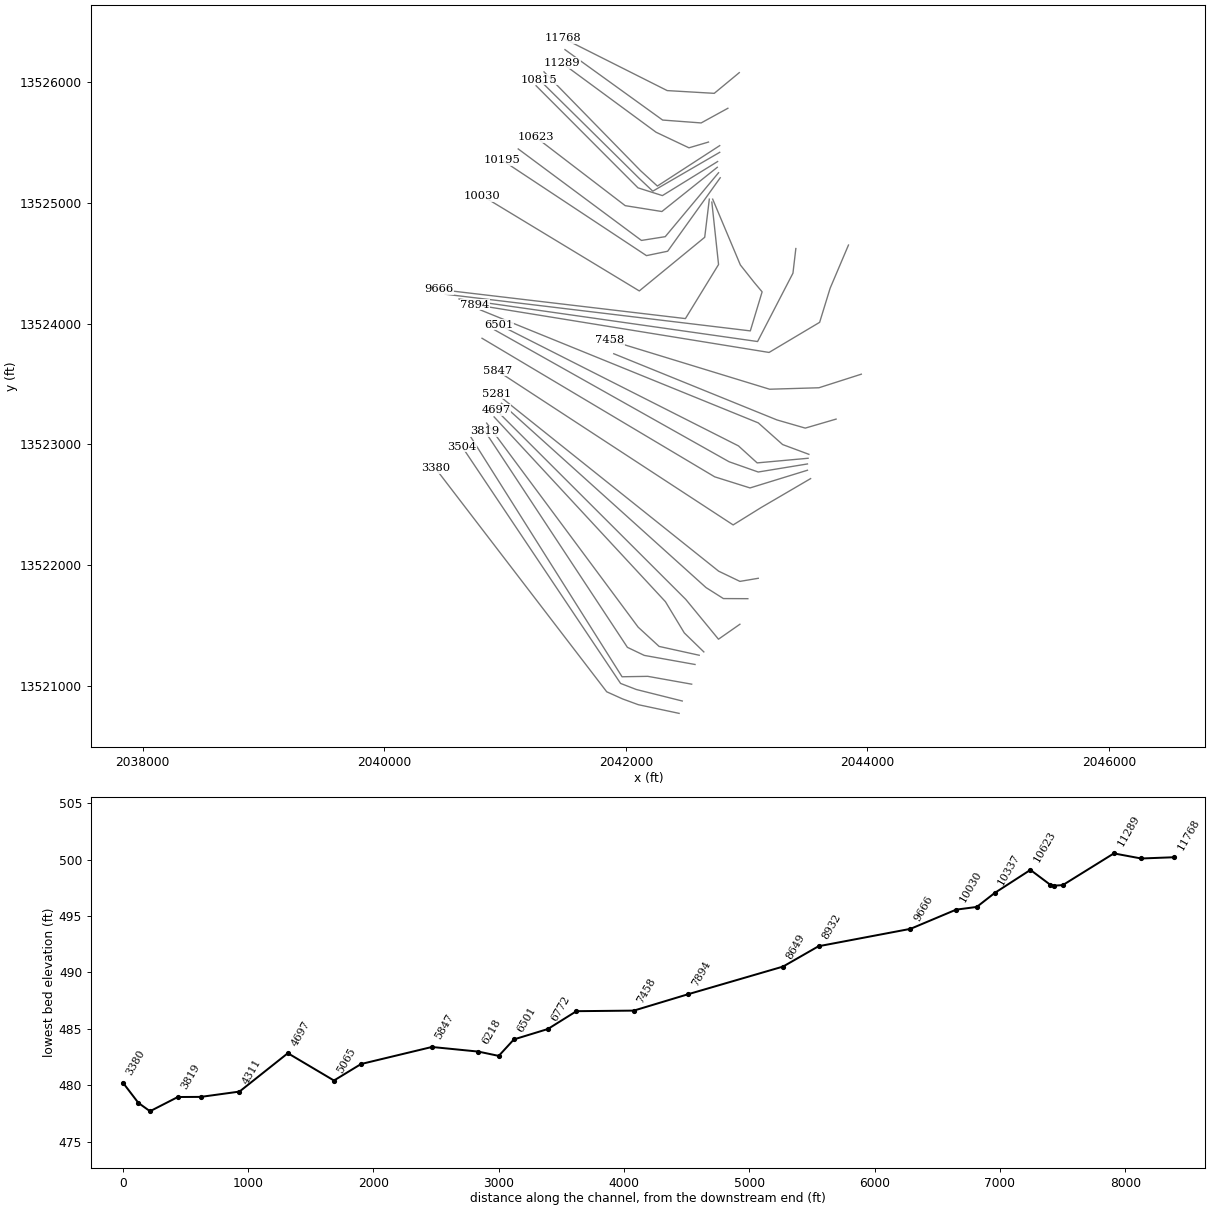
HEC-RAS study ELM Cr.prj: ELM Cr Base Level Engineering

--- ELM Cr.g01 (geometry) --- (continued)

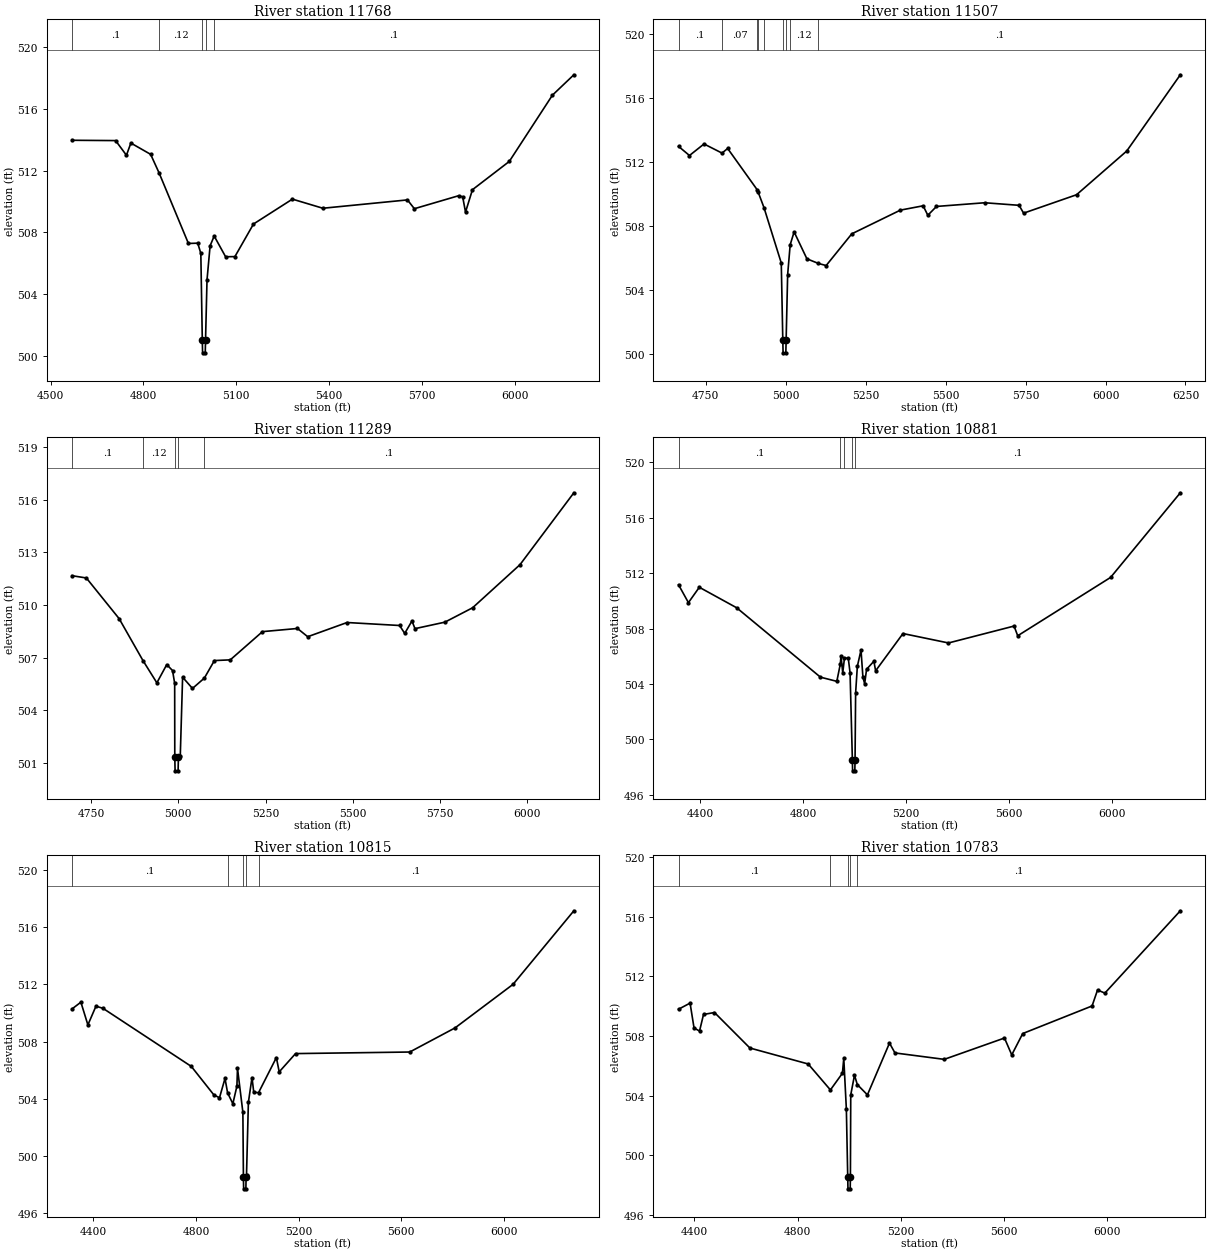
Type RM Length L Ch R = 1,11768,261,261,261
BEGIN DESCRIPTION:
Mapping XS 9a84e8ec
END DESCRIPTION:
XS GIS Cut Line= 4
      2042939.30     13526078.90      2042732.06     13525907.46
      2042342.52     13525930.24      2041482.06     13526363.17
#Sta/Elev= 30
  4569.5  513.96  4710.2  513.94  4745.3  512.99  4759.6  513.78  4823.5  513.05
  4850.8  511.85  4945.7  507.28  4975.8  507.30  4985.8  506.64  4990.6  501.00
  4991.5  500.20  5000.1  500.20  5001.0  501.00  5005.8  504.92  5015.8  507.13
  5029.0  507.76  5065.9  506.42  5096.0  506.43  5156.1  508.54  5281.9  510.15
  5380.4  509.56  5653.9  510.10  5676.2  509.53  5819.2  510.37  5832.4  510.30
  5841.6  509.31  5864.0  510.76  5983.1  512.59  6122.6  516.88  6191.9  518.20
#Mann=5,-1,0
  4569.5     0.1       0  4850.8    0.12       0  4990.6    0.07       0
  5001.0    0.12       0  5029.0     0.1       0
Bank Sta=4990.6,5001
Exp/Cntr=0.3,0.1

Type RM Length L Ch R = 1,11507,218,218,218
BEGIN DESCRIPTION:
Mapping XS 17e5df28
END DESCRIPTION:
XS GIS Cut Line= 4
      2042844.90     13525783.76      2042623.55     13525662.23
      2042304.54     13525686.10      2041495.99     13526269.39
#Sta/Elev= 30
  4664.5  512.98  4698.7  512.41  4744.2  513.13  4800.6  512.56  4818.1  512.85
  4910.9  510.26  4913.6  510.12  4931.7  509.16  4985.8  505.70  4990.6  500.89
  4991.5  500.09  5000.1  500.09  5001.0  500.89  5005.8  504.98  5013.7  506.84
  5026.0  507.64  5066.0  505.96  5102.1  505.67  5126.2  505.54  5206.4  507.52
  5358.4  509.00  5429.5  509.27  5444.2  508.68  5471.3  509.23  5622.2  509.46
  5729.6  509.30  5743.7  508.81  5909.3  509.96  6066.3  512.69  6233.9  517.45
#Mann=9,-1,0
  4664.5     0.1       0  4800.6    0.07       0  4910.9     0.1       0
  4913.6    0.07       0  4931.7     0.1       0  4990.6    0.07       0
  5001.0     0.1       0  5013.7    0.12       0  5102.1     0.1       0
Bank Sta=4990.6,5001
Exp/Cntr=0.3,0.1

Type RM Length L Ch R = 1,11289,408,408,408
BEGIN DESCRIPTION:
Mapping XS 3fd61b72
END DESCRIPTION:
XS GIS Cut Line= 4
      2042684.27     13525503.80      2042522.64     13525456.07
      2042250.29     13525585.19      2041471.62     13526158.33
#Sta/Elev= 30
  4696.1  511.67  4737.0  511.54  4830.9  509.22  4899.1  506.83  4938.9  505.56
  4967.2  506.60  4983.8  506.26  4989.9  505.53  4990.2  501.34  4991.1  500.54
  4999.7  500.54  5000.6  501.34  5005.9  501.37  5012.6  505.88  5040.9  505.24
  5074.9  505.83  5103.6  506.83  5149.1  506.87  5241.3  508.48  5341.5  508.66
  5370.8  508.19  5483.5  509.00  5633.9  508.83  5648.6  508.38  5669.4  509.09
  5677.9  508.65  5763.5  509.02  5842.9  509.84  5978.7  512.30  6132.9  516.40
#Mann=5,-1,0
  4696.1     0.1       0  4899.1    0.12       0  4990.2    0.07       0
  5000.6    0.12       0  5074.9     0.1       0
Bank Sta=4990.2,5000.6
Exp/Cntr=0.3,0.1

Type RM Length L Ch R = 1,10881,66,66,66
BEGIN DESCRIPTION:
Mapping XS fe2c94e0
END DESCRIPTION:
XS GIS Cut Line= 4
      2042777.21     13525474.28      2042261.14     13525139.23
      2042122.25     13525266.18      2041322.37     13526085.36
#Sta/Elev= 30
  4316.5  511.16  4354.9  509.87  4397.2  510.98  4542.2  509.50  4867.6  504.49
  4931.1  504.19  4944.6  505.43  4947.3  506.04  4954.1  504.80  4960.9  505.89
  4975.7  505.84  4982.5  504.81  4991.5  498.53  4992.3  497.73  5001.0  497.73
  5001.9  498.53  5004.1  503.35  5010.8  505.27  5025.0  506.45  5032.4  504.50
  5039.2  504.01  5046.6  505.06  5075.0  505.64  5081.8  504.95  5188.0  507.64
  5364.7  506.96  5619.3  508.18  5633.5  507.48  5994.1  511.69  6264.9  517.80
#Mann=5,-1,0
  4316.5     0.1       0  4944.6    0.12       0  4960.9     0.1       0
  4991.5    0.07       0  5001.9     0.1       0
Bank Sta=4991.5,5001.9
Exp/Cntr=0.3,0.1

Type RM Length L Ch R = 1,10815,32,32,32
BEGIN DESCRIPTION:
Mapping XS ab2c24bb
END DESCRIPTION:
XS GIS Cut Line= 4
      2042777.24     13525418.74      2042223.16     13525096.91
      2042109.23     13525204.33      2041284.18     13526019.39
#Sta/Elev= 30
  4316.8  510.29  4351.2  510.76  4378.5  509.17  4410.0  510.48  4437.3  510.33
  4782.0  506.26  4870.2  504.26  4891.8  504.07  4913.3  505.42  4923.4  504.41
  4943.9  503.65  4959.7  504.88  4962.0  506.13  4983.0  503.05  4985.1  498.49
  4986.0  497.69  4994.7  497.69  4995.5  498.49  4997.2  498.68  5004.5  503.75
  5018.6  505.48  5025.5  504.44  5044.3  504.43  5113.6  506.88  5124.7  505.88
  5188.4  507.16  5633.8  507.27  5810.6  508.96  6036.8  512.01  6273.9  517.16
#Mann=5,-1,0
  4316.8     0.1       0  4923.4    0.12       0  4985.1    0.07       0
  4995.5    0.12       0  5044.3     0.1       0
Bank Sta=4985.1,4995.5
Exp/Cntr=0.3,0.1

Type RM Length L Ch R = 1,10783,160,160,160
BEGIN DESCRIPTION:
Mapping XS 0c3f4220
END DESCRIPTION:
XS GIS Cut Line= 4
      2042759.88     13525342.35      2042302.80     13525060.23
      2042100.55     13525124.47      2041256.81     13525970.37
#Sta/Elev= 30
  4338.4  509.79  4383.1  510.20  4398.5  508.53  4419.8  508.33  4435.2  509.44
  4477.7  509.57  4614.9  507.19  4840.7  506.12  4926.8  504.38  4973.4  505.50
  4978.6  506.50  4988.6  503.10  4993.9  498.55  4994.8  497.75  5003.5  497.75
  5004.3  498.55  5005.6  504.05  5020.1  505.37  5031.0  504.74  5070.2  504.05
  5155.7  507.52  5176.9  506.86  5367.8  506.43  5601.2  507.86  5629.4  506.73
  5671.9  508.16  5940.6  510.01  5961.8  511.08  5990.1  510.87  6282.5  516.39
#Mann=5,-1,0
  4338.4     0.1       0  4926.8    0.12       0  4993.9    0.07       0
  5004.3    0.12       0  5031.0     0.1       0
Bank Sta=4993.9,5004.3
Exp/Cntr=0.3,0.1

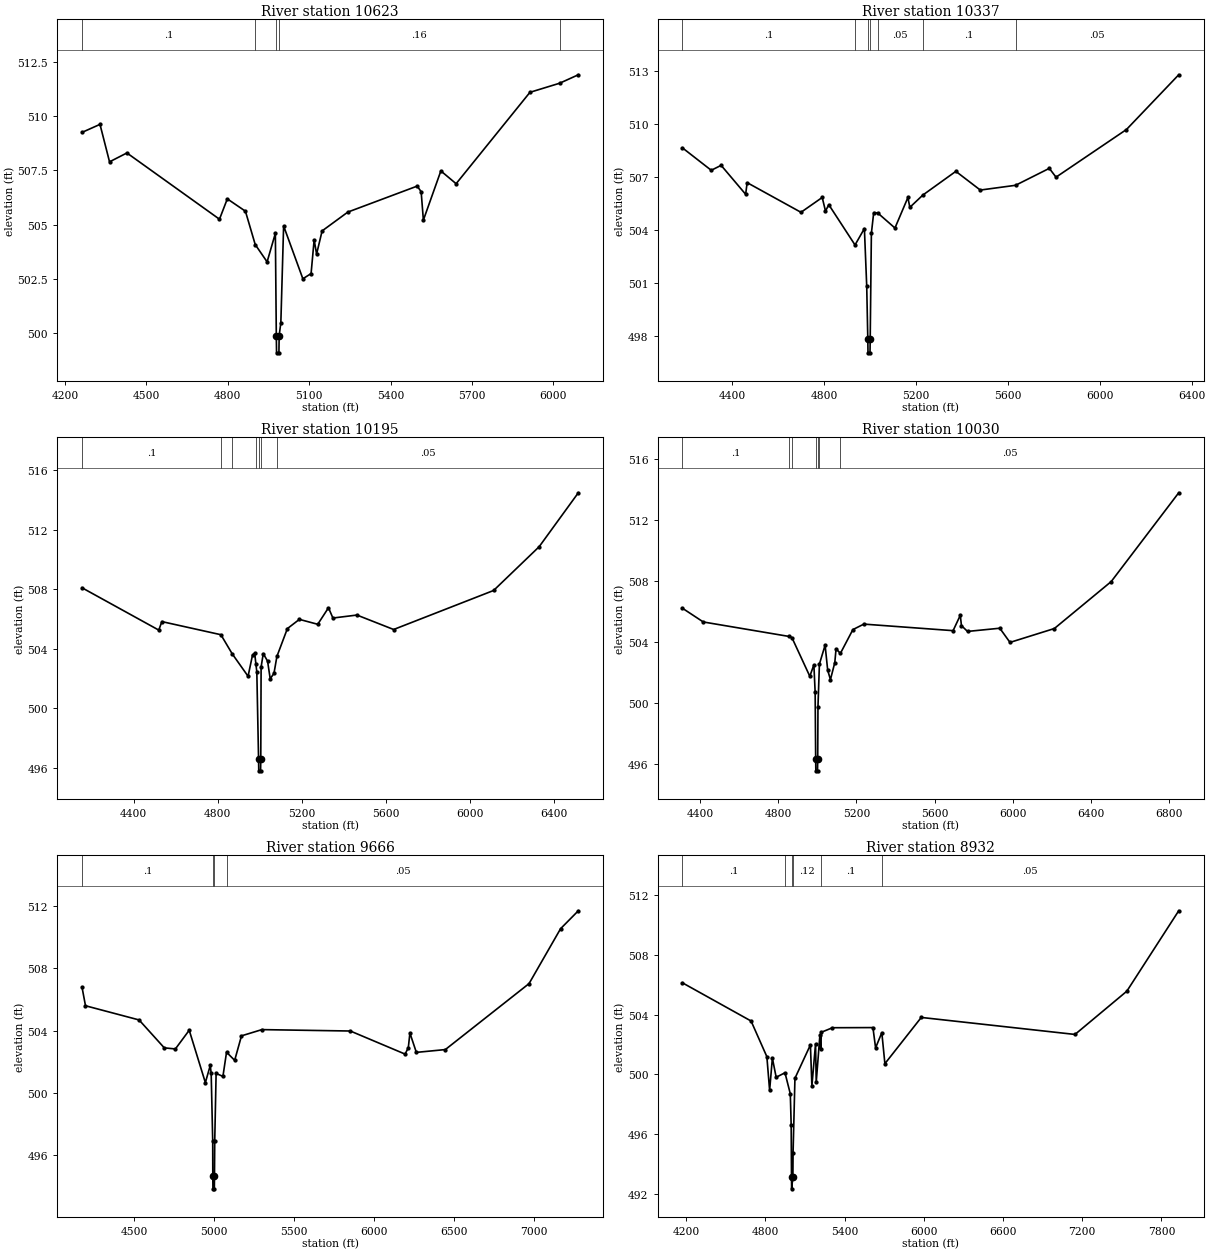
Type RM Length L Ch R = 1,10623,286,286,286
BEGIN DESCRIPTION:
Mapping XS 70d38d58
END DESCRIPTION:
XS GIS Cut Line= 4
      2042757.27     13525294.70      2042298.46     13524928.29
      2041994.64     13524976.90      2041253.74     13525544.70
#Sta/Elev= 30
  4263.3  509.26  4329.4  509.63  4364.6  507.90  4428.6  508.31  4769.6  505.25
  4798.5  506.19  4865.2  505.62  4901.3  504.08  4945.1  503.28  4975.5  504.60
  4979.0  499.88  4979.9  499.08  4988.6  499.08  4989.5  499.88  4995.7  500.47
  5005.9  504.94  5076.8  502.50  5107.1  502.74  5118.4  504.30  5127.4  503.64
  5147.7  504.71  5242.5  505.58  5498.1  506.78  5512.6  506.52  5520.8  505.21
  5585.2  507.48  5641.4  506.89  5913.4  511.11  6022.8  511.53  6091.6  511.92
#Mann=5,-1,0
  4263.3     0.1       0  4901.3    0.16       0  4979.0    0.07       0
  4989.5    0.16       0  6022.8    0.05       0
Bank Sta=4979,4989.5
Exp/Cntr=0.3,0.1

Type RM Length L Ch R = 1,10337,142,142,142
BEGIN DESCRIPTION:
Mapping XS afe3d079
END DESCRIPTION:
XS GIS Cut Line= 4
      2042767.64     13525249.51      2042326.24     13524719.96
      2042129.19     13524688.71      2041108.95     13525446.70
#Sta/Elev= 30
  4183.6  508.64  4309.0  507.37  4352.0  507.65  4458.7  506.01  4465.2  506.67
  4699.5  504.99  4791.9  505.83  4806.2  505.06  4820.6  505.42  4934.7  503.14
  4975.5  504.07  4985.6  500.81  4990.3  497.83  4991.2  497.03  4999.9  497.03
  5000.8  497.83  5005.9  503.80  5016.0  504.97  5033.8  504.95  5108.5  504.10
  5164.9  505.83  5173.2  505.27  5230.2  505.97  5373.5  507.31  5479.9  506.25
  5633.3  506.52  5780.3  507.48  5809.5  506.98  6116.1  509.68  6343.5  512.78
#Mann=7,-1,0
  4183.6     0.1       0  4934.7    0.12       0  4990.3    0.07       0
  5000.8    0.12       0  5033.8    0.05       0  5230.2     0.1       0
  5633.3    0.05       0
Bank Sta=4990.3,5000.8
Exp/Cntr=0.3,0.1

Type RM Length L Ch R = 1,10195,165,165,165
BEGIN DESCRIPTION:
Mapping XS abf590ec
END DESCRIPTION:
XS GIS Cut Line= 4
      2042781.55     13525207.87      2042346.21     13524599.30
      2042170.86     13524562.84      2040976.03     13525353.68
#Sta/Elev= 30
  4154.3  508.09  4519.2  505.25  4534.0  505.82  4814.6  504.94  4868.3  503.66
  4943.9  502.15  4965.1  503.58  4975.3  503.70  4981.2  502.97  4985.5  502.44
  4993.8  496.60  4994.7  495.80  5003.4  495.80  5004.3  496.60  5005.9  502.77
  5016.1  503.67  5036.6  503.17  5049.2  501.98  5067.2  502.35  5081.0  503.48
  5130.8  505.35  5187.9  505.97  5275.2  505.64  5326.3  506.75  5347.4  506.06
  5461.7  506.26  5636.2  505.29  6111.6  507.91  6328.3  510.85  6514.5  514.47
#Mann=7,-1,0
  4154.3     0.1       0  4814.6    0.07       0  4868.3    0.12       0
  4981.2     0.1       0  4993.8    0.07       0  5004.3     0.1       0
  5081.0    0.05       0
Bank Sta=4993.8,5004.3
Exp/Cntr=0.3,0.1

Type RM Length L Ch R = 1,10030,364,364,364
BEGIN DESCRIPTION:
Mapping XS 058432c2
END DESCRIPTION:
XS GIS Cut Line= 4
      2042691.27     13525030.82      2042653.08     13524714.82
      2042111.41     13524270.37      2040812.49     13525057.36
#Sta/Elev= 30
  4310.4  506.22  4417.0  505.32  4856.2  504.37  4870.0  504.30  4961.7  501.76
  4982.5  502.51  4989.0  500.71  4991.6  496.36  4992.5  495.56  5001.2  495.56
  5002.1  496.36  5003.4  499.75  5010.8  502.56  5039.9  503.80  5053.1  502.16
  5067.2  501.54  5089.5  502.66  5095.9  503.56  5118.1  503.26  5182.0  504.82
  5238.0  505.18  5694.4  504.75  5731.2  505.76  5737.1  505.08  5768.1  504.70
  5933.2  504.91  5985.3  503.98  6212.2  504.89  6503.0  507.97  6848.1  513.79
#Mann=7,-1,0
  4310.4     0.1       0  4856.2    0.07       0  4870.0    0.12       0
  4991.6    0.07       0  5002.1    0.12       0  5010.8     0.1       0
  5118.1    0.05       0
Bank Sta=4991.6,5002.1
Exp/Cntr=0.3,0.1

Type RM Length L Ch R = 1,9666,734,734,734
BEGIN DESCRIPTION:
Mapping XS 5331390b
END DESCRIPTION:
XS GIS Cut Line= 4
      2042712.11     13525006.45      2042767.66     13524489.12
      2042493.35     13524041.20      2040448.94     13524282.93
#Sta/Elev= 30
  4173.2  506.78  4194.8  505.60  4529.9  504.69  4687.6  502.90  4757.0  502.83
  4843.6  504.03  4944.6  500.67  4975.1  501.77  4980.9  501.28  4990.5  496.95
  4991.1  494.66  4992.0  493.86  5000.7  493.86  5001.6  494.66  5003.2  496.94
  5011.8  501.26  5054.4  501.07  5077.0  502.62  5127.9  502.10  5170.5  503.67
  5298.2  504.07  5851.5  503.98  6193.8  502.50  6214.0  502.91  6224.0  503.85
  6264.3  502.61  6445.6  502.79  6969.2  507.02  7166.4  510.54  7277.4  511.69
#Mann=4,-1,0
  4173.2     0.1       0  4991.1    0.07       0  5001.6     0.1       0
  5077.0    0.05       0
Bank Sta=4991.1,5001.6
Exp/Cntr=0.3,0.1

Type RM Length L Ch R = 1,8932,283,283,283
BEGIN DESCRIPTION:
Mapping XS e9348a9c
END DESCRIPTION:
XS GIS Cut Line= 6
      2042719.06     13525030.75      2042948.21     13524485.65
      2043062.79     13524340.92      2043128.41     13524262.79
      2043030.76     13523939.27      2040504.73     13524243.09
#Sta/Elev= 30
  4171.3  506.13  4691.3  503.57  4810.9  501.18  4831.8  498.92  4852.7  501.08
  4881.4  499.80  4948.2  500.10  4988.5  498.69  4995.1  496.62  4997.6  493.12
  4998.5  492.32  5008.1  493.12  5009.4  494.72  5023.7  499.73  5140.9  501.97
  5152.1  499.22  5179.8  502.04  5185.0  499.47  5212.8  502.63  5218.6  501.67
  5224.5  502.82  5308.1  503.12  5614.6  503.13  5634.7  501.77  5681.9  502.79
  5705.2  500.71  5980.8  503.81  7145.5  502.67  7538.3  505.57  7931.4  510.96
#Mann=6,-1,0
  4171.3     0.1       0  4948.2    0.12       0  4997.6    0.07       0
  5008.1    0.12       0  5218.6     0.1       0  5681.9    0.05       0
Bank Sta=4997.6,5008.1
Exp/Cntr=0.3,0.1

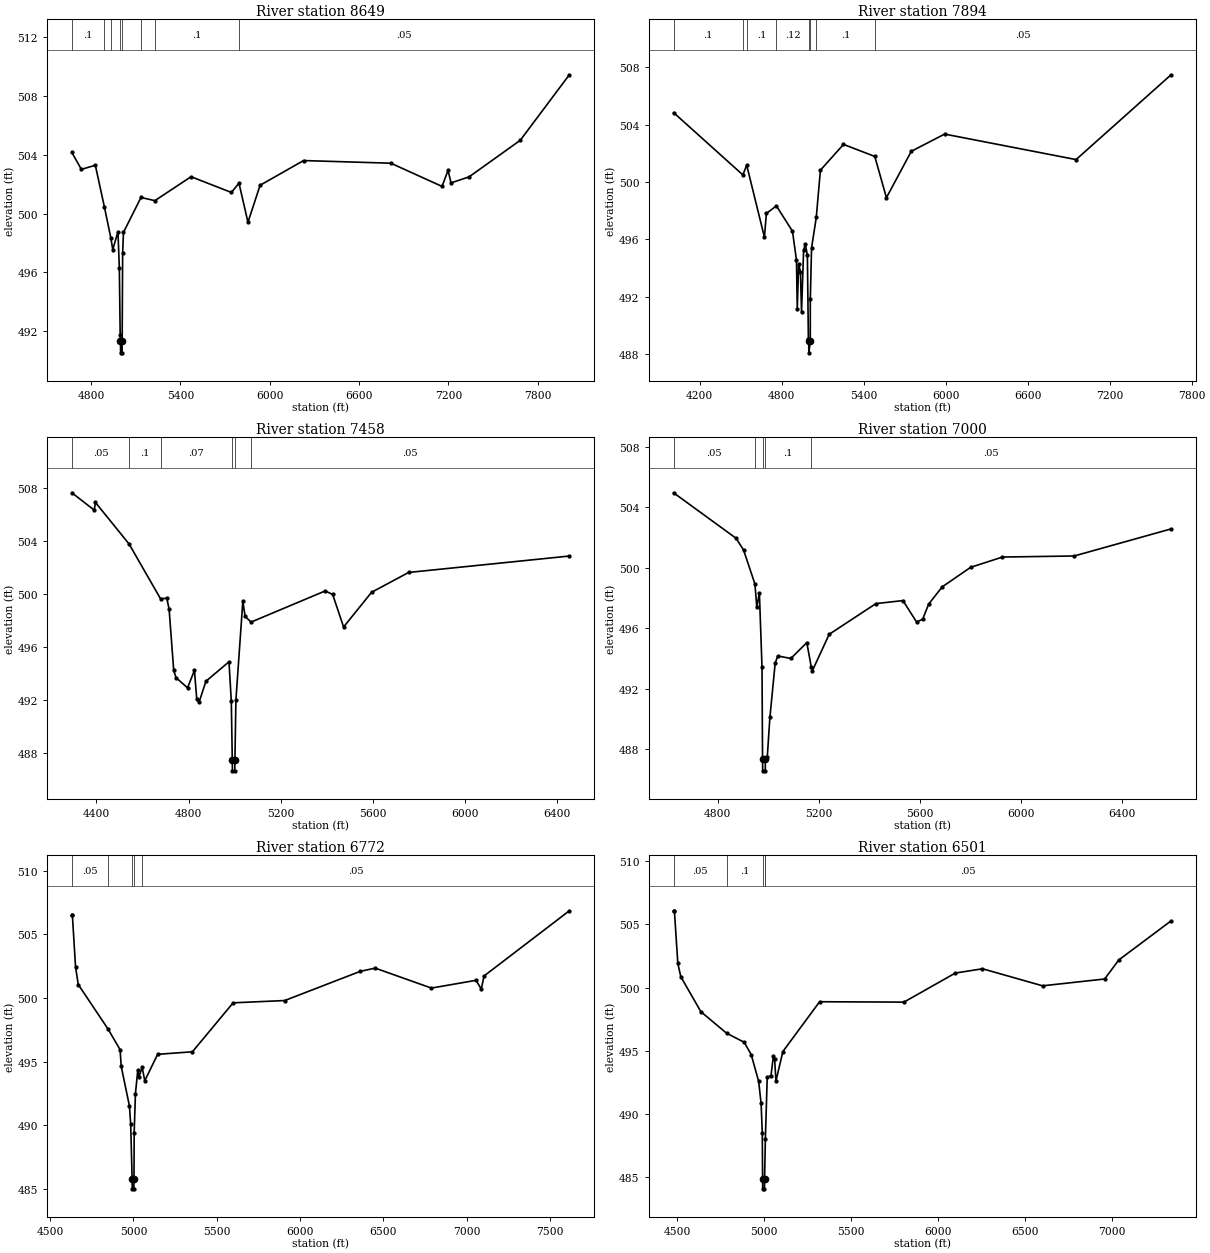
Type RM Length L Ch R = 1,8649,755,755,755
BEGIN DESCRIPTION:
Mapping XS d88111e9
END DESCRIPTION:
XS GIS Cut Line= 4
      2043407.66     13524621.58      2043383.79     13524417.56
      2043090.82     13523851.15      2040618.76     13524203.86
#Sta/Elev= 30
  4671.4  504.16  4735.4  503.01  4829.0  503.29  4890.2  500.44  4933.8  498.31
  4946.0  497.55  4981.0  498.76  4990.3  496.27  4995.9  491.73  4997.9  491.32
  4998.6  490.52  5008.5  490.52  5009.2  491.32  5012.4  497.31  5018.0  498.72
  5135.7  501.10  5228.6  500.88  5471.8  502.51  5742.6  501.44  5793.6  502.07
  5853.7  499.41  5935.4  501.93  6227.5  503.61  6813.3  503.43  7156.8  501.85
  7197.2  502.94  7217.4  502.09  7338.6  502.50  7682.1  504.99  8011.6  509.45
#Mann=8,-1,0
  4671.4     0.1       0  4890.2    0.12       0  4933.8    0.07       0
  4997.9    0.07       0  5009.2    0.07       0  5135.7    0.12       0
  5228.6     0.1       0  5793.6    0.05       0
Bank Sta=4997.9,5009.2
Exp/Cntr=0.3,0.1

Type RM Length L Ch R = 1,7894,436,436,436
BEGIN DESCRIPTION:
Mapping XS 6a66fbd6
END DESCRIPTION:
XS GIS Cut Line= 5
      2043843.46     13524650.47      2043691.53     13524292.37
      2043604.73     13524010.25      2043185.89     13523760.69
      2040748.88     13524156.10
#Sta/Elev= 30
  4008.6  504.85  4515.8  500.50  4543.8  501.18  4673.5  496.15  4687.7  497.81
  4761.0  498.34  4878.7  496.57  4908.0  494.55  4913.8  491.12  4923.6  494.29
  4936.9  493.75  4945.0  490.94  4960.2  495.24  4972.2  495.69  4987.8  494.90
  4995.1  489.04  4997.7  488.88  4998.3  488.08  5009.1  488.88  5009.2  491.82
  5018.4  495.40  5052.8  497.53  5083.2  500.83  5252.1  502.63  5481.1  501.79
  5566.2  498.91  5748.5  502.15  5992.2  503.35  6954.1  501.57  7649.2  507.49
#Mann=8,-1,0
  4008.6     0.1       0  4515.8    0.07       0  4543.8     0.1       0
  4761.0    0.12       0  4997.7    0.07       0  5009.1    0.12       0
  5052.8     0.1       0  5481.1    0.05       0
Bank Sta=4997.7,5009.1
Exp/Cntr=0.3,0.1

Type RM Length L Ch R = 1,7458,458,458,458
BEGIN DESCRIPTION:
Mapping XS cd0ceef7
END DESCRIPTION:
XS GIS Cut Line= 4
      2043949.78     13523580.56      2043598.65     13523468.11
      2043190.66     13523455.96      2041867.58     13523861.14
#Sta/Elev= 30
  4293.3  507.63  4390.5  506.32  4395.8  506.90  4542.2  503.75  4678.5  499.62
  4705.7  499.66  4715.7  498.83  4735.7  494.21  4745.7  493.66  4795.7  492.89
  4825.7  494.21  4835.7  492.05  4845.7  491.80  4875.7  493.39  4975.8  494.86
  4985.8  491.88  4990.1  487.42  4990.7  486.62  5000.8  486.62  5001.5  487.42
  5005.8  491.97  5035.8  499.43  5045.8  498.29  5071.7  497.86  5393.2  500.21
  5426.0  499.95  5473.5  497.49  5595.0  500.11  5755.9  501.61  6453.9  502.85
#Mann=6,-1,0
  4293.3    0.05       0  4542.2     0.1       0  4678.5    0.07       0
  4990.1    0.07       0  5001.5    0.07       0  5071.7    0.05       0
Bank Sta=4990.1,5001.5
Exp/Cntr=0.3,0.1

Type RM Length L Ch R = 1,7000,228,228,228
BEGIN DESCRIPTION:
Mapping XS 2df3b3b3
END DESCRIPTION:
XS GIS Cut Line= 4
      2043740.91     13523208.44      2043485.75     13523133.80
      2043251.37     13523201.51      2041899.96     13523750.02
#Sta/Elev= 30
  4624.9  504.96  4872.3  501.95  4901.9  501.17  4946.7  498.93  4954.2  497.41
  4964.4  498.34  4974.8  493.43  4976.9  487.37  4977.5  486.57  4987.6  486.57
  4988.3  487.37  4995.6  487.48  5006.0  490.10  5026.9  493.70  5037.3  494.17
  5088.7  494.00  5152.1  495.05  5169.3  493.47  5174.0  493.19  5240.6  495.60
  5425.4  497.63  5532.5  497.83  5586.1  496.42  5610.2  496.59  5634.3  497.60
  5687.9  498.74  5800.4  500.03  5926.2  500.71  6210.0  500.78  6593.2  502.57
#Mann=5,-1,0
  4624.9    0.05       0  4946.7     0.1       0  4976.9    0.07       0
  4988.3     0.1       0  5169.3    0.05       0
Bank Sta=4976.9,4988.3
Exp/Cntr=0.3,0.1

Type RM Length L Ch R = 1,6772,271,271,271
BEGIN DESCRIPTION:
Mapping XS a1555649
END DESCRIPTION:
XS GIS Cut Line= 4
      2043515.71     13522916.52      2043298.25     13522997.52
      2043096.92     13523176.92      2040795.49     13524112.89
#Sta/Elev= 30
  4630.2  506.55  4633.2  506.55  4652.3  502.45  4668.6  501.06  4848.4  497.54
  4919.8  495.93  4926.5  494.62  4975.8  491.51  4983.4  490.07  4991.9  485.79
  4992.5  484.99  5002.6  484.99  5003.3  485.79  5004.3  489.40  5011.8  492.46
  5026.0  494.34  5032.7  493.81  5052.5  494.54  5067.8  493.49  5145.1  495.57
  5353.9  495.77  5598.2  499.62  5907.9  499.80  6360.2  502.09  6451.0  502.35
  6788.5  500.78  7056.1  501.39  7088.0  500.70  7104.3  501.73  7616.4  506.86
#Mann=5,-1,0
  4630.2    0.05       0  4848.4     0.1       0  4991.9    0.07       0
  5003.3     0.1       0  5052.5    0.05       0
Bank Sta=4991.9,5003.3
Exp/Cntr=0.3,0.1

Type RM Length L Ch R = 1,6501,121,121,121
BEGIN DESCRIPTION:
Mapping XS 79397a3d
END DESCRIPTION:
XS GIS Cut Line= 4
      2043509.27     13522883.95      2043087.35     13522845.56
      2042932.84     13522986.19      2040947.47     13523991.33
#Sta/Elev= 30
  4480.4  506.08  4485.1  506.08  4504.8  501.92  4521.9  500.86  4637.3  498.09
  4784.9  496.39  4886.3  495.67  4926.5  494.69  4969.1  492.58  4983.3  490.83
  4990.0  488.46  4991.8  484.87  4992.4  484.07  5002.5  484.07  5003.2  484.87
  5007.7  488.01  5018.4  492.91  5040.0  493.02  5054.2  494.62  5061.0  494.32
  5068.4  492.60  5108.4  494.94  5319.3  498.88  5803.8  498.85  6099.0  501.15
  6255.0  501.49  6600.2  500.14  6956.7  500.68  7038.4  502.19  7338.3  505.28
#Mann=5,-1,0
  4480.4    0.05       0  4784.9     0.1       0  4991.8    0.07       0
  5003.2     0.1       0  5007.7    0.05       0
Bank Sta=4991.8,5003.2
Exp/Cntr=0.3,0.1

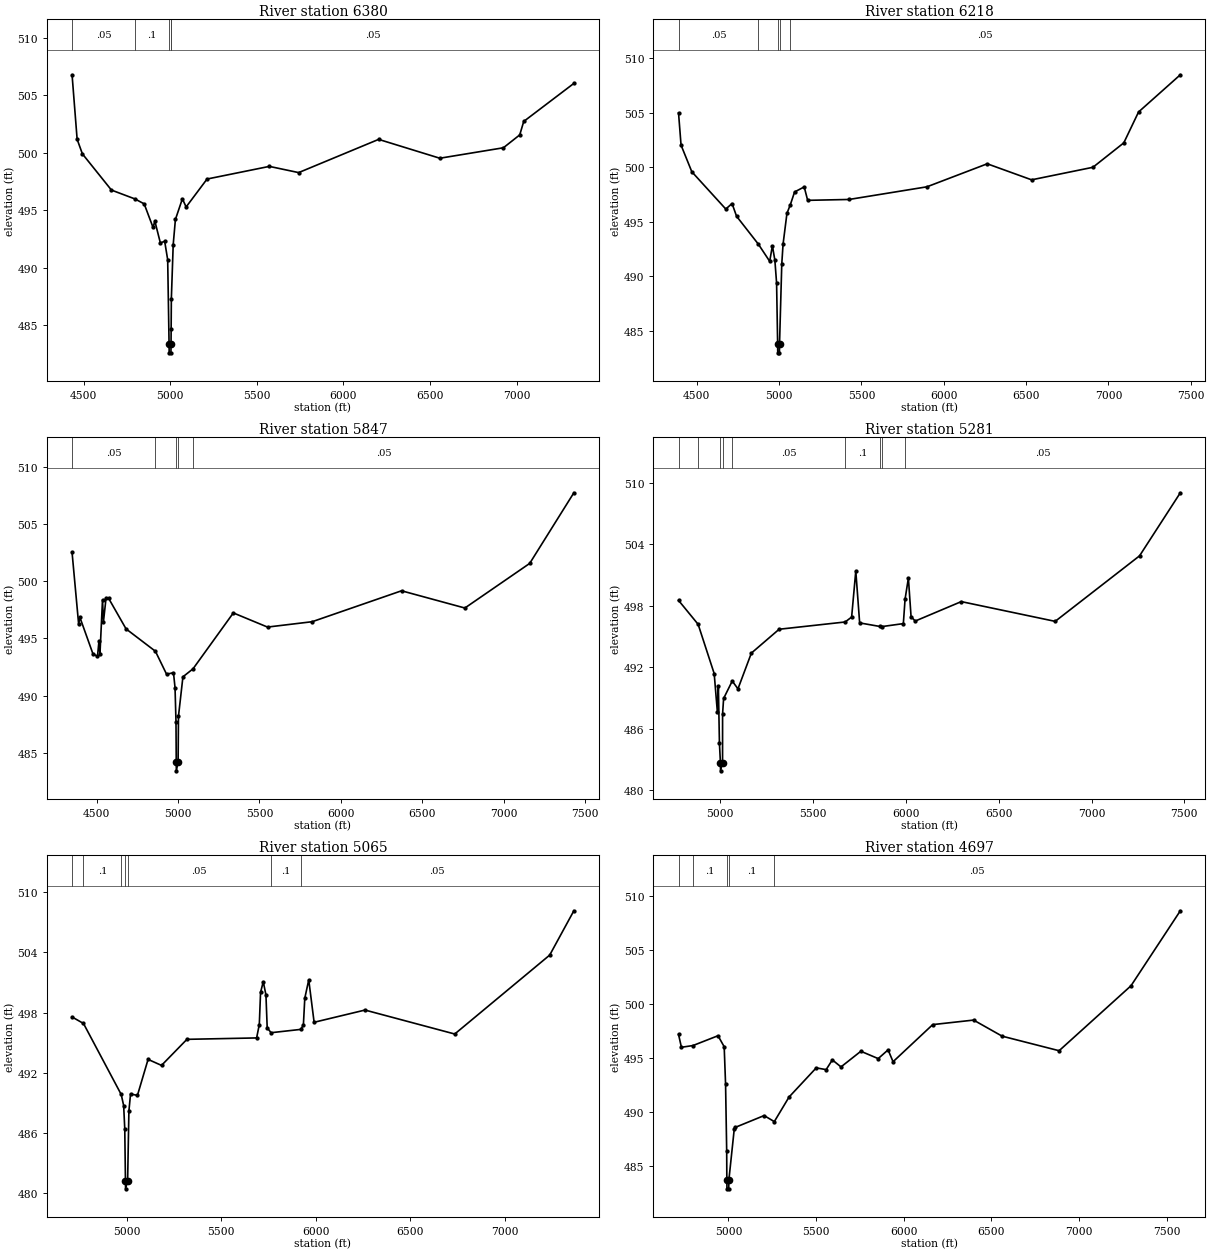
Type RM Length L Ch R = 1,6380,162,162,162
BEGIN DESCRIPTION:
Mapping XS c8d47849
END DESCRIPTION:
XS GIS Cut Line= 4
      2043503.81     13522836.83      2043096.03     13522770.04
      2042854.71     13522855.11      2040912.67     13523947.97
#Sta/Elev= 30
  4432.8  506.80  4462.0  501.19  4492.4  499.92  4660.1  496.77  4795.7  496.00
  4849.2  495.57  4900.1  493.53  4911.0  494.06  4942.5  492.18  4967.6  492.31
  4984.9  490.71  4992.9  483.41  4993.5  482.61  5003.7  482.61  5004.3  483.41
  5004.9  484.71  5006.1  487.32  5016.8  492.03  5029.5  494.21  5069.8  496.01
  5091.4  495.30  5212.2  497.73  5572.0  498.83  5741.2  498.29  6203.1  501.18
  6556.3  499.54  6923.5  500.45  7017.8  501.57  7040.8  502.74  7330.3  506.05
#Mann=5,-1,0
  4432.8    0.05       0  4795.7     0.1       0  4992.9    0.07       0
  5004.3     0.1       0  5004.9    0.05       0
Bank Sta=4992.9,5004.3
Exp/Cntr=0.3,0.1

Type RM Length L Ch R = 1,6218,371,371,371
BEGIN DESCRIPTION:
Mapping XS 7c84529d
END DESCRIPTION:
XS GIS Cut Line= 4
      2043503.81     13522784.74      2043028.32     13522638.10
      2042735.79     13522730.11      2040809.23     13523878.09
#Sta/Elev= 30
  4389.7  504.98  4405.0  502.03  4470.3  499.59  4676.7  496.17  4714.6  496.68
  4742.1  495.51  4874.5  492.95  4943.2  491.38  4959.6  492.80  4974.6  491.49
  4985.1  489.39  4991.5  483.79  4992.1  482.99  5002.3  482.99  5002.9  483.79
  5016.6  491.15  5024.4  492.95  5048.0  495.78  5068.6  496.57  5094.4  497.74
  5152.8  498.20  5173.8  496.97  5425.0  497.05  5898.1  498.21  6264.1  500.32
  6533.5  498.85  6906.0  500.00  7093.4  502.24  7183.0  505.07  7436.6  508.48
#Mann=5,-1,0
  4389.7    0.05       0  4874.5     0.1       0  4991.5    0.07       0
  5002.9     0.1       0  5068.6    0.05       0
Bank Sta=4991.5,5002.9
Exp/Cntr=0.3,0.1

Type RM Length L Ch R = 1,5847,566,566,566
BEGIN DESCRIPTION:
Mapping XS 21c43478
END DESCRIPTION:
XS GIS Cut Line= 4
      2043529.85     13522715.29      2043120.34     13522475.77
      2042888.57     13522331.67      2040934.44     13523609.39
#Sta/Elev= 30
  4349.5  502.54  4389.9  496.25  4397.6  496.85  4477.8  493.65  4505.7  493.43
  4515.0  494.81  4520.8  493.63  4536.5  498.40  4542.3  496.48  4558.0  498.51
  4573.6  498.53  4681.1  495.84  4861.4  493.88  4929.9  491.87  4972.4  492.00
  4981.9  490.70  4987.8  487.72  4989.4  484.20  4990.0  483.40  5000.8  484.20
  5003.1  488.19  5030.4  491.64  5092.4  492.34  5340.0  497.24  5549.9  496.00
  5824.3  496.47  6373.2  499.18  6762.2  497.67  7160.4  501.58  7431.6  507.77
#Mann=5,-1,0
  4349.5    0.05       0  4861.4     0.1       0  4989.4    0.07       0
  5000.8     0.1       0  5092.4    0.05       0
Bank Sta=4989.4,5000.8
Exp/Cntr=0.3,0.1

Type RM Length L Ch R = 1,5281,216,216,216
BEGIN DESCRIPTION:
Mapping XS 731d1d3b
END DESCRIPTION:
XS GIS Cut Line= 4
      2043096.66     13521889.53      2042944.61     13521863.84
      2042768.23     13521948.57      2040930.04     13523418.46
#Sta/Elev= 30
  4775.0  498.54  4880.6  496.20  4967.1  491.39  4984.2  487.65  4989.7  490.15
  4995.3  484.60  5000.7  482.69  5001.3  481.89  5012.2  482.69  5012.3  487.45
  5017.9  488.96  5064.3  490.66  5095.2  489.90  5167.4  493.39  5317.0  495.72
  5672.7  496.43  5707.6  496.91  5730.0  501.41  5750.8  496.34  5860.5  495.99
  5870.5  495.98  5986.2  496.27  5995.5  498.66  6013.4  500.72  6027.8  496.95
  6050.2  496.52  6298.3  498.42  6804.2  496.49  7258.8  502.89  7478.5  509.05
#Mann=9,-1,0
  4775.0    0.05       0  4880.6     0.1       0  5000.7    0.07       0
  5012.2     0.1       0  5064.3    0.05       0  5672.7     0.1       0
  5860.5    0.05       0  5870.5     0.1       0  5995.5    0.05       0
Bank Sta=5000.7,5012.2
Exp/Cntr=0.3,0.1

Type RM Length L Ch R = 1,5065,368,368,368
BEGIN DESCRIPTION:
Mapping XS d53a2722
END DESCRIPTION:
XS GIS Cut Line= 4
      2043010.39     13521720.55      2042807.81     13521721.48
      2042664.06     13521812.45      2040969.73     13523339.77
#Sta/Elev= 30
  4710.4  497.57  4770.8  496.92  4970.3  489.84  4983.2  488.74  4989.1  486.42
  4992.7  481.23  4993.4  480.43  5004.2  481.23  5011.0  488.20  5019.7  489.89
  5056.1  489.75  5112.4  493.34  5183.4  492.74  5317.9  495.34  5686.4  495.48
  5700.6  496.81  5707.3  500.02  5721.5  501.09  5735.7  499.77  5742.4  496.49
  5762.8  496.00  5919.5  496.33  5933.7  496.75  5941.2  499.44  5962.1  501.27
  5990.5  497.04  6259.6  498.26  6734.2  495.87  7236.4  503.74  7364.2  508.16
#Mann=7,-1,0
  4710.4    0.05       0  4770.8     0.1       0  4970.3    0.05       0
  4992.7    0.03       0  5004.2    0.05       0  5762.8     0.1       0
  5919.5    0.05       0
Bank Sta=4992.7,5004.2
Exp/Cntr=0.3,0.1

Type RM Length L Ch R = 1,4697,386,386,386
BEGIN DESCRIPTION:
Mapping XS d20af3ac
END DESCRIPTION:
XS GIS Cut Line= 4
      2042944.42     13521508.72      2042767.05     13521384.78
      2042496.22     13521714.64      2040925.74     13523283.88
#Sta/Elev= 30
  4715.4  497.16  4731.8  495.97  4797.8  496.13  4940.7  497.04  4975.9  496.02
  4983.8  492.55  4990.2  486.34  4991.0  483.65  4991.7  482.85  5001.9  482.85
  5002.5  483.65  5033.3  488.39  5039.7  488.55  5203.8  489.64  5261.9  489.08
  5346.1  491.36  5501.1  494.06  5557.7  493.90  5593.0  494.80  5642.5  494.15
  5755.7  495.60  5854.7  494.92  5911.2  495.73  5939.5  494.63  6165.8  498.07
  6399.1  498.49  6561.8  497.00  6887.0  495.65  7297.2  501.67  7578.7  508.62
#Mann=5,-1,0
  4715.4    0.05       0  4797.8     0.1       0  4991.0    0.07       0
  5002.5     0.1       0  5261.9    0.05       0
Bank Sta=4991,5002.5
Exp/Cntr=0.3,0.1

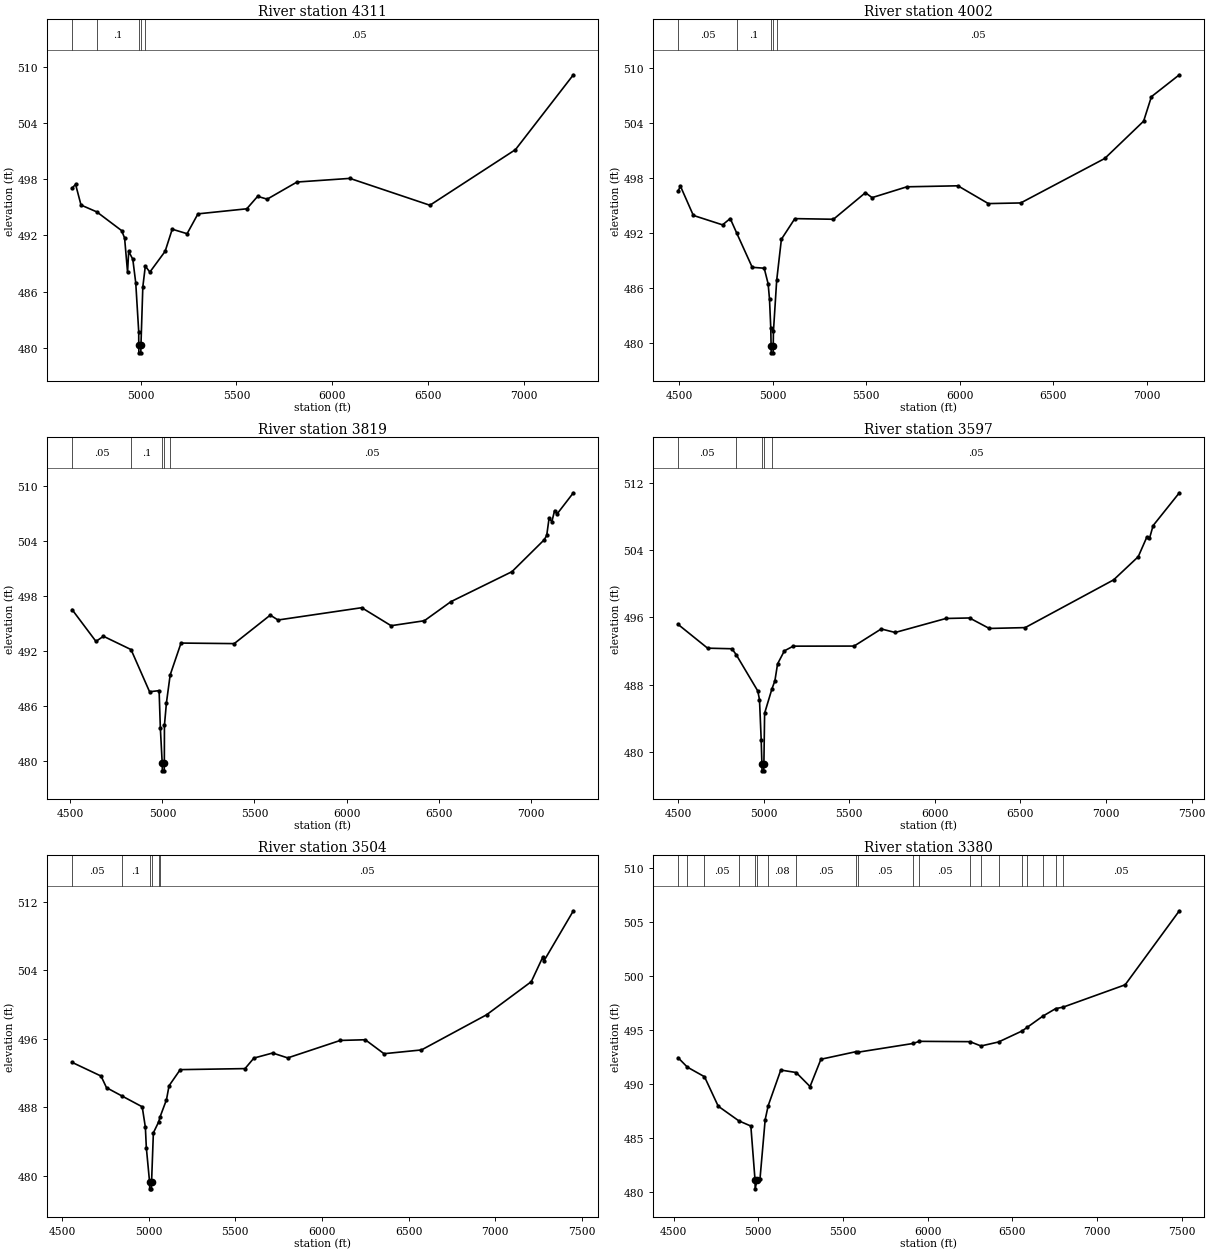
Type RM Length L Ch R = 1,4311,309,309,309
BEGIN DESCRIPTION:
Mapping XS cf310f7c
END DESCRIPTION:
XS GIS Cut Line= 4
      2042645.83     13521279.59      2042484.06     13521436.86
      2042327.81     13521695.54      2040909.16     13523226.60
#Sta/Elev= 30
  4642.6  497.05  4661.1  497.45  4689.4  495.24  4771.7  494.51  4901.2  492.51
  4916.7  491.72  4932.2  488.06  4938.0  490.29  4959.5  489.45  4974.9  486.92
  4990.4  481.69  4990.5  480.25  4991.2  479.45  5001.4  479.45  5002.0  480.25
  5011.8  486.50  5024.8  488.71  5048.6  488.08  5128.2  490.30  5165.1  492.66
  5242.7  492.18  5299.4  494.30  5554.0  494.84  5610.7  496.17  5660.5  495.87
  5815.9  497.70  6092.0  498.09  6509.3  495.22  6955.5  501.16  7257.7  509.16
#Mann=5,-1,0
  4642.6    0.05       0  4771.7     0.1       0  4990.5    0.07       0
  5002.0     0.1       0  5024.8    0.05       0
Bank Sta=4990.5,5002
Exp/Cntr=0.3,0.1

Type RM Length L Ch R = 1,4002,183,183,183
BEGIN DESCRIPTION:
Mapping XS f2ea270e
END DESCRIPTION:
XS GIS Cut Line= 4
      2042607.65     13521251.80      2042275.48     13521325.01
      2042101.87     13521484.73      2040847.58     13523175.41
#Sta/Elev= 30
  4494.1  496.61  4507.1  497.16  4576.1  493.97  4732.3  492.94  4773.3  493.63
  4809.0  492.00  4891.0  488.31  4955.1  488.21  4976.1  486.51  4983.4  484.83
  4990.2  481.70  4991.9  479.78  4992.5  478.98  5002.7  478.98  5003.4  479.78
  5004.4  481.31  5021.8  486.88  5047.0  491.37  5118.9  493.62  5325.4  493.55
  5496.5  496.45  5531.9  495.91  5718.0  497.09  5991.0  497.20  6153.8  495.26
  6327.0  495.33  6776.3  500.18  6984.2  504.25  7025.9  506.92  7175.3  509.31
#Mann=5,-1,0
  4494.1    0.05       0  4809.0     0.1       0  4991.9    0.07       0
  5003.4     0.1       0  5021.8    0.05       0
Bank Sta=4991.9,5003.4
Exp/Cntr=0.3,0.1

Type RM Length L Ch R = 1,3819,222,222,222
BEGIN DESCRIPTION:
Mapping XS ebf138ae
END DESCRIPTION:
XS GIS Cut Line= 4
      2042572.87     13521175.42      2042152.57     13521250.70
      2042012.98     13521317.37      2040834.55     13523105.97
#Sta/Elev= 30
  4508.8  496.53  4638.7  493.06  4679.3  493.62  4829.3  492.17  4930.0  487.58
  4981.8  487.70  4988.5  483.65  4998.7  479.77  4999.4  478.97  5009.6  478.97
  5010.2  479.77  5010.7  483.92  5021.6  486.38  5041.9  489.41  5100.8  492.88
  5389.9  492.82  5585.6  495.92  5627.8  495.39  6082.5  496.73  6242.1  494.77
  6422.8  495.31  6567.4  497.39  6898.6  500.65  7073.3  504.11  7087.5  504.59
  7100.4  506.48  7115.5  506.10  7130.5  507.31  7145.6  506.98  7232.4  509.24
#Mann=5,-1,0
  4508.8    0.05       0  4829.3     0.1       0  4998.7    0.07       0
  5010.2     0.1       0  5041.9    0.05       0
Bank Sta=4998.7,5010.2
Exp/Cntr=0.3,0.1

Type RM Length L Ch R = 1,3597,93,93,93
BEGIN DESCRIPTION:
Mapping XS 7a3a310b
END DESCRIPTION:
XS GIS Cut Line= 4
      2042545.14     13521012.22      2042181.73     13521077.09
      2041968.54     13521073.62      2040717.40     13523058.18
#Sta/Elev= 30
  4499.9  495.17  4672.7  492.33  4814.9  492.26  4839.6  491.56  4965.8  487.23
  4975.8  486.21  4985.8  481.40  4990.0  478.51  4990.7  477.71  5000.9  477.71
  5001.5  478.51  5005.8  484.58  5048.4  487.47  5065.8  488.44  5081.5  490.46
  5121.2  492.01  5172.9  492.57  5528.4  492.58  5686.8  494.62  5768.5  494.20
  6065.1  495.87  6202.8  495.93  6318.2  494.68  6527.7  494.78  7044.4  500.47
  7188.1  503.23  7238.6  505.58  7253.9  505.41  7275.1  506.94  7428.3  510.85
#Mann=5,-1,0
  4499.9    0.05       0  4839.6     0.1       0  4990.0    0.07       0
  5001.5     0.1       0  5048.4    0.05       0
Bank Sta=4990,5001.5
Exp/Cntr=0.3,0.1

Type RM Length L Ch R = 1,3504,124,124,124
BEGIN DESCRIPTION:
Mapping XS 4bf54393
END DESCRIPTION:
XS GIS Cut Line= 4
      2042467.21     13520872.70      2042086.55     13520968.15
      2041956.34     13521018.50      2040643.64     13522980.02
#Sta/Elev= 30
  4558.5  493.22  4725.7  491.62  4757.4  490.26  4844.1  489.32  4963.3  488.03
  4981.6  485.63  4987.0  483.27  5005.8  479.25  5006.5  478.45  5016.7  478.45
  5017.3  479.25  5027.7  484.99  5057.8  486.25  5067.0  486.89  5103.2  488.85
  5118.2  490.49  5182.6  492.37  5556.5  492.49  5607.6  493.72  5715.7  494.31
  5802.7  493.74  6106.0  495.78  6250.1  495.86  6358.2  494.23  6574.4  494.67
  6949.6  498.77  7207.9  502.64  7273.9  505.49  7279.9  505.03  7450.8  510.92
#Mann=6,-1,0
  4558.5    0.05       0  4844.1     0.1       0  5005.8    0.07       0
  5017.3     0.1       0  5057.8    0.08       0  5067.0    0.05       0
Bank Sta=5005.8,5017.3
Exp/Cntr=0.3,0.1

Type RM Length L Ch R = 1,3380,382,382,382
BEGIN DESCRIPTION:
Mapping XS a9c3dd7d
END DESCRIPTION:
XS GIS Cut Line= 5
      2042441.16     13520770.27      2042103.04     13520842.28
      2041972.83     13520890.02      2041841.76     13520949.05
      2040423.05     13522801.07
#Sta/Elev= 30
  4526.1  492.41  4581.3  491.53  4682.5  490.64  4763.6  487.91  4885.5  486.55
  4956.3  486.07  4981.1  481.05  4981.7  480.25  4992.6  481.05  5010.4  481.18
  5041.0  486.67  5058.8  487.96  5133.2  491.26  5224.0  491.03  5305.9  489.73
  5370.2  492.26  5576.6  492.96  5587.9  492.91  5913.6  493.72  5951.7  493.92
  6250.7  493.89  6315.6  493.49  6419.2  493.86  6558.2  494.88  6587.8  495.21
  6679.5  496.24  6756.3  496.95  6800.8  497.09  7167.1  499.16  7487.2  506.02
#Mann=20,-1,0
  4526.1    0.05       0  4581.3    0.08       0  4682.5    0.05       0
  4885.5    0.08       0  4981.1    0.04       0  4992.6    0.08       0
  5058.8    0.08       0  5224.0    0.05       0  5576.6    0.08       0
  5587.9    0.05       0  5913.6    0.08       0  5951.7    0.05       0
  6250.7    0.08       0  6315.6    0.05       0  6419.2    0.08       0
  6558.2    0.05       0  6587.8    0.08       0  6679.5    0.05       0
  6756.3    0.08       0  6800.8    0.05       0
Bank Sta=4981.1,4992.6
Exp/Cntr=0.3,0.1