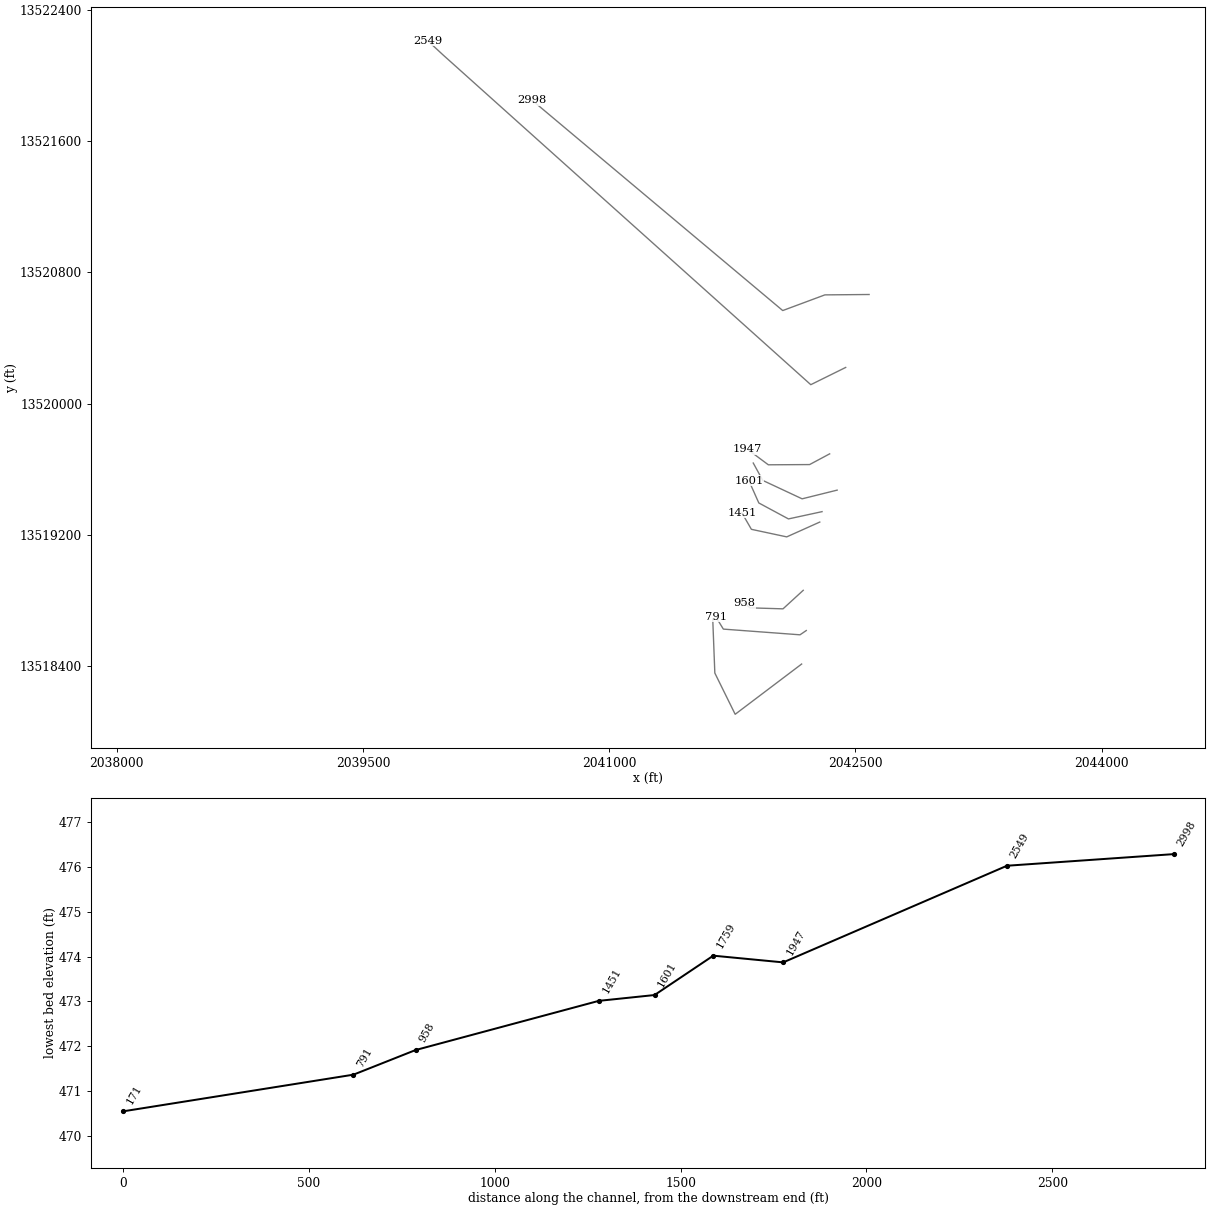
HEC-RAS study ELM Cr.prj: ELM Cr Base Level Engineering

--- ELM Cr.g01 (geometry) --- (continued)

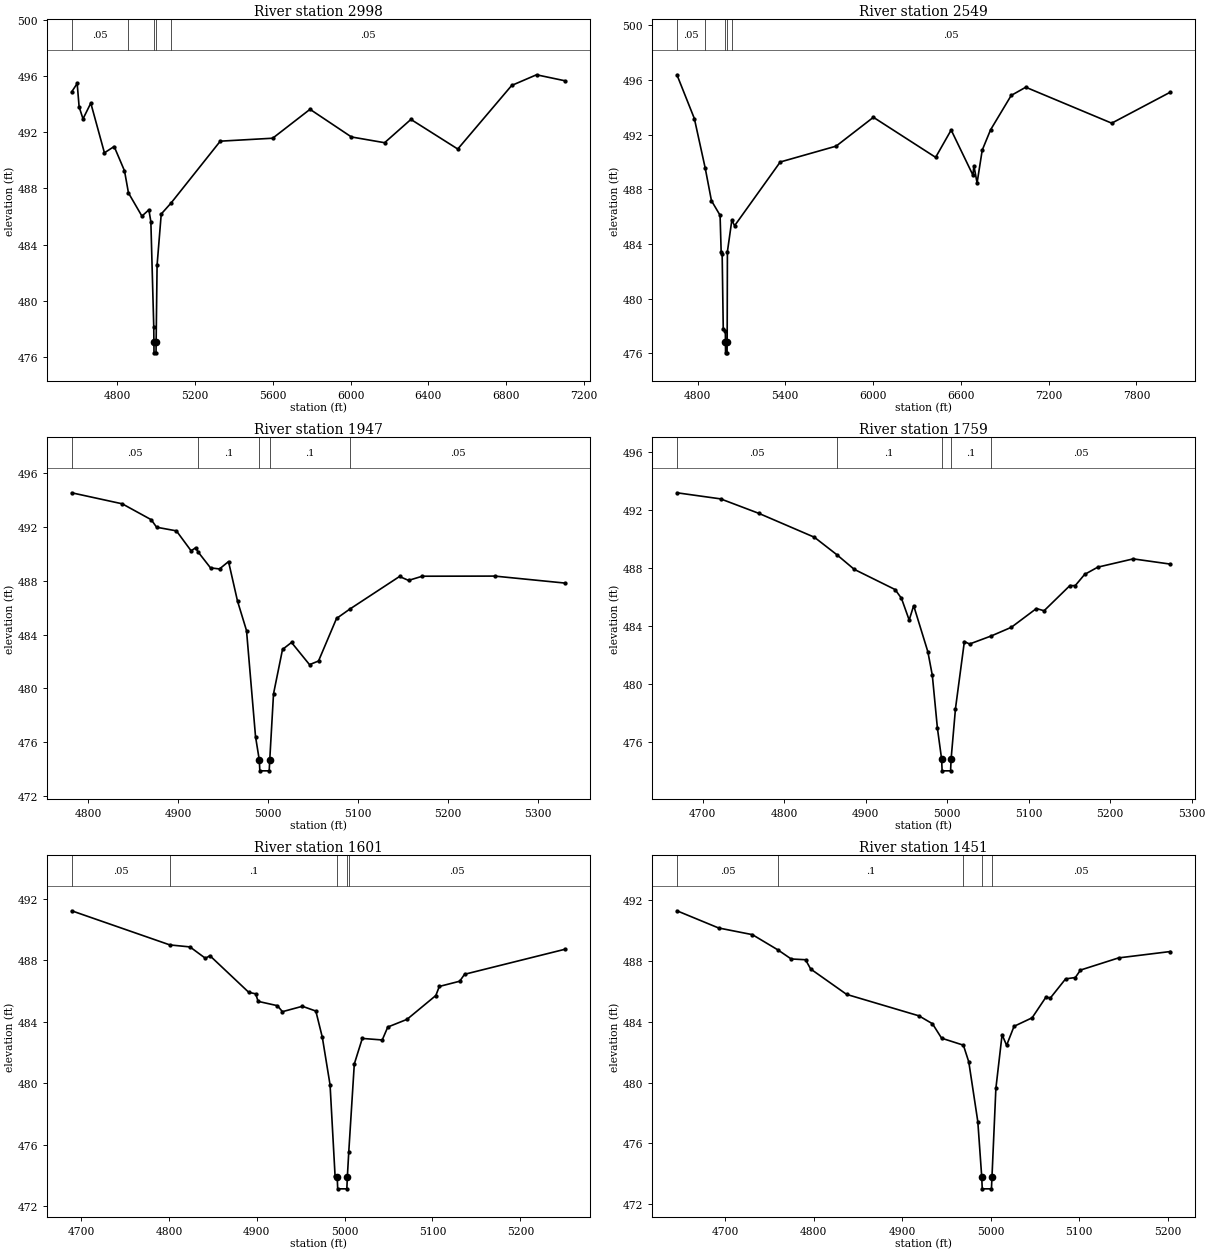
Type RM Length L Ch R = 1,2998,449,449,449
BEGIN DESCRIPTION:
Mapping XS 9c51cf4f
END DESCRIPTION:
XS GIS Cut Line= 4
      2042583.36     13520664.99      2042313.92     13520662.69
      2042056.98     13520567.21      2040530.76     13521847.25
#Sta/Elev= 30
  4567.2  494.88  4595.6  495.48  4605.6  493.81  4625.6  492.96  4665.6  494.08
  4735.6  490.54  4785.6  490.99  4838.7  489.26  4859.2  487.68  4928.3  486.03
  4964.0  486.48  4974.2  485.63  4989.1  478.13  4989.8  477.09  4990.4  476.29
  5000.7  476.29  5001.3  477.09  5006.2  482.54  5027.5  486.18  5078.4  486.97
  5330.8  491.37  5600.1  491.58  5792.0  493.64  6004.7  491.67  6175.2  491.26
  6310.4  492.92  6551.1  490.81  6828.2  495.34  6955.7  496.10  7102.7  495.67
#Mann=5,-1,0
  4567.2    0.05       0  4859.2     0.1       0  4989.8    0.07       0
  5001.3     0.1       0  5078.4    0.05       0
Bank Sta=4989.8,5001.3
Exp/Cntr=0.3,0.1

Type RM Length L Ch R = 1,2549,602,602,602
BEGIN DESCRIPTION:
Mapping XS d541df88
END DESCRIPTION:
XS GIS Cut Line= 4
      2042440.62     13520220.83      2042227.98     13520115.82
      2039985.80     13522125.37      2039894.00     13522210.24
#Sta/Elev= 30
  4659.2  496.37  4778.3  493.17  4852.5  489.55  4895.2  487.16  4954.2  486.09
  4961.7  483.39  4968.4  483.29  4975.9  477.80  4990.1  477.65  4991.0  476.83
  4991.6  476.03  5002.0  476.03  5002.6  476.83  5004.3  483.43  5034.6  485.73
  5053.6  485.33  5365.4  489.99  5747.4  491.15  6002.3  493.26  6427.7  490.33
  6533.8  492.33  6682.6  489.03  6689.3  489.71  6711.0  488.46  6746.2  490.86
  6803.0  492.34  6944.3  494.86  7043.7  495.46  7631.3  492.83  8032.3  495.10
#Mann=5,-1,0
  4659.2    0.05       0  4852.5     0.1       0  4991.0    0.07       0
  5002.6     0.1       0  5034.6    0.05       0
Bank Sta=4991,5002.6
Exp/Cntr=0.3,0.1

Type RM Length L Ch R = 1,1947,188,188,188
BEGIN DESCRIPTION:
Mapping XS fb3c904c
END DESCRIPTION:
XS GIS Cut Line= 4
      2042342.95     13519694.66      2042220.69     13519629.36
      2041969.30     13519627.97      2041842.25     13519722.40
#Sta/Elev= 30
  4781.5  494.53  4837.7  493.71  4869.9  492.53  4875.9  491.97  4897.9  491.70
  4914.2  490.22  4919.4  490.45  4921.8  490.15  4935.8  488.95  4945.8  488.87
  4955.8  489.42  4965.8  486.48  4975.8  484.29  4985.8  476.42  4990.0  474.67
  4990.6  473.87  5001.0  473.87  5001.6  474.67  5005.8  479.59  5015.8  482.89
  5025.8  483.41  5045.8  481.76  5055.8  482.03  5075.8  485.19  5090.4  485.88
  5145.8  488.31  5155.8  488.02  5171.1  488.33  5251.6  488.34  5329.8  487.82
#Mann=5,-1,0
  4781.5    0.05       0  4921.8     0.1       0  4990.0    0.07       0
  5001.6     0.1       0  5090.4    0.05       0
Bank Sta=4990,5001.6
Exp/Cntr=0.3,0.1

Type RM Length L Ch R = 1,1759,158,158,158
BEGIN DESCRIPTION:
Mapping XS 01633ece
END DESCRIPTION:
XS GIS Cut Line= 4
      2042388.68     13519473.75      2042175.15     13519420.80
      2041935.57     13519532.78      2041877.40     13519638.69
#Sta/Elev= 30
  4668.6  493.16  4722.2  492.74  4768.8  491.75  4837.2  490.10  4864.7  488.90
  4886.1  487.89  4936.2  486.50  4944.0  485.90  4953.5  484.40  4959.0  485.39
  4976.4  482.22  4981.9  480.59  4988.1  476.97  4993.3  474.82  4993.9  474.02
  5004.3  474.02  5004.9  474.82  5010.3  478.31  5021.2  482.92  5027.6  482.75
  5054.4  483.31  5078.8  483.90  5109.5  485.19  5119.0  485.04  5150.6  486.77
  5157.2  486.77  5168.7  487.54  5184.8  488.04  5228.3  488.61  5273.9  488.25
#Mann=5,-1,0
  4668.6    0.05       0  4864.7     0.1       0  4993.3    0.07       0
  5004.9     0.1       0  5054.4    0.05       0
Bank Sta=4993.3,5004.9
Exp/Cntr=0.3,0.1

Type RM Length L Ch R = 1,1601,150,150,150
BEGIN DESCRIPTION:
Mapping XS 3042e684
END DESCRIPTION:
XS GIS Cut Line= 4
      2042296.64     13519342.66      2042091.82     13519298.40
      2041911.26     13519395.62      2041851.40     13519530.09
#Sta/Elev= 30
  4689.2  491.22  4801.0  489.00  4823.9  488.87  4841.5  488.13  4846.6  488.30
  4890.8  485.92  4898.7  485.82  4901.5  485.33  4923.4  485.05  4929.2  484.66
  4951.9  485.01  4967.2  484.70  4974.6  482.99  4983.4  479.90  4989.1  473.97
  4991.5  473.94  4992.1  473.14  5002.5  473.14  5003.1  473.94  5004.7  475.55
  5011.0  481.26  5020.1  482.92  5042.8  482.82  5049.1  483.66  5071.0  484.16
  5103.8  485.71  5107.8  486.30  5131.0  486.64  5136.5  487.09  5251.0  488.72
#Mann=5,-1,0
  4689.2    0.05       0  4801.0     0.1       0  4991.5    0.07       0
  5003.1     0.1       0  5004.7    0.05       0
Bank Sta=4991.5,5003.1
Exp/Cntr=0.3,0.1

Type RM Length L Ch R = 1,1451,493,493,493
BEGIN DESCRIPTION:
Mapping XS 34bcf862
END DESCRIPTION:
XS GIS Cut Line= 4
      2042282.74     13519279.28      2042081.40     13519189.03
      2041866.12     13519235.03      2041807.95     13519335.75
#Sta/Elev= 30
  4645.8  491.30  4692.8  490.17  4731.0  489.73  4760.0  488.72  4774.8  488.13
  4791.0  488.08  4796.8  487.47  4837.4  485.80  4919.0  484.39  4934.3  483.87
  4944.6  482.92  4969.2  482.46  4975.3  481.36  4985.5  477.43  4989.9  473.81
  4990.5  473.01  5000.9  473.01  5001.5  473.81  5005.9  479.62  5012.9  483.15
  5018.0  482.45  5026.4  483.70  5046.8  484.26  5062.3  485.61  5067.5  485.57
  5084.6  486.82  5095.6  486.91  5101.4  487.40  5144.4  488.20  5202.9  488.62
#Mann=5,-1,0
  4645.8    0.05       0  4760.0     0.1       0  4969.2    0.05       0
  4989.9    0.03       0  5001.5    0.05       0
Bank Sta=4989.9,5001.5
Exp/Cntr=0.3,0.1

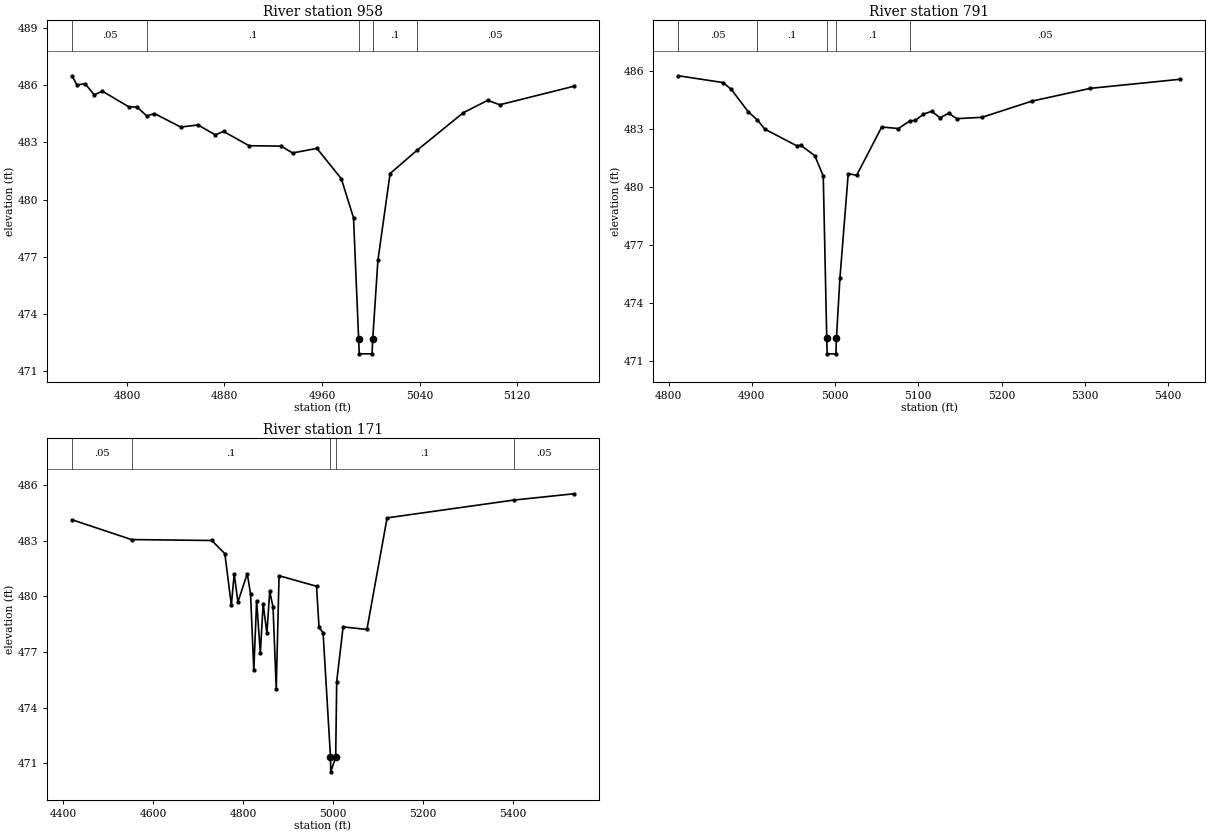
Type RM Length L Ch R = 1,958,167,167,167
BEGIN DESCRIPTION:
Mapping XS ee26024b
END DESCRIPTION:
XS GIS Cut Line= 4
      2042182.00     13518863.67      2042058.70     13518750.79
      2041858.18     13518756.86      2041824.30     13518784.66
#Sta/Elev= 30
  4754.9  486.50  4759.0  486.02  4765.7  486.08  4773.2  485.50  4779.9  485.69
  4801.5  484.87  4808.3  484.86  4816.3  484.39  4822.5  484.52  4844.1  483.81
  4858.3  483.92  4872.4  483.40  4879.2  483.58  4900.2  482.83  4926.4  482.81
  4935.8  482.45  4955.8  482.69  4975.8  481.10  4985.8  479.05  4990.0  472.71
  4990.5  471.91  5001.0  471.91  5001.6  472.71  5005.8  476.81  5015.8  481.37
  5037.7  482.58  5075.8  484.56  5095.8  485.21  5105.8  484.98  5166.5  485.95
#Mann=5,-1,0
  4754.9    0.05       0  4816.3     0.1       0  4990.0    0.07       0
  5001.6     0.1       0  5037.7    0.05       0
Bank Sta=4990,5001.6
Exp/Cntr=0.3,0.1

Type RM Length L Ch R = 1,791,620,620,620
BEGIN DESCRIPTION:
Mapping XS d8283722
END DESCRIPTION:
XS GIS Cut Line= 4
      2042200.47     13518618.72      2042162.27     13518592.67
      2041695.25     13518627.39      2041649.20     13518702.44
#Sta/Elev= 30
  4811.9  485.75  4865.4  485.40  4875.5  485.04  4895.5  483.90  4906.8  483.46
  4915.6  482.99  4953.8  482.13  4958.9  482.15  4975.7  481.61  4985.8  480.56
  4990.0  472.16  4990.5  471.36  5001.0  471.36  5001.6  472.16  5005.8  475.27
  5015.8  480.69  5025.9  480.60  5056.0  483.10  5076.0  483.02  5090.0  483.42
  5096.5  483.44  5106.1  483.77  5116.1  483.91  5126.1  483.57  5136.2  483.81
  5146.2  483.53  5176.3  483.60  5236.4  484.44  5306.6  485.10  5414.5  485.57
#Mann=5,-1,0
  4811.9    0.05       0  4906.8     0.1       0  4990.0    0.07       0
  5001.6     0.1       0  5090.0    0.05       0
Bank Sta=4990,5001.6
Exp/Cntr=0.3,0.1

Type RM Length L Ch R = 1,171,0,0,0
BEGIN DESCRIPTION:
ELM Cr 1.0
END DESCRIPTION:
XS GIS Cut Line= 4
      2042172.21     13518414.71      2041767.29     13518108.74
      2041643.34     13518359.82      2041630.57     13518689.44
#Sta/Elev= 30
  4419.1  484.14  4551.7  483.07  4730.3  483.02  4759.5  482.31  4774.0  479.53
  4780.3  481.22  4788.6  479.70  4809.4  481.23  4816.7  480.14  4824.0  476.01
  4830.2  479.76  4838.5  476.95  4844.8  479.61  4853.1  478.01  4859.4  480.28
  4866.8  479.42  4873.9  475.02  4880.2  481.12  4963.6  480.55  4969.2  478.33
  4978.2  478.04  4994.7  471.34  4995.3  470.54  5006.3  471.34  5008.5  475.41
  5022.8  478.36  5075.8  478.22  5120.7  484.24  5402.6  485.20  5536.5  485.54
#Mann=5,-1,0
  4419.1    0.05       0  4551.7     0.1       0  4994.7    0.07       0
  5006.3     0.1       0  5402.6    0.05       0
Bank Sta=4994.7,5006.3
Exp/Cntr=0.3,0.1

Chan Stop Cuts=-1