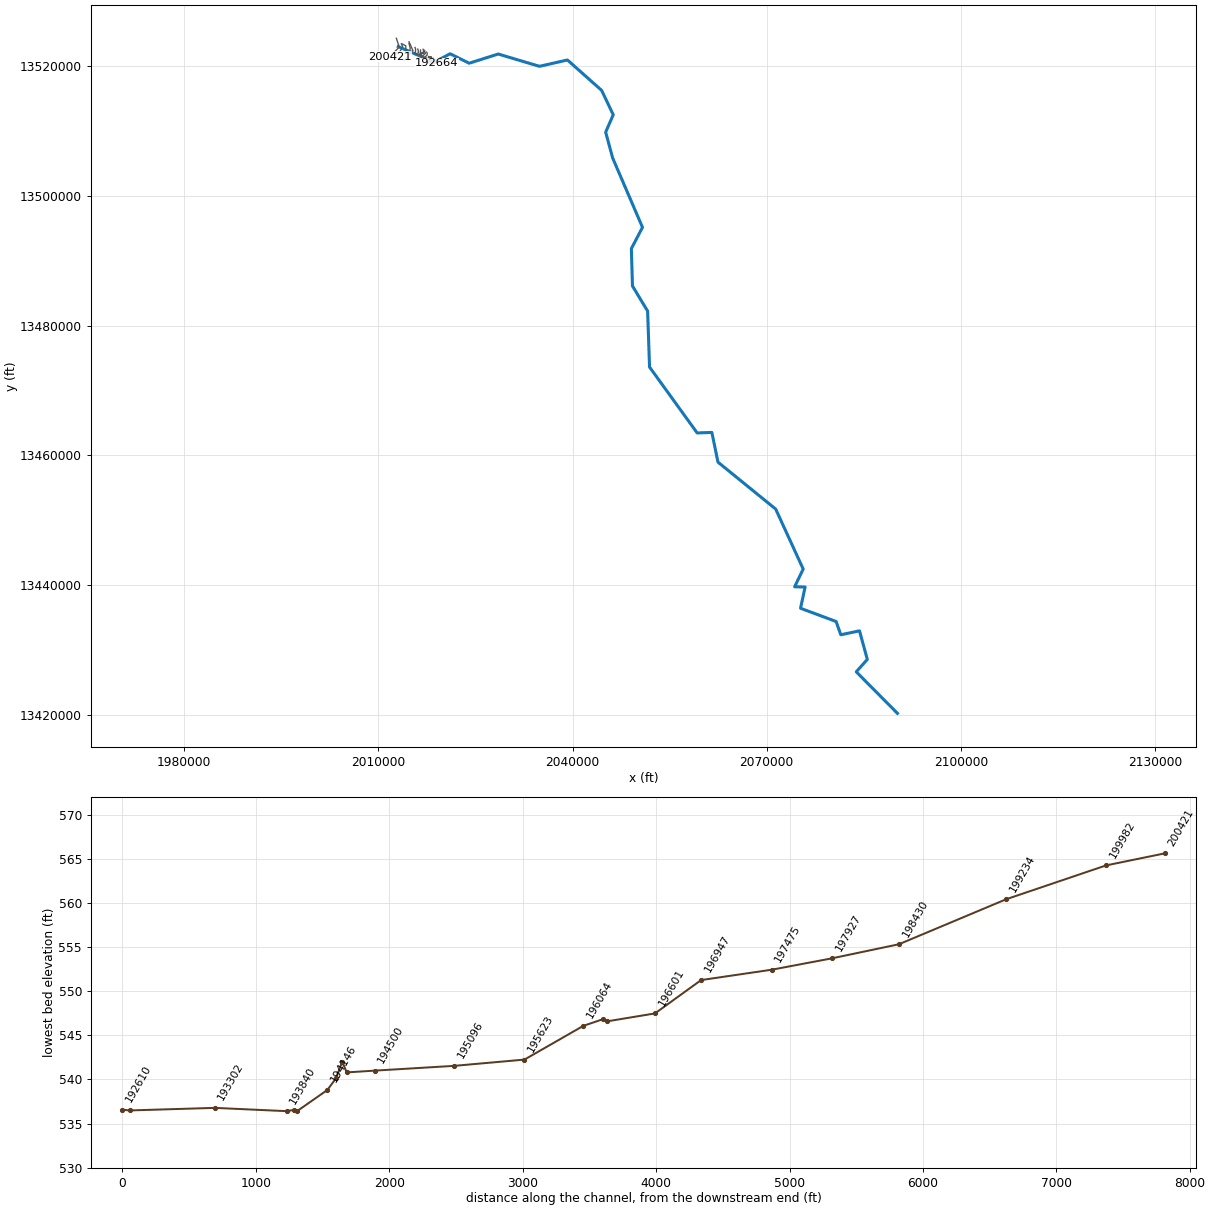
--- LAGUNILLAS Cr.prj (project) ---

Proj Title=LAGUNILLAS Cr Base Level Engineering
Current Plan=p01
Default Exp/Contr=0.3,0.1
English Units
Geom File=g01
Flow File=f01
Plan File=p01
Y Axis Title=Elevation
X Axis Title(PF)=Main Channel Distance
X Axis Title(XS)=Station
BEGIN DESCRIPTION:
LAGUNILLAS Cr
END DESCRIPTION:
DSS Export Rating Curves= 0
DSS Export Rating Curve Sorted= 0
DSS Export Volume Flow Curves= 0
DXF OffsetX= 0
DXF OffsetY= 0
DXF ScaleX= 1
DXF ScaleY= 10

--- LAGUNILLAS Cr.p01 (plan) ---

Plan Title=Multiple Run
Short Identifier=Multiple
Geom File=g01
Flow File=f01
Subcritical Flow
K Sum by GR= 0
Std Step Tol= 0.01
Critical Tol= 0.01
Num of Std Step Trials= 20
Max Error Tol= 0.3
Flow Tol Ratio= 0.001
Split Flow NTrial= 30
Split Flow Tol= 0.02
Split Flow Ratio= 0.02
Log Output Level= 0
Friction Slope Method= 1
Unsteady Friction Slope Method= 2
Unsteady Bridges Friction Slope Method= 1
Parabolic Critical Depth
Global Vel Dist=  1 , 1 , 1
Global Log Level= 0
CheckData=True
Encroach Param= -1, 0, 0, 0
BEGIN DESCRIPTION:
Multiple Run
END DESCRIPTION:

--- LAGUNILLAS Cr.f01 (steady flow) ---

Flow Title=Multiple
Program Version=5.05
Number of Profiles= 7
Profile Names=10-year,25-year,50-year,1pct_min,100-year,1pct_plu,500-year
River Rch & RM=LAGUNILLAS Cr,Reach-1         ,200421
     121     159     189     112     224     447     319
River Rch & RM=LAGUNILLAS Cr,Reach-1         ,196240
     160     215     258     155     308     615     448
River Rch & RM=LAGUNILLAS Cr,Reach-1         ,194500
     245     335     409     249     496     990     741
River Rch & RM=LAGUNILLAS Cr,Reach-1         ,189696
     419     589     731     451     901    1797    1389
River Rch & RM=LAGUNILLAS Cr,Reach-1         ,185119
     463     653     813     503    1003    2002    1553
River Rch & RM=LAGUNILLAS Cr,Reach-1         ,181897
     584     832    1042     648    1293    2581    2026
River Rch & RM=LAGUNILLAS Cr,Reach-1         ,181007
     699     999    1254     781    1559    3110    2448
River Rch & RM=LAGUNILLAS Cr,Reach-1         ,172478
     817    1174    1478     924    1843    3678    2911
River Rch & RM=LAGUNILLAS Cr,Reach-1         ,164238
    1141    1651    2092    1314    2621    5229    4179
River Rch & RM=LAGUNILLAS Cr,Reach-1         ,158579
    1164    1686    2136    1341    2676    5340    4269
River Rch & RM=LAGUNILLAS Cr,Reach-1         ,156895
    1451    2115    2691    1697    3386    6756    5441
River Rch & RM=LAGUNILLAS Cr,Reach-1         ,155578
    1605    2348    2995    1894    3779    7539    6104
River Rch & RM=LAGUNILLAS Cr,Reach-1         ,154520
    1588    2317    2952    1862    3716    7415    5980
River Rch & RM=LAGUNILLAS Cr,Reach-1         ,148041
    1827    2681    3428    2171    4332    8643    7022
River Rch & RM=LAGUNILLAS Cr,Reach-1         ,147001
    1803    2635    3360    2122    4234    8447    6822
River Rch & RM=LAGUNILLAS Cr,Reach-1         ,142116
    1854    2711    3458    2185    4359    8698    7030
River Rch & RM=LAGUNILLAS Cr,Reach-1         ,138744
    1949    2851    3639    2300    4589    9156    7405
River Rch & RM=LAGUNILLAS Cr,Reach-1         ,134493
    1951    2849    3632    2292    4574    9126    7362
River Rch & RM=LAGUNILLAS Cr,Reach-1         ,133431
    2032    2975    3797    2400    4788    9554    7728
River Rch & RM=LAGUNILLAS Cr,Reach-1         ,127766
    2142    3137    4006    2533    5053   10083    8160
River Rch & RM=LAGUNILLAS Cr,Reach-1         ,121325
    2126    3108    3965    2503    4995    9966    8045
River Rch & RM=LAGUNILLAS Cr,Reach-1         ,119676
    2170    3172    4045    2553    5094   10164    8200
River Rch & RM=LAGUNILLAS Cr,Reach-1         ,116112
    2231    3260    4156    2623    5233   10441    8419
River Rch & RM=LAGUNILLAS Cr,Reach-1         ,115363
    2231    3260    4156    2623    5233   10441    8419
River Rch & RM=LAGUNILLAS Cr,Reach-1         ,108813
    2285    3343    4265    2694    5375   10725    8661
River Rch & RM=LAGUNILLAS Cr,Reach-1         ,107257
    2811    4128    5283    3345    6674   13317   10806
River Rch & RM=LAGUNILLAS Cr,Reach-1         ,105312
    2811    4128    5283    3345    6674   13317   10806
River Rch & RM=LAGUNILLAS Cr,Reach-1         ,102260
    2843    4175    5344    3384    6752   13471   10934
River Rch & RM=LAGUNILLAS Cr,Reach-1         ,100145
    3766    5547    7116    4515    9008   17974   14638
River Rch & RM=LAGUNILLAS Cr,Reach-1         ,34997
    3766    5547    7116    4515    9008   17974   14638
River Rch & RM=LAGUNILLAS Cr,Reach-1         ,34145
    3789    5582    7162    4544    9067   18092   14737
River Rch & RM=LAGUNILLAS Cr,Reach-1         ,26322
    3792    5583    7160    4542    9062   18080   14715
River Rch & RM=LAGUNILLAS Cr,Reach-1         ,21028
    4116    6067    7785    4941    9859   19672   16028
River Rch & RM=LAGUNILLAS Cr,Reach-1         ,17444
    4165    6146    7893    5014   10004   19961   16291
River Rch & RM=LAGUNILLAS Cr,Reach-1         ,14990
    4118    6068    7787    4942    9860   19673   16026
River Rch & RM=LAGUNILLAS Cr,Reach-1         ,13683
    4167    6147    7893    5013   10003   19958   16282
River Rch & RM=LAGUNILLAS Cr,Reach-1         ,12529
    4202    6201    7966    5060   10097   20146   16445
River Rch & RM=LAGUNILLAS Cr,Reach-1         ,11462
    4147    6110    7839    4975    9926   19804   16129
River Rch & RM=LAGUNILLAS Cr,Reach-1         ,7545
    4159    6127    7862    4989    9955   19862   16177
River Rch & RM=LAGUNILLAS Cr,Reach-1         ,3083
    4161    6130    7866    4992    9960   19873   16186
Boundary for River Rch & Prof#=LAGUNILLAS Cr,Reach-1         , 1
Up Type= 0
Dn Type= 3
Dn Slope=0.00124
Boundary for River Rch & Prof#=LAGUNILLAS Cr,Reach-1         , 2
Up Type= 0
Dn Type= 3
Dn Slope=0.00124
Boundary for River Rch & Prof#=LAGUNILLAS Cr,Reach-1         , 3
Up Type= 0
Dn Type= 3
Dn Slope=0.00124
Boundary for River Rch & Prof#=LAGUNILLAS Cr,Reach-1         , 4
Up Type= 0
Dn Type= 3
Dn Slope=0.00124
Boundary for River Rch & Prof#=LAGUNILLAS Cr,Reach-1         , 5
Up Type= 0
Dn Type= 3
Dn Slope=0.00124
Boundary for River Rch & Prof#=LAGUNILLAS Cr,Reach-1         , 6
Up Type= 0
Dn Type= 3
Dn Slope=0.00124
Boundary for River Rch & Prof#=LAGUNILLAS Cr,Reach-1         , 7
Up Type= 0
Dn Type= 3
Dn Slope=0.00124
DSS Import GetInterval= 0
DSS Import GetPeak= 0
DSS Import FillOption= 0

--- LAGUNILLAS Cr.g01 (geometry) ---

Geom Title=Existing Conditions
Program Version=5.07

River Reach=LAGUNILLAS Cr   ,Reach-1
Reach XY= 30
       2013065.8     13523029.54      2018617.68     13520621.01
       2021070.8     13521924.54       2024020.8     13520464.54
       2028510.8     13521884.54       2034880.8     13519984.54
      2039196.04      13520969.3       2044490.8     13516274.54
       2046280.8     13512514.54       2045110.8     13509834.54
      2046191.14     13505845.02       2050800.8     13495154.54
       2049080.8     13491874.54       2049250.8     13486104.54
       2051590.8     13482244.54       2051890.8     13473604.54
       2059250.8     13463444.54       2061520.8     13463524.54
       2062460.8     13458944.54       2071380.8     13451704.54
       2075630.8     13442454.54       2074310.8     13439714.54
      2075928.09     13439684.85       2075220.8     13436404.54
      2080718.02     13434363.84       2081440.8     13432314.54
       2084330.8     13432924.54       2085540.8     13428514.54
       2083830.8     13426604.54       2090200.8     13420194.54

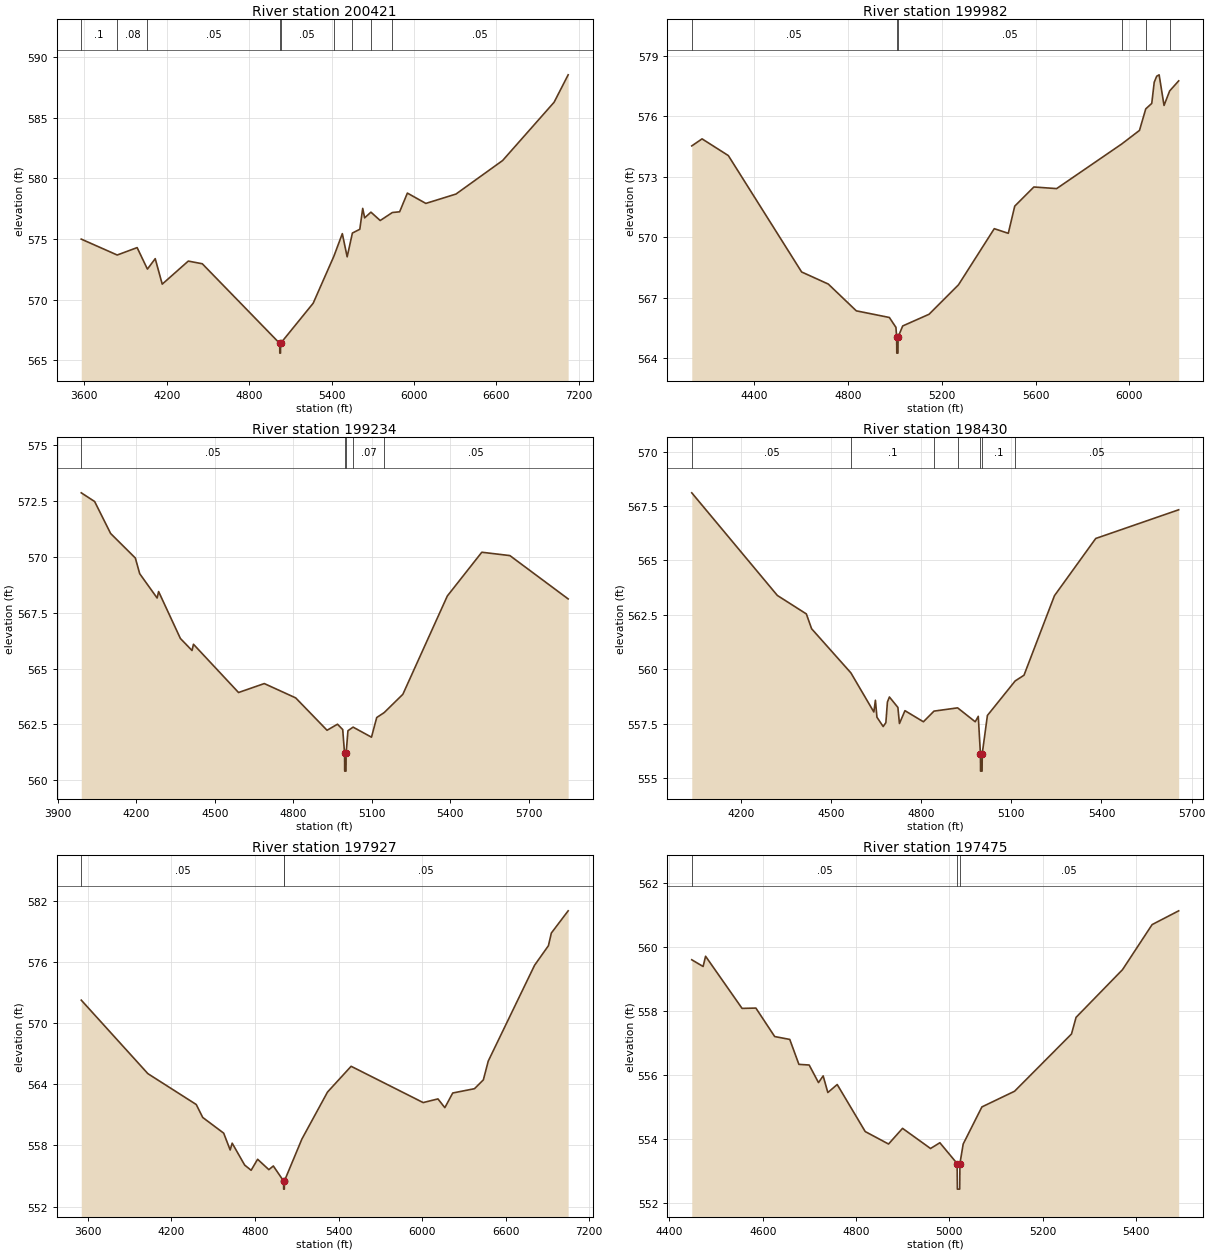
Type RM Length L Ch R = 1 ,200421  ,439,439,439
BEGIN DESCRIPTION:
LAGUNILLAS Cr 219.0
END DESCRIPTION:
XS GIS Cut Line= 3
      2012770.84     13524304.13      2013220.83     13522954.17
      2011720.84     13521454.17
#Sta/Elev= 30
  3577.4  574.99  3839.1  573.68  3984.1  574.29    4059  572.52  4115.8  573.38
  4166.8  571.28  4356.5  573.18  4458.4  572.96  5022.1   566.4  5022.6   565.6
  5027.6   565.6  5028.1   566.4  5265.6  569.71  5416.3  573.58  5477.7  575.44
    5513  573.53  5551.1  575.49    5605   575.8  5626.2  577.52  5640.3  576.74
    5686  577.21  5753.5  576.52    5842  577.18  5894.9  577.24  5951.4  578.78
  6085.8  577.93    6305   578.7  6644.4  581.46  7019.2  586.26  7121.7  588.52
#Mann= 9 ,-1 , 0
  3577.4      .1       0  3839.1     .08       0    4059     .05       0
  5022.1    .035       0  5028.1     .05       0  5416.3     .08       0
  5551.1     .05       0    5686      .1       0    5842     .05       0
Bank Sta=5022.1,5028.1
XS Rating Curve= 0 ,0
Exp/Cntr=0.3,0.1

Type RM Length L Ch R = 1 ,199982  ,748,748,748
BEGIN DESCRIPTION:
Mapping XS 778c47c1
END DESCRIPTION:
XS GIS Cut Line= 4
      2013533.08      13523464.4      2013741.43      13523042.5
      2013231.01       13522105.      2012715.38     13521943.54
#Sta/Elev= 30
  4132.4  574.53  4176.3  574.88  4288.5  574.05  4601.3  568.27  4715.1  567.67
  4834.7  566.34  4975.8  566.01  5003.8  565.52    5007  565.04  5007.5  564.24
  5012.5  564.24    5013  565.04  5032.8  565.59  5145.3  566.17  5270.7  567.63
  5423.6  570.42  5483.4  570.19    5511  571.54  5592.6  572.49  5689.8  572.41
  5968.1  574.63  6043.4   575.3  6070.2  576.37  6095.8  576.64  6106.3  577.69
  6116.8  577.99  6127.3  578.06  6148.2  576.54  6172.2  577.26  6210.7  577.76
#Mann= 6 ,-1 , 0
  4132.4     .05       0    5007    .035       0    5013     .05       0
  5968.1      .1       0  6070.2     .08       0  6172.2     .05       0
Bank Sta=5007,5013
XS Rating Curve= 0 ,0
Exp/Cntr=0.3,0.1

Type RM Length L Ch R = 1 ,199234  ,804,804,804
BEGIN DESCRIPTION:
Mapping XS 7f0d6280
END DESCRIPTION:
XS GIS Cut Line= 4
      2013684.14     13523433.12       2014225.8     13523157.08
      2014231.01     13522245.62      2014049.34     13521954.95
#Sta/Elev= 30
  3989.5  572.87  4040.7  572.48  4101.8  571.05  4196.4  569.95    4213  569.25
  4279.7  568.16  4285.3  568.45  4368.6  566.35  4413.1  565.81  4418.7  566.09
    4591  563.93  4689.5  564.33  4809.5  563.69  4929.5  562.24  4969.5  562.51
  4989.5  562.27  4996.5  561.21    4997  560.41    5002  560.41  5002.5  561.21
  5009.5  562.22  5029.1  562.38  5099.5  561.93  5119.5  562.81    5148  563.03
  5219.5  563.85  5389.5  568.25  5521.4  570.21  5628.8  570.06  5851.7  568.12
#Mann= 5 ,-1 , 0
  3989.5     .05       0  4996.5     .03       0  5002.5     .05       0
  5029.1     .07       0    5148     .05       0
Bank Sta=4996.5,5002.5
XS Rating Curve= 0 ,0
Exp/Cntr=0.3,0.1

Type RM Length L Ch R = 1 ,198430  ,503,503,503
BEGIN DESCRIPTION:
Mapping XS 836bb4d9
END DESCRIPTION:
XS GIS Cut Line= 4
      2014721.71       13523510.      2014912.67     13522798.23
      2014812.85     13522199.27      2014582.84     13522047.38
#Sta/Elev= 30
  4037.1  568.11  4321.8  563.39  4418.3  562.54  4435.7  561.86  4566.4  559.83
  4642.8  558.03    4648  558.57  4653.1  557.79  4673.9  557.36  4682.8  557.54
    4688  558.49  4694.6  558.72  4722.8  558.24    4728   557.5  4746.3  558.09
  4807.7  557.58  4842.9  558.07  4921.5  558.22  4980.1  557.58  4990.2  557.83
  4997.4  556.11  4997.9  555.31  5002.9  555.31  5003.4  556.11  5020.6  557.87
  5113.1  559.46  5142.3  559.72  5243.7  563.38  5380.9  566.01  5656.9  567.33
#Mann= 7 ,-1 , 0
  4037.1     .05       0  4566.4      .1       0  4842.9     .05       0
  4921.5      .1       0  4997.4     .07       0  5003.4      .1       0
  5113.1     .05       0
Bank Sta=4997.4,5003.4
XS Rating Curve= 0 ,0
Exp/Cntr=0.3,0.1

Type RM Length L Ch R = 1 ,197927  ,452,452,452
BEGIN DESCRIPTION:
LAGUNILLAS Cr 218.0
END DESCRIPTION:
XS GIS Cut Line= 3
      2014725.01     13523774.98        2015325.       13522425.
      2013974.97     13520924.96
#Sta/Elev= 30
  3552.9  572.25    4031  565.04  4378.4  562.01  4424.9  560.74  4575.4   559.2
  4621.9  557.55  4636.3  558.22  4725.9  556.07  4772.4  555.56  4818.9  556.64
  4899.6  555.62  4931.7  555.98  5005.3  554.51  5005.8  553.71  5010.8  553.71
  5011.3  554.51  5136.7  558.62  5320.6  563.23  5490.2  565.76  6007.5   562.2
  6113.6  562.56  6162.9   561.7  6219.7  563.14  6375.6  563.56  6439.5  564.43
  6474.6  566.27  6807.2  575.67  6906.6  577.59  6927.5  578.83  7048.3  581.01
#Mann= 3 ,-1 , 0
  3552.9     .05       0  5005.3    .035       0  5011.3     .05       0
Bank Sta=5005.3,5011.3
XS Rating Curve= 0 ,0
Exp/Cntr=0.3,0.1

Type RM Length L Ch R = 1 ,197475  ,528,528,528
BEGIN DESCRIPTION:
Mapping XS bf9b0d36
END DESCRIPTION:
XS GIS Cut Line= 4
        2015650.     13522900.01      2015736.44     13522683.56
      2015721.25     13522103.05      2015549.96     13521949.97
#Sta/Elev= 30
  4447.8  559.59  4472.1  559.38  4477.4   559.7  4555.6  558.07  4585.2  558.08
  4625.5  557.19  4657.8   557.1  4677.4  556.32  4699.4   556.3  4719.4  555.75
  4729.4  555.96  4739.4  555.44  4759.5  555.69  4819.5  554.22  4869.5  553.83
  4899.5  554.32  4959.5  553.69  4979.5  553.87  5016.5  553.22    5017  552.42
    5022  552.42  5022.5  553.22  5029.5  553.83  5069.6  554.99  5139.6  555.48
  5261.6  557.27  5271.4  557.79  5370.9  559.28  5434.4  560.69  5491.3  561.12
#Mann= 3 ,-1 , 0
  4447.8     .05       0  5016.5    .035       0  5022.5     .05       0
Bank Sta=5016.5,5022.5
XS Rating Curve= 0 ,0
Exp/Cntr=0.3,0.1

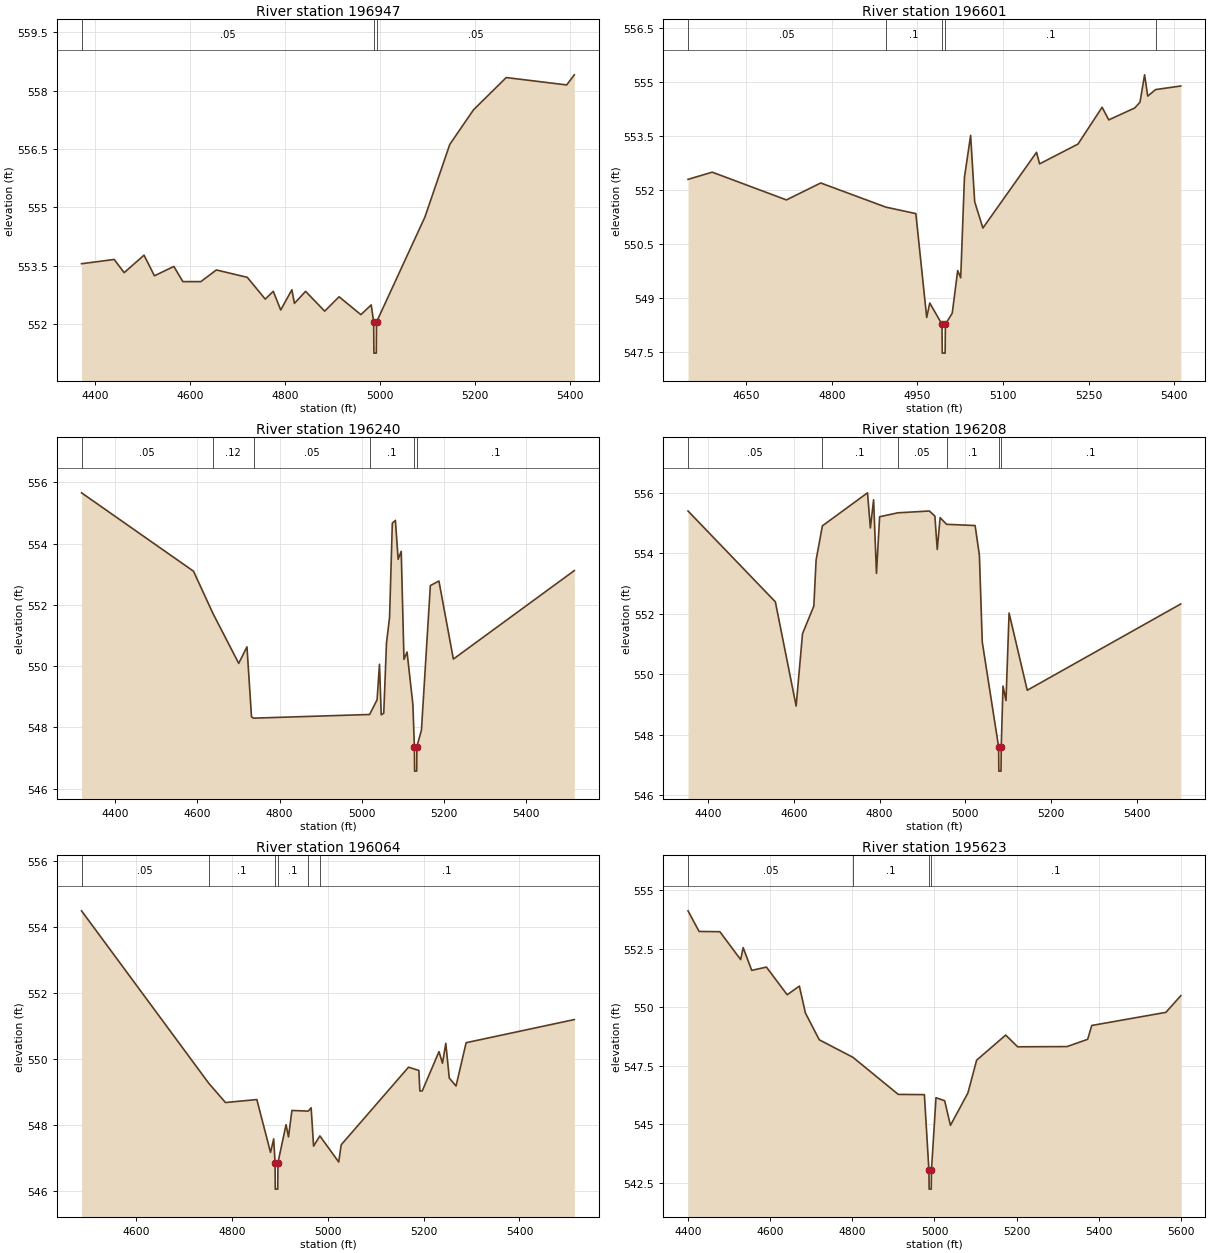
Type RM Length L Ch R = 1 ,196947  ,346,346,346
BEGIN DESCRIPTION:
Mapping XS 55333a8d
END DESCRIPTION:
XS GIS Cut Line= 4
      2016075.86      13522650.7        2016200.       13522250.
      2016054.36     13521913.16      2015815.48      13521834.7
#Sta/Elev= 30
  4371.6  553.55  4440.4  553.66  4461.3  553.32  4503.2  553.77  4525.1  553.24
    4566  553.48    4585  553.09  4622.9  553.09  4655.5  553.39  4720.7   553.2
  4758.5  552.64  4775.4  552.84  4791.1  552.36  4814.6  552.88    4820  552.53
  4843.5  552.84  4883.7  552.33    4914   552.7    4960  552.24  4981.7  552.49
  4986.9  552.05  4987.4  551.25  4992.4  551.25  4992.9  552.05  5094.8  554.75
  5147.2  556.62  5197.2  557.51  5266.1  558.34  5393.4  558.15  5409.5  558.41
#Mann= 3 ,-1 , 0
  4371.6     .05       0  4986.9    .035       0  4992.9     .05       0
Bank Sta=4986.9,4992.9
XS Rating Curve= 0 ,0
Exp/Cntr=0.3,0.1

Type RM Length L Ch R = 1 ,196601  ,361,361,361
BEGIN DESCRIPTION:
Mapping XS f7632188
END DESCRIPTION:
XS GIS Cut Line= 4
      2016496.88      13522507.4      2016509.89     13522194.93
      2016375.35     13521852.05      2016210.39     13521773.91
#Sta/Elev= 30
  4548.1  552.29  4590.5  552.49  4720.6  551.72  4780.7  552.19  4894.8  551.52
  4947.4  551.34  4966.4  548.46  4971.8  548.86  4993.2  548.27  4993.7  547.47
  4998.7  547.47  4999.2  548.27  5011.2  548.58  5020.7  549.76    5026  549.56
  5032.6  552.35  5043.4  553.51  5050.5  551.67  5064.9  550.94  5158.9  553.04
  5164.3  552.72  5231.6  553.27  5273.8  554.29  5285.5  553.94    5331  554.27
  5340.2  554.43  5348.3  555.19  5353.8   554.6  5367.5  554.78  5411.7  554.88
#Mann= 5 ,-1 , 0
  4548.1     .05       0  4894.8      .1       0  4993.2     .07       0
  4999.2      .1       0  5367.5     .05       0
Bank Sta=4993.2,4999.2
XS Rating Curve= 0 ,0
Exp/Cntr=0.3,0.1

Type RM Length L Ch R = 1 ,196240  ,32,32,32
BEGIN DESCRIPTION:
Mapping XS 41877524
END DESCRIPTION:
XS GIS Cut Line= 6
      2016905.06     13522609.77      2016962.57     13522407.95
      2016947.37     13522165.98      2016919.16     13522079.17
      2016731.45     13522111.73      2016384.03     13521799.97
#Sta/Elev= 30
  4317.5  555.66  4590.4   553.1  4637.8  551.72  4700.6  550.09  4720.7  550.63
  4731.8  548.34  4736.8   548.3  5019.6  548.42  5037.9   548.9  5043.7  550.06
    5048  548.41  5054.1  548.46  5060.8  550.76  5068.3  551.59    5075  554.67
  5082.5  554.76  5089.2  553.49  5096.7  553.75  5103.4  550.22  5110.9  550.46
  5125.1  548.75  5128.8  547.37  5129.3  546.57  5134.4  546.57  5134.9  547.37
    5146  547.91  5167.7  552.63  5188.6  552.78  5223.8  550.23  5518.6  553.12
#Mann= 6 ,-1 , 0
  4317.5     .05       0  4637.8     .12       0  4736.8     .05       0
  5019.6      .1       0  5128.8    .033       0  5134.9      .1       0
Bank Sta=5128.8,5134.9
XS Rating Curve= 0 ,0
Exp/Cntr=0.3,0.1

Type RM Length L Ch R = 1 ,196208  ,144,144,144
BEGIN DESCRIPTION:
Mapping XS e5c827a8
END DESCRIPTION:
XS GIS Cut Line= 6
      2017046.12      13522492.6      2017043.95     13522334.17
       2016982.1     13522095.45      2016921.33     13522028.18
      2016746.64     13522069.41      2016423.49     13521739.61
#Sta/Elev= 30
  4352.9  555.39  4556.8  552.39  4605.3  548.95  4620.2  551.34  4646.6  552.25
  4651.9  553.77  4666.6   554.9  4771.9  555.99  4778.6  554.83  4786.1  555.76
  4792.8  553.33  4800.2   555.2  4842.9  555.33  4916.4  555.39  4929.2  555.22
  4934.7  554.12  4941.4  555.17  4956.4  554.95  5023.1  554.91  5033.1  553.93
  5039.8  551.06    5078   547.6  5078.5   546.8  5083.6   546.8  5084.1   547.6
  5088.2  549.61  5095.2  549.13  5102.4  552.02  5144.8  549.47  5503.2  552.32
#Mann= 6 ,-1 , 0
  4352.9     .05       0  4666.6      .1       0  4842.9     .05       0
  4956.4      .1       0    5078     .07       0  5084.1      .1       0
Bank Sta=5078,5084.1
XS Rating Curve= 0 ,0
Exp/Cntr=0.3,0.1

Type RM Length L Ch R = 1 ,196064  ,441,441,441
BEGIN DESCRIPTION:
Mapping XS 3ec368de
END DESCRIPTION:
XS GIS Cut Line= 6
      2017165.48     13522353.72      2017030.92     13522061.81
      2016972.33     13521993.45      2016805.23     13521961.99
      2016696.53     13521899.79      2016475.18     13521665.43
#Sta/Elev= 30
  4485.4  554.48  4751.2  549.26    4786  548.68  4851.5  548.77  4880.1  547.17
  4886.7  547.58  4889.5  546.86    4890  546.06  4895.1  546.06  4895.6  546.86
  4912.5  548.01  4917.6  547.64  4924.7  548.44  4958.7  548.42  4964.9  548.52
    4970  547.36  4983.1  547.67  5022.5  546.88  5027.6   547.4  5168.3  549.75
  5189.9  549.65  5191.9  549.03  5196.9  549.03  5231.9  550.22  5239.2  549.87
  5246.1  550.47  5253.4  549.42  5267.5  549.18  5288.6  550.49  5514.5  551.19
#Mann= 6 ,-1 , 0
  4485.4     .05       0  4751.2      .1       0  4889.5     .07       0
  4895.6      .1       0  4958.7     .05       0  4983.1      .1       0
Bank Sta=4889.5,4895.6
XS Rating Curve= 0 ,0
Exp/Cntr=0.3,0.1

Type RM Length L Ch R = 1 ,195623  ,527,527,527
BEGIN DESCRIPTION:
Mapping XS 7705fe70
END DESCRIPTION:
XS GIS Cut Line= 4
      2017386.62     13522190.57      2017202.37     13521927.27
      2016863.82      13521597.4      2016458.91     13521565.68
#Sta/Elev= 30
  4399.8  554.11  4426.8  553.23  4477.4  553.22    4528  552.03  4534.1  552.54
    4555  551.57  4590.8  551.71  4641.3  550.53    4671   550.9  4685.8  549.75
  4719.5  548.61  4801.7  547.86  4911.9  546.28  4975.5  546.27  4986.6  543.04
  4987.1  542.24  4992.2  542.24  4992.7  543.04  5003.8  546.14  5024.9  546.01
    5039  544.96  5081.5  546.34  5102.8  547.74  5173.5  548.81  5202.7  548.31
  5323.1  548.32  5373.2  548.63  5383.2  549.22  5563.8  549.78    5600  550.49
#Mann= 4 ,-1 , 0
  4399.8     .05       0  4801.7      .1       0  4986.6     .07       0
  4992.7      .1       0
Bank Sta=4986.6,4992.7
XS Rating Curve= 0 ,0
Exp/Cntr=0.3,0.1

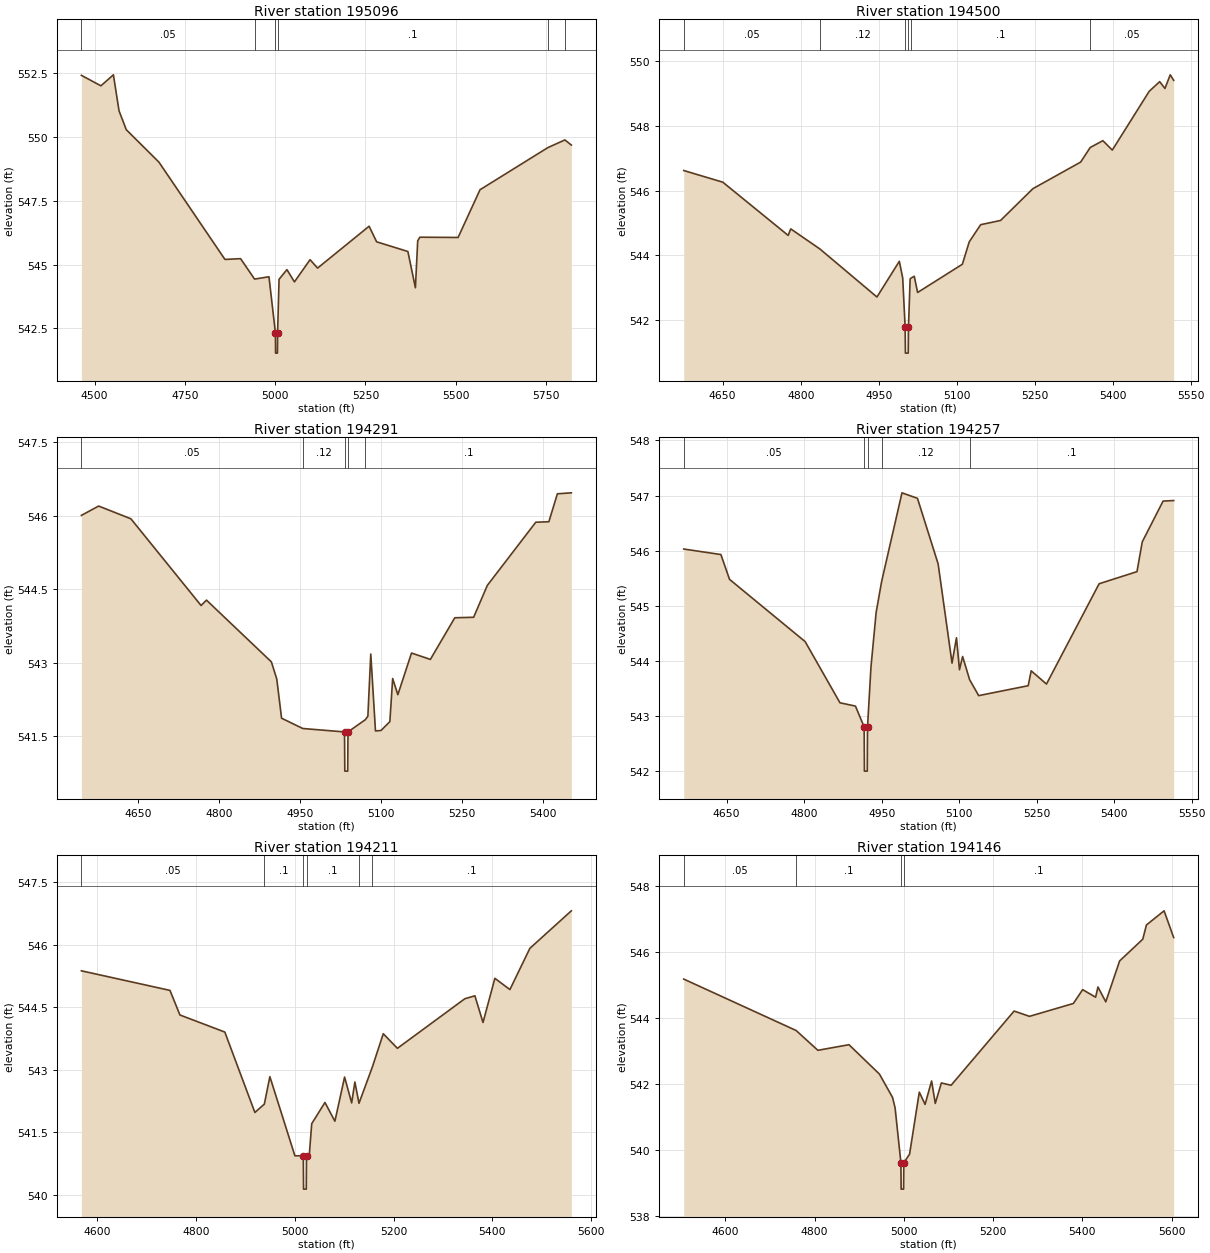
Type RM Length L Ch R = 1 ,195096  ,596,596,596
BEGIN DESCRIPTION:
Mapping XS f5f4f579
END DESCRIPTION:
XS GIS Cut Line= 4
      2017538.54     13522038.71      2017503.82     13521682.78
      2017048.09     13521322.54      2016635.73     13521253.09
#Sta/Elev= 30
  4463.5  552.41  4517.5     552  4552.1  552.43  4567.7  551.02  4587.8  550.28
  4678.2  549.01    4861   545.2  4904.3  545.23    4943  544.43  4982.9  544.52
  5000.7  542.33  5001.2  541.53  5006.3  541.53  5006.8  542.33  5010.8  544.42
  5032.6   544.8  5053.4  544.32  5096.7  545.19  5117.5  544.86  5260.2   546.5
    5281  545.89  5367.6  545.51  5388.4  544.09  5394.8  545.93  5400.8  546.07
  5506.6  546.06  5567.4  547.93  5755.3  549.58  5802.3  549.88  5820.2  549.68
#Mann= 6 ,-1 , 0
  4463.5     .05       0    4943      .1       0  5000.7     .07       0
  5006.8      .1       0  5755.3     .05       0  5802.3      .1       0
Bank Sta=5000.7,5006.8
XS Rating Curve= 0 ,0
Exp/Cntr=0.3,0.1

Type RM Length L Ch R = 1 ,194500  ,209,209,209
BEGIN DESCRIPTION:
Mapping XS 57b7d1a0
END DESCRIPTION:
XS GIS Cut Line= 4
        2017750.     13521499.99      2017764.43     13521210.03
      2017523.55     13521011.47      2017188.44     13520958.18
#Sta/Elev= 30
  4575.2  546.62  4650.3  546.26  4775.9  544.62  4780.9  544.82    4837   544.2
  4946.6  542.72  4989.6  543.82  4996.1  543.31  5000.8  541.79  5001.3  540.99
  5006.7  540.99  5007.2  541.79  5010.4  543.28    5013  543.31  5018.3  543.36
  5024.8  542.86  5110.8  543.73    5124  544.42    5146  544.95  5184.2  545.08
  5246.4  546.06  5338.2  546.88  5356.6  547.33  5380.9  547.54    5399  547.25
  5469.9  549.06  5490.1  549.36  5500.2  549.15  5510.4  549.57    5517   549.4
#Mann= 6 ,-1 , 0
  4575.2     .05       0    4837     .12       0  5000.8     .07       0
  5007.2     .12       0    5013      .1       0  5356.6     .05       0
Bank Sta=5000.8,5007.2
XS Rating Curve= 0 ,0
Exp/Cntr=0.3,0.1

Type RM Length L Ch R = 1 ,194291  ,34,34,34
BEGIN DESCRIPTION:
Mapping XS 0eb35770
END DESCRIPTION:
XS GIS Cut Line= 6
      2017824.99     13521444.02       2017795.9     13521276.22
      2017801.32     13521072.23      2017828.45     13521033.17
      2017823.03     13520919.24       2017464.8     13520823.42
#Sta/Elev= 30
  4545.7  546.01  4577.6   546.2  4637.3  545.94  4767.2  544.17  4777.2  544.28
  4897.3  543.02  4907.3  542.67  4916.2  541.87  4955.4  541.66  5032.7  541.59
  5033.2  540.79  5038.6  540.79  5039.1  541.59  5071.2  541.84  5075.9  541.91
  5081.3  543.18    5090  541.61  5100.3  541.62  5116.6   541.8  5121.8  542.68
  5131.4  542.35  5156.7   543.2  5191.6  543.07  5236.8  543.92  5271.7  543.93
    5297  544.58  5386.7  545.87  5410.9  545.88  5426.7  546.45  5452.5  546.47
#Mann= 5 ,-1 , 0
  4545.7     .05       0  4955.4     .12       0  5032.7     .07       0
  5039.1     .12       0  5071.2      .1       0
Bank Sta=5032.7,5039.1
XS Rating Curve= 0 ,0
Exp/Cntr=0.3,0.1

Type RM Length L Ch R = 1 ,194257  ,46,46,46
BEGIN DESCRIPTION:
Mapping XS bf34067c
END DESCRIPTION:
XS GIS Cut Line= 5
      2017877.08     13521426.71      2017858.83     13521194.84
        2017861.     13520906.21       2017679.8     13520799.88
      2017464.71     13520771.31
#Sta/Elev= 30
  4566.9  546.03  4638.8  545.93  4655.5  545.48  4801.9  544.35  4869.3  543.24
  4899.3  543.18  4916.1   542.8  4916.6     542  4922.1     542  4922.6   542.8
  4929.3  543.89  4939.3  544.88  4949.9  545.44  4989.3  547.05  5019.3  546.95
  5059.3  545.76  5086.2  543.96  5094.8  544.42  5100.6  543.84  5106.7  544.08
  5120.2  543.66  5137.8  543.37  5233.6  543.55  5239.4  543.82    5269  543.58
  5370.9   545.4  5444.2  545.62  5454.4  546.16  5494.7   546.9  5515.2  546.91
#Mann= 5 ,-1 , 0
  4566.9     .05       0  4916.1     .07       0  4922.6     .05       0
  4949.9     .12       0  5120.2      .1       0
Bank Sta=4916.1,4922.6
XS Rating Curve= 0 ,0
Exp/Cntr=0.3,0.1

Type RM Length L Ch R = 1 ,194211  ,65,65,65
BEGIN DESCRIPTION:
Mapping XS e207eb88
END DESCRIPTION:
XS GIS Cut Line= 5
      2017920.49     13521413.64      2017936.96     13521187.25
      2017892.47     13520905.13      2017779.62     13520768.41
      2017482.15     13520723.58
#Sta/Elev= 30
  4568.9  545.37    4748   544.9  4768.1  544.31  4858.9   543.9  4919.7  541.97
  4938.8  542.17    4950  542.83  5000.6  540.93  5017.6  540.93  5018.1  540.13
  5023.6  540.13  5024.1  540.93  5029.6  540.93  5034.6   541.7  5061.4  542.21
  5081.5  541.76  5101.1  542.82  5115.4   542.2  5121.9   542.7  5130.2  542.19
  5157.5  543.07  5179.3  543.86  5207.9  543.51  5344.3   544.7  5364.6  544.77
    5381  544.13    5405  545.19  5435.4  544.92  5475.8  545.91  5559.6  546.81
#Mann= 6 ,-1 , 0
  4568.9     .05       0  4938.8      .1       0  5017.6     .07       0
  5024.1      .1       0  5130.2     .12       0  5157.5      .1       0
Bank Sta=5017.6,5024.1
XS Rating Curve= 0 ,0
Exp/Cntr=0.3,0.1

Type RM Length L Ch R = 1 ,194146  ,228,228,228
BEGIN DESCRIPTION:
Mapping XS 7be223d8
END DESCRIPTION:
XS GIS Cut Line= 4
      2017994.27     13521422.35      2018048.72     13521123.23
      2017847.98     13520753.22      2017488.24     13520654.62
#Sta/Elev= 30
  4506.7  545.17  4758.6  543.61  4807.3  543.01    4877  543.18  4945.2  542.29
  4974.7  541.58  4980.4  541.26  4993.4   539.6  4993.9   538.8  4999.4   538.8
  4999.9   539.6  5012.8  539.86  5034.6  541.74  5047.6  541.37  5062.2  542.08
  5070.4   541.4  5084.1  542.02  5105.9  541.95  5247.1   544.2  5281.6  544.04
  5379.9  544.43  5400.7  544.85  5429.8  544.62    5435  544.93  5452.5  544.48
  5483.6  545.72  5535.5  546.38  5543.6  546.81  5583.2  547.24  5604.7  546.43
#Mann= 4 ,-1 , 0
  4506.7     .05       0  4758.6      .1       0  4993.4     .07       0
  4999.9      .1       0
Bank Sta=4993.4,4999.9
XS Rating Curve= 0 ,0
Exp/Cntr=0.3,0.1

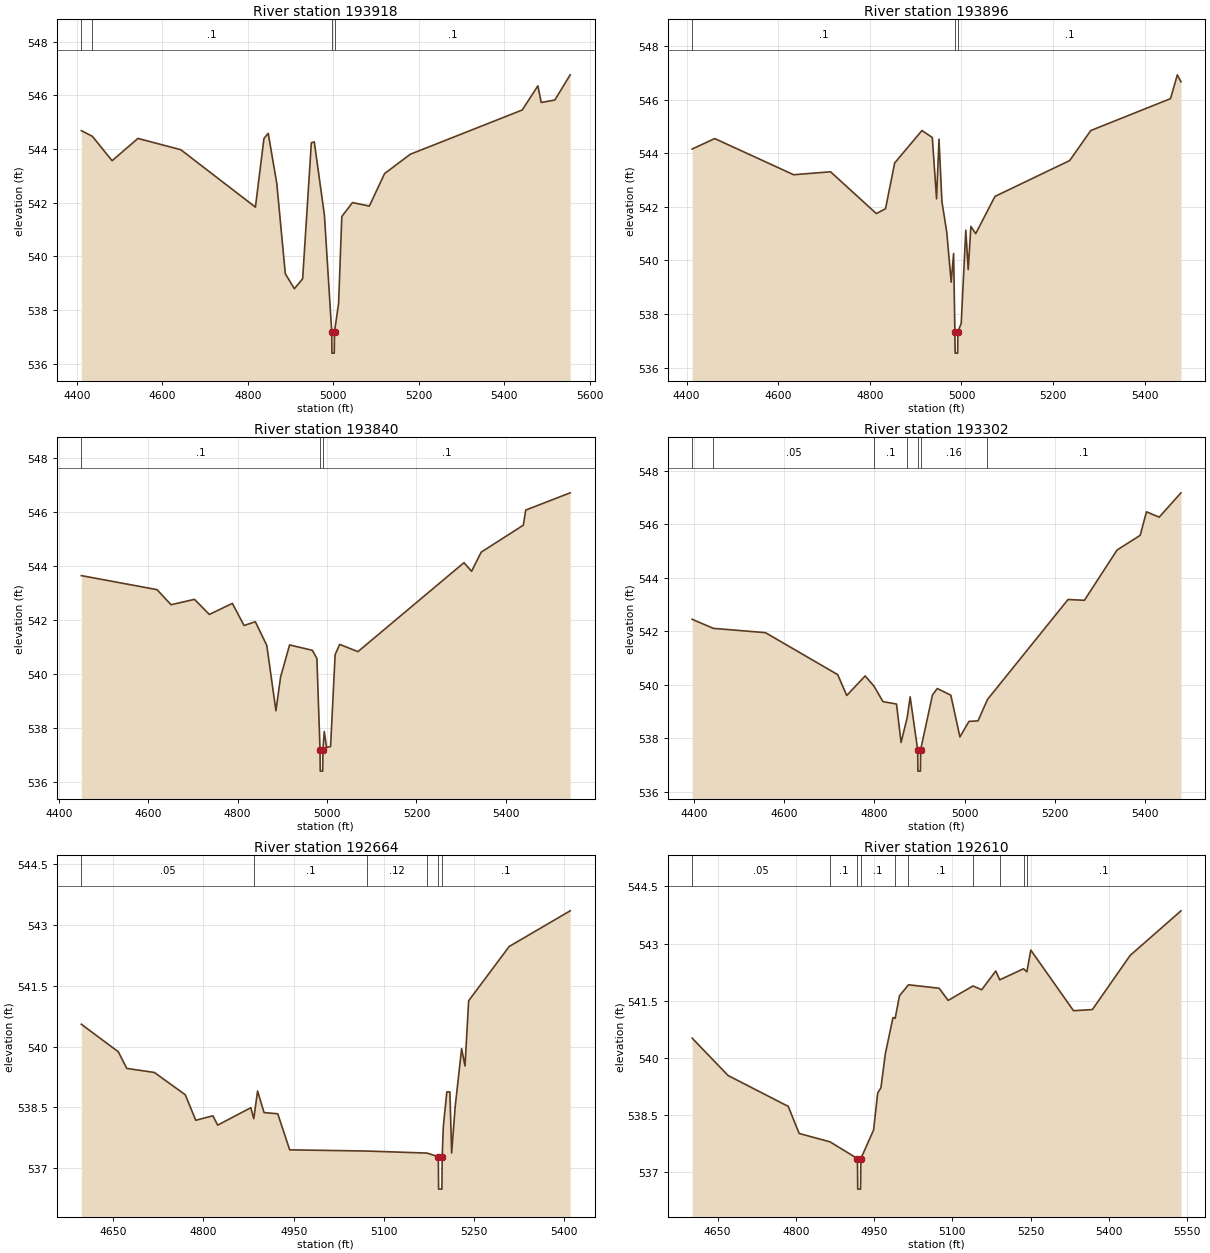
Type RM Length L Ch R = 1 ,193918  ,22,22,22
BEGIN DESCRIPTION:
Mapping XS 52a34a8c
END DESCRIPTION:
XS GIS Cut Line= 5
      2018063.71     13521413.68      2018136.61      13521117.8
      2018132.27     13520939.85      2018106.23      13520805.3
      2017634.03     13520576.01
#Sta/Elev= 30
    4410  544.68  4435.7  544.47    4482  543.56  4542.5  544.39  4642.8  543.97
  4817.6  541.83  4837.6  544.39  4847.6  544.58  4867.6  542.72  4887.6  539.35
  4908.8  538.79  4928.2  539.16  4948.6  544.23  4955.5  544.26  4979.2  541.53
  4996.3  537.19  4996.8  536.39  5002.3  536.39  5002.8  537.19  5012.4  538.24
  5019.9  541.48  5044.9     542  5084.4  541.87  5120.1  543.08  5180.2   543.8
  5442.5  545.45  5479.1  546.35  5486.9  545.73  5518.7  545.82  5554.7  546.76
#Mann= 4 ,-1 , 0
    4410     .05       0  4435.7      .1       0  4996.3     .07       0
  5002.8      .1       0
Bank Sta=4996.3,5002.8
XS Rating Curve= 0 ,0
Exp/Cntr=0.3,0.1

Type RM Length L Ch R = 1 ,193896  ,56,56,56
BEGIN DESCRIPTION:
Mapping XS 6b0c51b9
END DESCRIPTION:
XS GIS Cut Line= 5
      2018120.14     13521413.66      2018161.57     13521157.95
      2018166.99     13520934.43       2018100.8     13520731.52
      2017764.25     13520576.02
#Sta/Elev= 30
  4412.3  544.16  4461.6  544.55  4633.8   543.2  4714.3  543.31  4814.3  541.75
  4834.3  541.93  4854.3  543.64  4913.8  544.85  4936.4  544.59  4945.7   542.3
    4951  544.53  4957.4   542.2    4968  541.05  4977.6  539.19  4982.9  540.26
  4985.7  537.34  4986.2  536.54  4991.7  536.54  4992.2  537.34  4999.5  537.65
  5009.5  541.13  5014.8  539.66  5020.6  541.27  5031.1     541  5073.1  542.39
  5236.3  543.73  5282.2  544.85  5456.2  546.04  5471.2  546.93  5479.1  546.67
#Mann= 3 ,-1 , 0
  4412.3      .1       0  4985.7     .07       0  4992.2      .1       0
Bank Sta=4985.7,4992.2
XS Rating Curve= 0 ,0
Exp/Cntr=0.3,0.1

Type RM Length L Ch R = 1 ,193840  ,538,538,538
BEGIN DESCRIPTION:
Mapping XS 4102cd8f
END DESCRIPTION:
XS GIS Cut Line= 4
      2018180.91     13521400.64      2018236.96     13521157.78
        2018138.     13520653.87      2017829.62     13520532.72
#Sta/Elev= 30
  4450.1  543.65  4619.5  543.13  4650.9  542.57  4703.3  542.77  4736.6  542.21
  4788.1  542.62  4814.3   541.8  4839.5  541.94  4865.2  541.06  4885.6  538.64
    4896  539.89  4916.2  541.08  4967.1  540.88  4977.3  540.58  4984.3   537.2
  4984.8   536.4  4990.3   536.4  4990.8   537.2  4993.8  537.87  4998.9  537.28
  5007.9  537.31  5018.1  540.72  5028.3   541.1  5069.1  540.83  5306.5  544.13
  5323.5  543.81    5345  544.52  5439.3  545.52  5444.7  546.08  5544.2  546.72
#Mann= 3 ,-1 , 0
  4450.1      .1       0  4984.3     .07       0  4990.8      .1       0
Bank Sta=4984.3,4990.8
XS Rating Curve= 0 ,0
Exp/Cntr=0.3,0.1

Type RM Length L Ch R = 1 ,193302  ,638,638,638
BEGIN DESCRIPTION:
Mapping XS 037fbc06
END DESCRIPTION:
XS GIS Cut Line= 4
      2018480.39     13521214.01      2018599.37     13521016.28
      2018564.65     13520469.41      2018311.15      13520302.6
#Sta/Elev= 30
  4396.6  542.45  4443.6  542.11  4558.8  541.95  4718.8  540.38  4738.9   539.6
  4779.6  540.33  4799.2  539.95    4819  539.37  4849.1  539.28  4859.1  537.84
  4872.8  538.78  4879.2  539.55  4895.9  537.57  4896.4  536.77  4901.9  536.77
  4902.4  537.57  4928.7  539.62  4939.3  539.86  4969.3  539.61  4989.4  538.05
  5009.4  538.63  5029.5  538.65  5050.4  539.45  5228.8  543.19    5265  543.16
  5337.3  545.04  5388.5  545.59  5402.4  546.47  5430.6  546.27  5478.8  547.18
#Mann= 7 ,-1 , 0
  4396.6      .1       0  4443.6     .05       0  4799.2      .1       0
  4872.8     .16       0  4895.9     .07       0  4902.4     .16       0
  5050.4      .1       0
Bank Sta=4895.9,4902.4
XS Rating Curve= 0 ,0
Exp/Cntr=0.3,0.1

Type RM Length L Ch R = 1 ,192664  ,54,54,54
BEGIN DESCRIPTION:
Mapping XS 93d390fc
END DESCRIPTION:
XS GIS Cut Line= 5
      2018719.16     13521040.59      2019012.57     13520905.17
      2019101.11     13520806.21      2019132.36     13520655.17
      2019040.36     13520474.64
#Sta/Elev= 30
    4597  540.55  4658.5  539.87  4672.5  539.46  4718.4  539.36  4769.8  538.81
  4787.2  538.18  4815.7  538.29  4823.7  538.06  4878.8  538.49  4883.7  538.22
    4890   538.9  4900.8  538.37  4923.6  538.34  4943.4  537.45  5071.9  537.42
  5171.9  537.37  5190.5  537.28    5191  536.48  5196.5  536.48    5197  537.28
  5198.9  538.03  5204.7  538.88  5209.8  538.88  5212.7  537.37  5218.6  538.52
  5229.3  539.95  5234.9  539.52    5241  541.13  5308.4  542.47  5409.8  543.35
#Mann= 6 ,-1 , 0
    4597     .05       0  4883.7      .1       0  5071.9     .12       0
  5171.9      .1       0  5190.5     .07       0    5197      .1       0
Bank Sta=5190.5,5197
XS Rating Curve= 0 ,0
Exp/Cntr=0.3,0.1

Type RM Length L Ch R = 1 ,192610  ,35,35,35
BEGIN DESCRIPTION:
Mapping XS 2bf6e60a
END DESCRIPTION:
XS GIS Cut Line= 6
      2018734.83     13521064.89      2018904.93     13521028.44
      2019146.25     13520851.35      2019189.65     13520715.94
      2019106.32     13520481.56      2019052.46     13520432.92
#Sta/Elev= 30
  4601.4  540.52  4670.3  539.54  4785.6  538.73  4806.5  538.02  4865.7   537.8
  4918.2  537.36  4918.7  536.56  4924.2  536.56  4924.7  537.36  4949.1  538.11
    4957  539.08  4963.2  539.22  4971.6  540.11  4986.3  541.06  4990.5  541.04
  4998.7  541.63    5016  541.92  5074.7  541.83    5092  541.51  5139.6  541.89
  5156.3  541.79  5183.2  542.28  5190.9  542.05  5236.5  542.34  5242.9  542.26
  5250.4  542.83  5332.3  541.24  5368.4  541.27  5440.8  542.69  5538.2  543.86
#Mann= 10 ,-1 , 0
  4601.4     .05       0  4865.7      .1       0  4918.2     .07       0
  4924.7      .1       0  4990.5     .07       0    5016      .1       0
  5139.6     .12       0  5190.9      .1       0  5236.5     .12       0
  5242.9      .1       0
Bank Sta=4918.2,4924.7
XS Rating Curve= 0 ,0
Exp/Cntr=0.3,0.1