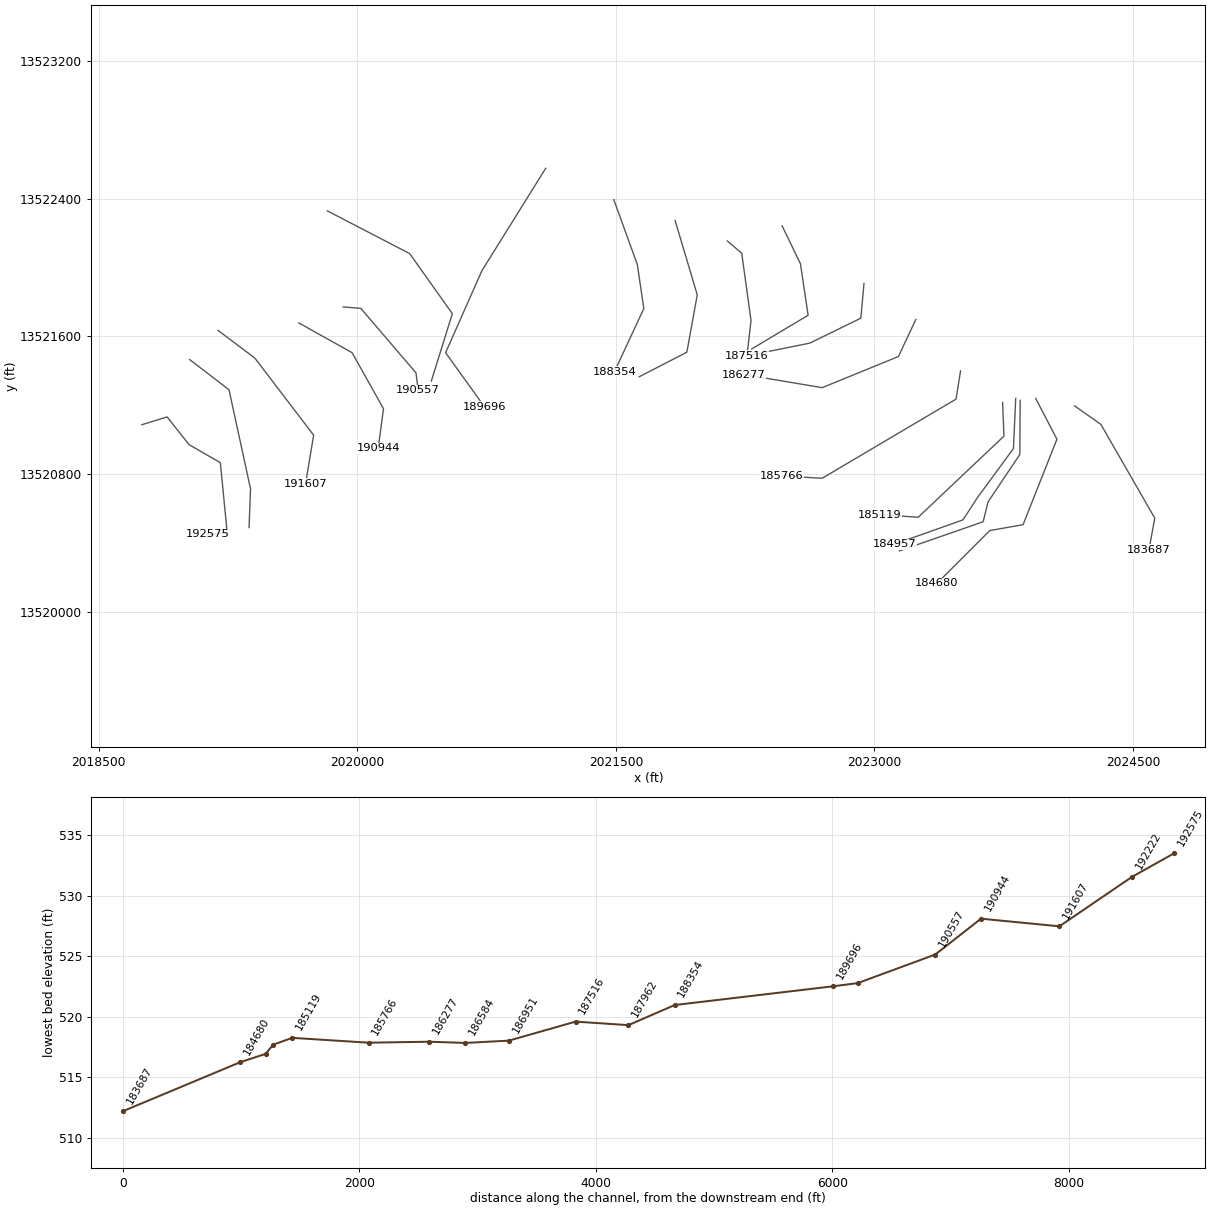
HEC-RAS study LAGUNILLAS Cr.prj: LAGUNILLAS Cr Base Level Engineering

--- LAGUNILLAS Cr.g01 (geometry) --- (continued)

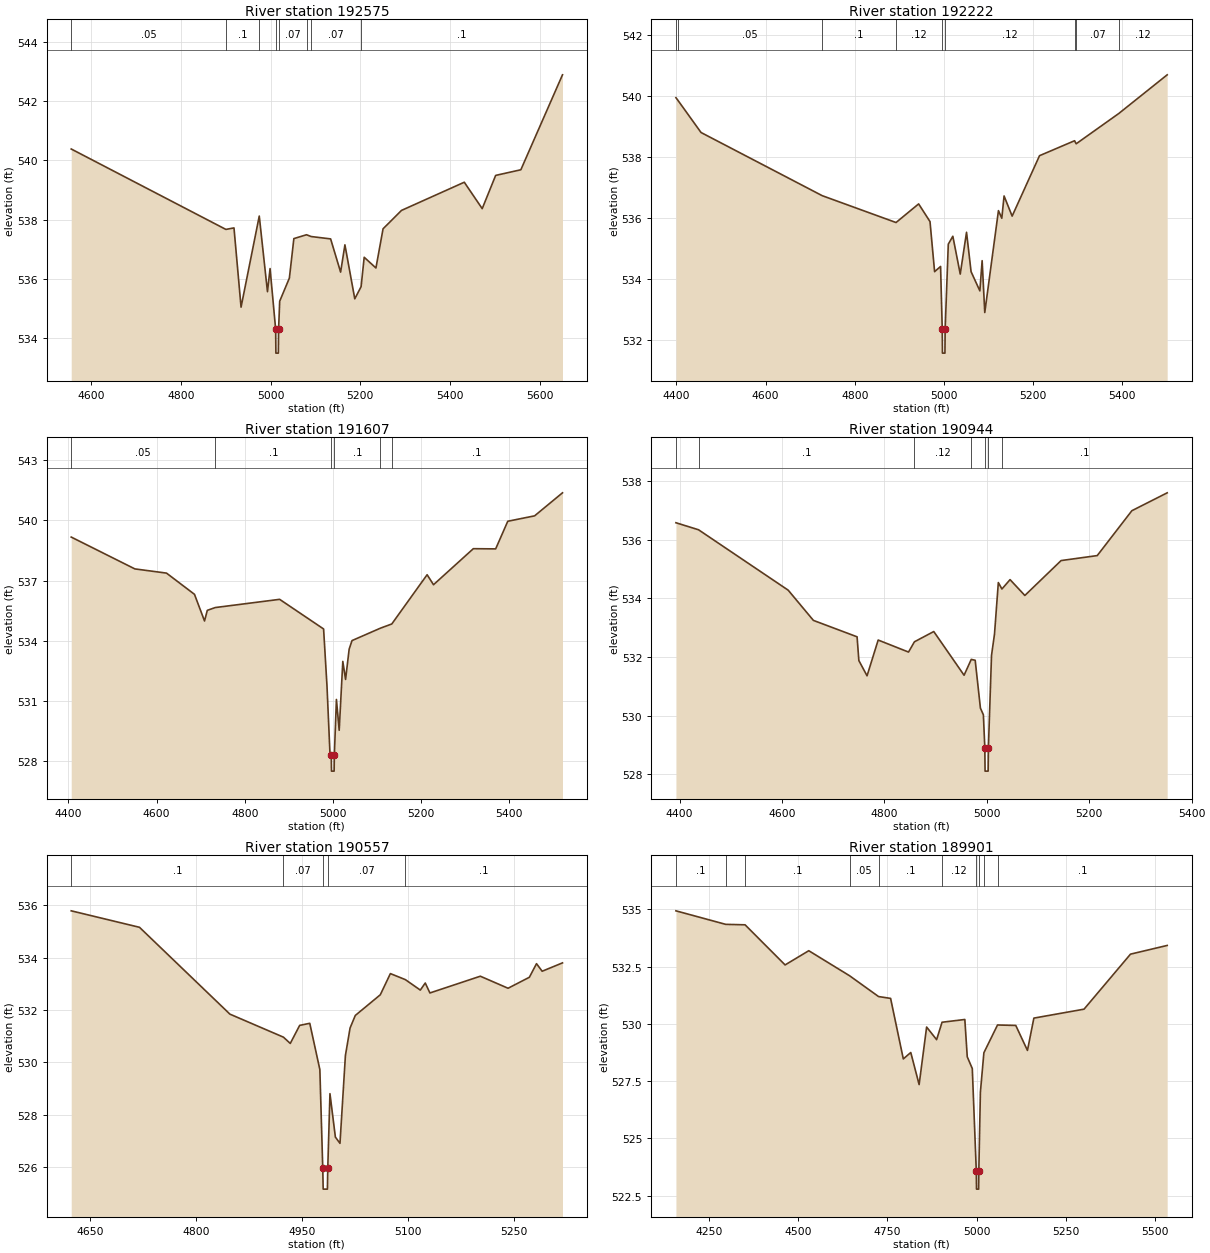
Type RM Length L Ch R = 1 ,192575  ,353,353,353
BEGIN DESCRIPTION:
Mapping XS 28680f2e
END DESCRIPTION:
XS GIS Cut Line= 6
      2018750.46     13521087.48      2018896.25      13521132.6
      2019024.72     13520971.15      2019205.27     13520866.98
       2019245.2     13520458.99      2019132.32     13520452.05
#Sta/Elev= 30
    4555  540.38    4900  537.67  4918.1  537.72  4933.9  535.05  4974.5  538.12
  4992.8  535.57  4998.6  536.35  5011.1   534.3  5011.6   533.5  5017.1   533.5
  5017.6   534.3  5020.1  535.25  5041.7  536.03  5051.7  537.36  5079.9  537.49
  5090.1  537.43  5133.7  537.35    5156  536.23  5165.6  537.15  5187.6  535.33
  5201.7  535.74  5208.6  536.73  5234.8  536.37  5250.7  537.69  5291.8  538.31
  5431.9  539.26  5471.9  538.37  5501.9  539.49  5558.1  539.68    5651  542.88
#Mann= 8 ,-1 , 0
    4555     .05       0    4900      .1       0  4974.5     .07       0
  5011.1     .07       0  5017.6     .07       0  5079.9      .1       0
  5090.1     .07       0  5201.7      .1       0
Bank Sta=5011.1,5017.6
XS Rating Curve= 0 ,0
Exp/Cntr=0.3,0.1

Type RM Length L Ch R = 1 ,192222  ,615,615,615
BEGIN DESCRIPTION:
Mapping XS 08f5b016
END DESCRIPTION:
XS GIS Cut Line= 4
      2019027.24     13521465.78      2019255.62     13521290.59
      2019380.62      13520714.2      2019371.94     13520490.29
#Sta/Elev= 30
    4399  539.94  4403.2  539.86  4455.3   538.8    4727  536.73  4892.6  535.85
  4943.3  536.46  4968.8  535.88  4979.1  534.24  4992.5  534.41  4996.2  532.37
  4996.7  531.57  5002.3  531.57  5002.8  532.37  5009.8  535.14    5020   535.4
  5036.6  534.16  5050.7  535.53  5060.9  534.24  5080.6  533.61  5085.7   534.6
  5091.6   532.9  5122.3  536.24  5129.8  535.99  5134.9  536.72    5153  536.06
  5214.4  538.04    5293  538.53  5296.6  538.43  5391.9  539.42  5500.7  540.69
#Mann= 9 ,-1 , 0
    4399      .1       0  4403.2     .05       0    4727      .1       0
  4892.6     .12       0  4996.2     .07       0  5002.8     .12       0
    5293      .1       0  5296.6     .07       0  5391.9     .12       0
Bank Sta=4996.2,5002.8
XS Rating Curve= 0 ,0
Exp/Cntr=0.3,0.1

Type RM Length L Ch R = 1 ,191607  ,663,663,663
BEGIN DESCRIPTION:
Mapping XS 90155dc2
END DESCRIPTION:
XS GIS Cut Line= 4
      2019192.15     13521635.06      2019405.57     13521474.42
      2019746.72      13521026.5      2019700.01     13520745.32
#Sta/Elev= 30
  4406.2  539.17  4550.7  537.58  4622.5  537.37    4686  536.31  4708.8  534.98
  4715.1  535.51  4733.2  535.65  4879.3  536.06  4979.1  534.58  4986.8  531.73
  4993.7   528.3  4996.5  528.28    4997  527.48    5003  527.48  5003.5  528.28
  5008.2  531.06  5014.5  529.52  5022.7  532.96    5029  532.06  5037.1  533.57
  5043.6     534  5108.1  534.62  5133.9  534.83  5214.1  537.29  5228.6  536.79
    5319  538.59  5369.7  538.58  5397.2  539.96  5458.1  540.23  5521.4  541.38
#Mann= 6 ,-1 , 0
  4406.2     .05       0  4733.2      .1       0  4996.5     .07       0
  5003.5      .1       0  5108.1     .07       0  5133.9      .1       0
Bank Sta=4996.5,5003.5
XS Rating Curve= 0 ,0
Exp/Cntr=0.3,0.1

Type RM Length L Ch R = 1 ,190944  ,387,387,387
BEGIN DESCRIPTION:
Mapping XS d9e19c1f
END DESCRIPTION:
XS GIS Cut Line= 4
      2019660.97     13521678.42      2019969.77     13521505.69
      2020152.06     13521180.17      2020121.06     13520949.66
#Sta/Elev= 30
  4392.7  536.58  4436.9  536.34    4612  534.28  4661.2  533.25  4746.5  532.69
    4750  531.88    4766  531.36  4787.7  532.58    4847  532.17  4858.5  532.52
  4896.3  532.87  4955.5  531.38  4969.5  531.92  4977.2  531.89  4987.4  530.26
  4993.2  530.03    4996  528.91  4996.5  528.11  5002.5  528.11    5003  528.91
  5009.1  532.06  5014.9  532.78  5022.4  534.54  5029.4  534.32  5045.3  534.64
  5074.2   534.1    5145  535.29  5215.6  535.46  5283.2  536.99  5352.2   537.6
#Mann= 7 ,-1 , 0
  4392.7     .05       0  4436.9      .1       0  4858.5     .12       0
  4969.5     .07       0    4996     .07       0    5003     .07       0
  5029.4      .1       0
Bank Sta=4996,5003
XS Rating Curve= 0 ,0
Exp/Cntr=0.3,0.1

Type RM Length L Ch R = 1 ,190557  ,656,656,656
BEGIN DESCRIPTION:
Mapping XS 39165ef5
END DESCRIPTION:
XS GIS Cut Line= 4
      2019918.55      13521771.3      2020020.16     13521763.48
      2020340.47     13521388.48      2020353.29     13521288.49
#Sta/Elev= 30
  4623.3  535.79    4720  535.16  4848.1  531.84  4923.9  530.96  4933.6  530.72
  4946.9  531.41  4961.2  531.49  4975.5  529.72  4979.6  525.95  4980.2  525.15
  4986.2  525.15  4986.7  525.95  4989.8   528.8  4997.5  527.14    5004   526.9
  5011.7  530.26  5018.3  531.31  5025.7  531.79  5061.1  532.58  5075.4  533.39
  5096.6  533.16  5117.8  532.76  5124.8  533.03  5131.4  532.65  5202.8  533.29
  5242.1  532.83  5272.3  533.25  5282.4  533.77  5290.4  533.48  5319.2   533.8
#Mann= 5 ,-1 , 0
  4623.3      .1       0  4923.9     .07       0  4979.6     .07       0
  4986.7     .07       0  5096.6      .1       0
Bank Sta=4979.6,4986.7
XS Rating Curve= 0 ,0
Exp/Cntr=0.3,0.1

Type RM Length L Ch R = 1 ,189901  ,205,205,205
BEGIN DESCRIPTION:
Mapping XS bc2b2cc0
END DESCRIPTION:
XS GIS Cut Line= 4
      2019825.86     13522329.48      2020304.01     13522081.19
      2020551.41     13521732.23       2020429.6      13521341.3
#Sta/Elev= 30
  4157.5  534.93  4296.9  534.34  4351.2  534.32  4463.3  532.57  4529.6  533.19
  4643.7   532.1  4725.1  531.19  4758.8  531.11  4794.4  528.47  4815.3  528.75
  4838.7  527.35  4859.7  529.86  4887.7  529.31  4902.9  530.07  4966.7  530.19
  4973.5  528.56  4987.6  528.05  4998.8  523.59  4999.4  522.79  5005.4  522.79
  5005.9  523.59  5010.3  527.02  5020.1  528.74  5058.3  529.95  5109.4  529.93
  5142.1  528.84  5160.1  530.25  5300.6  530.64  5430.7  533.04  5533.5  533.42
#Mann= 10 ,-1 , 0
  4157.5      .1       0  4296.9     .05       0  4351.2      .1       0
  4643.7     .05       0  4725.1      .1       0  4902.9     .12       0
  4998.8     .07       0  5005.9     .12       0  5020.1     .07       0
  5058.3      .1       0
Bank Sta=4998.8,5005.9
XS Rating Curve= 0 ,0
Exp/Cntr=0.3,0.1

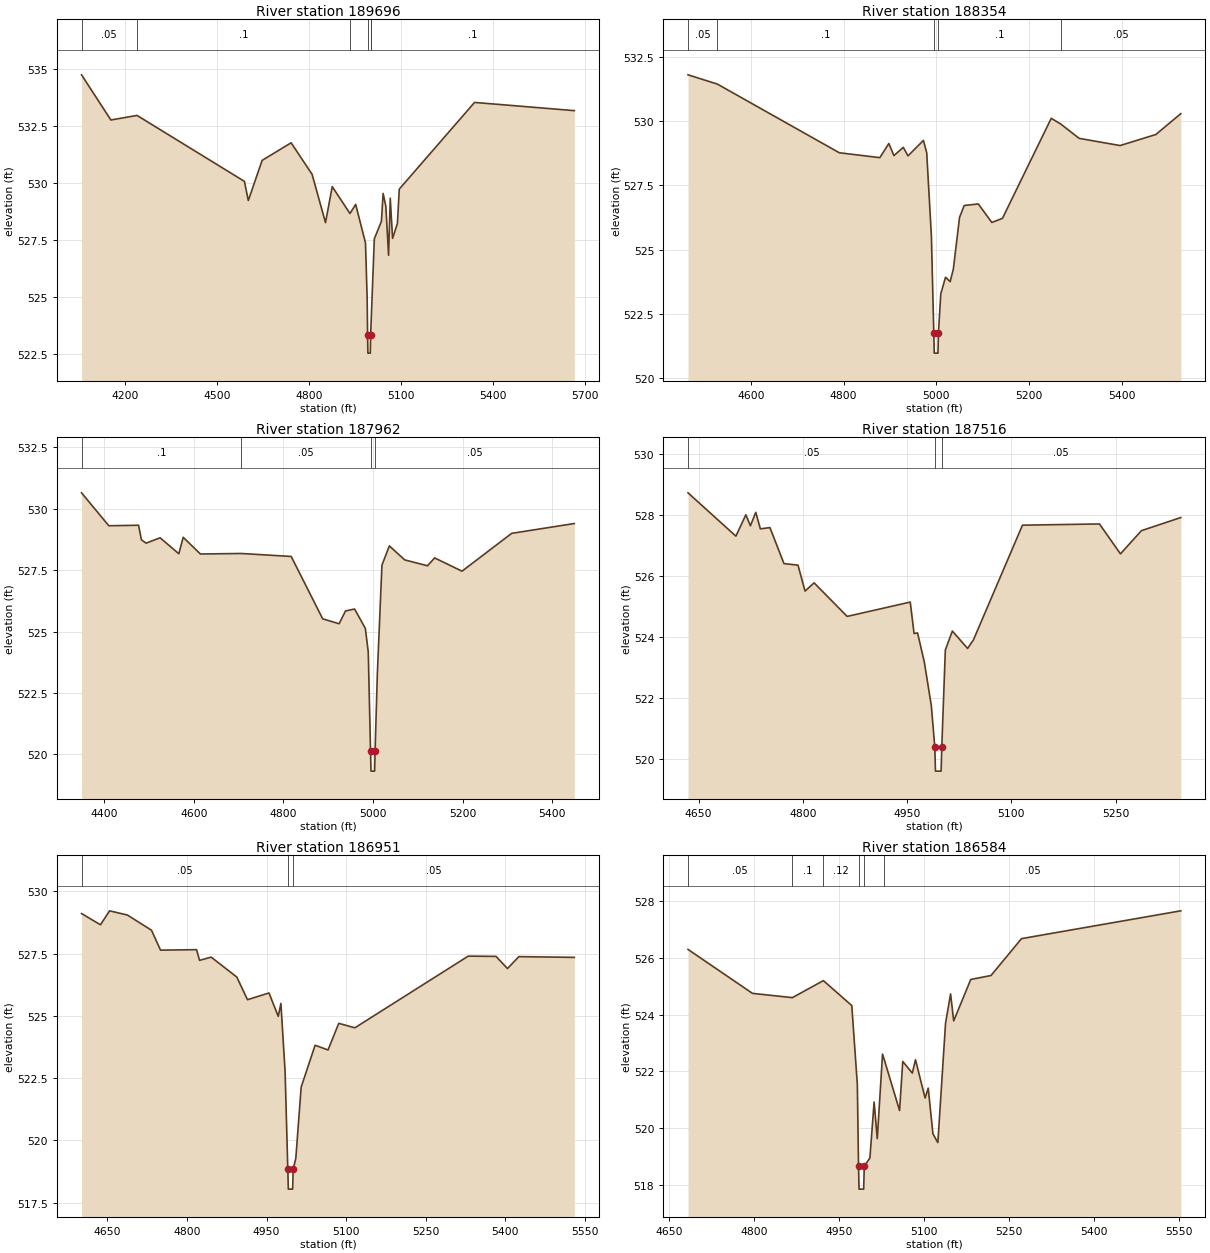
Type RM Length L Ch R = 1 ,189696  ,1342,1342,1342
BEGIN DESCRIPTION:
Mapping XS cf8ca89c
END DESCRIPTION:
XS GIS Cut Line= 4
      2021093.21     13522576.84      2020723.28     13521982.23
      2020512.35     13521505.67      2020737.33     13521192.32
#Sta/Elev= 30
    4057  534.73  4152.6  532.75    4238  532.95  4588.2  530.06  4600.9  529.22
    4646  530.98  4740.5  531.75  4808.9  530.37  4852.7  528.25  4874.6  529.83
  4932.5  528.65  4951.1  529.05  4983.1  527.36  4988.6  524.91  4989.9  523.33
  4990.9  522.53  4998.8  522.53  4999.8  523.33  5000.2  523.44  5011.9  527.54
  5035.1  528.31  5040.6  529.53  5049.5  528.97  5058.4  526.82  5063.9  529.32
  5071.4  527.56  5087.2  528.21  5093.3  529.72  5338.8  533.52  5664.2  533.16
#Mann= 6 ,-1 , 0
    4057     .05       0    4238      .1       0  4932.5     .07       0
  4989.9     .07       0  4999.8     .07       0  5000.2      .1       0
Bank Sta=4989.9,4999.8
XS Rating Curve= 0 ,0
Exp/Cntr=0.3,0.1

Type RM Length L Ch R = 1 ,188354  ,392,392,392
BEGIN DESCRIPTION:
Mapping XS 90751aec
END DESCRIPTION:
XS GIS Cut Line= 4
      2021488.21     13522394.55      2021624.72     13522017.41
      2021662.48      13521762.2      2021492.53     13521396.31
#Sta/Elev= 30
  4464.6   531.8  4527.9  531.44  4790.8  528.77  4878.2  528.58  4897.6  529.13
  4908.6  528.66  4928.8  528.98  4938.9  528.65  4972.2  529.25  4979.3  528.77
  4989.4  525.52  4994.5  521.78  4995.5  520.98  5003.6  520.98  5004.6  521.78
  5009.6  523.28  5019.8  523.93  5029.9  523.76  5036.7  524.25  5050.1  526.26
  5060.2  526.72  5090.5  526.78  5119.7  526.06  5142.6  526.22  5247.8  530.11
  5268.1  529.89    5308  529.33  5396.2  529.05  5473.4  529.48  5527.1  530.29
#Mann= 5 ,-1 , 0
  4464.6     .05       0  4527.9      .1       0  4994.5     .07       0
  5004.6      .1       0  5268.1     .05       0
Bank Sta=4994.5,5004.6
XS Rating Curve= 0 ,0
Exp/Cntr=0.3,0.1

Type RM Length L Ch R = 1 ,187962  ,446,446,446
BEGIN DESCRIPTION:
Mapping XS dbf56f06
END DESCRIPTION:
XS GIS Cut Line= 4
      2021844.09     13522273.07      2021972.37     13521841.63
      2021912.11     13521508.52      2021635.75     13521365.93
#Sta/Elev= 30
  4349.6  530.65  4410.4  529.31  4476.8  529.33  4483.2  528.74  4493.6   528.6
  4524.9  528.82  4566.7  528.17  4576.4  528.84  4614.8  528.16  4706.1  528.18
  4817.4  528.06  4887.7  525.52  4924.4  525.32  4938.6  525.84  4958.9  525.92
  4982.9  525.13  4989.4  524.17  4994.5  520.12  4995.5  519.32  5003.6  519.32
  5004.6  520.12  5009.7  523.29  5019.9   527.7  5036.4  528.49  5070.7  527.92
  5121.5  527.68  5137.5     528  5198.6  527.46  5309.4     529  5449.2   529.4
#Mann= 4 ,-1 , 0
  4349.6      .1       0  4706.1     .05       0  4994.5     .03       0
  5004.6     .05       0
Bank Sta=4994.5,5004.6
XS Rating Curve= 0 ,0
Exp/Cntr=0.3,0.1

Type RM Length L Ch R = 1 ,187516  ,565,565,565
BEGIN DESCRIPTION:
Mapping XS 336a2050
END DESCRIPTION:
XS GIS Cut Line= 4
      2022147.15     13522154.42      2022230.51     13522083.22
      2022284.33     13521692.59      2022260.91     13521488.77
#Sta/Elev= 30
  4634.7  528.73  4703.6  527.31  4717.9  528.01  4724.5  527.65  4732.2  528.09
  4738.8  527.55  4752.6  527.59  4772.8  526.41    4793  526.36  4803.1  525.51
  4816.1  525.78  4863.7  524.68  4954.5  525.15    4960  524.12    4965  524.14
  4974.7  523.19  4984.8  521.76  4989.8  520.41  4990.8  519.61  4998.9  519.61
  4999.9  520.41    5005  523.58  5015.1   524.2    5037  523.63  5045.4  523.91
    5116  527.67  5226.8  527.71    5257  526.73  5287.2  527.49  5343.8  527.92
#Mann= 3 ,-1 , 0
  4634.7     .05       0  4989.8     .03       0  4999.9     .05       0
Bank Sta=4989.8,4999.9
XS Rating Curve= 0 ,0
Exp/Cntr=0.3,0.1

Type RM Length L Ch R = 1 ,186951  ,367,367,367
BEGIN DESCRIPTION:
Mapping XS 62e79390
END DESCRIPTION:
XS GIS Cut Line= 4
      2022464.75     13522242.69      2022571.33     13522021.32
       2022615.6     13521723.14      2022288.39     13521527.47
#Sta/Elev= 30
  4601.5  529.11  4637.2  528.66  4654.3  529.22    4688  529.05  4733.3  528.44
  4750.3  527.64  4818.2  527.66  4823.8  527.23  4845.7  527.36    4894  526.56
  4914.2  525.65  4954.7  525.92  4972.1  524.98  4977.1   525.5    4985  522.76
  4990.1  518.84  4991.1  518.04  4999.2  518.04  5000.2  518.84  5005.2  519.28
  5015.3  522.14  5041.5  523.82  5065.9  523.63  5086.1   524.7  5116.4  524.52
    5330   527.4  5382.4  527.39    5404   526.9  5425.4  527.38  5529.9  527.35
#Mann= 3 ,-1 , 0
  4601.5     .05       0  4990.1     .03       0  5000.2     .05       0
Bank Sta=4990.1,5000.2
XS Rating Curve= 0 ,0
Exp/Cntr=0.3,0.1

Type RM Length L Ch R = 1 ,186584  ,307,307,307
BEGIN DESCRIPTION:
Mapping XS 3b1316af
END DESCRIPTION:
XS GIS Cut Line= 4
      2022939.82     13521908.04      2022921.59     13521706.21
      2022625.35     13521561.25      2022294.12     13521494.22
#Sta/Elev= 30
  4683.5   526.3  4797.4  524.75  4867.8   524.6  4922.6   525.2  4972.8  524.32
  4982.6  521.53  4984.7  518.65  4985.6  517.85  4993.8  517.85  4994.8  518.65
  5004.8  518.95  5012.2  520.92  5017.8  519.63  5027.1  522.61  5030.5  522.39
  5057.2  520.62  5062.8  522.35  5079.7  521.94  5085.3  522.41  5102.3  521.06
  5107.8  521.41  5116.1   519.8  5124.8  519.49  5138.4   523.7  5147.3  524.73
  5152.8  523.78  5182.9  525.24  5218.7  525.38  5272.6  526.68  5553.9  527.66
#Mann= 6 ,-1 , 0
  4683.5     .05       0  4867.8      .1       0  4922.6     .12       0
  4984.7     .07       0  4994.8     .12       0  5030.5     .05       0
Bank Sta=4984.7,4994.8
XS Rating Curve= 0 ,0
Exp/Cntr=0.3,0.1

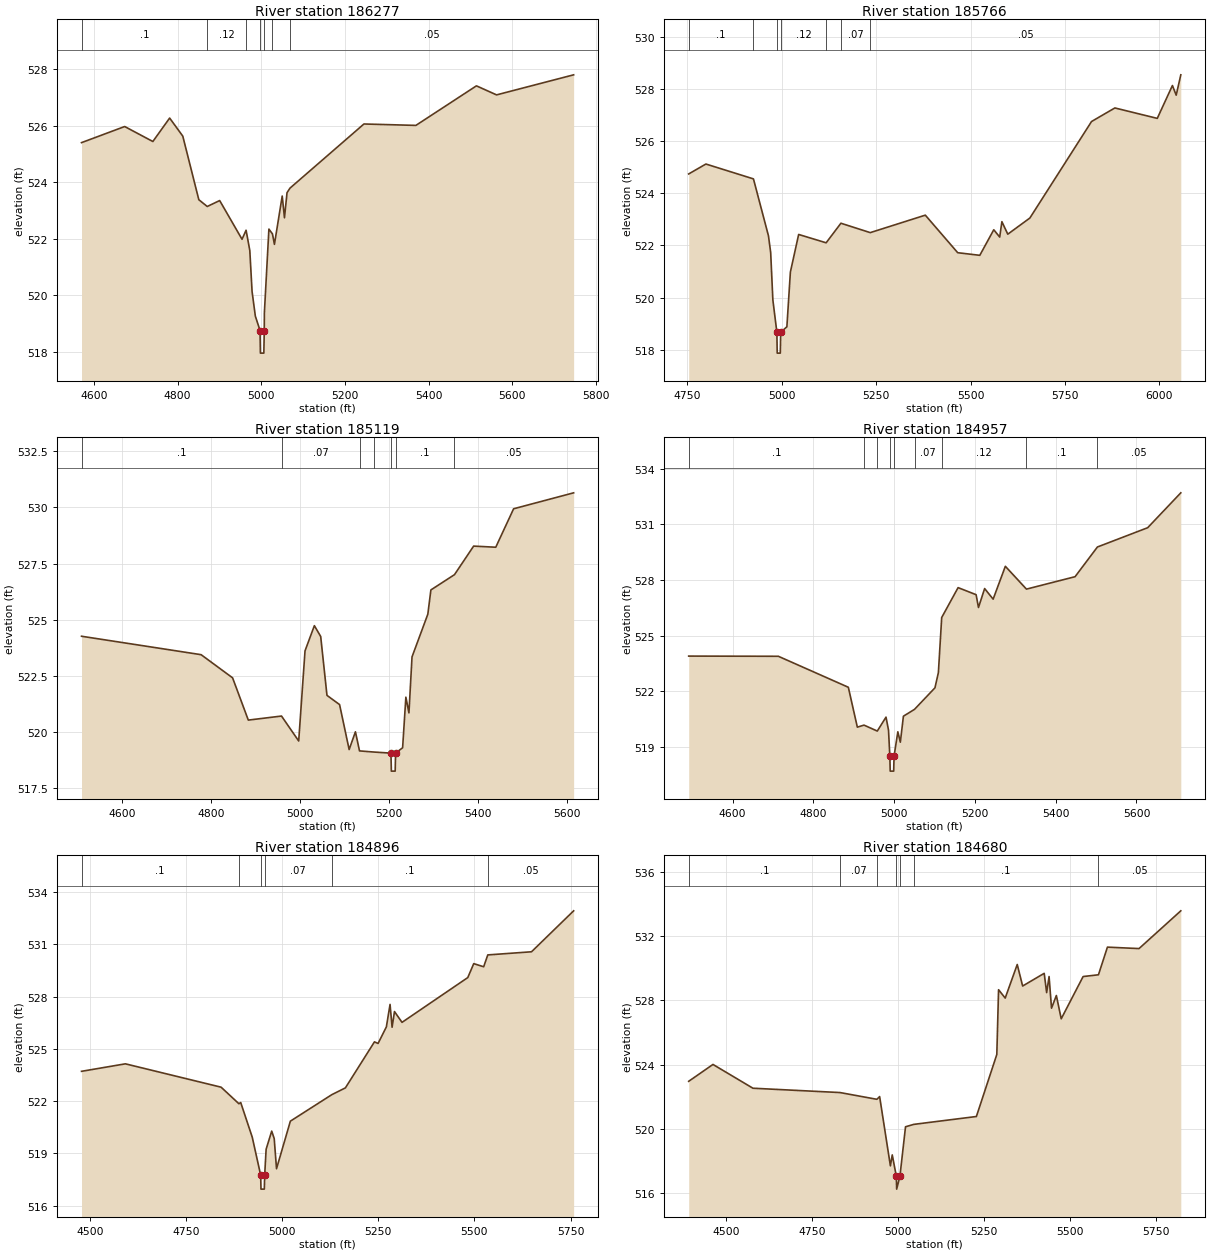
Type RM Length L Ch R = 1 ,186277  ,511,511,511
BEGIN DESCRIPTION:
Mapping XS d8708d6e
END DESCRIPTION:
XS GIS Cut Line= 4
      2023240.52      13521698.3      2023139.63     13521483.44
      2022697.24     13521302.54      2022243.44     13521378.95
#Sta/Elev= 30
  4570.7   525.4  4673.8  525.97  4741.1  525.44  4781.2  526.27  4812.6  525.63
  4850.9  523.38    4871  523.14  4900.7  523.35  4954.1  521.98  4963.8   522.3
  4972.7  521.58  4978.1  520.13  4985.9  519.26  4997.1  518.75    4998  517.95
  5006.2  517.95  5007.2  518.75  5007.5  519.38  5018.3  522.34  5026.8  522.17
  5031.5   521.8  5050.1  523.51  5055.5  522.74  5061.6  523.63  5068.7  523.79
  5245.3  526.06  5369.4  526.01    5514  527.41  5562.1  527.09  5746.2   527.8
#Mann= 7 ,-1 , 0
  4570.7      .1       0    4871     .12       0  4963.8     .05       0
  4997.1     .03       0  5007.2     .05       0  5026.8     .07       0
  5068.7     .05       0
Bank Sta=4997.1,5007.2
XS Rating Curve= 0 ,0
Exp/Cntr=0.3,0.1

Type RM Length L Ch R = 1 ,185766  ,647,647,647
BEGIN DESCRIPTION:
Mapping XS d83154af
END DESCRIPTION:
XS GIS Cut Line= 4
        2023500.     13521400.03      2023473.83     13521236.05
      2022697.24      13520776.5      2022462.83     13520789.53
#Sta/Elev= 30
  4753.3  524.74  4798.9  525.12  4924.8  524.55  4964.5  522.37  4970.4  521.73
  4976.2  519.91  4986.8  518.67  4987.7  517.87  4995.9  517.87  4996.9  518.67
  5013.3  518.88  5022.6  520.98  5044.5  522.42  5117.3   522.1  5156.4  522.85
  5234.1  522.49  5379.9  523.16  5465.7  521.72  5524.2  521.62  5561.2   522.6
  5576.9  522.32  5582.7  522.91  5598.3  522.43  5656.8  523.05  5820.1  526.75
  5881.9  527.27  5994.2  526.87  6034.3  528.13  6044.3  527.76  6056.5  528.54
#Mann= 7 ,-1 , 0
  4753.3      .1       0  4924.8     .12       0  4986.8     .07       0
  4996.9     .12       0  5117.3      .1       0  5156.4     .07       0
  5234.1     .05       0
Bank Sta=4986.8,4996.9
XS Rating Curve= 0 ,0
Exp/Cntr=0.3,0.1

Type RM Length L Ch R = 1 ,185119  ,162,162,162
BEGIN DESCRIPTION:
Mapping XS 7072a722
END DESCRIPTION:
XS GIS Cut Line= 4
      2023744.11     13521216.64      2023751.93     13521021.29
      2023254.53     13520549.94      2023030.54     13520565.57
#Sta/Elev= 30
  4508.9  524.27  4777.5  523.45  4848.2  522.42  4883.5  520.54  4958.1  520.72
  4996.7  519.61  5010.9  523.62  5031.9  524.74  5046.1  524.26  5060.2  521.64
  5088.5  521.23    5110  519.23  5124.1  520.02  5133.3  519.17    5165  519.12
  5203.9  519.07  5204.8  518.27  5213.4  518.27  5214.3  519.07  5230.1  519.31
  5237.4  521.56  5244.3  520.86  5251.2  523.35  5286.7  525.25  5293.6  526.33
  5346.6  527.01  5389.6  528.28  5439.3  528.23  5479.4  529.94  5614.2  530.65
#Mann= 7 ,-1 , 0
  4508.9      .1       0  4958.1     .07       0  5133.3     .12       0
    5165      .1       0  5203.9     .07       0  5214.3      .1       0
  5346.6     .05       0
Bank Sta=5203.9,5214.3
XS Rating Curve= 0 ,0
Exp/Cntr=0.3,0.1

Type RM Length L Ch R = 1 ,184957  ,61,61,61
BEGIN DESCRIPTION:
Mapping XS 170fc789
END DESCRIPTION:
XS GIS Cut Line= 5
      2023820.02     13521239.85        2023807.      13520949.1
      2023598.67     13520664.81      2023514.03      13520534.6
      2023118.44     13520394.09
#Sta/Elev= 30
  4491.2   523.9  4713.2  523.89  4886.5  522.22  4908.8  520.07  4925.3  520.18
  4958.2  519.86  4979.8  520.61    4986  519.91  4989.3   518.5  4990.2   517.7
  4998.8   517.7  4999.7   518.5  5009.1  519.82  5015.3  519.26  5022.9  520.66
  5050.4  521.03    5101  522.19  5109.5  523.01  5117.7  525.98  5158.3  527.59
  5202.9  527.21  5208.8  526.52    5224  527.54  5245.1  526.97  5275.3  528.74
  5327.6  527.51    5448  528.18  5503.3  529.78  5627.8  530.82  5709.8   532.7
#Mann= 9 ,-1 , 0
  4491.2      .1       0  4925.3     .07       0  4958.2     .12       0
  4989.3     .07       0  4999.7     .12       0  5050.4     .07       0
  5117.7     .12       0  5327.6      .1       0  5503.3     .05       0
Bank Sta=4989.3,4999.7
XS Rating Curve= 0 ,0
Exp/Cntr=0.3,0.1

Type RM Length L Ch R = 1 ,184896  ,216,216,216
BEGIN DESCRIPTION:
Mapping XS 1cea3bbb
END DESCRIPTION:
XS GIS Cut Line= 5
      2023846.06     13521229.09      2023843.89     13520914.38
      2023659.43     13520638.77      2023631.22     13520523.75
      2023145.14     13520354.49
#Sta/Elev= 30
  4478.6  523.71  4592.7  524.14  4841.5   522.8  4887.8  521.85  4892.5  521.92
  4922.5  519.93  4944.4  517.75  4945.2  516.95  4953.9  516.95  4954.8  517.75
  4958.6  519.24  4973.1  520.28  4979.6  519.85  4985.6  518.12  5021.6  520.85
  5129.3  522.37  5164.7  522.76  5240.2   525.4  5249.7  525.31  5271.2  526.26
  5280.8  527.55  5286.1  526.24  5292.3  527.14  5311.9  526.52  5482.9  529.09
  5498.4  529.89  5524.2  529.71  5534.9  530.39  5648.6  530.57  5758.1  532.92
#Mann= 6 ,-1 , 0
  4478.6      .1       0  4887.8     .07       0  4944.4     .07       0
  4954.8     .07       0  5129.3      .1       0  5534.9     .05       0
Bank Sta=4944.4,4954.8
XS Rating Curve= 0 ,0
Exp/Cntr=0.3,0.1

Type RM Length L Ch R = 1 ,184680  ,993,993,993
BEGIN DESCRIPTION:
Mapping XS c6794dc9
END DESCRIPTION:
XS GIS Cut Line= 5
      2023936.13     13521240.04      2024059.22     13521003.06
      2023862.76     13520506.64      2023670.05     13520472.79
      2023362.72     13520165.47
#Sta/Elev= 30
  4390.4  522.97    4461  524.02  4577.2  522.54  4830.4  522.27  4937.7  521.85
  4945.7  522.02    4977  517.71  4982.4  518.39  4994.3  517.06  4995.2  516.26
  5004.7  517.06    5021  520.14  5045.1  520.29  5227.1  520.78  5286.5  524.64
  5291.6  528.67  5310.9  528.15  5345.9  530.24  5361.6   528.9  5424.3  529.69
  5431.4  528.49  5438.5  529.49  5445.6  527.52  5459.7  528.31  5473.8  526.86
  5537.5  529.49  5582.1   529.6  5608.2  531.32  5700.1  531.23  5821.6  533.58
#Mann= 7 ,-1 , 0
  4390.4      .1       0  4830.4     .07       0  4937.7     .12       0
  4994.3     .07       0  5004.7     .12       0  5045.1      .1       0
  5582.1     .05       0
Bank Sta=4994.3,5004.7
XS Rating Curve= 0 ,0
Exp/Cntr=0.3,0.1

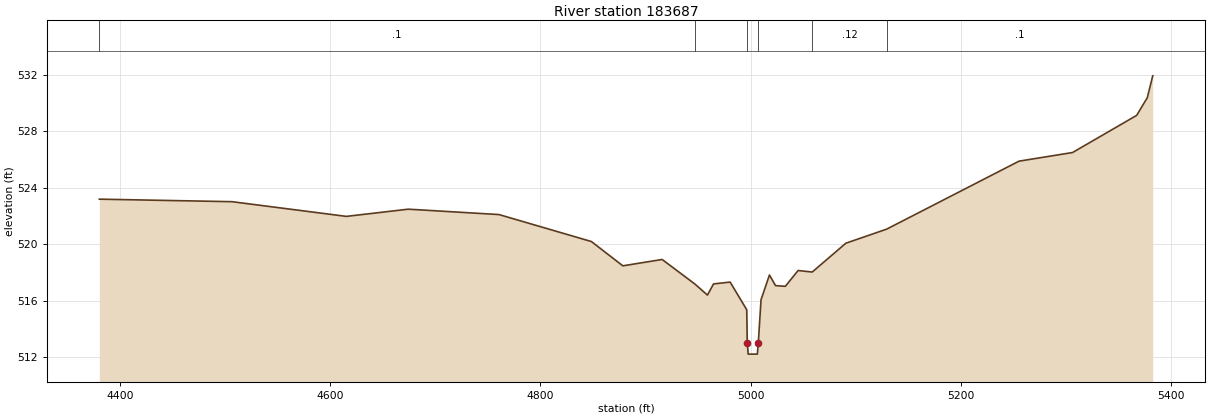
Type RM Length L Ch R = 1 ,183687  ,344,344,344
BEGIN DESCRIPTION:
Mapping XS 49271228
END DESCRIPTION:
XS GIS Cut Line= 4
      2024161.79     13521196.68      2024314.43       13521089.
      2024626.93     13520544.73      2024593.09     13520359.91
#Sta/Elev= 30
  4380.4  523.18  4506.7     523  4615.4  521.96  4674.3  522.47  4760.6  522.09
  4848.6  520.18  4878.5  518.46  4915.9  518.91  4947.1  517.17    4959  516.39
  4964.8  517.18  4980.6  517.31  4996.4  515.35  4996.9  513.01  4997.8  512.21
  5006.5  512.21  5007.4  513.01    5010  516.06    5018  517.81  5023.8  517.06
  5033.1  517.01  5045.3  518.13  5058.7  518.02  5090.7  520.06  5129.6  521.06
  5255.5  525.87  5306.4  526.48  5367.4  529.11  5377.5  530.36  5382.7  531.91
#Mann= 6 ,-1 , 0
  4380.4      .1       0  4947.1     .07       0  4996.9     .07       0
  5007.4     .07       0  5058.7     .12       0  5129.6      .1       0
Bank Sta=4996.9,5007.4
XS Rating Curve= 0 ,0
Exp/Cntr=0.3,0.1