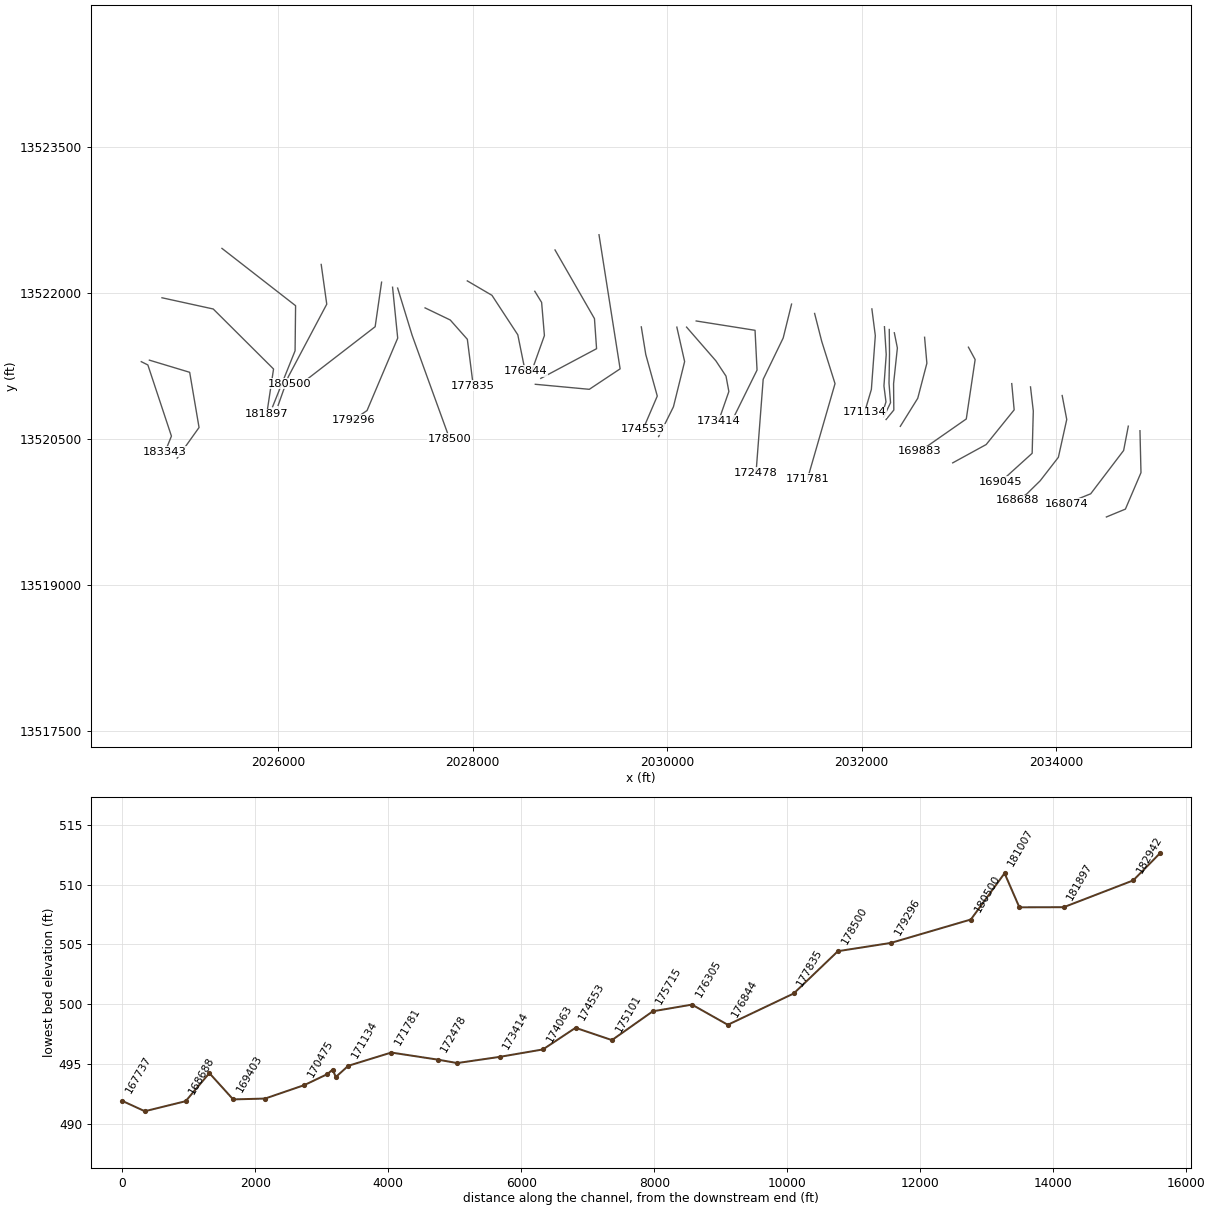
HEC-RAS study LAGUNILLAS Cr.prj: LAGUNILLAS Cr Base Level Engineering

--- LAGUNILLAS Cr.g01 (geometry) --- (continued)

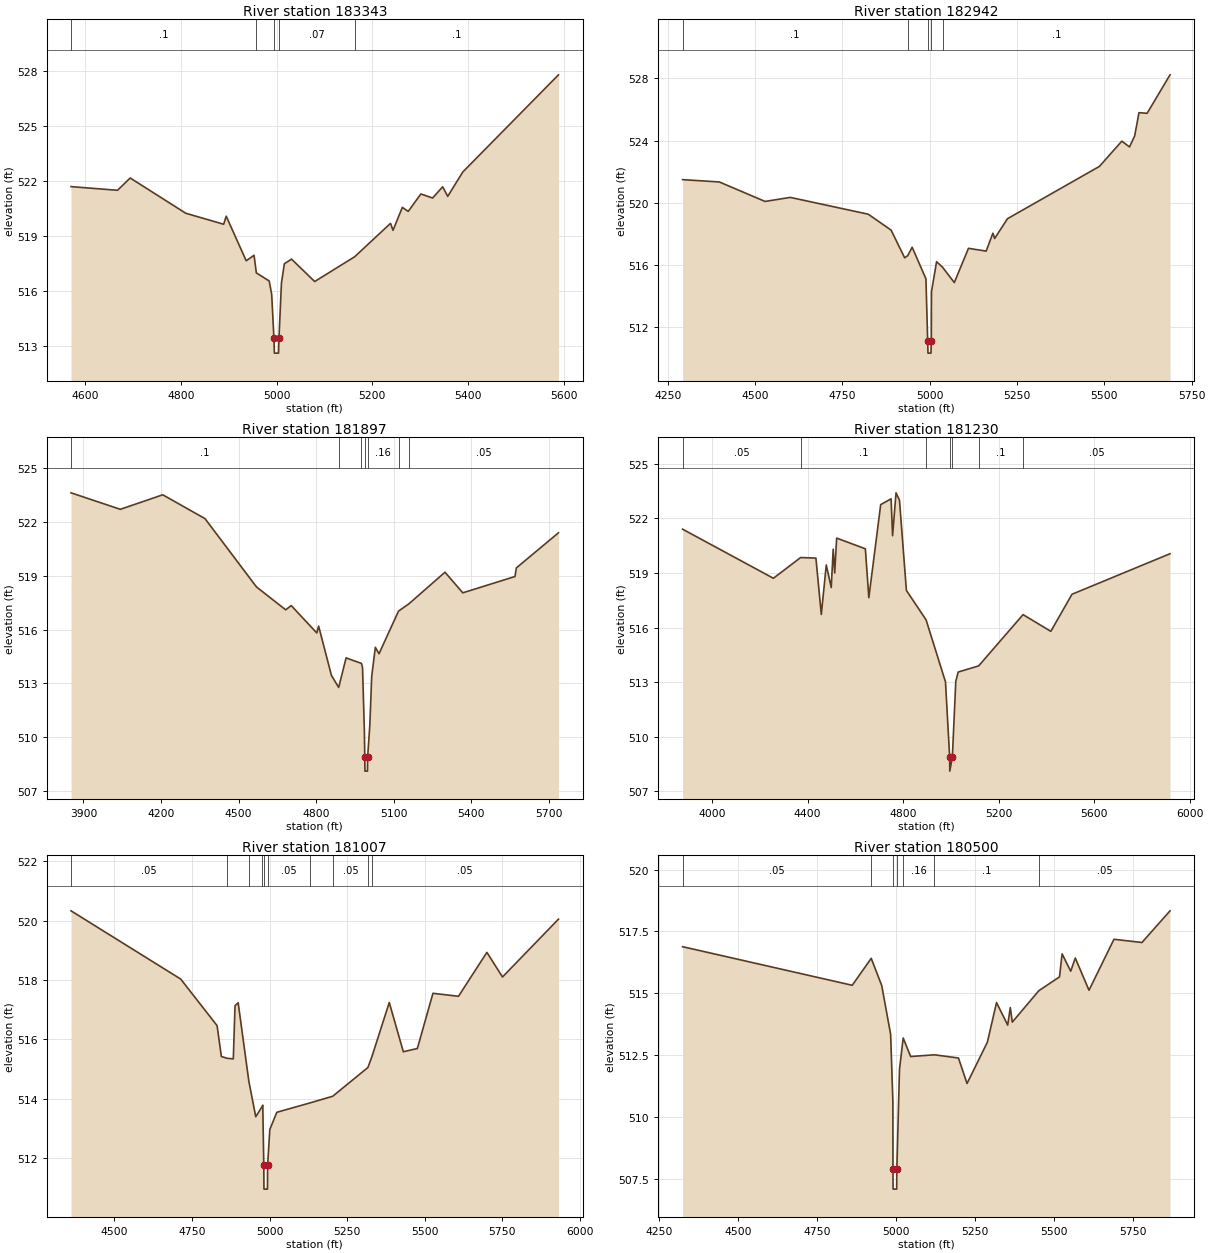
Type RM Length L Ch R = 1 ,183343  ,401,401,401
BEGIN DESCRIPTION:
Mapping XS bdb55ac2
END DESCRIPTION:
XS GIS Cut Line= 4
      2024595.66     13521294.74      2024663.39     13521260.88
      2024905.57     13520529.11      2024840.96     13520368.87
#Sta/Elev= 30
    4570  521.68  4667.2  521.48  4693.7  522.15  4809.9  520.23  4889.2  519.63
  4894.5  520.07  4936.3  517.64  4952.7  517.94  4957.5  516.98  4984.4  516.54
  4989.6  515.81  4994.3  513.41  4995.2  512.61  5003.9  512.61  5004.8  513.41
    5010  516.43  5016.1  517.48  5031.1  517.73  5079.5  516.51  5163.1  517.86
  5238.1  519.68  5243.3   519.3  5262.8  520.55  5275.1  520.33  5301.5  521.28
  5326.1  521.06  5347.1  521.67  5357.7  521.15  5389.3  522.48  5589.3  527.77
#Mann= 5 ,-1 , 0
    4570      .1       0  4957.5     .07       0  4994.3     .07       0
  5004.8     .07       0  5163.1      .1       0
Bank Sta=4994.3,5004.8
XS Rating Curve= 0 ,0
Exp/Cntr=0.3,0.1

Type RM Length L Ch R = 1 ,182942  ,1045,1045,1045
BEGIN DESCRIPTION:
Mapping XS 996f07fb
END DESCRIPTION:
XS GIS Cut Line= 4
      2024679.02     13521310.35      2025093.07     13521185.36
      2025189.43     13520617.65      2024964.76     13520302.58
#Sta/Elev= 30
  4292.8  521.49  4398.1  521.34  4528.9  520.09  4601.1  520.35  4824.2  519.27
  4889.6  518.25  4928.5  516.47  4937.3  516.61  4949.9  517.15  4989.4  515.12
  4994.3  511.15  4995.2  510.35  5003.9  510.35  5004.8  511.15  5005.2  514.28
  5019.8  516.22  5036.8  515.87  5070.6  514.88  5111.1  517.08  5161.8   516.9
    5181  518.05  5186.1  517.71  5222.7  518.98    5486  522.34    5550  523.96
  5572.1  523.59  5586.8  524.29  5599.2  525.79  5622.5  525.75  5688.1  528.22
#Mann= 5 ,-1 , 0
  4292.8      .1       0  4937.3     .12       0  4994.3     .07       0
  5004.8     .12       0  5036.8      .1       0
Bank Sta=4994.3,5004.8
XS Rating Curve= 0 ,0
Exp/Cntr=0.3,0.1

Type RM Length L Ch R = 1 ,181897  ,667,667,667
BEGIN DESCRIPTION:
Mapping XS 2c031d4a
END DESCRIPTION:
XS GIS Cut Line= 4
      2024808.54     13521951.87      2025335.26      13521836.4
      2025955.05     13521219.21       2025884.9     13520753.98
#Sta/Elev= 30
  3852.3  523.64  4042.9  522.72    4207  523.53  4370.2   522.2  4569.1  518.39
  4682.2  517.11  4703.4  517.35  4802.4  515.82  4809.5   516.2    4859  513.45
    4887  512.78  4915.6  514.43  4975.1  514.12  4979.2  513.89  4986.3  510.34
  4987.8  508.91  4988.5  508.11  4998.3  508.11    4999  508.91  5007.5  510.71
  5014.6  513.39  5028.7  515.02  5042.9  514.66  5118.3  517.04    5158  517.44
  5297.9  519.21  5366.8  518.06  5568.6  518.97  5573.9  519.45  5736.7  521.41
#Mann= 7 ,-1 , 0
  3852.3      .1       0    4887     .12       0  4975.1     .16       0
  4987.8     .07       0    4999     .16       0  5118.3      .1       0
    5158     .05       0
Bank Sta=4987.8,4999
XS Rating Curve= 0 ,0
Exp/Cntr=0.3,0.1

Type RM Length L Ch R = 1 ,181230  ,223,223,223
BEGIN DESCRIPTION:
Mapping XS 3c1bd2e3
END DESCRIPTION:
XS GIS Cut Line= 4
      2025424.85     13522459.67      2026181.62     13521870.25
      2026176.41     13521406.71      2025945.67      13520832.1
#Sta/Elev= 30
  3876.3  521.41  4256.7  518.71  4370.8  519.85  4434.8  519.82  4457.4  516.72
  4478.2  519.44    4499   518.2  4507.2  520.31  4513.5     519  4521.7  520.92
    4642  520.33  4656.5  517.64  4706.2  522.76  4749.7  523.08    4756  521.05
  4770.5  523.41  4784.9     523  4813.9  518.04  4896.4  516.42  4977.6  513.01
    4995   508.9  4995.7   508.1  5006.5   508.9  5020.8  513.04  5030.8  513.55
  5116.6  513.89  5302.6  516.71  5418.9  515.79  5507.6  517.83  5918.3  520.06
#Mann= 7 ,-1 , 0
  3876.3     .05       0  4370.8      .1       0  4896.4     .16       0
    4995     .07       0  5006.5     .16       0  5116.6      .1       0
  5302.6     .05       0
Bank Sta=4995,5006.5
XS Rating Curve= 0 ,0
Exp/Cntr=0.3,0.1

Type RM Length L Ch R = 1 ,181007  ,507,507,507
BEGIN DESCRIPTION:
Mapping XS e9826c00
END DESCRIPTION:
XS GIS Cut Line= 4
      2026444.79     13522294.76      2026501.93     13521885.88
       2026106.1     13521138.48      2026002.07     13520845.08
#Sta/Elev= 30
  4360.7  520.33  4713.9  518.03  4831.1  516.46  4844.9  515.42  4863.1  515.36
  4883.3  515.34  4888.9  517.13    4899  517.23  4933.3  514.59  4955.6  513.39
  4976.6  513.74  4978.2  513.78  4981.5  511.75    4982  510.95  4993.3  510.95
  4993.8  511.75  5000.9  512.96  5023.5  513.54  5131.7  513.86  5203.4  514.08
  5316.9  515.05  5330.2  515.43  5385.6  517.24  5430.9  515.58  5476.1  515.69
  5526.3  517.55  5608.6  517.45    5700  518.93  5750.3   518.1  5930.6  520.05
#Mann= 10 ,-1 , 0
  4360.7     .05       0  4863.1      .1       0  4933.3     .08       0
  4976.6     .05       0  4981.5     .04       0  4993.8     .05       0
  5131.7     .08       0  5203.4     .05       0  5316.9     .08       0
  5330.2     .05       0
Bank Sta=4981.5,4993.8
XS Rating Curve= 0 ,0
Exp/Cntr=0.3,0.1

Type RM Length L Ch R = 1 ,180500  ,1204,1204,1204
BEGIN DESCRIPTION:
Mapping XS 430350d4
END DESCRIPTION:
XS GIS Cut Line= 4
      2027065.45     13522112.45      2026999.32     13521654.11
      2026244.12     13521070.77      2026119.59     13521068.18
#Sta/Elev= 30
  4324.4  516.88    4861  515.32  4921.1  516.41  4954.3  515.31  4982.5  513.34
  4989.7  510.57  4989.8  507.88  4990.3  507.08  5001.6  507.08  5002.1  507.88
  5010.5  511.92  5022.2  513.19  5045.8  512.44    5121  512.51  5197.1  512.38
  5224.2  511.35  5288.5  513.02  5317.5  514.62  5352.8  513.71    5361  514.42
  5367.3  513.83  5451.2   515.1  5516.7  515.66  5524.9  516.59  5552.1  515.89
  5566.6  516.42    5610  515.12  5688.9  517.18  5777.4  517.05  5866.3  518.33
#Mann= 7 ,-1 , 0
  4324.4     .05       0  4921.1      .1       0  4989.8     .07       0
  5002.1      .1       0  5022.2     .16       0    5121      .1       0
  5451.2     .05       0
Bank Sta=4989.8,5002.1
XS Rating Curve= 0 ,0
Exp/Cntr=0.3,0.1

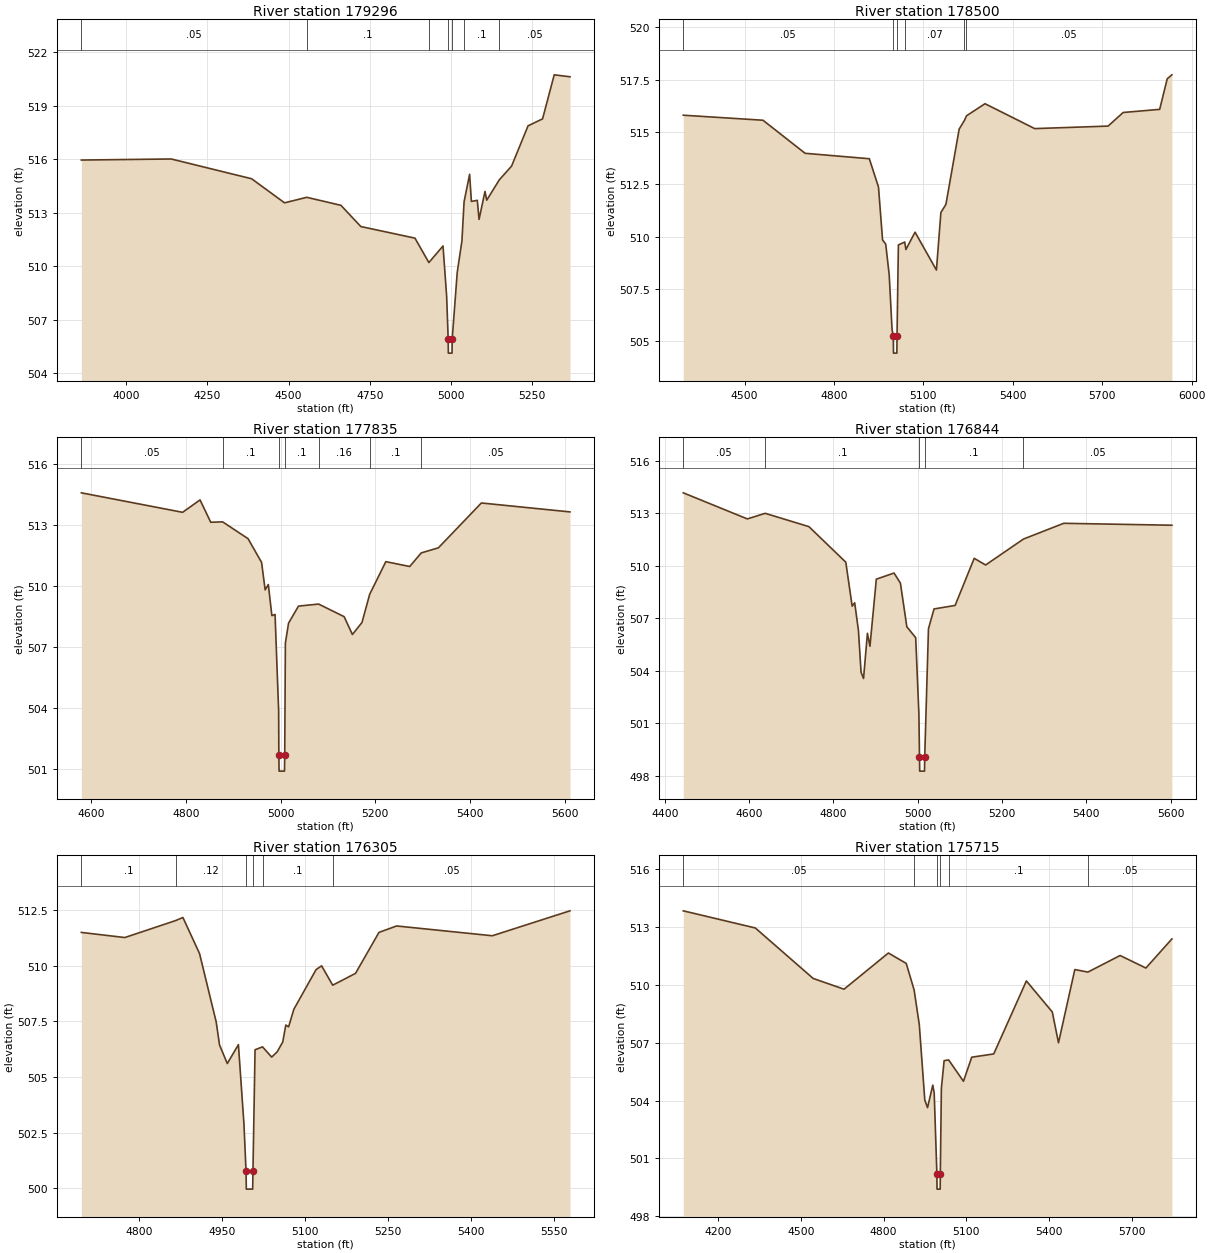
Type RM Length L Ch R = 1 ,179296  ,796,796,796
BEGIN DESCRIPTION:
Mapping XS ec24b5b5
END DESCRIPTION:
XS GIS Cut Line= 4
      2027178.29     13522060.42       2027231.1     13521536.92
      2026915.99     13520792.13      2026775.39     13520695.79
#Sta/Elev= 30
  3861.4  515.95  4138.2  516.01    4386   514.9  4487.4  513.55  4555.9  513.86
  4661.1  513.41  4722.4  512.22  4889.1  511.57    4932   510.2  4975.6  511.13
  4986.8   508.3  4991.5  505.92    4992  505.12  5003.4  505.12  5003.9  505.92
  5019.4  509.65  5033.8  511.41  5040.5  513.61  5057.5  515.15    5063  513.63
  5081.2  513.69  5086.6  512.62  5104.9  514.19  5110.3   513.7    5149  514.84
  5186.8  515.61  5237.6  517.87  5282.3  518.26  5318.2  520.73  5366.7  520.62
#Mann= 7 ,-1 , 0
  3861.4     .05       0  4555.9      .1       0    4932     .12       0
  4991.5     .07       0  5003.9     .12       0  5040.5      .1       0
    5149     .05       0
Bank Sta=4991.5,5003.9
XS Rating Curve= 0 ,0
Exp/Cntr=0.3,0.1

Type RM Length L Ch R = 1 ,178500  ,665,665,665
BEGIN DESCRIPTION:
Mapping XS 19418746
END DESCRIPTION:
XS GIS Cut Line= 4
      2027230.38     13522051.71      2027379.53     13521565.56
      2027538.39     13521125.46      2027764.23     13520502.23
#Sta/Elev= 30
  4294.4   515.8  4561.8  515.56  4703.2  513.98  4918.6  513.72  4949.3  512.37
    4963  509.84  4973.6  509.64  4985.3  508.17  4994.9  505.55  4999.1  505.23
  4999.6  504.43    5011  504.43  5011.5  505.23  5016.1   509.6  5037.4  509.74
  5041.3  509.38    5072  510.21  5143.7   508.4  5158.7  511.15  5175.6  511.54
  5220.1  515.14  5237.7  515.55  5244.6  515.77  5306.7  516.35  5473.4  515.16
  5719.6  515.28  5770.2  515.93  5892.7  516.08    5918  517.54  5933.7  517.73
#Mann= 6 ,-1 , 0
  4294.4     .05       0  4999.1     .03       0  5011.5     .05       0
  5037.4     .07       0  5237.7      .1       0  5244.6     .05       0
Bank Sta=4999.1,5011.5
XS Rating Curve= 0 ,0
Exp/Cntr=0.3,0.1

Type RM Length L Ch R = 1 ,177835  ,991,991,991
BEGIN DESCRIPTION:
Mapping XS 5ee34f5c
END DESCRIPTION:
XS GIS Cut Line= 4
      2027512.47     13521847.72       2027771.1     13521723.26
      2027946.88     13521524.69      2028007.24     13521049.52
#Sta/Elev= 30
  4579.5   514.6  4793.2  513.64    4830  514.25  4852.6  513.15  4877.7  513.17
  4931.4  512.34  4959.9  511.17  4967.4  509.82  4974.1  510.08  4981.6  508.55
  4988.3  508.61  4995.9  503.85  4996.3  501.69  4996.8  500.89  5008.2  500.89
  5008.7  501.69  5010.1   507.2  5016.8  508.18  5037.8  509.02  5080.2  509.12
  5134.1   508.5  5151.5  507.62  5171.7  508.21    5188   509.6  5222.1  511.21
  5272.5  510.97  5296.8  511.64    5333  511.89  5423.7   514.1  5610.7  513.66
#Mann= 7 ,-1 , 0
  4579.5     .05       0  4877.7      .1       0  4996.3     .07       0
  5008.7      .1       0  5080.2     .16       0    5188      .1       0
  5296.8     .05       0
Bank Sta=4996.3,5008.7
XS Rating Curve= 0 ,0
Exp/Cntr=0.3,0.1

Type RM Length L Ch R = 1 ,176844  ,539,539,539
BEGIN DESCRIPTION:
Mapping XS 5eb6b1b6
END DESCRIPTION:
XS GIS Cut Line= 4
      2027946.51      13522125.5      2028199.85     13521977.02
      2028465.47     13521570.77      2028540.81     13521198.34
#Sta/Elev= 30
  4443.8  514.16  4595.8  512.67    4638  512.99  4741.8  512.23  4829.3   510.2
  4844.4  507.69  4850.4  507.88  4859.3   506.3  4865.5  503.92  4871.4  503.56
  4880.6  506.14  4886.6   505.4  4901.7  509.23  4943.8  509.58  4958.9     509
  4974.1  506.51  4995.1  505.89  5002.7  501.53  5004.1  499.07  5004.6  498.27
    5016  498.27  5016.5  499.07  5025.4   506.4  5038.6  507.53  5088.6  507.73
  5133.9  510.42    5161  510.04  5250.7  511.52  5346.3  512.42  5602.8  512.31
#Mann= 5 ,-1 , 0
  4443.8     .05       0    4638      .1       0  5004.1     .07       0
  5016.5      .1       0  5250.7     .05       0
Bank Sta=5004.1,5016.5
XS Rating Curve= 0 ,0
Exp/Cntr=0.3,0.1

Type RM Length L Ch R = 1 ,176305  ,590,590,590
BEGIN DESCRIPTION:
Mapping XS 7c709fdb
END DESCRIPTION:
XS GIS Cut Line= 4
      2028639.95     13522018.69      2028710.26     13521904.11
      2028738.91     13521562.96      2028602.03     13521179.65
#Sta/Elev= 30
  4695.4  511.49    4774  511.26  4865.7  512.02  4879.1  512.16  4909.2  510.54
  4939.3  507.47  4945.3  506.44  4959.4   505.6  4979.5  506.45  4989.5  502.89
  4993.3  500.76  4993.8  499.96  5005.3  499.96  5005.8  500.76  5009.6  506.22
  5023.1  506.35  5039.7  505.89  5049.7  506.13  5059.7  506.57  5065.2  507.33
  5070.3  507.25  5079.8  508.04    5120  509.82    5130  509.99    5150  509.12
  5191.3  509.65  5233.7  511.49  5265.6  511.78  5438.7  511.34  5579.2  512.46
#Mann= 6 ,-1 , 0
  4695.4      .1       0  4865.7     .12       0  4993.3     .07       0
  5005.8     .12       0  5023.1      .1       0    5150     .05       0
Bank Sta=4993.3,5005.8
XS Rating Curve= 0 ,0
Exp/Cntr=0.3,0.1

Type RM Length L Ch R = 1 ,175715  ,614,614,614
BEGIN DESCRIPTION:
Mapping XS da6f4f29
END DESCRIPTION:
XS GIS Cut Line= 4
      2028847.97      13522443.5       2029253.3     13521737.36
        2029275.     13521428.12       2028701.7     13521122.87
#Sta/Elev= 30
  4072.7  513.85  4334.2  512.96  4544.1  510.34  4656.3  509.78  4817.3  511.66
  4882.1  511.12  4910.7  509.74  4929.4  507.95  4949.4  504.03  4959.4  503.63
  4978.5   504.8  4983.6  504.39  4993.3   500.2  4993.8   499.4  5005.3   499.4
  5005.8   500.2  5009.6  504.63  5019.6  506.07  5035.9  506.11  5089.8     505
  5119.8  506.25  5199.7  506.42  5318.2  510.21  5412.2   508.6  5434.8     507
    5494   510.8  5541.6  510.67  5658.4  511.53    5752  510.88  5846.4  512.39
#Mann= 6 ,-1 , 0
  4072.7     .05       0  4910.7     .16       0  4993.3     .07       0
  5005.8     .16       0  5035.9      .1       0  5541.6     .05       0
Bank Sta=4993.3,5005.8
XS Rating Curve= 0 ,0
Exp/Cntr=0.3,0.1

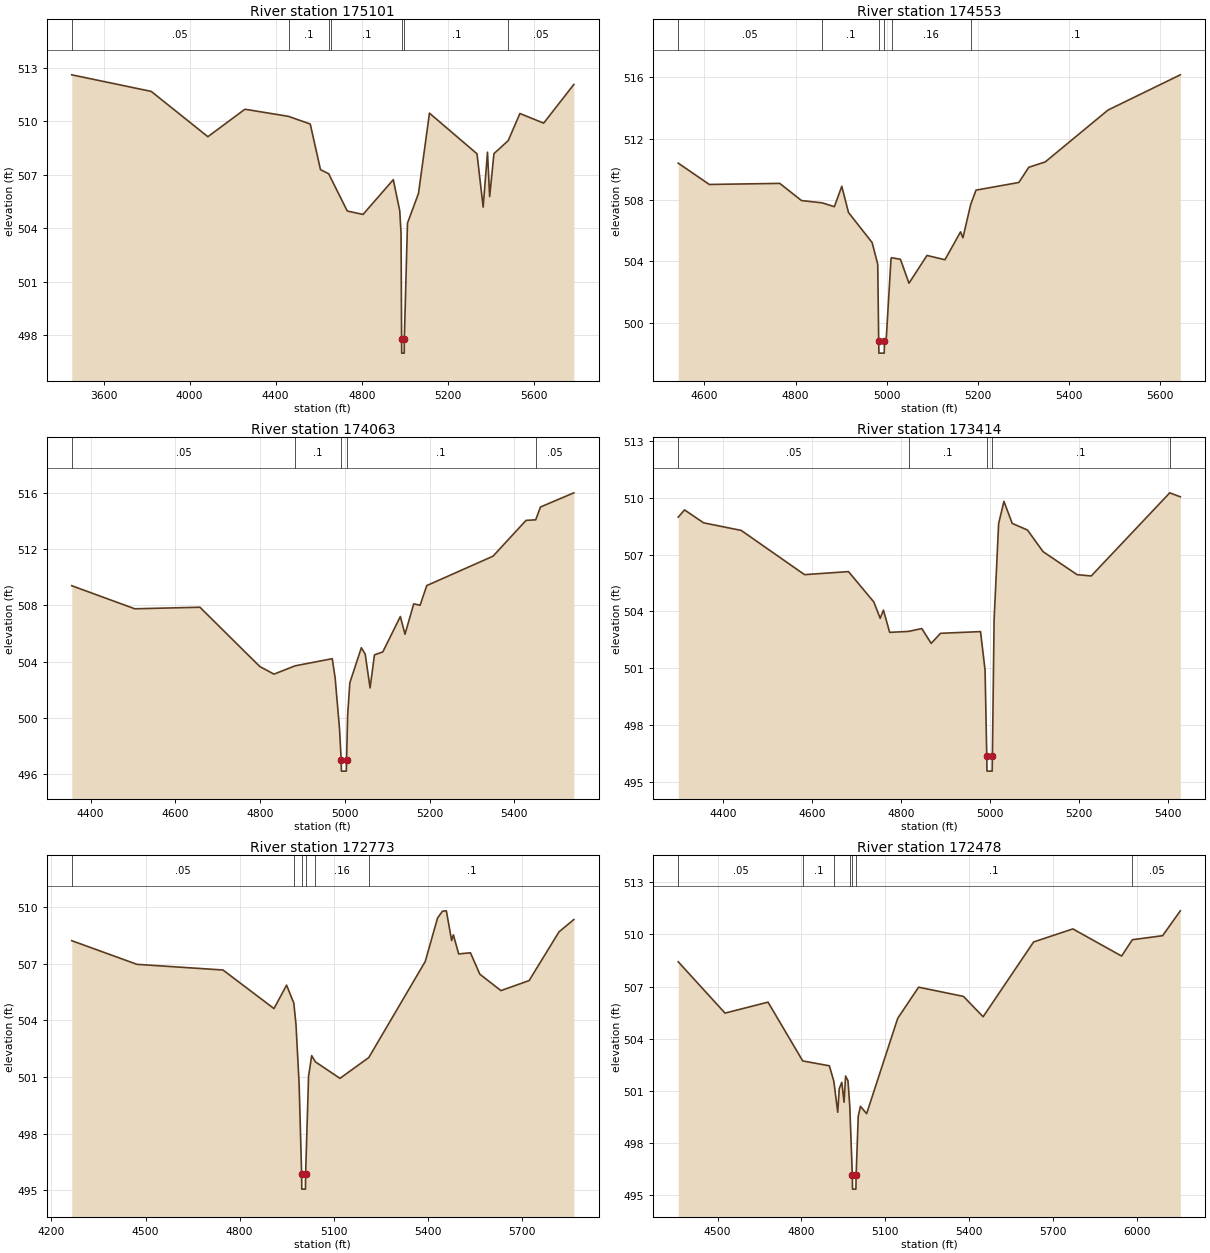
Type RM Length L Ch R = 1 ,175101  ,548,548,548
BEGIN DESCRIPTION:
Mapping XS 76bf0a0a
END DESCRIPTION:
XS GIS Cut Line= 4
        2029300.     13522600.03      2029516.97     13521220.87
      2029200.13     13521010.37      2028645.35     13521062.11
#Sta/Elev= 30
  3452.4   512.6  3821.9  511.67  4085.1  509.13  4257.2  510.67  4459.9  510.27
  4560.9  509.84  4608.5  507.28  4646.9  507.05    4659  506.75    4733  504.96
  4806.3  504.77  4946.9  506.72  4976.8  504.98  4982.9  503.74  4985.5  497.79
    4986  496.99  4997.7  496.99  4998.2  497.79  5012.8  504.28    5064  505.95
    5115  510.45  5336.1  508.17  5364.6  505.18  5384.7  508.26  5394.8  505.77
  5414.8  508.18  5481.1  508.91  5535.4  510.43  5645.8  509.89  5786.1  512.06
#Mann= 7 ,-1 , 0
  3452.4     .05       0  4459.9      .1       0  4646.9     .05       0
    4659      .1       0  4985.5     .07       0  4998.2      .1       0
  5481.1     .05       0
Bank Sta=4985.5,4998.2
XS Rating Curve= 0 ,0
Exp/Cntr=0.3,0.1

Type RM Length L Ch R = 1 ,174553  ,490,490,490
BEGIN DESCRIPTION:
Mapping XS cda40f9c
END DESCRIPTION:
XS GIS Cut Line= 4
      2029734.72     13521652.39      2029780.64     13521368.44
      2029898.92     13520940.92      2029752.56     13520598.83
#Sta/Elev= 30
  4542.3  510.41  4610.6  509.02  4765.4  509.09  4813.2  507.97  4858.7  507.82
  4885.4  507.57  4901.7   508.9  4916.5  507.19  4968.4  505.23  4980.7  503.82
  4982.8  498.82  4983.3  498.02    4995  498.02  4995.5  498.82  4999.5     499
  5009.9  504.19  5011.3  504.24  5030.6  504.14  5049.4  502.58  5088.9  504.39
  5128.4  504.11  5162.7  505.93  5167.9  505.54    5185  507.72  5196.7  508.65
  5290.8  509.15  5312.6  510.14  5348.8  510.49  5486.6  513.87  5645.6  516.17
#Mann= 6 ,-1 , 0
  4542.3     .05       0  4858.7      .1       0  4982.8     .07       0
  4995.5      .1       0  5011.3     .16       0    5185      .1       0
Bank Sta=4982.8,4995.5
XS Rating Curve= 0 ,0
Exp/Cntr=0.3,0.1

Type RM Length L Ch R = 1 ,174063  ,649,649,649
BEGIN DESCRIPTION:
Mapping XS e1c43933
END DESCRIPTION:
XS GIS Cut Line= 4
        2030100.       13521650.      2030179.95     13521295.74
      2030064.93     13520830.25      2029912.69     13520523.96
#Sta/Elev= 30
  4355.7   509.4  4504.4  507.76  4658.1  507.87  4799.5  503.65  4832.9  503.11
  4882.4   503.7  4970.4  504.21  4977.2  502.83  4987.5  499.22  4991.4  497.01
  4991.9  496.21  5003.6  496.21  5004.1  497.01  5006.7  500.21  5011.8  502.49
    5039  504.99  5048.1  504.53  5059.6  502.13  5069.9  504.48  5089.6  504.69
    5131  507.21    5142  505.95  5162.6  508.11  5177.6  508.01  5193.3  509.41
  5349.6   511.5  5427.6  514.05  5450.4  514.09  5461.6     515  5540.4  516.01
#Mann= 5 ,-1 , 0
  4355.7     .05       0  4882.4      .1       0  4991.4     .07       0
  5004.1      .1       0  5450.4     .05       0
Bank Sta=4991.4,5004.1
XS Rating Curve= 0 ,0
Exp/Cntr=0.3,0.1

Type RM Length L Ch R = 1 ,173414  ,641,641,641
BEGIN DESCRIPTION:
Mapping XS e2d57063
END DESCRIPTION:
XS GIS Cut Line= 5
      2030200.01     13521649.99      2030501.13     13521303.34
       2030605.3       13521146.      2030634.59     13520987.58
      2030529.49     13520685.94
#Sta/Elev= 30
  4299.8  508.97    4314  509.35  4356.8  508.67  4441.3  508.27  4583.7  505.94
  4682.5   506.1  4739.4   504.5  4753.7  503.64    4761  504.07    4775   502.9
  4817.5  502.95  4847.2   503.1  4868.3  502.32  4889.3  502.85  4979.2  502.94
  4989.4  500.91  4993.2  496.39  4993.7  495.59  5005.4  495.59  5005.9  496.39
  5009.7  503.56  5019.9  508.63  5031.8   509.8  5050.4  508.64  5084.7  508.29
  5119.8  507.15  5196.2  505.94    5228  505.87  5404.5  510.25  5428.2  510.04
#Mann= 5 ,-1 , 0
  4299.8     .05       0  4817.5      .1       0  4993.2     .07       0
  5005.9      .1       0  5404.5     .05       0
Bank Sta=4993.2,5005.9
XS Rating Curve= 0 ,0
Exp/Cntr=0.3,0.1

Type RM Length L Ch R = 1 ,172773  ,295,295,295
BEGIN DESCRIPTION:
Mapping XS 4a2557e9
END DESCRIPTION:
XS GIS Cut Line= 4
      2030298.92     13521713.17      2030903.66     13521617.29
      2030924.27     13521208.22      2030668.18     13520689.47
#Sta/Elev= 30
  4264.8  508.21  4472.5  506.96  4746.8  506.66  4909.4  504.62  4949.5  505.86
  4972.6  504.91  4979.5  503.79  4989.5  500.64  4997.5  495.87    4998  495.07
  5009.7  495.07  5010.2  495.87  5019.6  501.04  5029.6  502.13  5041.5   501.8
  5119.7  500.93  5211.6  502.03  5391.5  507.11  5430.8  509.41  5446.4  509.77
  5458.8  509.79  5475.7  508.22  5481.2  508.52  5498.1  507.51  5535.6  507.57
  5565.5  506.44  5632.8  505.57  5722.6   506.1    5818  508.68  5865.2  509.33
#Mann= 6 ,-1 , 0
  4264.8     .05       0  4972.6      .1       0  4997.5     .07       0
  5010.2      .1       0  5041.5     .16       0  5211.6      .1       0
Bank Sta=4997.5,5010.2
XS Rating Curve= 0 ,0
Exp/Cntr=0.3,0.1

Type RM Length L Ch R = 1 ,172478  ,697,697,697
BEGIN DESCRIPTION:
Mapping XS d26213fa
END DESCRIPTION:
XS GIS Cut Line= 4
        2031279.     13521886.79      2031193.15     13521538.73
      2030987.33     13521113.33      2030913.93      13520151.9
#Sta/Elev= 30
  4359.6  508.43  4526.9  505.48  4680.7  506.11  4804.8  502.73    4900  502.45
    4916  501.56  4929.9  499.78  4935.4  501.14  4944.4   501.5  4952.5  500.36
    4958  501.86  4966.6  501.59    4973  500.13  4982.1  496.16  4982.8  495.36
  4994.9  495.36  4995.7  496.16  5003.2  499.54  5011.1  500.12  5033.3   499.7
  5144.4  505.18  5219.1  506.97  5379.5  506.44  5449.8  505.27  5630.3  509.57
  5770.7  510.32    5945  508.76  5983.4   509.7  6091.6  509.93  6154.9  511.36
#Mann= 7 ,-1 , 0
  4359.6     .05       0  4804.8      .1       0    4916     .16       0
    4973      .1       0  4982.1     .07       0  4995.7      .1       0
  5983.4     .05       0
Bank Sta=4982.1,4995.7
XS Rating Curve= 0 ,0
Exp/Cntr=0.3,0.1

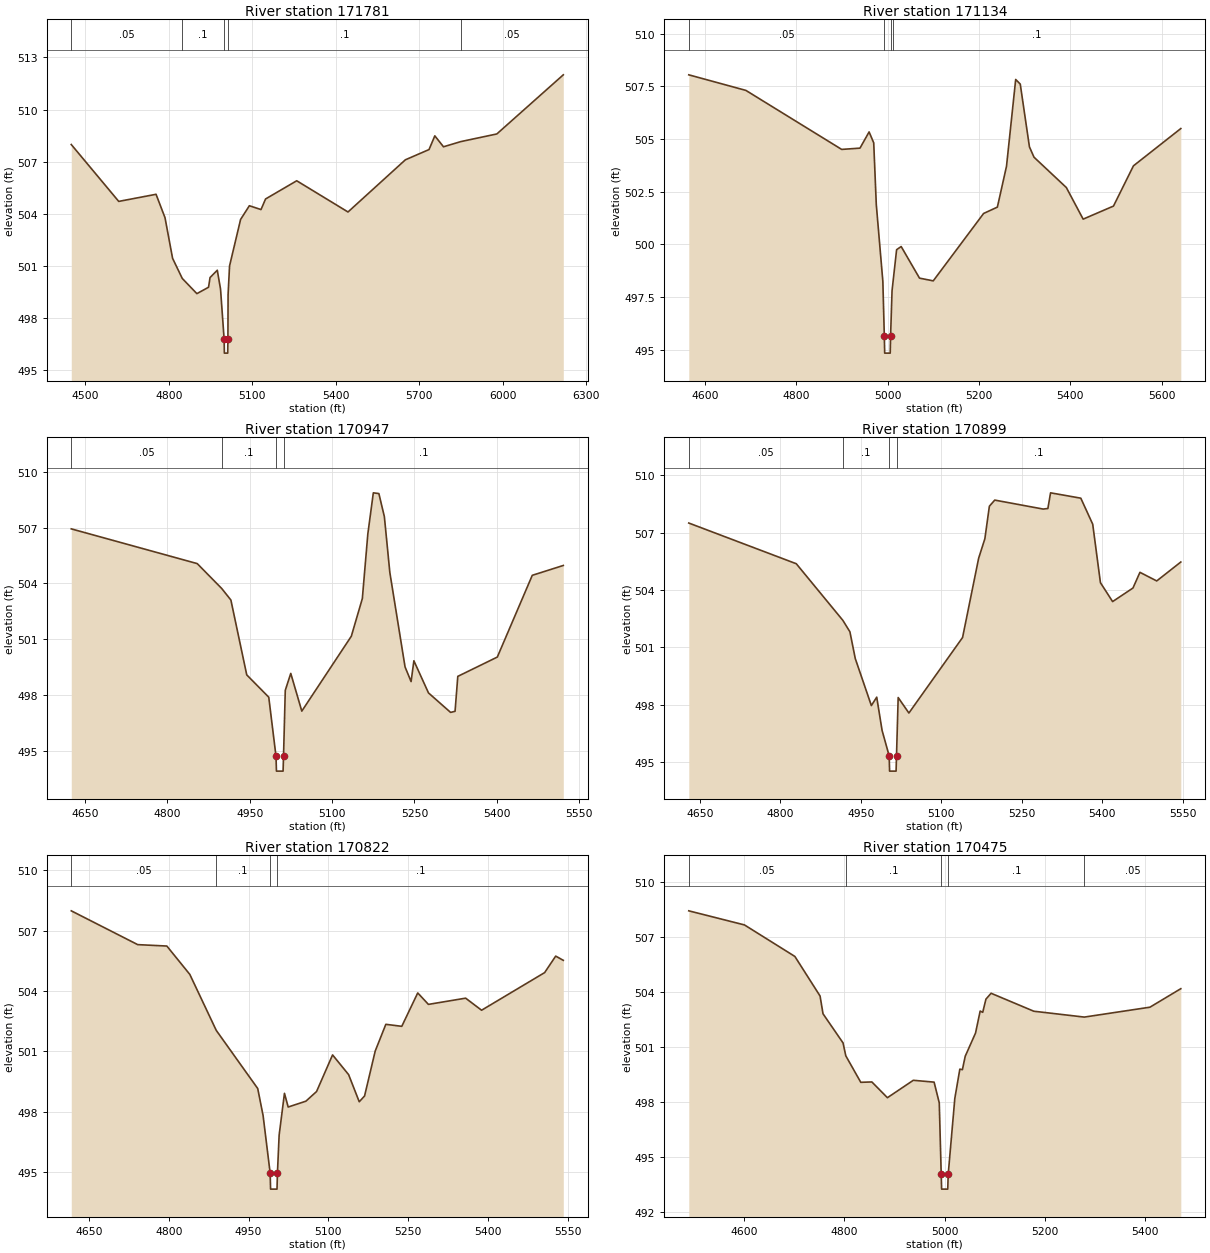
Type RM Length L Ch R = 1 ,171781  ,647,647,647
BEGIN DESCRIPTION:
Mapping XS f79434da
END DESCRIPTION:
XS GIS Cut Line= 4
      2031515.98     13521790.38      2031588.89     13521503.96
      2031725.71     13521068.68      2031443.45     13520091.15
#Sta/Elev= 30
  4449.1  507.98  4619.8   504.7    4754  505.11  4786.2  503.76  4813.4  501.42
  4848.1  500.26  4900.8  499.38  4942.7  499.75  4948.2  500.31  4974.2  500.73
  4985.9  499.64  4998.8  496.75  4999.6  495.95  5011.7  495.95  5012.4  496.75
    5013  499.32  5018.3  500.98    5058  503.66  5089.5  504.45  5131.4  504.23
  5147.8  504.84  5259.8  505.89  5444.2  504.09  5650.6   507.1  5735.6  507.69
  5756.4  508.48  5787.6  507.85  5850.1  508.15  5979.4  508.59  6218.4     512
#Mann= 5 ,-1 , 0
  4449.1     .05       0  4848.1      .1       0  4998.8     .07       0
  5012.4      .1       0  5850.1     .05       0
Bank Sta=4998.8,5012.4
XS Rating Curve= 0 ,0
Exp/Cntr=0.3,0.1

Type RM Length L Ch R = 1 ,171134  ,187,187,187
BEGIN DESCRIPTION:
Mapping XS d0d25599
END DESCRIPTION:
XS GIS Cut Line= 4
      2032104.52     13521837.27      2032139.77     13521562.17
       2032099.3     13521009.17      2032029.51     13520773.93
#Sta/Elev= 30
  4564.6  508.05  4689.7  507.31  4899.3  504.51  4939.4  504.57  4959.4  505.34
  4969.5  504.82  4975.1   501.9  4989.5  498.24  4992.7  495.64  4993.5  494.84
  5005.6  494.84  5006.4  495.64  5009.6   497.8  5012.1  498.29  5019.6  499.75
  5029.6   499.9  5069.7   498.4  5099.8  498.27  5210.1  501.47  5240.2  501.77
  5260.2  503.71  5280.3  507.83  5290.3  507.61  5310.4  504.63  5320.4  504.14
  5391.2   502.7    5428   501.2  5494.4  501.82  5538.1  503.73  5641.8   505.5
#Mann= 4 ,-1 , 0
  4564.6     .05       0  4992.7    .035       0  5006.4     .05       0
  5012.1      .1       0
Bank Sta=4992.7,5006.4
XS Rating Curve= 0 ,0
Exp/Cntr=0.3,0.1

Type RM Length L Ch R = 1 ,170947  ,48,48,48
BEGIN DESCRIPTION:
Mapping XS e8e20003
END DESCRIPTION:
XS GIS Cut Line= 5
       2032233.7     13521654.07      2032251.93     13521367.65
      2032228.49     13521044.73      2032249.32     13520880.67
      2032212.86     13520766.08
#Sta/Elev= 30
  4624.9  506.94  4854.4  505.07    4899  503.73  4915.7  503.11  4944.6  499.08
  4984.7  497.88  4997.9   494.7  4998.7   493.9  5010.8   493.9  5011.6   494.7
  5014.8  498.25  5024.8  499.16  5044.9  497.13  5135.1  501.16  5155.2  503.19
  5165.2  506.67  5175.2  508.88  5185.3  508.84  5195.3   507.6  5205.3  504.59
    5233  499.51    5244  498.72  5249.1  499.84  5275.7  498.11    5316  497.06
  5324.1  497.12  5329.1     499  5401.1  500.04  5464.8  504.44  5521.3  504.97
#Mann= 4 ,-1 , 0
  4624.9     .05       0    4899      .1       0  4997.9     .07       0
  5011.6      .1       0
Bank Sta=4997.9,5011.6
XS Rating Curve= 0 ,0
Exp/Cntr=0.3,0.1

Type RM Length L Ch R = 1 ,170899  ,77,77,77
BEGIN DESCRIPTION:
Mapping XS 2979fda5
END DESCRIPTION:
XS GIS Cut Line= 5
      2032283.18     13521625.51      2032285.78     13521375.46
      2032280.57     13521073.38       2032296.2     13520872.86
      2032225.87     13520724.39
#Sta/Elev= 30
    4629  507.51  4829.5  505.38  4916.3  502.42  4929.5  501.82  4939.5  500.42
  4969.5  497.96  4979.5   498.4  4989.5  496.66  5002.7  495.33  5003.5  494.53
  5015.6  494.53  5016.4  495.33  5019.5  498.38  5039.5  497.57  5139.6  501.52
  5169.6  505.67  5181.2  506.69  5189.6  508.39  5199.6  508.71  5289.9  508.24
  5298.7  508.27  5303.7  509.09  5360.1  508.81  5382.3  507.45  5396.7  504.39
  5419.4   503.4  5457.4  504.11  5470.4  504.93  5501.7  504.48  5546.6  505.47
#Mann= 4 ,-1 , 0
    4629     .05       0  4916.3      .1       0  5002.7     .07       0
  5016.4      .1       0
Bank Sta=5002.7,5016.4
XS Rating Curve= 0 ,0
Exp/Cntr=0.3,0.1

Type RM Length L Ch R = 1 ,170822  ,347,347,347
BEGIN DESCRIPTION:
Mapping XS 32f82ce7
END DESCRIPTION:
XS GIS Cut Line= 5
      2032335.27     13521591.58      2032366.51     13521435.36
      2032327.45     13521068.17      2032330.05     13520797.34
      2032250.36     13520699.64
#Sta/Elev= 30
  4616.6  507.98  4741.6   506.3  4796.4  506.23  4839.6  504.82  4889.3  502.04
  4967.3  499.15  4977.4  497.81  4990.7  494.95  4991.5  494.15  5003.6  494.15
  5004.4  494.95  5007.6  496.83  5017.6  498.91  5024.6  498.23  5057.9  498.52
    5078     499  5108.1  500.82  5138.3  499.84  5158.3  498.49  5168.3  498.78
  5188.3  501.01  5208.3  502.34  5238.3  502.24  5268.3   503.9  5288.4  503.33
  5358.4  503.64  5388.4  503.04    5507  504.91  5527.8  505.73  5542.1  505.52
#Mann= 4 ,-1 , 0
  4616.6     .05       0  4889.3      .1       0  4990.7     .07       0
  5004.4      .1       0
Bank Sta=4990.7,5004.4
XS Rating Curve= 0 ,0
Exp/Cntr=0.3,0.1

Type RM Length L Ch R = 1 ,170475  ,592,592,592
BEGIN DESCRIPTION:
Mapping XS b6d864b7
END DESCRIPTION:
XS GIS Cut Line= 4
      2032646.18      13521545.6      2032669.72     13521278.32
      2032575.87     13520918.02       2032396.5     13520629.47
#Sta/Elev= 30
  4490.1  508.42  4601.1  507.65  4701.5  505.93  4751.7  503.77  4757.6   502.8
  4797.5  501.21  4802.9  500.51  4832.8  499.06  4854.9  499.08  4885.9  498.22
  4937.5  499.17  4978.9  499.07  4989.2  497.94  4993.1  494.03  4993.9  493.23
  5006.1  493.23    5007  494.03  5020.2  498.18  5030.2  499.78  5035.3  499.75
  5040.9  500.48  5061.5  501.75  5070.7  502.95  5075.8  502.88  5082.2   503.6
  5092.5  503.92  5177.6  502.94  5278.2  502.62    5409  503.16  5470.5  504.17
#Mann= 5 ,-1 , 0
  4490.1     .05       0  4802.9      .1       0  4993.1     .07       0
    5007      .1       0  5278.2     .05       0
Bank Sta=4993.1,5007
XS Rating Curve= 0 ,0
Exp/Cntr=0.3,0.1

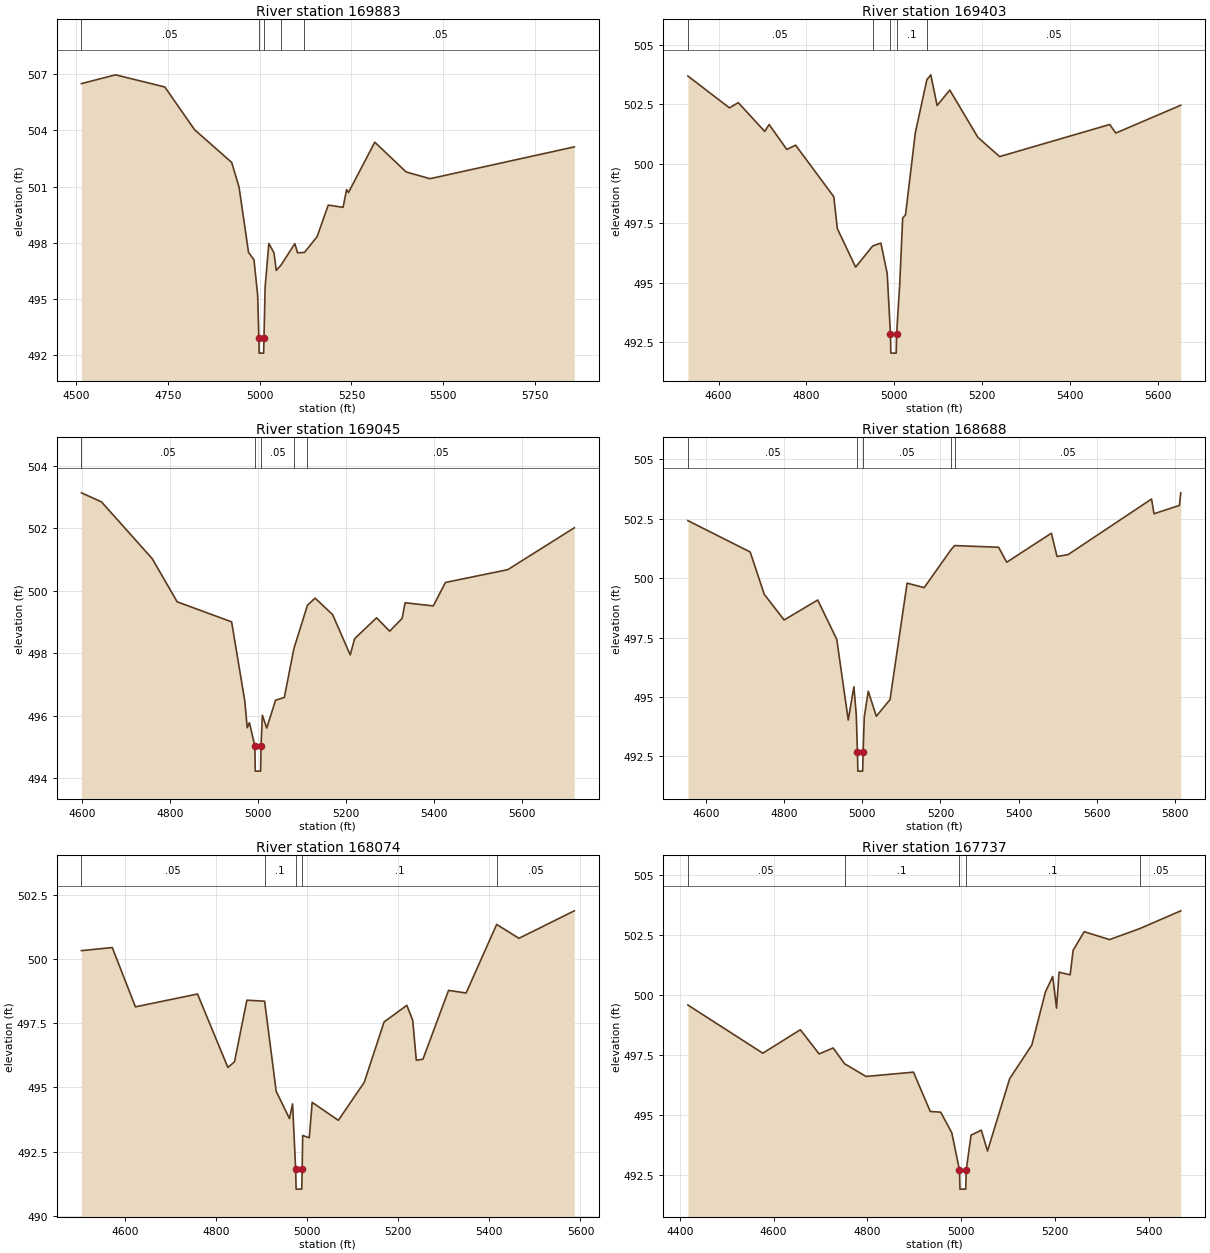
Type RM Length L Ch R = 1 ,169883  ,480,480,480
BEGIN DESCRIPTION:
Mapping XS e5898eff
END DESCRIPTION:
XS GIS Cut Line= 4
      2033096.82     13521443.64      2033165.81     13521316.08
      2033074.67      13520705.4      2032599.62     13520373.97
#Sta/Elev= 30
  4514.9   506.5  4607.8  506.97  4741.9  506.32  4822.8  504.04  4923.9  502.29
  4944.1  500.96  4969.8  497.48  4984.6  497.09  4994.7  495.19  4997.8   492.9
  4998.7   492.1  5010.9   492.1  5011.8   492.9  5014.9  495.61    5025  497.96
  5039.1  497.46  5045.2  496.52  5058.5  496.81  5095.8  497.95  5103.3  497.46
    5122  497.48  5156.4  498.32  5186.8  500.01  5227.2  499.89  5236.7  500.84
  5241.8  500.68  5313.5  503.37  5398.9  501.78  5463.8  501.42  5856.6  503.12
#Mann= 5 ,-1 , 0
  4514.9     .05       0  4997.8     .03       0  5011.8     .05       0
  5058.5      .1       0    5122     .05       0
Bank Sta=4997.8,5011.8
XS Rating Curve= 0 ,0
Exp/Cntr=0.3,0.1

Type RM Length L Ch R = 1 ,169403  ,358,358,358
BEGIN DESCRIPTION:
Mapping XS e0fa360f
END DESCRIPTION:
XS GIS Cut Line= 4
      2033542.01     13521069.09      2033566.85     13520799.15
      2033279.09     13520442.38      2032935.26     13520253.97
#Sta/Elev= 30
  4530.3  503.69  4624.8  502.35  4644.9  502.57  4705.1  501.36  4715.2  501.65
  4755.3   500.6  4775.4  500.78  4862.3  498.61  4870.3  497.27  4911.9  495.65
  4950.8  496.54  4969.4  496.66  4983.8  495.38  4991.2  492.83  4992.1  492.03
  5004.3  492.03  5005.2  492.83  5012.3  494.93    5019  497.71  5025.5  497.85
  5047.8   501.3    5074  503.53    5083  503.74  5097.4  502.45  5126.2   503.1
  5190.1  501.11  5239.7   500.3  5490.2  501.65  5503.9  501.29  5651.8  502.46
#Mann= 5 ,-1 , 0
  4530.3     .05       0  4950.8      .1       0  4991.2     .07       0
  5005.2      .1       0    5074     .05       0
Bank Sta=4991.2,5005.2
XS Rating Curve= 0 ,0
Exp/Cntr=0.3,0.1

Type RM Length L Ch R = 1 ,169045  ,357,357,357
BEGIN DESCRIPTION:
Mapping XS 3e4b2a71
END DESCRIPTION:
XS GIS Cut Line= 4
      2033734.72     13521035.22      2033763.47     13520787.43
      2033751.75     13520352.53      2033427.41     13520058.63
#Sta/Elev= 30
  4597.6  503.14  4643.3  502.85  4758.9  501.03  4815.6  499.65  4939.5  499.01
  4969.5  496.48  4975.1  495.62  4980.1  495.78  4992.5  495.03  4993.4  494.23
  5005.6  494.23  5006.5  495.03  5009.5  496.02  5019.5  495.61  5039.6   496.5
  5059.6  496.59  5081.3  498.15  5112.2  499.54  5129.6  499.77  5169.6  499.24
  5209.6  497.95  5219.6  498.47  5269.6  499.14  5299.4  498.71  5327.8  499.12
  5334.5  499.62  5398.7  499.52  5426.4  500.27  5568.3  500.68  5719.8  502.02
#Mann= 5 ,-1 , 0
  4597.6     .05       0  4992.5     .03       0  5006.5     .05       0
  5081.3      .1       0  5112.2     .05       0
Bank Sta=4992.5,5006.5
XS Rating Curve= 0 ,0
Exp/Cntr=0.3,0.1

Type RM Length L Ch R = 1 ,168688  ,614,614,614
BEGIN DESCRIPTION:
Mapping XS 7236a0d4
END DESCRIPTION:
XS GIS Cut Line= 6
      2034060.25     13520946.63      2034107.22     13520700.19
      2034021.18     13520311.25      2033833.68     13520069.06
      2033698.26     13519936.25       2033605.5     13519869.26
#Sta/Elev= 30
  4554.5  502.42  4713.7   501.1  4749.6  499.32  4800.4  498.24  4886.3  499.08
    4935  497.42  4964.3  494.03  4978.7  495.43  4984.8  494.26  4987.8  492.68
  4988.9  491.88  5001.2  491.88  5002.2  492.68  5005.3  494.17  5015.5  495.24
    5036  494.19  5071.1  494.89  5114.7  499.79  5158.3   499.6  5226.6  501.19
    5236  501.37  5348.5   501.3  5369.3  500.67  5483.4  501.89  5497.9  500.91
  5526.1  500.99  5739.5  503.33  5745.7  502.71  5810.7  503.06  5814.1  503.59
#Mann= 5 ,-1 , 0
  4554.5     .05       0  4987.8     .03       0  5002.2     .05       0
  5226.6      .1       0    5236     .05       0
Bank Sta=4987.8,5002.2
XS Rating Curve= 0 ,0
Exp/Cntr=0.3,0.1

Type RM Length L Ch R = 1 ,168074  ,337,337,337
BEGIN DESCRIPTION:
Mapping XS b07bf361
END DESCRIPTION:
XS GIS Cut Line= 4
      2034739.92     13520631.51      2034691.85     13520381.18
      2034353.31     13519935.87      2034104.65     13519835.62
#Sta/Elev= 30
  4504.1  500.33  4571.8  500.45  4622.7  498.14    4759  498.64  4825.7  495.78
  4840.3     496  4867.4   498.4  4906.4  498.36  4931.8  494.85  4960.9  493.79
  4967.8  494.36  4974.5  491.84  4975.6  491.04  4987.9  491.04  4988.9  491.84
    4990  493.13  5004.5  493.04  5010.8  494.42  5068.3  493.72  5125.2   495.2
  5168.7  497.55  5218.7   498.2  5231.6  497.62  5239.5  496.06  5254.1   496.1
  5310.3  498.78  5348.9  498.68    5416  501.35    5465  500.81  5586.5  501.88
#Mann= 5 ,-1 , 0
  4504.1     .05       0  4906.4      .1       0  4974.5     .07       0
  4988.9      .1       0    5416     .05       0
Bank Sta=4974.5,4988.9
XS Rating Curve= 0 ,0
Exp/Cntr=0.3,0.1

Type RM Length L Ch R = 1 ,167737  ,248,248,248
BEGIN DESCRIPTION:
Mapping XS 7a76061c
END DESCRIPTION:
XS GIS Cut Line= 4
      2034859.72     13520584.65      2034870.24     13520153.32
      2034710.08     13519778.32      2034514.74     13519697.58
#Sta/Elev= 30
  4417.5  499.58  4577.2  497.57  4657.2  498.55  4697.2  497.54  4727.2  497.79
  4751.5  497.13  4797.3   496.6  4898.3  496.78  4934.1  495.14  4956.4  495.11
    4980  494.25  4996.4   492.7  4997.4   491.9  5009.7   491.9  5010.8   492.7
  5021.1  494.15  5042.9  494.36  5056.2  493.49  5103.4  496.51  5150.6  497.91
  5179.7  500.13  5195.1  500.77  5203.3  499.45  5208.7  500.95  5232.3  500.84
  5238.6  501.86  5262.2  502.64  5316.3  502.31  5380.9  502.77  5468.1  503.51
#Mann= 5 ,-1 , 0
  4417.5     .05       0  4751.5      .1       0  4996.4     .07       0
  5010.8      .1       0  5380.9     .05       0
Bank Sta=4996.4,5010.8
XS Rating Curve= 0 ,0
Exp/Cntr=0.3,0.1