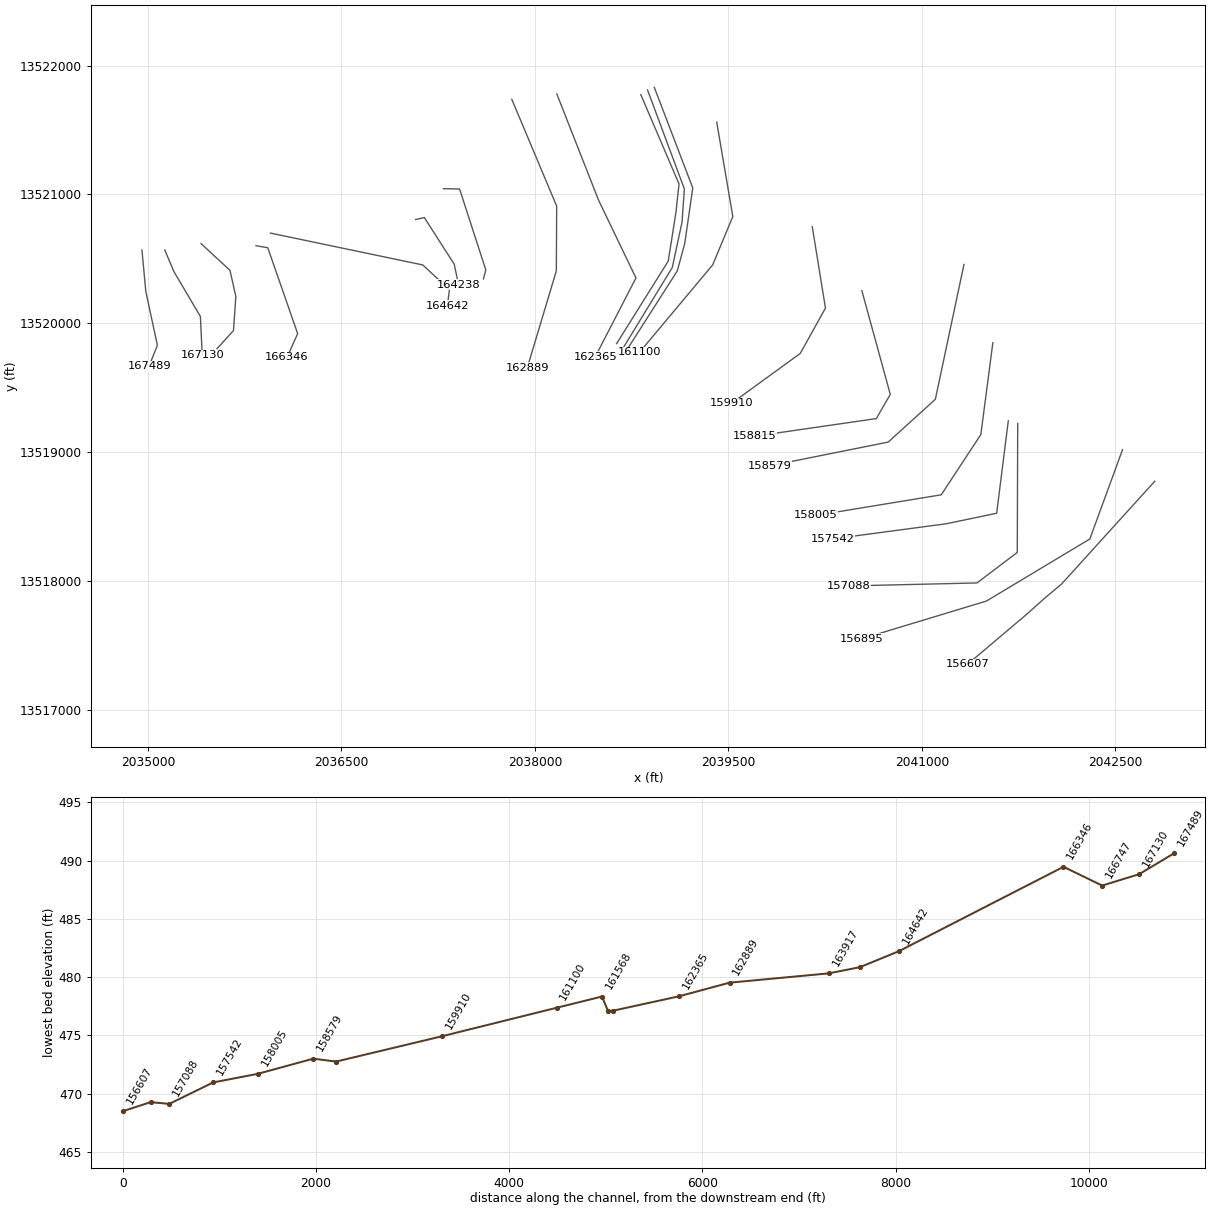
HEC-RAS study LAGUNILLAS Cr.prj: LAGUNILLAS Cr Base Level Engineering

--- LAGUNILLAS Cr.g01 (geometry) --- (continued)

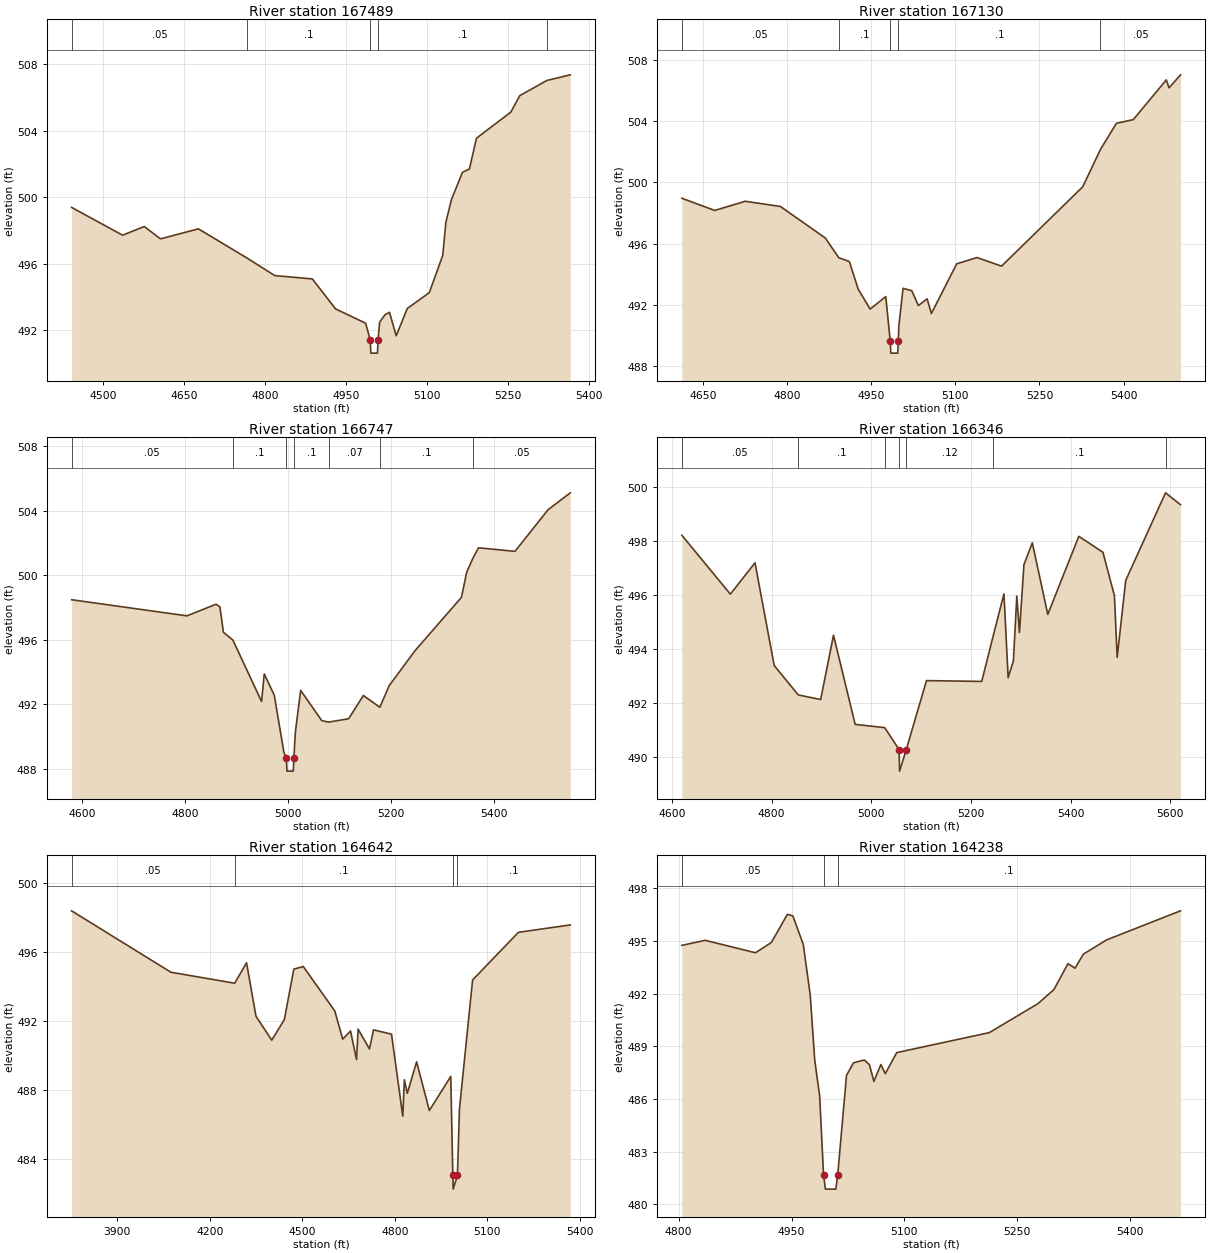
Type RM Length L Ch R = 1 ,167489  ,359,359,359
BEGIN DESCRIPTION:
Mapping XS a4e4e59f
END DESCRIPTION:
XS GIS Cut Line= 4
      2034953.47      13520569.1      2034983.52     13520247.07
      2035073.36      13519829.1      2035008.98     13519668.15
#Sta/Elev= 30
    4441  499.38  4535.5  497.71  4575.7  498.23  4605.8  497.49  4676.1  498.09
  4766.5  496.33  4817.7  495.28  4887.3  495.08  4930.2  493.28    4986  492.42
  4994.6  491.42  4995.7  490.62    5008  490.62  5009.1  491.42    5012  492.48
  5022.3  492.94  5030.3  493.07  5042.7  491.66  5063.2   493.3  5104.1  494.26
    5129   496.5  5134.8  498.49    5145  499.84  5165.5  501.49  5178.4  501.69
  5191.5  503.54  5255.2  505.11  5271.8   506.1  5321.9  507.01  5365.3  507.35
#Mann= 5 ,-1 , 0
    4441     .05       0  4766.5      .1       0  4994.6     .07       0
  5009.1      .1       0  5321.9     .05       0
Bank Sta=4994.6,5009.1
XS Rating Curve= 0 ,0
Exp/Cntr=0.3,0.1

Type RM Length L Ch R = 1 ,167130  ,383,383,383
BEGIN DESCRIPTION:
Mapping XS c755a7ed
END DESCRIPTION:
XS GIS Cut Line= 4
      2035130.56     13520569.06      2035200.97     13520402.01
       2035406.7     13520053.06      2035421.02     13519750.96
#Sta/Elev= 30
  4612.7  498.97  4671.4  498.17  4725.6  498.77  4788.4  498.43  4868.4  496.37
  4892.4  495.08  4911.3  494.83    4927  493.03  4948.4  491.72  4976.2  492.54
  4984.1  489.64  4985.2  488.84  4997.5  488.84  4998.6  489.64  4999.5  490.61
    5007  493.08  5022.6  492.92  5034.3  491.95  5049.9  492.39  5057.5  491.43
  5102.6  494.68  5138.8  495.09  5182.6  494.53  5327.3  499.72  5358.9  502.16
  5387.3  503.87  5417.4  504.11  5476.2  506.71  5481.2  506.19  5501.5  507.04
#Mann= 5 ,-1 , 0
  4612.7     .05       0  4892.4      .1       0  4984.1     .07       0
  4998.6      .1       0  5358.9     .05       0
Bank Sta=4984.1,4998.6
XS Rating Curve= 0 ,0
Exp/Cntr=0.3,0.1

Type RM Length L Ch R = 1 ,166747  ,401,401,401
BEGIN DESCRIPTION:
Mapping XS 8f413bcf
END DESCRIPTION:
XS GIS Cut Line= 5
       2035411.8     13520618.54      2035635.86     13520411.13
      2035681.44       13520208.      2035663.21     13519943.68
      2035535.63     13519803.09
#Sta/Elev= 30
  4579.1  498.49    4803  497.49  4859.7  498.21  4867.1  498.05  4873.9  496.47
  4892.3  495.99    4948  492.18  4953.2  493.89  4972.7  492.57  4991.4  489.02
  4996.2  488.66  4997.3  487.86  5009.6  487.86  5010.7  488.66  5013.7   490.3
  5023.9  492.87  5064.9  490.99  5078.5   490.9  5117.1  491.11  5145.7  492.55
  5177.7  491.82  5195.8  493.16    5246  495.33  5336.2  498.64  5346.2  500.18
  5358.2  501.05  5369.3  501.71  5440.1  501.49  5504.3  504.07  5547.4  505.12
#Mann= 7 ,-1 , 0
  4579.1     .05       0  4892.3      .1       0  4996.2     .07       0
  5010.7      .1       0  5078.5     .07       0  5177.7      .1       0
  5358.2     .05       0
Bank Sta=4996.2,5010.7
XS Rating Curve= 0 ,0
Exp/Cntr=0.3,0.1

Type RM Length L Ch R = 1 ,166346  ,1704,1704,1704
BEGIN DESCRIPTION:
Mapping XS 1aed98a5
END DESCRIPTION:
XS GIS Cut Line= 4
      2035837.86     13520602.02      2035929.01      13520586.4
      2036160.78     13519919.73      2036077.45     13519734.83
#Sta/Elev= 30
  4619.7   498.2  4717.1  496.02  4766.6  497.18  4805.1  493.38  4853.4  492.29
  4898.4  492.12  4924.2   494.5  4967.7   491.2    5027  491.08  5055.8  490.27
  5056.9  489.47  5070.3  490.27  5110.9  492.82  5221.8  492.79  5245.3  494.51
  5266.4  496.03  5274.8  492.93  5285.4  493.55  5292.2  495.95  5297.5   494.6
  5306.5  497.11  5323.3  497.92  5354.4  495.27  5416.7  498.16  5465.1  497.57
  5488.2  495.96  5493.7  493.68  5510.9  496.53  5590.8  499.77  5620.8  499.33
#Mann= 7 ,-1 , 0
  4619.7     .05       0  4853.4      .1       0    5027     .12       0
  5055.8     .07       0  5070.3     .12       0  5245.3      .1       0
  5590.8     .05       0
Bank Sta=5055.8,5070.3
XS Rating Curve= 0 ,0
Exp/Cntr=0.3,0.1

Type RM Length L Ch R = 1 ,164642  ,404,404,404
BEGIN DESCRIPTION:
Mapping XS 81906862
END DESCRIPTION:
XS GIS Cut Line= 4
      2035949.97     13520700.01      2037130.66     13520452.96
      2037337.22     13520260.85      2037320.95     13520133.94
#Sta/Elev= 30
  3752.3  498.41  4074.2  494.84  4280.9   494.2  4319.4  495.39    4350  492.28
  4401.1  490.89    4442  492.09  4472.6  495.02  4503.3  495.17  4605.4  492.59
  4631.1  490.95  4656.5  491.42  4675.9  489.76    4681  491.53  4717.8  490.38
    4731  491.49  4789.3  491.24  4825.8  486.47  4830.9  488.59  4840.4   487.8
  4870.7  489.63  4911.9   486.8  4981.3  488.78    4988  483.03  4989.3  482.23
  5002.9  483.03  5009.6  486.91  5052.1  494.39  5200.7  497.16  5368.6  497.59
#Mann= 4 ,-1 , 0
  3752.3     .05       0  4280.9      .1       0    4988     .07       0
  5002.9      .1       0
Bank Sta=4988,5002.9
XS Rating Curve= 0 ,0
Exp/Cntr=0.3,0.1

Type RM Length L Ch R = 1 ,164238  ,321,321,321
BEGIN DESCRIPTION:
Mapping XS 3866f916
END DESCRIPTION:
XS GIS Cut Line= 4
      2037074.84     13520805.15      2037142.55     13520820.77
      2037374.32     13520458.79       2037407.9     13520298.69
#Sta/Elev= 30
  4804.2  494.75  4835.2  495.04  4902.2  494.33  4923.3  494.92  4944.5  496.52
  4951.8  496.43  4965.6  494.81  4974.9  491.92  4980.9   488.2  4987.4  486.18
  4992.6  481.66  4995.1  480.86  5008.9  480.86  5011.4  481.66  5023.1  487.34
  5032.4  488.06  5046.8  488.22  5053.6  487.95  5059.5     487  5068.8  487.96
  5074.7  487.44  5089.9  488.64    5213  489.78  5277.6  491.43  5298.8  492.23
  5317.6  493.71  5326.9  493.45    5338  494.25  5368.7  495.06  5467.1  496.72
#Mann= 3 ,-1 , 0
  4804.2     .05       0  4992.6     .07       0  5011.4      .1       0
Bank Sta=4992.6,5011.4
XS Rating Curve= 0 ,0
Exp/Cntr=0.3,0.1

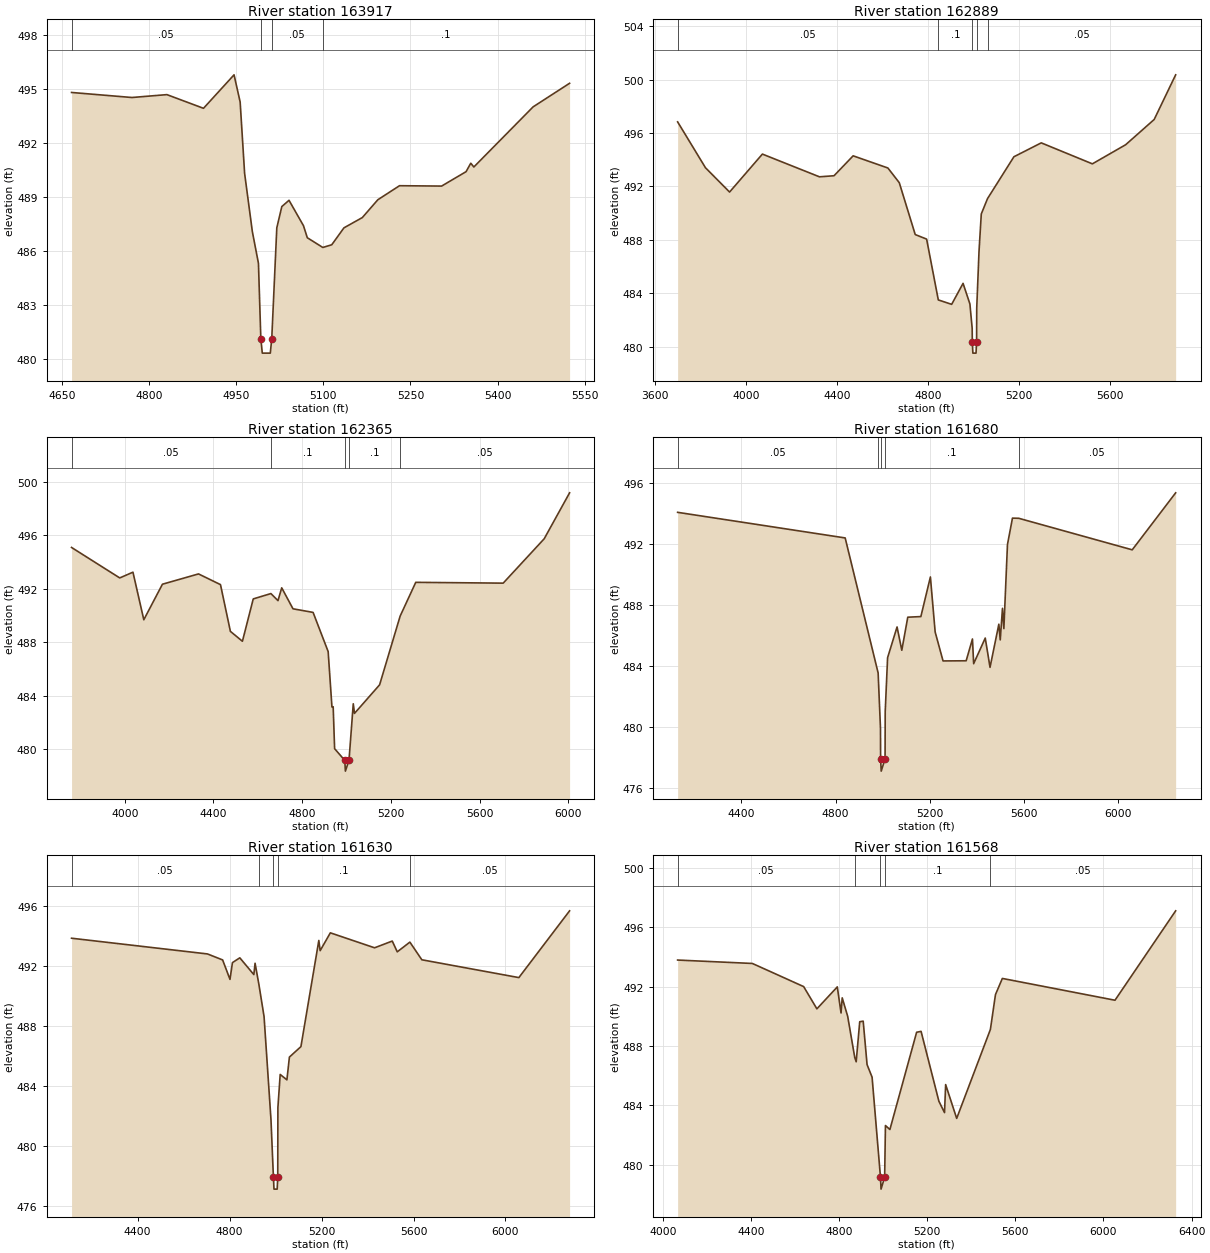
Type RM Length L Ch R = 1 ,163917  ,1028,1028,1028
BEGIN DESCRIPTION:
Mapping XS 8c523bf4
END DESCRIPTION:
XS GIS Cut Line= 4
      2037290.98     13521044.73      2037415.99     13521042.13
      2037619.12     13520414.52       2037600.9     13520344.24
#Sta/Elev= 30
  4666.6  494.81  4770.6  494.53  4830.7  494.69  4893.7  493.93  4946.3  495.79
  4956.8  494.28  4964.5  490.31  4977.8  487.08  4988.3  485.32  4992.4  481.13
  4994.9  480.33  5008.7  480.33  5011.2  481.13  5019.9  487.29  5028.5  488.47
  5040.9  488.82  5065.8  487.41  5072.4  486.74  5099.1   486.2  5114.5  486.35
  5135.5  487.29  5167.1  487.86  5193.8  488.85  5231.1  489.63  5303.6  489.61
  5345.7  490.41  5353.8  490.88  5359.1  490.67  5461.1  494.01  5523.9  495.32
#Mann= 4 ,-1 , 0
  4666.6     .05       0  4992.4     .03       0  5011.2     .05       0
  5099.1      .1       0
Bank Sta=4992.4,5011.2
XS Rating Curve= 0 ,0
Exp/Cntr=0.3,0.1

Type RM Length L Ch R = 1 ,162889  ,524,524,524
BEGIN DESCRIPTION:
Mapping XS 80e118b7
END DESCRIPTION:
XS GIS Cut Line= 4
      2037820.78     13521738.08       2038168.6     13520909.31
      2038165.99     13520406.71      2037940.56     13519654.78
#Sta/Elev= 30
  3700.7  496.83  3822.9   493.4  3928.8  491.58  4072.8  494.42  4323.3  492.72
  4387.3   492.8  4471.3  494.29  4623.8  493.38  4673.8  492.28  4743.8   488.4
  4793.8  488.06  4845.1  483.51  4903.8  483.18  4953.8  484.75  4983.8  483.21
  4993.8  481.39  4994.4  480.33  4996.9  479.53  5010.7  479.53  5013.2  480.33
  5013.8   482.9  5023.8  487.13  5033.8  489.94  5061.2  491.09    5177  494.22
  5297.1  495.26  5521.5  493.69  5667.6  495.12  5792.9  497.01  5887.1  500.35
#Mann= 5 ,-1 , 0
  3700.7     .05       0  4845.1      .1       0  4994.4     .07       0
  5013.2      .1       0  5061.2     .05       0
Bank Sta=4994.4,5013.2
XS Rating Curve= 0 ,0
Exp/Cntr=0.3,0.1

Type RM Length L Ch R = 1 ,162365  ,685,685,685
BEGIN DESCRIPTION:
Mapping XS 8999a712
END DESCRIPTION:
XS GIS Cut Line= 4
      2038169.73     13521779.78      2038494.12     13520953.59
      2038783.18     13520352.02      2038467.07     13519739.03
#Sta/Elev= 30
  3760.5   495.1  3977.6  492.82  4037.2  493.25  4086.1  489.69  4170.1  492.35
  4332.7  493.12  4431.7  492.32  4476.4  488.82  4530.6  488.08  4579.4  491.25
    4659  491.65  4690.9  491.12  4707.7  492.08  4758.5  490.51  4849.1  490.24
    4917  487.31  4934.1  483.16  4939.6  483.18  4946.1  480.04  4992.1  479.16
  4994.6  478.36  5010.9  479.16  5030.2   483.4  5035.7  482.68  5148.9  484.82
  5241.4  489.96  5311.8  492.49  5705.9  492.43  5890.7  495.75  6005.2  499.19
#Mann= 5 ,-1 , 0
  3760.5     .05       0    4659      .1       0  4992.1     .07       0
  5010.9      .1       0  5241.4     .05       0
Bank Sta=4992.1,5010.9
XS Rating Curve= 0 ,0
Exp/Cntr=0.3,0.1

Type RM Length L Ch R = 1 ,161680  ,50,50,50
BEGIN DESCRIPTION:
Mapping XS 10215ca6
END DESCRIPTION:
XS GIS Cut Line= 5
      2038820.76      13521774.6      2039117.07     13521081.58
      2039093.03     13520859.56      2039033.52     13520483.04
      2038633.28      13519842.3
#Sta/Elev= 30
  4129.3   494.1  4840.4  492.42  4980.3  483.56  4990.2  479.94  4990.8  477.92
  4993.3  477.12  5009.7  477.92  5010.3  481.01  5020.4  484.56  5060.6  486.58
  5080.7  485.05  5106.1  487.22  5161.6  487.26  5202.1  489.86  5222.3  486.25
  5255.8  484.35  5353.9  484.36  5380.6  485.79  5385.7  484.17  5434.9  485.85
  5455.2  483.93  5492.6  486.76  5498.5  485.73    5508   487.8  5513.9  486.47
  5529.2  491.99  5550.4  493.72  5576.9  493.71  6058.7  491.64    6243  495.38
#Mann= 5 ,-1 , 0
  4129.3     .05       0  4980.3      .1       0  4990.8     .07       0
  5009.7      .1       0  5576.9     .05       0
Bank Sta=4990.8,5009.7
XS Rating Curve= 0 ,0
Exp/Cntr=0.3,0.1

Type RM Length L Ch R = 1 ,161630  ,62,62,62
BEGIN DESCRIPTION:
Mapping XS 28d2a3e0
END DESCRIPTION:
XS GIS Cut Line= 5
      2038872.86     13521811.02      2039158.54     13521042.49
      2039140.31     13520784.68      2039064.79     13520433.11
      2038685.36     13519811.05
#Sta/Elev= 30
  4112.4  493.86  4703.6  492.81  4769.6  492.41  4801.6  491.11  4812.3  492.23
  4844.3  492.55  4905.4  491.43  4910.7  492.19  4927.4  490.77  4949.8  488.63
  4979.9  481.75  4990.5   477.9    4993   477.1  5006.9   477.1  5009.4   477.9
    5010  482.54    5020  484.76  5049.2   484.4  5060.1  485.92  5110.2  486.62
  5188.1  493.71  5193.9  493.03  5238.2  494.22  5430.6  493.22  5507.5  493.67
  5529.3  492.95  5584.2   493.6  5636.2  492.42  6058.3  491.23    6279  495.69
#Mann= 5 ,-1 , 0
  4112.4     .05       0  4927.4      .1       0  4990.5     .07       0
  5009.4      .1       0  5584.2     .05       0
Bank Sta=4990.5,5009.4
XS Rating Curve= 0 ,0
Exp/Cntr=0.3,0.1

Type RM Length L Ch R = 1 ,161568  ,468,468,468
BEGIN DESCRIPTION:
Mapping XS 778dc736
END DESCRIPTION:
XS GIS Cut Line= 5
      2038924.93     13521831.88      2039223.64      13521050.3
      2039161.14     13520618.01      2039103.85     13520407.07
      2038690.92     13519759.52
#Sta/Elev= 30
  4067.4  493.79  4406.6  493.56  4639.3     492  4699.4   490.5    4792  491.98
    4809  490.22  4814.3  491.24  4839.1     490  4871.2  487.22  4877.7  486.93
  4893.8  489.63  4909.5  489.67  4927.1  486.74  4949.9  485.89    4988  479.14
  4990.5  478.34  5006.9  479.14  5010.5  482.63  5030.7  482.36    5152  488.92
  5172.2  488.98    5253  484.27  5278.6   483.5  5283.7  485.39  5333.8  483.11
  5486.8  489.11  5509.8  491.46  5541.1  492.55  6052.2  491.08  6327.5  497.11
#Mann= 5 ,-1 , 0
  4067.4     .05       0  4871.2      .1       0    4988     .07       0
  5006.9      .1       0  5486.8     .05       0
Bank Sta=4988,5006.9
XS Rating Curve= 0 ,0
Exp/Cntr=0.3,0.1

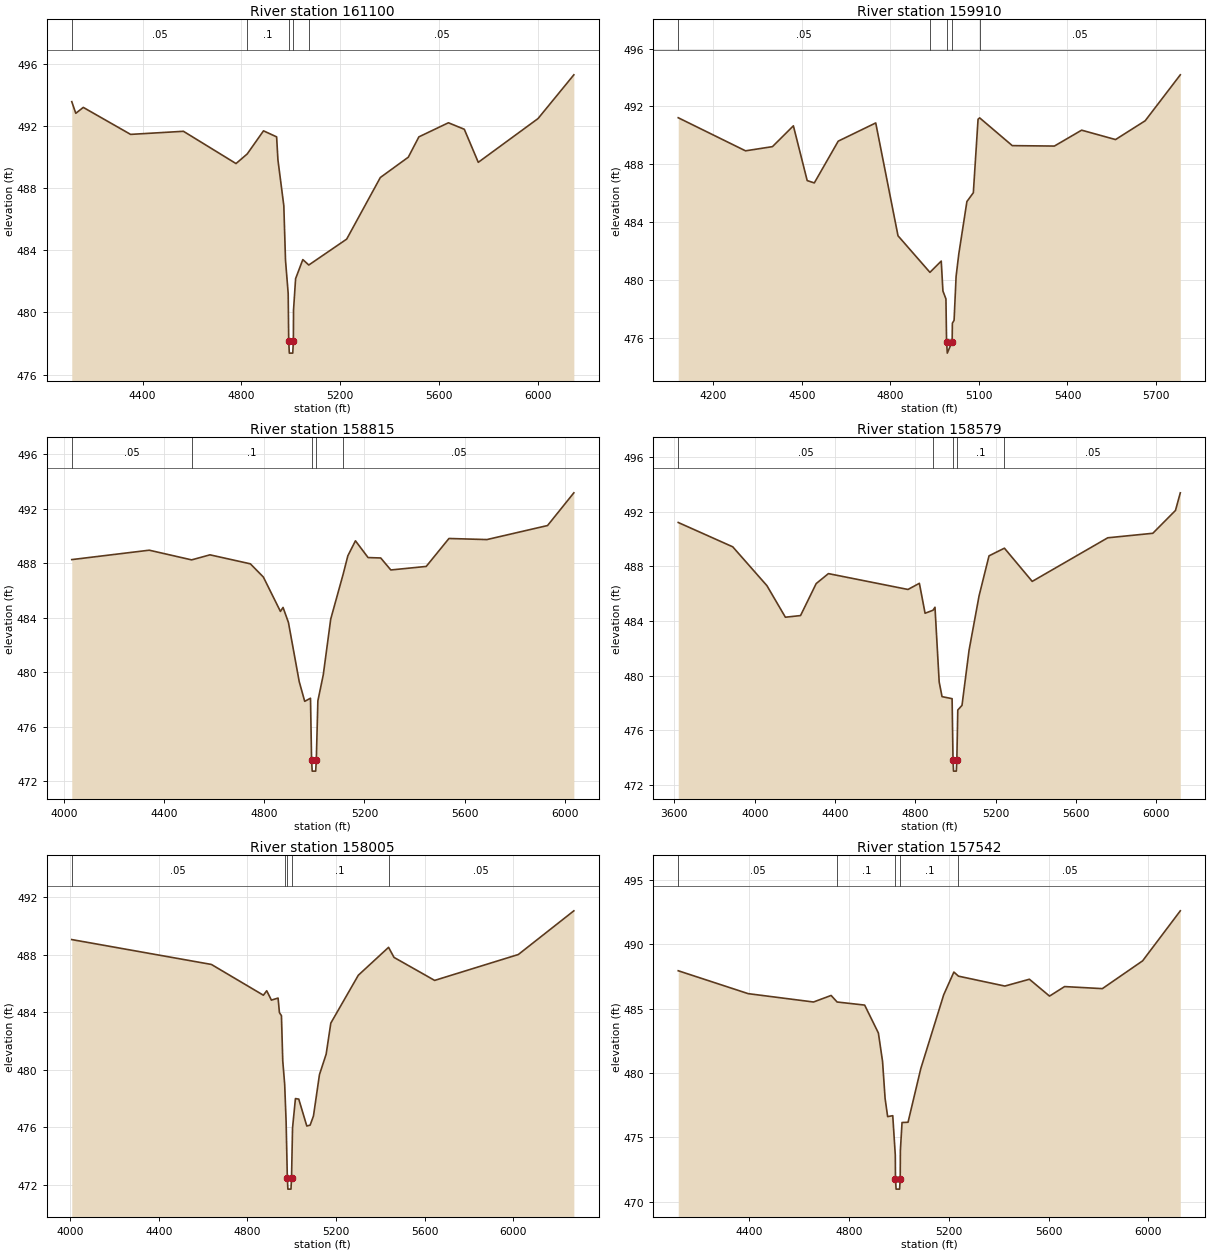
Type RM Length L Ch R = 1 ,161100  ,1190,1190,1190
BEGIN DESCRIPTION:
Mapping XS 6539a787
END DESCRIPTION:
XS GIS Cut Line= 4
       2039409.3     13521561.06      2039534.08     13520828.53
      2039377.83      13520453.1      2038810.34     13519774.56
#Sta/Elev= 30
  4112.9  493.59  4129.2  492.84  4159.6  493.22  4351.3  491.48  4565.4  491.68
  4778.4   489.6  4823.8  490.22  4889.8  491.71  4942.9  491.32  4948.3  489.83
  4972.1  486.88  4978.9  483.37  4989.8  481.22  4991.9  478.18  4994.4  477.38
  5008.3  477.38  5010.8  478.18  5011.4  480.15  5019.8  482.18  5049.1  483.41
  5073.3  483.06  5226.8  484.73  5363.1   488.7  5476.4  490.01  5519.3  491.32
    5639  492.23  5703.4  491.81    5760  489.68  6002.1   492.5  6147.2  495.32
#Mann= 5 ,-1 , 0
  4112.9     .05       0  4823.8      .1       0  4991.9     .07       0
  5010.8      .1       0  5073.3     .05       0
Bank Sta=4991.9,5010.8
XS Rating Curve= 0 ,0
Exp/Cntr=0.3,0.1

Type RM Length L Ch R = 1 ,159910  ,1095,1095,1095
BEGIN DESCRIPTION:
Mapping XS 5cdd1103
END DESCRIPTION:
XS GIS Cut Line= 4
        2040150.     13520749.98      2040252.29     13520118.01
      2040056.98     13519766.45      2039524.73     13519379.35
#Sta/Elev= 30
  4081.6  491.22  4309.5  488.93  4400.7  489.22  4471.6  490.66  4518.4  486.87
  4542.5  486.71  4623.5   489.6  4750.5  490.86    4826  483.05  4934.1  480.52
  4972.4   481.3  4978.1  479.23  4988.3  478.68  4990.4  475.73  4992.9  474.93
  5009.3  475.73  5010.1     477  5015.9   477.2  5022.7  480.24  5031.9   481.8
  5059.3  485.42  5081.1  486.03  5097.1  491.12  5102.6  491.21    5213  489.29
  5355.6  489.26  5447.9  490.36  5562.7  489.71  5663.1  491.01  5782.1  494.19
#Mann= 5 ,-1 , 0
  4081.6     .05       0  4934.1      .1       0  4990.4     .07       0
  5009.3      .1       0  5102.6     .05       0
Bank Sta=4990.4,5009.3
XS Rating Curve= 0 ,0
Exp/Cntr=0.3,0.1

Type RM Length L Ch R = 1 ,158815  ,236,236,236
BEGIN DESCRIPTION:
Mapping XS d29d1eab
END DESCRIPTION:
XS GIS Cut Line= 4
      2040534.32      13520253.7      2040754.79     13519448.32
      2040646.28     13519260.61      2039700.99     13519123.54
#Sta/Elev= 30
    4030  488.28  4339.7  488.97  4509.2  488.26  4582.5  488.63    4744  487.97
  4795.9     487  4864.1  484.48  4874.6  484.77  4896.1  483.67  4939.2  479.33
  4961.2  477.88  4984.3  478.11  4988.6  473.56  4991.1  472.76    5005  472.76
  5007.5  473.56  5013.8  477.92  5035.4  479.83  5065.2  483.92    5115  487.22
  5133.6  488.56    5164  489.66  5214.5  488.43    5265   488.4  5305.4  487.52
  5446.9  487.78  5537.8  489.83  5689.4  489.75  5931.9  490.78    6037  493.18
#Mann= 5 ,-1 , 0
    4030     .05       0  4509.2      .1       0  4988.6     .07       0
  5007.5      .1       0    5115     .05       0
Bank Sta=4988.6,5007.5
XS Rating Curve= 0 ,0
Exp/Cntr=0.3,0.1

Type RM Length L Ch R = 1 ,158579  ,574,574,574
BEGIN DESCRIPTION:
Mapping XS a3021843
END DESCRIPTION:
XS GIS Cut Line= 4
      2041325.98     13520456.89      2041104.18     13519410.35
      2040738.51     13519078.32      2039820.77     13518894.37
#Sta/Elev= 30
  3619.3   491.2  3890.7  489.42  4060.8  486.58  4152.8  484.27  4228.2  484.39
  4306.1  486.73    4367  487.46  4763.1   486.3  4819.9  486.75  4848.3  484.56
  4887.8  484.78  4897.6     485  4918.5  479.53  4932.7  478.46  4982.8  478.31
  4987.4  473.81  4989.9  473.01  5003.9  473.01  5006.4  473.81  5011.1  477.48
  5032.1  477.82  5067.2  481.85  5117.2  485.84  5166.6  488.76  5243.3  489.32
  5381.7  486.89  5757.7  490.08  5982.1  490.41  6094.9  492.08    6119  493.37
#Mann= 5 ,-1 , 0
  3619.3     .05       0  4887.8      .1       0  4987.4     .07       0
  5006.4      .1       0  5243.3     .05       0
Bank Sta=4987.4,5006.4
XS Rating Curve= 0 ,0
Exp/Cntr=0.3,0.1

Type RM Length L Ch R = 1 ,158005  ,463,463,463
BEGIN DESCRIPTION:
Mapping XS 1ecb96ea
END DESCRIPTION:
XS GIS Cut Line= 4
        2041550.     13519849.99      2041456.83     13519136.91
      2041149.75     13518669.24      2040174.95     13518508.95
#Sta/Elev= 30
  4007.6  489.07  4637.9  487.34  4872.6   485.2  4887.7  485.51  4908.8  484.86
    4939     485    4945  483.99  4954.1  483.78  4960.1  480.63  4968.7  479.01
  4975.2  476.41  4980.7  472.51  4983.2  471.71  4997.2  471.71  4999.7  472.51
  5004.2  475.96  5017.3  478.01  5032.4  477.97  5068.6   476.1  5083.6  476.16
  5098.7   476.8  5125.8  479.68    5156   481.1    5177  483.26  5301.2  486.59
  5437.7  488.53  5462.3  487.83  5645.7  486.23  6023.4  488.03  6274.1  491.07
#Mann= 5 ,-1 , 0
  4007.6     .05       0  4968.7      .1       0  4980.7     .07       0
  4999.7      .1       0  5437.7     .05       0
Bank Sta=4980.7,4999.7
XS Rating Curve= 0 ,0
Exp/Cntr=0.3,0.1

Type RM Length L Ch R = 1 ,157542  ,454,454,454
BEGIN DESCRIPTION:
Mapping XS 2b98bcc4
END DESCRIPTION:
XS GIS Cut Line= 4
      2041669.72     13519243.29      2041579.44     13518526.02
       2041189.9     13518444.63      2040305.11     13518326.65
#Sta/Elev= 30
    4115  487.95  4395.5  486.17  4657.5  485.52  4728.1  486.03  4752.2  485.52
  4862.6  485.28  4917.7  483.11  4934.4   480.9  4944.6  478.02  4954.8  476.61
  4975.3  476.68  4985.5  473.61  4986.2  471.77  4988.7  470.97  5002.7  470.97
  5005.2  471.77  5005.9  473.98  5012.5  476.15  5036.6  476.17  5087.7  480.34
  5179.6  486.08  5220.5  487.85  5238.8  487.53  5424.9  486.76  5523.3  487.29
    5604  485.98  5664.5  486.72  5815.9  486.56  5977.3  488.72  6128.5  492.61
#Mann= 5 ,-1 , 0
    4115     .05       0  4752.2      .1       0  4986.2     .07       0
  5005.2      .1       0  5238.8     .05       0
Bank Sta=4986.2,5005.2
XS Rating Curve= 0 ,0
Exp/Cntr=0.3,0.1

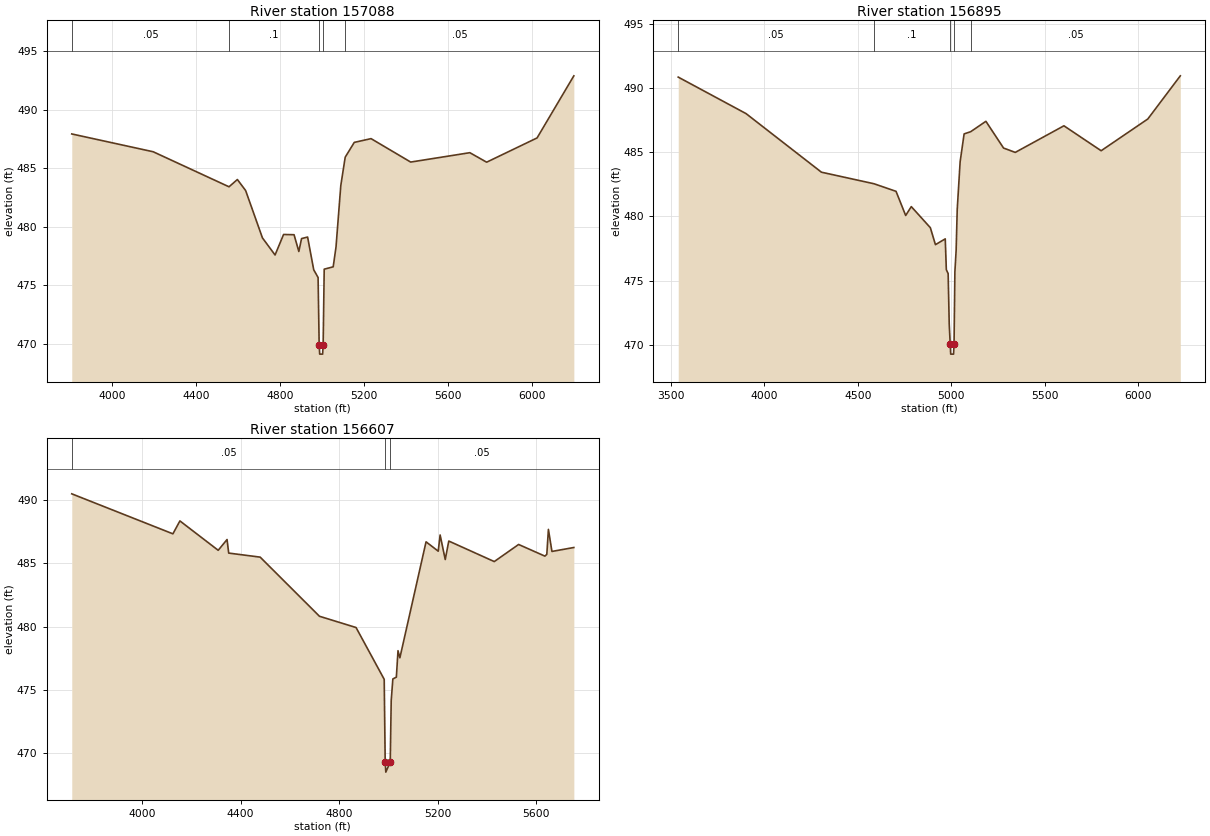
Type RM Length L Ch R = 1 ,157088  ,193,193,193
BEGIN DESCRIPTION:
Mapping XS 66557395
END DESCRIPTION:
XS GIS Cut Line= 4
      2041742.64     13519222.53      2041739.27     13518222.18
      2041426.77      13517985.2      2040430.09     13517962.07
#Sta/Elev= 30
  3809.7  487.92  4197.2   486.4    4558  483.41  4597.9  484.03  4637.2  483.09
  4717.2  479.05  4777.2  477.59  4817.7  479.34  4867.6  479.32  4890.4  477.89
  4903.3  478.99  4932.1  479.12  4961.2  476.33    4982  475.67  4987.1  469.93
  4989.6  469.13  5003.6  469.13  5006.1  469.93  5011.1  476.38  5053.9  476.58
  5067.3  478.27  5090.1  483.52  5111.1  485.94  5154.3   487.2    5234  487.52
  5422.7  485.52  5704.2  486.32  5784.2  485.51  6024.2  487.58  6199.2  492.88
#Mann= 5 ,-1 , 0
  3809.7     .05       0    4558      .1       0  4987.1     .07       0
  5006.1      .1       0  5111.1     .05       0
Bank Sta=4987.1,5006.1
XS Rating Curve= 0 ,0
Exp/Cntr=0.3,0.1

Type RM Length L Ch R = 1 ,156895  ,288,288,288
BEGIN DESCRIPTION:
Mapping XS 63b09613
END DESCRIPTION:
XS GIS Cut Line= 4
      2042555.14     13519019.36      2042301.77     13518326.34
      2041499.69     13517844.57      2040529.54     13517550.75
#Sta/Elev= 30
  3538.6  490.84  3901.5     488    4305  483.44  4586.4  482.54  4704.3  481.95
  4755.9  480.07    4786  480.76    4888  479.12  4915.2   477.8  4967.7  478.25
  4973.5  475.85  4983.2  475.55    4989  471.62  4994.3  470.08  4996.8  469.28
  5012.3  469.28  5014.8  470.08  5019.3  475.69    5026  477.36  5031.8  480.53
  5047.3  484.24  5068.7  486.42  5103.6  486.59  5185.3   487.4  5279.7  485.32
  5342.4  484.98  5602.9  487.05  5802.1  485.11  6051.8  487.58  6225.8  490.94
#Mann= 5 ,-1 , 0
  3538.6     .05       0  4586.4      .1       0  4994.3     .07       0
  5014.8      .1       0  5103.6     .05       0
Bank Sta=4994.3,5014.8
XS Rating Curve= 0 ,0
Exp/Cntr=0.3,0.1

Type RM Length L Ch R = 1 ,156607  ,67,67,67
BEGIN DESCRIPTION:
Mapping XS 35f4afe4
END DESCRIPTION:
XS GIS Cut Line= 5
      2042805.15     13518774.58      2042080.96     13517975.15
      2041955.09      13517869.9      2041806.44     13517737.52
      2041351.99     13517352.68
#Sta/Elev= 30
    3715  490.48  4125.4  487.32  4153.8  488.34  4309.2  486.02  4345.1  486.87
  4351.8   485.8  4479.5  485.48  4720.1  480.81  4868.6  479.92  4982.8  475.83
  4986.8   469.3  4989.3   468.5  5007.3   469.3  5011.2  474.15  5017.9  475.86
  5032.1     476  5038.8  478.09  5046.4  477.53  5152.6  486.69    5202  485.95
  5209.7  487.23  5230.5  485.29  5244.8  486.75  5429.4  485.13  5528.2  486.48
  5634.8  485.56  5642.6   485.7  5649.1  487.67  5663.4  485.93  5752.3  486.24
#Mann= 3 ,-1 , 0
    3715     .05       0  4986.8     .04       0  5007.3     .05       0
Bank Sta=4986.8,5007.3
XS Rating Curve= 0 ,0
Exp/Cntr=0.3,0.1