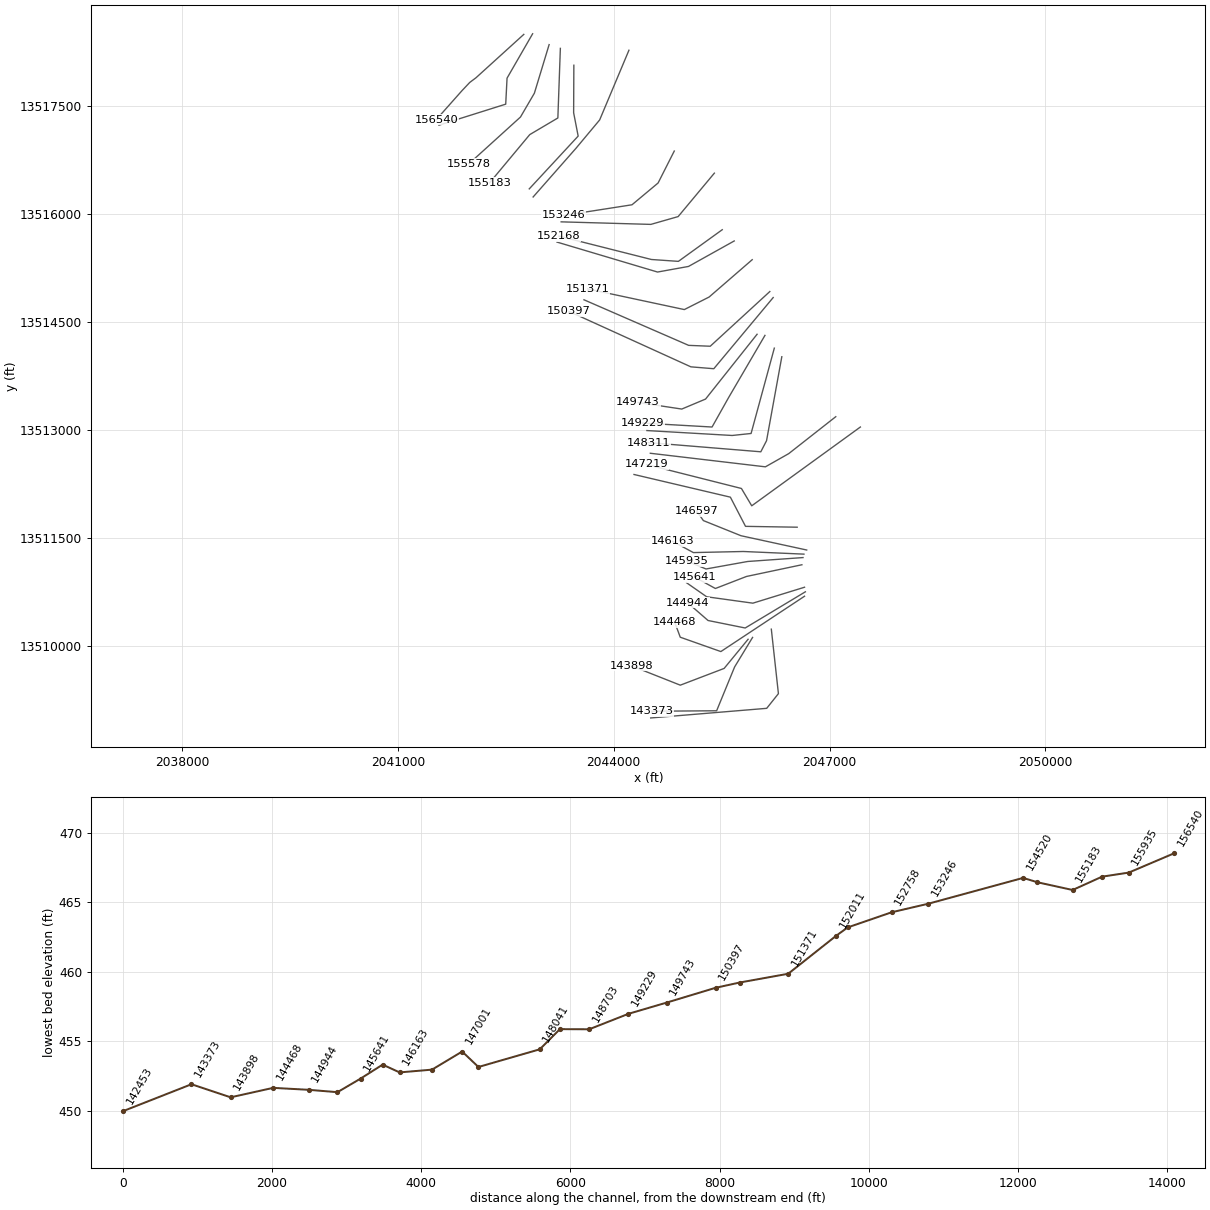
HEC-RAS study LAGUNILLAS Cr.prj: LAGUNILLAS Cr Base Level Engineering

--- LAGUNILLAS Cr.g01 (geometry) --- (continued)

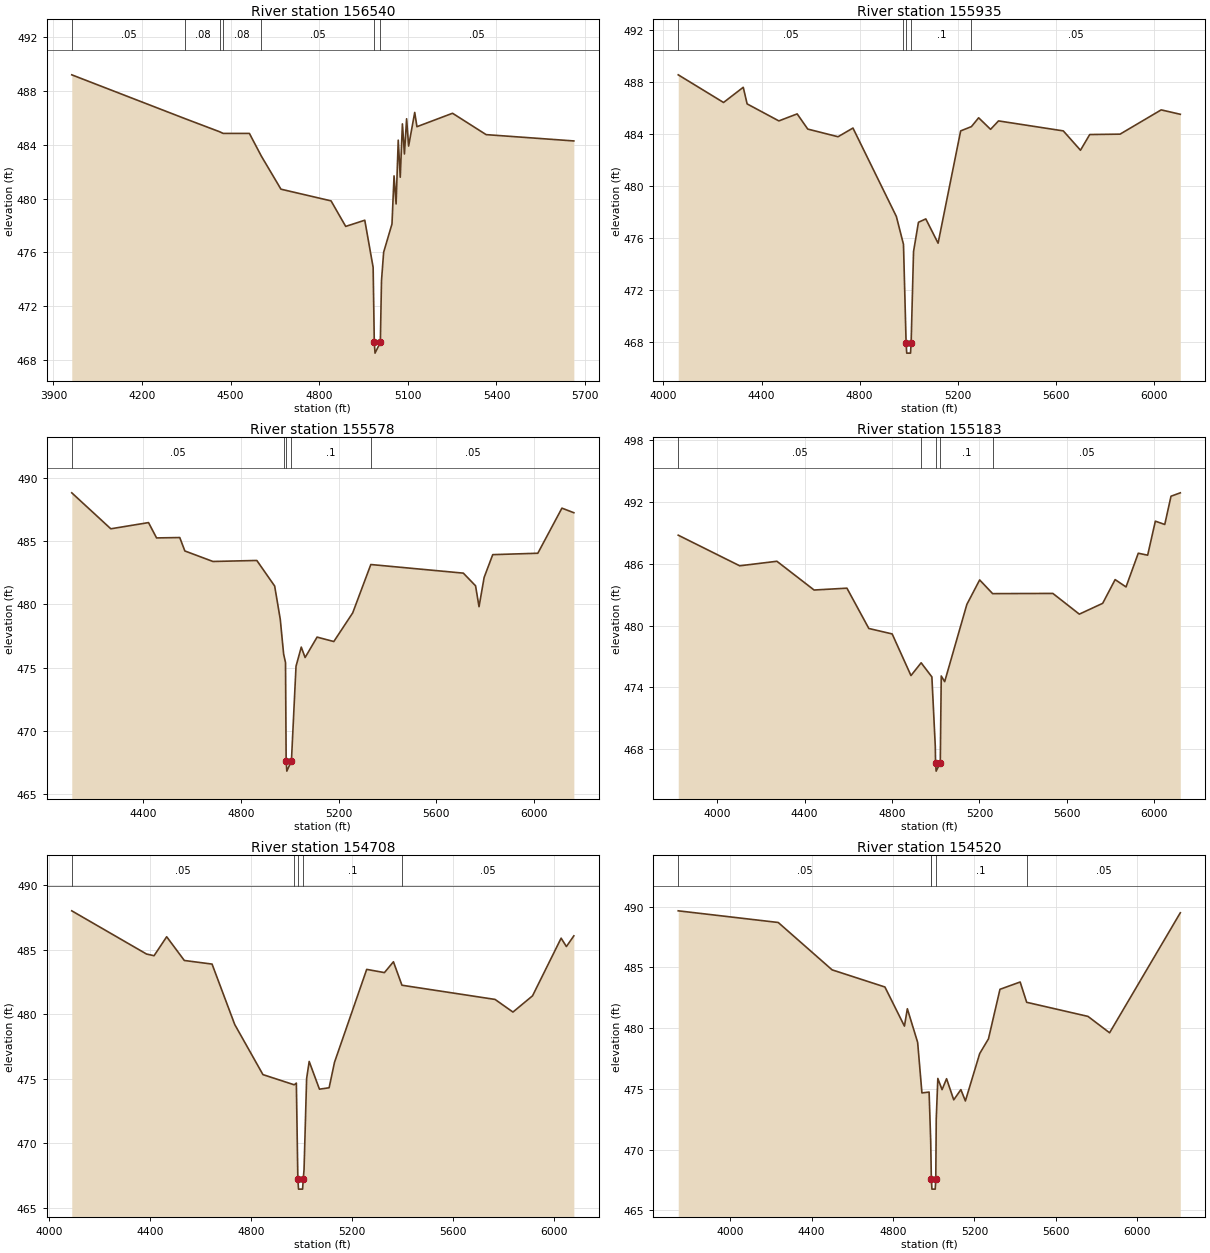
Type RM Length L Ch R = 1 ,156540  ,605,605,605
BEGIN DESCRIPTION:
Mapping XS fb0fa72f
END DESCRIPTION:
XS GIS Cut Line= 5
      2042749.97     13518499.97       2042085.3     13517897.02
      2041998.49     13517831.92      2041891.07     13517717.99
       2041534.3     13517316.23
#Sta/Elev= 30
  3962.2  489.22  4345.5  485.96  4463.2  484.98  4474.7  484.86  4563.6  484.86
  4603.8  483.18  4670.4  480.71    4840  479.84  4889.6  477.94  4954.2   478.4
  4982.5  474.89  4986.4  469.31  4988.9  468.51  5006.9  469.31  5010.8  473.91
  5018.1  476.02  5046.3  478.12  5053.3   481.7  5060.2  479.61  5067.5  484.36
  5074.3   481.6  5081.6  485.57  5088.5  483.33  5095.8  485.95  5102.6  483.92
  5123.3  486.42  5130.8  485.36  5251.3  486.36    5365  484.77    5662   484.3
#Mann= 7 ,-1 , 0
  3962.2     .05       0  4345.5     .08       0  4463.2     .05       0
  4474.7     .08       0  4603.8     .05       0  4986.4     .04       0
  5006.9     .05       0
Bank Sta=4986.4,5006.9
XS Rating Curve= 0 ,0
Exp/Cntr=0.3,0.1

Type RM Length L Ch R = 1 ,155935  ,357,357,357
BEGIN DESCRIPTION:
Mapping XS 33fd90d1
END DESCRIPTION:
XS GIS Cut Line= 4
      2042872.83     13518508.91      2042517.16      13517891.6
      2042498.71     13517530.27      2041570.76     13517238.11
#Sta/Elev= 30
  4060.2  488.57  4244.9  486.44  4325.3  487.61  4341.1  486.33  4470.5  485.02
  4545.1  485.56  4588.3  484.39  4711.8   483.8  4772.6  484.47  4949.5  477.66
  4978.6  475.51  4989.3  467.93  4991.8  467.13  5007.3  467.13  5009.8  467.93
  5019.6  474.95  5039.6  477.21  5069.6  477.47  5119.7   475.6  5211.7  484.25
  5255.6  484.58  5285.1  485.26  5333.7  484.37  5366.1  485.02  5630.3  484.25
  5700.3  482.76  5737.9  483.97  5861.7     484  6029.3  485.87  6107.3  485.53
#Mann= 5 ,-1 , 0
  4060.2     .05       0  4978.6      .1       0  4989.3     .07       0
  5009.8      .1       0  5255.6     .05       0
Bank Sta=4989.3,5009.8
XS Rating Curve= 0 ,0
Exp/Cntr=0.3,0.1

Type RM Length L Ch R = 1 ,155578  ,395,395,395
BEGIN DESCRIPTION:
Mapping XS c013cfb0
END DESCRIPTION:
XS GIS Cut Line= 4
      2043102.01      13518357.9      2042896.93     13517682.18
      2042703.79     13517351.23      2041988.73     13516702.83
#Sta/Elev= 30
  4108.3  488.81  4268.1  485.97  4422.4  486.46  4455.3  485.25  4550.2  485.28
  4571.1  484.22  4686.1  483.39  4865.6  483.47  4938.6  481.45  4961.5  478.83
  4975.3  476.08    4983  475.41  4985.6  467.64  4988.4  466.84  5007.2  467.64
    5026  475.12  5047.5  476.63  5063.2  475.81  5112.2  477.42  5180.6  477.07
  5257.9  479.33  5332.1  483.15  5710.7  482.47  5760.7  481.47  5774.9  479.82
  5795.8  482.13    5831  483.93  6015.5  484.04  6114.1   487.6  6162.9  487.24
#Mann= 5 ,-1 , 0
  4108.3     .05       0  4975.3      .1       0  4985.6     .07       0
  5007.2      .1       0  5332.1     .05       0
Bank Sta=4985.6,5007.2
XS Rating Curve= 0 ,0
Exp/Cntr=0.3,0.1

Type RM Length L Ch R = 1 ,155183  ,475,475,475
BEGIN DESCRIPTION:
Mapping XS fe5af2a2
END DESCRIPTION:
XS GIS Cut Line= 4
      2043258.27     13518305.81      2043223.54     13517338.21
      2042832.91     13517107.09      2042273.89     13516436.03
#Sta/Elev= 30
  3822.7  488.77  4103.7   485.8  4273.8  486.24  4443.9  483.45    4594  483.63
  4694.1  479.72  4800.8  479.19  4886.8  475.15  4933.3  476.39  4982.4  475.02
    4998  468.26  4999.2  466.68  5001.9  465.88  5020.8  466.68  5025.2  475.11
  5040.9  474.56  5142.2  482.05  5200.8  484.43  5260.1   483.1  5535.5  483.12
  5656.5  481.11  5763.3  482.16  5820.2  484.46    5870  483.75    5926  487.02
  5968.9  486.83  6004.1  490.13  6047.1  489.81  6075.7  492.55  6118.2  492.88
#Mann= 5 ,-1 , 0
  3822.7     .05       0  4933.3      .1       0  4999.2     .07       0
  5020.8      .1       0  5260.1     .05       0
Bank Sta=4999.2,5020.8
XS Rating Curve= 0 ,0
Exp/Cntr=0.3,0.1

Type RM Length L Ch R = 1 ,154708  ,188,188,188
BEGIN DESCRIPTION:
Mapping XS 509e0947
END DESCRIPTION:
XS GIS Cut Line= 4
      2043445.77     13518071.44      2043442.72     13517410.91
      2043505.65     13517086.48      2042825.98     13516352.71
#Sta/Elev= 30
  4088.5  488.02  4384.9  484.67  4414.9  484.54  4464.9  486.01  4534.9  484.17
  4644.9  483.89  4734.9   479.2  4846.7  475.32  4970.6  474.53  4979.2  474.66
  4985.1  467.24  4987.8  466.44  5003.9  466.44  5006.7  467.24  5009.7  467.96
  5019.9  475.01  5030.1  476.34  5070.8  474.19  5109.1   474.3  5130.6  476.28
  5258.2  483.48  5328.5  483.23  5364.2  484.07    5398  482.25  5767.3  481.15
  5838.2  480.17  5915.9  481.43  6029.3   485.9  6050.2  485.25  6079.7  486.08
#Mann= 5 ,-1 , 0
  4088.5     .05       0  4970.6      .1       0  4985.1     .07       0
  5006.7      .1       0    5398     .05       0
Bank Sta=4985.1,5006.7
XS Rating Curve= 0 ,0
Exp/Cntr=0.3,0.1

Type RM Length L Ch R = 1 ,154520  ,1274,1274,1274
BEGIN DESCRIPTION:
Mapping XS a8eba8e9
END DESCRIPTION:
XS GIS Cut Line= 4
       2044211.4     13518279.79      2043804.37     13517310.72
      2043473.64     13516914.88      2042879.85     13516240.15
#Sta/Elev= 30
  3745.4  489.66  4236.5   488.7  4501.1   484.8  4760.4  483.39  4856.3  480.17
  4870.6   481.6  4921.2  478.83  4942.2  474.67  4977.4  474.74  4985.2  470.75
    4988  468.03  4988.5  467.55  4991.3  466.75  5007.5  466.75  5010.2  467.55
  5012.5  472.53  5020.3  475.86  5041.1  474.94  5063.2  475.84  5098.4   474.1
  5133.5  474.94  5155.6  474.01  5225.9  477.91  5268.9  479.12  5325.5   483.2
  5424.6   483.8  5456.6  482.13  5757.6  480.97  5863.8  479.62  6211.1   489.5
#Mann= 5 ,-1 , 0
  3745.4     .05       0    4988      .1       0  4988.5     .07       0
  5010.2      .1       0  5456.6     .05       0
Bank Sta=4988.5,5010.2
XS Rating Curve= 0 ,0
Exp/Cntr=0.3,0.1

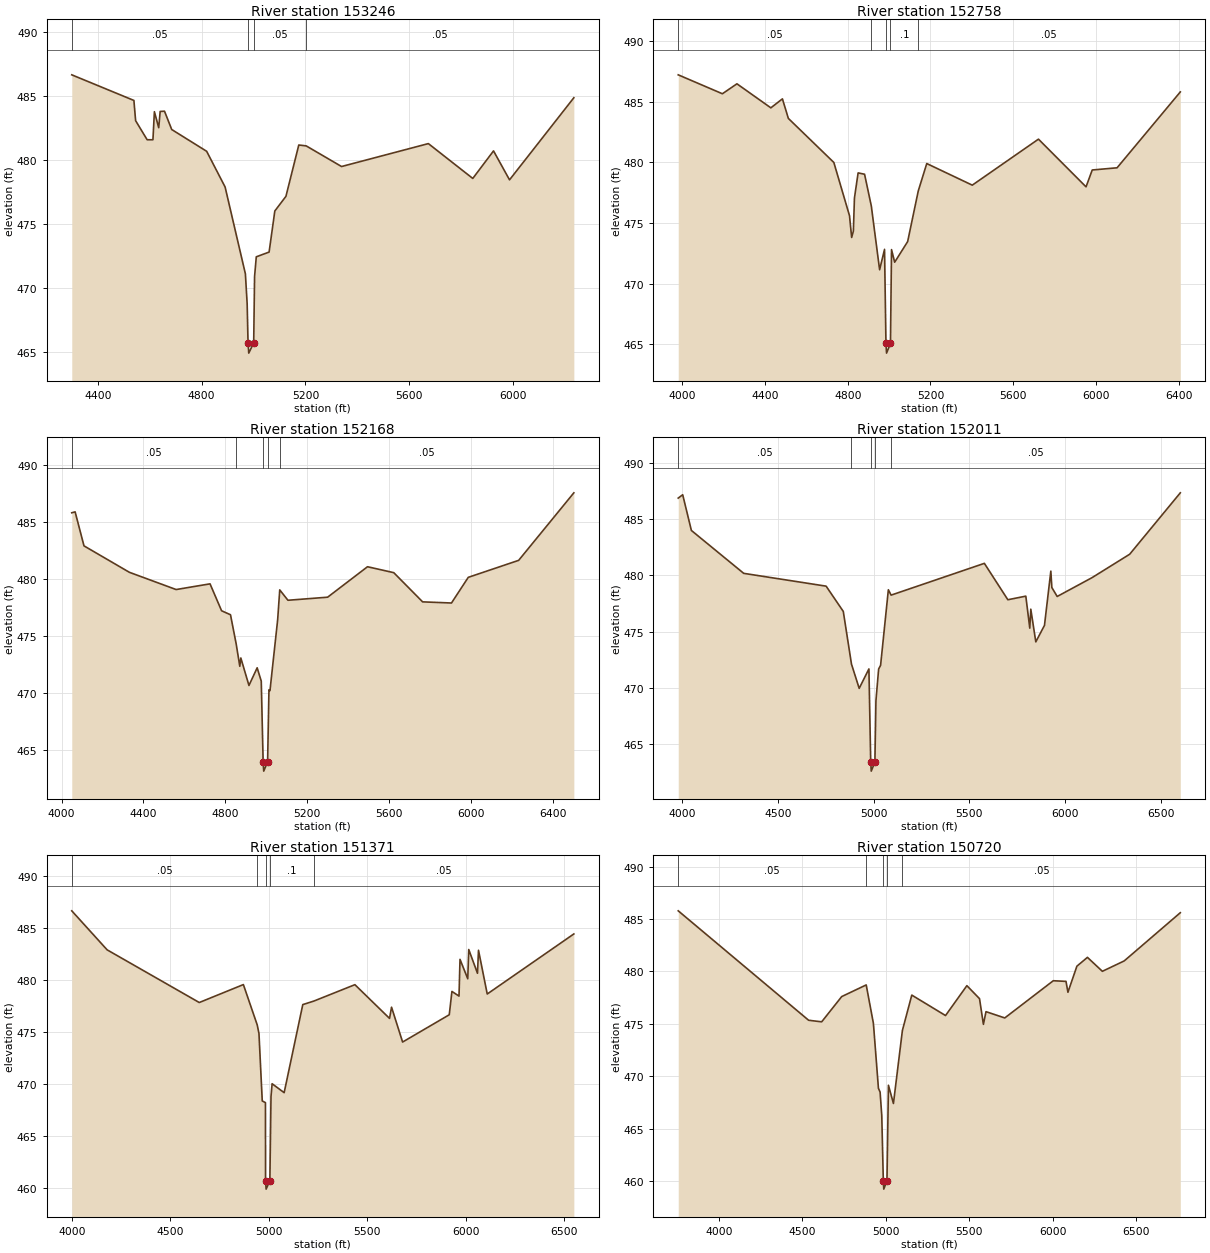
Type RM Length L Ch R = 1 ,153246  ,488,488,488
BEGIN DESCRIPTION:
Mapping XS aea43c7a
END DESCRIPTION:
XS GIS Cut Line= 4
      2044841.61     13516878.76      2044616.77     13516434.57
      2044253.92     13516131.61      2043299.98     13515982.92
#Sta/Elev= 30
  4299.1  486.62  4538.7  484.62  4545.3  483.04  4589.8  481.55  4612.1  481.55
  4617.7  483.74  4634.4  482.49    4640  483.76  4656.7  483.78  4684.5  482.35
  4819.2  480.65  4890.4  477.86  4968.6  471.08  4975.4  468.75  4978.8  465.69
  4981.6  464.89  5000.6  465.69    5004  470.87  5010.6  472.41    5060  472.78
  5082.1  475.99  5124.9  477.13  5174.5  481.14  5203.2  481.07  5339.4  479.46
  5674.1  481.25  5845.4  478.53  5925.4  480.68  5987.1  478.42  6235.1  484.83
#Mann= 4 ,-1 , 0
  4299.1     .05       0  4978.8     .07       0  5000.6     .05       0
  5203.2     .05       0
Bank Sta=4978.8,5000.6
XS Rating Curve= 0 ,0
Exp/Cntr=0.3,0.1

Type RM Length L Ch R = 1 ,152758  ,590,590,590
BEGIN DESCRIPTION:
Mapping XS 9a6026f9
END DESCRIPTION:
XS GIS Cut Line= 4
      2045398.91     13516571.47      2044895.41     13515967.55
      2044516.07     13515859.04       2043269.3     13515894.35
#Sta/Elev= 30
  3980.1  487.21  4193.7  485.65    4264  486.47    4428  484.49    4484  485.23
  4512.6  483.62  4732.6  479.99  4808.4   475.6  4818.8  473.81  4827.1  474.33
  4832.3  477.06    4850  479.13  4881.2  479.02  4913.8  476.41    4954  471.15
  4977.8  472.83  4984.7  465.08  4987.5  464.28  5006.5  465.08  5011.6  472.81
  5026.8  471.77  5089.6  473.47  5140.9  477.64    5182   479.9  5402.1  478.12
  5722.2  481.91  5952.3  477.98  5982.3  479.37  6102.4  479.55  6408.2   485.8
#Mann= 5 ,-1 , 0
  3980.1     .05       0  4913.8      .1       0  4984.7     .07       0
  5006.5      .1       0  5140.9     .05       0
Bank Sta=4984.7,5006.5
XS Rating Curve= 0 ,0
Exp/Cntr=0.3,0.1

Type RM Length L Ch R = 1 ,152168  ,157,157,157
BEGIN DESCRIPTION:
Mapping XS a243036f
END DESCRIPTION:
XS GIS Cut Line= 4
      2045508.27     13515784.99      2044898.88     13515345.16
      2044523.88      13515371.2      2043238.76     13515696.11
#Sta/Elev= 30
  4049.9  485.84  4066.3  485.92  4109.6  482.94  4331.6  480.62  4559.8  479.11
  4725.4  479.61  4781.9  477.25  4825.4   476.9    4853  474.36  4870.9  472.38
  4875.9  473.11  4915.6   470.7  4955.7  472.25  4975.7  471.08  4984.9  463.99
  4987.7  463.19  5006.7  463.99  5013.3  470.32  5018.3  470.25  5055.9  476.48
    5066  479.08  5106.1  478.17    5300  478.44  5494.8  481.11  5623.1  480.59
  5764.1  478.03  5905.1  477.93  5987.1  480.18  6233.3  481.67  6502.9  487.59
#Mann= 5 ,-1 , 0
  4049.9     .05       0    4853      .1       0  4984.9     .07       0
  5006.7      .1       0    5066     .05       0
Bank Sta=4984.9,5006.7
XS Rating Curve= 0 ,0
Exp/Cntr=0.3,0.1

Type RM Length L Ch R = 1 ,152011  ,640,640,640
BEGIN DESCRIPTION:
Mapping XS d0573819
END DESCRIPTION:
XS GIS Cut Line= 4
      2045674.97     13515628.76      2045039.52     13515274.58
      2044608.95     13515196.72      2043211.41     13515613.11
#Sta/Elev= 30
  3979.1  486.89  4002.4  487.19  4047.8  484.01  4321.3  480.19  4751.8  479.05
  4841.5   476.8  4884.3  472.11  4924.6  469.95  4975.4  471.68  4984.8  463.38
  4987.6  462.58  5006.6  463.38  5012.1  468.85  5026.2  471.67  5036.4     472
    5077  478.73  5091.3  478.25  5578.6  481.08  5701.3  477.84  5795.2  478.16
  5815.9  475.31  5821.2     477  5847.4  474.09  5892.7  475.56  5925.9  480.39
  5931.1  478.93    5959  478.13  6140.5   479.8  6337.8  481.89  6602.4  487.36
#Mann= 5 ,-1 , 0
  3979.1     .05       0  4884.3      .1       0  4984.8     .07       0
  5006.6      .1       0  5091.3     .05       0
Bank Sta=4984.8,5006.6
XS Rating Curve= 0 ,0
Exp/Cntr=0.3,0.1

Type RM Length L Ch R = 1 ,151371  ,651,651,651
BEGIN DESCRIPTION:
Mapping XS 532d4712
END DESCRIPTION:
XS GIS Cut Line= 4
      2045924.95     13515368.34      2045325.97      13514849.5
      2044981.35     13514675.02      2043639.19     13514961.92
#Sta/Elev= 30
  3999.1  486.69  4178.7  482.93    4647  477.85  4871.1  479.58  4941.3   475.7
  4950.3  474.87    4967  468.36  4983.2   468.2  4983.9  460.66  4986.7  459.86
  5005.7  460.66  5011.5  468.79  5017.1  470.02  5078.3  469.16    5173  477.65
  5229.3  477.99  5437.8  479.57  5613.8  476.32    5624   477.4  5680.2  474.04
  5917.3  476.67  5930.8  478.92  5966.8  478.47  5971.9  482.01  6011.2  480.14
  6016.3  482.96  6060.7  480.67  6065.8  482.89  6110.2  478.67  6550.3  484.46
#Mann= 5 ,-1 , 0
  3999.1     .05       0  4941.3      .1       0  4983.9     .07       0
  5005.7      .1       0  5229.3     .05       0
Bank Sta=4983.9,5005.7
XS Rating Curve= 0 ,0
Exp/Cntr=0.3,0.1

Type RM Length L Ch R = 1 ,150720  ,323,323,323
BEGIN DESCRIPTION:
Mapping XS 555c92f3
END DESCRIPTION:
XS GIS Cut Line= 4
      2046169.72     13514925.61      2045341.59     13514165.47
      2045041.24     13514177.62      2043586.36     13514811.05
#Sta/Elev= 30
    3755  485.78  4537.1  475.34  4615.4  475.19  4735.6   477.6  4882.5  478.71
  4925.7  475.04  4955.8  468.85  4965.8  468.49  4975.8  466.25  4985.1  460.03
  4987.9  459.23    5007  460.03  5015.8  469.14  5045.8   467.4  5099.6  474.37
  5155.9  477.74  5358.3  475.79  5486.4  478.64  5562.1   477.4  5585.5  474.95
    5601  476.16  5713.6  475.56  6004.5  479.11  6080.9  479.05  6092.4  478.01
  6146.3   480.5  6209.5  481.34    6299  480.01  6429.9     481  6766.5   485.6
#Mann= 5 ,-1 , 0
    3755     .05       0  4882.5      .1       0  4985.1     .07       0
    5007      .1       0  5099.6     .05       0
Bank Sta=4985.1,5007
XS Rating Curve= 0 ,0
Exp/Cntr=0.3,0.1

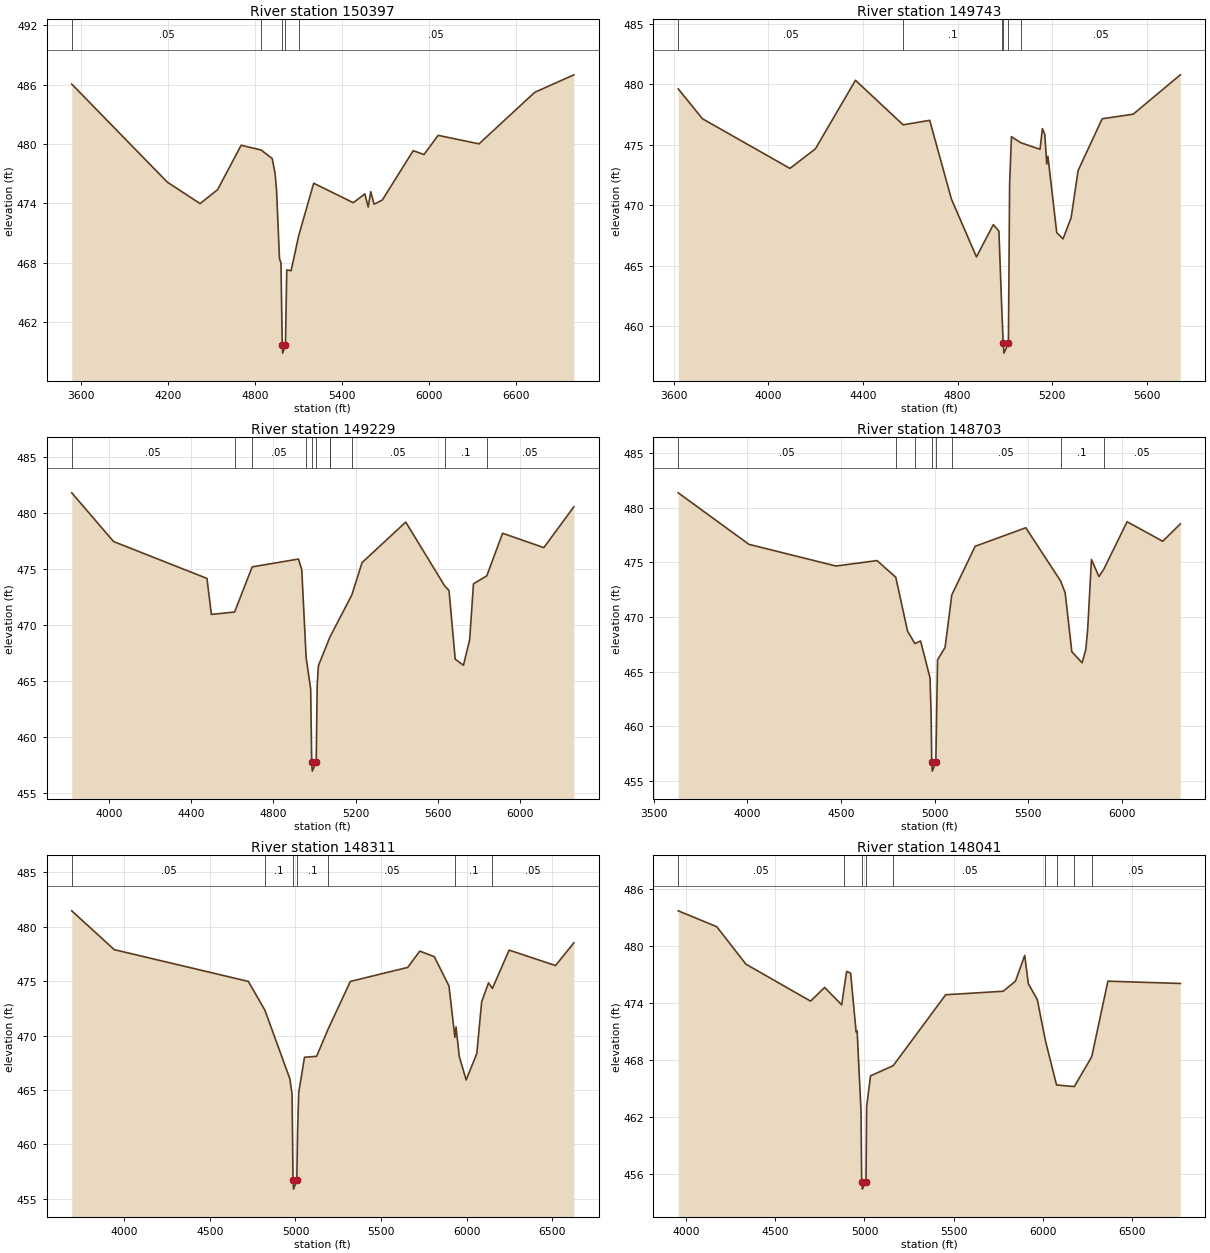
Type RM Length L Ch R = 1 ,150397  ,654,654,654
BEGIN DESCRIPTION:
Mapping XS 956a3c8b
END DESCRIPTION:
XS GIS Cut Line= 4
      2046216.57     13514842.25      2045391.07     13513852.97
      2045072.49     13513879.01      2043378.99     13514649.15
#Sta/Elev= 30
  3533.6  486.05  4193.6  476.14    4420  473.97  4541.1  475.38  4703.8  479.87
  4841.5  479.39  4918.5  478.52  4938.5  476.99  4948.6  475.25  4968.6   468.4
  4978.7  467.98  4987.8  459.65  4990.6  458.85  5009.7  459.65  5018.8  467.26
  5048.9  467.19  5101.3  470.72  5204.9  476.03  5478.1  474.06  5558.3  474.95
  5581.4  473.62    5599  475.17    5622  473.91  5679.1  474.33  5892.2  479.32
  5966.9  478.93  6064.6  480.87  6346.9  480.01  6731.8  485.22  7002.1  486.99
#Mann= 5 ,-1 , 0
  3533.6     .05       0  4841.5      .1       0  4987.8     .07       0
  5009.7      .1       0  5101.3     .05       0
Bank Sta=4987.8,5009.7
XS Rating Curve= 0 ,0
Exp/Cntr=0.3,0.1

Type RM Length L Ch R = 1 ,149743  ,514,514,514
BEGIN DESCRIPTION:
Mapping XS 8a22c8e7
END DESCRIPTION:
XS GIS Cut Line= 4
      2045992.62     13514331.84      2045276.49     13513431.09
      2044945.76      13513292.2      2044338.15     13513383.69
#Sta/Elev= 30
  3618.4  479.62    3721  477.15    4091  473.05  4198.4  474.66  4368.1  480.33
  4569.8  476.65  4682.1  477.02  4774.1  470.51  4879.9  465.74  4951.2   468.4
    4975  467.87  4986.3  461.81  4993.2  458.59  4996.1  457.79  5015.1  458.59
  5020.2  471.71  5027.9  475.67  5067.7  475.17  5148.8  474.63    5159  476.34
  5169.1  475.85  5177.2  473.42  5182.2  474.05  5219.6  467.74  5246.1  467.23
  5280.3  468.96  5310.1  472.88  5411.8  477.15  5543.2  477.53  5742.3  480.78
#Mann= 6 ,-1 , 0
  3618.4     .05       0  4569.8      .1       0  4986.3     .07       0
  4993.2     .07       0  5015.1     .07       0  5067.7     .05       0
Bank Sta=4993.2,5015.1
XS Rating Curve= 0 ,0
Exp/Cntr=0.3,0.1

Type RM Length L Ch R = 1 ,149229  ,526,526,526
BEGIN DESCRIPTION:
Mapping XS b2e93f7c
END DESCRIPTION:
XS GIS Cut Line= 4
      2046102.03     13514316.26      2045593.44     13513446.13
      2045366.87     13513042.49      2044399.47     13513097.46
#Sta/Elev= 30
  3820.1  481.82  4023.3  477.47    4477  474.18  4498.5  470.97  4611.3  471.18
  4696.8  475.21  4921.7  475.91  4937.7  474.96  4958.9  467.12    4981  464.31
    4986  457.78  4988.9  456.98  5007.9  457.78  5012.7  464.71  5018.7   466.4
  5073.7  468.91    5074  468.93  5180.9   472.7  5230.6  475.59    5443  479.21
    5632  473.52  5653.3   473.1  5683.3  466.97  5723.4  466.43  5753.5  468.71
  5772.1   473.7  5836.7  474.41  5913.7  478.21    6114  476.93  6259.8  480.57
#Mann= 11 ,-1 , 0
  3820.1     .05       0  4611.3      .1       0  4696.8     .05       0
  4958.9      .1       0    4986     .07       0  5007.9      .1       0
  5073.7     .12       0    5074      .1       0  5180.9     .05       0
    5632      .1       0  5836.7     .05       0
Bank Sta=4986,5007.9
XS Rating Curve= 0 ,0
Exp/Cntr=0.3,0.1

Type RM Length L Ch R = 1 ,148703  ,392,392,392
BEGIN DESCRIPTION:
Mapping XS df19ae9c
END DESCRIPTION:
XS GIS Cut Line= 4
      2046232.23     13514139.16       2045909.3     13512952.79
      2045646.28     13512925.02      2044461.36     13512993.33
#Sta/Elev= 30
  3631.2  481.38  4008.6  476.66  4473.6  474.67  4692.6  475.17  4792.9  473.64
  4855.7   468.7    4895  467.56  4925.4   467.8  4975.7  464.41  4981.6  461.02
  4984.8  456.67  4987.7  455.87  5006.7  456.67  5015.9  466.07  5056.1  467.21
  5092.1  472.03  5216.7  476.48  5487.1  478.18    5673   473.3  5697.4  472.21
  5732.8  466.82  5787.6   465.8  5807.6  467.02  5817.6  468.89  5837.7  475.27
  5877.7   473.7  5903.6  474.38    6028  478.73  6218.3  476.94  6312.1  478.53
#Mann= 8 ,-1 , 0
  3631.2     .05       0  4792.9      .1       0    4895     .12       0
  4984.8     .07       0  5006.7     .12       0  5092.1     .05       0
    5673      .1       0  5903.6     .05       0
Bank Sta=4984.8,5006.7
XS Rating Curve= 0 ,0
Exp/Cntr=0.3,0.1

Type RM Length L Ch R = 1 ,148311  ,270,270,270
BEGIN DESCRIPTION:
Mapping XS c732034d
END DESCRIPTION:
XS GIS Cut Line= 4
      2046336.39     13514019.34      2046124.32     13512853.01
      2046044.46     13512698.15       2044478.5     13512826.54
#Sta/Elev= 30
  3694.3  481.46  3942.6  477.89  4725.3  474.97  4821.7  472.33  4967.5  466.02
  4980.4  464.59    4986  456.68  4988.9  455.88  5007.9  456.68  5012.5  461.16
  5019.1  464.75  5052.9     468  5123.7  468.09  5189.7  470.55  5320.4  474.97
  5655.5  476.26  5725.7  477.76  5810.9  477.24  5896.3  474.55  5930.8  469.83
  5937.4  470.79  5956.5  468.07  5996.6  465.92  6058.7  468.34  6086.9  473.08
    6127  474.84  6149.9  474.33  6247.4  477.85  6518.3  476.43  6625.2  478.52
#Mann= 7 ,-1 , 0
  3694.3     .05       0  4821.7      .1       0    4986     .07       0
  5007.9      .1       0  5189.7     .05       0  5930.8      .1       0
  6149.9     .05       0
Bank Sta=4986,5007.9
XS Rating Curve= 0 ,0
Exp/Cntr=0.3,0.1

Type RM Length L Ch R = 1 ,148041  ,822,822,822
BEGIN DESCRIPTION:
Mapping XS 91fc2287
END DESCRIPTION:
XS GIS Cut Line= 4
      2047086.39     13513186.04      2046432.56     13512672.75
      2046108.35     13512489.16      2044508.86     13512677.77
#Sta/Elev= 30
    3956  483.74  4171.9  482.07  4335.5  478.12    4698  474.23  4776.6  475.67
  4872.3  473.84  4883.8  475.35  4899.7  477.35  4922.3  477.19  4953.1  470.99
  4958.9  471.09  4980.5  462.69  4984.3  455.23    4988  454.43  5008.5  455.23
  5012.3  463.15  5033.9  466.36  5160.9  467.43  5455.2   474.9  5777.4  475.27
  5846.5  476.33  5898.3  479.05  5918.4  476.07  5968.7  474.39  6014.6  470.04
  6076.6   465.4    6176  465.23  6273.9  468.37  6364.5  476.33  6770.4  476.09
#Mann= 9 ,-1 , 0
    3956     .05       0  4883.8      .1       0  4984.3     .07       0
  5008.5      .1       0  5160.9     .05       0  6014.6      .1       0
  6076.6     .05       0    6176      .1       0  6273.9     .05       0
Bank Sta=4984.3,5008.5
XS Rating Curve= 0 ,0
Exp/Cntr=0.3,0.1

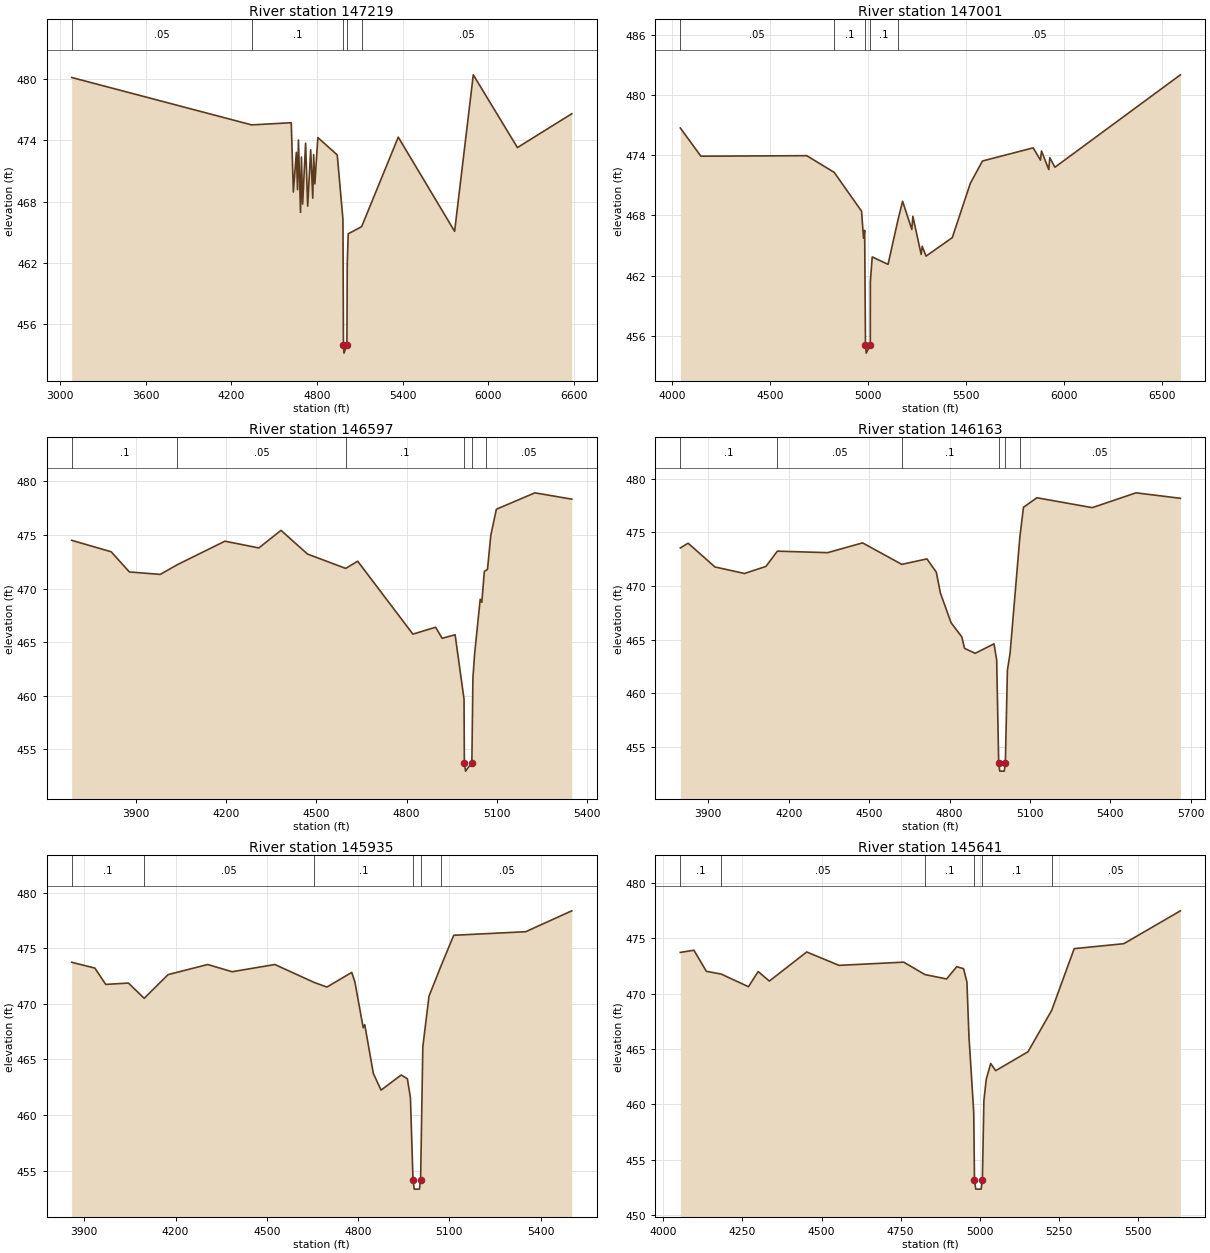
Type RM Length L Ch R = 1 ,147219  ,218,218,218
BEGIN DESCRIPTION:
Mapping XS bb8f6454
END DESCRIPTION:
XS GIS Cut Line= 4
      2047428.33     13513042.58      2045918.24     13511947.49
      2045775.01     13512188.38      2044455.57     13512521.66
#Sta/Elev= 30
  3079.9  480.14  4342.1   475.5  4619.6  475.71  4634.3  468.93  4655.2  472.81
  4663.7  469.16  4669.9  474.02  4684.6  466.94  4690.8  472.36  4699.3  467.75
  4720.1  473.71  4734.8  467.55  4755.7  473.06  4770.4  468.33  4776.6   472.6
  4785.1  469.73    4806  474.26    4942  472.56    4982  466.26  4985.5  453.96
  4989.2  453.16  5009.7  453.96  5012.2  461.92    5019  464.84  5113.1  465.54
  5369.9   474.3    5765  465.08  5895.9   480.4  6205.4  473.28  6586.4  476.59
#Mann= 5 ,-1 , 0
  3079.9     .05       0  4342.1      .1       0  4985.5     .07       0
  5009.7      .1       0  5113.1     .05       0
Bank Sta=4985.5,5009.7
XS Rating Curve= 0 ,0
Exp/Cntr=0.3,0.1

Type RM Length L Ch R = 1 ,147001  ,404,404,404
BEGIN DESCRIPTION:
Mapping XS 4ddc7561
END DESCRIPTION:
XS GIS Cut Line= 4
        2046550.       13511650.      2045831.87     13511661.83
      2045621.37     13512067.64      2044281.93     13512382.78
#Sta/Elev= 30
  4041.6  476.71  4146.6   473.9  4686.7  473.95  4826.6  472.29  4966.2  468.42
  4976.4  465.72  4982.1  466.51  4986.3  455.07  4990.1  454.27  5010.9  455.07
  5011.2  461.42  5020.7  463.86  5101.4  463.12  5152.7   467.6  5175.6  469.41
  5222.8   466.6    5228  467.91  5270.4  464.11  5275.5  464.92  5295.4  463.94
    5429  465.78  5521.5  471.21  5583.1  473.42  5841.8  474.73  5879.1  473.51
  5884.2  474.42  5921.4  472.57  5926.6  473.75  5952.9   472.8    6593  482.01
#Mann= 5 ,-1 , 0
  4041.6     .05       0  4826.6      .1       0  4986.3     .07       0
  5010.9      .1       0  5152.7     .05       0
Bank Sta=4986.3,5010.9
XS Rating Curve= 0 ,0
Exp/Cntr=0.3,0.1

Type RM Length L Ch R = 1 ,146597  ,434,434,434
BEGIN DESCRIPTION:
Mapping XS 05f02a13
END DESCRIPTION:
XS GIS Cut Line= 4
      2046682.25     13511332.94      2045768.94     13511531.62
      2045245.93     13511742.12      2045152.62     13511874.49
#Sta/Elev= 30
  3687.9   474.5  3819.2  473.43  3879.5  471.55  3981.9  471.32  4038.9  472.23
  4196.8  474.42  4309.4  473.79  4382.9  475.43  4470.9  473.22  4597.7  471.88
  4637.6  472.55  4820.8  465.75  4896.3  466.39    4918  465.36    4961  465.69
  4990.6  459.69  4991.7  453.77  4995.6  452.97  5016.6  453.77  5020.1  461.66
  5025.7  463.89  5044.3     469  5049.7  468.72    5058   471.6  5062.6  471.68
  5068.5  471.79  5079.6  474.98    5098   477.4  5225.9  478.93  5348.3  478.34
#Mann= 6 ,-1 , 0
  3687.9      .1       0  4038.9     .05       0  4597.7      .1       0
  4991.7     .07       0  5016.6      .1       0  5062.6     .05       0
Bank Sta=4991.7,5016.6
XS Rating Curve= 0 ,0
Exp/Cntr=0.3,0.1

Type RM Length L Ch R = 1 ,146163  ,228,228,228
BEGIN DESCRIPTION:
Mapping XS 78311302
END DESCRIPTION:
XS GIS Cut Line= 4
      2046644.11     13511275.68      2045801.49     13511312.44
      2045107.04     13511297.24      2044819.24     13511453.05
#Sta/Elev= 30
  3795.8  473.55  3824.9  473.99    3925  471.78  4035.1  471.17  4115.2  471.83
  4157.8  473.25  4345.4  473.11  4475.6  474.02  4621.9  472.02  4715.7  472.53
  4750.7  471.29  4765.7  469.37  4805.8  466.58  4845.8  465.27  4855.8   464.2
  4895.8  463.74  4965.8  464.62  4975.8  463.12  4983.3  453.57  4987.3  452.77
  5004.3  452.77  5008.2  453.57  5015.8  462.15  5025.8  463.75  5062.3  474.57
  5075.8  477.34  5125.8  478.22  5332.4   477.3  5495.4  478.68  5661.1  478.17
#Mann= 6 ,-1 , 0
  3795.8      .1       0  4157.8     .05       0  4621.9      .1       0
  4983.3     .07       0  5008.2      .1       0  5062.3     .05       0
Bank Sta=4983.3,5008.2
XS Rating Curve= 0 ,0
Exp/Cntr=0.3,0.1

Type RM Length L Ch R = 1 ,145935  ,294,294,294
BEGIN DESCRIPTION:
Mapping XS 064d2780
END DESCRIPTION:
XS GIS Cut Line= 4
      2046631.01     13511227.94      2045862.25     13511173.55
      2045282.82     13511069.38      2045020.26     13511177.88
#Sta/Elev= 30
  3858.6  473.74  3934.8  473.22  3970.5  471.75  4045.1  471.87    4097   470.5
  4175.4  472.63  4305.7  473.54  4385.9  472.89  4526.3  473.54  4656.1  471.92
  4697.6  471.51  4778.9  472.83  4789.1  472.01  4816.7  467.85  4821.7  468.13
    4850  463.74  4875.4  462.24  4941.5   463.6  4961.8  463.26  4971.9  461.56
  4980.4  454.13  4984.4  453.33  5001.4  453.33  5005.3  454.13  5012.6  466.13
  5032.9  470.69  5073.4  473.48  5114.2  476.17  5350.7  476.49  5502.1  478.37
#Mann= 6 ,-1 , 0
  3858.6      .1       0    4097     .05       0  4656.1      .1       0
  4980.4     .07       0  5005.3      .1       0  5073.4     .05       0
Bank Sta=4980.4,5005.3
XS Rating Curve= 0 ,0
Exp/Cntr=0.3,0.1

Type RM Length L Ch R = 1 ,145641  ,311,311,311
BEGIN DESCRIPTION:
Mapping XS a0725c11
END DESCRIPTION:
XS GIS Cut Line= 4
      2046615.66     13511128.09      2045844.89     13510965.21
      2045413.03     13510798.11       2045124.4     13510956.53
#Sta/Elev= 30
  4053.9  473.73  4096.8  473.93  4136.3  472.02  4183.4  471.77  4269.2  470.63
  4299.9     472  4335.3  471.14  4453.2  473.77  4555.4  472.56  4759.8  472.85
  4826.6  471.73  4895.2  471.33  4927.4  472.44  4948.8  472.26  4959.5  471.05
  4965.9  466.13    4981  459.28  4983.4  453.13  4987.4  452.33  5004.4  452.33
  5008.3  453.13  5013.1  460.33  5020.5  462.26  5034.6  463.69  5050.4  463.04
  5152.5  464.75  5227.2  468.49  5298.4  474.07  5455.3  474.52    5634  477.49
#Mann= 6 ,-1 , 0
  4053.9      .1       0  4183.4     .05       0  4826.6      .1       0
  4983.4     .07       0  5008.3      .1       0  5227.2     .05       0
Bank Sta=4983.4,5008.3
XS Rating Curve= 0 ,0
Exp/Cntr=0.3,0.1

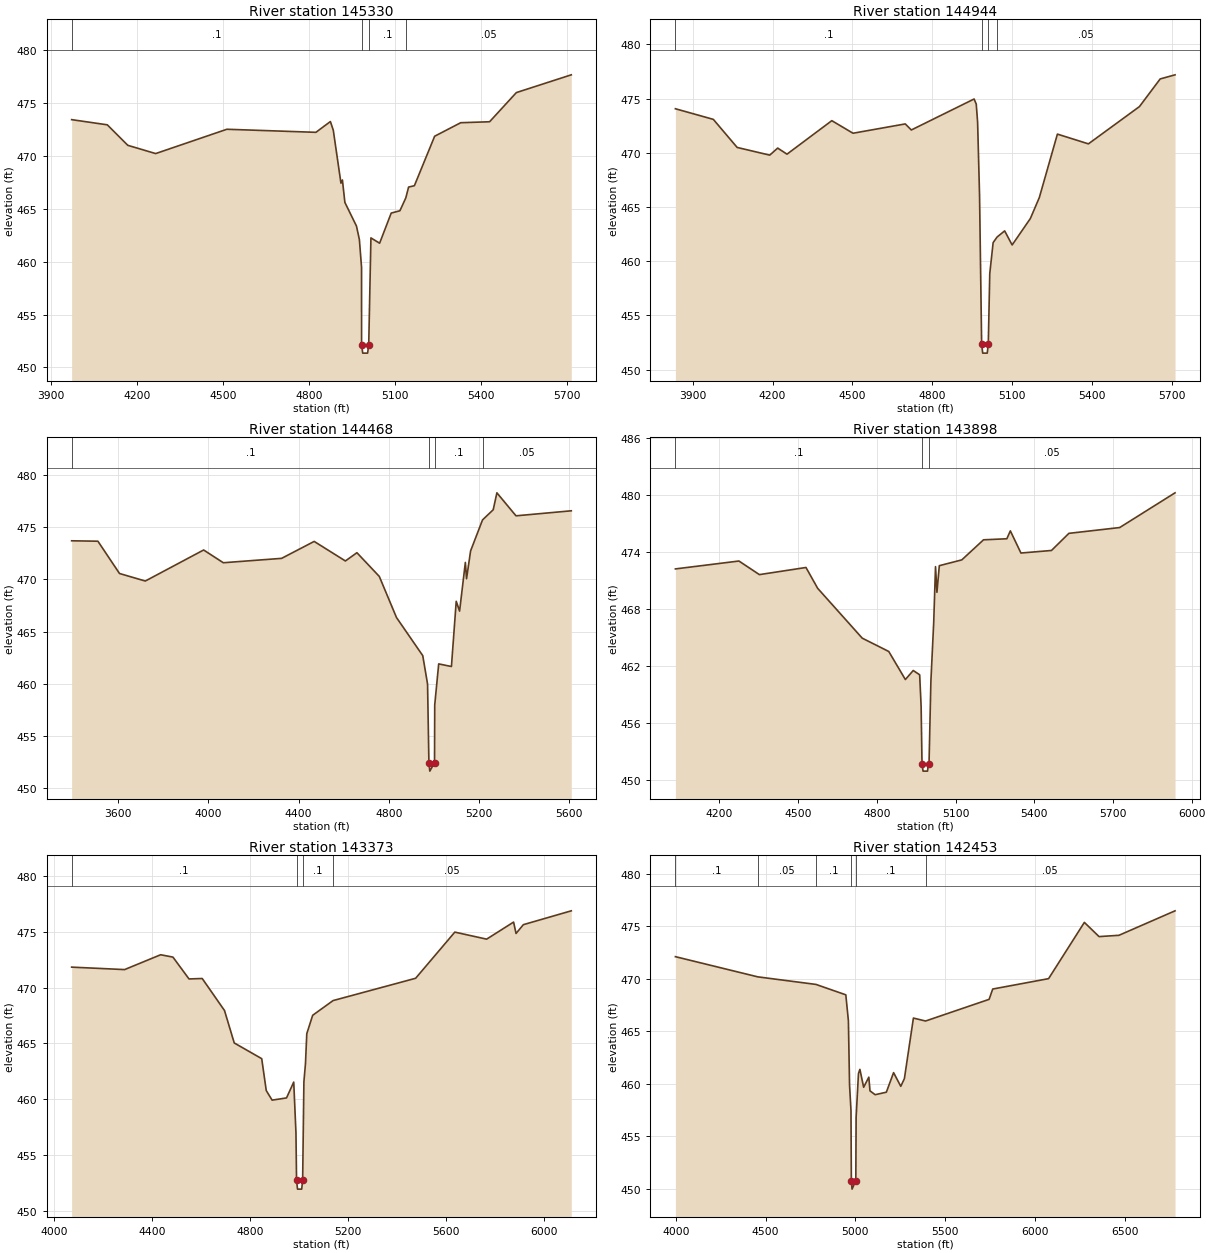
Type RM Length L Ch R = 1 ,145330  ,386,386,386
BEGIN DESCRIPTION:
Mapping XS 102dc86f
END DESCRIPTION:
XS GIS Cut Line= 4
      2046652.12     13510815.59      2045933.87     13510594.12
      2045291.51      13510683.1      2045011.53     13510878.43
#Sta/Elev= 30
  3972.7  473.44    4097  472.95  4168.5  471.01  4265.6  470.23  4513.8  472.53
  4824.1  472.24  4874.6  473.26  4884.7  472.44  4911.4  467.43  4916.5  467.73
  4925.1  465.61  4965.5  463.37  4975.6   462.1  4983.2  459.46  4983.3  452.15
  4987.3  451.35  5004.3  451.35  5008.2  452.15  5015.9  462.25  5046.2  461.75
  5086.6   464.6  5116.9  464.82  5137.4  466.03  5147.2  467.06  5167.4  467.19
    5238  471.87  5328.9  473.15  5429.5  473.24  5522.8     476  5714.2  477.68
#Mann= 4 ,-1 , 0
  3972.7      .1       0  4983.3     .07       0  5008.2      .1       0
  5137.4     .05       0
Bank Sta=4983.3,5008.2
XS Rating Curve= 0 ,0
Exp/Cntr=0.3,0.1

Type RM Length L Ch R = 1 ,144944  ,476,476,476
BEGIN DESCRIPTION:
Mapping XS 685e29dd
END DESCRIPTION:
XS GIS Cut Line= 4
      2046664.04     13510752.22      2045827.53     13510249.07
      2045311.04     13510353.23      2045029.49     13510597.96
#Sta/Elev= 30
  3835.2  474.07  3977.6  473.09    4067   470.5  4189.4  469.79  4219.2  470.44
  4254.2  469.88  4422.5  472.97  4502.1  471.81  4698.3  472.67    4721  472.11
  4956.8  474.97  4964.8   474.5  4969.9  472.86  4977.2  466.13  4985.1  452.32
  4989.1  451.52  5006.1  451.52    5010  452.32  5015.6  458.86  5028.2  461.71
    5043  462.23  5071.5   462.8  5099.6   461.5    5168  463.94  5201.6  465.87
  5269.6  471.73    5386  470.83  5577.7  474.27  5655.5  476.82  5711.3   477.2
#Mann= 4 ,-1 , 0
  3835.2      .1       0  4985.1     .07       0    5010      .1       0
    5043     .05       0
Bank Sta=4985.1,5010
XS Rating Curve= 0 ,0
Exp/Cntr=0.3,0.1

Type RM Length L Ch R = 1 ,144468  ,570,570,570
BEGIN DESCRIPTION:
Mapping XS da503910
END DESCRIPTION:
XS GIS Cut Line= 4
      2046652.14     13510690.59      2045488.99     13509921.38
      2044924.75     13510121.03      2044846.92     13510330.74
#Sta/Elev= 30
  3392.9   473.7  3509.4  473.66  3605.3  470.57  3719.7  469.85  3978.5  472.82
  4065.8   471.6  4324.6  472.02    4469  473.64  4607.5  471.77  4658.6  472.56
  4757.9  470.29  4834.1  466.36  4950.7  462.71    4972  459.99    4978  452.46
    4982  451.66  5002.9  452.46  5003.8     458  5021.4  461.92  5077.9  461.67
  5099.2  467.91  5114.1  466.97  5139.7  471.63    5145  470.07  5162.9  472.73
  5215.9   475.7  5263.3  476.67  5279.6  478.29  5364.4  476.09  5609.6  476.57
#Mann= 4 ,-1 , 0
  3392.9      .1       0    4978     .07       0  5002.9      .1       0
  5215.9     .05       0
Bank Sta=4978,5002.9
XS Rating Curve= 0 ,0
Exp/Cntr=0.3,0.1

Type RM Length L Ch R = 1 ,143898  ,525,525,525
BEGIN DESCRIPTION:
Mapping XS 9c57bd16
END DESCRIPTION:
XS GIS Cut Line= 4
      2045867.65      13510092.3      2045534.56       13509687.
      2044925.19     13509454.36      2044248.93     13509722.07
#Sta/Elev= 30
  4032.5  472.24  4274.6  473.07  4352.6  471.64  4530.1  472.39  4574.7   470.2
  4744.5  464.96  4845.6  463.56  4908.9  460.61  4938.9  461.56  4963.4  461.11
    4969  457.76  4972.3  451.78  4976.3  450.98  4993.3  450.98  4997.2  451.78
  4999.1   451.8  5006.2  460.45  5016.9  466.59  5023.8  472.48  5029.2  469.78
  5038.3  472.58    5124  473.19  5206.8   475.3  5295.6  475.41    5309  476.24
  5349.4  473.91  5465.8  474.18  5532.2  475.98  5725.8  476.59  5936.7  480.24
#Mann= 3 ,-1 , 0
  4032.5      .1       0  4972.3     .03       0  4997.2     .05       0
Bank Sta=4972.3,4997.2
XS Rating Curve= 0 ,0
Exp/Cntr=0.3,0.1

Type RM Length L Ch R = 1 ,143373  ,920,920,920
BEGIN DESCRIPTION:
Mapping XS b6edb9ba
END DESCRIPTION:
XS GIS Cut Line= 4
      2045930.13     13510118.31      2045680.39     13509707.84
      2045430.39     13509098.46      2044529.55     13509092.29
#Sta/Elev= 30
  4072.8  471.83    4289  471.61  4436.1  472.94  4486.4  472.73    4552  470.77
    4606  470.81  4696.9  467.94  4736.7  465.03  4848.9  463.62  4867.4  460.76
  4891.4   459.9  4950.2   460.1  4979.6  461.52  4988.7  456.96  4991.1  452.72
  4995.1  451.92  5012.1  451.92    5016  452.72  5021.1  461.55  5027.5  463.16
  5032.9  465.86  5056.9  467.51  5140.2  468.83  5477.3  470.83  5637.3  474.97
  5767.3  474.34  5877.3  475.87  5887.3  474.85  5917.3  475.64  6112.8  476.88
#Mann= 4 ,-1 , 0
  4072.8      .1       0  4991.1     .07       0    5016      .1       0
  5140.2     .05       0
Bank Sta=4991.1,5016
XS Rating Curve= 0 ,0
Exp/Cntr=0.3,0.1

Type RM Length L Ch R = 1 ,142453  ,337,337,337
BEGIN DESCRIPTION:
Mapping XS b2937d87
END DESCRIPTION:
XS GIS Cut Line= 4
      2046190.56      13510232.9      2046289.18     13509336.39
      2046126.42      13509132.4      2044513.45     13508998.53
#Sta/Elev= 30
  3998.3  472.09  4456.7  470.17  4780.9  469.45  4946.9  468.46  4961.3  465.99
  4967.7   459.9  4975.7  457.45  4977.7  450.78  4981.6  449.98  5002.6  450.78
  5004.3  456.82  5017.3  460.97  5025.3  461.37  5046.2  459.67    5075  460.63
  5081.4  459.33  5110.2  458.96  5172.6   459.2  5212.8  461.06  5252.9  459.76
    5273  460.49  5323.2  466.25  5390.9  465.97  5744.6  468.03  5764.7  469.01
  6075.7     470  6274.9  475.35  6356.7     474  6467.1  474.12  6779.7  476.45
#Mann= 6 ,-1 , 0
  3998.3      .1       0  4456.7     .05       0  4780.9      .1       0
  4977.7     .07       0  5002.6      .1       0  5390.9     .05       0
Bank Sta=4977.7,5002.6
XS Rating Curve= 0 ,0
Exp/Cntr=0.3,0.1