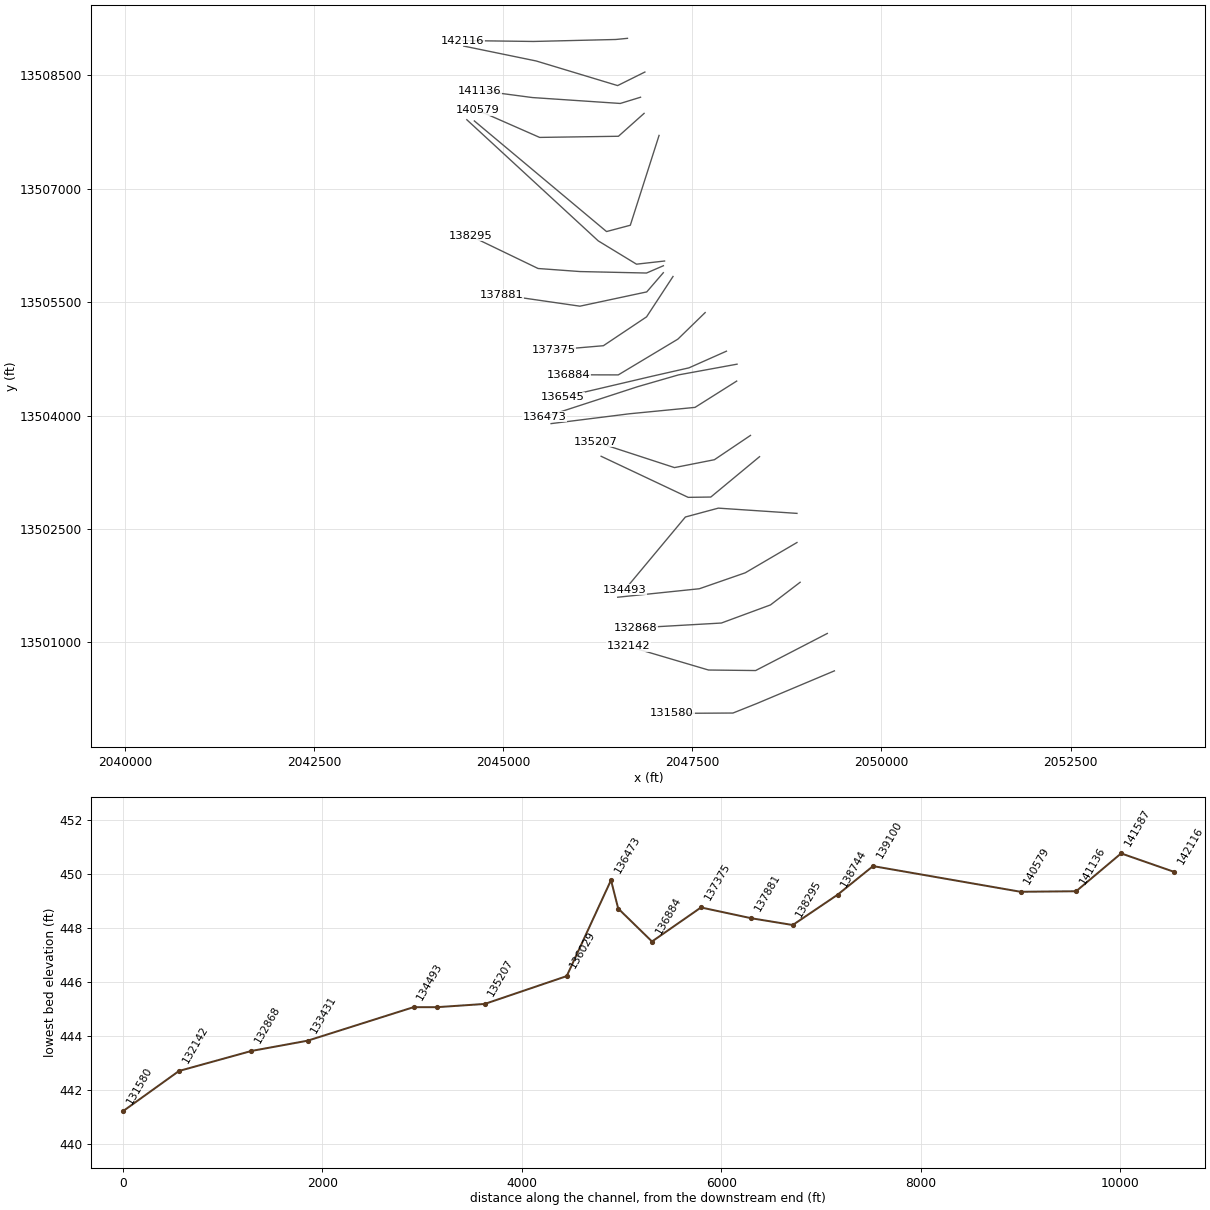
HEC-RAS study LAGUNILLAS Cr.prj: LAGUNILLAS Cr Base Level Engineering

--- LAGUNILLAS Cr.g01 (geometry) --- (continued)

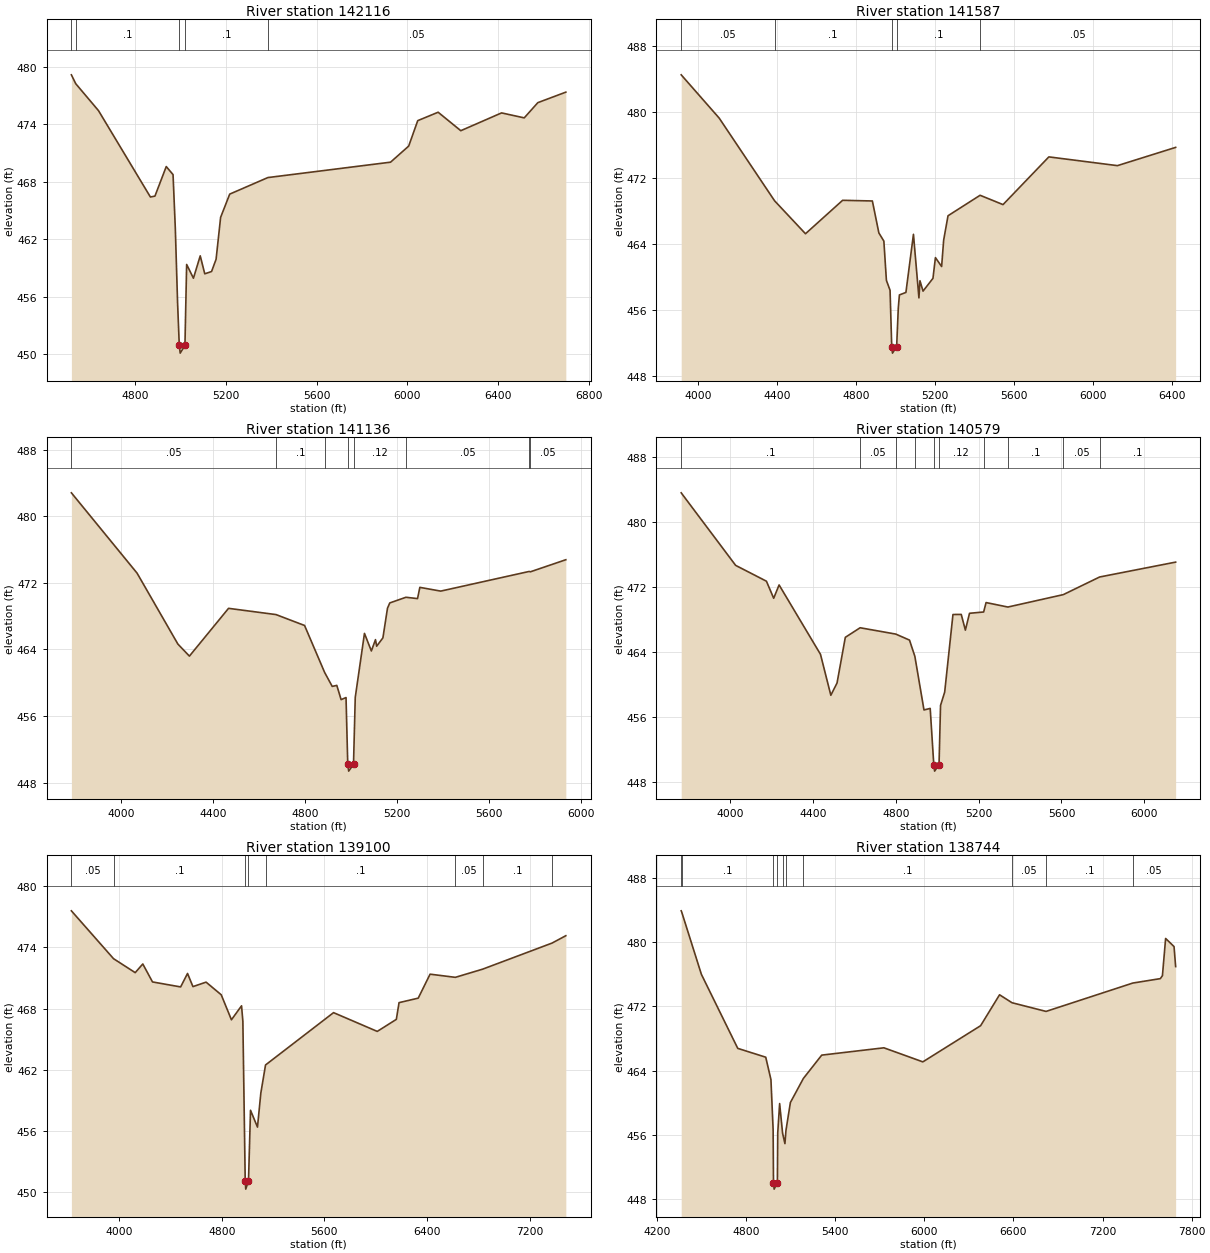
Type RM Length L Ch R = 1 ,142116  ,529,529,529
BEGIN DESCRIPTION:
Mapping XS 1de90a01
END DESCRIPTION:
XS GIS Cut Line= 4
      2046642.96     13508991.34      2046488.84     13508976.15
        2045400.       13508950.       2044461.4     13508962.07
#Sta/Elev= 30
    4517  479.18  4536.3  478.25  4636.6  475.44  4865.8  466.41  4885.8   466.5
  4935.8  469.59  4965.8  468.75  4975.8  463.13  4985.8  455.37  4993.3  450.89
  4997.3  450.09  5018.3  450.89  5025.8  459.36  5055.8  457.92  5085.8  460.26
  5105.8  458.38  5135.8  458.62  5155.8   459.9  5175.8  464.28  5215.9  466.71
  5384.3  468.44    5926  470.05    6006  471.73    6046  474.39    6136  475.27
  6236.1  473.34  6416.1   475.2  6516.1  474.68  6576.1  476.27  6699.7  477.37
#Mann= 5 ,-1 , 0
    4517     .05       0  4536.3      .1       0  4993.3     .07       0
  5018.3      .1       0  5384.3     .05       0
Bank Sta=4993.3,5018.3
XS Rating Curve= 0 ,0
Exp/Cntr=0.3,0.1

Type RM Length L Ch R = 1 ,141587  ,451,451,451
BEGIN DESCRIPTION:
Mapping XS eeccb3f8
END DESCRIPTION:
XS GIS Cut Line= 4
      2046872.84      13508545.4      2046512.71     13508366.34
      2045436.32     13508691.86      2044478.49     13508888.86
#Sta/Elev= 30
  3915.9  484.48  4108.3  479.24    4389  469.22  4545.5  465.23  4733.6  469.28
  4884.3   469.2  4917.2  465.33  4942.5  464.34  4955.4  459.58  4973.9  458.38
  4982.3  451.57  4986.3  450.77  5007.3  451.57  5015.7  456.29  5021.3  457.82
  5054.2  458.12  5092.4  465.16  5120.1  457.46  5125.3  459.54    5141  458.28
  5191.2  459.83  5203.7  462.34  5235.1  461.26  5245.5  464.47  5267.5  467.41
    5430  469.89  5546.1  468.76  5778.3  474.54  6125.6  473.48  6420.5  475.69
#Mann= 5 ,-1 , 0
  3915.9     .05       0    4389      .1       0  4982.3     .07       0
  5007.3      .1       0    5430     .05       0
Bank Sta=4982.3,5007.3
XS Rating Curve= 0 ,0
Exp/Cntr=0.3,0.1

Type RM Length L Ch R = 1 ,141136  ,557,557,557
BEGIN DESCRIPTION:
Mapping XS 6892d7ef
END DESCRIPTION:
XS GIS Cut Line= 4
      2046815.59     13508212.09      2046547.43     13508129.79
      2045386.41     13508207.92      2044685.36     13508300.62
#Sta/Elev= 30
  3782.2  482.81    4068  473.16  4245.5  464.64  4295.7  463.19    4466  468.93
  4672.4  468.18  4796.8  466.87  4883.9  461.24  4917.1  459.55  4937.1  459.67
  4955.8  457.96  4977.2  458.21  4984.7  450.17  4988.7  449.37  5009.7  450.17
  5017.3  458.22  5057.4  465.92  5087.4  463.81  5105.4  465.17  5110.5  464.38
  5137.6  465.38  5157.6  468.95  5167.6  469.58  5237.9  470.26  5288.3   470.1
  5298.4  471.45  5389.2     471  5773.7  473.36  5779.4  473.32  5933.5  474.77
#Mann= 8 ,-1 , 0
  3782.2     .05       0  4672.4      .1       0  4883.9     .12       0
  4984.7     .07       0  5009.7     .12       0  5237.9     .05       0
  5773.7      .1       0  5779.4     .05       0
Bank Sta=4984.7,5009.7
XS Rating Curve= 0 ,0
Exp/Cntr=0.3,0.1

Type RM Length L Ch R = 1 ,140579  ,1479,1479,1479
BEGIN DESCRIPTION:
Mapping XS 0cb3de2e
END DESCRIPTION:
XS GIS Cut Line= 4
      2046862.45     13507998.54      2046523.56     13507695.77
      2045481.89     13507680.58      2044664.71     13508040.12
#Sta/Elev= 30
  3762.6  483.61  4025.6  474.68  4174.4  472.73  4209.5  470.63  4235.6  472.27
  4435.6  463.73  4485.6  458.69  4515.6   460.2  4555.6  465.82  4627.2     467
  4799.3  466.22  4865.7  465.48  4891.6  463.48  4935.7  456.88  4965.7  457.07
    4983  450.15  4987.1  449.35  5008.4  450.15  5015.7  457.44  5035.7  459.08
  5075.7  468.63  5115.7  468.64  5135.7  466.71  5155.7  468.78    5224  468.94
  5235.7   470.1  5341.2  469.55  5609.1  471.08  5784.5  473.25  6151.6  475.08
#Mann= 10 ,-1 , 0
  3762.6      .1       0  4627.2     .05       0  4799.3      .1       0
  4891.6     .12       0    4983     .07       0  5008.4     .12       0
    5224     .05       0  5341.2      .1       0  5609.1     .05       0
  5784.5      .1       0
Bank Sta=4983,5008.4
XS Rating Curve= 0 ,0
Exp/Cntr=0.3,0.1

Type RM Length L Ch R = 1 ,139100  ,356,356,356
BEGIN DESCRIPTION:
Mapping XS ebeaed2b
END DESCRIPTION:
XS GIS Cut Line= 4
      2047060.36     13507706.91      2046680.39      13506518.6
      2046366.16     13506435.27      2044618.84     13507898.57
#Sta/Elev= 30
  3628.7  477.58    3957  472.89  4125.9  471.52    4185  472.37  4260.6  470.61
  4479.7  470.12  4533.6  471.44  4575.6  470.15    4678  470.59  4796.1  469.35
  4875.5   466.9  4954.3  468.27  4964.6  466.75  4982.9   451.1  4987.1   450.3
  5008.4   451.1  5024.2  458.03  5078.4  456.38  5104.6  459.72  5141.2  462.47
    5671   467.6  6011.6  465.76  6160.2  466.94  6181.2  468.58  6330.7  469.02
    6423  471.37  6619.8  471.06  6832.2  471.86  7373.5  474.42  7480.5  475.14
#Mann= 8 ,-1 , 0
  3628.7     .05       0    3957      .1       0  4982.9     .07       0
  5008.4      .1       0  5141.2      .1       0  6619.8     .05       0
  6832.2      .1       0  7373.5     .05       0
Bank Sta=4982.9,5008.4
XS Rating Curve= 0 ,0
Exp/Cntr=0.3,0.1

Type RM Length L Ch R = 1 ,138744  ,449,449,449
BEGIN DESCRIPTION:
Mapping XS d491777e
END DESCRIPTION:
XS GIS Cut Line= 4
      2047133.23      13506045.4       2046762.1     13506003.67
      2046256.46     13506311.83      2044519.33     13507914.61
#Sta/Elev= 30
    4363  483.88  4366.4  483.73    4499  475.97  4743.8  466.76  4932.2  465.66
  4967.3  462.87    4982  456.64  4984.4  450.04  4988.8  449.24  5010.6  450.04
    5013  456.24  5025.8  459.89  5045.7   456.2  5061.5   454.9  5068.4  456.55
  5098.2  460.02  5185.8  463.02  5309.3  465.92    5728  466.83    5990  465.08
    6379  469.58  6506.6  473.43  6590.6  472.44  6819.6  471.36  7403.9  474.89
  7589.2  475.44  7603.3  475.81  7624.8  480.44  7681.5  479.43  7692.2  476.94
#Mann= 10 ,-1 , 0
    4363     .05       0  4366.4      .1       0  4984.4     .07       0
  5010.6      .1       0  5045.7     .12       0  5068.4     .07       0
  5185.8      .1       0  6590.6     .05       0  6819.6      .1       0
  7403.9     .05       0
Bank Sta=4984.4,5010.6
XS Rating Curve= 0 ,0
Exp/Cntr=0.3,0.1

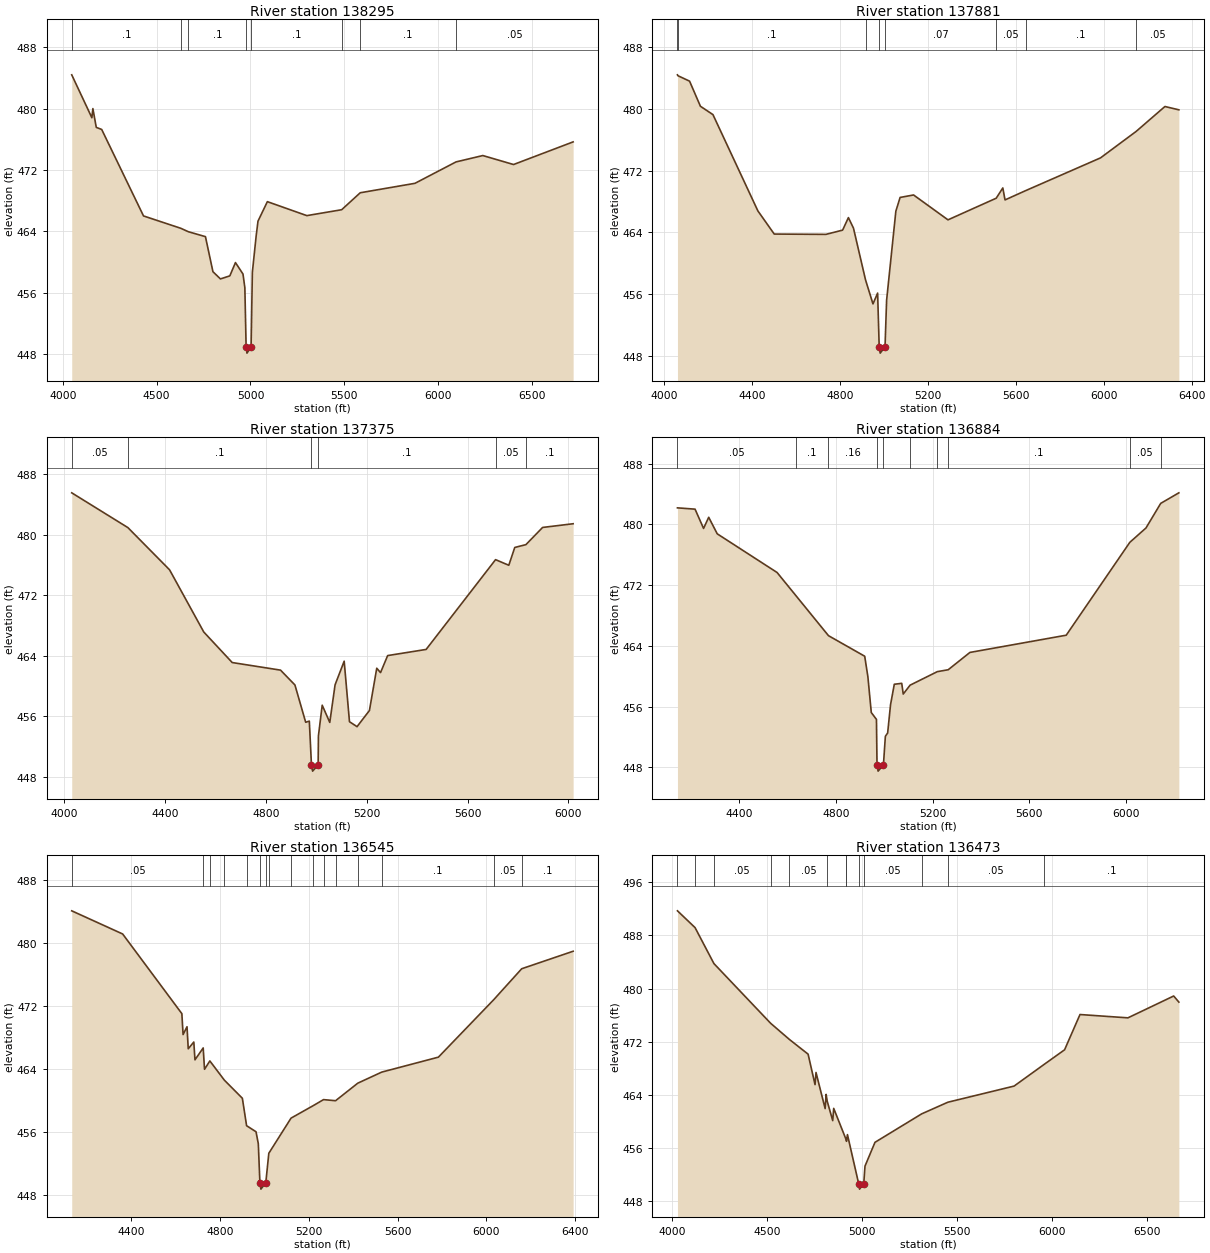
Type RM Length L Ch R = 1 ,138295  ,414,414,414
BEGIN DESCRIPTION:
Mapping XS a9c83329
END DESCRIPTION:
XS GIS Cut Line= 5
      2047117.64     13505982.91      2046894.48     13505886.48
      2046015.57     13505906.01      2045461.39     13505946.45
      2044565.53     13506378.76
#Sta/Elev= 30
  4047.3  484.39  4154.6   478.8    4160  479.99  4178.1  477.54    4207  477.27
  4429.9     466  4628.5  464.39  4669.2  463.94    4760   463.3    4800  458.73
    4840  457.79    4890  458.19    4920  459.92  4960.1  458.43  4970.1  456.64
  4976.8  448.92  4981.3  448.12  5003.3  448.92  5010.1  458.66  5030.1  463.34
  5040.1  465.32  5090.1  467.86  5300.4  466.04  5486.2  466.81  5585.1  469.02
  5876.8  470.25  6095.6  473.04  6238.5  473.87  6402.3   472.7  6719.9  475.65
#Mann= 8 ,-1 , 0
  4047.3      .1       0  4628.5     .12       0  4669.2      .1       0
  4976.8     .07       0  5003.3      .1       0  5486.2     .08       0
  5585.1      .1       0  6095.6     .05       0
Bank Sta=4976.8,5003.3
XS Rating Curve= 0 ,0
Exp/Cntr=0.3,0.1

Type RM Length L Ch R = 1 ,137881  ,506,506,506
BEGIN DESCRIPTION:
Mapping XS ff765618
END DESCRIPTION:
XS GIS Cut Line= 4
      2047116.83     13505890.73      2046897.63      13505636.8
      2046014.38       13505448.      2044982.21     13505597.49
#Sta/Elev= 30
  4060.3  484.39  4062.1  484.28  4115.4  483.57  4164.8  480.32  4221.8  479.24
  4426.2  466.78  4500.7  463.78  4735.9  463.74  4811.8  464.29  4838.2  465.91
  4861.3  464.54  4916.1  457.85    4950  454.74  4971.1  456.14  4978.3  449.17
  4982.8  448.37  5004.8  449.17    5012  455.21  5054.1  466.74  5073.4  468.52
  5134.7  468.84  5291.3  465.62  5510.7  468.42  5540.8  469.75  5550.9   468.2
  5645.4  469.41  5985.4  473.64  6147.3  477.06  6278.5  480.29  6341.9  479.86
#Mann= 8 ,-1 , 0
  4060.3     .05       0  4062.1      .1       0  4916.1     .07       0
  4978.3     .07       0  5004.8     .07       0  5510.7     .05       0
  5645.4      .1       0  6147.3     .05       0
Bank Sta=4978.3,5004.8
XS Rating Curve= 0 ,0
Exp/Cntr=0.3,0.1

Type RM Length L Ch R = 1 ,137375  ,491,491,491
BEGIN DESCRIPTION:
Mapping XS 03bf6a58
END DESCRIPTION:
XS GIS Cut Line= 4
      2047244.82     13505840.75      2046895.46     13505306.94
      2046324.71     13504924.99      2045664.47     13504868.32
#Sta/Elev= 30
  4031.2   485.5  4253.8  480.91    4419  475.34  4554.6  467.13  4667.3   463.1
  4858.8   462.1  4915.9  460.14  4958.5  455.22  4972.9  455.37  4981.4  449.57
  4985.9  448.77  5007.9  449.57    5009  453.42    5024  457.47    5054   455.2
    5075  460.16  5111.1  463.28  5132.1  455.29  5162.1  454.64  5211.2  456.77
  5240.2  462.35  5255.2  461.77  5283.4  464.02  5435.9  464.83  5711.1  476.68
  5763.6  475.94  5787.2  478.29  5831.3  478.66  5897.6  480.93  6018.6  481.42
#Mann= 6 ,-1 , 0
  4031.2     .05       0  4253.8      .1       0  4981.4     .07       0
  5007.9      .1       0  5711.1     .05       0  5831.3      .1       0
Bank Sta=4981.4,5007.9
XS Rating Curve= 0 ,0
Exp/Cntr=0.3,0.1

Type RM Length L Ch R = 1 ,136884  ,339,339,339
BEGIN DESCRIPTION:
Mapping XS 01817dfc
END DESCRIPTION:
XS GIS Cut Line= 4
      2047669.71      13505363.1      2047308.97     13505011.91
      2046521.21     13504538.82      2045868.87      13504540.2
#Sta/Elev= 30
  4144.6  482.18  4217.4  482.01  4252.6  479.47  4273.9  480.94  4309.2  478.76
  4556.7  473.67  4634.5  470.63  4769.4  465.35  4919.4  462.64  4932.6  459.93
  4946.6  455.23    4968  454.32  4970.3  448.31  4974.8  447.51  4996.8  448.31
  5004.9   452.1  5014.3  452.53  5026.3  456.26  5041.8  458.95  5072.6  459.07
  5078.8  457.66  5107.2  458.83  5219.8  460.61  5264.8  460.86  5354.7  463.14
  5753.2  465.41  6016.4  477.64  6083.2  479.53  6144.2  482.77  6219.3  484.16
#Mann= 10 ,-1 , 0
  4144.6     .05       0  4634.5      .1       0  4769.4     .16       0
  4970.3     .07       0  4996.8     .16       0  5107.2     .12       0
  5219.8     .16       0  5264.8      .1       0  6016.4     .05       0
  6144.2      .1       0
Bank Sta=4970.3,4996.8
XS Rating Curve= 0 ,0
Exp/Cntr=0.3,0.1

Type RM Length L Ch R = 1 ,136545  ,72,72,72
BEGIN DESCRIPTION:
Mapping XS e3b8bb33
END DESCRIPTION:
XS GIS Cut Line= 4
      2047950.96     13504852.69      2047455.35     13504632.02
      2046977.92     13504523.52      2045784.28     13504243.32
#Sta/Elev= 30
  4132.5  484.05  4361.9  481.11  4628.5     471    4634  468.35  4651.7  469.34
  4657.2  466.54  4682.3   467.4  4687.5  465.14  4724.6  466.65  4730.5  463.94
  4754.6     465  4819.9  462.56    4901  460.26    4920  456.78  4962.5  456.01
  4972.8  454.49    4980  449.53  4984.5  448.73  5006.5  449.53  5020.1  453.28
  5120.2  457.74  5220.4  459.33  5266.5  460.09  5320.7  459.95    5421  462.18
  5528.6  463.58  5783.9  465.48  6032.7  472.76  6159.1   476.7  6390.7  478.92
#Mann= 16 ,-1 , 0
  4132.5     .05       0  4724.6      .1       0  4754.6     .05       0
  4819.9     .08       0    4920     .05       0    4980     .04       0
  5006.5     .05       0  5020.1      .1       0  5120.2     .07       0
  5220.4      .1       0  5266.5     .05       0  5320.7     .08       0
    5421     .05       0  5528.6      .1       0  6032.7     .05       0
  6159.1      .1       0
Bank Sta=4980,5006.5
XS Rating Curve= 0 ,0
Exp/Cntr=0.3,0.1

Type RM Length L Ch R = 1 ,136473  ,444,444,444
BEGIN DESCRIPTION:
Mapping XS 62d738ad
END DESCRIPTION:
XS GIS Cut Line= 4
      2048091.59     13504680.82      2047316.46     13504538.71
       2046776.1     13504382.46        2045550.     13503982.93
#Sta/Elev= 30
  4027.6   491.7  4120.3  489.17  4219.7  483.75  4517.9  474.77  4617.3  472.32
  4715.5  470.11    4752  465.52  4757.1  467.35  4805.2  461.91  4810.3  464.05
  4816.1  463.02  4845.1   460.1  4850.3  461.94  4915.8  457.23  4917.6  456.98
  4922.7  457.99  4981.9  450.58  4986.4  449.78  5008.4  450.58    5015  453.24
  5067.6  456.83  5313.7  461.12  5451.4  462.87    5800   465.3  5959.9   468.6
    6066  470.77  6147.1  476.08  6399.5  475.58  6640.5  478.87  6667.7  477.95
#Mann= 13 ,-1 , 0
  4027.6     .05       0  4120.3     .08       0  4219.7     .05       0
  4517.9     .08       0  4617.3     .05       0  4816.1     .08       0
  4915.8      .1       0  4917.6     .05       0  4981.9     .04       0
  5008.4     .05       0  5313.7      .1       0  5451.4     .05       0
  5959.9      .1       0
Bank Sta=4981.9,5008.4
XS Rating Curve= 0 ,0
Exp/Cntr=0.3,0.1

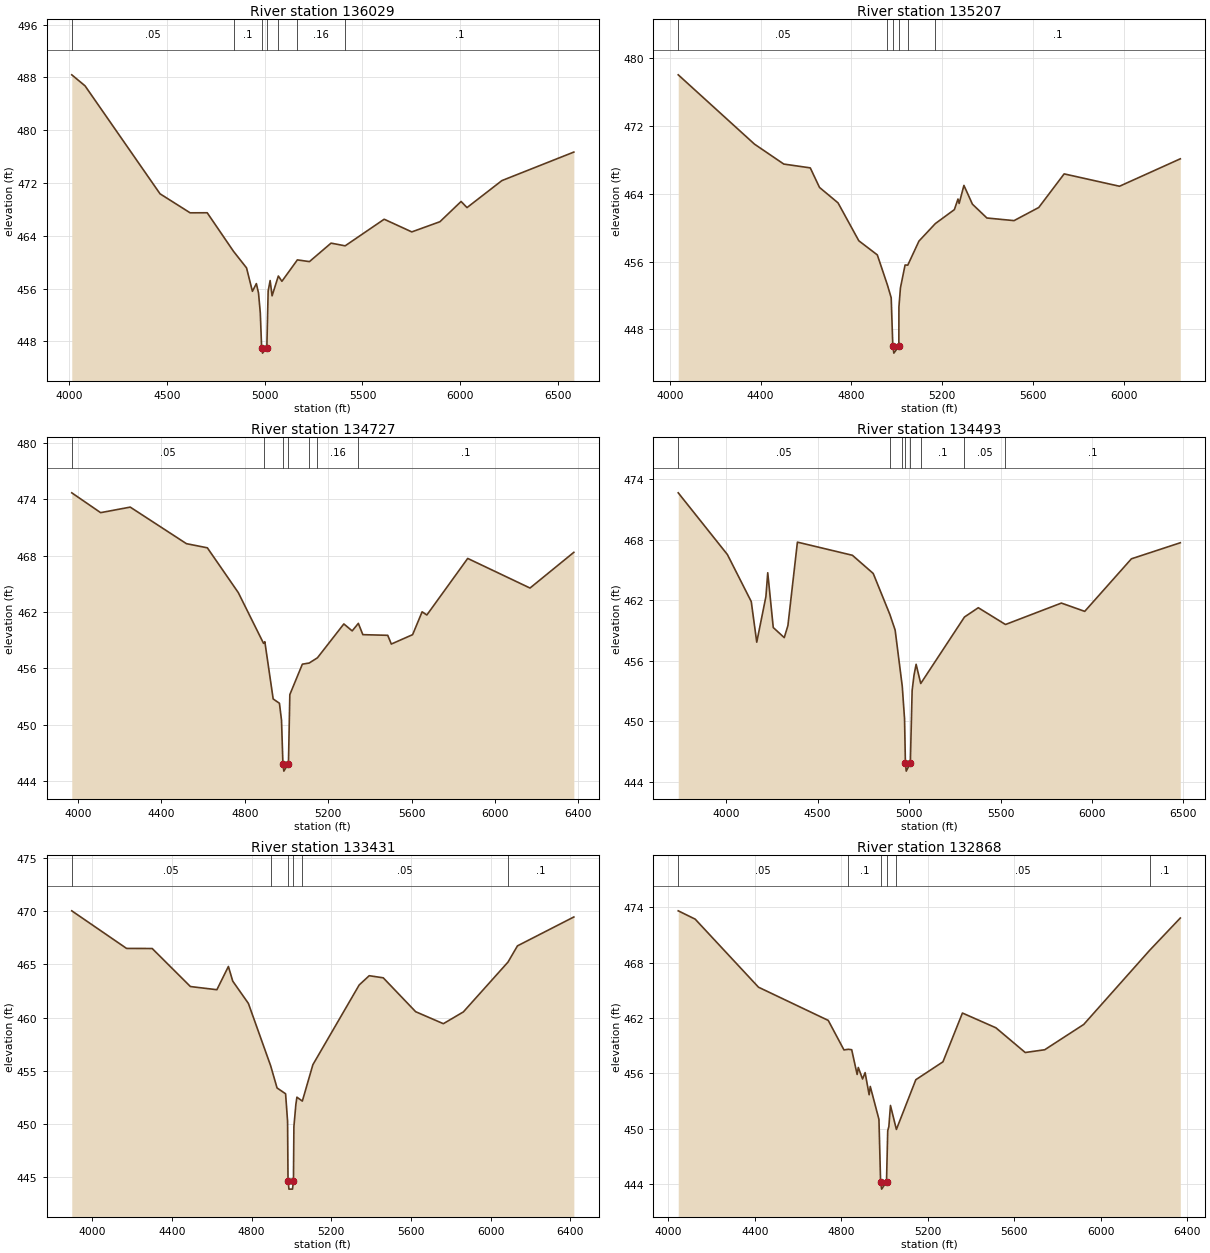
Type RM Length L Ch R = 1 ,136029  ,822,822,822
BEGIN DESCRIPTION:
Mapping XS cd87aa13
END DESCRIPTION:
XS GIS Cut Line= 4
      2048086.39     13504456.87      2047535.65     13504109.02
      2046669.73     13504024.58       2045633.3     13503894.37
#Sta/Elev= 30
  4014.2  488.38  4082.1  486.71  4465.3  470.36  4619.1  467.48  4706.4  467.49
    4841  461.64  4907.4  459.14  4937.5  455.59  4957.6  456.76  4968.6  455.34
  4977.7  452.34  4984.6  447.03  4989.1  446.23  5011.1  447.03  5017.9  455.64
    5028  457.22    5038  454.91    5070  457.91  5088.2  457.11  5167.2  460.35
  5228.9  460.09  5339.4  462.89  5411.4  462.48  5610.9  466.51    5752  464.59
  5895.7  466.13    6004   469.2  6034.2  468.27  6212.4  472.36  6580.2  476.68
#Mann= 7 ,-1 , 0
  4014.2     .05       0    4841      .1       0  4984.6     .07       0
  5011.1      .1       0    5070      .1       0  5167.2     .16       0
  5411.4      .1       0
Bank Sta=4984.6,5011.1
XS Rating Curve= 0 ,0
Exp/Cntr=0.3,0.1

Type RM Length L Ch R = 1 ,135207  ,480,480,480
BEGIN DESCRIPTION:
Mapping XS 8a0d949b
END DESCRIPTION:
XS GIS Cut Line= 4
      2048268.67     13503738.11      2047791.72     13503416.75
      2047264.38     13503312.58       2046218.3     13503654.23
#Sta/Elev= 30
  4036.6  478.07  4372.9  469.88  4501.9  467.53  4618.6  467.08  4659.3  464.77
  4740.9  462.95  4832.6  458.47  4914.2   456.8  4958.8  453.24  4975.3  451.74
  4982.5     446    4987   445.2    5009     446  5009.4  450.66  5016.1  452.91
  5036.5  455.61  5048.4  455.59  5097.6  458.43  5169.9   460.5  5253.8  462.15
  5269.7   463.4  5274.9  462.88  5295.9  465.01  5333.4  462.79  5397.2  461.16
  5516.8  460.85  5625.7   462.4  5737.7  466.37  5981.7  464.91  6249.7  468.15
#Mann= 6 ,-1 , 0
  4036.6     .05       0  4958.8     .07       0  4982.5     .07       0
    5009     .07       0  5048.4     .16       0  5169.9      .1       0
Bank Sta=4982.5,5009
XS Rating Curve= 0 ,0
Exp/Cntr=0.3,0.1

Type RM Length L Ch R = 1 ,134727  ,234,234,234
BEGIN DESCRIPTION:
Mapping XS f995d7a7
END DESCRIPTION:
XS GIS Cut Line= 4
      2048388.46     13503456.85      2047744.39     13502922.94
      2047445.02     13502918.83      2046294.74     13503462.07
#Sta/Elev= 30
  3969.8  474.69  4108.3  472.58  4250.2  473.17  4519.8  469.28  4620.1  468.84
  4768.6  464.07  4889.7  458.67  4895.8  458.85  4935.8  452.76  4965.8   452.3
  4975.8   450.5  4982.5  445.88    4987  445.08  5009.1  445.88  5015.7  453.22
  5075.8  456.46  5108.5  456.58  5148.2  457.14  5274.8  460.74  5314.8     460
  5344.3   460.8  5365.9   459.6  5485.3  459.53  5502.5   458.6  5604.6   459.6
  5650.2  462.03  5672.9  461.69  5868.9  467.71  6167.7  464.56  6377.9  468.36
#Mann= 7 ,-1 , 0
  3969.8     .05       0  4889.7      .1       0  4982.5     .07       0
  5009.1      .1       0  5108.5      .1       0  5148.2     .16       0
  5344.3      .1       0
Bank Sta=4982.5,5009.1
XS Rating Curve= 0 ,0
Exp/Cntr=0.3,0.1

Type RM Length L Ch R = 1 ,134493  ,1062,1062,1062
BEGIN DESCRIPTION:
Mapping XS 3729f88b
END DESCRIPTION:
XS GIS Cut Line= 4
      2048883.31     13502706.86      2047843.69     13502776.18
      2047408.67     13502659.08      2046607.24     13501696.46
#Sta/Elev= 30
  3737.6  472.62  4006.5  466.51  4136.8  461.86  4166.9  457.84    4217  462.36
    4227  464.71  4257.1  459.29  4317.2  458.29  4337.2  459.48  4389.2  467.74
  4689.8  466.44  4803.7  464.64  4894.5  460.59  4923.5  459.04  4962.4  453.48
  4974.9  450.26  4979.6  445.88  4984.2  445.08  5006.6  445.88  5016.4  453.06
  5026.7  454.58  5038.2  455.65  5063.4  453.75  5302.5  460.33  5378.1  461.25
  5526.8  459.59  5832.4  461.71    5960  460.89  6215.2  466.09  6482.6  467.68
#Mann= 8 ,-1 , 0
  3737.6     .05       0  4894.5      .1       0  4962.4     .16       0
  4979.6     .07       0  5006.6     .16       0  5063.4      .1       0
  5302.5     .05       0  5526.8      .1       0
Bank Sta=4979.6,5006.6
XS Rating Curve= 0 ,0
Exp/Cntr=0.3,0.1

Type RM Length L Ch R = 1 ,133431  ,563,563,563
BEGIN DESCRIPTION:
Mapping XS 3079a64f
END DESCRIPTION:
XS GIS Cut Line= 4
      2048883.23     13502321.43      2048199.98     13501920.77
      2047593.21     13501709.83      2046513.49     13501597.49
#Sta/Elev= 30
  3897.3  470.05  4172.3  466.51  4301.1   466.5  4492.7  462.92  4625.6  462.62
  4683.5  464.81  4705.2  463.43  4783.8  461.33  4895.7  455.45  4927.6  453.37
  4970.5  452.82  4980.5  450.22  4982.7  444.64  4987.4  443.84  5005.2  443.84
    5010  444.64  5012.2  449.72  5022.1  451.82  5027.4   452.5  5054.6  452.13
  5107.5  455.56    5340  463.07  5390.3  463.94  5460.7  463.74  5623.3  460.55
  5762.3  459.42  5862.8  460.53  6086.7  465.22  6134.3  466.75  6417.3  469.47
#Mann= 6 ,-1 , 0
  3897.3     .05       0  4895.7      .1       0  4982.7     .07       0
    5010      .1       0  5054.6     .05       0  6086.7      .1       0
Bank Sta=4982.7,5010
XS Rating Curve= 0 ,0
Exp/Cntr=0.3,0.1

Type RM Length L Ch R = 1 ,132868  ,726,726,726
BEGIN DESCRIPTION:
Mapping XS 4573d6a3
END DESCRIPTION:
XS GIS Cut Line= 4
      2048924.96     13501795.43      2048533.04     13501495.74
      2047883.74     13501256.16      2046748.95      13501191.3
#Sta/Elev= 30
  4045.9  473.63  4124.2  472.73  4417.1  465.35  4739.7  461.75  4812.4  458.55
  4832.8  458.62  4848.2  458.57  4873.3  455.89  4878.6  456.65  4898.4   455.4
  4910.2  456.09  4928.8  453.69  4934.1  454.59  4974.2  451.02  4981.8  444.26
  4986.6  443.46  5009.2  444.26  5014.8  449.79  5020.1  450.25  5027.5  452.53
  5054.9  449.93  5144.7  455.32  5270.2  457.26  5360.3  462.55  5515.1  460.95
  5650.8  458.27  5740.9  458.57  5921.2  461.31  6226.2  469.35    6368  472.85
#Mann= 6 ,-1 , 0
  4045.9     .05       0  4832.8      .1       0  4981.8     .07       0
  5009.2      .1       0  5054.9     .05       0  6226.2      .1       0
Bank Sta=4981.8,5009.2
XS Rating Curve= 0 ,0
Exp/Cntr=0.3,0.1

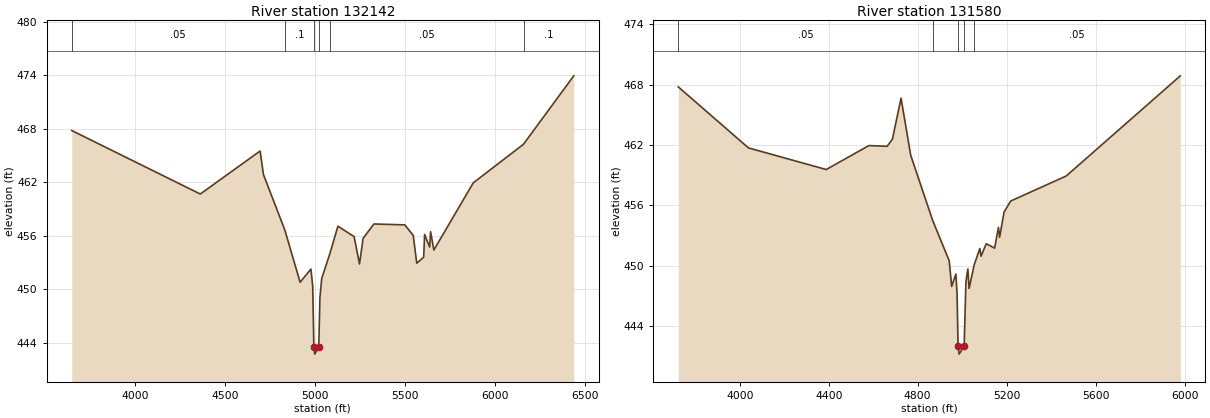
Type RM Length L Ch R = 1 ,132142  ,562,562,562
BEGIN DESCRIPTION:
Mapping XS 9fef0de6
END DESCRIPTION:
XS GIS Cut Line= 4
      2049284.28     13501118.31      2048336.86     13500627.68
       2047713.6     13500634.63      2046659.65     13500946.35
#Sta/Elev= 30
    3647  467.82  4361.1  460.69  4693.5  465.52  4712.2  462.87  4830.6  456.67
  4915.8  450.79  4975.8  452.27  4985.8  450.34  4992.1  443.52  4996.9  442.72
  5019.5  443.52  5025.8  449.05  5035.8  451.21  5082.4  454.08  5125.8  457.08
  5215.8  455.91  5245.8  452.84  5265.8  455.71  5325.8  457.33  5497.3  457.23
  5544.3  456.05  5563.8  452.93  5602.3   453.6  5607.5  456.15  5635.6  454.74
  5640.8  456.46    5659  454.41    5878  461.95    6157  466.28  6436.3  473.96
#Mann= 6 ,-1 , 0
    3647     .05       0  4830.6      .1       0  4992.1     .07       0
  5019.5      .1       0  5082.4     .05       0    6157      .1       0
Bank Sta=4992.1,5019.5
XS Rating Curve= 0 ,0
Exp/Cntr=0.3,0.1

Type RM Length L Ch R = 1 ,131580  ,377,377,377
BEGIN DESCRIPTION:
Mapping XS f991527b
END DESCRIPTION:
XS GIS Cut Line= 4
      2049378.04     13500623.52      2048353.79     13500191.92
      2048037.38     13500065.62      2047232.25     13500061.03
#Sta/Elev= 30
  3723.8  467.78  4039.1  461.72    4389  459.57  4580.8  461.95  4662.9  461.88
  4686.6  462.59  4725.4  466.66  4768.8  460.99  4867.8   454.5  4941.6  450.52
  4953.1  447.96  4971.9  449.19  4977.3  447.21  4981.7  442.03  4986.6  441.23
  5009.2  442.03    5017   448.4  5025.8  449.69  5031.2  447.75  5054.3  450.11
  5079.7  451.72  5085.1  450.96  5108.5   452.2  5146.2  451.76  5163.3  453.82
  5168.6  452.84  5188.3  455.33  5218.3  456.44  5468.3  458.93  5981.1  468.88
#Mann= 5 ,-1 , 0
  3723.8     .05       0  4867.8      .1       0  4981.7     .07       0
  5009.2      .1       0  5054.3     .05       0
Bank Sta=4981.7,5009.2
XS Rating Curve= 0 ,0
Exp/Cntr=0.3,0.1