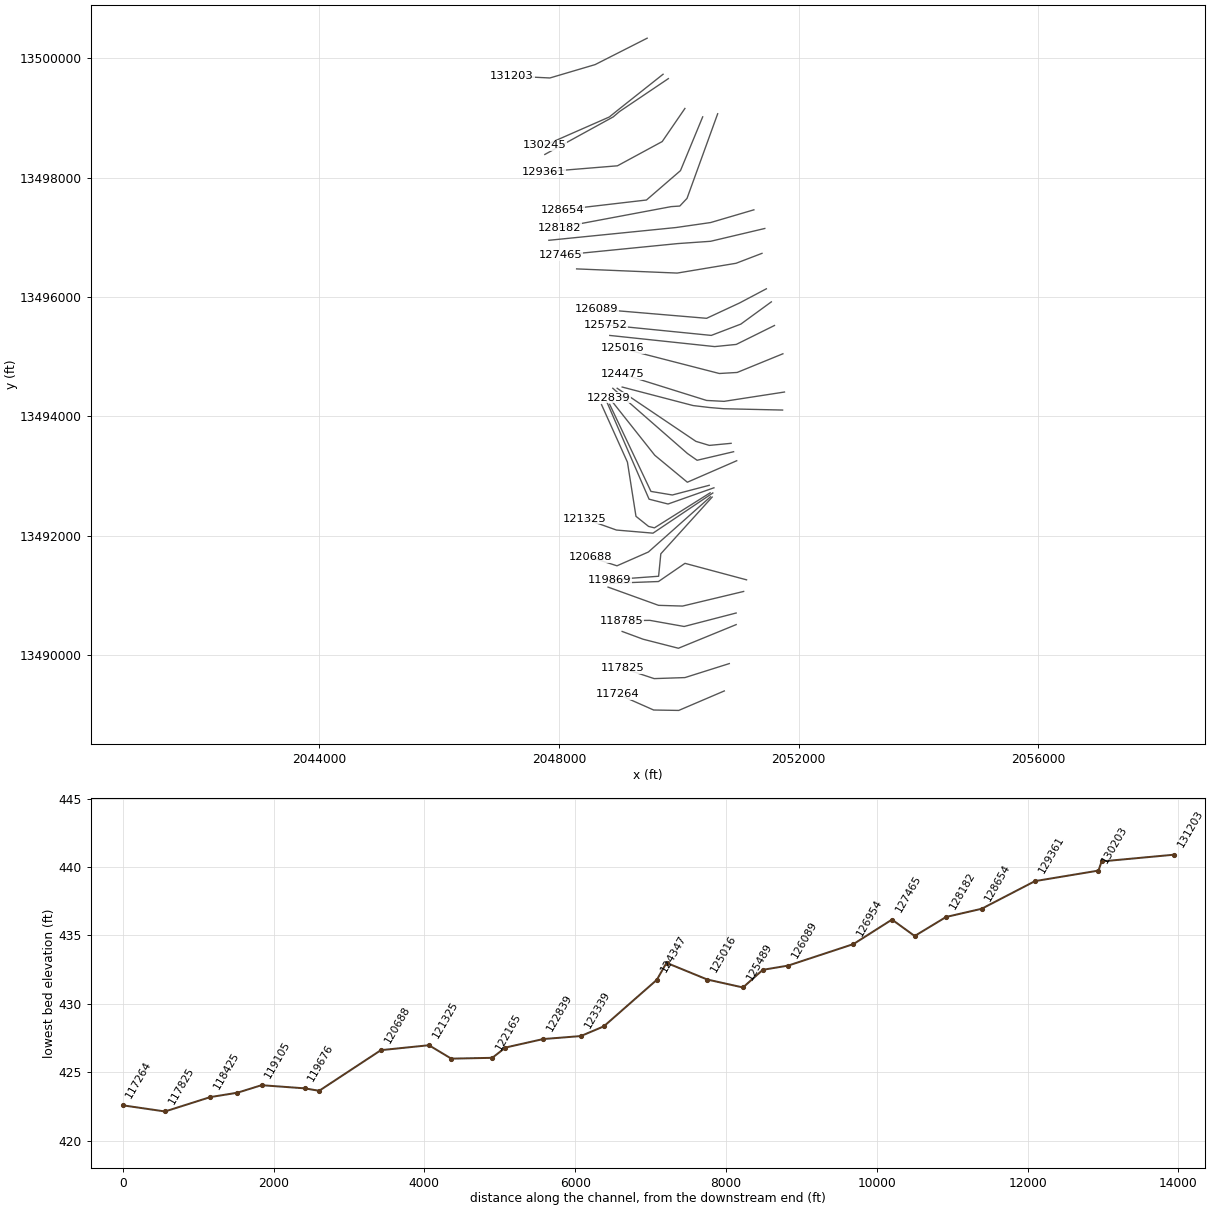
HEC-RAS study LAGUNILLAS Cr.prj: LAGUNILLAS Cr Base Level Engineering

--- LAGUNILLAS Cr.g01 (geometry) --- (continued)

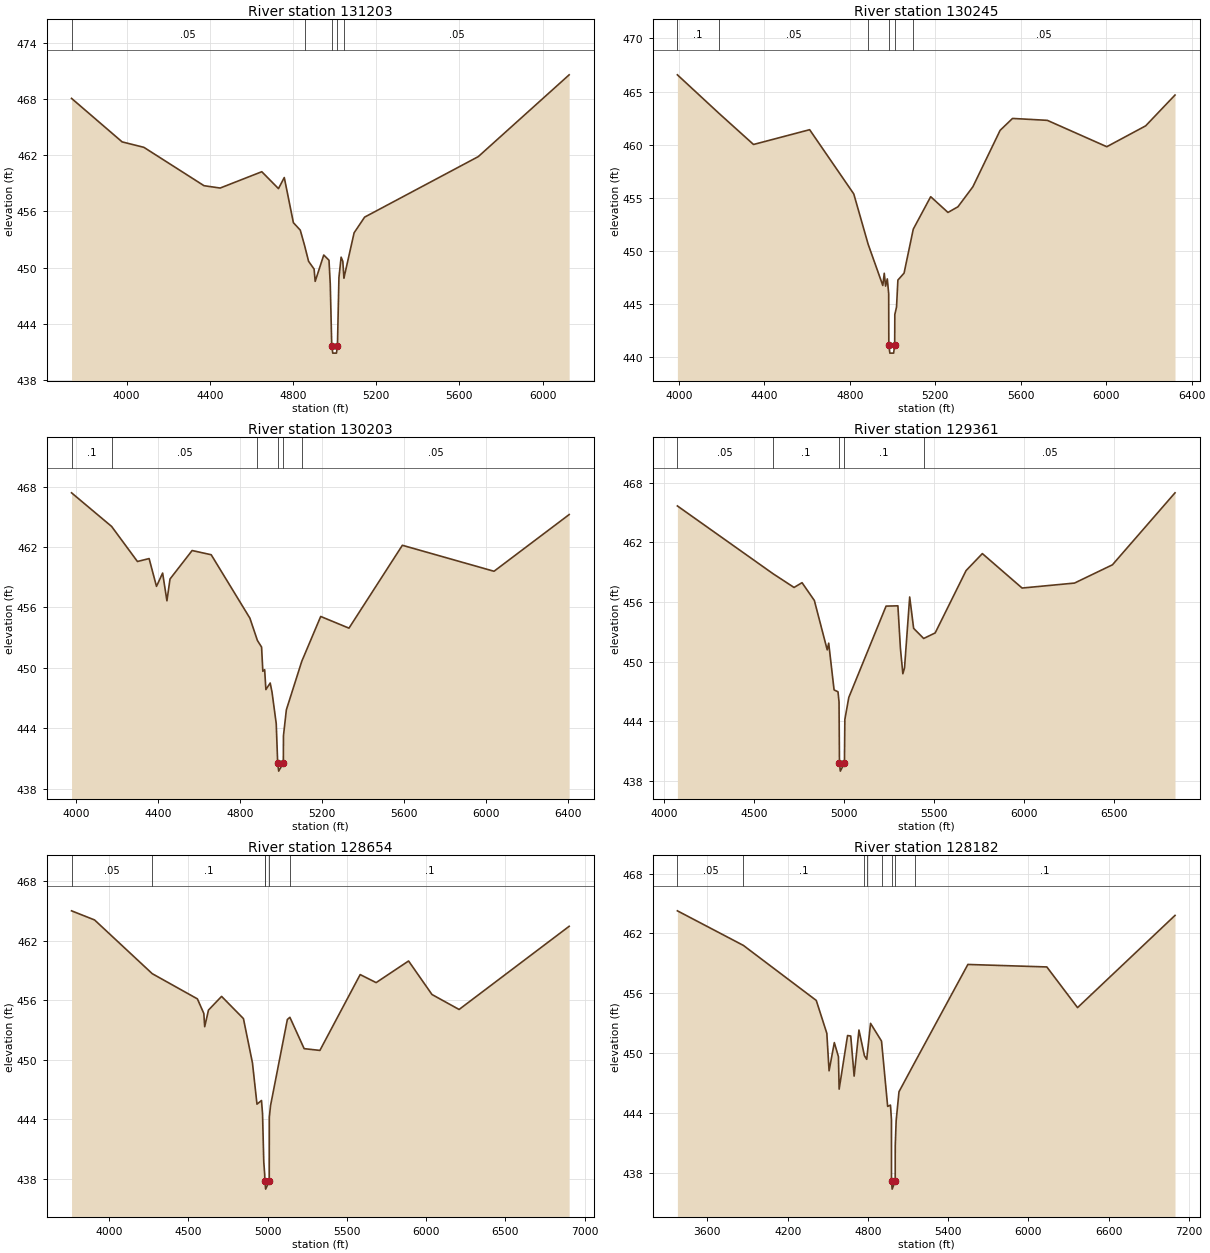
Type RM Length L Ch R = 1 ,131203  ,958,958,958
BEGIN DESCRIPTION:
Mapping XS 1906c78d
END DESCRIPTION:
XS GIS Cut Line= 4
      2049471.78     13500337.06      2048603.63     13499894.72
      2047848.42     13499670.77      2047218.34     13499701.57
#Sta/Elev= 30
  3735.1  468.06  3978.4  463.42    4083  462.84  4372.1  458.75  4449.8   458.5
    4650  460.24  4730.1  458.44  4758.1  459.62  4801.9  454.81    4835  454.01
  4855.9  452.36  4874.9  450.69  4901.5  449.86  4906.7  448.55  4947.9  451.36
  4973.1   450.8  4979.2  448.27  4986.3   441.7  4991.2   440.9    5009   440.9
  5013.8   441.7  5020.9  448.96  5031.4  451.13  5039.6  450.69  5044.8  448.89
  5047.3  449.14  5093.9  453.73  5144.5   455.4    5691  461.85    6128  470.57
#Mann= 5 ,-1 , 0
  3735.1     .05       0  4855.9      .1       0  4986.3     .07       0
  5013.8      .1       0  5047.3     .05       0
Bank Sta=4986.3,5013.8
XS Rating Curve= 0 ,0
Exp/Cntr=0.3,0.1

Type RM Length L Ch R = 1 ,130245  ,42,42,42
BEGIN DESCRIPTION:
Mapping XS 93efa612
END DESCRIPTION:
XS GIS Cut Line= 4
      2049737.45     13499732.92      2048991.81     13499139.84
      2048840.77     13499017.44      2047759.17      13498540.6
#Sta/Elev= 30
    3993  466.58    4187  462.97  4349.3  460.03    4612  461.42  4818.6  455.38
    4886  450.64  4954.5  446.77  4961.2  447.92  4967.6  446.71  4975.5  447.39
    4982  446.01  4982.6  441.21  4987.4  440.41  5005.2  440.41  5010.1  441.21
  5010.7  444.04  5018.7  444.74  5025.1  447.28  5053.9  447.93  5097.1  452.07
  5178.6  455.12  5259.5  453.64  5306.1  454.17    5376  456.05  5503.6  461.36
  5561.7  462.48  5724.5   462.3  6002.9  459.82  6184.7  461.78  6322.2  464.68
#Mann= 6 ,-1 , 0
    3993      .1       0    4187     .05       0    4886      .1       0
  4982.6     .07       0  5010.1      .1       0  5097.1     .05       0
Bank Sta=4982.6,5010.1
XS Rating Curve= 0 ,0
Exp/Cntr=0.3,0.1

Type RM Length L Ch R = 1 ,130203  ,842,842,842
BEGIN DESCRIPTION:
Mapping XS f2107614
END DESCRIPTION:
XS GIS Cut Line= 4
      2049825.94     13499659.97      2049011.77     13499109.46
        2048905.     13499018.31       2047764.2     13498389.56
#Sta/Elev= 30
  3978.8  467.38  4174.2  464.04    4300  460.56  4356.9  460.85  4392.9  458.09
  4422.8  459.41  4443.8  456.66  4458.8  458.82  4566.6  461.65  4659.6  461.23
  4848.3  454.93  4884.8  452.72  4905.2  452.06  4911.3  449.66  4920.2  449.81
  4926.2  447.84  4947.2  448.49  4956.2  447.57  4976.6  444.46  4983.7  440.54
  4988.5  439.74  5011.3  440.54  5011.8  443.25    5026  445.83    5101  450.64
  5193.4   455.1  5331.2  453.94  5591.5  462.17  6038.3  459.59  6404.6  465.22
#Mann= 6 ,-1 , 0
  3978.8      .1       0  4174.2     .05       0  4884.8      .1       0
  4983.7     .07       0  5011.3      .1       0    5101     .05       0
Bank Sta=4983.7,5011.3
XS Rating Curve= 0 ,0
Exp/Cntr=0.3,0.1

Type RM Length L Ch R = 1 ,129361  ,707,707,707
BEGIN DESCRIPTION:
Mapping XS 8bfd08ce
END DESCRIPTION:
XS GIS Cut Line= 4
      2050101.99     13499159.95      2049723.42     13498605.66
      2048976.02     13498199.41      2047738.71      13498097.6
#Sta/Elev= 30
  4075.3  465.68  4605.9  458.86  4723.1  457.47  4767.5  457.95  4835.8  456.16
  4907.4  451.18  4915.5  451.86  4945.4  447.15  4967.2  446.96  4972.9  445.94
  4975.3  439.77  4980.1  438.97  5002.9  439.77  5005.2  444.17  5027.1  446.39
  5234.1  455.59  5299.8  455.62  5313.8  451.34  5327.3  448.78  5336.6  449.36
  5365.3  456.51  5387.2  453.35    5443  452.33  5506.9  452.89  5678.5  459.17
  5768.8  460.88  5989.5  457.41  6280.5  457.91  6491.2  459.75  6838.7     467
#Mann= 5 ,-1 , 0
  4075.3     .05       0  4605.9      .1       0  4975.3     .07       0
  5002.9      .1       0    5443     .05       0
Bank Sta=4975.3,5002.9
XS Rating Curve= 0 ,0
Exp/Cntr=0.3,0.1

Type RM Length L Ch R = 1 ,128654  ,472,472,472
BEGIN DESCRIPTION:
Mapping XS 80d58535
END DESCRIPTION:
XS GIS Cut Line= 4
      2050398.88     13499019.33       2050028.1     13498118.68
       2049460.4      13497626.5      2048055.12     13497462.07
#Sta/Elev= 30
  3762.7  465.02    3908   464.1    4272  458.68  4556.8  456.14  4597.5  454.67
  4602.9  453.33  4626.9  455.01  4709.5  456.39  4847.4  454.15  4904.4  449.68
  4932.9  445.52  4961.4  445.89    4968  444.54  4975.7  439.72  4981.5  438.44
  4982.7  437.75  4987.6  436.95  5010.3  437.75  5010.8   444.2  5018.4  445.37
  5124.6  454.06  5140.6  454.28  5230.5  451.12  5329.9  450.94  5584.1  458.59
  5684.8  457.78  5889.6  459.96  6037.2  456.58  6208.3  455.07  6902.9  463.46
#Mann= 6 ,-1 , 0
  3762.7     .05       0    4272      .1       0  4981.5     .16       0
  4982.7     .07       0  5010.3     .16       0  5140.6      .1       0
Bank Sta=4982.7,5010.3
XS Rating Curve= 0 ,0
Exp/Cntr=0.3,0.1

Type RM Length L Ch R = 1 ,128182  ,416,416,416
BEGIN DESCRIPTION:
Mapping XS 045c0d7f
END DESCRIPTION:
XS GIS Cut Line= 5
       2050648.9     13499071.46      2050137.21     13497653.73
      2050016.55     13497525.25      2049873.32     13497515.71
       2048013.5      13497165.2
#Sta/Elev= 30
  3375.6  464.27  3868.9   460.8  4413.7  455.28  4492.6  451.98  4509.4  448.22
  4548.6  451.05  4579.3  449.64  4584.6  446.38  4647.6  451.76  4671.3  451.71
  4696.7  447.69  4732.7  452.31  4773.6  449.74  4790.7  449.37  4819.4  452.98
  4901.4   451.2  4947.3  444.65  4968.3  444.78  4975.6  443.32    4976  437.15
  4980.9  436.35  5003.7  437.15    5004  440.69  5010.8  443.21    5032  446.12
  5150.1  449.07  5546.9  458.89  6137.1  458.64  6366.7  454.56  7095.2  463.81
#Mann= 8 ,-1 , 0
  3375.6     .05       0  3868.9      .1       0  4773.6     .16       0
  4790.7      .1       0  4901.4     .16       0    4976     .07       0
  5003.7     .16       0  5150.1      .1       0
Bank Sta=4976,5003.7
XS Rating Curve= 0 ,0
Exp/Cntr=0.3,0.1

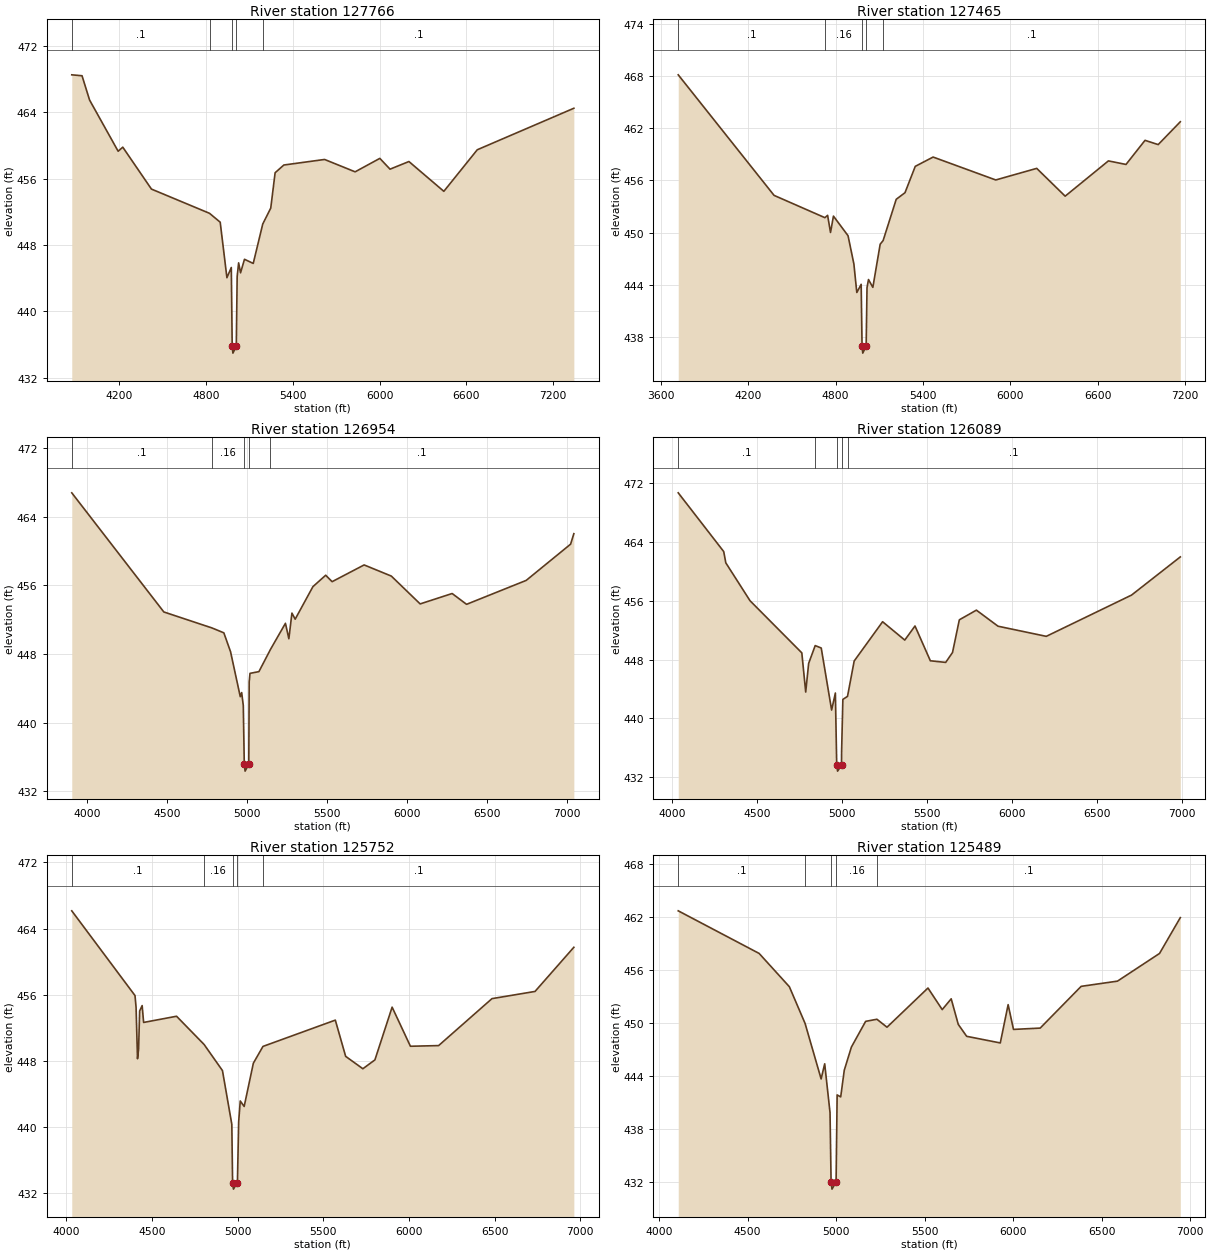
Type RM Length L Ch R = 1 ,127766  ,301,301,301
BEGIN DESCRIPTION:
Mapping XS 4aa8988c
END DESCRIPTION:
XS GIS Cut Line= 4
      2051253.04     13497462.07      2050531.77     13497249.03
      2049955.38     13497165.69      2047831.19     13496951.66
#Sta/Elev= 30
  3873.1   468.5    3944  468.39  3996.2  465.46  4193.6  459.29  4225.6  459.78
  4423.7  454.73  4824.9  451.81  4898.8  450.74  4945.2  444.05  4975.5  445.28
  4981.7  435.76  4986.7  434.96  5009.9  435.76    5016  444.18  5026.1  445.84
  5039.5  444.64  5066.5  446.27  5127.1  445.77  5192.8  450.52  5248.1  452.44
  5278.3   456.7  5338.6  457.63    5620   458.3  5831.1  456.81  6001.9  458.43
  6072.3  457.13  6202.9  458.05  6444.2  454.46  6675.3  459.47  7342.5  464.47
#Mann= 5 ,-1 , 0
  3873.1      .1       0  4824.9     .16       0  4981.7     .07       0
  5009.9     .16       0  5192.8      .1       0
Bank Sta=4981.7,5009.9
XS Rating Curve= 0 ,0
Exp/Cntr=0.3,0.1

Type RM Length L Ch R = 1 ,127465  ,511,511,511
BEGIN DESCRIPTION:
Mapping XS f16d5147
END DESCRIPTION:
XS GIS Cut Line= 4
      2051435.32     13497149.57      2050530.03     13496934.79
      2049983.16      13496896.6      2048023.85     13496701.65
#Sta/Elev= 30
  3719.5  468.11  4377.6  454.27  4726.7  451.71  4745.2  451.98  4765.2  450.01
  4785.3  451.89  4885.5  449.64  4925.6   446.4  4945.7  443.12  4975.7  444.06
  4981.7  436.96  4986.7  436.16  5009.9  436.96  5015.8  443.67  5025.9  444.61
  5055.9  443.71  5106.1  448.66  5126.3  449.08  5216.4  453.82  5276.7  454.58
    5347   457.6  5469.7  458.67  5899.7  456.04  6181.1  457.37  6376.4  454.18
  6673.5  458.23  6794.1  457.82  6924.8  460.59  7015.2   460.1  7167.1  462.72
#Mann= 5 ,-1 , 0
  3719.5      .1       0  4726.7     .16       0  4981.7     .07       0
  5009.9     .16       0  5126.3      .1       0
Bank Sta=4981.7,5009.9
XS Rating Curve= 0 ,0
Exp/Cntr=0.3,0.1

Type RM Length L Ch R = 1 ,126954  ,865,865,865
BEGIN DESCRIPTION:
Mapping XS b461b9aa
END DESCRIPTION:
XS GIS Cut Line= 4
       2051388.5     13496732.92      2050955.19      13496566.6
      2049973.42     13496402.54      2048294.69     13496472.49
#Sta/Elev= 30
  3904.8  466.79  4480.6  452.91  4781.7  451.05  4855.8  450.48  4897.9  448.27
  4958.6  443.04  4967.3  443.52  4977.4  442.01  4983.6  435.17  4988.7  434.37
  5011.8  435.17  5014.3  444.77  5019.4  445.76  5075.1  445.96  5147.5  448.55
    5241  451.59  5262.4  449.79  5281.6  452.78  5301.9  452.07  5412.8  455.86
  5492.8  457.19  5532.9  456.44  5733.1  458.39  5903.2  457.09  6083.4  453.85
  6283.5  455.06  6373.6   453.8  6746.7  456.59  7024.2  460.81  7044.5  462.03
#Mann= 5 ,-1 , 0
  3904.8      .1       0  4781.7     .16       0  4983.6     .07       0
  5011.8     .16       0  5147.5      .1       0
Bank Sta=4983.6,5011.8
XS Rating Curve= 0 ,0
Exp/Cntr=0.3,0.1

Type RM Length L Ch R = 1 ,126089  ,337,337,337
BEGIN DESCRIPTION:
Mapping XS 264a9c13
END DESCRIPTION:
XS GIS Cut Line= 4
      2051461.43     13496139.18      2051014.41     13495901.81
      2050464.06     13495644.86      2048629.06     13495800.53
#Sta/Elev= 30
  4037.4  470.71  4305.1  462.71  4317.5  461.17    4460  456.01  4764.8  448.91
  4787.7  443.57    4805  447.47  4843.5   449.9  4879.1  449.57  4940.2  441.12
  4962.3  443.44  4970.2   433.6  4975.3   432.8  4998.4   433.6  4998.9  435.45
  5006.4  442.57  5033.7  442.98    5073   447.8  5240.3  453.15  5370.8  450.65
    5431  452.57  5521.3  447.83  5611.6  447.61  5651.8  448.96  5691.9  453.41
  5792.3  454.73  5919.6  452.54  6203.7  451.16  6705.5  456.78  6992.5  461.98
#Mann= 5 ,-1 , 0
  4037.4      .1       0  4843.5     .16       0  4970.2     .07       0
  4998.4     .16       0  5033.7      .1       0
Bank Sta=4970.2,4998.4
XS Rating Curve= 0 ,0
Exp/Cntr=0.3,0.1

Type RM Length L Ch R = 1 ,125752  ,263,263,263
BEGIN DESCRIPTION:
Mapping XS 3939d8de
END DESCRIPTION:
XS GIS Cut Line= 4
      2051544.73     13495920.41      2051035.24     13495547.64
      2050542.19      13495358.4      2048779.52     13495534.95
#Sta/Elev= 30
  4031.9  466.15  4401.1   455.9  4407.3  454.47  4415.7  448.26    4422  449.43
  4428.2  454.04  4442.8  454.69  4451.3  452.65  4643.6   453.4  4804.6  449.98
  4911.5  446.83  4966.2  440.33  4970.7  433.29  4975.7  432.49  4998.9  433.29
  5006.2  440.64  5015.5  443.15  5038.3  442.49  5091.9  447.72    5148  449.75
  5570.4  452.93  5630.7  448.55  5731.2  447.05  5801.5  448.12    5902   454.5
  6008.8  449.77  6173.4  449.85  6484.9  455.53  6736.2   456.4  6962.8  461.74
#Mann= 5 ,-1 , 0
  4031.9      .1       0  4804.6     .16       0  4970.7     .07       0
  4998.9     .16       0    5148      .1       0
Bank Sta=4970.7,4998.9
XS Rating Curve= 0 ,0
Exp/Cntr=0.3,0.1

Type RM Length L Ch R = 1 ,125489  ,473,473,473
BEGIN DESCRIPTION:
Mapping XS 27552c99
END DESCRIPTION:
XS GIS Cut Line= 4
      2051596.78     13495524.56      2050958.85     13495207.36
      2050599.48      13495170.9      2048848.37     13495357.74
#Sta/Elev= 30
  4108.6  462.67  4565.5  457.85    4736  454.09  4824.9  449.93  4915.4  443.66
  4935.5  445.37  4965.6  439.86  4971.6     432  4976.7   431.2  4999.8     432
  5005.8  441.85  5025.9  441.63    5046  444.64  5086.2  447.26  5166.6  450.17
  5230.3  450.41  5287.3  449.51  5518.6  453.94  5599.1   451.5  5649.7  452.72
  5689.6  449.83  5737.1  448.48  5926.9  447.73  5971.2  452.06  6001.4  449.26
  6152.2  449.41  6383.5  454.13  6588.6  454.72    6826  457.85  6943.3   461.9
#Mann= 5 ,-1 , 0
  4108.6      .1       0  4824.9     .16       0  4971.6     .07       0
  4999.8     .16       0  5230.3      .1       0
Bank Sta=4971.6,4999.8
XS Rating Curve= 0 ,0
Exp/Cntr=0.3,0.1

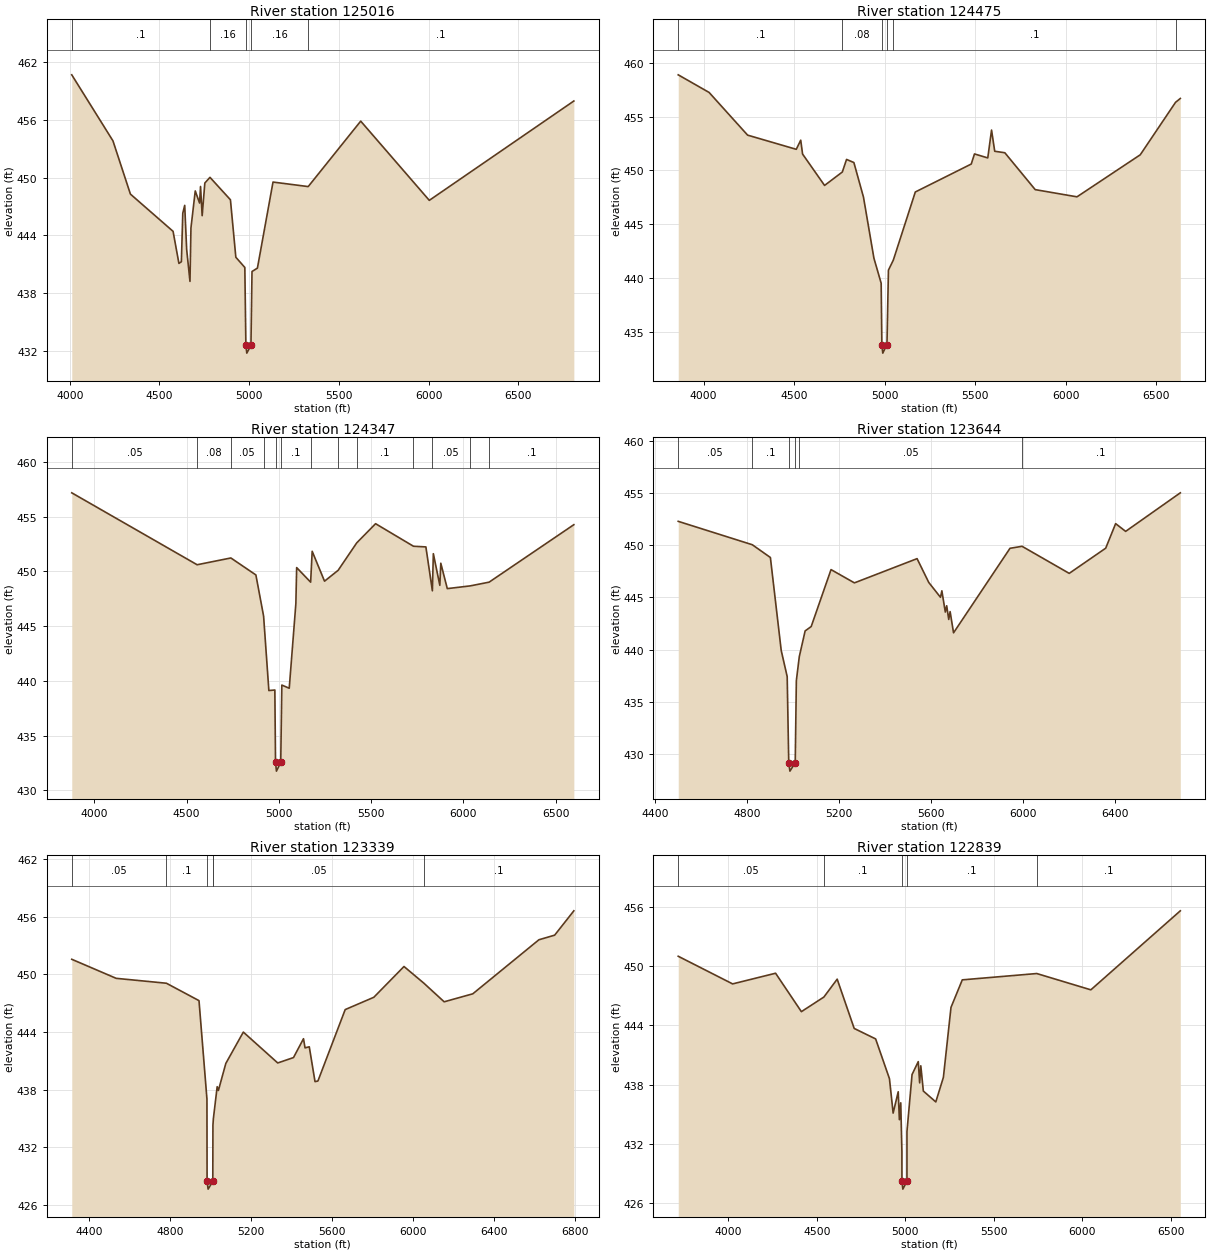
Type RM Length L Ch R = 1 ,125016  ,541,541,541
BEGIN DESCRIPTION:
Mapping XS 9d9fe8d0
END DESCRIPTION:
XS GIS Cut Line= 4
      2051737.39      13495050.6      2050973.61     13494737.63
       2050676.3     13494720.27      2049055.17     13495139.15
#Sta/Elev= 30
  4011.5  460.69    4241  453.83  4338.3   448.3    4576  444.43  4608.5   441.1
  4622.2  441.27  4630.1  446.32  4640.8  447.13  4651.7  442.55  4670.2  439.23
  4675.6  444.79  4699.6  448.63  4723.6  447.37    4729  449.09  4738.1  446.06
    4753  449.45  4781.6  450.04  4895.6  447.71  4925.7  441.74  4975.8  440.68
  4981.7  432.58  4986.7  431.78  5009.9  432.58  5015.8  440.26  5045.9  440.61
  5132.9  449.55    5329  449.08  5621.5  455.88  6003.7  447.65  6809.1  457.97
#Mann= 5 ,-1 , 0
  4011.5      .1       0  4781.6     .16       0  4981.7     .07       0
  5009.9     .16       0    5329      .1       0
Bank Sta=4981.7,5009.9
XS Rating Curve= 0 ,0
Exp/Cntr=0.3,0.1

Type RM Length L Ch R = 1 ,124475  ,128,128,128
BEGIN DESCRIPTION:
Mapping XS 9f5484a4
END DESCRIPTION:
XS GIS Cut Line= 4
      2051763.46     13494409.99      2050755.51     13494253.69
      2050463.63     13494268.88      2049070.74     13494706.88
#Sta/Elev= 30
  3860.5  458.89    4031  457.25  4243.5  453.28  4512.3  451.96  4536.9  452.81
  4547.1  451.52  4668.5   448.6  4766.7  449.85  4789.9  451.02  4830.4  450.73
  4883.3  447.52  4941.1  441.83  4981.1   439.5  4984.9   433.8    4990     433
  5013.1   433.8  5021.2  440.72  5048.1  441.65  5169.6  447.99  5478.5  450.59
  5496.3  451.53  5569.7  451.16  5590.6  453.75  5608.1  451.78    5664  451.64
  5831.7  448.21  6062.4  447.54  6411.7  451.45  6606.5  456.33  6632.9  456.69
#Mann= 6 ,-1 , 0
  3860.5      .1       0  4766.7     .08       0  4984.9     .07       0
  5013.1     .08       0  5048.1      .1       0  6606.5     .05       0
Bank Sta=4984.9,5013.1
XS Rating Curve= 0 ,0
Exp/Cntr=0.3,0.1

Type RM Length L Ch R = 1 ,124347  ,703,703,703
BEGIN DESCRIPTION:
Mapping XS b5766e75
END DESCRIPTION:
XS GIS Cut Line= 5
      2051732.23     13494107.91      2050752.25       13494130.
      2050511.37     13494150.61      2050239.02     13494183.16
      2049055.16     13494493.32
#Sta/Elev= 30
  3877.8  457.18    4557  450.61  4739.8  451.23  4875.3  449.68  4917.1  445.92
  4945.6  439.12    4978  439.17  4981.7  432.56  4986.7  431.76  5009.9  432.56
  5015.9  439.62    5056  439.33  5091.9  447.06  5096.2  450.35  5171.9  449.02
  5180.3  451.84  5247.2  449.11  5320.8   450.1  5421.7  452.61  5523.8  454.36
  5729.1   452.3  5796.3  452.24  5831.5  448.23  5836.7  451.62  5871.9  448.73
  5877.1  450.75  5912.3  448.43  6036.5  448.68  6138.9  449.02  6597.9  454.27
#Mann= 13 ,-1 , 0
  3877.8     .05       0    4557     .08       0  4739.8     .05       0
  4917.1      .1       0  4981.7     .07       0  5009.9      .1       0
  5171.9     .05       0  5320.8     .08       0  5421.7      .1       0
  5729.1     .08       0  5831.5     .05       0  6036.5     .08       0
  6138.9      .1       0
Bank Sta=4981.7,5009.9
XS Rating Curve= 0 ,0
Exp/Cntr=0.3,0.1

Type RM Length L Ch R = 1 ,123644  ,305,305,305
BEGIN DESCRIPTION:
Mapping XS c490534e
END DESCRIPTION:
XS GIS Cut Line= 4
      2050872.88     13493550.62      2050509.63     13493515.85
      2050285.67     13493583.55      2048971.82     13494472.49
#Sta/Elev= 30
  4500.5  452.27  4822.9  450.03  4901.6  448.81  4948.7  439.91  4974.7  437.41
  4981.5  429.16  4986.6  428.36  5009.7  429.16  5014.6  437.02  5027.4  439.32
  5052.8  441.78  5079.2   442.2  5165.5  447.65  5267.3  446.38    5540   448.7
  5590.9  446.42  5641.9     445  5647.9  445.62  5662.9  443.59  5668.9  444.19
  5677.8  442.88  5683.8  443.63  5698.8   441.6  5944.5  449.69    5997  449.88
  6202.2  447.29    6361   449.7  6404.2  452.05  6447.8  451.31  6685.7     455
#Mann= 6 ,-1 , 0
  4500.5     .05       0  4822.9      .1       0  4981.5     .07       0
  5009.7      .1       0  5027.4     .05       0    5997      .1       0
Bank Sta=4981.5,5009.7
XS Rating Curve= 0 ,0
Exp/Cntr=0.3,0.1

Type RM Length L Ch R = 1 ,123339  ,500,500,500
BEGIN DESCRIPTION:
Mapping XS ed4db4a5
END DESCRIPTION:
XS GIS Cut Line= 4
      2050914.47     13493409.98      2050305.64     13493266.71
      2050145.05     13493379.56      2048898.87     13494472.51
#Sta/Elev= 30
  4315.2  451.55  4534.5  449.57  4782.6  449.06  4943.5  447.25  4982.7  437.02
  4983.4  428.45  4988.5  427.65  5011.6  428.45  5012.3  434.31  5014.6     435
  5033.2   438.3  5039.3  437.91  5075.9  440.72  5162.4  443.98  5332.3  440.77
  5410.1  441.33  5459.5  443.29  5467.1  442.34    5488  442.45  5516.4  438.83
  5530.7  438.89  5665.4  446.32  5806.8   447.6  5955.8   450.8  6053.6  449.07
  6154.1  447.13  6295.5  447.96    6622  453.58  6699.8  454.06  6794.5  456.59
#Mann= 6 ,-1 , 0
  4315.2     .05       0  4782.6      .1       0  4983.4     .07       0
  5011.6      .1       0  5014.6     .05       0  6053.6      .1       0
Bank Sta=4983.4,5011.6
XS Rating Curve= 0 ,0
Exp/Cntr=0.3,0.1

Type RM Length L Ch R = 1 ,122839  ,500,500,500
BEGIN DESCRIPTION:
Mapping XS b3698418
END DESCRIPTION:
XS GIS Cut Line= 4
      2050966.56     13493258.93      2050142.69     13492899.06
      2049599.28     13493350.45       2048836.4     13494316.23
#Sta/Elev= 30
  3716.8  451.01    4024  448.21  4266.7  449.29  4412.5   445.4  4539.6  446.88
  4614.7  448.69  4710.8   443.7  4831.9  442.64    4910  438.61  4930.8  435.13
  4959.5  437.29    4966  434.46  4973.8  436.17  4980.3  431.22  4980.5  428.23
  4985.6  427.43  5008.8  428.23  5008.9  433.26  5037.6  439.03  5072.7  440.34
  5080.6  438.19  5087.1  439.92  5101.4  437.36  5171.8  436.26  5214.7  438.75
  5257.6  445.83  5321.4  448.62  5742.1  449.26  6047.6  447.61    6553  455.61
#Mann= 5 ,-1 , 0
  3716.8     .05       0  4539.6      .1       0  4980.5     .03       0
  5008.8      .1       0  5742.1      .1       0
Bank Sta=4980.5,5008.8
XS Rating Curve= 0 ,0
Exp/Cntr=0.3,0.1

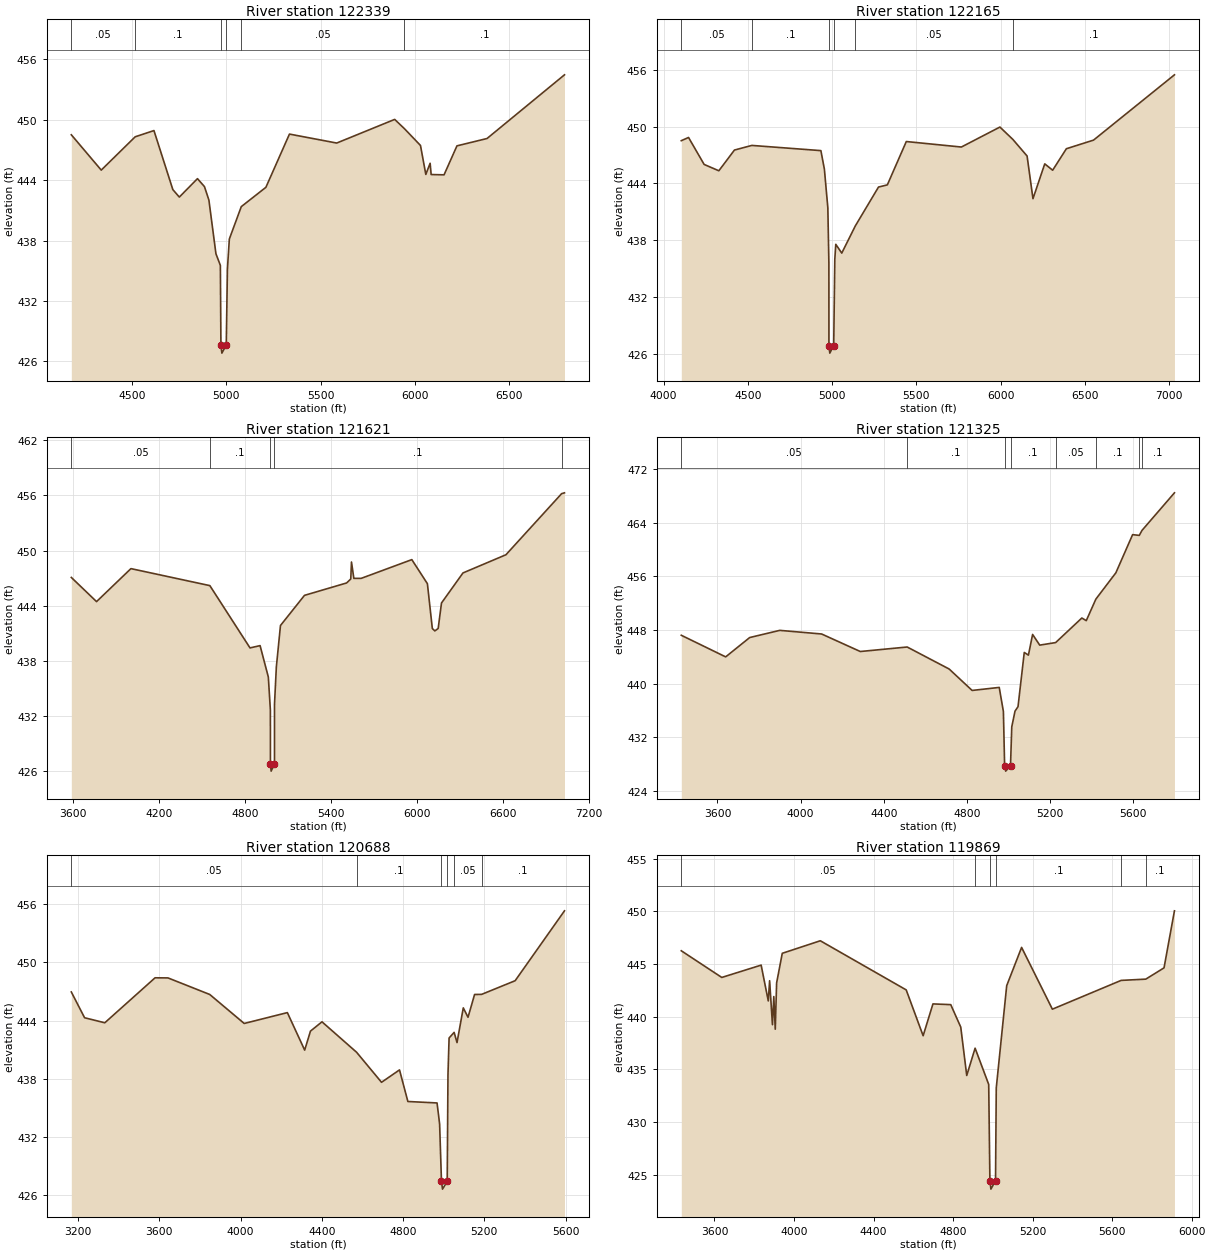
Type RM Length L Ch R = 1 ,122339  ,174,174,174
BEGIN DESCRIPTION:
Mapping XS ad705c23
END DESCRIPTION:
XS GIS Cut Line= 4
      2050508.23     13492847.48      2049892.01     13492685.12
      2049535.24     13492745.01        2048846.     13494203.66
#Sta/Elev= 30
    4179  448.51  4337.5     445  4517.3  448.31  4616.7  448.93  4716.8  443.06
  4751.1  442.32  4847.2  444.15  4884.2  443.36  4907.8  442.02    4945  436.69
  4968.5  435.53  4971.4  427.61  4976.5  426.81  4999.7  427.61  5005.9  435.18
    5016  438.15  5079.3  441.37  5209.7  443.29  5334.5  448.58  5584.9  447.69
  5891.9  450.04  5943.4  449.12  6028.5  447.45  6056.8  444.57  6079.6  445.68
  6085.1  444.56  6153.4  444.53  6221.7  447.41    6381  448.14  6791.3  454.47
#Mann= 6 ,-1 , 0
    4179     .05       0  4517.3      .1       0  4971.4     .07       0
  4999.7      .1       0  5079.3     .05       0  5943.4      .1       0
Bank Sta=4971.4,4999.7
XS Rating Curve= 0 ,0
Exp/Cntr=0.3,0.1

Type RM Length L Ch R = 1 ,122165  ,544,544,544
BEGIN DESCRIPTION:
Mapping XS 79783cc7
END DESCRIPTION:
XS GIS Cut Line= 4
      2050586.37     13492805.82       2049820.4     13492534.07
      2049503.99      13492614.8      2048793.91     13494255.76
#Sta/Elev= 30
  4105.1  448.51  4148.1  448.85  4240.7     446    4328  445.33  4420.6  447.52
  4523.8  448.01  4933.7  447.46  4954.4  445.51    4975  441.42  4981.2  435.56
  4981.5  426.86  4986.6  426.06  5009.8  426.86  5016.3  435.97  5022.1  437.56
  5057.6  436.63  5138.3  439.51  5275.7  443.61  5328.2  443.84  5440.7  448.42
  5767.6  447.84  5996.4  449.95  6073.4  448.64  6157.7  446.89  6192.6  442.38
  6262.5  446.06  6309.5  445.39  6390.9  447.66  6552.1  448.57  7032.4  455.47
#Mann= 6 ,-1 , 0
  4105.1     .05       0  4523.8      .1       0  4981.5     .07       0
  5009.8      .1       0  5138.3     .05       0  6073.4      .1       0
Bank Sta=4981.5,5009.8
XS Rating Curve= 0 ,0
Exp/Cntr=0.3,0.1

Type RM Length L Ch R = 1 ,121621  ,296,296,296
BEGIN DESCRIPTION:
Mapping XS f68b55f5
END DESCRIPTION:
XS GIS Cut Line= 6
      2050523.32     13492721.32      2049593.38     13492134.74
      2049495.73     13492158.61      2049285.22     13492327.88
      2049142.87     13493234.93      2048710.56     13494198.51
#Sta/Elev= 30
    3586  447.08  3762.2  444.45  4002.3  448.04  4553.6  446.19    4834  439.41
  4904.4  439.66    4962  436.24  4976.4   432.6  4976.6   426.8  4981.7     426
  5004.9   426.8  5005.1  433.29    5018  437.34  5046.8  441.85  5214.5  445.13
  5508.7  446.48  5537.7  446.91  5542.7  448.76  5559.3  446.98  5610.4  446.98
  5964.2  449.02    6073   446.4  6107.4  441.52  6125.1  441.26  6148.3  441.53
  6171.4   444.3  6321.5  447.57  6621.5  449.55  7010.5   456.2  7030.4  456.29
#Mann= 5 ,-1 , 0
    3586     .05       0  4553.6      .1       0  4976.6     .07       0
  5004.9      .1       0  7010.5     .05       0
Bank Sta=4976.6,5004.9
XS Rating Curve= 0 ,0
Exp/Cntr=0.3,0.1

Type RM Length L Ch R = 1 ,121325  ,637,637,637
BEGIN DESCRIPTION:
Mapping XS fc2eaa3b
END DESCRIPTION:
XS GIS Cut Line= 4
      2050567.86     13492718.84      2049569.51     13492045.77
       2048959.7     13492097.85      2048435.37     13492284.98
#Sta/Elev= 30
  3425.9  447.22  3639.4     444    3755  446.88  3899.7  447.95  4101.1  447.41
  4287.1   444.8  4512.8  445.47  4714.8  442.19  4825.2     439  4955.6  439.45
  4975.7  435.86  4981.6  427.78  4986.7  426.98  5009.9  427.78  5015.9  433.57
  5031.6  435.92    5046  436.58  5076.1  444.66  5096.1  444.26  5116.2  447.34
  5150.5  445.75  5227.1  446.13  5353.1  449.79  5374.4   449.4  5420.7  452.61
  5516.9  456.53  5597.4  462.21  5629.5   462.1  5642.5  462.84  5798.7  468.44
#Mann= 8 ,-1 , 0
  3425.9     .05       0  4512.8      .1       0  4981.6     .07       0
  5009.9      .1       0  5227.1     .05       0  5420.7      .1       0
  5629.5     .05       0  5642.5      .1       0
Bank Sta=4981.6,5009.9
XS Rating Curve= 0 ,0
Exp/Cntr=0.3,0.1

Type RM Length L Ch R = 1 ,120688  ,819,819,819
BEGIN DESCRIPTION:
Mapping XS 8ff74b6a
END DESCRIPTION:
XS GIS Cut Line= 4
      2050528.22     13492653.98      2049492.94     13491730.36
      2048968.38     13491498.89       2048523.9     13491642.63
#Sta/Elev= 30
  3166.7  446.96    3232   444.3  3331.5  443.78    3579  448.42  3642.5  448.41
  3848.2   446.7  4017.9  443.71  4230.3  444.83  4315.6  440.96    4344  442.92
  4400.8  443.88  4571.1  440.74  4693.9  437.64  4782.4  438.92  4823.6  435.66
  4967.2  435.51  4979.8  433.37    4989  427.42  4994.1  426.62  5017.3  427.42
    5021  438.41  5026.5  442.21  5051.3  442.79  5065.6  441.74  5096.4  445.32
  5119.7  444.35    5152   446.7  5186.6  446.71  5351.7  448.12  5594.6  455.33
#Mann= 6 ,-1 , 0
  3166.7     .05       0  4571.1      .1       0    4989     .07       0
  5017.3      .1       0  5051.3     .05       0  5186.6      .1       0
Bank Sta=4989,5017.3
XS Rating Curve= 0 ,0
Exp/Cntr=0.3,0.1

Type RM Length L Ch R = 1 ,119869  ,193,193,193
BEGIN DESCRIPTION:
Mapping XS c3f77533
END DESCRIPTION:
XS GIS Cut Line= 4
      2050557.07     13492650.39        2049700.       13491700.
      2049663.09     13491323.98      2048842.79     13491263.81
#Sta/Elev= 30
  3433.4  446.26    3637  443.73    3835   444.9  3870.9   441.5  3877.6  443.42
  3891.8  439.25  3898.6  441.92    3906  438.82  3912.8  443.21  3941.2  446.02
  4132.5  447.21  4564.4  442.55  4649.6   438.2    4699  441.22  4788.5  441.15
  4838.8  439.02  4868.9  434.43    4911  437.02  4979.4  433.58  4985.4  424.45
  4990.4  423.65  5013.7  424.45  5017.4  433.25  5069.9  442.95  5144.8  446.58
  5299.6  440.72  5645.3  443.45  5769.4  443.57  5861.1  444.64  5913.5  450.05
#Mann= 6 ,-1 , 0
  3433.4     .05       0    4911      .1       0  4985.4     .07       0
  5013.7      .1       0  5645.3     .05       0  5769.4      .1       0
Bank Sta=4985.4,5013.7
XS Rating Curve= 0 ,0
Exp/Cntr=0.3,0.1

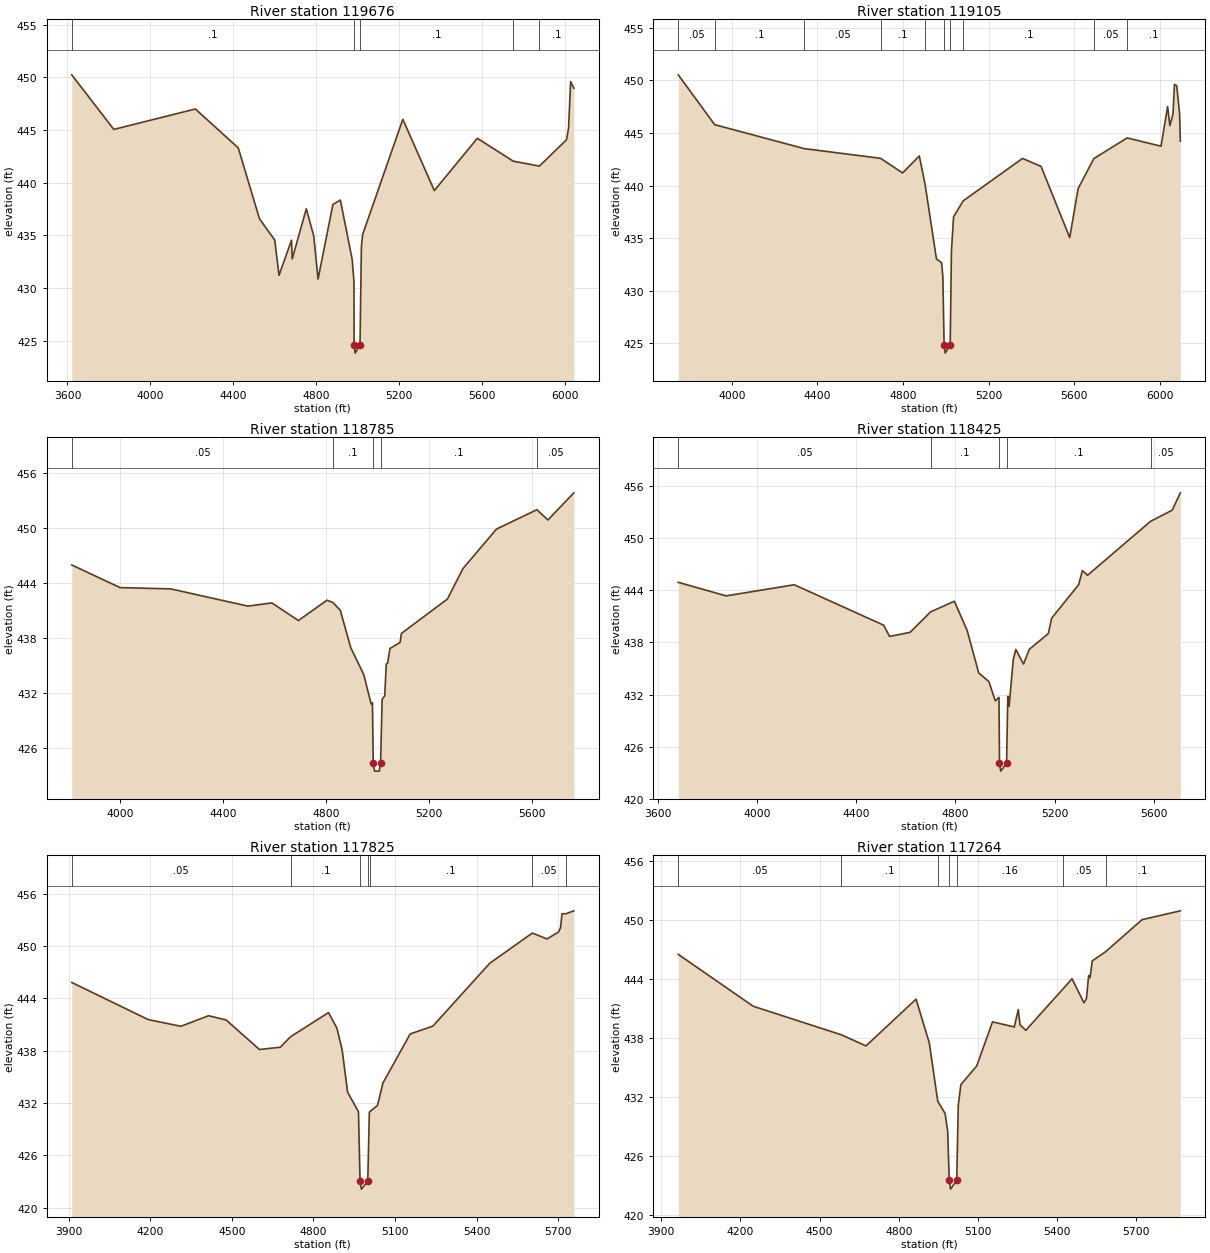
Type RM Length L Ch R = 1 ,119676  ,571,571,571
BEGIN DESCRIPTION:
Mapping XS 768258cb
END DESCRIPTION:
XS GIS Cut Line= 4
      2051130.97     13491263.82      2050103.19     13491540.12
      2049660.48     13491235.44      2048839.64     13491204.79
#Sta/Elev= 30
  3620.8  450.23  3823.7  445.05  4217.2  446.99  4424.3   443.3  4526.6  436.58
  4600.4  434.55  4621.1  431.22  4681.3  434.54  4684.8  432.77  4752.7  437.52
  4788.6  434.94  4809.5  430.86  4881.2  437.93  4917.1  438.35  4974.2  432.72
  4982.7  430.58  4983.4  424.63  4988.5  423.83  5011.9  424.63  5018.6  433.92
  5024.6  435.08  5218.5  446.01  5370.6  439.25  5578.2  444.21  5751.5  442.04
  5877.6  441.57  6008.5  444.07  6018.5   445.2  6028.5  449.59  6043.9  448.96
#Mann= 5 ,-1 , 0
  3620.8      .1       0  4983.4     .07       0  5011.9      .1       0
  5751.5     .05       0  5877.6      .1       0
Bank Sta=4983.4,5011.9
XS Rating Curve= 0 ,0
Exp/Cntr=0.3,0.1

Type RM Length L Ch R = 1 ,119105  ,320,320,320
BEGIN DESCRIPTION:
Mapping XS 17b5a254
END DESCRIPTION:
XS GIS Cut Line= 4
      2051082.41     13491069.37      2050063.02      13490824.5
      2049661.98     13490836.65      2048819.21     13491142.03
#Sta/Elev= 30
  3749.3  450.53  3919.7  445.79  4338.2  443.51  4694.5  442.59  4797.7   441.2
  4875.7  442.81  4902.7  440.12  4955.8  433.02  4980.1  432.66  4985.8   431.3
  4991.6  424.86  4996.7  424.06  5020.1  424.86  5025.8  433.71  5035.8  437.02
  5080.7  438.54    5358  442.58  5444.6  441.82  5578.6  435.05  5617.8  439.71
  5691.2  442.56  5846.7  444.53  6005.3  443.74    6036  447.51  6046.6  445.69
  6061.3  446.82  6067.9  449.61  6078.5   449.5  6091.9  446.84  6095.3  444.22
#Mann= 10 ,-1 , 0
  3749.3     .05       0  3919.7      .1       0  4338.2     .05       0
  4694.5      .1       0  4902.7     .16       0  4991.6     .07       0
  5020.1     .16       0  5080.7      .1       0  5691.2     .05       0
  5846.7      .1       0
Bank Sta=4991.6,5020.1
XS Rating Curve= 0 ,0
Exp/Cntr=0.3,0.1

Type RM Length L Ch R = 1 ,118785  ,360,360,360
BEGIN DESCRIPTION:
Mapping XS 4ba24e17
END DESCRIPTION:
XS GIS Cut Line= 4
      2050957.43     13490708.26      2050089.06     13490482.48
      2049517.88     13490584.91      2049044.25     13490579.78
#Sta/Elev= 30
  3811.7     446  3999.3  443.53  4196.5  443.39  4496.2  441.51  4589.2  441.86
  4692.5  439.94  4803.8  442.16  4826.8   441.9  4855.3  441.05  4895.9  436.98
  4946.7  434.02  4975.1  430.84  4980.2  430.97  4983.3  424.41  4988.4  423.51
  5006.7  423.51  5011.8  424.41  5017.9  431.35    5028  431.73  5033.9  435.19
    5039  435.26  5048.3  436.89  5087.7  437.55  5092.7  438.53  5271.8  442.29
  5332.1  445.61  5462.1  449.91  5619.2  452.03  5662.1  450.91  5762.9  453.87
#Mann= 5 ,-1 , 0
  3811.7     .05       0  4826.8      .1       0  4983.3     .07       0
  5011.8      .1       0  5619.2     .05       0
Bank Sta=4983.3,5011.8
XS Rating Curve= 0 ,0
Exp/Cntr=0.3,0.1

Type RM Length L Ch R = 1 ,118425  ,600,600,600
BEGIN DESCRIPTION:
Mapping XS debf550d
END DESCRIPTION:
XS GIS Cut Line= 4
       2050957.4     13490513.81      2049993.57      13490117.9
      2049405.03     13490268.94      2049054.65     13490399.22
#Sta/Elev= 30
  3683.1   444.9  3876.1  443.34  4150.6  444.62  4510.9  439.97  4534.8  438.68
  4617.5  439.15  4700.2   441.5  4795.9  442.72  4847.5  439.36  4894.2  434.47
  4934.9  433.49    4961  431.27  4975.7  431.67  4977.8  424.09  4982.9  423.19
  5006.3  424.09  5011.3  431.79  5016.5  430.63  5033.3  436.03  5043.6  437.18
  5074.6   435.5    5098   437.2  5174.4     439  5188.2  440.78  5296.6  444.62
  5312.1  446.25  5332.7  445.71  5586.4  451.91  5674.1   453.2  5706.5  455.19
#Mann= 5 ,-1 , 0
  3683.1     .05       0  4700.2      .1       0  4977.8     .07       0
  5006.3      .1       0  5586.4     .05       0
Bank Sta=4977.8,5006.3
XS Rating Curve= 0 ,0
Exp/Cntr=0.3,0.1

Type RM Length L Ch R = 1 ,117825  ,561,561,561
BEGIN DESCRIPTION:
Mapping XS 121f04c3
END DESCRIPTION:
XS GIS Cut Line= 4
      2050842.86     13489861.05      2050102.95     13489626.58
      2049589.06     13489609.22      2049061.52     13489784.66
#Sta/Elev= 30
  3911.5  445.82  4192.5  441.57  4312.7   440.8  4414.8  442.01  4479.3  441.52
  4601.6  438.14  4678.3   438.4    4716   439.6  4855.7  442.37  4886.7  440.57
  4905.7  438.11  4925.8  433.25  4965.8  431.01  4971.5  423.04  4976.6  422.14
    5000  423.04  5005.8  430.95  5008.3  431.04  5035.8  431.73  5055.8   434.3
  5155.9  439.92  5239.5  440.82  5448.5  448.02  5605.1  451.48  5659.3  450.81
  5701.4   451.6    5709  452.09  5714.3  453.71  5728.7  453.69  5757.8  454.03
#Mann= 7 ,-1 , 0
  3911.5     .05       0    4716      .1       0  4971.5     .07       0
    5000      .1       0  5008.3      .1       0  5605.1     .05       0
  5728.7      .1       0
Bank Sta=4971.5,5000
XS Rating Curve= 0 ,0
Exp/Cntr=0.3,0.1

Type RM Length L Ch R = 1 ,117264  ,315,315,315
BEGIN DESCRIPTION:
Mapping XS beddb56d
END DESCRIPTION:
XS GIS Cut Line= 4
      2050759.48      13489402.7      2049998.78     13489076.23
      2049580.38     13489083.18       2048979.8     13489349.92
#Sta/Elev= 30
  3964.2  446.51  4248.3  441.22  4582.7  438.31    4676  437.18  4865.8  441.94
  4915.8  437.51  4948.1  431.54  4975.8   430.3  4985.8  428.47  4991.5  423.49
  4996.6  422.59    5020  423.49  5025.8  431.12  5035.8  433.24  5095.8  435.14
  5155.8  439.63  5238.2  439.11  5253.3  440.87  5260.1  439.33    5282  438.77
  5421.7  442.95  5457.1  444.02  5502.3  441.57  5511.8  441.99  5520.1  444.35
  5525.5  444.12  5533.7  445.84  5584.2  446.77  5722.6  450.04  5867.6  450.94
#Mann= 7 ,-1 , 0
  3964.2     .05       0  4582.7      .1       0  4948.1     .16       0
  4991.5     .07       0    5020     .16       0  5421.7     .05       0
  5584.2      .1       0
Bank Sta=4991.5,5020
XS Rating Curve= 0 ,0
Exp/Cntr=0.3,0.1