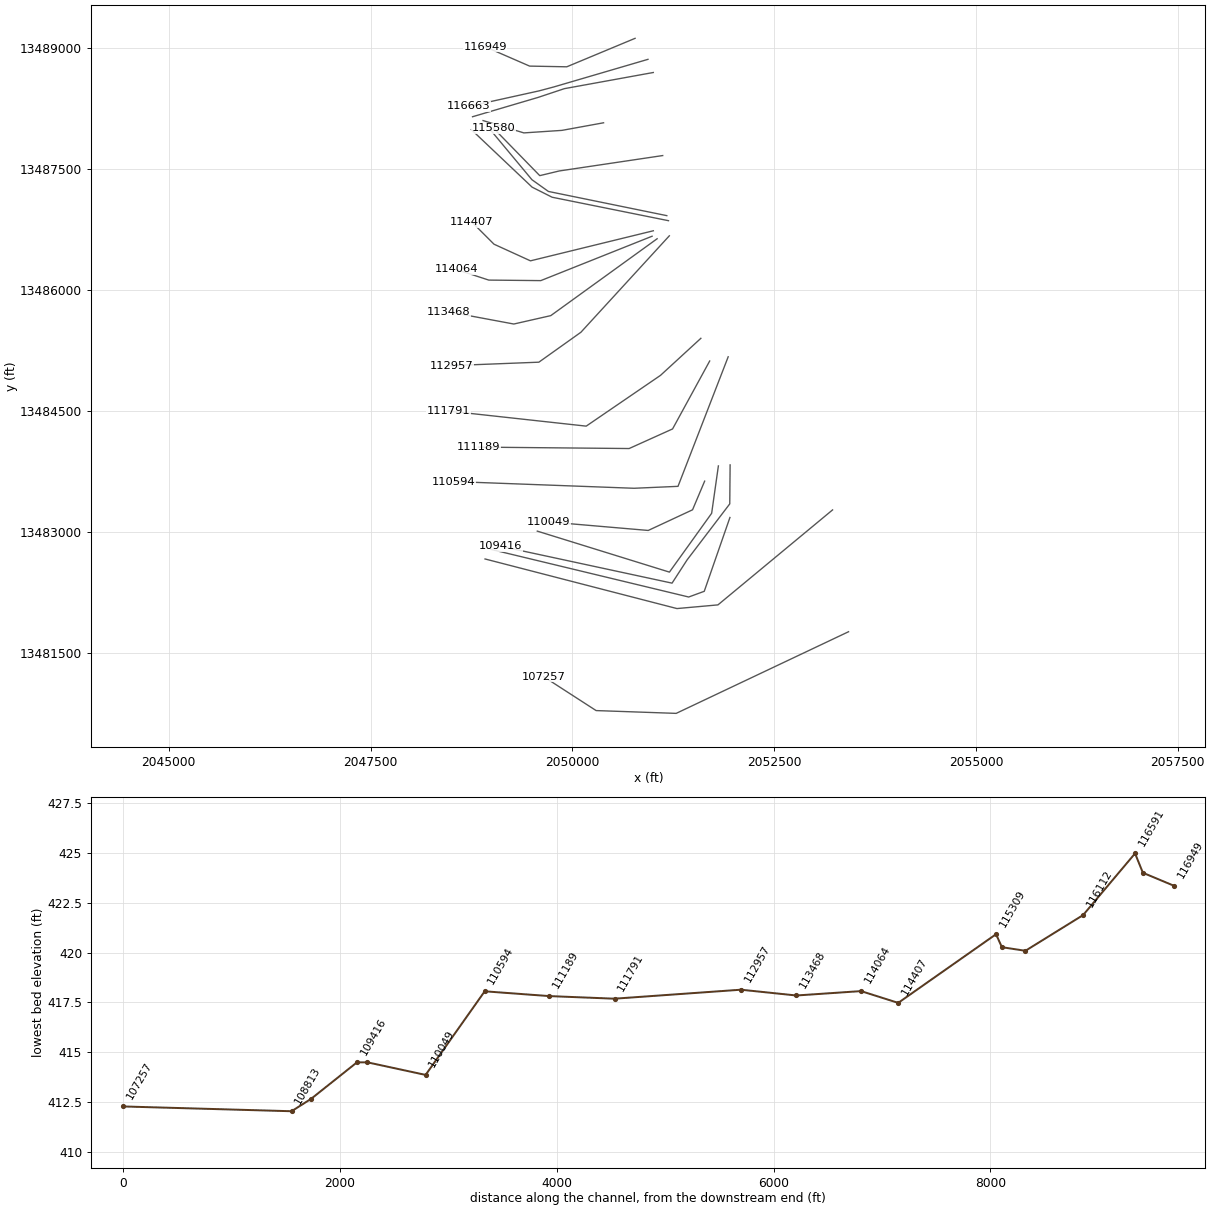
HEC-RAS study LAGUNILLAS Cr.prj: LAGUNILLAS Cr Base Level Engineering

--- LAGUNILLAS Cr.g01 (geometry) --- (continued)

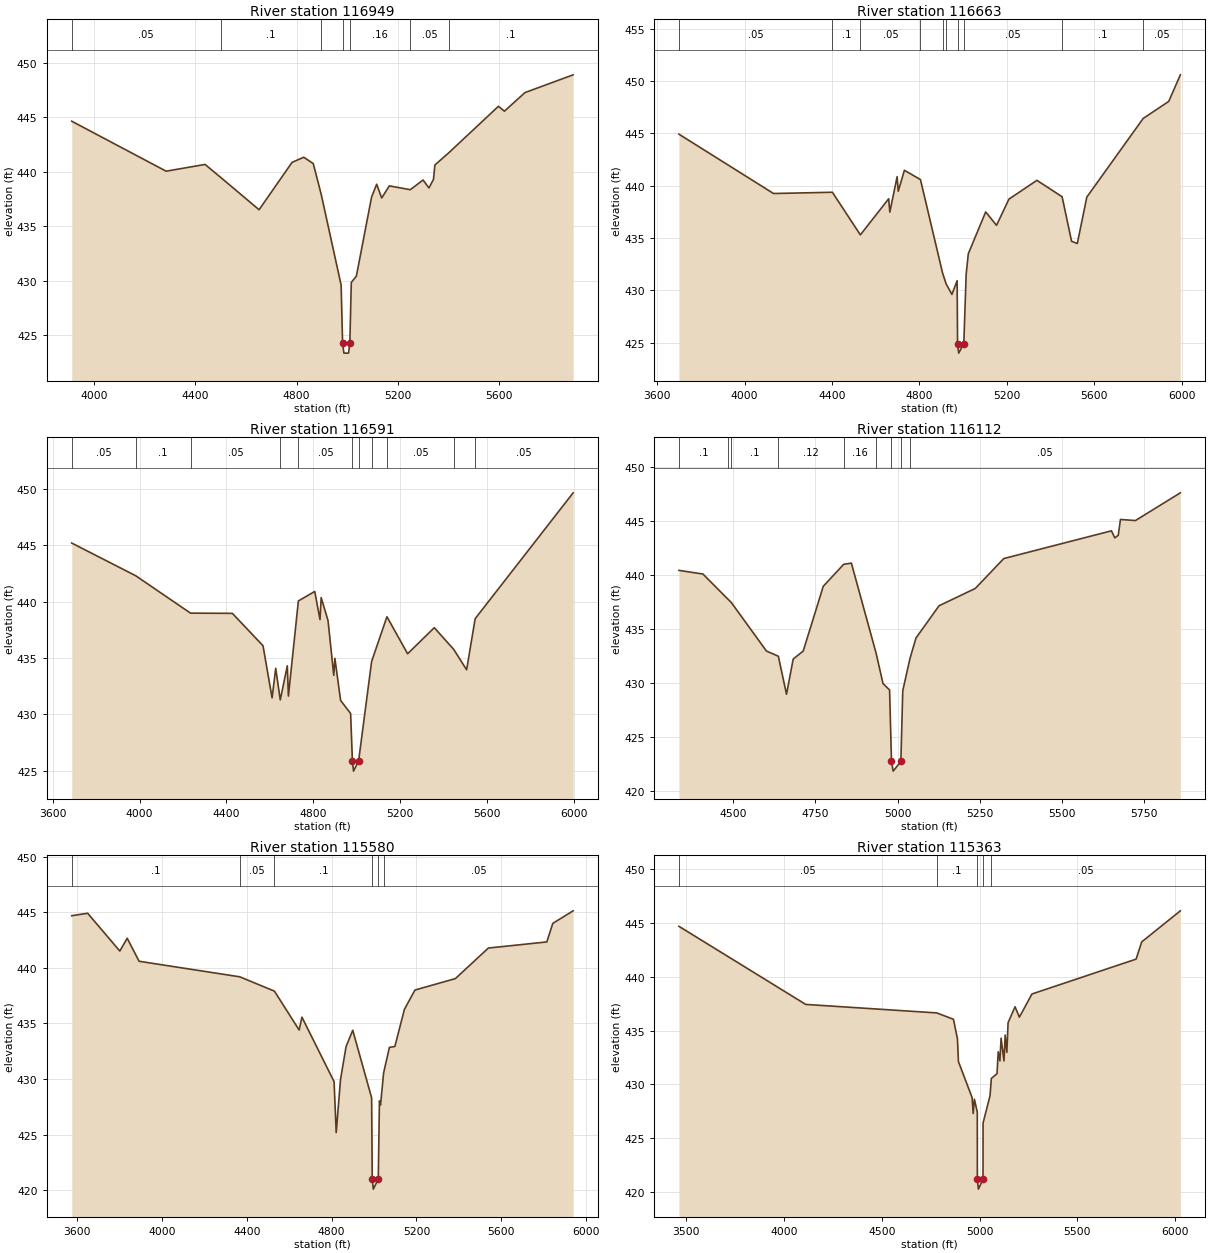
Type RM Length L Ch R = 1 ,116949  ,286,286,286
BEGIN DESCRIPTION:
Mapping XS f4044b1a
END DESCRIPTION:
XS GIS Cut Line= 4
      2050777.16     13489121.89      2049931.07     13488768.94
        2049471.     13488777.62      2048919.78     13489017.59
#Sta/Elev= 30
    3913  444.65  4285.4  440.06  4439.1  440.68  4500.6  439.49  4652.1  436.52
  4782.2  440.87  4828.4  441.34  4865.8  440.76    4897  437.95  4975.8   429.6
  4981.6  424.25  4986.7  423.35    5005  423.35  5010.1  424.25  5015.9  429.84
  5035.9  430.42  5095.9  437.68  5115.9  438.86  5135.9   437.6  5165.9  438.71
  5248.6  438.36  5298.9  439.25  5322.3  438.52  5340.1  439.31  5345.7  440.63
  5399.5  441.73  5596.4  446.02  5619.9  445.57  5701.1  447.28  5891.1  448.91
#Mann= 7 ,-1 , 0
    3913     .05       0  4500.6      .1       0    4897     .16       0
  4981.6     .07       0  5010.1     .16       0  5248.6     .05       0
  5399.5      .1       0
Bank Sta=4981.6,5010.1
XS Rating Curve= 0 ,0
Exp/Cntr=0.3,0.1

Type RM Length L Ch R = 1 ,116663  ,72,72,72
BEGIN DESCRIPTION:
Mapping XS 9be1d751
END DESCRIPTION:
XS GIS Cut Line= 4
      2050936.85     13488861.47      2049769.62     13488518.94
      2049587.32     13488470.33      2048719.01     13488278.33
#Sta/Elev= 30
  3699.4  444.92  4132.3  439.25  4401.5  439.37  4529.6   435.3  4659.2  438.75
  4664.4  437.47  4697.8  440.86    4703  439.47  4731.2  441.47  4804.6  440.58
  4906.2  431.62    4922  430.62  4948.5  429.61  4972.4  430.92  4974.4   424.9
  4979.5     424  5002.9   424.9  5013.8  431.56  5023.6   433.5  5103.1  437.49
  5152.7  436.21  5209.3  438.71  5337.5  440.51  5452.8  438.94  5496.1  434.69
  5522.3  434.47  5565.9  438.91  5823.7  446.42  5940.7  448.05  5993.8  450.59
#Mann= 10 ,-1 , 0
  3699.4     .05       0  4401.5      .1       0  4529.6     .05       0
  4804.6      .1       0  4906.2     .12       0    4922     .05       0
  4974.4     .04       0  5002.9     .05       0  5452.8      .1       0
  5823.7     .05       0
Bank Sta=4974.4,5002.9
XS Rating Curve= 0 ,0
Exp/Cntr=0.3,0.1

Type RM Length L Ch R = 1 ,116591  ,479,479,479
BEGIN DESCRIPTION:
Mapping XS d5ee58c9
END DESCRIPTION:
XS GIS Cut Line= 4
      2051002.85     13488698.28      2049901.56     13488498.11
      2049573.44     13488388.73      2048763.86     13488149.84
#Sta/Elev= 30
  3687.5  445.18  3982.4  442.28  4234.5  438.97  4427.3  438.95  4568.5  436.08
  4610.2  431.46    4627  434.08  4647.9  431.28  4680.4   434.3  4685.4  431.62
  4731.3  440.05  4806.8  440.89    4831  438.39  4836.3  440.35  4867.9  438.31
  4894.3  433.46  4899.5  434.96  4925.9  431.23  4971.9  430.08  4980.2  425.87
  4985.3  424.97  5008.7  425.87  5068.7  434.69  5139.2  438.65  5234.5  435.37
  5357.3  437.68  5447.1  435.75  5506.2  433.95  5545.6  438.48  5996.8  449.63
#Mann= 11 ,-1 , 0
  3687.5     .05       0  3982.4      .1       0  4234.5     .05       0
  4647.9      .1       0  4731.3     .05       0  4980.2     .04       0
  5008.7     .05       0  5068.7      .1       0  5139.2     .05       0
  5447.1      .1       0  5545.6     .05       0
Bank Sta=4980.2,5008.7
XS Rating Curve= 0 ,0
Exp/Cntr=0.3,0.1

Type RM Length L Ch R = 1 ,116112  ,532,532,532
BEGIN DESCRIPTION:
Double Mapping XS 032fc0f0
END DESCRIPTION:
XS GIS Cut Line= 4
      2050386.79     13488074.78      2049870.97     13487980.75
      2049399.61      13487949.5      2048894.33     13488102.31
#Sta/Elev= 30
  4335.2  440.42  4408.2  440.08  4483.5  437.78  4493.8  437.48  4601.3  432.97
  4637.5  432.49  4662.3  428.98  4682.6  432.23  4713.1  432.97  4774.1  438.95
  4836.2  440.98  4859.5  441.09  4934.8  432.76  4955.7  429.97  4975.7  429.37
  4981.5  422.78  4986.6  421.88    5010  422.78  5015.8  429.31  5037.5  432.25
  5055.9  434.17  5126.1  437.15  5236.3  438.75  5322.9  441.51  5650.2  444.07
  5660.6  443.42    5671  443.66  5677.7  445.12  5723.3  445.02  5859.8  447.58
#Mann= 9 ,-1 , 0
  4335.2      .1       0  4483.5     .12       0  4493.8      .1       0
  4637.5     .12       0  4836.2     .16       0  4934.8      .1       0
  4981.5     .07       0    5010      .1       0  5037.5     .05       0
Bank Sta=4981.5,5010
XS Rating Curve= 0 ,0
Exp/Cntr=0.3,0.1

Type RM Length L Ch R = 1 ,115580  ,217,217,217
BEGIN DESCRIPTION:
Mapping XS 9f21dc04
END DESCRIPTION:
XS GIS Cut Line= 4
      2051119.43     13487668.53      2049838.14     13487477.55
      2049596.44     13487419.55      2049022.82     13488008.59
#Sta/Elev= 30
  3573.6   444.7  3648.9  444.92  3800.5  441.52  3835.4  442.67  3891.5   440.6
  4366.8   439.2  4530.2  437.91  4646.8  434.41  4659.9  435.57  4811.6  429.77
  4821.7  425.18  4841.9  429.94  4868.1  432.91  4899.7  434.39  4988.8  428.31
  4991.7  420.99  4996.8  420.09  5020.2  420.99  5025.7  428.03  5030.8  427.67
  5045.5  430.56  5072.8  432.85  5098.5  432.93  5143.7  436.28  5193.3  438.01
  5384.1  439.04  5539.7  441.79  5815.5  442.34  5843.8  444.01  5939.8  445.14
#Mann= 6 ,-1 , 0
  3573.6      .1       0  4366.8     .05       0  4530.2      .1       0
  4991.7     .07       0  5020.2      .1       0  5045.5     .05       0
Bank Sta=4991.7,5020.2
XS Rating Curve= 0 ,0
Exp/Cntr=0.3,0.1

Type RM Length L Ch R = 1 ,115363  ,54,54,54
BEGIN DESCRIPTION:
Mapping XS a5b000bf
END DESCRIPTION:
XS GIS Cut Line= 4
      2051170.13     13486923.54      2049703.64     13487223.59
      2049499.65     13487368.99      2048977.45     13487996.44
#Sta/Elev= 30
  3462.8   444.7  4111.1  437.44  4781.2  436.65  4866.4  436.06  4886.8  434.25
  4891.9  432.13  4961.9  428.77  4967.4   427.3  4973.6  428.62  4988.3  427.43
  4988.7  421.17  4993.9  420.27  5017.5  421.17  5017.8  426.42  5053.5  428.96
  5060.2  430.56  5089.1     431  5095.3  433.04  5103.9  432.19    5110   434.3
  5124.8  432.19  5130.9  434.59  5139.5  432.98  5145.7  435.74  5181.3  437.22
  5203.6  436.26  5267.8  438.41  5800.3  441.65  5828.9  443.25  6026.5  446.14
#Mann= 5 ,-1 , 0
  3462.8     .05       0  4781.2      .1       0  4988.7     .07       0
  5017.5      .1       0  5060.2     .05       0
Bank Sta=4988.7,5017.5
XS Rating Curve= 0 ,0
Exp/Cntr=0.3,0.1

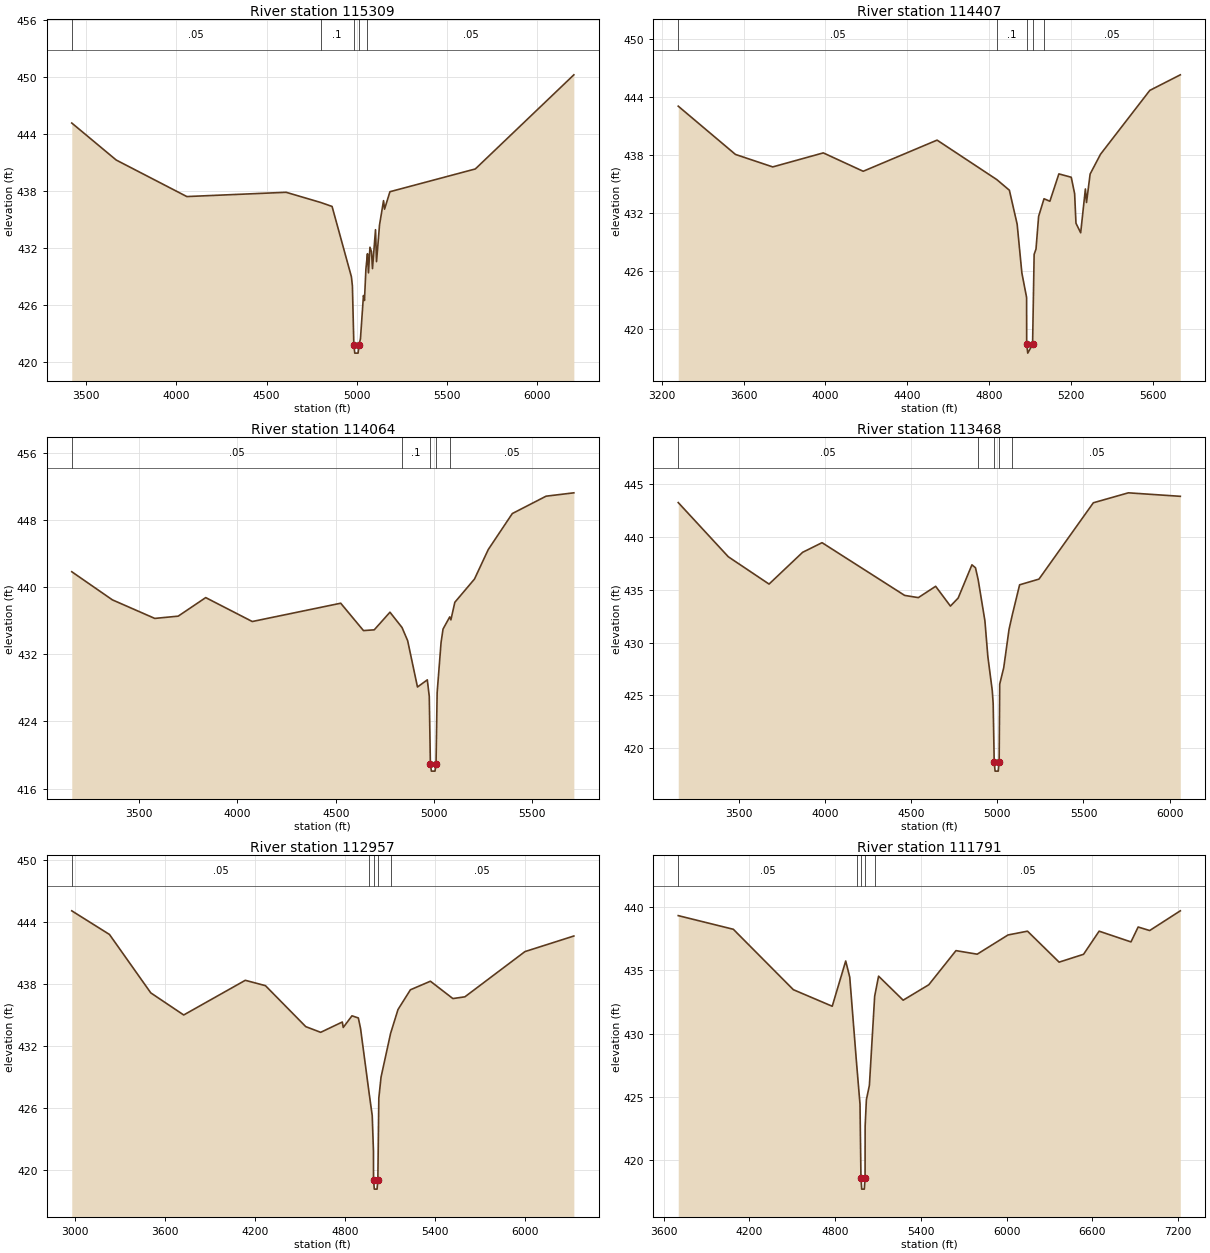
Type RM Length L Ch R = 1 ,115309  ,902,902,902
BEGIN DESCRIPTION:
Mapping XS 9060bfb6
END DESCRIPTION:
XS GIS Cut Line= 4
      2051191.03     13486861.02      2049749.22     13487151.97
      2049501.82     13487276.75      2048748.26     13487991.25
#Sta/Elev= 30
  3418.9  445.17  3665.6  441.27  4057.5  437.42  4608.4  437.87  4799.9   436.8
  4863.5  436.38  4970.8  428.97  4976.4     428  4984.3  421.82  4989.5  420.92
  5007.9  420.92  5013.1  421.82    5021  422.42  5037.7  426.99  5043.3  426.47
  5051.3  429.78  5056.6  430.77    5060   431.4  5065.6  429.38  5073.7  432.08
  5082.3  431.61  5087.9  429.83  5104.6  433.93  5110.2  430.56  5126.9  434.43
  5149.2  436.99  5154.8  436.09  5184.6  437.93  5658.6  440.33  6205.3  450.25
#Mann= 5 ,-1 , 0
  3418.9     .05       0  4799.9      .1       0  4984.3     .07       0
  5013.1      .1       0  5056.6     .05       0
Bank Sta=4984.3,5013.1
XS Rating Curve= 0 ,0
Exp/Cntr=0.3,0.1

Type RM Length L Ch R = 1 ,114407  ,343,343,343
BEGIN DESCRIPTION:
Mapping XS 04f111f4
END DESCRIPTION:
XS GIS Cut Line= 4
      2051003.45     13486736.03      2049481.28     13486363.27
      2049029.89     13486569.44      2048754.25     13486845.07
#Sta/Elev= 30
  3280.6  443.01  3560.2  438.02  3742.3  436.73  3989.4  438.18  4184.3  436.28
  4545.3   439.5  4837.8  435.41  4898.6  434.32  4936.6  430.81  4959.7  425.76
  4982.7  423.24  4983.2  418.38  4988.4  417.48    5012  418.38  5019.6  427.69
  5028.7  428.24  5041.5  431.62  5067.9  433.44  5096.5  433.18  5140.5  436.01
  5200.9  435.66  5217.4  433.97    5224  430.91    5247  429.92    5270  434.45
  5275.5  433.05  5293.1  435.99  5343.9  438.04  5584.7  444.64  5733.8  446.25
#Mann= 5 ,-1 , 0
  3280.6     .05       0  4837.8      .1       0  4983.2     .07       0
    5012      .1       0  5067.9     .05       0
Bank Sta=4983.2,5012
XS Rating Curve= 0 ,0
Exp/Cntr=0.3,0.1

Type RM Length L Ch R = 1 ,114064  ,596,596,596
BEGIN DESCRIPTION:
Mapping XS 56942101
END DESCRIPTION:
XS GIS Cut Line= 4
      2050987.81     13486668.31      2049609.31     13486118.05
      2048964.78     13486124.56      2048560.73     13486256.88
#Sta/Elev= 30
  3157.2  441.82  3363.9  438.47  3579.5  436.26  3698.6  436.53  3838.6  438.74
  4075.4  435.89  4525.3  438.07  4641.1  434.81  4695.8   434.9  4775.8     437
  4837.1  435.18  4865.8  433.61  4915.8  428.09  4965.8  428.94  4975.8  426.96
  4981.4  418.97  4986.6  418.07    5005  418.07  5010.2  418.97  5015.8   427.4
  5035.8   433.4  5045.8  434.99  5079.8  436.44  5085.8  436.09  5105.8  438.18
  5205.8  440.95  5275.8  444.46  5398.1  448.75  5569.9  450.82  5711.2  451.22
#Mann= 5 ,-1 , 0
  3157.2     .05       0  4837.1      .1       0  4981.4     .07       0
  5010.2      .1       0  5079.8     .05       0
Bank Sta=4981.4,5010.2
XS Rating Curve= 0 ,0
Exp/Cntr=0.3,0.1

Type RM Length L Ch R = 1 ,113468  ,511,511,511
BEGIN DESCRIPTION:
Mapping XS 9058590f
END DESCRIPTION:
XS GIS Cut Line= 4
      2051050.32     13486637.05      2049733.01     13485684.02
      2049275.11     13485579.85      2048468.48     13485730.55
#Sta/Elev= 30
  3146.2  443.22    3437   438.1  3673.7  435.52  3868.6  438.52  3981.5  439.43
  4461.1  434.45  4540.7  434.24  4641.3  435.31  4727.1  433.44  4772.1   434.2
  4852.1  437.34  4872.6  437.06  4888.3  435.93  4927.3  432.06  4944.4  428.69
  4970.3  425.43  4975.4  424.23  4981.3  418.75  4986.5  417.85  5004.9  417.85
  5010.1  418.75  5013.4  426.07  5036.7  427.62  5067.5  431.24  5086.9  432.64
    5129  435.45  5241.4  435.99  5557.2   443.2  5760.6  444.14  6062.3  443.81
#Mann= 5 ,-1 , 0
  3146.2     .05       0  4888.3      .1       0  4981.3     .07       0
  5010.1      .1       0  5086.9     .05       0
Bank Sta=4981.3,5010.1
XS Rating Curve= 0 ,0
Exp/Cntr=0.3,0.1

Type RM Length L Ch R = 1 ,112957  ,1166,1166,1166
BEGIN DESCRIPTION:
Mapping XS 18e9c632
END DESCRIPTION:
XS GIS Cut Line= 4
      2051201.43     13486673.57      2050106.28     13485477.86
      2049585.44     13485106.76      2048499.13     13485064.19
#Sta/Elev= 30
  2977.9   445.1  3229.3  442.81  3504.9  437.15  3724.4  435.01  4135.1  438.37
  4269.5  437.85  4538.4  433.88  4637.7  433.33  4782.1  434.33  4788.2   433.8
  4846.5  434.93    4889  434.72  4903.8  433.69    4961  427.42  4981.5  425.27
  4989.8  421.77  4990.2  419.04  4995.4  418.14  5013.8  418.14    5019  419.04
  5025.5  426.96  5040.3  428.99  5103.9  433.22  5153.4  435.54  5236.1  437.45
  5369.4  438.28  5519.5   436.6  5599.6  436.77  5999.9  441.15    6326  442.66
#Mann= 5 ,-1 , 0
  2977.9     .05       0    4961      .1       0  4990.2     .07       0
    5019      .1       0  5103.9     .05       0
Bank Sta=4990.2,5019
XS Rating Curve= 0 ,0
Exp/Cntr=0.3,0.1

Type RM Length L Ch R = 1 ,111791  ,602,602,602
BEGIN DESCRIPTION:
Mapping XS 5f3b5d5d
END DESCRIPTION:
XS GIS Cut Line= 4
      2051592.04     13485402.71      2051091.98     13484943.25
      2050171.84     13484313.91      2048461.78     13484501.66
#Sta/Elev= 30
  3701.6  439.33  4087.3  438.25  4507.3  433.47  4779.5  432.16  4873.8  435.74
  4902.1  434.46  4949.4  427.71  4973.9  424.41  4980.5  418.59  4985.7  417.69
  5004.1  417.69  5009.3  418.59  5009.8  422.66  5018.6  424.77  5039.6   425.9
  5076.5  432.95  5103.9  434.54  5275.9  432.64  5455.3  433.86  5645.6  436.56
  5794.1  436.28  6009.9   437.8  6146.2   438.1  6367.5  435.65  6538.5  436.27
  6647.5   438.1  6870.5  437.25  6920.7  438.43  7001.3  438.15  7215.8  439.71
#Mann= 5 ,-1 , 0
  3701.6     .05       0  4949.4      .1       0  4980.5     .07       0
  5009.3      .1       0  5076.5     .05       0
Bank Sta=4980.5,5009.3
XS Rating Curve= 0 ,0
Exp/Cntr=0.3,0.1

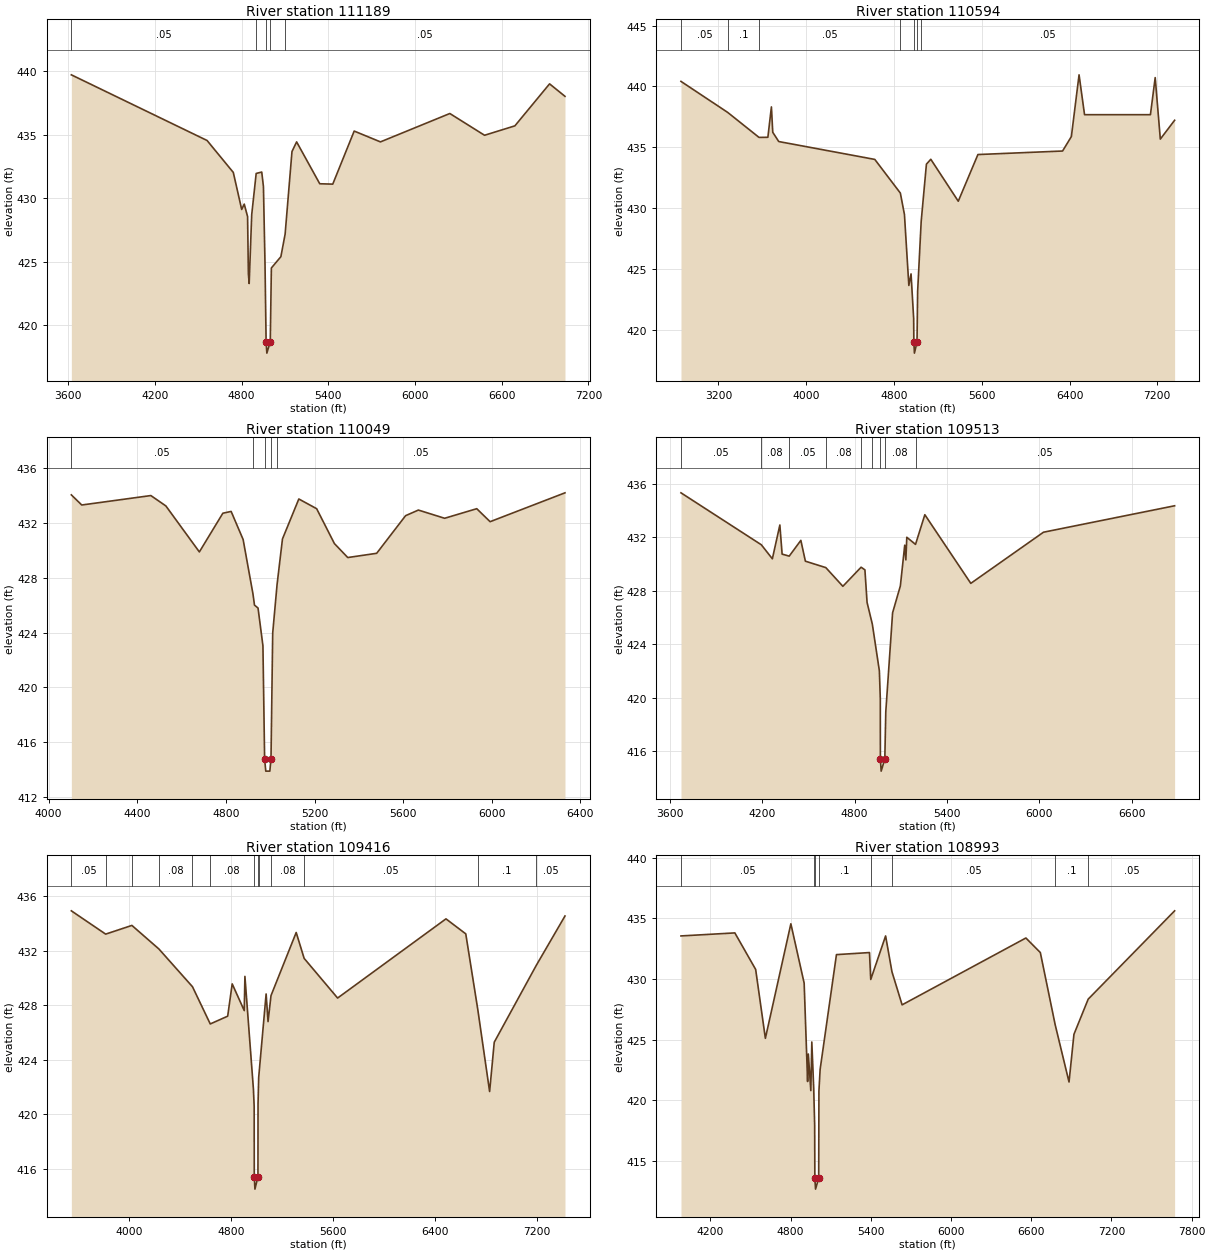
Type RM Length L Ch R = 1 ,111189  ,595,595,595
BEGIN DESCRIPTION:
Mapping XS 3773d531
END DESCRIPTION:
XS GIS Cut Line= 4
       2051701.4     13485121.45      2051241.72     13484279.19
      2050703.52     13484036.13      2048838.38     13484053.73
#Sta/Elev= 30
  3622.5  439.69  4561.5  434.53    4743  432.02    4801  429.11  4818.7  429.53
  4841.8  428.55  4847.3  424.07  4852.8  423.29  4870.4   428.7  4901.3  431.94
  4939.8  432.05  4951.5  430.91  4962.5  424.77    4970  418.72  4975.2  417.82
  4998.8  418.72  5006.4  424.51  5072.2   425.4  5101.5  427.17    5149  433.66
  5181.1  434.42  5341.1  431.13  5431.1   431.1  5579.4  435.27  5761.1  434.42
  6241.1  436.65  6481.2  434.94  6691.2  435.68  6931.2  438.98  7037.8     438
#Mann= 5 ,-1 , 0
  3622.5     .05       0  4901.3      .1       0    4970     .07       0
  4998.8      .1       0  5101.5     .05       0
Bank Sta=4970,4998.8
XS Rating Curve= 0 ,0
Exp/Cntr=0.3,0.1

Type RM Length L Ch R = 1 ,110594  ,545,545,545
BEGIN DESCRIPTION:
Mapping XS c746d622
END DESCRIPTION:
XS GIS Cut Line= 4
      2051930.55     13485173.51      2051308.99     13483567.38
      2050764.28     13483543.51      2048534.77     13483626.66
#Sta/Elev= 30
  2859.2  440.42  3284.5  437.87  3570.5  435.81  3651.1  435.82  3683.3  438.32
  3695.6  436.23  3750.2  435.47  4625.4     434  4858.4  431.23  4895.7  429.46
  4935.7  423.63  4955.8  424.58  4979.6  420.92  4981.4  418.96  4986.6  418.06
  5010.2  418.96  5015.8  423.13  5048.2   428.9  5095.9  433.61  5135.9  434.01
  5386.1  430.56  5565.2   434.4  6336.8  434.69  6416.8  435.88  6486.9  440.96
  6536.9  437.68  7137.3  437.68  7180.7  440.73  7227.4  435.67  7357.7  437.22
#Mann= 7 ,-1 , 0
  2859.2     .05       0  3284.5      .1       0  3570.5     .05       0
  4858.4      .1       0  4981.4     .07       0  5010.2      .1       0
  5048.2     .05       0
Bank Sta=4981.4,5010.2
XS Rating Curve= 0 ,0
Exp/Cntr=0.3,0.1

Type RM Length L Ch R = 1 ,110049  ,536,536,536
BEGIN DESCRIPTION:
Mapping XS a5f1242f
END DESCRIPTION:
XS GIS Cut Line= 4
      2051638.89     13483631.85      2051489.11     13483276.58
      2050940.07     13483020.51       2049708.3     13483126.51
#Sta/Elev= 30
  4102.5  434.06  4149.5  433.32  4461.3  434.01  4529.2  433.25  4680.2  429.89
  4786.3  432.72  4823.6  432.85  4877.7   430.8    4922  426.83    4929     426
    4945  425.79  4967.1  423.03  4974.7  414.77  4979.9  413.87  4998.3  413.87
  5003.5  414.77  5011.2  423.96  5030.9  427.51  5055.3  430.84  5129.1  433.76
  5209.5  433.05  5289.7   430.5  5349.9  429.48  5480.4  429.79  5610.9  432.54
  5668.6  432.95  5787.1  432.35    5932  433.05  5992.3   432.1  6330.2  434.21
#Mann= 5 ,-1 , 0
  4102.5     .05       0    4922      .1       0  4974.7     .07       0
  5003.5      .1       0  5030.9     .05       0
Bank Sta=4974.7,5003.5
XS Rating Curve= 0 ,0
Exp/Cntr=0.3,0.1

Type RM Length L Ch R = 1 ,109513  ,97,97,97
BEGIN DESCRIPTION:
Mapping XS c1a7d865
END DESCRIPTION:
XS GIS Cut Line= 4
      2051809.04     13483820.52      2051725.66     13483233.18
      2051202.65     13482504.01      2049565.97     13483012.08
#Sta/Elev= 30
  3673.3  435.34  4194.8  431.45  4266.5   430.4  4315.1  432.93  4329.8  430.75
  4375.9   430.6  4451.4  431.78  4480.9  430.22  4613.5  429.74  4724.1  428.34
  4842.5  429.77  4867.3  429.57  4881.3  427.13  4915.5   425.5  4961.1  422.01
  4967.2  419.89  4967.6   415.4  4972.8   414.5  4996.4   415.4  5002.8  418.95
    5047  426.36  5097.4  428.37  5125.7  431.42    5133  430.32  5139.2  432.01
  5195.8  431.48  5256.2   433.7  5554.6  428.56  6026.3  432.39  6877.6  434.37
#Mann= 9 ,-1 , 0
  3673.3     .05       0  4194.8     .08       0  4375.9     .05       0
  4613.5     .08       0  4842.5      .1       0  4915.5     .08       0
  4967.6     .07       0  4996.4     .08       0  5195.8     .05       0
Bank Sta=4967.6,4996.4
XS Rating Curve= 0 ,0
Exp/Cntr=0.3,0.1

Type RM Length L Ch R = 1 ,109416  ,423,423,423
BEGIN DESCRIPTION:
Mapping XS 636274b3
END DESCRIPTION:
XS GIS Cut Line= 5
      2051954.44     13483833.53        2051950.       13483350.
      2051421.84     13482655.92       2051235.2     13482367.29
      2049112.85     13482824.58
#Sta/Elev= 30
  3548.5  434.92  3817.6  433.21  4023.1  433.85    4235  432.12  4498.4  429.35
  4637.7  426.62  4774.3  427.19  4809.7  429.56  4904.2   427.6  4909.4  430.11
  4976.1  421.84    4982  420.56  4982.8   415.4    4988   414.5  5011.6   415.4
  5012.3  420.75  5017.4  422.69  5075.7  428.82  5090.8  426.79    5114   428.7
  5311.5  433.33  5373.9  431.43  5636.2  428.52  6485.9  434.33  6641.1  433.23
  6735.5  427.67  6828.1  421.66  6864.4  425.28  7193.5  430.91    7419  434.54
#Mann= 13 ,-1 , 0
  3548.5     .05       0  3817.6     .08       0  4023.1     .05       0
    4235     .08       0  4498.4     .05       0  4637.7     .08       0
  4982.8     .07       0  5011.6     .08       0  5017.4      .1       0
    5114     .08       0  5373.9     .05       0  6735.5      .1       0
  7193.5     .05       0
Bank Sta=4982.8,5011.6
XS Rating Curve= 0 ,0
Exp/Cntr=0.3,0.1

Type RM Length L Ch R = 1 ,108993  ,180,180,180
BEGIN DESCRIPTION:
Mapping XS ab47fbe8
END DESCRIPTION:
XS GIS Cut Line= 4
      2051952.04     13483181.22      2051633.98     13482265.98
      2051441.19     13482195.31      2048993.69     13482785.41
#Sta/Elev= 30
  3980.7  433.54  4383.6  433.79  4539.2  430.78  4611.9   425.1  4802.5  434.54
  4901.9  429.65  4927.7  421.54    4933  423.81  4951.8  420.79  4959.2   424.8
  4973.5  420.95  4980.5  417.93  4981.9  413.57  4987.1  412.67  5010.7  413.57
  5012.4  420.76  5021.4  422.54  5143.5     432  5390.5  432.17  5399.9  429.95
  5511.1  433.54  5558.5  430.59  5634.5  427.86  6560.3  433.37  6668.3  432.17
  6779.1  426.23  6882.9   421.5  6919.7  425.43  7026.3  428.33  7672.6  435.61
#Mann= 8 ,-1 , 0
  3980.7     .05       0  4973.5      .1       0  4981.9     .07       0
  5010.7      .1       0  5399.9     .08       0  5558.5     .05       0
  6779.1      .1       0  7026.3     .05       0
Bank Sta=4981.9,5010.7
XS Rating Curve= 0 ,0
Exp/Cntr=0.3,0.1

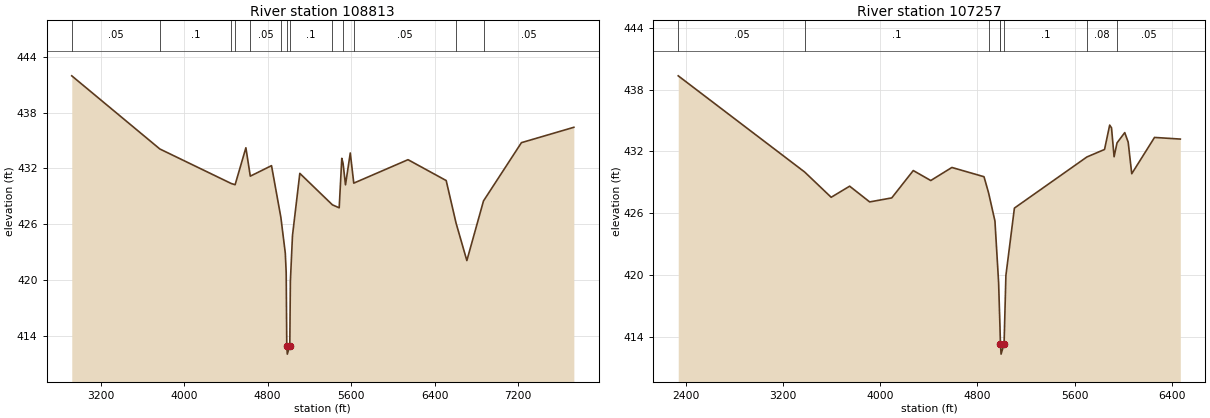
Type RM Length L Ch R = 1 ,108813  ,1556,1556,1556
BEGIN DESCRIPTION:
Mapping XS 341ba685
END DESCRIPTION:
XS GIS Cut Line= 4
       2053223.5     13483275.31       2051803.6     13482097.65
      2051295.79     13482052.08       2048918.7     13482666.99
#Sta/Elev= 30
    2924  441.95  3767.8  434.09  4451.9  430.38  4488.8  430.25  4592.1  434.22
  4634.3  431.17  4837.6   432.3  4927.3  426.74  4969.7  422.89  4978.2   420.8
  4983.8  412.95    4989  412.05  5012.7  412.95  5018.3  419.87  5038.4  424.78
  5108.7  431.47  5420.9  428.09    5486  427.77  5510.8  433.09  5523.2  432.53
  5546.3  430.24  5592.1  433.66  5625.6  430.42  6145.3  432.94  6510.9   430.7
  6605.5  426.13  6708.9   422.1  6868.4  428.51  7231.8  434.77  7733.9  436.42
#Mann= 13 ,-1 , 0
    2924     .05       0  3767.8      .1       0  4451.9     .05       0
  4488.8      .1       0  4634.3     .05       0  4927.3      .1       0
  4983.8     .07       0  5012.7      .1       0  5420.9     .05       0
  5523.2     .08       0  5625.6     .05       0  6605.5      .1       0
  6868.4     .05       0
Bank Sta=4983.8,5012.7
XS Rating Curve= 0 ,0
Exp/Cntr=0.3,0.1

Type RM Length L Ch R = 1 ,107257  ,1397,1397,1397
BEGIN DESCRIPTION:
Double Mapping XS 9bd5a611
END DESCRIPTION:
XS GIS Cut Line= 4
      2053421.46     13481764.92      2051286.24      13480752.6
      2050294.49     13480787.32      2049645.14     13481207.25
#Sta/Elev= 30
  2339.8  439.35  3379.1     430  3597.5  427.54  3749.4  428.62  3914.1  427.09
  4095.5  427.48  4272.6  430.14  4416.5  429.17  4590.1  430.44  4854.2  429.54
  4891.9  427.97  4944.2  425.23  4974.2  419.28  4985.6  414.93  4989.3  413.29
  4994.6  412.29  5019.3  413.29  5034.3  419.94  5104.3  426.49  5700.3  431.46
  5845.4  432.19  5887.7  434.56  5902.8  434.29    5924  431.48  5948.1  432.83
  6011.7  433.83  6039.9   432.9  6069.1  429.83  6256.4  433.36  6468.5   433.2
#Mann= 8 ,-1 , 0
  2339.8     .05       0  3379.1      .1       0  4891.9     .07       0
  4985.6      .1       0  4989.3     .07       0  5019.3      .1       0
  5700.3     .08       0  5948.1     .05       0
Bank Sta=4989.3,5019.3
XS Rating Curve= 0 ,0
Exp/Cntr=0.3,0.1