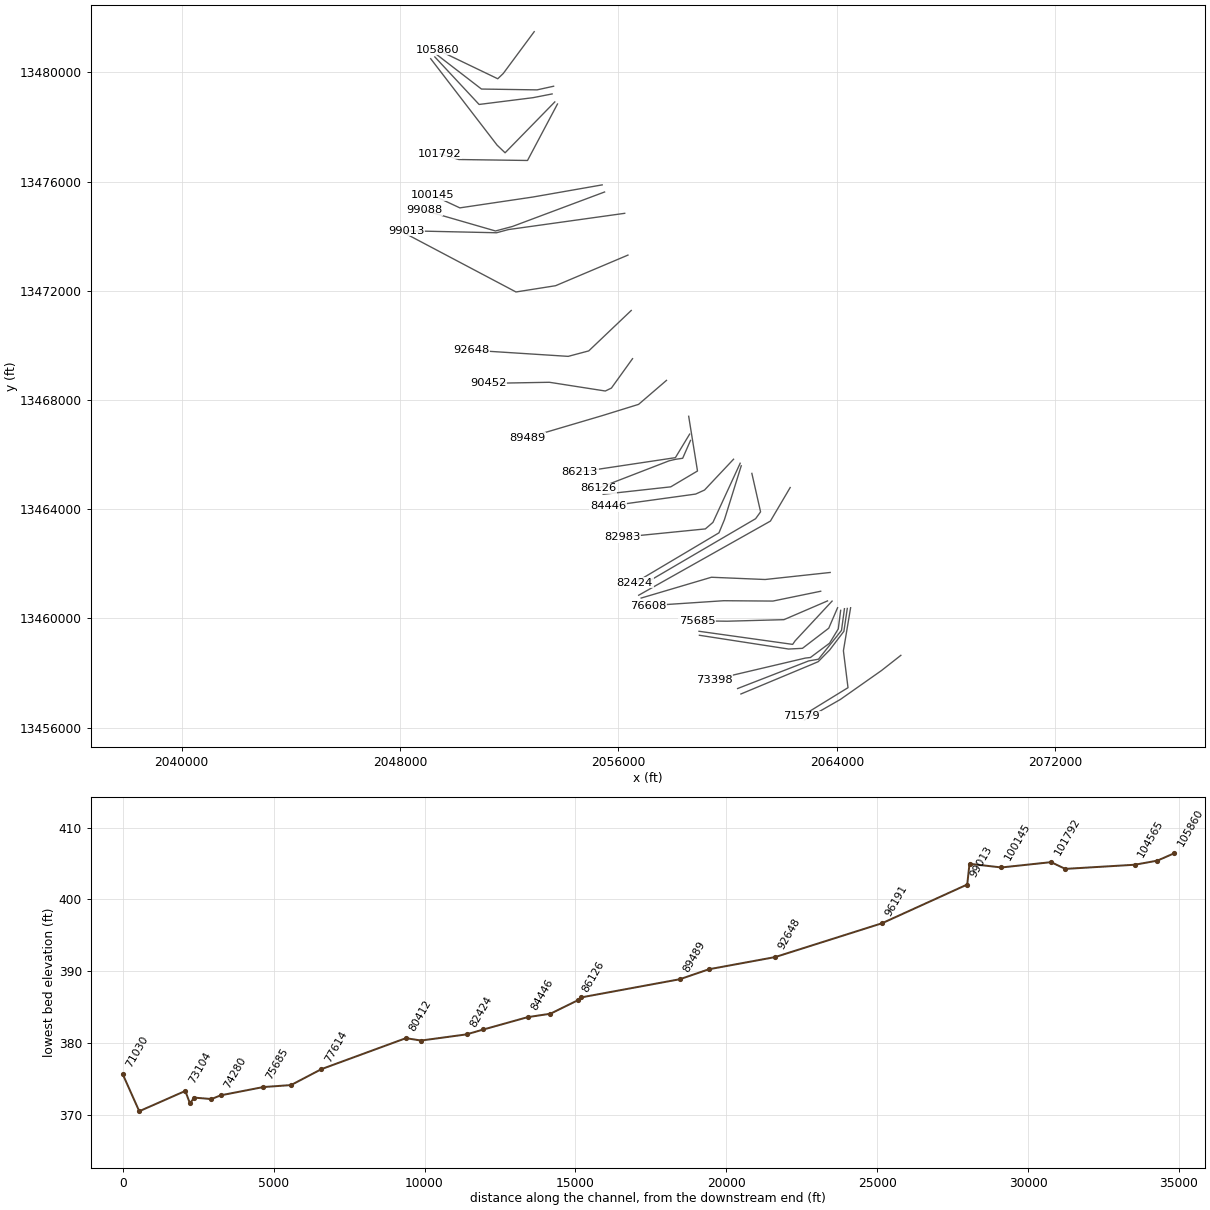
HEC-RAS study LAGUNILLAS Cr.prj: LAGUNILLAS Cr Base Level Engineering

--- LAGUNILLAS Cr.g01 (geometry) --- (continued)

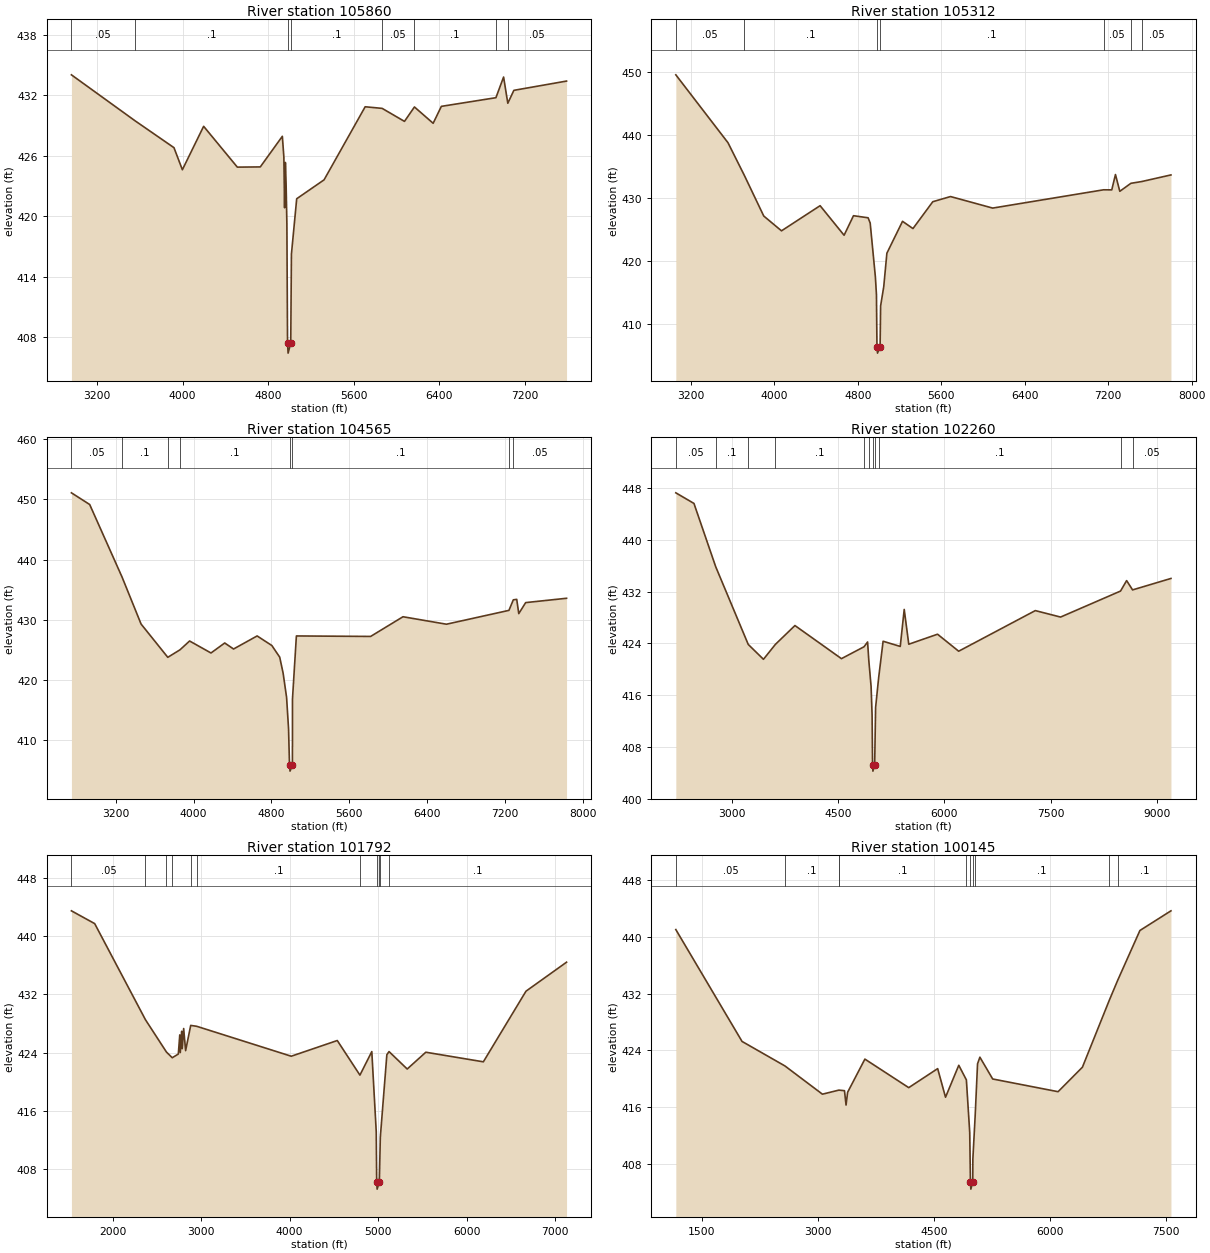
Type RM Length L Ch R = 1 ,105860  ,548,548,548
BEGIN DESCRIPTION:
Double Mapping XS 3b1f2c75
END DESCRIPTION:
XS GIS Cut Line= 4
      2052912.63     13481489.44      2051778.28     13479957.46
      2051576.89     13479764.75      2049369.88      13480825.6
#Sta/Elev= 30
  2959.1  434.04  3555.7  429.47  3918.9  426.81  3997.4  424.62  4196.5  428.93
  4511.7  424.88  4726.7   424.9  4933.1  427.94  4947.2  425.89  4954.1  420.85
  4961.4  425.34  4968.3  423.13  4975.5  419.25  4981.6  407.42  4986.9  406.42
  5011.6  407.42    5018  416.24  5067.4  421.74  5323.7  423.62  5708.3  430.87
    5867  430.71  6076.1  429.42  6169.3  430.85  6344.5  429.23  6421.1  430.91
  6931.7  431.77  7003.7  433.82    7043  431.22  7099.8   432.5  7592.8  433.42
#Mann= 8 ,-1 , 0
  2959.1     .05       0  3555.7      .1       0  4981.6     .07       0
  5011.6      .1       0    5867     .05       0  6169.3      .1       0
  6931.7     .08       0    7043     .05       0
Bank Sta=4981.6,5011.6
XS Rating Curve= 0 ,0
Exp/Cntr=0.3,0.1

Type RM Length L Ch R = 1 ,105312  ,747,747,747
BEGIN DESCRIPTION:
Mapping XS de49313b
END DESCRIPTION:
XS GIS Cut Line= 4
      2053623.29       13479491.      2053016.25     13479357.78
      2050980.65     13479388.16      2049326.42     13480662.87
#Sta/Elev= 30
  3055.9  449.56  3555.8  438.79  3712.3  433.62  3898.7  427.16  4068.7  424.81
  4438.7   428.8  4668.7  424.11  4758.8  427.21  4898.8  426.88  4918.8  426.05
  4968.8  417.46  4978.8  414.69  4983.8  406.41  4989.1  405.41  5013.8  406.41
  5018.8   412.9  5048.8  415.96  5078.8  421.26  5228.8  426.32  5328.8  425.17
  5518.8  429.43  5688.9  430.25  6092.9  428.42  7155.7  431.32  7234.4  431.31
  7269.7  433.74  7311.4  431.08  7417.6  432.35  7521.4  432.63  7801.6  433.68
#Mann= 7 ,-1 , 0
  3055.9     .05       0  3712.3      .1       0  4983.8     .07       0
  5013.8      .1       0  7155.7     .05       0  7417.6     .08       0
  7521.4     .05       0
Bank Sta=4983.8,5013.8
XS Rating Curve= 0 ,0
Exp/Cntr=0.3,0.1

Type RM Length L Ch R = 1 ,104565  ,2305,2305,2305
BEGIN DESCRIPTION:
Mapping XS dcfb3b07
END DESCRIPTION:
XS GIS Cut Line= 4
      2053569.04     13479208.88      2052864.34     13479071.32
      2050893.85     13478823.93      2049272.19     13480565.18
#Sta/Elev= 30
  2746.5  451.08    2934  449.14  3267.1  437.06  3461.6  429.28  3735.9  423.75
  3861.4     425  3959.7  426.46  4179.4  424.47  4320.5  426.13  4411.2  425.13
  4653.1   427.3  4804.3  425.71  4884.9  423.78  4920.1  421.11  4955.5   417.1
  4975.6  411.94  4985.6  405.84  4990.9  404.84  5015.6  405.84  5015.9  416.77
  5056.2   427.3  5818.5  427.22  6150.7  430.49  6596.8  429.25  7238.5  431.55
  7283.4   433.3  7318.4  433.38  7339.4  431.01  7410.2  432.84  7829.9  433.56
#Mann= 8 ,-1 , 0
  2746.5     .05       0  3267.1      .1       0  3735.9     .05       0
  3861.4      .1       0  4985.6     .07       0  5015.6      .1       0
  7238.5     .08       0  7283.4     .05       0
Bank Sta=4985.6,5015.6
XS Rating Curve= 0 ,0
Exp/Cntr=0.3,0.1

Type RM Length L Ch R = 1 ,102260  ,468,468,468
BEGIN DESCRIPTION:
Mapping XS 8522db82
END DESCRIPTION:
XS GIS Cut Line= 4
      2053666.69     13478915.91      2051845.87     13477053.56
      2051555.07     13477331.34       2049120.3     13480500.05
#Sta/Elev= 30
  2200.2  447.29  2456.6  445.65  2764.4  435.86  3224.3  423.85  3439.6  421.55
  3607.8  423.85    3885  426.77  4542.7  421.65  4862.3  423.49  4912.5  424.23
  4929.9  421.33  4961.9  417.35  4976.1  412.91  4982.5  405.26  4987.8  404.26
  5012.5  405.26  5025.8   414.1  5068.2  418.64  5131.8  424.34  5374.3  423.54
  5430.4  429.26  5494.8  423.88  5901.7  425.43  6200.7   422.8  7284.6  429.08
  7641.7  428.08  8489.9   432.1  8576.1  433.72  8660.3  432.28    9203  434.05
#Mann= 11 ,-1 , 0
  2200.2     .05       0  2764.4      .1       0  3224.3     .05       0
  3607.8      .1       0  4862.3     .07       0  4929.9     .16       0
  4982.5     .07       0  5012.5     .16       0  5068.2      .1       0
  8489.9     .08       0  8660.3     .05       0
Bank Sta=4982.5,5012.5
XS Rating Curve= 0 ,0
Exp/Cntr=0.3,0.1

Type RM Length L Ch R = 1 ,101792  ,1647,1647,1647
BEGIN DESCRIPTION:
Mapping XS d48d3682
END DESCRIPTION:
XS GIS Cut Line= 4
      2053764.35     13478839.95       2052667.2     13476771.74
      2050153.31     13476806.46      2049445.82     13477017.03
#Sta/Elev= 30
    1535   443.5  1797.8  441.74  2371.6  428.51  2608.3  424.07  2673.8  423.28
  2742.7  423.79  2759.1  426.43  2764.7  423.99    2781  426.93  2786.7  424.53
    2803   427.3    2825  424.26  2882.6  427.73  2950.1  427.61  4018.4  423.49
  4538.5  425.65  4794.3  420.89  4928.5  424.13  4978.5  413.12  4983.5   406.2
  4988.8   405.2  5013.5   406.2  5024.7  412.34  5098.5   423.7  5123.1  424.13
  5328.5  421.73  5538.6  424.04  6188.6  422.72  6670.3  432.44  7128.5  436.43
#Mann= 11 ,-1 , 0
    1535     .05       0  2371.6      .1       0  2608.3     .05       0
  2673.8      .1       0  2882.6     .05       0  2950.1      .1       0
  4794.3     .16       0  4983.5     .07       0  5013.5     .16       0
  5024.7     .07       0  5123.1      .1       0
Bank Sta=4983.5,5013.5
XS Rating Curve= 0 ,0
Exp/Cntr=0.3,0.1

Type RM Length L Ch R = 1 ,100145  ,1057,1057,1057
BEGIN DESCRIPTION:
Double Mapping XS 8c7156ae
END DESCRIPTION:
XS GIS Cut Line= 4
      2055402.78     13475877.71       2052854.7     13475431.46
      2050188.03     13475035.62       2049174.5      13475508.8
#Sta/Elev= 30
  1162.4  441.01  2018.3  425.26  2572.6  421.81  3057.8  417.83  3269.5   418.4
  3273.3   418.4  3342.9  418.32  3363.2   416.3  3383.5   418.1  3606.8  422.77
  4173.6  418.75  4547.6  421.43  4649.2   417.4  4820.6   421.9  4918.9  419.84
  4962.1  412.44  4971.3  405.46  4976.5  404.46  5001.3  405.46  5002.5  408.66
    5033   414.9  5063.2   422.1  5093.5  423.04  5258.9  419.97  6104.5  418.18
  6419.1  421.63  6765.6  431.03  6875.7  433.88  7162.5  440.88  7563.7  443.65
#Mann= 10 ,-1 , 0
  1162.4     .05       0  2572.6      .1       0  3269.5     .07       0
  3273.3      .1       0  4918.9     .12       0  4971.3     .07       0
  5001.3     .12       0    5033      .1       0  6765.6     .08       0
  6875.7      .1       0
Bank Sta=4971.3,5001.3
XS Rating Curve= 0 ,0
Exp/Cntr=0.3,0.1

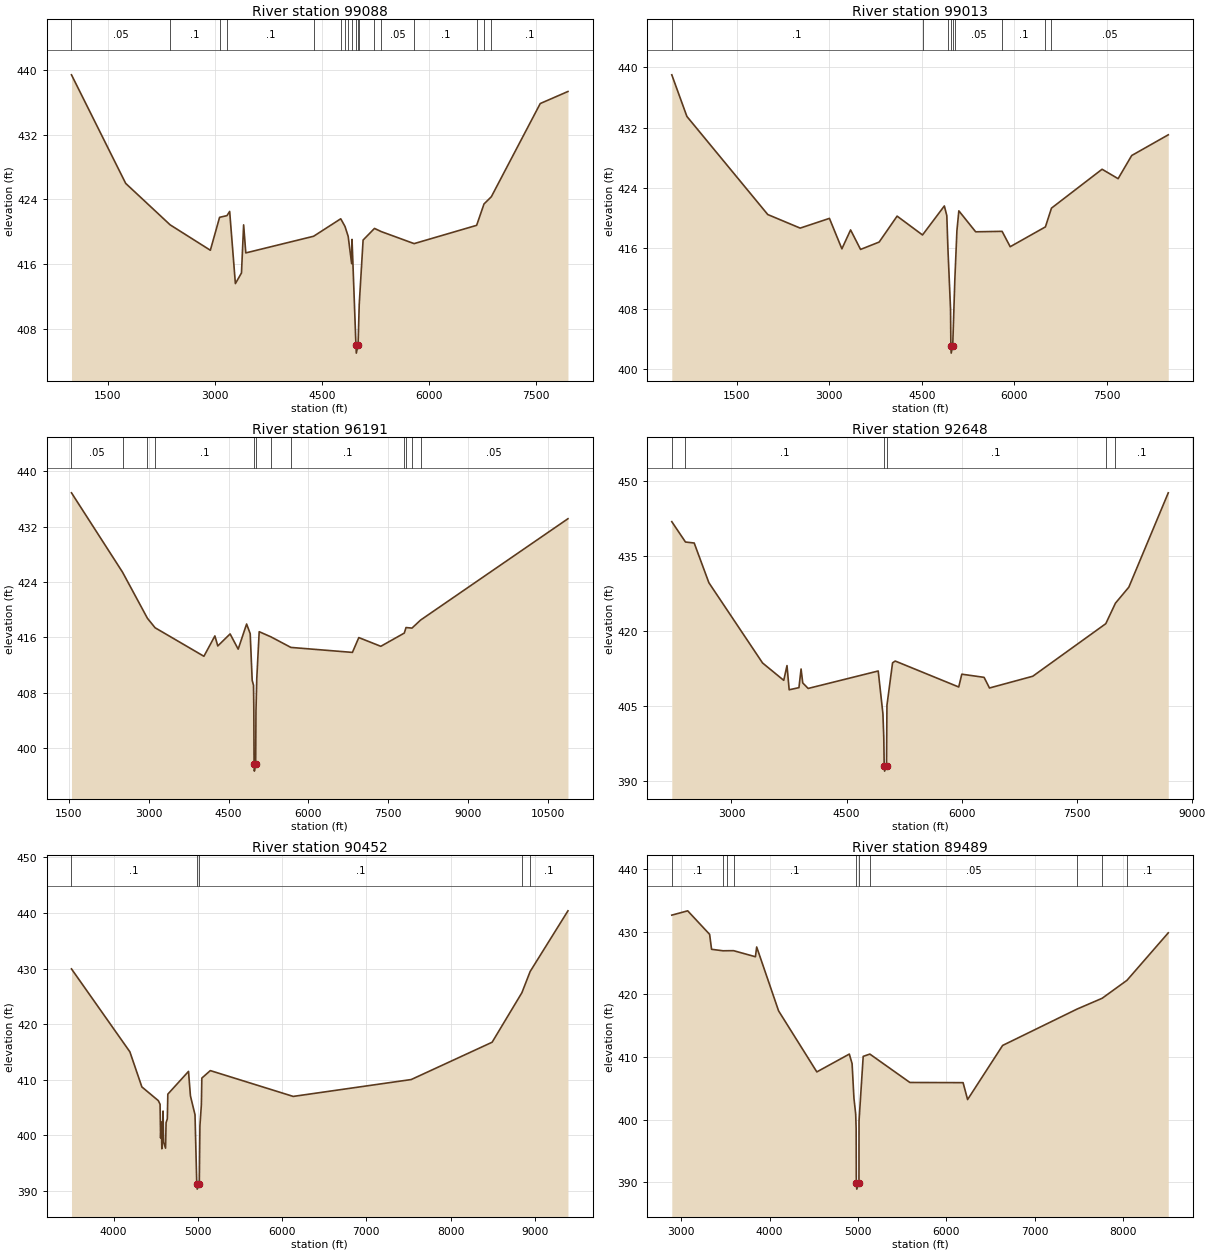
Type RM Length L Ch R = 1 ,99088   ,75,75,75
BEGIN DESCRIPTION:
Double Mapping XS d88d07a7
END DESCRIPTION:
XS GIS Cut Line= 4
      2055489.65     13475617.31      2052114.25      13474354.2
      2051493.59     13474189.27      2048881.49     13474944.57
#Sta/Elev= 30
   988.9  439.38  1749.1  425.96  2373.2  420.83  2937.1  417.69  3066.6  421.76
  3170.3  421.97  3208.1  422.49  3288.3  413.57  3373.8  414.88    3404  420.83
  3434.3  417.36  4385.8  419.42  4766.3  421.58  4825.8  420.64  4870.7  419.41
  4919.4  416.03  4924.8  419.03  4979.6  405.97  4984.8  404.97  5009.6  405.97
  5025.7  410.99  5080.1  418.95  5239.9  420.39  5333.8     420  5795.8  418.51
  6672.9  420.77  6776.2  423.41  6879.4  424.31  7565.4  435.83  7954.2  437.32
#Mann= 18 ,-1 , 0
   988.9     .05       0  2373.2      .1       0  3066.6     .07       0
  3170.3      .1       0  4385.8     .05       0  4766.3      .1       0
  4825.8     .12       0  4870.7     .05       0  4924.8     .08       0
  4979.6     .07       0  5009.6     .08       0  5025.7     .05       0
  5239.9      .1       0  5333.8     .05       0  5795.8      .1       0
  6672.9     .08       0  6776.2     .05       0  6879.4      .1       0
Bank Sta=4979.6,5009.6
XS Rating Curve= 0 ,0
Exp/Cntr=0.3,0.1

Type RM Length L Ch R = 1 ,99013   ,2822,2822,2822
BEGIN DESCRIPTION:
Double Mapping XS c5a33e5e
END DESCRIPTION:
XS GIS Cut Line= 4
      2056227.47     13474836.05      2051971.02     13474241.35
      2051532.65     13474124.17      2048231.61     13474197.01
#Sta/Elev= 30
   443.2  439.01     688  433.49  2000.1  420.47  2525.7  418.67  3000.3  419.96
  3202.2  415.92  3343.6  418.43  3505.1  415.84  3807.1  416.82  4098.1  420.26
  4510.3  417.76  4864.3  421.61  4904.4  420.32  4922.4  415.93  4964.6  407.95
  4970.3  403.08  4975.5  402.08  5000.3  403.08  5034.6  411.84  5068.1  418.31
  5099.5  420.96  5372.4  418.18  5801.1  418.24  5932.6   416.2  6503.6  418.83
    6602  421.32  7422.9  426.48    7683  425.23  7903.1   428.3  8496.6  431.05
#Mann= 9 ,-1 , 0
   443.2      .1       0  4510.3     .05       0  4922.4     .08       0
  4970.3     .07       0  5000.3     .08       0  5034.6     .05       0
  5801.1      .1       0  6503.6     .08       0    6602     .05       0
Bank Sta=4970.3,5000.3
XS Rating Curve= 0 ,0
Exp/Cntr=0.3,0.1

Type RM Length L Ch R = 1 ,96191   ,3543,3543,3543
BEGIN DESCRIPTION:
Double Mapping XS 636570b0
END DESCRIPTION:
XS GIS Cut Line= 4
      2056346.79     13473306.09      2053696.21     13472184.57
      2052244.82     13471955.41      2047839.95     13474282.62
#Sta/Elev= 30
  1549.5  436.88  2508.5  425.42  2976.4  418.76  3120.3  417.39    4038  413.27
  4244.3  416.21  4298.6  414.76    4530   416.5  4681.9   414.3  4840.2  417.93
  4907.7  416.54  4945.1  409.79  4970.1  409.08  4975.5  405.91  4980.7  397.68
    4986  396.68  5010.7  397.68    5016  405.32  5031.2  410.05  5076.7  416.82
  5298.6  416.07  5672.1  414.55  6828.5  413.83  6948.6  415.97  7361.9  414.71
    7803  416.62  7835.9  417.42  7947.7  417.34  8109.5   418.5 10878.8  433.14
#Mann= 12 ,-1 , 0
  1549.5     .05       0  2508.5      .1       0  2976.4     .05       0
  3120.3      .1       0  4980.7     .07       0  5010.7      .1       0
  5298.6     .05       0  5672.1      .1       0    7803     .05       0
  7835.9     .08       0  7947.7      .1       0  8109.5     .05       0
Bank Sta=4980.7,5010.7
XS Rating Curve= 0 ,0
Exp/Cntr=0.3,0.1

Type RM Length L Ch R = 1 ,92648   ,2196,2196,2196
BEGIN DESCRIPTION:
Triple Mapping XS 445588b1
END DESCRIPTION:
XS GIS Cut Line= 4
      2056466.19     13471277.03      2054910.27      13469796.9
      2054157.65     13469596.39      2050618.85     13469822.95
#Sta/Elev= 30
  2221.8  441.86  2400.2  437.79  2513.9  437.59  2705.2  429.65  3405.4  413.59
  3681.2  410.12  3723.7  413.07    3752  408.23  3879.4  408.66  3907.3  412.39
  3928.8  409.61  3999.5   408.5  4912.9  411.99  4974.3  403.42  4985.3  398.75
    4991  392.96  4996.3  391.96    5021  392.96  5026.7  405.12  5099.8  413.62
  5134.7  413.98  5962.5  408.79  6002.5  411.35  6293.1  410.72  6363.3  408.59
  6927.9  410.94  7879.4  421.45  8005.6  425.56  8180.2  428.76  8694.2  447.63
#Mann= 6 ,-1 , 0
  2221.8     .05       0  2400.2      .1       0    4991     .07       0
    5021      .1       0  7879.4     .08       0  8005.6      .1       0
Bank Sta=4991,5021
XS Rating Curve= 0 ,0
Exp/Cntr=0.3,0.1

Type RM Length L Ch R = 1 ,90452   ,963,963,963
BEGIN DESCRIPTION:
Triple  Mapping XS b1376e07
END DESCRIPTION:
XS GIS Cut Line= 5
      2056514.46     13469512.21      2055740.83     13468435.37
      2055518.17      13468327.3      2053470.06     13468647.05
      2051225.26     13468607.75
#Sta/Elev= 30
  3501.3  429.93    4194     415  4336.5  408.67  4531.7   406.2  4552.5  405.54
  4558.7  399.47  4567.3  402.34  4573.4  397.54  4588.1  404.32  4594.3  398.72
  4617.6  397.64  4623.8  402.23  4638.5  402.92  4644.6  407.37  4890.1  411.47
  4912.7  407.06  4967.1  403.66  4987.9  391.26  4993.2  390.26  5017.9  391.26
  5025.5  401.68  5042.5  405.44  5048.1  410.26  5148.8  411.61  6132.5  406.96
  7532.8     410  8492.9  416.72  8846.1  425.64  8944.4  429.47  9392.8  440.39
#Mann= 5 ,-1 , 0
  3501.3      .1       0  4987.9     .07       0  5017.9      .1       0
  8846.1     .08       0  8944.4      .1       0
Bank Sta=4987.9,5017.9
XS Rating Curve= 0 ,0
Exp/Cntr=0.3,0.1

Type RM Length L Ch R = 1 ,89489   ,3276,3276,3276
BEGIN DESCRIPTION:
Double Mapping XS eea110a8
END DESCRIPTION:
XS GIS Cut Line= 4
      2057757.44     13468716.28      2056735.34     13467837.88
      2055402.81     13467425.03      2052648.39     13466611.71
#Sta/Elev= 30
  2894.7  432.67  3074.5  433.36  3322.5   429.6  3344.5  427.21  3474.1  426.97
    3516  426.98  3593.5  426.99  3840.5  426.02  3854.7  427.58  4102.7  417.36
    4535  407.61  4902.3  410.46  4933.7  408.93  4954.6  403.42  4974.5  400.87
  4979.7  398.49  4981.5  389.87  4986.7  388.87  5011.5  389.87  5012.3  399.79
  5059.3  410.09  5134.5  410.46  5587.4  405.92  6188.9  405.89  6239.9  403.19
  6636.1  411.84  7477.3  417.65  7761.6  419.38  8042.3  422.25  8509.4  429.84
#Mann= 10 ,-1 , 0
  2894.7      .1       0  3474.1     .05       0    3516     .08       0
  3593.5      .1       0  4981.5     .07       0  5011.5      .1       0
  5134.5     .05       0  7477.3      .1       0  7761.6     .05       0
  8042.3      .1       0
Bank Sta=4981.5,5011.5
XS Rating Curve= 0 ,0
Exp/Cntr=0.3,0.1

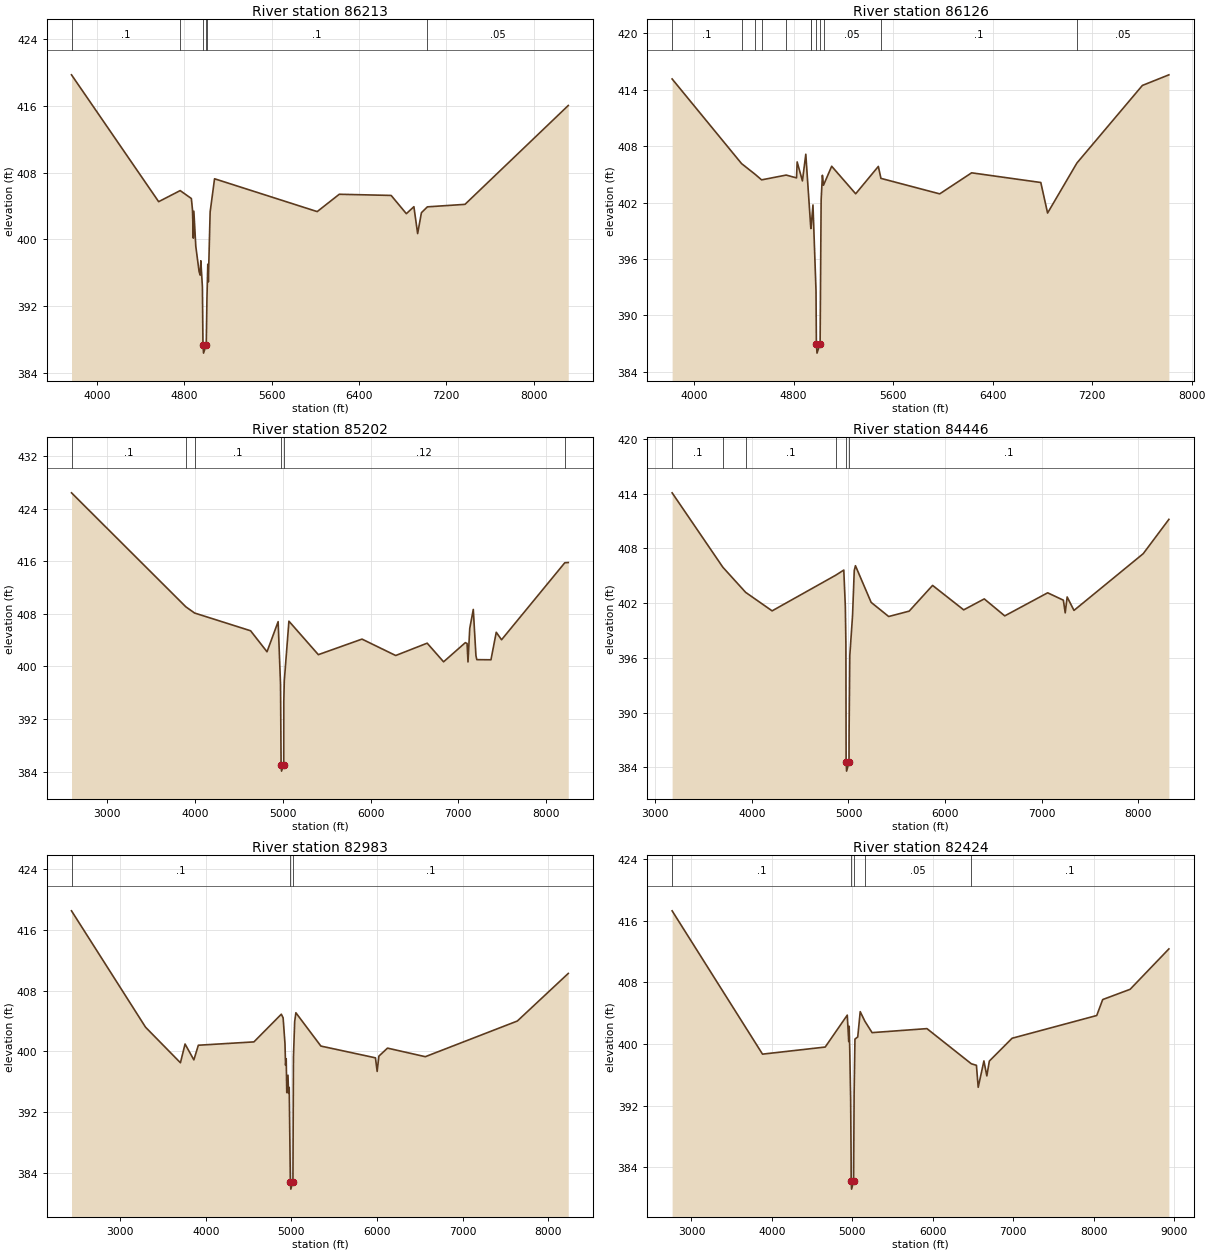
Type RM Length L Ch R = 1 ,86213   ,87,87,87
BEGIN DESCRIPTION:
Doulbe Mapping XS ff5e19f8
END DESCRIPTION:
XS GIS Cut Line= 4
      2058605.92     13466748.88       2058084.3     13465886.49
      2057773.53     13465839.62      2054580.28     13465360.15
#Sta/Elev= 30
  3766.1  419.72  4564.6   404.5  4761.7  405.83  4864.3  404.88  4874.4  403.54
    4882  400.13  4887.1  403.36  4904.7  399.16  4935.1   396.1  4945.2  395.69
  4950.9  397.41  4965.4  394.29  4970.6  387.33  4975.8  386.33  5000.6  387.33
    5007  392.87  5014.8     397  5019.8  394.88  5036.2  403.26  5076.7  407.25
  6017.1  403.31  6219.3  405.39  6694.6  405.25  6833.9  403.06    6903   403.9
  6937.3  400.67    6972  403.18  7026.6  403.88  7371.2  404.18  8317.3  416.04
#Mann= 6 ,-1 , 0
  3766.1      .1       0  4761.7     .08       0  4970.6     .07       0
  5000.6     .08       0    5007      .1       0  7026.6     .05       0
Bank Sta=4970.6,5000.6
XS Rating Curve= 0 ,0
Exp/Cntr=0.3,0.1

Type RM Length L Ch R = 1 ,86126   ,924,924,924
BEGIN DESCRIPTION:
Double Mapping XS 43283543
END DESCRIPTION:
XS GIS Cut Line= 5
      2058637.18     13466517.12      2058350.72     13465863.47
      2058089.51     13465825.73      2057853.39     13465770.17
      2055266.17     13464769.93
#Sta/Elev= 30
  3822.9  415.15  4381.3  406.14  4490.5     405  4542.3  404.41  4740.1  404.92
    4823  404.62  4828.2  406.32  4870.5   404.3  4897.6  407.14  4938.1  399.23
  4939.7  399.28  4955.3  401.74  4979.8   392.6  4982.7  386.97  4987.8  385.97
  5012.7  386.97  5020.9  402.22  5031.1   404.9    5040  403.84  5105.7  405.86
  5298.6  402.93  5480.9  405.84  5501.7  404.57  5974.1  402.92    6231  405.16
  6787.1  404.13  6841.6  400.88  7077.2   406.2  7603.7  414.46  7816.9  415.59
#Mann= 12 ,-1 , 0
  3822.9      .1       0  4381.3     .08       0  4490.5      .1       0
  4542.3     .05       0  4740.1     .08       0  4938.1      .1       0
  4939.7     .08       0  4982.7     .07       0  5012.7     .08       0
    5040     .05       0  5501.7      .1       0  7077.2     .05       0
Bank Sta=4982.7,5012.7
XS Rating Curve= 0 ,0
Exp/Cntr=0.3,0.1

Type RM Length L Ch R = 1 ,85202   ,756,756,756
BEGIN DESCRIPTION:
Double Mapping XS fc114c3e
END DESCRIPTION:
XS GIS Cut Line= 4
      2058570.93     13467402.07      2058893.47     13465397.79
      2057914.16     13464817.05      2055439.78     13464544.18
#Sta/Elev= 30
  2593.4  426.45  3896.3  409.08  3995.7  408.14  4633.1  405.44  4820.2  402.24
  4946.9  406.83  4974.2  397.27  4980.6  385.06  4985.7  384.06  5010.6  385.06
  5011.2  394.59    5017  397.79  5069.7   406.9  5404.9   401.8    5902  404.17
  6285.9  401.67  6644.4  403.55  6831.3  400.71  7079.1  403.63  7098.9   403.5
  7109.3  400.69  7129.4   405.8  7169.7  408.69  7199.8  401.65  7209.9  401.04
  7370.9  401.02  7431.2  405.21  7491.6  404.07  8211.9   415.8  8251.4  415.83
#Mann= 6 ,-1 , 0
  2593.4      .1       0  3896.3     .08       0  3995.7      .1       0
  4980.6     .07       0  5010.6     .12       0  8211.9     .05       0
Bank Sta=4980.6,5010.6
XS Rating Curve= 0 ,0
Exp/Cntr=0.3,0.1

Type RM Length L Ch R = 1 ,84446   ,1463,1463,1463
BEGIN DESCRIPTION:
Triple Mapping XS 4b08c73b
END DESCRIPTION:
XS GIS Cut Line= 4
      2060213.91     13465828.88      2059151.14     13464699.86
      2058825.62     13464552.29      2055621.93     13464110.14
#Sta/Elev= 30
  3174.6  414.09  3699.9  405.93  3935.4  403.18  4209.6  401.15  4866.6  405.05
  4951.5  405.62  4967.5  401.62  4973.4  397.47  4975.6  384.58  4980.7  383.58
  5005.6  384.58  5006.4  387.84  5013.6  396.23  5042.2  400.64  5059.8  405.57
  5072.2   406.1  5234.6  402.08  5416.3  400.53  5628.3  401.12  5870.6  403.94
  6192.5  401.26  6405.6  402.46  6617.6   400.6  7061.7  403.13  7224.4  402.32
  7243.5  400.93  7263.6  402.67  7334.3   401.2    8051  407.42  8316.6  411.18
#Mann= 6 ,-1 , 0
  3174.6      .1       0  3699.9     .05       0  3935.4      .1       0
  4866.6     .16       0  4975.6     .07       0  5005.6      .1       0
Bank Sta=4975.6,5005.6
XS Rating Curve= 0 ,0
Exp/Cntr=0.3,0.1

Type RM Length L Ch R = 1 ,82983   ,559,559,559
BEGIN DESCRIPTION:
Triple Mapping XS d58b2412
END DESCRIPTION:
XS GIS Cut Line= 4
      2060456.97      13465681.3       2059459.3     13463514.96
      2059181.52     13463276.25       2056142.7     13462972.98
#Sta/Elev= 30
  2430.2  418.53  3295.9  403.19  3703.2  398.51  3757.2  400.98  3860.1  398.89
  3912.4  400.82    4562  401.26  4882.2  404.91  4903.1  404.44    4925  401.01
  4931.6  398.18  4939.3  399.05  4945.9  394.57  4960.1  396.87  4966.7  394.48
  4974.4  395.27  4987.9  382.86  4993.1  381.86  5017.9  382.86  5023.8  399.19
  5038.1  403.92  5052.3   405.1  5344.5  400.71    5982  399.16  6002.1  397.37
  6022.2  399.38  6122.7  400.44  6564.8  399.31  7640.2  404.01  8235.4  410.28
#Mann= 3 ,-1 , 0
  2430.2      .1       0  4987.9     .07       0  5017.9      .1       0
Bank Sta=4987.9,5017.9
XS Rating Curve= 0 ,0
Exp/Cntr=0.3,0.1

Type RM Length L Ch R = 1 ,82424   ,1507,1507,1507
BEGIN DESCRIPTION:
Triple Mapping XS 9aa8f26b
END DESCRIPTION:
XS GIS Cut Line= 4
      2060495.89     13465588.03       2059880.3     13463614.79
      2059680.65     13463133.02      2056598.72     13461302.29
#Sta/Elev= 30
  2759.5  417.28  3882.8  398.69  4661.8  399.61  4935.9  403.75  4954.4  400.32
  4959.8   402.3    4967  399.15  4977.9  392.95  4983.7  385.25  4984.5  382.18
  4989.6  381.18  5014.5  382.18  5021.1  393.47  5031.4  400.64  5066.1  400.92
  5096.9   404.2  5154.7  402.96  5244.2  401.48  5926.1     402  6477.7  397.44
    6541  397.24  6563.2  394.39    6634  397.81  6670.3  395.87  6701.5  397.79
    6984  400.75    8036   403.7  8110.1  405.77    8451   407.1  8932.7  412.34
#Mann= 5 ,-1 , 0
  2759.5      .1       0  4984.5     .07       0  5014.5      .1       0
  5154.7     .05       0  6477.7      .1       0
Bank Sta=4984.5,5014.5
XS Rating Curve= 0 ,0
Exp/Cntr=0.3,0.1

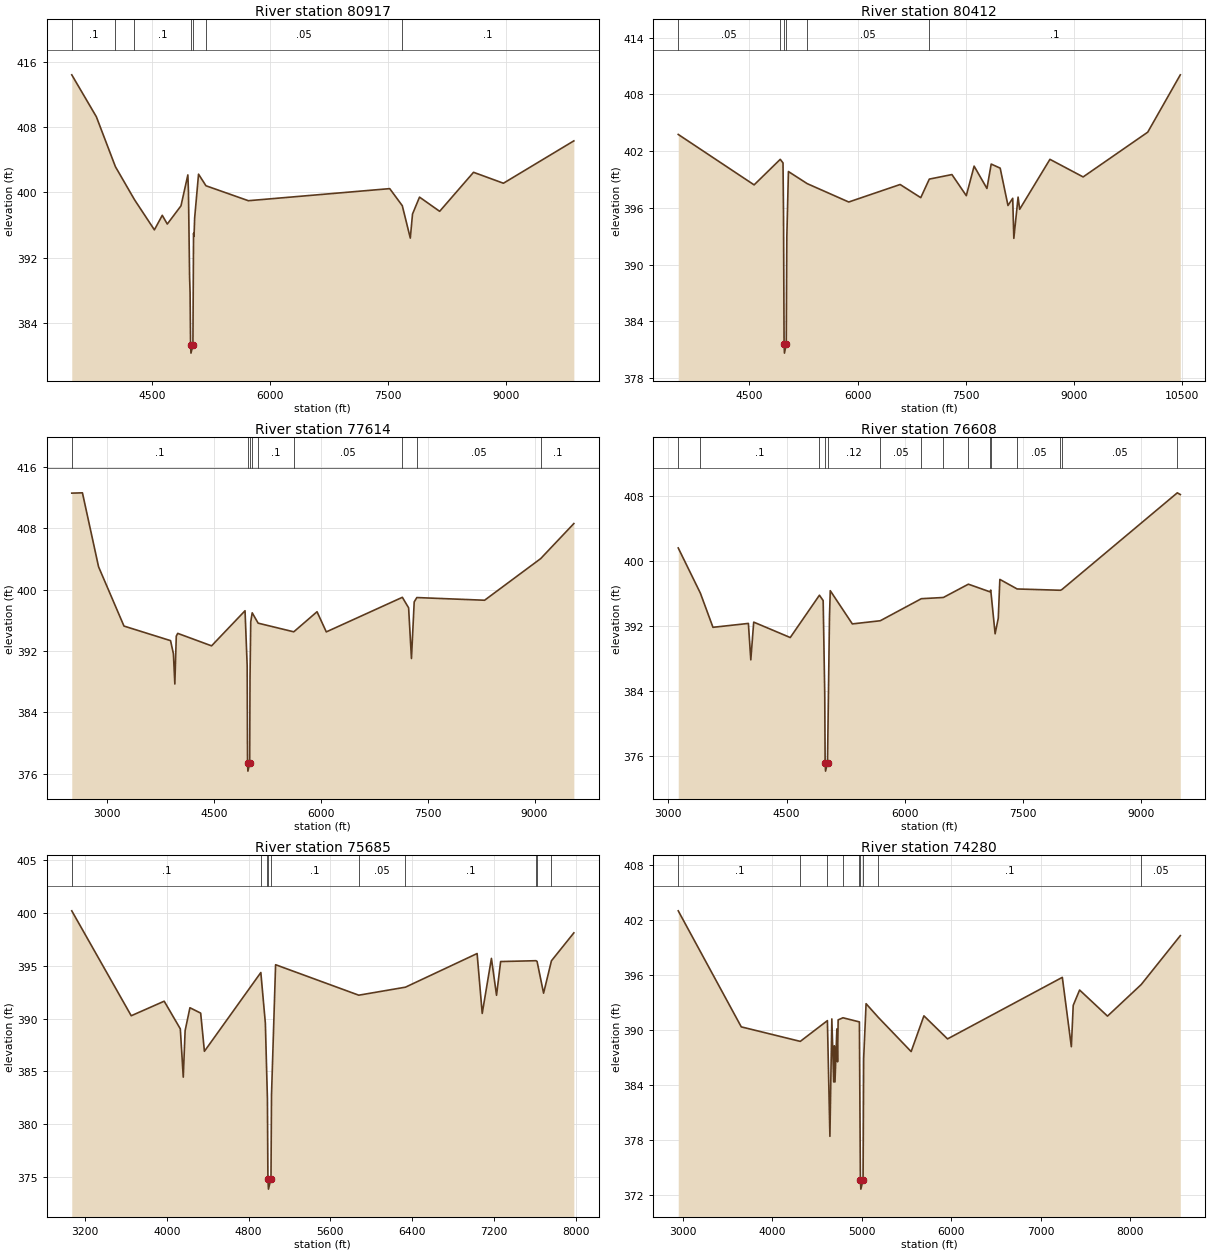
Type RM Length L Ch R = 1 ,80917   ,505,505,505
BEGIN DESCRIPTION:
Triple Mapping XS 3ada0255
END DESCRIPTION:
XS GIS Cut Line= 4
      2060885.09     13465310.33      2061204.09     13463901.25
       2061021.8     13463649.51      2057023.46     13461309.28
#Sta/Elev= 30
  3472.9  414.41    3786  409.27  4028.1  403.16  4270.7  399.12  4524.2  395.42
  4624.5   397.2  4688.2  396.13  4862.5  398.36    4950  402.15  4957.5  400.19
  4972.2  389.61  4978.3  387.76  4984.4  381.32  4989.6  380.32  5014.4  381.32
  5022.4  394.99  5028.6  394.62  5036.5  396.87  5085.9  402.24  5180.5  400.82
  5719.8  398.99  7518.5  400.47  7678.5  398.38  7780.4  394.41  7808.6  397.36
  7897.8  399.43  8153.9  397.69  8584.9  402.47  8965.3  401.13  9861.3  406.32
#Mann= 7 ,-1 , 0
  3472.9      .1       0  4028.1     .05       0  4270.7      .1       0
  4984.4     .07       0  5014.4      .1       0  5180.5     .05       0
  7678.5      .1       0
Bank Sta=4984.4,5014.4
XS Rating Curve= 0 ,0
Exp/Cntr=0.3,0.1

Type RM Length L Ch R = 1 ,80412   ,2798,2798,2798
BEGIN DESCRIPTION:
Double Mapping XS 6d982e55
END DESCRIPTION:
XS GIS Cut Line= 4
      2062288.56     13464791.54      2061564.33     13463562.71
      2061403.74     13463471.56       2056739.3     13460846.72
#Sta/Elev= 30
  3513.7  403.76    4566  398.43  4928.6  401.13  4966.9  400.75  4973.8  395.34
  4981.8  381.65  4986.9  380.65  5011.8  381.65  5019.8  392.92  5041.9  399.84
  5302.7  398.56  5878.6  396.62  6591.2  398.47  6877.3  397.08  6995.9  399.04
  7309.5  399.52  7508.9  397.29  7617.3  400.41  7795.1  398.05  7854.2  400.63
  7978.7   400.2    8087  396.25  8152.6  397.01    8168  392.78  8227.2  397.14
  8248.9  395.85  8668.9  401.13  9129.1  399.27 10025.2     404   10477  410.06
#Mann= 6 ,-1 , 0
  3513.7     .05       0  4928.6      .1       0  4981.8     .07       0
  5011.8      .1       0  5302.7     .05       0  6995.9      .1       0
Bank Sta=4981.8,5011.8
XS Rating Curve= 0 ,0
Exp/Cntr=0.3,0.1

Type RM Length L Ch R = 1 ,77614   ,1006,1006,1006
BEGIN DESCRIPTION:
Triple Mapping XS 19e0287d
END DESCRIPTION:
XS GIS Cut Line= 4
      2063753.85     13461680.45      2061369.02     13461422.95
      2059402.87     13461505.42      2056830.58     13460743.59
#Sta/Elev= 30
    2503  412.59  2652.7  412.63  2879.4  402.98  3236.1  395.25  3889.9  393.35
  3930.1  391.64  3950.2  387.69  3970.3  393.93  3990.4   394.3  4465.8  392.67
  4935.7  397.25  4965.8  390.08  4970.8  377.33  4975.9  376.33  5000.8  377.33
  5005.8   388.5  5015.8   395.8  5036.3  396.98  5119.8  395.63  5619.9   394.5
  5946.6  397.12  6076.7  394.49  7144.6     399  7232.4  397.63  7272.4  391.02
  7310.9   398.4  7347.9  398.97  8299.3  398.62  9086.8  404.05  9552.3  408.62
#Mann= 9 ,-1 , 0
    2503      .1       0  4970.8     .07       0  5000.8      .1       0
  5036.3     .05       0  5119.8      .1       0  5619.9     .05       0
  7144.6      .1       0  7347.9     .05       0  9086.8      .1       0
Bank Sta=4970.8,5000.8
XS Rating Curve= 0 ,0
Exp/Cntr=0.3,0.1

Type RM Length L Ch R = 1 ,76608   ,923,923,923
BEGIN DESCRIPTION:
Triple Mapping XS 6e7712ff
END DESCRIPTION:
XS GIS Cut Line= 4
      2063406.59     13460992.94      2061655.48     13460633.02
      2059854.26     13460646.04      2057081.27     13460461.67
#Sta/Elev= 30
  3126.7  401.64  3407.8  396.06  3567.3  391.85  4016.5  392.33  4047.1  387.84
    4084  392.49  4547.4  390.59  4917.6  395.81  4964.9  395.15  4984.9  383.66
  4989.9  375.11  4995.1  374.11  5019.9  375.11  5044.9  393.01  5054.9  396.37
  5334.9  392.27  5689.3  392.66    6210  395.38  6489.3  395.53  6806.7  397.17
  7079.8  396.23  7090.5  396.44  7145.9  391.05    7186  392.98    7206  397.76
  7425.4  396.58  7975.1  396.42  7994.4  396.52  9456.7  408.44  9494.8  408.23
#Mann= 15 ,-1 , 0
  3126.7     .05       0  3407.8      .1       0  4917.6     .12       0
  4989.9     .07       0  5019.9     .12       0  5689.3     .05       0
    6210     .08       0  6489.3     .05       0  6806.7      .1       0
  7079.8     .05       0  7090.5      .1       0  7425.4     .05       0
  7975.1      .1       0  7994.4     .05       0  9456.7      .1       0
Bank Sta=4989.9,5019.9
XS Rating Curve= 0 ,0
Exp/Cntr=0.3,0.1

Type RM Length L Ch R = 1 ,75685   ,1405,1405,1405
BEGIN DESCRIPTION:
Triple  Mapping XS 27b398ea
END DESCRIPTION:
XS GIS Cut Line= 4
       2063656.6     13460638.77      2062059.12      13459951.6
      2059980.13     13459895.17      2058889.08     13459908.44
#Sta/Elev= 30
  3070.7  400.22  3652.2  390.27  3974.6  391.65  4132.1  389.03  4161.1  384.45
  4179.2  388.86  4226.3  391.03  4331.3  390.52  4367.9   386.9  4919.6  394.37
  4963.9  389.57  4978.6  384.29  4983.9  382.46  4988.9  374.83  4994.1  373.83
  5018.9  374.83  5023.9  382.72  5063.9  395.11  5877.3  392.22  6334.1  392.98
  7034.6  396.17  7084.6  390.49  7174.6  395.71  7224.6  392.21  7264.6  395.41
  7610.1  395.49  7621.1  395.42  7684.7  392.41  7761.4  395.48  7980.6  398.13
#Mann= 10 ,-1 , 0
  3070.7      .1       0  4919.6     .12       0  4978.6      .1       0
  4988.9     .07       0  5018.9      .1       0  5877.3     .05       0
  6334.1      .1       0  7610.1     .07       0  7621.1      .1       0
  7761.4     .05       0
Bank Sta=4988.9,5018.9
XS Rating Curve= 0 ,0
Exp/Cntr=0.3,0.1

Type RM Length L Ch R = 1 ,74280   ,311,311,311
BEGIN DESCRIPTION:
Triple Mapping XS 3ba08305
END DESCRIPTION:
XS GIS Cut Line= 4
      2063823.26     13460631.81      2062469.77     13459176.63
      2062379.93     13459046.42      2058949.47     13459526.43
#Sta/Elev= 30
  2947.2  402.97  3651.5  390.34  4310.7  388.76  4613.8  391.02  4641.8  378.43
  4663.3   391.2  4684.3  384.35  4691.2  388.27  4698.5  384.35  4719.5  390.12
  4726.9  386.54  4733.7   391.1  4787.6  391.33  4971.2  390.88  4982.3  373.68
  4987.4  372.68  5012.3  373.68  5018.8  386.89  5045.9  392.86  5182.8  391.37
  5549.3  387.65  5692.1  391.54    5956  389.03  7238.4  395.73  7339.3  388.18
  7360.1  392.68  7431.5  394.35  7743.2  391.51  8120.1  394.95  8556.6  400.27
#Mann= 9 ,-1 , 0
  2947.2      .1       0  4310.7     .05       0  4613.8      .1       0
  4787.6     .16       0  4971.2     .12       0  4982.3     .07       0
  5012.3     .12       0  5182.8      .1       0  8120.1     .05       0
Bank Sta=4982.3,5012.3
XS Rating Curve= 0 ,0
Exp/Cntr=0.3,0.1

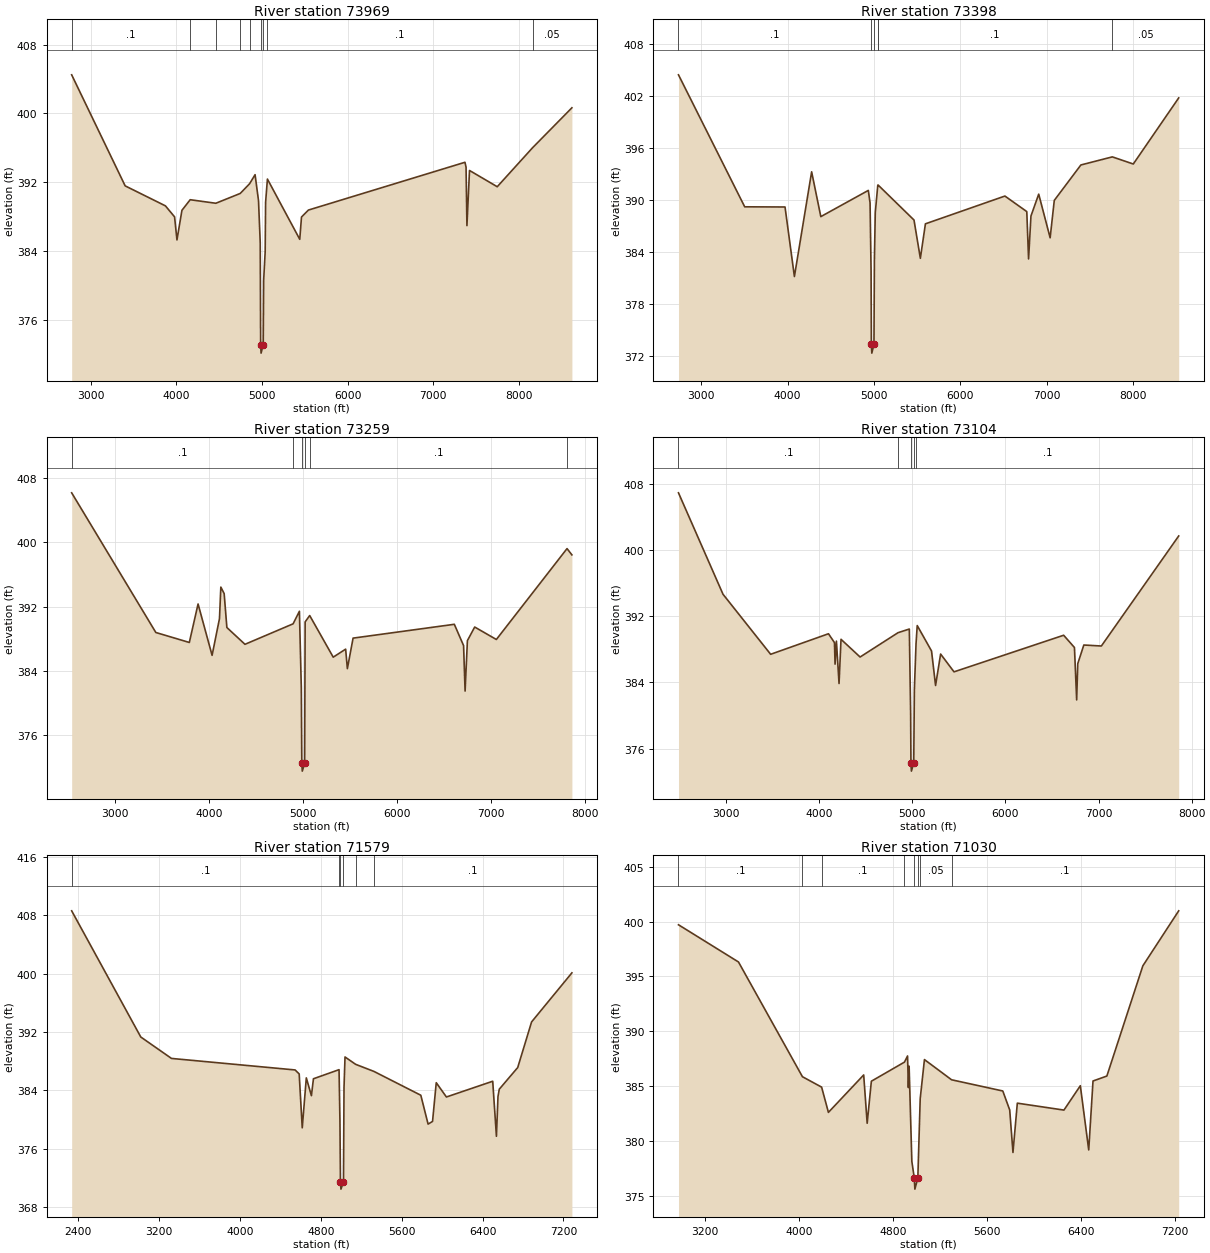
Type RM Length L Ch R = 1 ,73969   ,571,571,571
BEGIN DESCRIPTION:
Double Mapping XS 3633cb55
END DESCRIPTION:
XS GIS Cut Line= 5
      2064024.68     13460388.79      2063701.87     13459639.85
      2062738.33       13458902.      2062230.51     13458875.96
      2058962.91     13459380.14
#Sta/Elev= 30
  2775.6  404.49  3400.4  391.59  3870.6  389.27  3977.7  387.99  4005.6  385.31
  4063.7  388.75  4160.1  389.98  4459.8  389.57  4744.8  390.71  4854.3  391.84
  4918.2  392.89  4958.3  389.88  4978.3  385.01  4983.3  373.16  4988.3  372.16
  5013.3  373.16  5018.4  380.62  5036.2  383.94  5041.2  389.69  5062.4  392.38
  5440.2  385.38  5460.5  387.97  5541.5  388.78  7370.2  394.33    7383  393.76
  7393.1  386.97  7423.4  393.38  7747.2  391.49    8160  396.02  8619.5  400.66
#Mann= 9 ,-1 , 0
  2775.6      .1       0  4160.1     .05       0  4459.8      .1       0
  4744.8     .16       0  4854.3     .12       0  4983.3     .07       0
  5013.3     .12       0  5062.4      .1       0    8160     .05       0
Bank Sta=4983.3,5013.3
XS Rating Curve= 0 ,0
Exp/Cntr=0.3,0.1

Type RM Length L Ch R = 1 ,73398   ,139,139,139
BEGIN DESCRIPTION:
Double Mapping XS 15aeaacf
END DESCRIPTION:
XS GIS Cut Line= 6
      2064137.53     13460293.32      2064050.83     13459614.68
      2063731.38     13459090.37      2063029.99     13458566.06
      2062845.97     13458545.23       2059502.1     13457758.57
#Sta/Elev= 30
  2735.1  404.41  3502.2  389.21  3969.2  389.19  4077.9  381.18  4277.5  393.24
  4383.9  388.08  4934.1   391.1  4954.2  389.66  4966.1  381.78  4969.4  373.36
  4974.4  372.36  4999.4  373.36  5004.5  383.11  5014.6  388.53  5043.6  391.68
  5046.3  391.73  5463.1  387.69  5536.9  383.28  5595.4  387.25  6516.2  390.45
  6769.6  388.66  6790.2  383.21  6817.9  388.15  6907.8  390.67  7040.1  385.64
  7088.1  389.95  7396.3  394.03  7760.3  394.96  8003.3  394.14  8529.3  401.75
#Mann= 6 ,-1 , 0
  2735.1      .1       0  4969.4     .07       0  4999.4      .1       0
  5043.6     .07       0  5046.3      .1       0  7760.3     .05       0
Bank Sta=4969.4,4999.4
XS Rating Curve= 0 ,0
Exp/Cntr=0.3,0.1

Type RM Length L Ch R = 1 ,73259   ,155,155,155
BEGIN DESCRIPTION:
Double Mapping XS 721b8ae8
END DESCRIPTION:
XS GIS Cut Line= 5
      2064276.42     13460354.06      2064168.88     13459559.12
      2063325.13     13458503.56      2062967.49     13458441.06
      2060363.18     13457429.37
#Sta/Elev= 30
  2545.3  406.17  3438.9  388.79  3794.3  387.55  3887.1  392.34    4036  385.95
  4114.5  390.52  4128.9  394.44  4164.1  393.63  4192.9  389.41    4385  387.32
  4896.2  389.87  4962.9  391.43  4983.2  381.91  4988.5  372.54  4993.5  371.54
  5018.5  372.54  5023.8  390.11  5072.2   390.9    5322  385.72  5453.8  386.72
  5472.2  384.29  5532.8  388.09  6607.7  389.81  6705.9  387.16  6721.9   381.5
  6746.5  387.78    6824  389.47  7053.9  387.92  7804.1  399.23  7855.8  398.45
#Mann= 6 ,-1 , 0
  2545.3      .1       0  4896.2     .12       0  4988.5     .07       0
  5018.5     .12       0  5072.2      .1       0  7804.1     .05       0
Bank Sta=4988.5,5018.5
XS Rating Curve= 0 ,0
Exp/Cntr=0.3,0.1

Type RM Length L Ch R = 1 ,73104   ,1525,1525,1525
BEGIN DESCRIPTION:
Double Mapping XS 7ebef7ea
END DESCRIPTION:
XS GIS Cut Line= 6
      2064380.58     13460362.73      2064255.69      13459524.4
      2063731.38      13458836.9      2063314.72     13458413.29
      2063071.66     13458309.12      2060484.16     13457229.54
#Sta/Elev= 30
  2486.9   406.9  2965.4  394.65  3477.1   387.4  4098.5  389.88  4162.9  388.81
  4169.2  386.21  4183.8  388.99    4212  383.87  4233.2  389.21  4438.3  387.07
  4845.9  390.01    4967  390.45  4981.3  380.16  4984.5  374.29  4989.4  373.29
  5014.5  374.29  5021.4  383.12  5039.2  388.68  5052.1  390.87  5205.8   387.8
  5249.1  383.63  5303.3  387.43  5447.3  385.28  6625.2   389.7  6741.3  388.22
  6765.1  381.89  6776.9  386.27    6842  388.52  7030.4   388.4  7861.4  401.69
#Mann= 5 ,-1 , 0
  2486.9      .1       0  4845.9     .12       0  4984.5     .07       0
  5014.5     .12       0  5039.2      .1       0
Bank Sta=4984.5,5014.5
XS Rating Curve= 0 ,0
Exp/Cntr=0.3,0.1

Type RM Length L Ch R = 1 ,71579   ,549,549,549
BEGIN DESCRIPTION:
Double Mapping XS 478e3617
END DESCRIPTION:
XS GIS Cut Line= 4
       2064502.1     13460388.74      2064238.33     13458812.59
       2064406.7     13457460.69      2062713.06     13456419.51
#Sta/Elev= 30
  2335.7  408.64  3019.4  391.33    3323  388.39  4546.1  386.81  4586.4  386.26
  4616.6  378.87  4656.9  385.72  4707.3  383.28  4727.4   385.6  4980.7  386.85
  4989.5  379.82  4994.6  371.46  4999.6  370.46  5024.6  371.46  5029.8   384.4
  5039.8  388.59  5144.9  387.58  5325.7  386.61  5789.6  383.34  5861.6  379.38
  5905.6  379.75  5942.3  385.06  6042.8   383.1  6500.9  385.26  6537.6  377.71
    6553  383.16  6565.9  384.17  6748.2  387.14  6885.5   393.4  7284.2  400.13
#Mann= 6 ,-1 , 0
  2335.7      .1       0  4980.7     .12       0  4994.6     .07       0
  5024.6     .12       0  5144.9     .05       0  5325.7      .1       0
Bank Sta=4994.6,5024.6
XS Rating Curve= 0 ,0
Exp/Cntr=0.3,0.1

Type RM Length L Ch R = 1 ,71030   ,1200,1200,1200
BEGIN DESCRIPTION:
Double Mapping XS e7ee1d78
END DESCRIPTION:
XS GIS Cut Line= 4
       2066342.6     13458645.17      2065635.61     13458090.07
      2064129.03     13457030.57      2062809.83      13456275.5
#Sta/Elev= 30
    2974  399.71  3485.1  396.32  4029.8  385.87  4193.3  384.92    4251  382.62
  4551.5  386.03  4581.2  381.63  4616.9  385.46    4899   387.2    4925  387.76
  4932.3  384.88  4938.4  386.83  4961.7  378.16  4982.6  376.63  4987.5  375.63
  5012.6  376.63  5032.9  383.87    5069  387.43  5300.1  385.59  5736.3  384.57
  5795.3  382.84    5823  378.97  5860.1  383.46  6257.2  382.83  6396.8  385.05
  6468.3   379.2  6504.8  385.48  6622.8  385.93  6929.3  395.97  7234.7  400.98
#Mann= 8 ,-1 , 0
    2974      .1       0  4029.8     .05       0  4193.3      .1       0
    4899     .07       0  4982.6     .07       0  5012.6     .07       0
  5032.9     .05       0  5300.1      .1       0
Bank Sta=4982.6,5012.6
XS Rating Curve= 0 ,0
Exp/Cntr=0.3,0.1