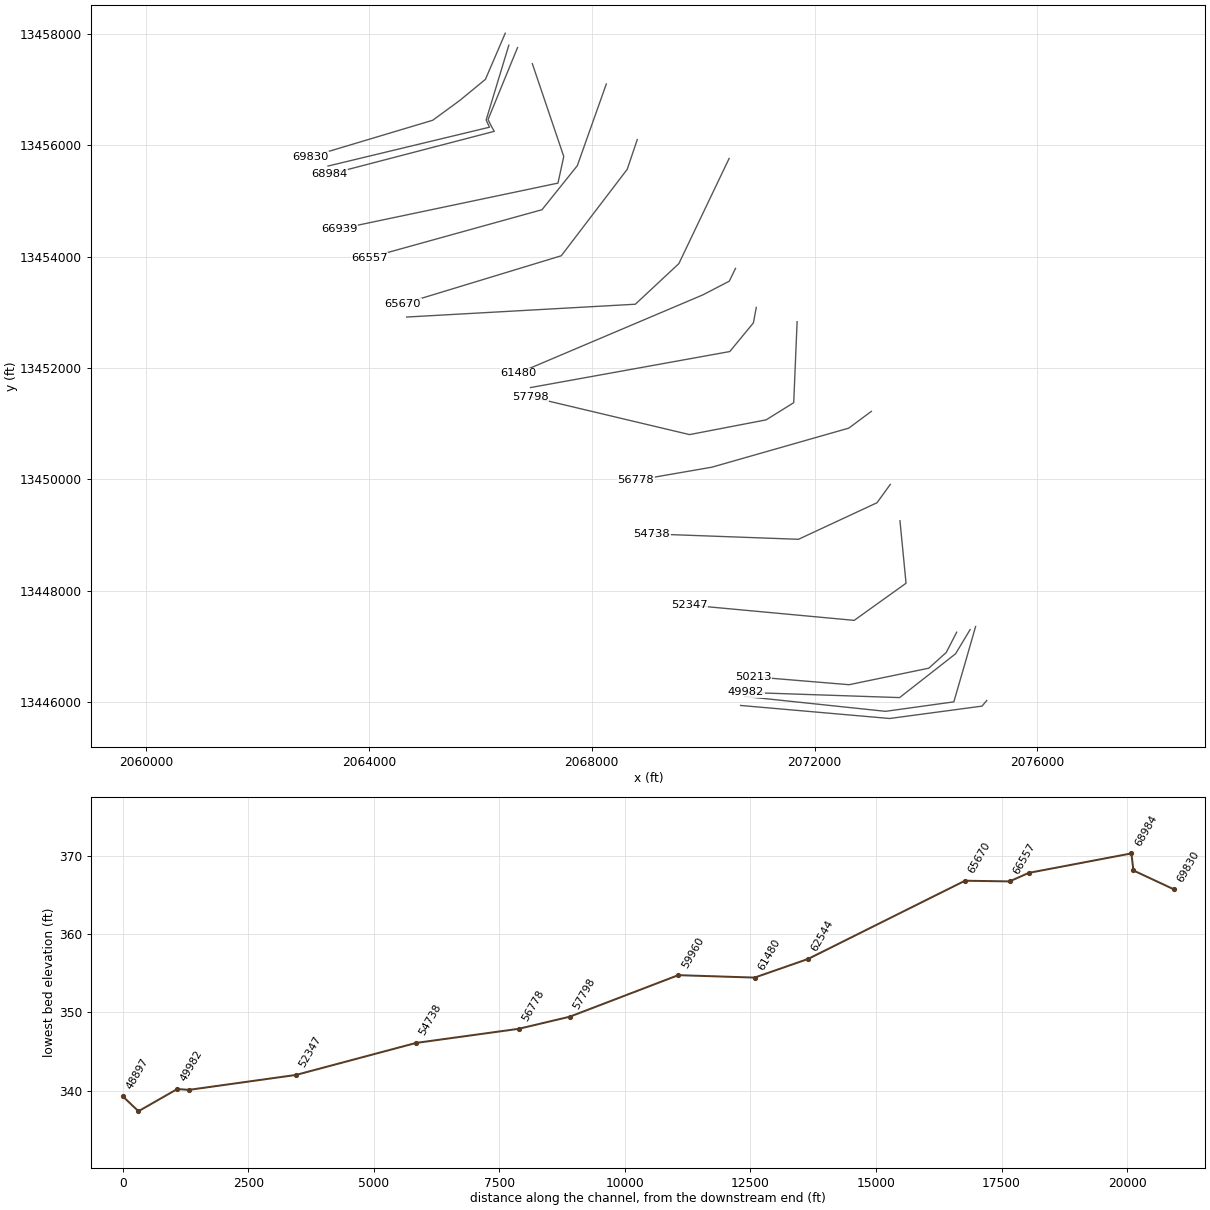
HEC-RAS study LAGUNILLAS Cr.prj: LAGUNILLAS Cr Base Level Engineering

--- LAGUNILLAS Cr.g01 (geometry) --- (continued)

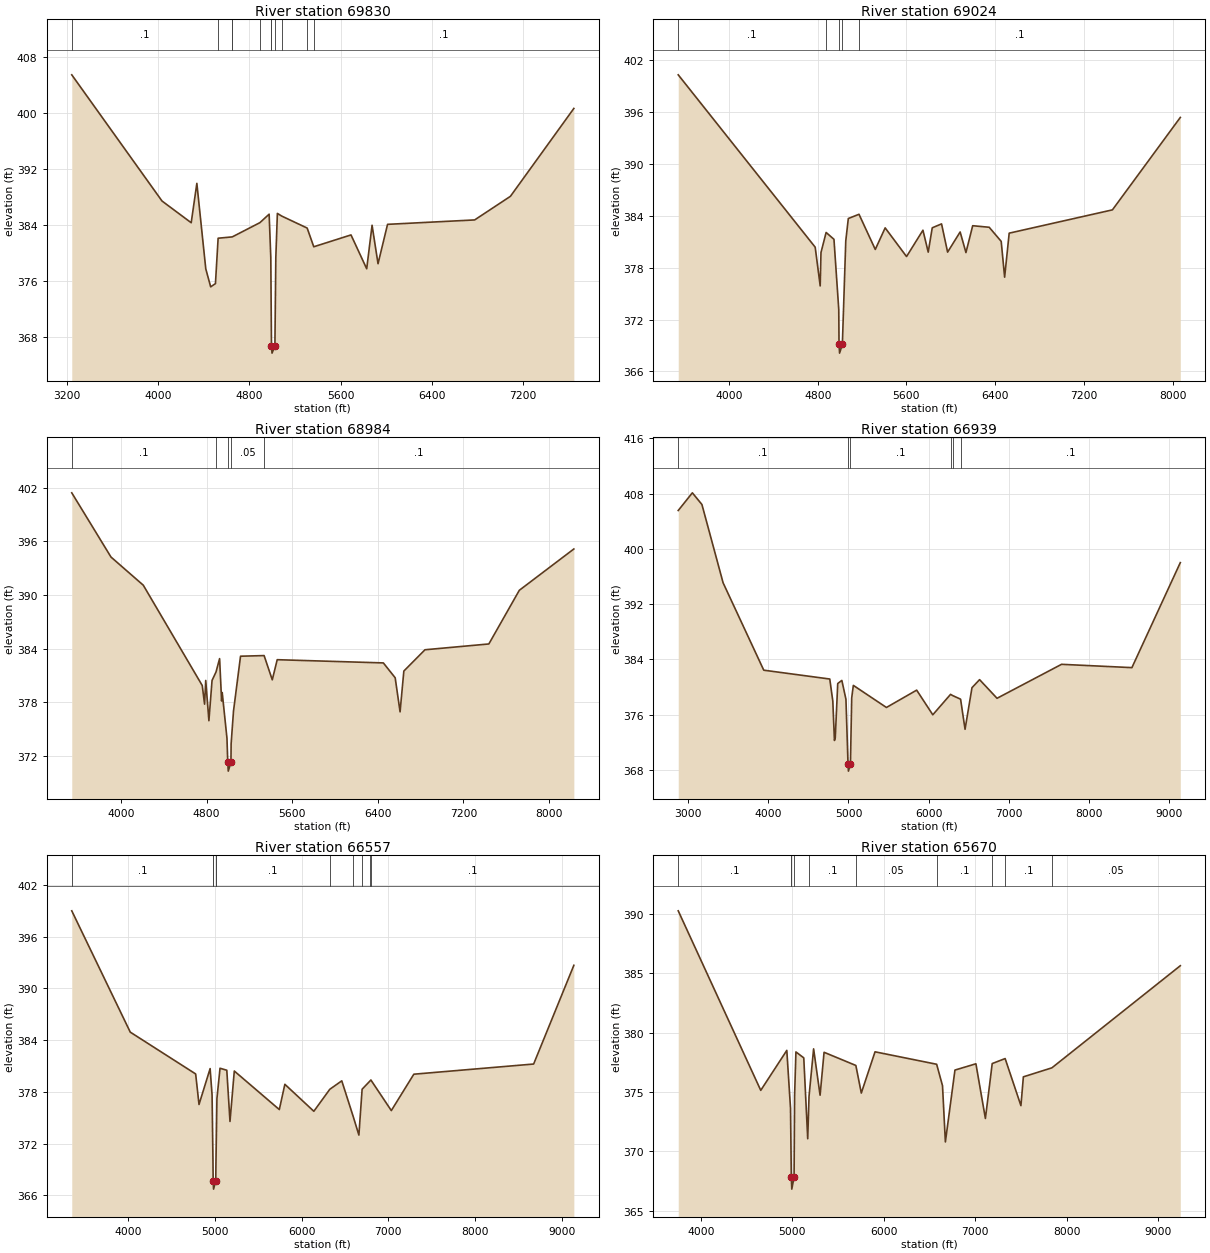
Type RM Length L Ch R = 1 ,69830   ,806,806,806
BEGIN DESCRIPTION:
Double Mapping XS b984e031
END DESCRIPTION:
XS GIS Cut Line= 5
      2066446.75     13458011.49      2066090.47     13457182.95
      2065630.76     13456804.87      2065144.65     13456448.97
      2062941.15     13455789.65
#Sta/Elev= 30
  3245.1  405.43  4035.9  387.42  4291.7  384.32  4341.2  389.94  4419.4  377.74
  4462.4  375.17  4504.1  375.63  4527.6  382.11  4651.5   382.3  4651.7   382.3
  4893.6  384.33  4974.6  385.54  4989.2  379.33  4992.9  371.42  4995.1  366.71
    5000  365.71  5025.1  366.71  5033.2  379.37  5046.8  385.65  5086.2  385.26
  5307.8  383.56  5365.7  380.89    5692  382.58  5829.6  377.75  5876.6  383.96
  5928.8  378.47  6012.3  384.09  6775.5  384.72    7089  388.09  7644.7  400.63
#Mann= 11 ,-1 , 0
  3245.1      .1       0  4527.6     .05       0  4651.5     .08       0
  4651.7      .1       0  4893.6     .07       0  4992.9     .12       0
  4995.1     .07       0  5025.1     .12       0  5086.2      .1       0
  5307.8     .05       0  5365.7      .1       0
Bank Sta=4995.1,5025.1
XS Rating Curve= 0 ,0
Exp/Cntr=0.3,0.1

Type RM Length L Ch R = 1 ,69024   ,40,40,40
BEGIN DESCRIPTION:
Double Mapping XS acfb6f6c
END DESCRIPTION:
XS GIS Cut Line= 4
      2066510.95     13457797.04      2066103.44     13456453.01
      2066163.33      13456324.1      2063264.48     13455626.94
#Sta/Elev= 30
  3542.1  400.25  4777.3  380.35  4822.4  375.88  4829.5  379.73  4875.8  382.05
  4946.6  381.26  4989.9  373.15  4992.3  369.12  4997.2  368.12  5022.3  369.12
  5053.1  381.08    5076  383.66  5172.4  384.15  5319.2  380.09  5408.3  382.58
  5601.2  379.27  5749.1  382.31  5796.7  379.78    5833  382.59  5916.9  383.04
  5971.5  379.78  6084.6  382.11  6136.9  379.73  6197.8  382.83  6346.7  382.65
  6454.9  381.02  6485.8  376.89  6526.9  381.97    7458  384.66  8070.2  395.33
#Mann= 5 ,-1 , 0
  3542.1      .1       0  4875.8     .05       0  4992.3     .04       0
  5022.3     .05       0  5172.4      .1       0
Bank Sta=4992.3,5022.3
XS Rating Curve= 0 ,0
Exp/Cntr=0.3,0.1

Type RM Length L Ch R = 1 ,68984   ,2045,2045,2045
BEGIN DESCRIPTION:
Double Mapping XS 4c13348f
END DESCRIPTION:
XS GIS Cut Line= 5
      2066667.21     13457753.66      2066137.29     13456460.82
       2066207.6      13456322.8        2066250.       13456250.
      2063291.72     13455479.69
#Sta/Elev= 30
  3539.6  401.42  3906.2  394.24  4208.2  391.09  4759.4  379.87    4781  377.79
  4791.8  380.44  4821.5  375.94  4850.9  380.44  4888.1  381.39  4921.5  382.88
  4940.3  378.14  4945.9  379.09  4990.4  373.97  4997.6   371.3  5002.5   370.3
  5027.6   371.3  5029.2  373.36  5051.5  377.02  5117.2  383.15  5337.5  383.22
  5413.9  380.51  5460.1  382.76  6452.2   382.4  6562.8  380.74  6608.5  376.93
  6643.8  381.49  6841.2  383.87  7438.5  384.52  7723.2  390.52  8232.9  395.14
#Mann= 5 ,-1 , 0
  3539.6      .1       0  4888.1     .05       0  4997.6     .04       0
  5027.6     .05       0  5337.5      .1       0
Bank Sta=4997.6,5027.6
XS Rating Curve= 0 ,0
Exp/Cntr=0.3,0.1

Type RM Length L Ch R = 1 ,66939   ,382,382,382
BEGIN DESCRIPTION:
Double Mapping XS 3bd30b90
END DESCRIPTION:
XS GIS Cut Line= 4
      2066932.84     13457464.61      2067497.08     13455797.93
      2067392.92      13455320.5      2063469.69     13454495.93
#Sta/Elev= 30
  2878.7  405.56  3054.7  408.12  3173.9  406.43  3437.8  395.09  3944.6  382.43
  4767.3  381.15  4805.1  377.96  4825.5  372.25  4835.8  372.67  4866.5   380.5
  4917.6  380.95  4968.8  378.22  4994.8  368.81  4999.7  367.81  5024.8  368.81
  5040.5   378.4  5060.9  380.23  5473.5  377.03  5850.3  379.54  6051.4  375.97
  6272.5  378.93  6297.8  378.76  6397.6  378.23  6453.2  373.87  6539.7   379.9
  6634.3  381.06  6851.8  378.36  7655.7  383.28  8532.7   382.8  9135.9  398.01
#Mann= 6 ,-1 , 0
  2878.7      .1       0  4994.8     .07       0  5024.8      .1       0
  6272.5     .05       0  6297.8     .08       0  6397.6      .1       0
Bank Sta=4994.8,5024.8
XS Rating Curve= 0 ,0
Exp/Cntr=0.3,0.1

Type RM Length L Ch R = 1 ,66557   ,887,887,887
BEGIN DESCRIPTION:
Double Mapping XS a296abea
END DESCRIPTION:
XS GIS Cut Line= 4
      2068260.96     13457099.98      2067740.14       13455633.
      2067106.46     13454843.07      2064008.74     13453984.04
#Sta/Elev= 30
  3352.4     399  4026.2  384.93  4779.6  380.08  4818.3  376.54  4946.3   380.7
  4968.7  377.64    4979  370.05  4981.3  367.72  4986.2  366.72  5011.3  367.72
    5013  369.42  5024.7  377.23  5060.4  380.74  5138.4  380.51  5175.2  374.57
  5224.8  380.42  5743.3  375.95  5807.3  378.88  6141.2  375.75  6324.9   378.3
  6462.9  379.28  6596.2  375.09  6660.1  372.99  6697.3  378.31  6787.7  379.26
  6798.4  379.38  7033.7  375.83  7293.1  380.05  8673.3  381.23  9136.4  392.68
#Mann= 10 ,-1 , 0
  3352.4      .1       0    4979     .12       0  4981.3     .07       0
  5011.3     .12       0    5013      .1       0  6324.9     .05       0
  6596.2      .1       0  6697.3     .05       0  6787.7     .08       0
  6798.4      .1       0
Bank Sta=4981.3,5011.3
XS Rating Curve= 0 ,0
Exp/Cntr=0.3,0.1

Type RM Length L Ch R = 1 ,65670   ,3126,3126,3126
BEGIN DESCRIPTION:
Double Mapping XS 7d2f30f9
END DESCRIPTION:
XS GIS Cut Line= 4
      2068816.54     13456101.79      2068636.47     13455568.36
      2067452.45     13454016.28      2064608.23      13453150.9
#Sta/Elev= 30
    3753  390.28    4655  375.14  4939.8  378.51  4980.4  373.62  4989.2  367.81
  4994.1  366.81  5019.2  367.81    5025   374.7  5039.5  378.38  5125.2  377.88
  5168.4  371.06  5182.7  374.64  5232.8  378.64  5303.5  374.73  5347.1  378.35
  5694.5  377.24  5754.1  374.91  5904.1  378.39  6577.8  377.34  6641.8  375.53
  6673.1  370.79  6777.7  376.85  7006.8  377.38  7110.6  372.77  7185.1   377.4
  7326.4  377.82  7498.9  373.85  7525.7  376.28  7837.6  377.04  9241.1  385.65
#Mann= 10 ,-1 , 0
    3753      .1       0  4980.4     .12       0  4989.2     .07       0
  5019.2     .12       0  5182.7      .1       0  5694.5     .05       0
  6577.8      .1       0  7185.1     .05       0  7326.4      .1       0
  7837.6     .05       0
Bank Sta=4989.2,5019.2
XS Rating Curve= 0 ,0
Exp/Cntr=0.3,0.1

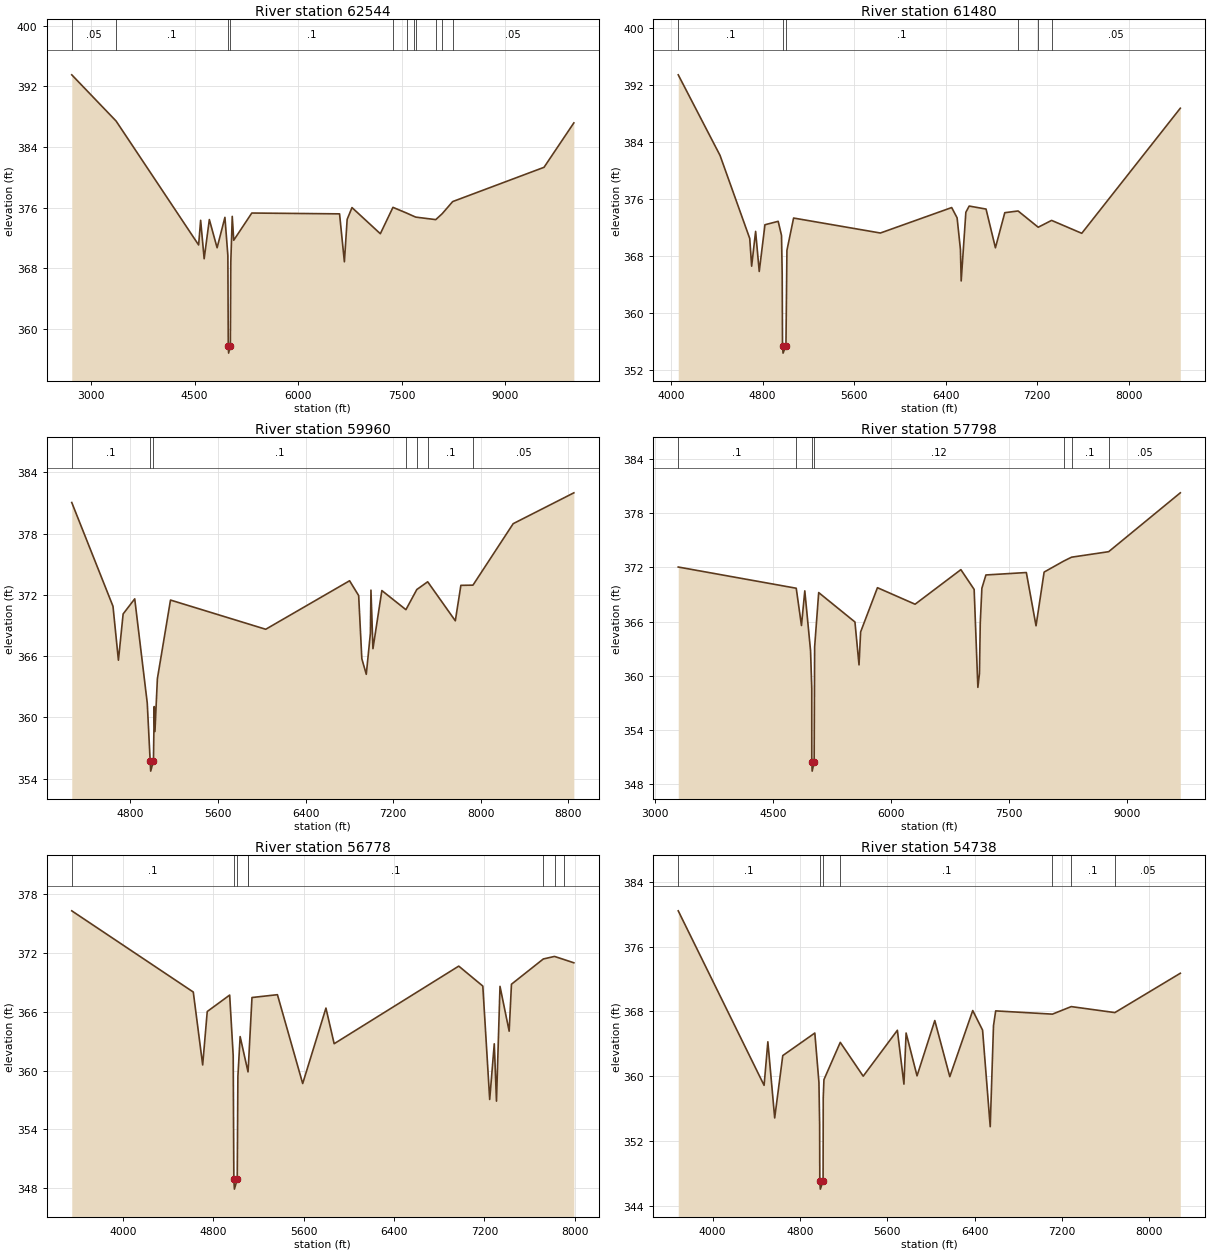
Type RM Length L Ch R = 1 ,62544   ,1064,1064,1064
BEGIN DESCRIPTION:
triple stream Mapping XS 90a1f3ca
END DESCRIPTION:
XS GIS Cut Line= 4
      2070465.85     13455763.24      2069563.41     13453875.22
      2068782.16     13453146.06      2064675.87     13452915.98
#Sta/Elev= 30
  2721.1  393.52  3363.7  387.42    4559  371.08  4588.2  374.33  4639.1  369.26
  4714.2  374.43  4826.7  370.71    4940  374.72  4982.6  369.69  4988.6  357.81
  4993.5  356.81  5018.6  357.81  5025.1  368.79  5046.1  374.85  5067.6   371.7
  5329.4  375.29  6600.7  375.18  6670.8  368.86  6710.8  374.45  6780.9  376.01
  7191.6  372.56  7374.5  376.04  7571.1  375.29  7674.4  374.87  7705.3  374.75
  7994.6  374.42  8086.6  375.19  8239.7   376.8    9563  381.32  9995.1  387.18
#Mann= 11 ,-1 , 0
  2721.1     .05       0  3363.7      .1       0  4988.6     .07       0
  5018.6      .1       0  7374.5     .05       0  7571.1      .1       0
  7674.4     .05       0  7705.3      .1       0  7994.6     .05       0
  8086.6      .1       0  8239.7     .05       0
Bank Sta=4988.6,5018.6
XS Rating Curve= 0 ,0
Exp/Cntr=0.3,0.1

Type RM Length L Ch R = 1 ,61480   ,1520,1520,1520
BEGIN DESCRIPTION:
quad  Mapping XS 55e44f09
END DESCRIPTION:
XS GIS Cut Line= 4
       2070580.3     13453789.26      2070469.19      13453560.1
      2069993.49     13453313.57      2066682.23     13451909.51
#Sta/Elev= 30
  4063.3  393.45  4428.3  382.16  4688.2   370.5  4704.7  366.62  4739.4   371.5
  4771.1  365.88    4821  372.43  4936.7  372.91  4965.8  370.93  4971.6  365.56
  4974.4  355.43  4979.3  354.43  5004.4  355.43  5013.1  368.84  5071.3  373.37
  5829.7  371.27  6452.7  374.84    6500   373.4  6529.1  368.99  6535.7  364.55
  6576.5  374.18  6605.6  375.05  6752.9  374.63  6834.9   369.2  6916.7  374.12
    7033  374.36  7208.7  372.08  7325.7  373.04  7589.3  371.23  8450.4  388.77
#Mann= 6 ,-1 , 0
  4063.3      .1       0  4974.4     .07       0  5004.4      .1       0
    7033     .05       0  7208.7      .1       0  7325.7     .05       0
Bank Sta=4974.4,5004.4
XS Rating Curve= 0 ,0
Exp/Cntr=0.3,0.1

Type RM Length L Ch R = 1 ,59960   ,2162,2162,2162
BEGIN DESCRIPTION:
triple  Mapping XS df564b5a
END DESCRIPTION:
XS GIS Cut Line= 4
      2070953.34     13453088.25      2070901.25     13452810.44
      2070477.63     13452296.55      2066900.02       13451650.
#Sta/Elev= 30
  4265.3  381.04  4641.7  370.88  4691.2   365.6  4734.3  370.13  4840.1  371.61
  4954.5  361.41  4981.1  355.74    4986  354.74  5011.1  355.74  5018.3  361.06
  5024.8  358.62    5047  363.79  5166.8  371.49  6036.3  368.63  6801.9  373.38
  6884.8  371.93  6913.7  365.75  6954.3  364.22  6991.9  368.23    6997  372.46
  7015.3  366.73  7096.6  372.42  7316.3  370.55  7415.6  372.52    7515  373.28
  7767.3  369.46  7818.1  372.93  7928.5  372.95  8295.7  378.97  8849.5  381.99
#Mann= 7 ,-1 , 0
  4265.3      .1       0  4981.1     .07       0  5011.1      .1       0
  7316.3     .05       0  7415.6     .08       0    7515      .1       0
  7928.5     .05       0
Bank Sta=4981.1,5011.1
XS Rating Curve= 0 ,0
Exp/Cntr=0.3,0.1

Type RM Length L Ch R = 1 ,57798   ,1020,1020,1020
BEGIN DESCRIPTION:
Triple Mapping XS e7ac9993
END DESCRIPTION:
XS GIS Cut Line= 5
      2071686.33     13452832.35      2071625.57     13451378.36
      2071130.77      13451070.2      2069754.91     13450805.44
       2066890.3     13451485.92
#Sta/Elev= 30
  3291.6  372.04  4791.9  369.69  4858.4  365.56  4900.8   369.4    4974  362.77
  4989.4  358.63  4989.7  350.43  4994.6  349.43  5019.7  350.43  5025.9  363.19
  5077.4  369.21  5538.4  365.95  5590.2   361.2  5610.6  364.85  5824.5  369.75
  6303.1  367.92  6885.2  371.75    7054  369.56  7101.3  358.71  7121.4  360.23
  7131.6  365.83  7152.2  369.69  7203.6  371.16  7717.5  371.43  7840.8  365.53
  7943.6  371.48  8190.8  372.69  8292.5  373.13  8764.4  373.74  9675.2  380.26
#Mann= 7 ,-1 , 0
  3291.6      .1       0  4791.9     .12       0  4989.7     .07       0
  5019.7     .12       0  8190.8     .08       0  8292.5      .1       0
  8764.4     .05       0
Bank Sta=4989.7,5019.7
XS Rating Curve= 0 ,0
Exp/Cntr=0.3,0.1

Type RM Length L Ch R = 1 ,56778   ,2040,2040,2040
BEGIN DESCRIPTION:
Double Mapping XS c9f67870
END DESCRIPTION:
XS GIS Cut Line= 4
      2073019.62     13451223.25      2072614.28     13450921.76
      2070155.95     13450220.38      2068790.51     13449983.69
#Sta/Elev= 30
  3544.9  376.32  4621.3  368.02  4704.5  360.57  4744.9  366.03  4943.6  367.71
  4974.8  361.54  4980.6  348.88  4985.5  347.88  5010.6  348.88  5016.4  359.38
  5036.3  363.47  5106.2  359.86  5110.1  360.63  5141.2  367.46  5366.7  367.75
  5590.4  358.67  5796.4  366.38  5869.2  362.74  6972.8  370.67    7186  368.63
  7246.9  357.04  7287.5  362.73    7307  356.87  7338.2   368.6  7419.4  364.02
  7439.7  368.82  7721.9   371.4  7821.1  371.66    7903  371.35  7992.3  371.01
#Mann= 8 ,-1 , 0
  3544.9      .1       0  4980.6     .07       0  5010.6      .1       0
  5106.2     .12       0  5110.1      .1       0  7721.9     .08       0
  7821.1     .05       0    7903      .1       0
Bank Sta=4980.6,5010.6
XS Rating Curve= 0 ,0
Exp/Cntr=0.3,0.1

Type RM Length L Ch R = 1 ,54738   ,2391,2391,2391
BEGIN DESCRIPTION:
Double Mapping XS 2aa75317
END DESCRIPTION:
XS GIS Cut Line= 4
      2073359.37     13449911.38       2073120.7     13449582.09
      2071710.98     13448925.84      2069074.62     13449022.46
#Sta/Elev= 30
  3684.5   380.4  4471.1  358.88  4505.6  364.25  4568.2  354.86  4642.3  362.55
  4935.8  365.33  4973.6  359.23  4979.9  354.11  4981.5  347.08  4986.4  346.08
  5011.5  347.08    5013  357.37  5019.4  359.58    5169  364.18  5379.1  360.01
  5692.2  365.67  5752.2  359.03  5772.2  365.33  5872.3  360.05    6035  366.87
  6172.5  359.95  6382.6   368.1  6472.7  365.69  6542.8  353.78  6572.8  366.23
  6592.8  368.06  7112.9  367.66    7285  368.59  7684.6  367.85  8284.3   372.7
#Mann= 7 ,-1 , 0
  3684.5      .1       0  4981.5     .07       0  5011.5      .1       0
    5169      .1       0  7112.9     .05       0    7285      .1       0
  7684.6     .05       0
Bank Sta=4981.5,5011.5
XS Rating Curve= 0 ,0
Exp/Cntr=0.3,0.1

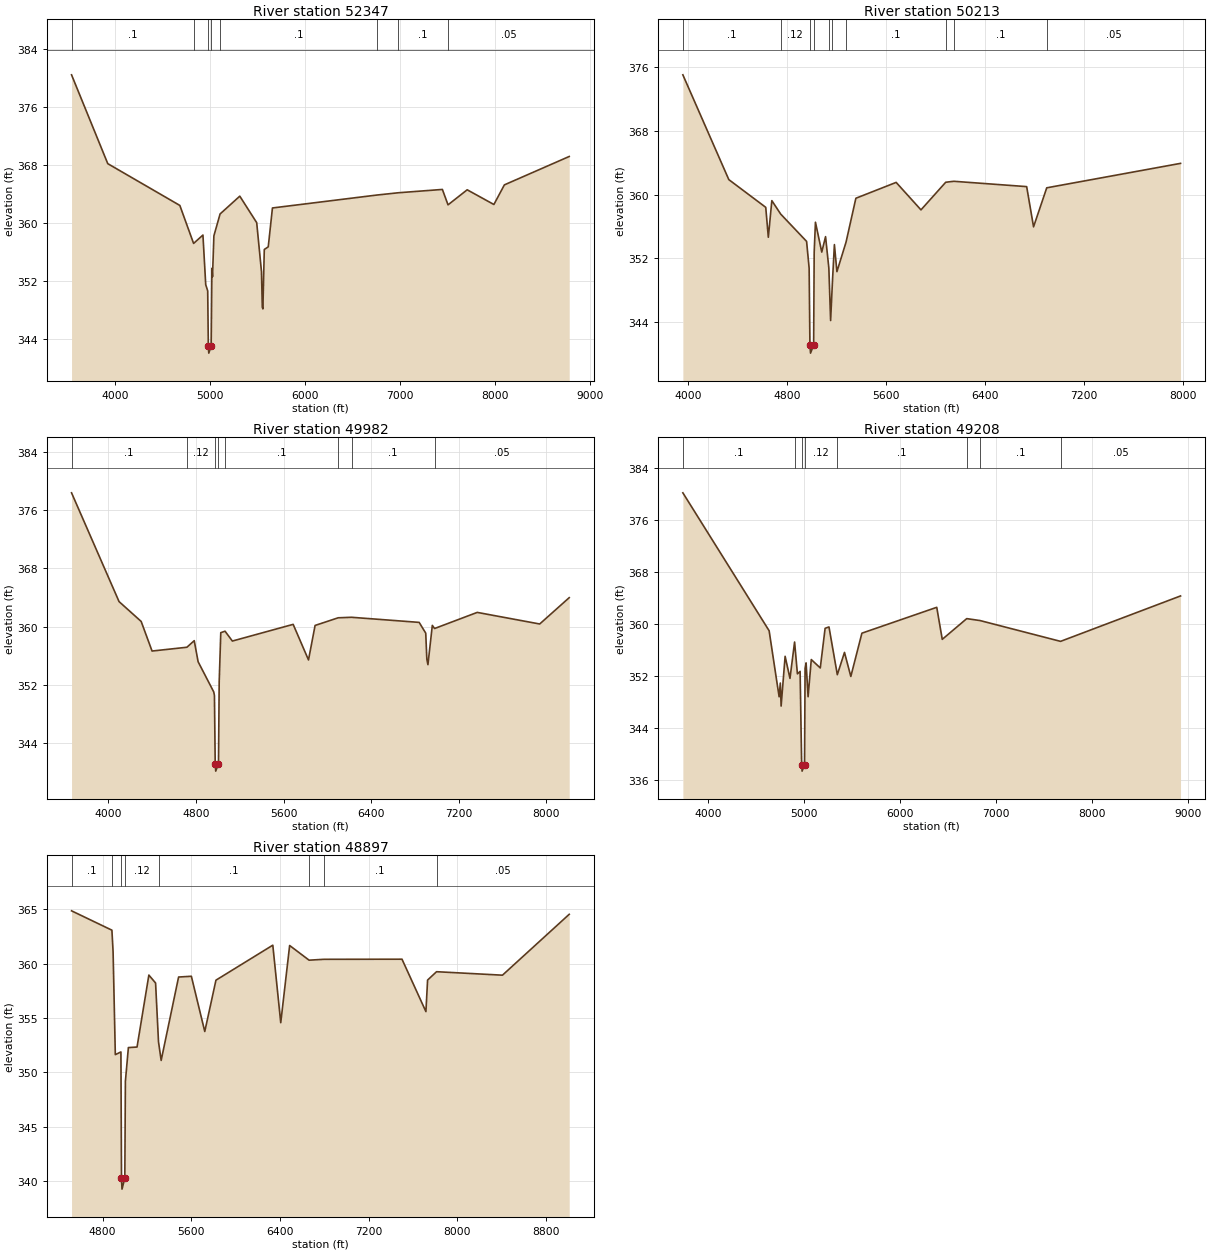
Type RM Length L Ch R = 1 ,52347   ,2134,2134,2134
BEGIN DESCRIPTION:
Double Mapping XS e09af441
END DESCRIPTION:
XS GIS Cut Line= 4
      2073532.97     13449258.56      2073642.06     13448137.04
       2072711.5     13447470.38      2069755.23     13447744.68
#Sta/Elev= 30
  3539.5  380.43  3920.9  368.16  4679.8  362.39  4824.7  357.14    4923   358.3
  4952.5  351.44  4973.3  350.59  4979.8  342.99  4984.7  341.99  5009.8  342.99
  5017.6  353.71  5023.7  352.54  5038.4  358.19  5103.5  361.21  5311.1  363.67
  5489.2  360.01  5539.6  353.23  5548.2  348.33  5554.3   348.1  5569.1  356.31
  5610.8  356.67    5655  362.04  6751.7  363.82  6980.8  364.14  7444.5   364.6
  7503.9  362.47  7705.6  364.55  7986.8  362.52  8097.3  365.23    8780  369.15
#Mann= 8 ,-1 , 0
  3539.5      .1       0  4824.7     .12       0  4979.8     .07       0
  5009.8     .12       0  5103.5      .1       0  6751.7     .05       0
  6980.8      .1       0  7503.9     .05       0
Bank Sta=4979.8,5009.8
XS Rating Curve= 0 ,0
Exp/Cntr=0.3,0.1

Type RM Length L Ch R = 1 ,50213   ,231,231,231
BEGIN DESCRIPTION:
Triple stream Mapping XS ee7c1e63
END DESCRIPTION:
XS GIS Cut Line= 5
      2074551.12      13447257.9      2074363.63     13446893.34
      2074051.13     13446612.09      2072618.84     13446315.21
      2070895.78     13446458.23
#Sta/Elev= 30
  3959.4  375.03  4330.8  361.87  4629.2  358.39  4650.1  354.63  4678.5  359.23
  4750.2  357.54  4959.4  354.11  4979.9  350.75  4986.3  341.08  4991.1  340.08
  5016.3  341.08  5020.7  352.73  5030.9  356.52    5082  352.77  5112.6  354.71
  5139.3  350.75  5153.5  344.17  5168.6  349.16  5184.1  353.71  5204.5  350.31
  5278.1  354.01  5357.7  359.53  5683.2  361.52  5883.8  358.07  6083.8  361.54
  6149.5  361.66    6738  360.99  6793.6  355.94  6900.3  360.84  7981.5  363.91
#Mann= 10 ,-1 , 0
  3959.4      .1       0  4750.2     .12       0  4986.3     .07       0
  5016.3     .12       0  5139.3      .1       0  5168.6     .12       0
  5278.1      .1       0  6083.8     .05       0  6149.5      .1       0
  6900.3     .05       0
Bank Sta=4986.3,5016.3
XS Rating Curve= 0 ,0
Exp/Cntr=0.3,0.1

Type RM Length L Ch R = 1 ,49982   ,774,774,774
BEGIN DESCRIPTION:
Double Mapping XS b05b69f4
END DESCRIPTION:
XS GIS Cut Line= 4
      2074792.18     13447304.21       2074531.3     13446870.29
      2073526.09     13446083.83      2070765.58     13446176.98
#Sta/Elev= 30
  3662.9  378.36  4096.8  363.44  4298.7  360.72  4398.1  356.66  4716.3  357.18
  4783.3  358.08  4818.6   355.2  4961.5  351.05  4967.8  350.56  4974.8  341.19
  4979.5  340.19  5004.8  341.19  5011.2  352.43  5025.7  359.18  5064.6  359.38
  5131.5  358.03  5686.7  360.32  5826.8  355.44  5886.9  360.17  6097.8  361.22
  6219.7  361.29  6837.4  360.59  6897.4  359.11  6907.4  355.55  6917.4  354.79
  6957.5  360.18  6978.1  359.75  7367.7  361.96    7938  360.37  8207.6  363.98
#Mann= 8 ,-1 , 0
  3662.9      .1       0  4716.3     .12       0  4974.8     .07       0
  5004.8     .12       0  5064.6      .1       0  6097.8     .05       0
  6219.7      .1       0  6978.1     .05       0
Bank Sta=4974.8,5004.8
XS Rating Curve= 0 ,0
Exp/Cntr=0.3,0.1

Type RM Length L Ch R = 1 ,49208   ,311,311,311
BEGIN DESCRIPTION:
Double Mapping XS 027d7286
END DESCRIPTION:
XS GIS Cut Line= 5
       2074890.6     13447359.26       2074718.8     13446760.83
      2074500.05     13446007.35      2073274.35     13445837.22
      2070744.73     13446104.07
#Sta/Elev= 30
  3736.4  380.18  4635.8  358.95  4739.9  348.79  4752.4  350.91  4760.8  347.36
  4802.4  355.02  4853.1  351.62  4901.1  357.22  4930.6  352.32  4958.6   352.7
  4974.9  338.35  4979.5  337.35  5004.9  338.35  5010.7  353.16  5021.1  354.01
  5041.9   348.8  5075.2  354.52  5168.9  353.23  5219.4  359.33  5259.7  359.54
  5346.7  352.19  5421.3  355.62  5487.5  351.92    5603  358.58  6383.2  362.56
  6440.7  357.63  6695.8  360.82  6835.1  360.52    7674  357.32  8924.7  364.31
#Mann= 8 ,-1 , 0
  3736.4      .1       0  4901.1     .12       0  4974.9     .07       0
  5004.9     .12       0  5346.7      .1       0  6695.8     .05       0
  6835.1      .1       0    7674     .05       0
Bank Sta=4974.9,5004.9
XS Rating Curve= 0 ,0
Exp/Cntr=0.3,0.1

Type RM Length L Ch R = 1 ,48897   ,1169,1169,1169
BEGIN DESCRIPTION:
Double Mapping XS 736590be
END DESCRIPTION:
XS GIS Cut Line= 4
      2075090.33     13446031.67      2075006.99     13445930.97
      2073347.27     13445708.74      2070671.82     13445942.61
#Sta/Elev= 30
    4520  364.85  4884.2  363.07  4894.9  361.08    4915  351.62  4965.5  351.87
  4970.7  340.25  4975.3  339.25  5000.7  340.25  5005.9  349.17  5032.9  352.27
    5111  352.32  5217.7  358.94  5278.3  358.21  5304.7   352.8  5328.7  351.09
    5486  358.76  5601.1  358.83  5722.2  353.75  5823.1  358.47  6336.1  361.69
  6407.8  354.56  6488.1  361.66  6663.6  360.31  6796.3  360.39    7502   360.4
  7717.8  355.58  7732.9  358.48  7813.7  359.25  8408.6  358.93  9010.9  364.53
#Mann= 8 ,-1 , 0
    4520      .1       0  4884.2     .12       0  4970.7     .07       0
  5000.7     .12       0  5304.7      .1       0  6663.6     .05       0
  6796.3      .1       0  7813.7     .05       0
Bank Sta=4970.7,5000.7
XS Rating Curve= 0 ,0
Exp/Cntr=0.3,0.1