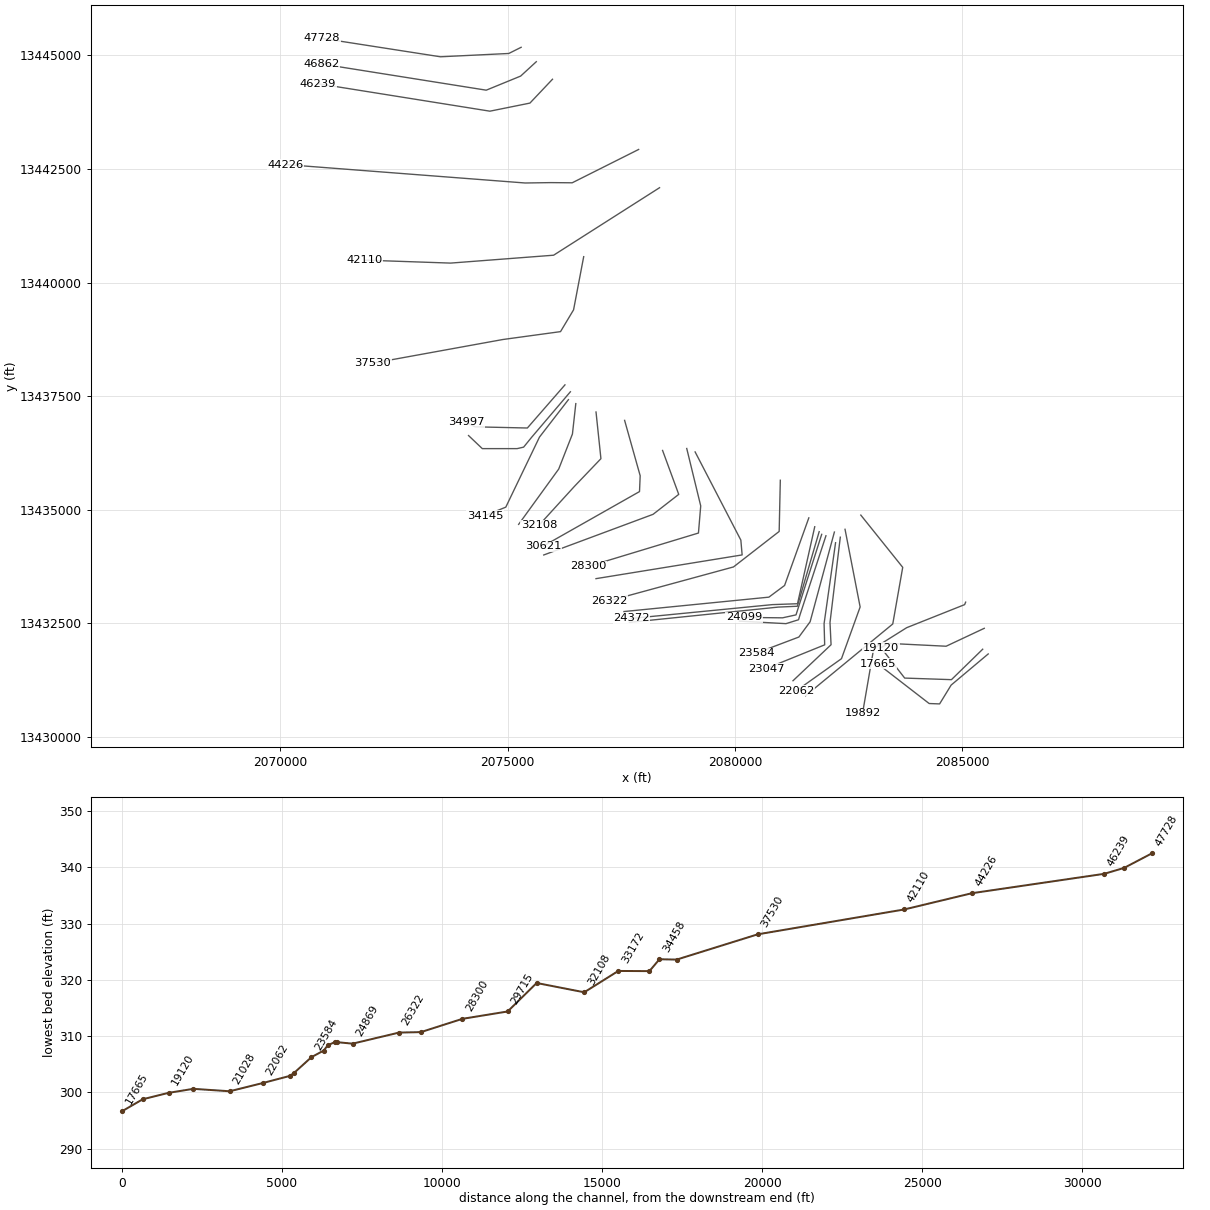
HEC-RAS study LAGUNILLAS Cr.prj: LAGUNILLAS Cr Base Level Engineering

--- LAGUNILLAS Cr.g01 (geometry) --- (continued)

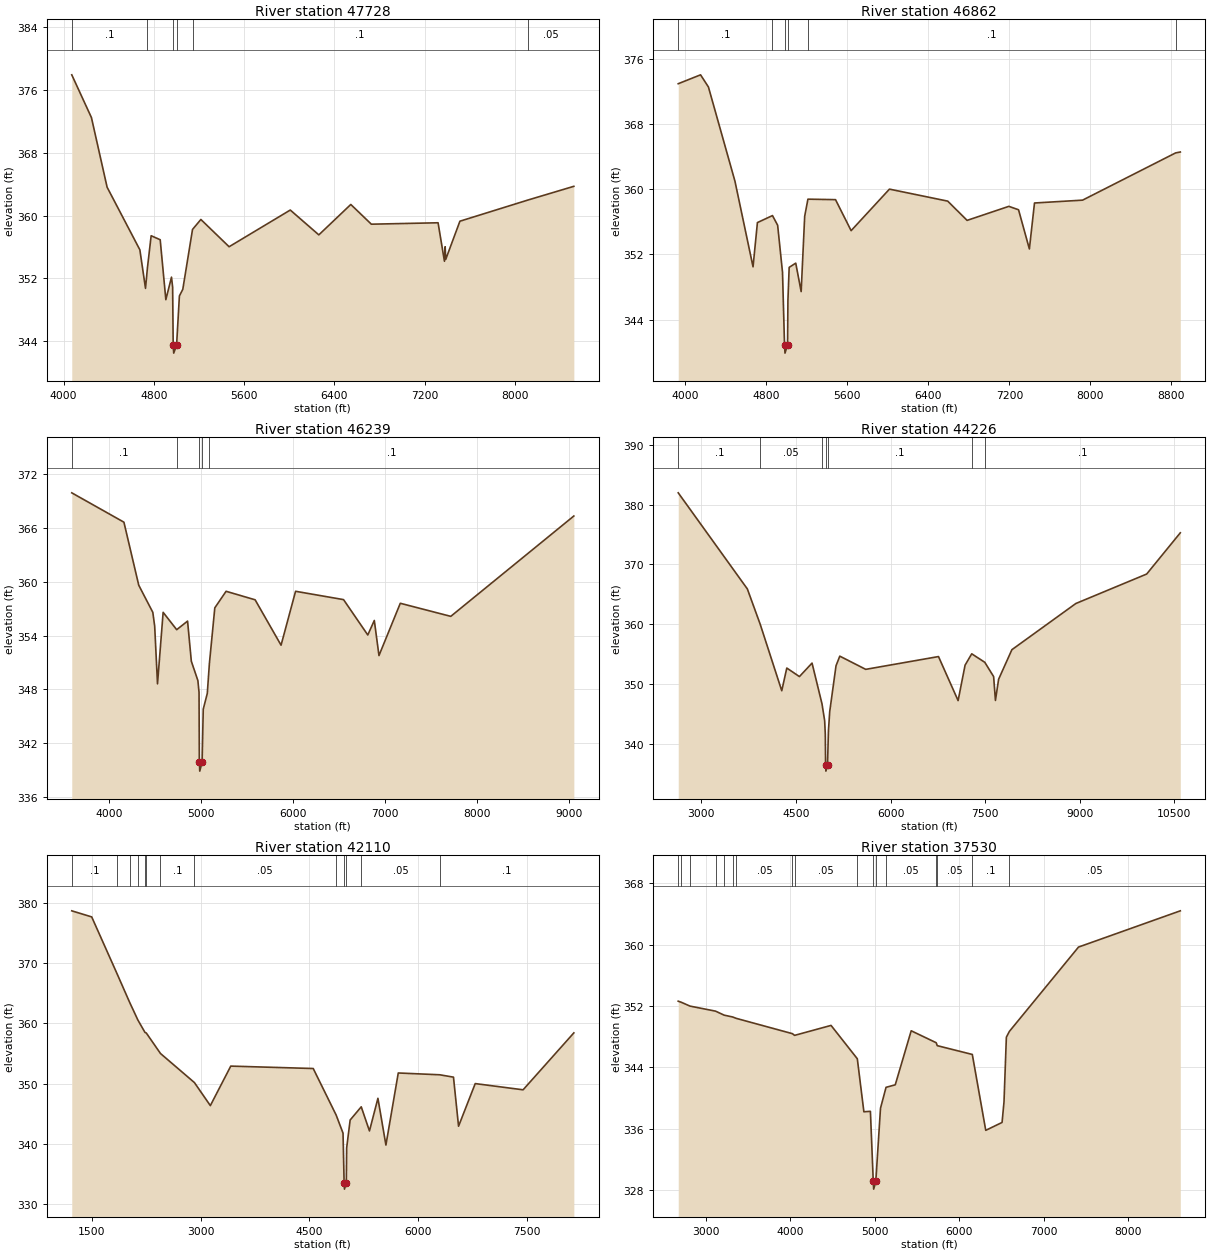
Type RM Length L Ch R = 1 ,47728   ,866,866,866
BEGIN DESCRIPTION:
Double Mapping XS 13647e21
END DESCRIPTION:
XS GIS Cut Line= 4
      2075296.02     13445177.86      2075024.35     13445042.08
      2073520.88     13444969.16      2070912.04     13445375.19
#Sta/Elev= 30
    4072  377.91  4246.3  372.47  4385.1  363.61  4675.4  355.64  4725.5  350.73
  4742.4  353.33  4775.5  357.43  4855.6  356.92  4905.7  349.29  4955.7  352.16
  4965.8  350.89  4970.8  343.49  4975.4  342.49  5000.8  343.49  5025.8  349.77
  5055.9  350.61  5142.1  358.23  5216.1   359.5  5466.3  356.03  6008.3   360.7
  6261.4  357.54  6544.7  361.41  6726.8   358.9    7318  359.08  7374.6  354.18
  7380.8  356.03  7385.9  354.42  7511.6  359.28  8113.5  361.97  8521.2  363.72
#Mann= 6 ,-1 , 0
    4072      .1       0  4742.4     .12       0  4970.8     .07       0
  5000.8     .12       0  5142.1      .1       0  8113.5     .05       0
Bank Sta=4970.8,5000.8
XS Rating Curve= 0 ,0
Exp/Cntr=0.3,0.1

Type RM Length L Ch R = 1 ,46862   ,623,623,623
BEGIN DESCRIPTION:
Double Mapping XS 7f389217
END DESCRIPTION:
XS GIS Cut Line= 4
      2075630.19     13444861.01      2075285.64     13444544.68
      2074528.26     13444234.35      2070903.37     13444810.96
#Sta/Elev= 30
  3930.5  372.93  4150.9  374.02  4228.6  372.53  4490.3  360.99    4669  350.49
  4712.3  355.91    4861  356.77    4912  355.58    4960  349.81  4979.8  340.91
  4984.4  339.91  5009.8  340.91  5013.4  346.38  5025.7  350.42  5090.6  350.94
  5144.1  347.45  5178.9  356.68  5210.8  358.78  5483.3  358.72  5637.4  354.92
  6015.7  360.01  6590.8  358.54  6782.5  356.18  7194.5   357.9  7290.2  357.48
  7397.1  352.68  7447.7  358.31  7922.4  358.66    8841  364.45  8887.2  364.56
#Mann= 6 ,-1 , 0
  3930.5      .1       0    4861     .12       0  4979.8     .07       0
  5009.8     .12       0  5210.8      .1       0    8841     .05       0
Bank Sta=4979.8,5009.8
XS Rating Curve= 0 ,0
Exp/Cntr=0.3,0.1

Type RM Length L Ch R = 1 ,46239   ,4129,4129,4129
BEGIN DESCRIPTION:
Double Mapping XS e3a10c01
END DESCRIPTION:
XS GIS Cut Line= 4
      2075986.12     13444474.76      2075489.63     13443950.06
      2074608.55     13443772.11      2070825.22     13444376.93
#Sta/Elev= 30
  3595.3  369.95  4161.7  366.67  4322.7  359.63  4475.4   356.6  4495.8  355.05
  4526.4  348.61  4587.6   356.6  4734.8  354.66  4852.9  355.62  4893.7  351.14
  4965.1  348.97  4977.5  347.65  4980.7  339.86  4985.4  338.86  5010.7  339.86
  5023.2  345.78  5067.1  347.54  5089.9  350.87  5148.7   357.1  5271.2  358.95
  5586.5     358  5868.3  352.93  6025.9  358.95  6546.8  358.02  6810.1  354.07
    6881  355.69  6931.6  351.77  7163.2  357.61  7711.4  356.15  9047.9  367.36
#Mann= 5 ,-1 , 0
  3595.3      .1       0  4734.8     .12       0  4980.7     .07       0
  5010.7     .12       0  5089.9      .1       0
Bank Sta=4980.7,5010.7
XS Rating Curve= 0 ,0
Exp/Cntr=0.3,0.1

Type RM Length L Ch R = 1 ,44226   ,2116,2116,2116
BEGIN DESCRIPTION:
Triple Mapping XS fee2bb3f
END DESCRIPTION:
XS GIS Cut Line= 5
      2077882.09     13442929.75       2076420.1     13442196.08
        2075950.       13442200.      2075382.79     13442191.74
      2070113.42     13442597.42
#Sta/Elev= 30
  2634.9  381.99  3730.3  365.91  3935.3  359.96  4275.8  348.87  4355.8  352.67
  4555.8  351.24  4755.8   353.5  4913.8  346.67  4955.8  343.86  4965.8  341.61
  4970.8  336.42  4975.4  335.42  5000.8  336.42  5015.8  342.18  5035.8  345.37
  5135.8  353.05  5195.8  354.66  5606.7  352.45  6760.1  354.59    7071  347.22
  7181.4  353.15    7287  355.05    7494  353.63    7634  351.24  7662.8  347.25
  7712.9  350.79  7923.5  355.74  8937.3  363.47 10059.9   368.4   10593   375.3
#Mann= 7 ,-1 , 0
  2634.9      .1       0  3935.3     .05       0  4913.8      .1       0
  4970.8     .07       0  5000.8      .1       0    7287     .05       0
    7494      .1       0
Bank Sta=4970.8,5000.8
XS Rating Curve= 0 ,0
Exp/Cntr=0.3,0.1

Type RM Length L Ch R = 1 ,42110   ,4580,4580,4580
BEGIN DESCRIPTION:
Mapping XS 80737ea4
END DESCRIPTION:
XS GIS Cut Line= 4
      2078342.19     13442087.74      2076010.97     13440602.46
      2073743.17     13440428.84       2071855.1     13440493.95
#Sta/Elev= 30
  1222.7  378.68  1497.8  377.67  1846.8  368.27  2020.3  363.53  2134.6  360.58
  2232.8  358.52  2251.1  358.42  2446.9  355.02  2915.1   350.2  3134.8  346.38
  3416.7  352.93  4554.5  352.53  4870.9  344.81  4965.7  341.81  4980.8  333.53
  4985.4  332.53  5010.8  333.53  5015.8  339.38    5064  343.99  5216.9  346.18
  5330.4  342.18  5447.1  347.59  5557.4  339.84  5727.9  351.79  6301.2  351.49
  6489.6   351.1  6559.7  342.96  6789.8  350.03  7450.2     349  8150.5  358.44
#Mann= 13 ,-1 , 0
  1222.7      .1       0  1846.8     .08       0  2020.3      .1       0
  2134.6     .08       0  2232.8      .1       0  2251.1     .05       0
  2446.9      .1       0  2915.1     .05       0  4870.9      .1       0
  4980.8     .07       0  5010.8      .1       0  5216.9     .05       0
  6301.2      .1       0
Bank Sta=4980.8,5010.8
XS Rating Curve= 0 ,0
Exp/Cntr=0.3,0.1

Type RM Length L Ch R = 1 ,37530   ,2533,2533,2533
BEGIN DESCRIPTION:
Mapping XS 32ecfcd9
END DESCRIPTION:
XS GIS Cut Line= 5
      2076672.92      13440570.4        2076450.       13439400.
      2076162.88      13438920.6      2074893.34     13438746.99
      2072029.39     13438226.27
#Sta/Elev= 30
  2673.9  352.63    2712  352.48    2813  351.99    3116  351.33    3217  350.81
  3318.1  350.57  3360.7  350.39  4026.1  348.39  4050.7  348.17  4482.6  349.47
  4793.4  345.12  4871.3   338.2  4948.5  338.26  4982.3  329.11    4987  328.11
  5012.3  329.11    5068  338.67  5133.5  341.39  5242.5  341.72  5431.3  348.77
  5727.2  347.21  5739.3  346.83  6154.6  345.68  6313.6  335.78  6506.8  336.81
  6529.7   339.5  6557.6  347.93  6593.4  348.69  7411.4  359.69  8616.4  364.42
#Mann= 17 ,-1 , 0
  2673.9     .05       0    2712     .08       0    2813     .05       0
    3116     .08       0    3217     .05       0  3318.1     .08       0
  3360.7     .05       0  4026.1      .1       0  4050.7     .05       0
  4793.4      .1       0  4982.3     .07       0  5012.3      .1       0
  5133.5     .05       0  5727.2      .1       0  5739.3     .05       0
  6154.6      .1       0  6593.4     .05       0
Bank Sta=4982.3,5012.3
XS Rating Curve= 0 ,0
Exp/Cntr=0.3,0.1

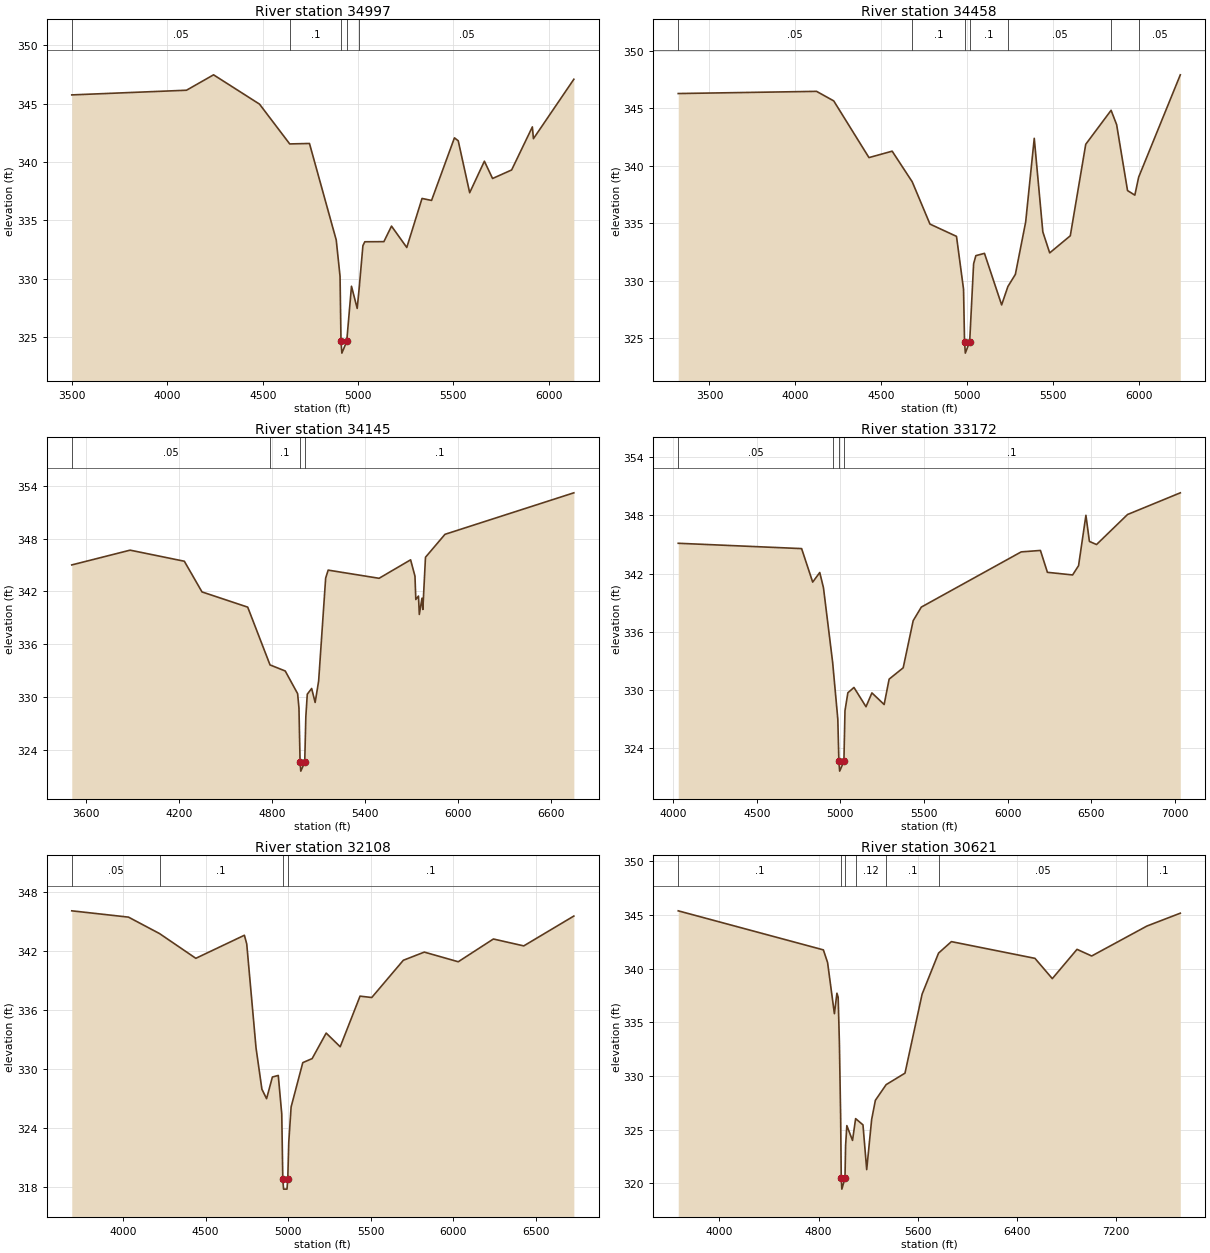
Type RM Length L Ch R = 1 ,34997   ,539,539,539
BEGIN DESCRIPTION:
Mapping XS 26014907
END DESCRIPTION:
XS GIS Cut Line= 4
      2076260.55     13437748.75       2075433.2     13436799.46
      2074283.03      13436825.5      2074081.59     13436924.37
#Sta/Elev= 30
  3498.3  345.74  4100.2  346.14  4242.2  347.46  4483.3  344.95  4641.8  341.54
  4745.4  341.58  4885.8  333.31  4905.8   330.2  4910.8  324.62  4915.4  323.62
  4940.8  324.62  4965.8  329.35  4995.8  327.45  5006.9  329.31  5025.8  332.83
  5035.8  333.16  5135.8  333.17  5175.8   334.5  5255.9  332.67  5335.9  336.87
  5385.9   336.7  5505.9  342.06  5525.9  341.81  5585.9  337.36  5663.1  340.06
    5706  338.58    5806  339.31  5914.8     343  5920.4  341.99  6132.4  347.08
#Mann= 5 ,-1 , 0
  3498.3     .05       0  4641.8      .1       0  4910.8     .07       0
  4940.8      .1       0  5006.9     .05       0
Bank Sta=4910.8,4940.8
XS Rating Curve= 0 ,0
Exp/Cntr=0.3,0.1

Type RM Length L Ch R = 1 ,34458   ,313,313,313
BEGIN DESCRIPTION:
Mapping XS de5a6dca
END DESCRIPTION:
XS GIS Cut Line= 6
      2076379.89     13437596.82      2075530.86      13436599.8
      2075350.74     13436378.45      2075207.51      13436345.9
      2074441.45      13436345.9      2074138.81     13436633.41
#Sta/Elev= 30
  3318.3  346.29  4124.3  346.48  4224.3  345.65  4429.6  340.71  4564.7  341.27
  4681.7   338.6    4785  334.92  4939.6  333.85  4980.6  329.25  4986.4  324.68
    4991  323.68  5016.4  324.68  5039.3  331.46  5052.4  332.17  5102.6  332.37
  5202.6  327.88    5239  329.48  5282.6  330.54  5342.6   335.1  5392.6  342.39
  5442.6  334.24  5482.6  332.41  5602.6   333.9  5692.6  341.87  5840.3  344.83
  5872.6  343.58  5936.1  337.84  5978.6  337.44    6001  339.01  6243.6  347.92
#Mann= 7 ,-1 , 0
  3318.3     .05       0  4681.7      .1       0  4986.4     .07       0
  5016.4      .1       0    5239     .05       0  5840.3      .1       0
    6001     .05       0
Bank Sta=4986.4,5016.4
XS Rating Curve= 0 ,0
Exp/Cntr=0.3,0.1

Type RM Length L Ch R = 1 ,34145   ,973,973,973
BEGIN DESCRIPTION:
Mapping XS 621e5961
END DESCRIPTION:
XS GIS Cut Line= 4
      2076336.46     13437423.17        2075700.       13436600.
      2074958.45     13435057.75      2074502.75      13434873.3
#Sta/Elev= 30
  3506.4  345.02  3883.3   346.7  4233.6  345.44  4347.7  341.95    4643  340.22
  4787.1  333.65  4885.3  332.96  4965.4  330.38  4974.1  328.75  4981.3  322.57
  4985.9  321.57  5011.3  322.57  5018.5  327.77  5027.8  330.32    5056  330.97
  5078.6  329.38  5101.2  331.82  5146.5  343.52  5162.7  344.43  5491.6   343.5
  5695.3   345.6  5723.5  343.74    5729  341.09  5746.1  341.48  5751.6  339.39
  5768.7  341.24  5774.3  339.95  5791.4  345.89  5917.3   348.5  6749.8  353.22
#Mann= 4 ,-1 , 0
  3506.4     .05       0  4787.1      .1       0  4981.3     .07       0
  5011.3      .1       0
Bank Sta=4981.3,5011.3
XS Rating Curve= 0 ,0
Exp/Cntr=0.3,0.1

Type RM Length L Ch R = 1 ,33172   ,1064,1064,1064
BEGIN DESCRIPTION:
Mapping XS 2fb3c145
END DESCRIPTION:
XS GIS Cut Line= 4
      2076499.25     13437336.39      2076424.96     13436667.08
      2076123.31     13435896.68      2075241.32     13434679.02
#Sta/Elev= 30
  4029.6  345.13  4767.9  344.58  4834.1  341.12  4876.4  342.11  4898.6  340.54
  4953.6  332.83  4984.5  326.97  4990.9   322.6  4995.5   321.6  5020.9   322.6
  5027.4  327.84  5044.6  329.69  5081.1  330.24  5153.2  328.25  5188.5  329.68
  5261.7  328.48  5291.6   331.1  5375.7  332.27  5435.5  337.14  5484.2  338.54
  6081.7  344.24  6196.9  344.39  6238.7  342.13  6389.5  341.86  6425.1  342.82
  6469.1  348.02    6490  345.32  6532.6     345  6718.1   348.1  7033.9  350.34
#Mann= 4 ,-1 , 0
  4029.6     .05       0  4953.6      .1       0  4990.9     .07       0
  5020.9      .1       0
Bank Sta=4990.9,5020.9
XS Rating Curve= 0 ,0
Exp/Cntr=0.3,0.1

Type RM Length L Ch R = 1 ,32108   ,1487,1487,1487
BEGIN DESCRIPTION:
Mapping XS e94da1b0
END DESCRIPTION:
XS GIS Cut Line= 4
      2076944.13      13437151.9      2077052.13     13436124.54
       2076472.7     13435519.07      2075685.41     13434656.24
#Sta/Elev= 30
  3690.2  346.06  4033.6  345.42  4221.5  343.75  4441.2  341.24  4735.1  343.58
  4749.3   342.7  4805.6  332.14  4841.1  327.95  4869.4  326.99  4904.6  329.19
  4940.2  329.35  4961.3  325.43  4967.6  318.81  4972.2  317.81    4993  317.81
  4997.6  318.81  5003.7  322.57  5017.9  326.15  5088.6  330.65  5145.2  331.06
  5230.2  333.65  5315.1  332.26  5435.2   337.4    5506  337.26  5697.1  341.04
  5824.1  341.87  6029.5  340.89  6242.3   343.2  6426.1   342.5  6729.3  345.53
#Mann= 4 ,-1 , 0
  3690.2     .05       0  4221.5      .1       0  4967.6     .07       0
  4997.6      .1       0
Bank Sta=4967.6,4997.6
XS Rating Curve= 0 ,0
Exp/Cntr=0.3,0.1

Type RM Length L Ch R = 1 ,30621   ,906,906,906
BEGIN DESCRIPTION:
Mapping XS d9b67bb2
END DESCRIPTION:
XS GIS Cut Line= 4
      2077573.47     13436967.46      2077915.79     13435749.52
      2077901.47     13435400.56      2075783.13     13434200.56
#Sta/Elev= 30
  3667.6   345.4  4838.1  341.76  4872.1  340.58    4927  335.81  4947.3  337.72
  4957.3  337.35  4967.3   333.1  4977.3  326.25  4982.3  320.46  4986.9  319.46
  5012.3  320.46  5017.3  323.52  5027.3  325.38  5073.1     324  5098.1  326.03
  5157.4  325.45  5187.5  321.28  5227.5  325.96  5257.5  327.74  5344.4   329.2
  5496.3  330.27  5634.2  337.63    5767  341.46  5870.6  342.53  6544.5  340.97
  6684.4  339.08  6883.6  341.81  7001.9  341.19  7446.9  343.98  7716.6  345.18
#Mann= 7 ,-1 , 0
  3667.6      .1       0  4982.3     .07       0  5012.3      .1       0
  5098.1     .12       0  5344.4      .1       0    5767     .05       0
  7446.9      .1       0
Bank Sta=4982.3,5012.3
XS Rating Curve= 0 ,0
Exp/Cntr=0.3,0.1

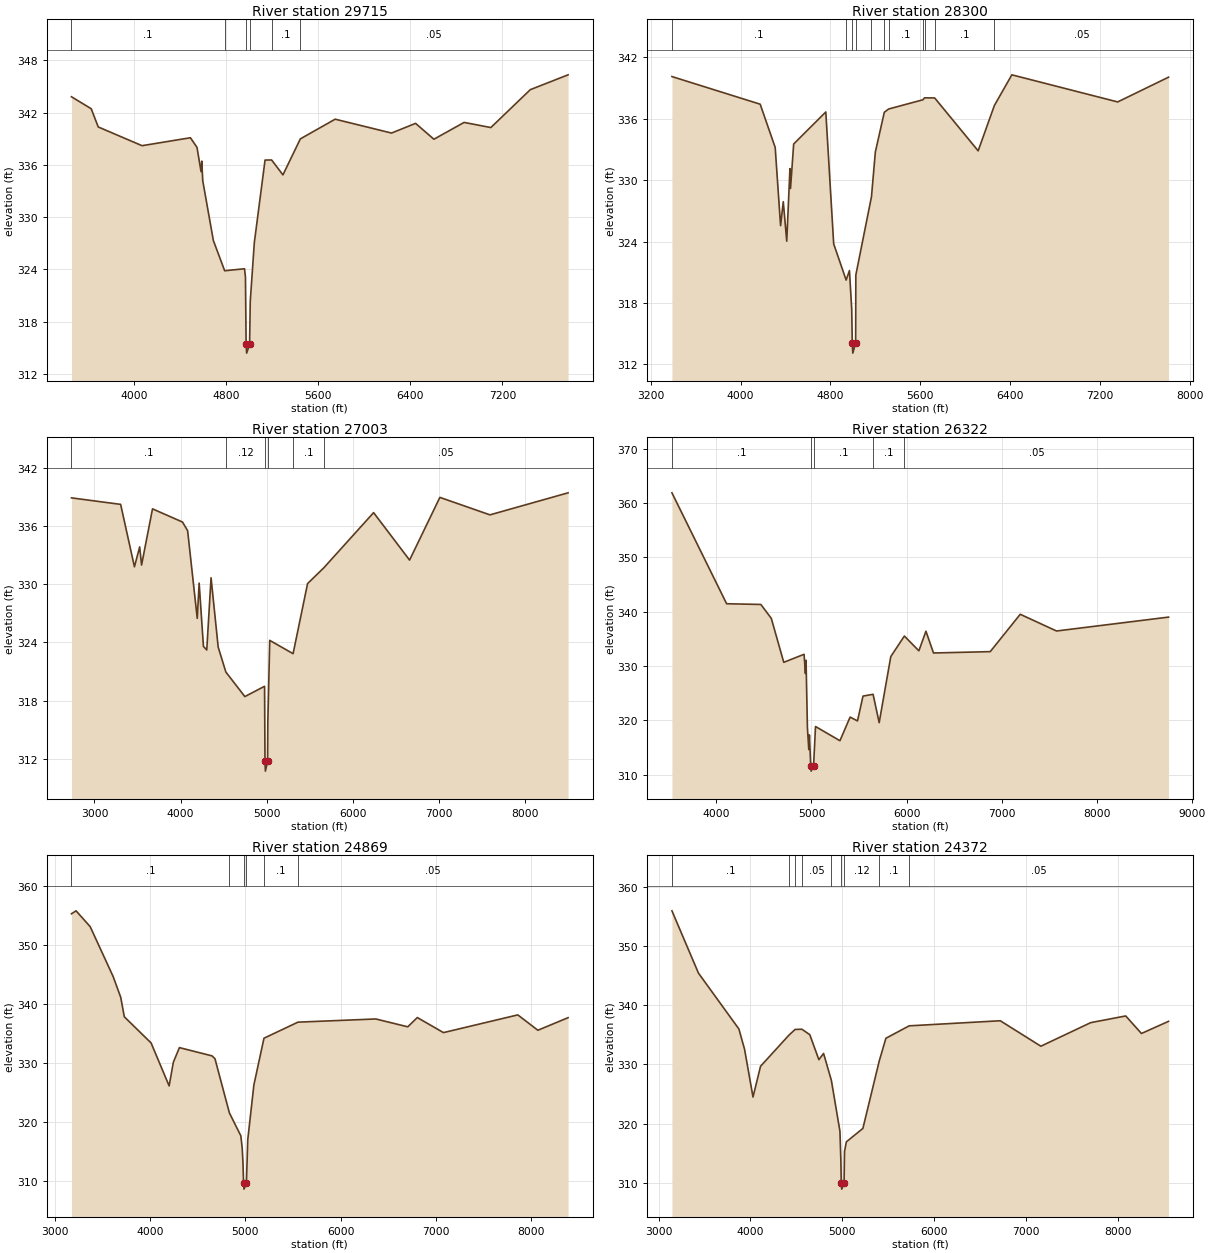
Type RM Length L Ch R = 1 ,29715   ,1415,1415,1415
BEGIN DESCRIPTION:
Mapping XS e6a3e642
END DESCRIPTION:
XS GIS Cut Line= 4
      2078408.98     13436305.55      2078764.37     13435338.95
        2078200.       13434900.      2075793.92     13434005.22
#Sta/Elev= 30
  3458.5  343.81  3629.6  342.44  3690.7  340.35  4070.9   338.2  4491.1  339.11
  4548.2  338.01  4583.5  335.22  4589.8  336.43    4598  334.19  4690.3  327.32
  4788.5  323.85  4960.8  324.08    4969  323.13  4974.8   315.4  4979.4   314.4
  5004.8   315.4  5010.6  320.32  5045.9  327.07  5139.1  336.55  5196.2  336.56
  5294.4  334.85  5445.6  338.98  5747.9  341.24  6237.2  339.65  6446.3  340.76
  6605.1  338.94  6867.5  340.87  7099.6  340.28  7442.5  344.63  7770.4  346.33
#Mann= 6 ,-1 , 0
  3458.5      .1       0  4788.5     .12       0  4974.8     .07       0
  5004.8     .12       0  5196.2      .1       0  5445.6     .05       0
Bank Sta=4974.8,5004.8
XS Rating Curve= 0 ,0
Exp/Cntr=0.3,0.1

Type RM Length L Ch R = 1 ,28300   ,1297,1297,1297
BEGIN DESCRIPTION:
Mapping XS 41fb0ba2
END DESCRIPTION:
XS GIS Cut Line= 4
      2078940.66     13436348.95      2079248.31     13435085.05
       2079198.4     13434488.26      2076781.36     13433755.67
#Sta/Elev= 30
  3387.6  340.12  4173.9  337.42  4307.7  333.19  4355.6  325.55  4379.7  327.89
  4410.6  324.03  4439.1  331.12  4444.2  329.18  4472.3  333.53  4758.7  336.66
  4828.9  323.77  4939.9  320.23  4969.4  321.16  4989.5  317.41  4994.6  314.09
  4999.2  313.09  5024.6  314.09  5026.3  320.72  5165.7  328.38  5200.2  332.75
    5280  336.63  5318.7  336.95  5623.9  337.85  5638.5  338.04  5728.9  338.03
  6116.3  332.86  6260.8  337.29  6416.5  340.29  7359.8  337.64  7812.9  340.06
#Mann= 11 ,-1 , 0
  3387.6      .1       0  4939.9     .12       0  4994.6     .07       0
  5024.6     .12       0  5165.7      .1       0    5280     .12       0
  5318.7      .1       0  5623.9     .12       0  5638.5     .05       0
  5728.9      .1       0  6260.8     .05       0
Bank Sta=4994.6,5024.6
XS Rating Curve= 0 ,0
Exp/Cntr=0.3,0.1

Type RM Length L Ch R = 1 ,27003   ,681,681,681
BEGIN DESCRIPTION:
Mapping XS a3236951
END DESCRIPTION:
XS GIS Cut Line= 4
      2079125.13     13436273.01      2080131.56     13434332.01
      2080159.77     13434006.49      2076944.12      13433484.4
#Sta/Elev= 30
  2733.1  338.88  3304.1  338.21  3464.6  331.78  3525.4  333.83  3547.5  331.96
  3674.6  337.75    4023  336.39  4082.6   335.5  4194.4  326.47  4216.5   330.1
  4266.4  323.58    4305  323.21  4354.9  330.65  4437.8  323.51  4526.9  320.94
  4747.6  318.41  4976.7  319.47  4981.8  311.73  4986.4  310.73  5011.8  311.73
  5014.6  315.78    5037   324.2  5308.2  322.83  5476.5  330.05  5664.6  331.67
  6243.9  337.36  6661.9  332.47  7013.9  338.93  7595.9  337.13    8504   339.4
#Mann= 6 ,-1 , 0
  2733.1      .1       0  4526.9     .12       0  4981.8     .07       0
  5011.8     .12       0  5308.2      .1       0  5664.6     .05       0
Bank Sta=4981.8,5011.8
XS Rating Curve= 0 ,0
Exp/Cntr=0.3,0.1

Type RM Length L Ch R = 1 ,26322   ,1453,1453,1453
BEGIN DESCRIPTION:
Mapping XS 5a0999ca
END DESCRIPTION:
XS GIS Cut Line= 4
        2081000.     13435650.04       2080974.8     13434523.33
       2079969.6     13433742.08      2077245.49     13432999.51
#Sta/Elev= 30
  3532.6  361.91  4107.8  341.48  4467.9  341.35  4577.9  338.78  4708.8  330.69
  4922.4  332.17  4936.8  328.63  4943.2  331.08  4957.7  318.62  4972.1  314.61
  4978.5  317.32  4992.4  311.65    4997  310.65  5022.4  311.65  5042.7  318.87
  5299.7  316.25  5406.6   320.6  5484.4   319.9  5542.3  324.47  5648.3   324.8
  5712.4  319.58  5834.6  331.75  5977.4  335.53    6130  332.81  6204.3  336.42
  6283.8  332.41  6880.7  332.66  7196.1  339.54    7578  336.46  8756.2  339.02
#Mann= 5 ,-1 , 0
  3532.6      .1       0  4992.4     .07       0  5022.4      .1       0
  5648.3      .1       0  5977.4     .05       0
Bank Sta=4992.4,5022.4
XS Rating Curve= 0 ,0
Exp/Cntr=0.3,0.1

Type RM Length L Ch R = 1 ,24869   ,497,497,497
BEGIN DESCRIPTION:
Mapping XS d7bcc558
END DESCRIPTION:
XS GIS Cut Line= 4
      2081627.36     13434821.95      2081093.92     13433334.19
      2080748.43     13433077.25       2077559.2     13432760.38
#Sta/Elev= 30
    3174   355.3    3222   355.8  3370.4  353.12  3611.1  344.69  3691.3  341.15
  3728.8  337.86    4010  333.43  4199.5  326.16  4243.7  330.16  4307.5  332.64
  4650.2  331.24  4680.9  330.76  4832.7  321.58  4952.6  317.71  4966.9  315.63
  4975.3  313.11  4981.1  309.68  4985.7  308.68  5011.1  309.68  5025.4  317.05
  5089.6  326.31  5195.7  334.23  5552.6  336.95  6370.1  337.49  6705.9  336.16
  6806.4  337.73  7080.9  335.18  7861.6  338.18  8072.6  335.58    8390  337.71
#Mann= 6 ,-1 , 0
    3174      .1       0  4832.7     .12       0  4981.1     .07       0
  5011.1     .12       0  5195.7      .1       0  5552.6     .05       0
Bank Sta=4981.1,5011.1
XS Rating Curve= 0 ,0
Exp/Cntr=0.3,0.1

Type RM Length L Ch R = 1 ,24372   ,61,61,61
BEGIN DESCRIPTION:
Mapping XS a1aa3809
END DESCRIPTION:
XS GIS Cut Line= 4
      2081757.57     13434626.62      2081378.34     13432932.35
      2080824.96     13432912.82      2077721.07     13432608.38
#Sta/Elev= 30
  3144.8  355.94  3433.4  345.43    3874  335.99  3935.5  332.58  4027.7   324.5
  4109.7  329.69  4419.8  334.96  4486.3  335.91  4559.6  335.95  4646.1  335.03
  4745.1  330.81  4796.3  331.86  4881.2  327.31  4974.4  318.73  4984.4  313.92
  4989.4  309.95    4994  308.95  5019.4  309.95  5024.4  315.31  5044.4  316.93
  5224.5   319.2  5402.7  330.59  5474.9  334.42  5728.5  336.52  6720.8  337.38
  7162.9  333.08  7705.5  337.06  8087.3  338.19  8258.2  335.23  8553.5  337.28
#Mann= 9 ,-1 , 0
  3144.8      .1       0  4419.8     .08       0  4486.3      .1       0
  4559.6     .05       0  4881.2     .12       0  4989.4     .07       0
  5019.4     .12       0  5402.7      .1       0  5728.5     .05       0
Bank Sta=4989.4,5019.4
XS Rating Curve= 0 ,0
Exp/Cntr=0.3,0.1

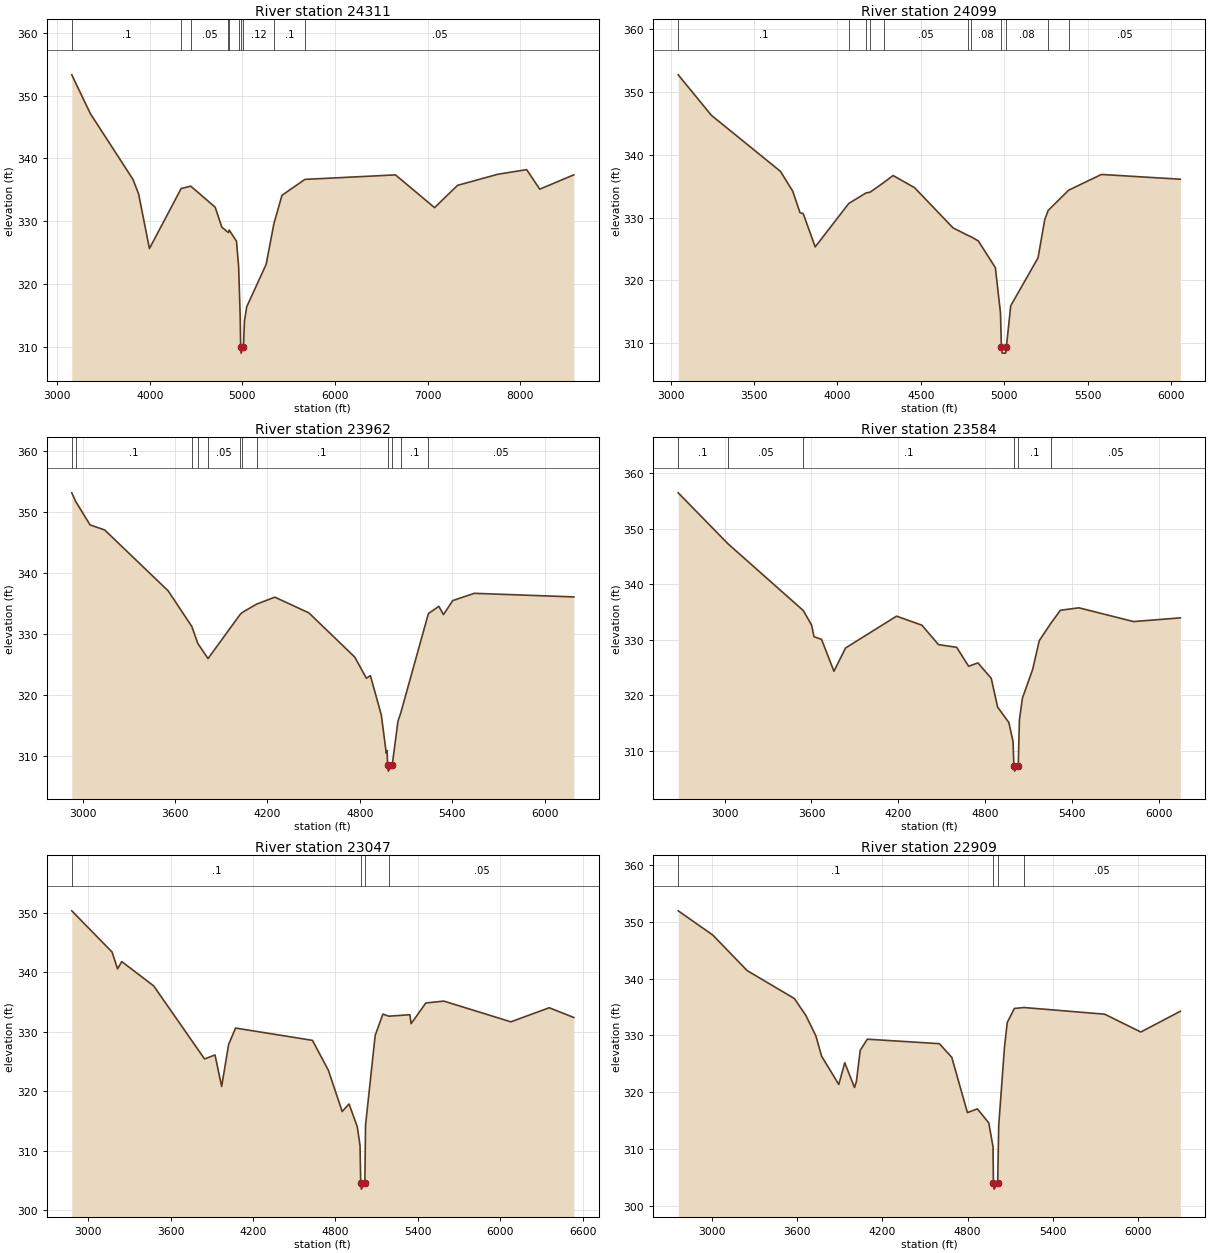
Type RM Length L Ch R = 1 ,24311   ,212,212,212
BEGIN DESCRIPTION:
Mapping XS 0f0ab17a
END DESCRIPTION:
XS GIS Cut Line= 4
      2081855.21     13434518.07      2081374.35     13432876.89
      2080957.34     13432858.57      2077678.08     13432521.86
#Sta/Elev= 30
  3156.8  353.34  3358.2  347.14  3818.6  336.65    3879  334.33  3996.1  325.63
  4338.8  335.21  4442.6  335.58    4706  332.23  4778.1  329.04  4849.3  328.17
  4857.5  328.58  4936.4   326.8  4959.7  322.72  4976.4  314.72  4981.5  309.95
  4986.1  308.95  5011.5  309.95  5022.7   314.1  5046.5  316.33  5256.8  323.11
  5340.2  329.57  5427.5  334.12  5675.6  336.66  6653.9  337.38  7076.1  332.16
  7324.4  335.71  7759.7  337.48  8071.3  338.22  8212.3   335.1  8580.9  337.39
#Mann= 10 ,-1 , 0
  3156.8      .1       0  4338.8     .08       0  4442.6     .05       0
  4849.3     .12       0  4857.5      .1       0  4959.7     .12       0
  4981.5     .07       0  5011.5     .12       0  5340.2      .1       0
  5675.6     .05       0
Bank Sta=4981.5,5011.5
XS Rating Curve= 0 ,0
Exp/Cntr=0.3,0.1

Type RM Length L Ch R = 1 ,24099   ,137,137,137
BEGIN DESCRIPTION:
Mapping XS 0272bcd3
END DESCRIPTION:
XS GIS Cut Line= 4
      2081910.46     13434459.17      2081345.79     13432687.13
      2081048.48     13432622.02      2080202.12     13432631.03
#Sta/Elev= 30
  3045.5  352.77  3244.3  346.32  3658.6  337.38  3732.1  334.22  3775.5   330.8
  3795.1  330.64  3866.8  325.34  4068.2  332.27  4172.8  333.96  4195.1  334.05
  4277.3  335.59  4333.6  336.72  4462.4  334.79  4693.1  328.38  4785.5  327.14
  4800.2  326.98  4844.6   326.3  4947.1  322.04  4977.8  314.83  4983.3  309.41
  4987.9  308.41  5008.7  308.41  5013.3  309.41  5039.2  315.96    5203   323.6
  5243.2  329.69  5263.6  331.15  5386.9  334.39  5583.2  336.89  6056.1  336.13
#Mann= 11 ,-1 , 0
  3045.5      .1       0  4068.2     .08       0  4172.8     .05       0
  4195.1     .08       0  4277.3     .05       0  4785.5      .1       0
  4800.2     .08       0  4983.3     .07       0  5013.3     .08       0
  5263.6      .1       0  5386.9     .05       0
Bank Sta=4983.3,5013.3
XS Rating Curve= 0 ,0
Exp/Cntr=0.3,0.1

Type RM Length L Ch R = 1 ,23962   ,378,378,378
BEGIN DESCRIPTION:
Mapping XS 1473a25d
END DESCRIPTION:
XS GIS Cut Line= 5
      2082004.21     13434427.94      2081432.03     13432684.02
      2081400.78     13432579.85      2081124.73     13432493.91
      2080100.02       13432550.
#Sta/Elev= 30
  2930.2  353.16  2956.1  351.73  3049.1  347.89  3143.8  347.06  3556.3  337.05
  3709.9  331.19  3748.3  328.43  3814.8  325.93  4021.9  333.13  4036.6   333.5
  4129.5  334.87  4248.9  336.02  4469.9  333.43  4767.7  326.17  4842.6   322.7
    4869  323.13  4939.6  316.68  4972.1  310.37  4977.3  310.82  4980.6  308.44
  4985.2  307.44  5010.6  308.44    5048  315.65  5065.5  316.96  5245.6  333.33
  5313.4  334.51  5343.5  333.15  5403.5  335.46  5543.8  336.65  6189.7  336.06
#Mann= 12 ,-1 , 0
  2930.2     .05       0  2956.1      .1       0  3709.9     .08       0
  3748.3      .1       0  3814.8     .05       0  4021.9      .1       0
  4036.6     .05       0  4129.5      .1       0  4980.6     .07       0
  5010.6      .1       0  5065.5      .1       0  5245.6     .05       0
Bank Sta=4980.6,5010.6
XS Rating Curve= 0 ,0
Exp/Cntr=0.3,0.1

Type RM Length L Ch R = 1 ,23584   ,537,537,537
BEGIN DESCRIPTION:
Mapping XS e0dd33cc
END DESCRIPTION:
XS GIS Cut Line= 4
      2082189.97     13434509.51      2081655.98     13432535.58
      2081408.59     13432199.64      2080471.18     13431844.56
#Sta/Elev= 30
  2680.6  356.47  3023.6  347.29  3543.6  335.24  3600.8  332.62  3617.6  330.53
  3669.4  330.04  3755.1  324.29  3835.2  328.49  4187.4  334.23  4361.9   332.6
  4476.3   329.1  4601.8  328.61  4684.6  325.19  4748.6   325.8  4840.5  323.02
  4884.4  317.83  4962.2  315.04  4990.9   311.6  4996.8  307.28  5001.4  306.28
  5026.8  307.28  5034.8   315.5  5055.7  319.45  5126.6  324.65  5171.6   329.8
    5251  332.91  5317.6  335.29  5445.9  335.73  5822.4  333.25  6145.1  333.92
#Mann= 6 ,-1 , 0
  2680.6      .1       0  3023.6     .05       0  3543.6      .1       0
  4996.8     .07       0  5026.8      .1       0    5251     .05       0
Bank Sta=4996.8,5026.8
XS Rating Curve= 0 ,0
Exp/Cntr=0.3,0.1

Type RM Length L Ch R = 1 ,23047   ,138,138,138
BEGIN DESCRIPTION:
Mapping XS d37f9b1e
END DESCRIPTION:
XS GIS Cut Line= 4
      2082216.01     13434275.17      2081963.28     13432493.91
       2081976.3     13432027.77      2080689.11     13431506.39
#Sta/Elev= 30
  2881.4  350.38  3174.5  343.45  3214.9  340.61  3245.2  341.84  3477.5  337.74
  3847.9  325.44  3923.9  326.11  3972.4  320.81  4022.9  327.87  4073.4  330.64
  4633.3  328.57  4749.4  323.51  4849.5  316.59  4899.5  317.86  4959.5  314.02
  4979.5  310.85  4984.5  304.52  4989.1  303.52  5014.5  304.52  5019.5  314.28
  5089.6  329.39  5145.7  332.99  5189.4  332.64  5342.4  332.89  5350.9  331.37
  5458.1  334.86  5589.4  335.18  6077.3  331.69  6356.6  334.06  6535.6  332.42
#Mann= 4 ,-1 , 0
  2881.4      .1       0  4984.5     .07       0  5014.5      .1       0
  5189.4     .05       0
Bank Sta=4984.5,5014.5
XS Rating Curve= 0 ,0
Exp/Cntr=0.3,0.1

Type RM Length L Ch R = 1 ,22909   ,847,847,847
BEGIN DESCRIPTION:
Mapping XS 41e2e6b0
END DESCRIPTION:
XS GIS Cut Line= 4
      2082320.18      13434396.7      2082093.48     13432519.95
      2082116.92     13432030.37      2081279.28     13431237.67
#Sta/Elev= 30
  2763.8  351.93  3007.3  347.66    3249  341.41  3581.4  336.49    3662  333.52
  3732.5  329.93  3772.8  326.35  3893.7  321.37  3935.9  325.19  4004.5  320.84
  4017.8  321.88  4044.7  327.38  4094.8  329.34  4601.8  328.55  4689.2  326.14
  4799.3  316.42  4869.4  317.07  4949.5  314.61  4979.5  310.38  4982.1  303.95
  4986.7  302.95  5012.1  303.95  5019.6  314.19  5059.6   327.8  5079.6  332.28
  5129.7  334.75  5197.8  334.91  5765.1  333.74  6019.5   330.6  6297.6  334.25
#Mann= 4 ,-1 , 0
  2763.8      .1       0  4982.1     .07       0  5012.1      .1       0
  5197.8     .05       0
Bank Sta=4982.1,5012.1
XS Rating Curve= 0 ,0
Exp/Cntr=0.3,0.1

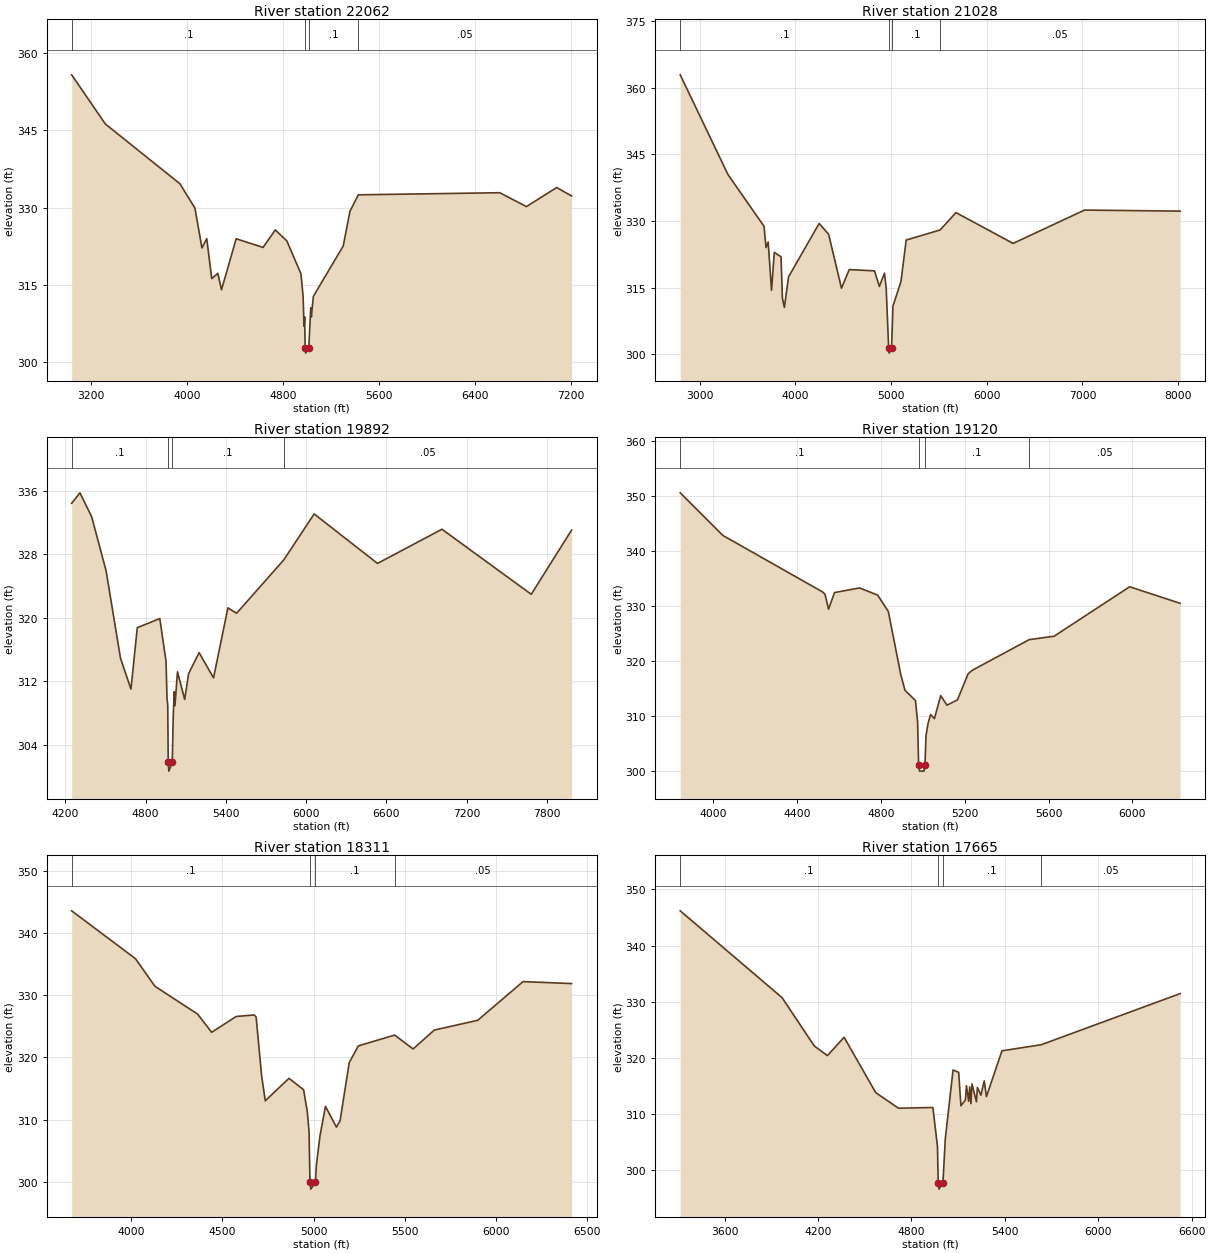
Type RM Length L Ch R = 1 ,22062   ,1034,1034,1034
BEGIN DESCRIPTION:
Mapping XS b21f1051
END DESCRIPTION:
XS GIS Cut Line= 4
      2082424.33      13434570.3      2082756.68      13432861.1
      2082346.22     13431723.05      2081356.69     13431019.96
#Sta/Elev= 30
  3039.2  355.83  3319.7  346.27  3941.1  334.64  4066.4  329.89  4124.5  322.14
  4164.6  323.96    4206  316.19  4256.9   317.2  4287.5     314  4409.7  323.93
  4633.8  322.25  4735.7  325.65  4832.2  323.51  4949.6   317.1  4967.6  312.64
  4974.9  306.91  4980.3  308.71  4984.5  302.68  4989.1  301.68  5014.5  302.68
    5031  310.49  5036.3  308.71  5052.7  312.72  5301.8  322.54  5357.9  329.28
  5427.5  332.48  6605.5  332.89  6828.1  330.19  7080.3   333.9  7204.1  332.26
#Mann= 4 ,-1 , 0
  3039.2      .1       0  4984.5     .07       0  5014.5      .1       0
  5427.5     .05       0
Bank Sta=4984.5,5014.5
XS Rating Curve= 0 ,0
Exp/Cntr=0.3,0.1

Type RM Length L Ch R = 1 ,21028   ,1136,1136,1136
BEGIN DESCRIPTION:
Mapping XS 77ff019b
END DESCRIPTION:
XS GIS Cut Line= 4
      2082771.57     13434882.76      2083693.88     13433733.14
      2083474.69     13432486.94      2081556.29     13430907.08
#Sta/Elev= 30
  2796.5   362.9  3294.7  340.47  3672.4  328.78  3693.2  323.99  3715.6  325.24
  3750.8  314.36  3779.6   322.9    3850  321.92  3864.4  312.62  3885.2  310.51
  3928.4  317.39  4248.5  329.43  4347.6  326.98  4481.7  314.84  4562.9  319.04
  4826.9  318.75  4877.7  315.24  4930.7  318.23  4948.8  314.95  4974.9  301.32
  4979.4  300.22  5005.1  301.32  5019.8  310.81  5103.5  316.37  5157.8  325.68
  5512.9  327.96  5678.4  331.87  6275.2  324.93  7021.9  332.44  8020.9   332.2
#Mann= 4 ,-1 , 0
  2796.5      .1       0  4974.9     .07       0  5005.1      .1       0
  5512.9     .05       0
Bank Sta=4974.9,5005.1
XS Rating Curve= 0 ,0
Exp/Cntr=0.3,0.1

Type RM Length L Ch R = 1 ,19892   ,772,772,772
BEGIN DESCRIPTION:
Mapping XS f9b99265
END DESCRIPTION:
XS GIS Cut Line= 5
      2085078.42     13432967.05      2085056.73     13432912.82
      2083780.69     13432405.01      2083055.69      13431949.9
      2082809.43     13430519.32
#Sta/Elev= 30
  4246.4  334.41  4308.4  335.73  4395.9  332.72  4503.8  325.92  4611.7  314.89
  4689.9  310.99  4737.2  318.73  4905.7  319.88  4952.4  314.48  4959.7  309.76
    4965  309.03  4968.8  301.75  4973.4  300.65    4999  301.75  5006.2  307.66
  5013.6  310.66    5019  308.88  5037.9  313.17  5091.8  309.69  5121.5  312.95
  5199.8  315.59  5307.6   312.4  5415.2  321.23  5480.3  320.55  5833.3  327.28
  6060.3  333.07  6534.1  326.83  7016.1  331.14  7684.2  322.94  7985.8  331.03
#Mann= 4 ,-1 , 0
  4246.4      .1       0  4968.8     .07       0    4999      .1       0
  5833.3     .05       0
Bank Sta=4968.8,4999
XS Rating Curve= 0 ,0
Exp/Cntr=0.3,0.1

Type RM Length L Ch R = 1 ,19120   ,809,809,809
BEGIN DESCRIPTION:
Mapping XS 3a49c504
END DESCRIPTION:
XS GIS Cut Line= 4
      2085488.61     13432391.46      2084648.74     13431997.02
      2083386.57     13432059.42      2083217.34     13431968.29
#Sta/Elev= 30
  3843.9  350.59  4046.7  342.85  4521.8  332.57    4534  332.16  4551.2  329.42
  4579.6  332.44  4699.2  333.28  4785.5  331.97  4836.3  328.99  4895.7  317.49
  4915.7  314.65  4965.8  312.78  4975.8  308.86  4980.7  301.04  4985.2  299.94
  5006.3  299.94  5010.9  301.04  5015.8  306.38  5025.8  308.65  5037.7  310.25
  5055.9  309.49  5085.9  313.68  5115.9  311.94    5166  312.92  5216.1  317.61
  5234.1  318.24  5507.8  323.87  5626.6  324.49    5987  333.49  6227.7  330.48
#Mann= 4 ,-1 , 0
  3843.9      .1       0  4980.7     .07       0  5010.9      .1       0
  5507.8     .05       0
Bank Sta=4980.7,5010.9
XS Rating Curve= 0 ,0
Exp/Cntr=0.3,0.1

Type RM Length L Ch R = 1 ,18311   ,646,646,646
BEGIN DESCRIPTION:
Mapping XS 1c68b63d
END DESCRIPTION:
XS GIS Cut Line= 4
      2085453.87     13431931.39      2084765.93     13431261.35
      2083737.28     13431296.07      2083275.02       13431888.
#Sta/Elev= 30
  3673.5  343.59  4023.7  335.88  4129.9  331.45  4363.2  326.99  4440.9  324.04
  4575.4  326.59  4674.8  326.83  4684.8  326.49  4714.8  317.07  4734.8  313.02
  4864.9  316.63  4944.9   314.8  4964.9  311.33  4974.9  308.09  4979.9   299.9
  4984.4   298.8  5010.1   299.9    5015  302.66    5035  307.41    5065  312.11
    5125  308.78    5145   309.8  5195.1  319.15  5245.1  321.85  5444.2  323.59
  5545.3  321.36  5661.7   324.4  5899.4  325.97  6148.1   332.2  6414.1  331.88
#Mann= 4 ,-1 , 0
  3673.5      .1       0  4979.9     .07       0  5010.1      .1       0
  5444.2     .05       0
Bank Sta=4979.9,5010.1
XS Rating Curve= 0 ,0
Exp/Cntr=0.3,0.1

Type RM Length L Ch R = 1 ,17665   ,221,221,221
BEGIN DESCRIPTION:
Mapping XS 34fec8b8
END DESCRIPTION:
XS GIS Cut Line= 5
       2085575.4     13431827.23      2084759.42     13431141.99
      2084505.51     13430727.49      2084275.48     13430736.17
      2083144.92     13431610.13
#Sta/Elev= 30
  3315.6  346.17    3970  330.72  4176.8  322.13  4261.4  320.42    4368  323.68
  4571.3  313.83  4717.7  311.06  4938.3  311.19  4967.8  304.26  4972.7  297.77
  4977.3  296.67  5002.9  297.77  5017.8  305.52  5067.9  317.86    5104  317.44
  5118.5   311.5  5147.5  312.54  5153.8  315.07  5168.3   312.3  5174.6  314.84
  5182.8  311.88  5189.1  315.39  5218.1  312.21  5224.4  314.74  5247.1  313.39
  5267.9  315.92  5282.4  313.13    5382  321.27  5635.2  322.36  6526.4  331.45
#Mann= 4 ,-1 , 0
  3315.6      .1       0  4972.7     .07       0  5002.9      .1       0
  5635.2     .05       0
Bank Sta=4972.7,5002.9
XS Rating Curve= 0 ,0
Exp/Cntr=0.3,0.1