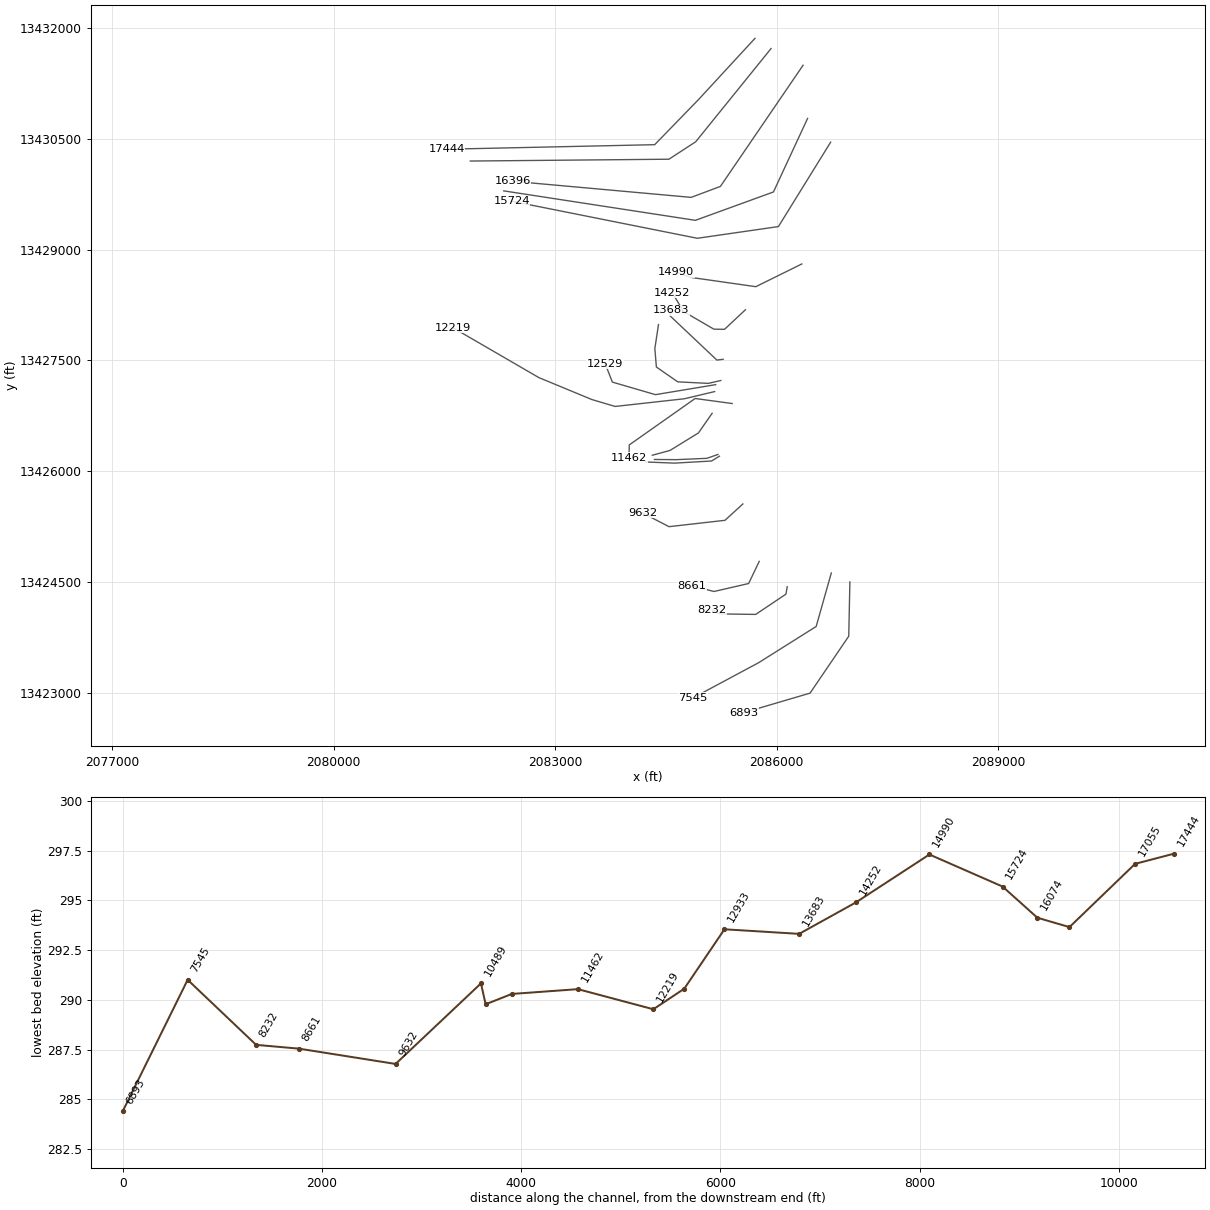
HEC-RAS study LAGUNILLAS Cr.prj: LAGUNILLAS Cr Base Level Engineering

--- LAGUNILLAS Cr.g01 (geometry) --- (continued)

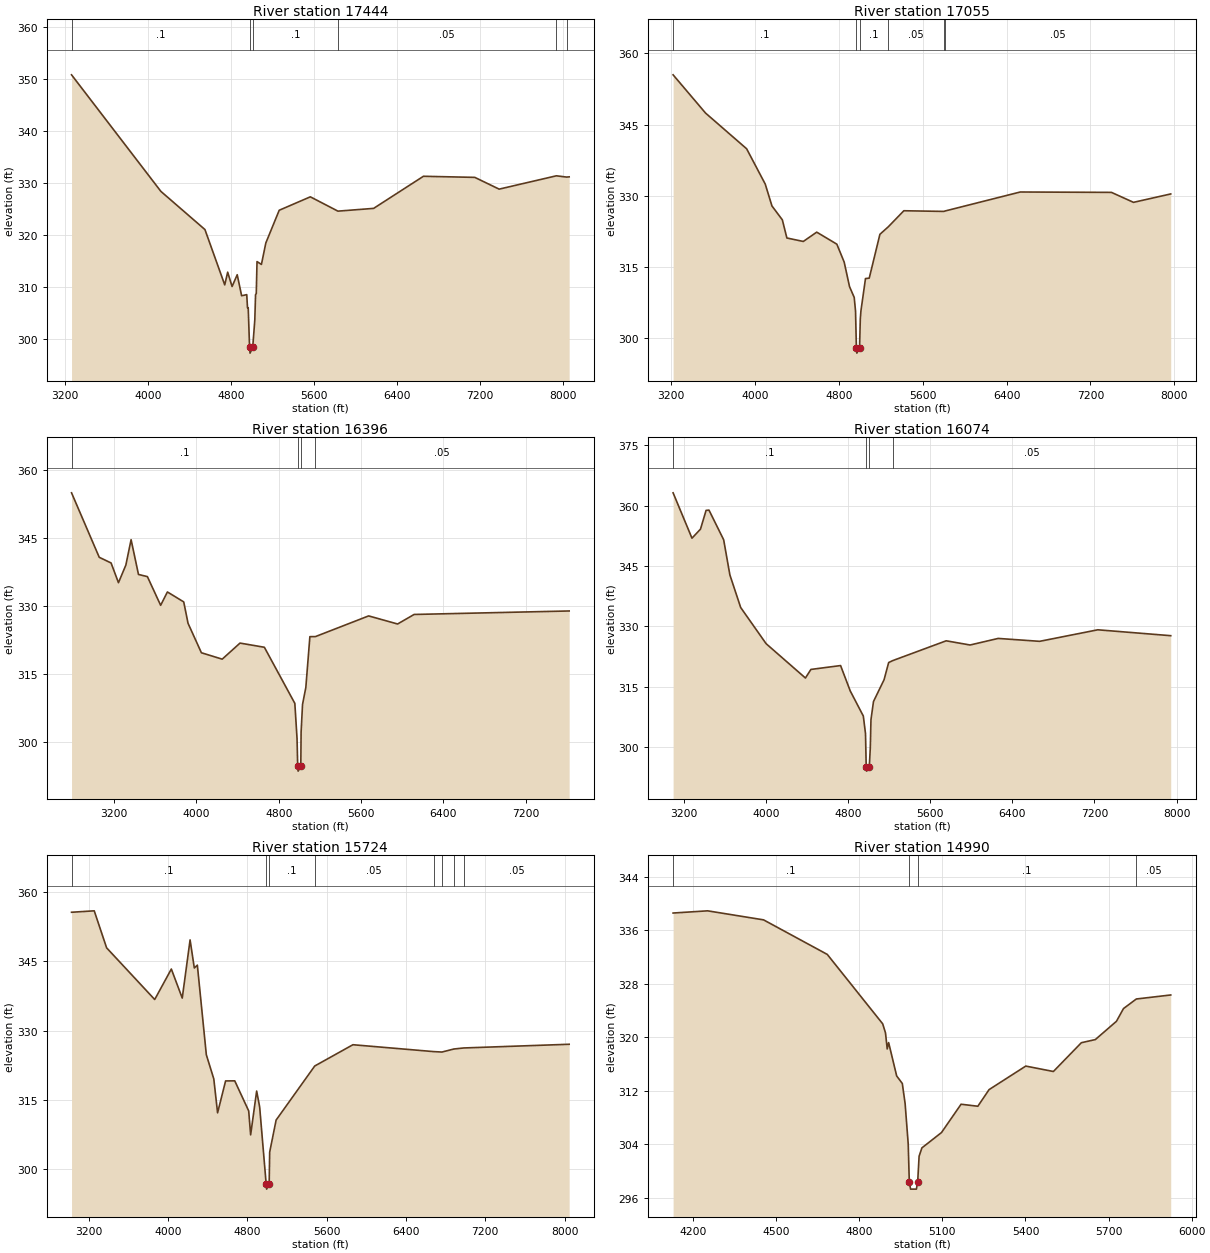
Type RM Length L Ch R = 1 ,17444   ,389,389,389
BEGIN DESCRIPTION:
Mapping XS e3ab2212
END DESCRIPTION:
XS GIS Cut Line= 4
      2085705.58     13431861.92      2084939.54     13431031.31
      2084347.09      13430421.5      2081530.29      13430360.2
#Sta/Elev= 30
  3265.1  350.84  4126.8  328.43  4551.2   321.1  4742.1  310.47  4770.4  312.91
  4812.8  310.15  4862.4  312.42  4904.9  308.38  4954.3  308.59  4961.5  306.05
  4968.4  306.07  4981.6  298.45  4986.2  297.35  5011.8  298.45    5032  303.73
  5039.2   308.6  5046.1  308.79  5053.3  314.94  5095.8   314.4  5138.2  318.52
  5267.3  324.81  5567.4  327.39  5833.5  324.64  6177.5  325.17  6657.7  331.34
  7152.8  331.13  7387.8  328.87  7939.2  331.43  8037.4  331.19  8062.7  331.23
#Mann= 6 ,-1 , 0
  3265.1      .1       0  4981.6     .07       0  5011.8      .1       0
  5833.5     .05       0  7939.2     .08       0  8037.4     .05       0
Bank Sta=4981.6,5011.8
XS Rating Curve= 0 ,0
Exp/Cntr=0.3,0.1

Type RM Length L Ch R = 1 ,17055   ,659,659,659
BEGIN DESCRIPTION:
Mapping XS 032d3e78
END DESCRIPTION:
XS GIS Cut Line= 4
      2085922.62     13431723.07      2084902.79     13430461.23
      2084539.95     13430224.68      2081850.03       13430200.
#Sta/Elev= 30
    3220  355.48  3529.5  347.42  3921.2   339.9  4098.7  332.46  4162.7  327.85
  4261.8  324.92    4305   321.1  4461.7  320.37  4589.6  322.33  4781.5   319.8
  4851.7  316.01  4902.5  310.85  4947.2  308.58  4959.8  305.69  4967.9  297.94
  4972.5  296.84  4998.1  297.94  5005.2  304.02  5011.2  305.73  5054.7  312.55
  5090.5  312.64  5192.3  321.88  5272.8  323.47  5420.5  326.84  5801.7   326.7
  5814.2  326.79  6530.6  330.79  7400.6  330.71  7610.6  328.61  7965.6  330.38
#Mann= 6 ,-1 , 0
    3220      .1       0  4967.9     .07       0  4998.1      .1       0
  5272.8     .05       0  5801.7      .1       0  5814.2     .05       0
Bank Sta=4967.9,4998.1
XS Rating Curve= 0 ,0
Exp/Cntr=0.3,0.1

Type RM Length L Ch R = 1 ,16396   ,322,322,322
BEGIN DESCRIPTION:
Mapping XS 8f9e4a16
END DESCRIPTION:
XS GIS Cut Line= 4
      2086356.61     13431497.32        2085237.     13429856.62
      2084840.94     13429707.97      2082424.32     13429926.17
#Sta/Elev= 30
  2786.9     355  3056.1  340.79  3171.1  339.54  3242.9  335.19  3314.7  339.08
  3365.6  344.67  3437.4  337.01  3524.1  336.53  3652.8  330.21  3718.5  333.15
    3877  330.96    3919  326.25  4048.8  319.75    4251  318.34  4424.1  321.88
  4660.8  320.96  4956.9  308.59  4978.3  300.84  4984.6  294.76  4989.1  293.66
  5014.8  294.76  5017.7  302.26  5031.7  308.37  5063.7   312.1  5103.1   323.3
  5156.8  323.31  5674.1  327.87  5955.3  326.09  6115.9  328.19  7622.7  328.96
#Mann= 4 ,-1 , 0
  2786.9      .1       0  4984.6     .07       0  5014.8      .1       0
  5156.8     .05       0
Bank Sta=4984.6,5014.8
XS Rating Curve= 0 ,0
Exp/Cntr=0.3,0.1

Type RM Length L Ch R = 1 ,16074   ,350,350,350
BEGIN DESCRIPTION:
Mapping XS 8d866339
END DESCRIPTION:
XS GIS Cut Line= 4
       2086417.4     13430776.88      2085955.17     13429781.31
      2084898.31      13429397.2       2082302.8     13429795.97
#Sta/Elev= 30
  3095.5  363.15  3279.4   351.9  3362.2  354.14  3416.8   358.8  3445.2  358.86
  3588.1  351.51  3648.8  342.78  3753.9  334.71  4001.6  325.74  4384.8  317.22
    4438  319.35  4727.3  320.31  4821.1  314.03  4948.8  307.79    4970  303.43
  4976.9  295.23  4981.5  294.13  5007.1  295.23  5016.7  299.92  5023.2  306.88
  5047.9   311.4  5150.9   316.8  5195.6  321.06  5234.4  321.53    5756  326.45
  5988.7  325.41  6262.5  327.04  6666.6  326.32  7233.2  329.18  7943.6  327.72
#Mann= 4 ,-1 , 0
  3095.5      .1       0  4976.9     .07       0  5007.1      .1       0
  5234.4     .05       0
Bank Sta=4976.9,5007.1
XS Rating Curve= 0 ,0
Exp/Cntr=0.3,0.1

Type RM Length L Ch R = 1 ,15724   ,734,734,734
BEGIN DESCRIPTION:
Mapping XS 9d18960c
END DESCRIPTION:
XS GIS Cut Line= 4
      2086729.91     13430455.71      2086022.44     13429312.56
      2084924.35     13429154.14      2082408.49     13429656.77
#Sta/Elev= 30
  3026.7  355.58  3255.7  355.89  3380.3  347.89  3865.5  336.71  4033.3   343.3
  4143.3  337.02  4222.4   349.6    4265  343.53  4295.7  344.14  4386.3  324.76
  4461.7  319.53  4499.8   312.2  4580.6   319.1  4672.9  319.12  4813.6  312.62
  4833.2  307.44  4893.9  316.91  4924.2  313.48  4989.9   296.8  4994.4   295.7
  5020.1   296.8  5025.2  303.69  5090.1  310.63  5479.7  322.33    5865  326.93
  6680.5  325.44  6763.3  325.35  6882.2     326  6983.1  326.23  8046.1  327.03
#Mann= 8 ,-1 , 0
  3026.7      .1       0  4989.9     .07       0  5020.1      .1       0
  5479.7     .05       0  6680.5     .08       0  6763.3     .05       0
  6882.2     .08       0  6983.1     .05       0
Bank Sta=4989.9,5020.1
XS Rating Curve= 0 ,0
Exp/Cntr=0.3,0.1

Type RM Length L Ch R = 1 ,14990   ,738,738,738
BEGIN DESCRIPTION:
Mapping XS b2b1495c
END DESCRIPTION:
XS GIS Cut Line= 4
      2086339.29     13428806.39      2085716.45     13428498.76
      2084836.36     13428624.42      2084636.13     13428696.52
#Sta/Elev= 30
  4127.9  338.55  4252.5  338.88  4454.5  337.53  4684.5  332.37  4884.6     322
  4894.7  320.64  4900.9  318.25    4906   319.2  4935.1  314.21  4955.4  313.09
  4965.5  310.09  4976.7  304.06  4980.6  298.41  4985.2  297.31  5006.3  297.31
  5010.9  298.41    5016  302.22  5026.1  303.47  5096.8  305.76  5167.5  309.99
  5228.1  309.69  5268.5  312.17  5401.1  315.69  5500.8  314.88  5601.8  319.18
  5652.3  319.65  5728.5  322.38  5753.9  324.28  5800.2  325.71  5924.4  326.31
#Mann= 4 ,-1 , 0
  4127.9      .1       0  4980.6     .07       0  5010.9      .1       0
  5800.2     .05       0
Bank Sta=4980.6,5010.9
XS Rating Curve= 0 ,0
Exp/Cntr=0.3,0.1

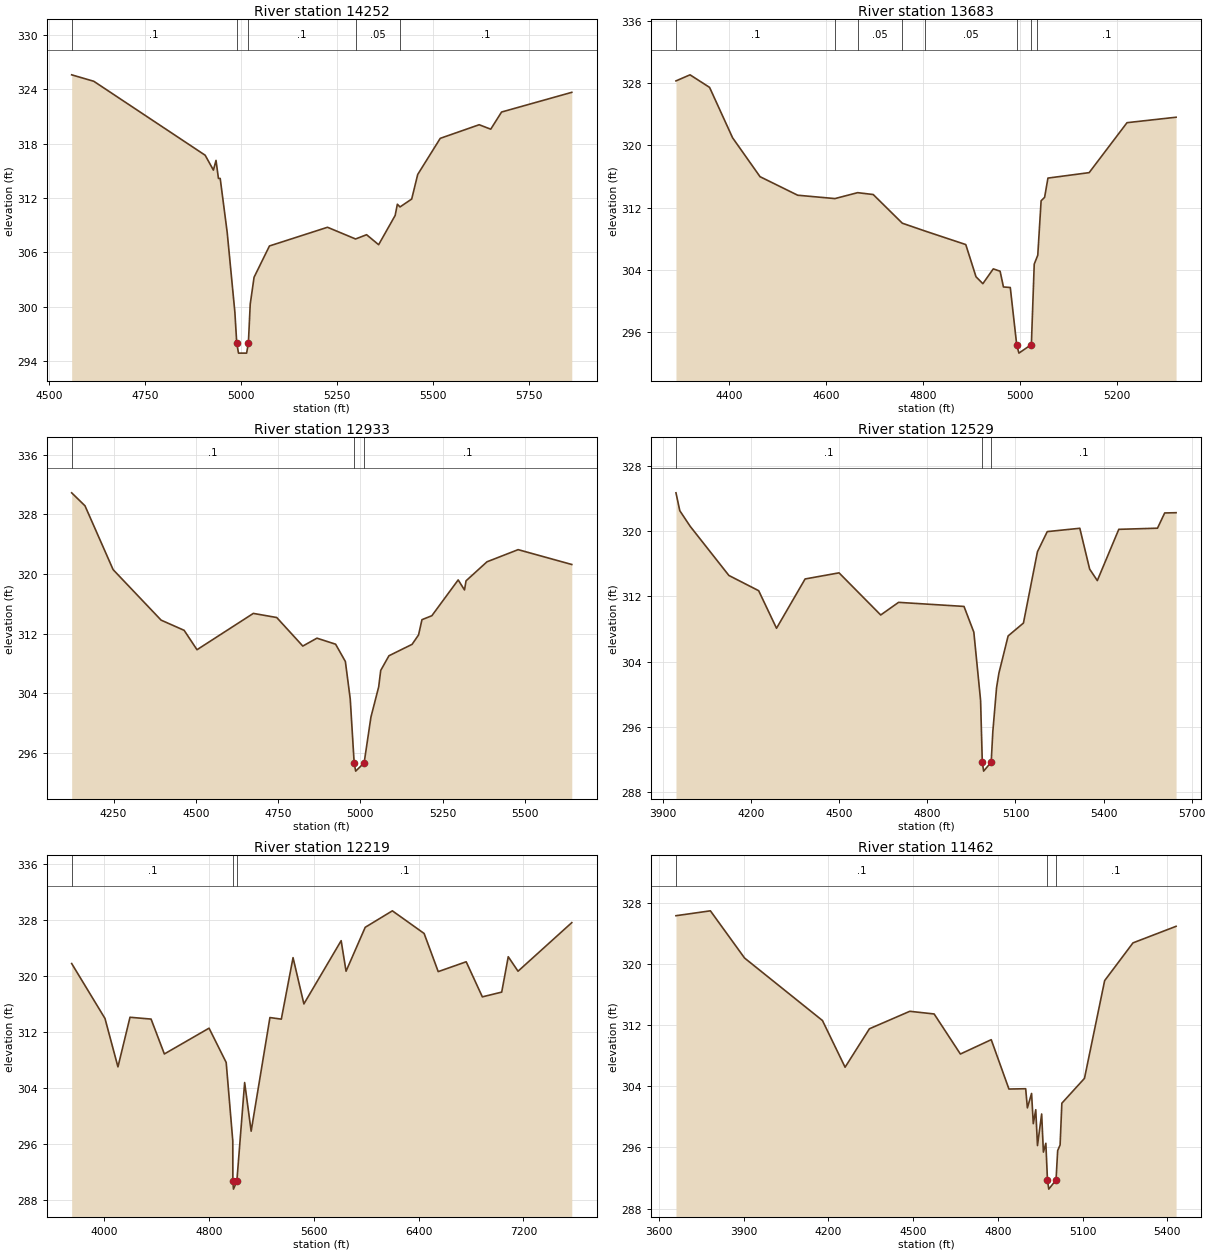
Type RM Length L Ch R = 1 ,14252   ,569,569,569
BEGIN DESCRIPTION:
Mapping XS 1ad6f37a
END DESCRIPTION:
XS GIS Cut Line= 5
      2085575.37     13428186.24      2085293.27      13427921.5
      2085147.87     13427923.67      2084737.72     13428162.39
      2084585.21     13428415.91
#Sta/Elev= 30
  4559.1  325.57  4616.7  324.86  4906.8  316.71  4928.3  315.07  4935.1  316.14
  4941.4  314.15    4946  314.15  4964.2  308.21  4984.2  299.42  4989.1     296
  4993.7   294.9  5014.8   294.9  5019.4     296  5024.2  300.29  5034.2  303.26
  5074.3  306.71  5225.5  308.77  5298.6  307.48  5327.3  307.95  5358.7  306.85
  5401.7  310.07  5407.5  311.31  5414.4  311.01  5444.8  311.88  5460.5  314.59
  5519.2  318.57  5620.6  320.07  5650.7  319.58  5678.9  321.47  5861.8  323.64
#Mann= 5 ,-1 , 0
  4559.1      .1       0  4989.1     .07       0  5019.4      .1       0
  5298.6     .05       0  5414.4      .1       0
Bank Sta=4989.1,5019.4
XS Rating Curve= 0 ,0
Exp/Cntr=0.3,0.1

Type RM Length L Ch R = 1 ,13683   ,750,750,750
BEGIN DESCRIPTION:
Mapping XS 22561042
END DESCRIPTION:
XS GIS Cut Line= 4
      2085273.76     13427515.69      2085189.11     13427504.84
      2084555.43      13428103.8      2084564.11     13428177.59
#Sta/Elev= 30
  4290.1  328.25  4319.1  329.03  4359.4  327.42  4406.9  320.95  4463.5  315.96
  4541.2  313.58    4618  313.15  4664.9  313.91    4697  313.67    4757  309.99
  4804.2  308.98  4887.9  307.25    4909  303.12  4923.1  302.23  4944.6  304.13
  4958.7  303.83  4965.6  301.81  4979.7  301.74  4992.9  294.42  4997.5  293.32
  5023.2  294.42  5029.1  304.74  5035.1  305.68  5036.4  305.88  5043.3  312.87
  5050.5  313.31  5057.4  315.78  5142.4  316.48  5220.5  322.89  5321.7  323.59
#Mann= 8 ,-1 , 0
  4290.1      .1       0    4618     .08       0  4664.9     .05       0
    4757      .1       0  4804.2     .05       0  4992.9     .04       0
  5023.2     .05       0  5035.1      .1       0
Bank Sta=4992.9,5023.2
XS Rating Curve= 0 ,0
Exp/Cntr=0.3,0.1

Type RM Length L Ch R = 1 ,12933   ,404,404,404
BEGIN DESCRIPTION:
Mapping XS c1b2dede
END DESCRIPTION:
XS GIS Cut Line= 6
      2085242.27     13427228.45      2085073.01     13427189.39
      2084658.95     13427210.22      2084369.89     13427410.74
      2084349.05     13427660.74      2084398.53     13427986.24
#Sta/Elev= 30
  4122.5  330.87    4163  329.13  4248.5  320.57  4394.3   313.8  4464.4  312.43
  4503.5  309.83  4674.7   314.7  4745.8  314.15  4825.1  310.32    4868  311.38
  4924.8  310.57  4954.5  308.25  4969.3  303.22  4981.2  294.65  4985.8  293.55
  5011.5  294.65  5032.2   300.8  5055.8  304.86  5061.9  307.05  5086.9  309.02
  5157.2  310.55  5176.9  311.81  5187.3  313.86  5217.4  314.39  5297.4  319.19
  5316.6  317.85  5321.3  319.07  5384.9  321.62  5479.6  323.25  5642.7  321.26
#Mann= 3 ,-1 , 0
  4122.5      .1       0  4981.2     .07       0  5011.5      .1       0
Bank Sta=4981.2,5011.5
XS Rating Curve= 0 ,0
Exp/Cntr=0.3,0.1

Type RM Length L Ch R = 1 ,12529   ,310,310,310
BEGIN DESCRIPTION:
Mapping XS 83a0833f
END DESCRIPTION:
XS GIS Cut Line= 4
      2085172.76     13427172.15      2084356.79     13427036.73
      2083773.46     13427206.87      2083676.24     13427456.86
#Sta/Elev= 30
    3944  324.71    3957  322.52  3992.4   320.6  4124.2  314.57  4225.6   312.7
  4286.4  308.09  4383.7  314.14  4499.3  314.89  4641.2  309.72    4702  311.27
  4924.8  310.77  4958.3  307.61  4981.3  299.24  4987.1  291.66  4991.7  290.56
  5017.4  291.66    5023  295.42  5035.7  300.81  5043.8   302.6  5075.1  307.15
  5127.2  308.73  5174.9  317.48  5208.3  319.95  5319.2  320.36  5352.7  315.35
  5378.8  313.94  5451.9  320.23  5583.7  320.37  5608.2  322.24    5647  322.27
#Mann= 3 ,-1 , 0
    3944      .1       0  4987.1     .07       0  5017.4      .1       0
Bank Sta=4987.1,5017.4
XS Rating Curve= 0 ,0
Exp/Cntr=0.3,0.1

Type RM Length L Ch R = 1 ,12219   ,757,757,757
BEGIN DESCRIPTION:
Mapping XS f3498549
END DESCRIPTION:
XS GIS Cut Line= 6
      2085158.83     13427078.38      2084749.15     13426981.17
      2083811.65     13426877.01      2083495.68     13426970.76
      2082778.93     13427267.32      2081612.26      13427944.4
#Sta/Elev= 30
  3750.7  321.81    4005  313.95  4104.1  307.02  4196.1  314.12    4357  313.86
  4458.4  308.87  4799.7  312.56  4930.5  307.65  4980.9  296.43  4981.5  290.63
  4986.1  289.53  5011.8  290.63  5071.4  304.78  5121.1  297.82  5264.5  314.08
  5351.4  313.85    5441  322.65  5523.8  316.03  5808.3  325.08  5845.8  320.71
  5991.9  326.99  6199.3  329.35  6441.8  326.11  6549.4  320.65    6763  322.06
  6886.4  317.04  7034.2  317.72  7084.2  322.78  7158.8  320.71  7569.2  327.66
#Mann= 3 ,-1 , 0
  3750.7      .1       0  4981.5     .07       0  5011.8      .1       0
Bank Sta=4981.5,5011.8
XS Rating Curve= 0 ,0
Exp/Cntr=0.3,0.1

Type RM Length L Ch R = 1 ,11462   ,663,663,663
BEGIN DESCRIPTION:
Mapping XS a7a2ad19
END DESCRIPTION:
XS GIS Cut Line= 4
      2085395.79     13426916.66      2084894.99     13426984.65
      2084002.63     13426356.17      2083999.15     13426182.57
#Sta/Elev= 30
  3660.8  326.38  3782.7  327.02  3903.7  320.83  4179.4  312.64  4259.5  306.52
  4345.7  311.56  4488.6  313.85  4574.8   313.5  4667.7  308.25  4776.9  310.13
  4839.6  303.66  4898.8   303.7  4904.9  301.19  4919.7  303.08  4925.8  299.12
  4934.5  300.95  4940.6  296.25  4955.4  300.39  4961.6  295.39  4970.2  296.55
    4976  291.74  4980.6  290.54  5006.3  291.74  5012.1  295.59  5020.7  296.33
  5026.9   301.8    5107  305.06  5178.4  317.87  5278.8  322.82  5431.3  324.99
#Mann= 3 ,-1 , 0
  3660.8      .1       0    4976     .07       0  5006.3      .1       0
Bank Sta=4976,5006.3
XS Rating Curve= 0 ,0
Exp/Cntr=0.3,0.1

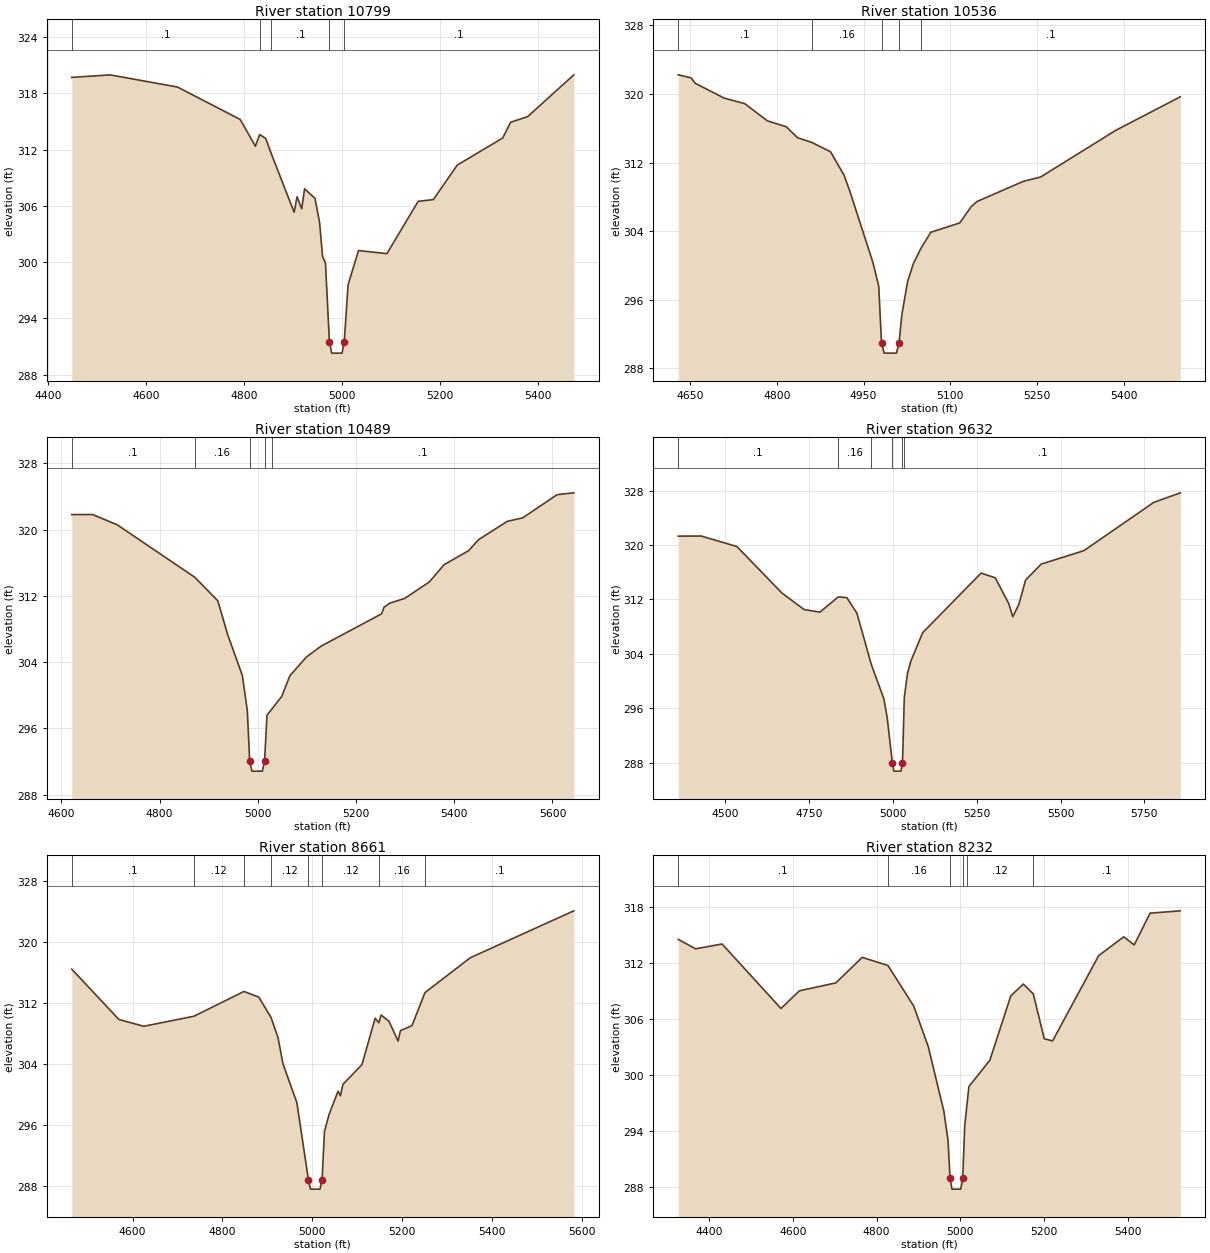
Type RM Length L Ch R = 1 ,10799   ,263,263,263
BEGIN DESCRIPTION:
Mapping XS 653aa457
END DESCRIPTION:
XS GIS Cut Line= 4
      2085124.97     13426784.61      2084939.79     13426518.44
      2084554.38     13426281.47      2084314.75     13426216.35
#Sta/Elev= 30
  4448.3  319.71    4527  319.97  4664.1  318.68  4792.2  315.22  4823.1  312.37
    4832  313.61  4844.3  313.19  4855.6  311.57  4902.3  305.32  4908.2  306.98
  4917.7  305.69  4923.6  307.83  4944.9   306.8  4954.3   304.2  4960.3   300.6
  4966.2  299.92  4974.3   291.5  4978.9   290.3  5000.1   290.3  5004.6   291.5
  5012.4   297.6  5033.7  301.24  5091.7  300.91  5155.5  306.49  5186.4  306.67
  5235.2  310.35    5328  313.24  5344.2  314.92  5378.9  315.52  5473.3  319.98
#Mann= 5 ,-1 , 0
  4448.3      .1       0    4832     .16       0  4855.6      .1       0
  4974.3     .07       0  5004.6      .1       0
Bank Sta=4974.3,5004.6
XS Rating Curve= 0 ,0
Exp/Cntr=0.3,0.1

Type RM Length L Ch R = 1 ,10536   ,47,47,47
BEGIN DESCRIPTION:
Mapping XS 0c540df4
END DESCRIPTION:
XS GIS Cut Line= 4
      2085202.81     13426226.78      2085054.38     13426174.69
      2084635.11     13426156.47      2084343.39     13426159.07
#Sta/Elev= 30
  4629.4  322.23  4651.7  321.88  4658.9  321.24  4708.4  319.53  4744.7  318.86
  4783.7  316.86  4816.1  316.18  4836.1  314.89  4860.8  314.34    4893  313.25
  4916.2  310.54  4926.2  308.69  4966.3  300.34  4976.3  297.59  4981.1  290.98
  4985.7  289.78  5006.9  289.78  5011.4  290.98  5016.3  294.23  5026.3  298.14
  5036.3  300.22  5048.6  301.91  5066.3  303.87  5116.4  304.96  5136.4  306.87
  5146.4  307.46  5226.5  309.81  5256.5  310.32  5386.5  315.76  5498.1  319.67
#Mann= 5 ,-1 , 0
  4629.4      .1       0  4860.8     .16       0  4981.1     .07       0
  5011.4     .16       0  5048.6      .1       0
Bank Sta=4981.1,5011.4
XS Rating Curve= 0 ,0
Exp/Cntr=0.3,0.1

Type RM Length L Ch R = 1 ,10489   ,857,857,857
BEGIN DESCRIPTION:
Mapping XS ebd9123b
END DESCRIPTION:
XS GIS Cut Line= 4
      2085223.69     13426203.37      2085116.88     13426138.24
      2084614.27     13426109.59        2084221.     13426125.22
#Sta/Elev= 30
  4621.4  321.82  4663.6  321.83  4713.6   320.6  4871.6  314.26  4918.7  311.41
  4938.7  307.34  4968.7  302.37  4978.8  298.14  4983.6  292.03  4988.2  290.83
  5009.4  290.83  5013.9  292.03  5018.8   297.6  5028.9  298.34  5048.9  299.86
  5065.4  302.35  5098.9  304.61    5129  305.93  5252.1  309.83  5257.2  310.64
  5269.2  311.13  5299.2   311.7  5349.3  313.68  5379.3  315.77  5429.3  317.46
  5449.4  318.79  5508.2  321.01  5539.4  321.43  5609.5  324.23  5643.5  324.45
#Mann= 5 ,-1 , 0
  4621.4      .1       0  4871.6     .16       0  4983.6     .07       0
  5013.9     .16       0  5028.9      .1       0
Bank Sta=4983.6,5013.9
XS Rating Curve= 0 ,0
Exp/Cntr=0.3,0.1

Type RM Length L Ch R = 1 ,9632    ,971,971,971
BEGIN DESCRIPTION:
Mapping XS 1314709f
END DESCRIPTION:
XS GIS Cut Line= 4
      2085540.85     13425556.53      2085298.65     13425335.15
      2084540.83     13425249.22      2084179.44     13425436.41
#Sta/Elev= 30
  4359.3   321.3  4428.2  321.31  4534.3  319.77  4668.7  312.94  4734.8  310.52
  4781.7  310.13  4836.6  312.37  4862.2  312.27  4892.4  309.97  4935.2  302.46
  4972.9  297.38    4983  294.52    4998  287.98  5002.6  286.78  5023.8  286.78
  5028.3  287.98  5033.7  297.58  5043.3  301.17  5053.4  302.96  5088.4  307.11
  5262.7  315.87    5305  315.18  5345.3  311.39  5357.4  309.46  5375.5  311.28
  5395.6  314.85    5442  317.19  5569.3  319.16  5777.8  326.25  5857.1  327.66
#Mann= 6 ,-1 , 0
  4359.3      .1       0  4836.6     .16       0  4935.2     .12       0
    4998     .07       0  5028.3     .12       0  5033.7      .1       0
Bank Sta=4998,5028.3
XS Rating Curve= 0 ,0
Exp/Cntr=0.3,0.1

Type RM Length L Ch R = 1 ,8661    ,429,429,429
BEGIN DESCRIPTION:
Mapping XS 2730a77d
END DESCRIPTION:
XS GIS Cut Line= 4
      2085763.07     13424779.62      2085618.96     13424479.25
      2085150.21     13424371.61       2084855.1     13424446.26
#Sta/Elev= 30
  4464.3  316.44  4569.3  309.83  4624.7  308.94  4736.6  310.26    4848  313.51
    4881  312.77  4908.3  310.08  4923.8  307.45  4934.9  303.98  4965.7  298.93
  4991.6  288.75  4996.1  287.55  5017.3  287.55  5021.9  288.75  5027.2  295.11
  5037.5  297.36  5057.5  300.41  5062.7  299.81  5068.3  301.31  5110.7  303.89
  5140.1  309.99  5148.4   309.4  5153.5  310.42  5170.9   309.6  5191.3     307
  5196.4  308.36  5222.2  309.02  5251.1  313.36  5352.1  317.94  5582.8   324.1
#Mann= 8 ,-1 , 0
  4464.3      .1       0  4736.6     .12       0    4848     .16       0
  4908.3     .12       0  4991.6     .07       0  5021.9     .12       0
  5148.4     .16       0  5251.1      .1       0
Bank Sta=4991.6,5021.9
XS Rating Curve= 0 ,0
Exp/Cntr=0.3,0.1

Type RM Length L Ch R = 1 ,8232    ,687,687,687
BEGIN DESCRIPTION:
Mapping XS 5ae523ed
END DESCRIPTION:
XS GIS Cut Line= 5
      2086141.52     13424436.05      2086124.15     13424335.34
      2085714.43     13424061.04      2085224.85     13424067.98
      2085124.15     13424123.54
#Sta/Elev= 30
  4325.9  314.56  4367.6  313.55  4430.6  314.07  4571.5  307.14  4615.5  309.04
  4702.6  309.89  4765.6  312.63  4827.1  311.76  4888.7   307.4  4923.4  303.05
  4960.6  296.13  4970.6  293.01  4975.5  288.94    4980  287.74  5001.2  287.74
  5005.8  288.94  5010.6  294.56    5015  296.41  5020.6  298.76  5070.6  301.58
  5120.6  308.49  5150.6  309.77  5174.5  308.71  5200.6  303.89  5220.6  303.66
  5330.6  312.81  5390.6  314.84  5415.7  313.97  5453.5  317.38  5525.8  317.63
#Mann= 6 ,-1 , 0
  4325.9      .1       0  4827.1     .16       0  4975.5     .07       0
  5005.8     .16       0    5015     .12       0  5174.5      .1       0
Bank Sta=4975.5,5005.8
XS Rating Curve= 0 ,0
Exp/Cntr=0.3,0.1

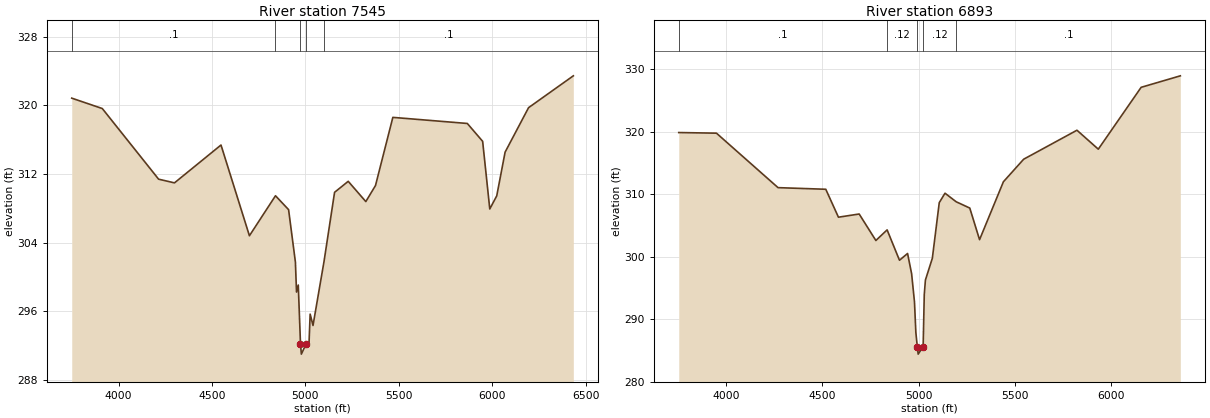
Type RM Length L Ch R = 1 ,7545    ,652,652,652
BEGIN DESCRIPTION:
Mapping XS 0041b575
END DESCRIPTION:
XS GIS Cut Line= 4
      2086738.57     13424622.34      2086533.88     13423897.84
       2085756.1     13423408.26      2084863.89     13422929.81
#Sta/Elev= 30
  3749.4  320.83  3912.9  319.62  4214.3  311.39  4299.2  310.96  4548.2  315.37
  4700.3   304.8  4839.8  309.46  4909.9  307.84  4946.4  301.73  4952.3  298.24
  4961.7  299.06  4973.6  292.21  4978.2  291.01  5003.9  292.21  5019.4  292.39
  5025.3  295.67  5040.6  294.35  5099.5   301.8    5156  309.86    5229  311.14
  5323.2  308.78    5375  310.65  5467.9  318.59  5866.4  317.88  5948.4   315.8
  5986.6  307.92  6023.9  309.45  6068.6  314.54  6194.2  319.72  6433.7  323.43
#Mann= 5 ,-1 , 0
  3749.4      .1       0  4839.8     .12       0  4973.6     .07       0
  5003.9     .12       0  5099.5      .1       0
Bank Sta=4973.6,5003.9
XS Rating Curve= 0 ,0
Exp/Cntr=0.3,0.1

Type RM Length L Ch R = 1 ,6893    ,833,833,833
BEGIN DESCRIPTION:
Mapping XS cc986891
END DESCRIPTION:
XS GIS Cut Line= 4
      2086990.31     13424500.85      2086974.85      13423765.9
      2086450.54     13422995.06      2085549.67     13422730.09
#Sta/Elev= 30
  3753.8  319.87  3949.7  319.77  4269.8  311.05  4517.8  310.79  4583.6  306.32
  4691.3  306.83  4778.1  302.59  4836.5  304.29  4900.8  299.43  4942.8  300.51
  4963.8  297.28  4978.7  292.77  4985.9  287.85  4993.4   285.6    4998   284.4
  5023.7   285.6  5029.6  293.95  5035.6  296.27  5071.5  299.74  5107.5  308.65
  5137.3  310.16  5195.4  308.79  5266.1  307.78  5316.9  302.72  5440.8  311.99
  5546.1   315.6    5823  320.24  5933.9  317.21  6156.6  327.11  6360.2  328.95
#Mann= 5 ,-1 , 0
  3753.8      .1       0  4836.5     .12       0  4993.4     .07       0
  5023.7     .12       0  5195.4      .1       0
Bank Sta=4993.4,5023.7
XS Rating Curve= 0 ,0
Exp/Cntr=0.3,0.1