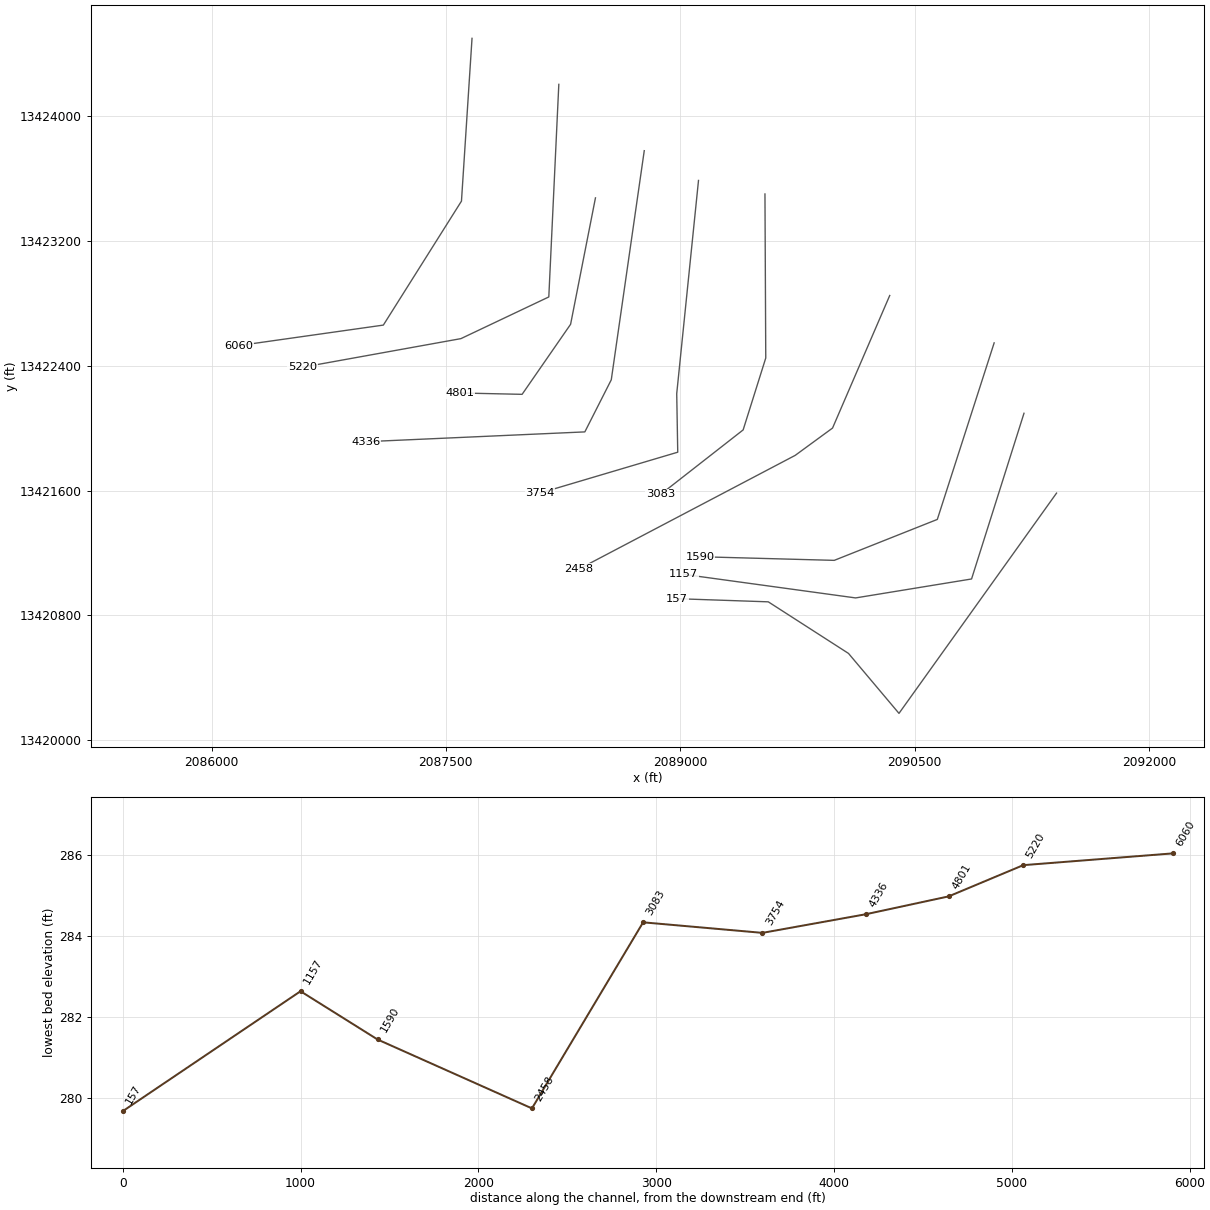
HEC-RAS study LAGUNILLAS Cr.prj: LAGUNILLAS Cr Base Level Engineering

--- LAGUNILLAS Cr.g01 (geometry) --- (continued)

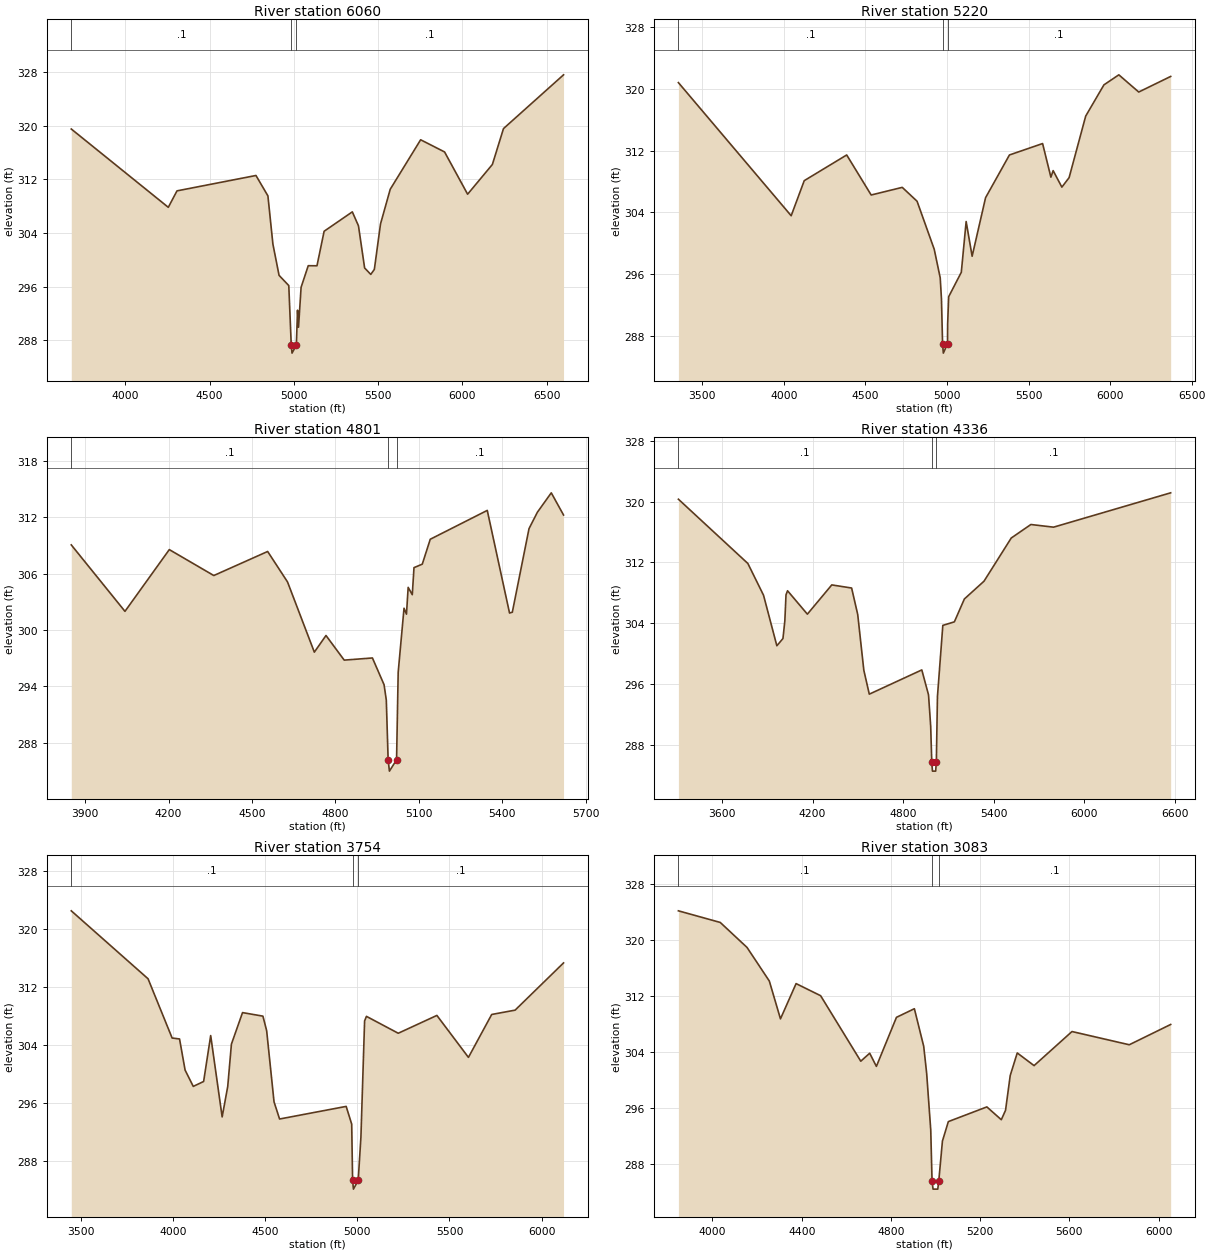
Type RM Length L Ch R = 1 ,6060    ,840,840,840
BEGIN DESCRIPTION:
Mapping XS 9324f96d
END DESCRIPTION:
XS GIS Cut Line= 4
       2087667.4     13424500.84      2087599.85     13423456.87
      2087099.85     13422661.73      2086174.36     13422530.34
#Sta/Elev= 30
  3679.4  319.55    4255  307.84  4306.5   310.3    4775   312.6  4845.9  309.55
  4875.5  302.34    4912  297.67  4969.7  296.14  4984.3  287.24  4988.9  286.04
  5014.6  287.24  5021.5  292.46  5027.4  289.91  5042.7  295.88  5085.1  299.11
  5136.9   299.1  5179.3  304.26  5346.6  307.16  5383.1  305.07  5419.6  298.77
  5456.1  297.81  5477.3  298.56  5513.8  305.35  5571.5  310.54  5751.9  317.94
  5893.8  316.12  6030.6   309.8  6177.5  314.25  6243.3  319.61  6599.6  327.65
#Mann= 3 ,-1 , 0
  3679.4      .1       0  4984.3     .07       0  5014.6      .1       0
Bank Sta=4984.3,5014.6
XS Rating Curve= 0 ,0
Exp/Cntr=0.3,0.1

Type RM Length L Ch R = 1 ,5220    ,419,419,419
BEGIN DESCRIPTION:
Mapping XS 0129c9d0
END DESCRIPTION:
XS GIS Cut Line= 4
      2088222.95     13424205.73      2088158.88     13422842.29
      2087596.38     13422574.92      2086582.29     13422391.44
#Sta/Elev= 30
    3353  320.82  4044.5  303.56  4124.6  308.11  4384.9  311.44    4535  306.25
  4725.5  307.24  4816.4  305.44  4921.5  299.22  4958.3  295.51  4965.8  292.82
  4972.8  286.95  4977.4  285.75  5003.1  286.95  5003.7  289.43  5010.1  293.06
  5087.6  296.23  5117.3  302.81    5154  298.31  5236.4   305.9  5382.8  311.44
    5586  312.92  5636.9  308.56  5650.7  309.41  5704.2  307.27  5748.6   308.5
  5850.3  316.48  5962.1  320.53  6053.5  321.83  6175.5   319.6  6371.3  321.62
#Mann= 3 ,-1 , 0
    3353      .1       0  4972.8     .07       0  5003.1      .1       0
Bank Sta=4972.8,5003.1
XS Rating Curve= 0 ,0
Exp/Cntr=0.3,0.1

Type RM Length L Ch R = 1 ,4801    ,465,465,465
BEGIN DESCRIPTION:
Mapping XS 2232173c
END DESCRIPTION:
XS GIS Cut Line= 4
      2088457.49     13423477.71      2088298.36     13422666.88
      2087988.03     13422217.66       2087590.9     13422226.34
#Sta/Elev= 30
  3850.3  309.05  4043.3  301.98  4202.7  308.55  4362.6  305.79  4556.2  308.35
  4627.6  305.11    4724  297.64  4765.9  299.41  4831.4  296.79  4932.8  297.02
  4974.7  294.17  4982.7  292.54  4989.3  286.18  4993.9  284.98  5019.6  286.18
  5025.4   295.5  5046.4  302.31  5055.2  301.68  5061.3  304.53  5076.1  303.75
  5082.2  306.63    5112     307  5140.7  309.65  5345.6  312.72  5425.7   301.8
  5435.7  301.89  5495.7  310.78  5525.7  312.52  5575.7  314.59  5619.8  312.23
#Mann= 3 ,-1 , 0
  3850.3      .1       0  4989.3     .07       0  5019.6      .1       0
Bank Sta=4989.3,5019.6
XS Rating Curve= 0 ,0
Exp/Cntr=0.3,0.1

Type RM Length L Ch R = 1 ,4336    ,582,582,582
BEGIN DESCRIPTION:
Mapping XS 4c583c45
END DESCRIPTION:
XS GIS Cut Line= 4
      2088769.82     13423780.31      2088558.77     13422310.98
       2088389.5     13421976.78      2086990.35     13421914.02
#Sta/Elev= 30
  3311.4  320.33  3771.4  311.87  3875.1  307.69  3963.3  301.04  4003.7  301.99
  4016.2  304.32  4023.9  307.74  4034.1  308.28  4165.4   305.2    4327  309.05
  4458.4  308.64  4498.8  305.15  4539.2  297.82  4575.4  294.67  4923.1  297.86
  4967.6  294.58  4981.9  290.46  4989.1  285.74  4993.7  284.54  5014.9  284.54
  5019.4  285.74  5026.7  294.35  5062.3  303.72  5138.8  304.19    5205   307.2
  5335.1  309.54  5515.3  315.22  5645.4     317  5795.6  316.65    6571  321.17
#Mann= 3 ,-1 , 0
  3311.4      .1       0  4989.1     .07       0  5019.4      .1       0
Bank Sta=4989.1,5019.4
XS Rating Curve= 0 ,0
Exp/Cntr=0.3,0.1

Type RM Length L Ch R = 1 ,3754    ,671,671,671
BEGIN DESCRIPTION:
Mapping XS 4826ae9d
END DESCRIPTION:
XS GIS Cut Line= 4
      2089117.05     13423589.41      2088977.61       13422222.
      2088984.12     13421846.57      2088101.39     13421584.15
#Sta/Elev= 30
  3447.9   322.5  3864.5  313.12  3995.1  304.94  4035.3  304.81  4065.5  300.51
  4109.8  298.26    4166  298.94  4204.3  305.28  4266.5  294.05  4296.7  298.24
  4316.8   304.1  4377.1  308.45  4487.7  307.96    4508  305.95    4548  296.13
  4578.1  293.76  4939.4   295.5  4969.4  293.05  4974.3  285.28  4978.8  284.08
  5004.6  285.28  5019.4  291.24  5039.4   307.3  5049.4  307.93    5222   305.6
  5431.6  308.06  5602.8  302.27    5729  308.19    5856  308.79  6118.8  315.31
#Mann= 3 ,-1 , 0
  3447.9      .1       0  4974.3     .07       0  5004.6      .1       0
Bank Sta=4974.3,5004.6
XS Rating Curve= 0 ,0
Exp/Cntr=0.3,0.1

Type RM Length L Ch R = 1 ,3083    ,625,625,625
BEGIN DESCRIPTION:
Mapping XS 359bcf00
END DESCRIPTION:
XS GIS Cut Line= 4
       2089542.4      13423502.6       2089547.5     13422450.59
      2089402.76     13421989.48      2088873.98     13421575.46
#Sta/Elev= 30
  3847.3  324.11  4034.9  322.45  4154.9  318.88  4254.9  314.08  4304.9  308.67
  4374.9  313.71  4484.9  311.98  4664.9  302.62  4704.9  303.76  4734.9  301.88
  4824.9  308.89  4905.2  310.12  4947.1  304.74  4960.3  300.88  4978.6  292.79
  4984.4  285.54  4988.9  284.34  5010.1  284.34  5014.7  285.54    5031  291.21
  5057.5  293.99  5230.1  296.09  5294.9  294.26  5313.9   295.6  5334.9  300.58
  5366.4   303.8  5441.8  301.99  5611.8  306.86  5868.6  304.97  6054.2  307.87
#Mann= 3 ,-1 , 0
  3847.3      .1       0  4984.4     .07       0  5014.7      .1       0
Bank Sta=4984.4,5014.7
XS Rating Curve= 0 ,0
Exp/Cntr=0.3,0.1

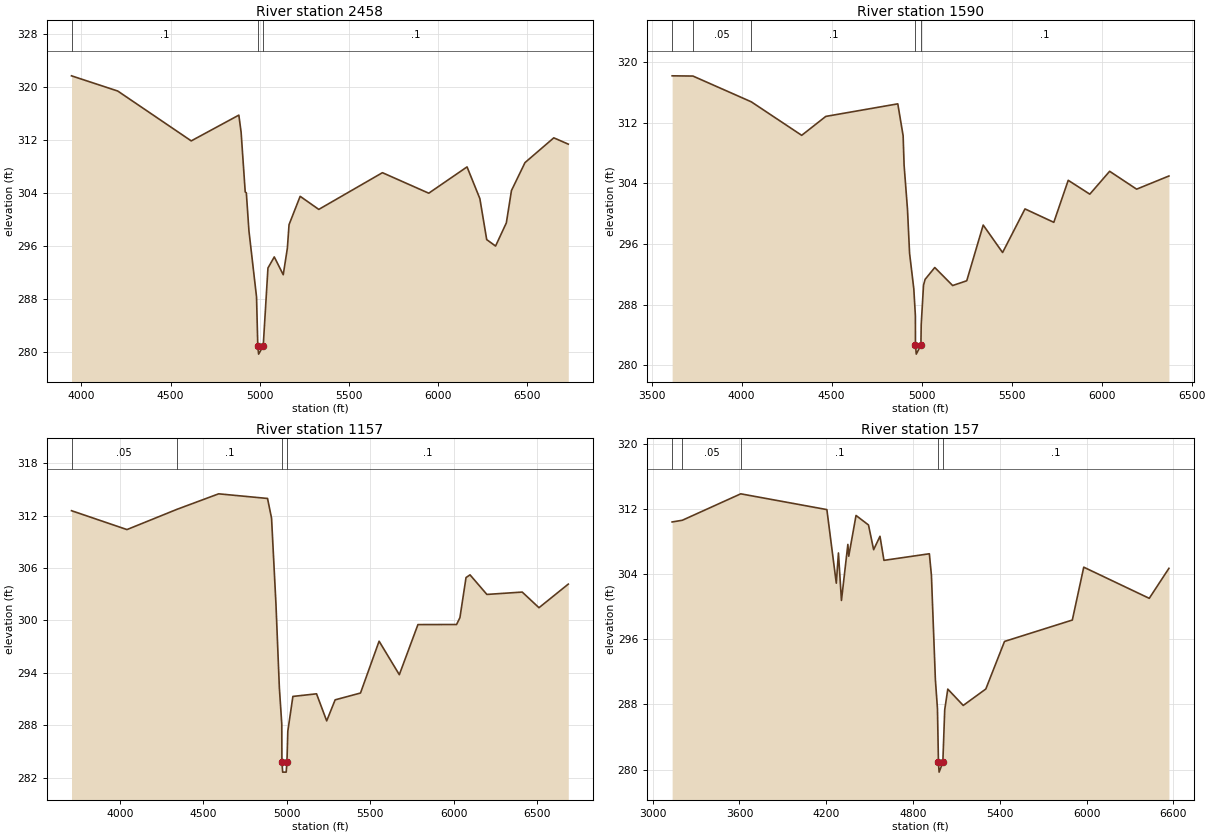
Type RM Length L Ch R = 1 ,2458    ,868,868,868
BEGIN DESCRIPTION:
Mapping XS cafc7221
END DESCRIPTION:
XS GIS Cut Line= 4
        2090341.      13422851.5      2089975.02     13422001.37
      2089736.09     13421826.28      2088353.19     13421098.06
#Sta/Elev= 30
  3944.9  321.67  4204.1  319.38  4616.1  311.87  4882.9  315.75  4895.6  313.19
  4918.7  304.17  4924.9  304.05  4939.6   298.3  4982.1  288.36  4989.2  280.95
  4993.8  279.75  5019.5  280.95  5046.1  292.72  5081.6  294.39  5131.8  291.71
  5154.9   295.7  5164.3  299.25  5226.6  303.52  5331.1  301.55  5687.8  307.08
  5947.4  303.99  6162.1  307.95  6233.9  303.18  6272.3     297    6322  296.03
  6382.4  299.52  6411.1  304.39    6487   308.6  6648.4  312.33  6729.6  311.38
#Mann= 3 ,-1 , 0
  3944.9      .1       0  4989.2     .07       0  5019.5      .1       0
Bank Sta=4989.2,5019.5
XS Rating Curve= 0 ,0
Exp/Cntr=0.3,0.1

Type RM Length L Ch R = 1 ,1590    ,433,433,433
BEGIN DESCRIPTION:
Mapping XS a6a347dd
END DESCRIPTION:
XS GIS Cut Line= 4
       2091009.4     13422547.67      2090645.59     13421415.43
      2089985.87     13421152.84       2089125.7     13421176.17
#Sta/Elev= 30
  3613.9  318.21  3729.4  318.18  4053.3  314.78  4333.6  310.35  4467.5  312.85
  4867.5  314.51  4897.1  310.29  4902.5   306.4  4921.4  300.55  4932.9  294.77
  4956.4  290.08  4965.2  286.52  4965.6  282.65  4970.1  281.45  4995.9  282.65
  4997.5  285.35  5010.4  290.56  5019.1  291.32  5072.9  292.89  5172.2  290.51
  5250.5  291.14  5341.9   298.5  5449.6  294.87  5574.1  300.63  5734.2  298.86
  5814.2  304.41  5934.2  302.58  6044.3   305.6  6194.3  303.24  6373.7  304.98
#Mann= 5 ,-1 , 0
  3613.9      .1       0  3729.4     .05       0  4053.3      .1       0
  4965.6     .07       0  4995.9      .1       0
Bank Sta=4965.6,4995.9
XS Rating Curve= 0 ,0
Exp/Cntr=0.3,0.1

Type RM Length L Ch R = 1 ,1157    ,1000,1000,1000
BEGIN DESCRIPTION:
Mapping XS d10c895a
END DESCRIPTION:
XS GIS Cut Line= 4
      2091200.37     13422096.27      2090864.78     13421033.49
      2090122.59     13420911.96      2089021.52     13421063.33
#Sta/Elev= 30
  3709.2  312.55  4041.7  310.39  4341.9  312.71  4591.4  314.48  4884.3  313.95
  4908.4   311.7  4934.9  301.83  4955.2   292.3  4969.7  288.13  4970.5  283.84
    4975  282.64  4996.2  282.64  5000.8  283.84  5005.9  287.32  5036.3   291.3
  5178.1   291.6  5238.9   288.5  5289.6  290.91  5441.6  291.69  5553.1  297.62
  5674.3  293.79    5786  299.52  6017.5  299.53  6037.7  300.32  6074.2   304.9
  6098.2  305.21  6199.2  302.97  6411.1  303.24  6511.5  301.45  6687.2  304.15
#Mann= 4 ,-1 , 0
  3709.2     .05       0  4341.9      .1       0  4970.5     .07       0
  5000.8      .1       0
Bank Sta=4970.5,5000.8
XS Rating Curve= 0 ,0
Exp/Cntr=0.3,0.1

Type RM Length L Ch R = 1 ,157     ,0,0,0
BEGIN DESCRIPTION:
LAGUNILLAS Cr 1.0
END DESCRIPTION:
XS GIS Cut Line= 5
      2091408.72     13421584.16      2090400.22     13420171.51
      2090077.02     13420556.06      2089563.69     13420886.88
      2088979.07     13420907.04
#Sta/Elev= 30
  3134.8  310.44  3205.2  310.65    3609   313.9  4204.3  311.96  4269.4  302.91
  4284.2  306.63    4305  300.79  4349.3  307.68  4355.4  306.23  4405.8  311.24
  4491.9  310.07  4527.5  307.03  4571.3  308.68  4598.8  305.72  4912.6  306.53
  4926.9  303.88  4954.3  291.04  4968.6  287.49  4975.5  280.88    4980  279.68
  5005.8  280.88  5018.8  287.35  5040.1  289.89  5146.7  287.88  5302.8   289.9
  5432.1  295.75  5900.8  298.38  5979.8  304.88  6432.5  301.05  6568.5  304.74
#Mann= 5 ,-1 , 0
  3134.8      .1       0  3205.2     .05       0    3609      .1       0
  4975.5     .07       0  5005.8      .1       0
Bank Sta=4975.5,5005.8
XS Rating Curve= 0 ,0
Exp/Cntr=0.3,0.1
LCMann Table=0

Chan Stop Cuts=-1
Use User Specified Reach Order=0
Composite Channel Slope=5