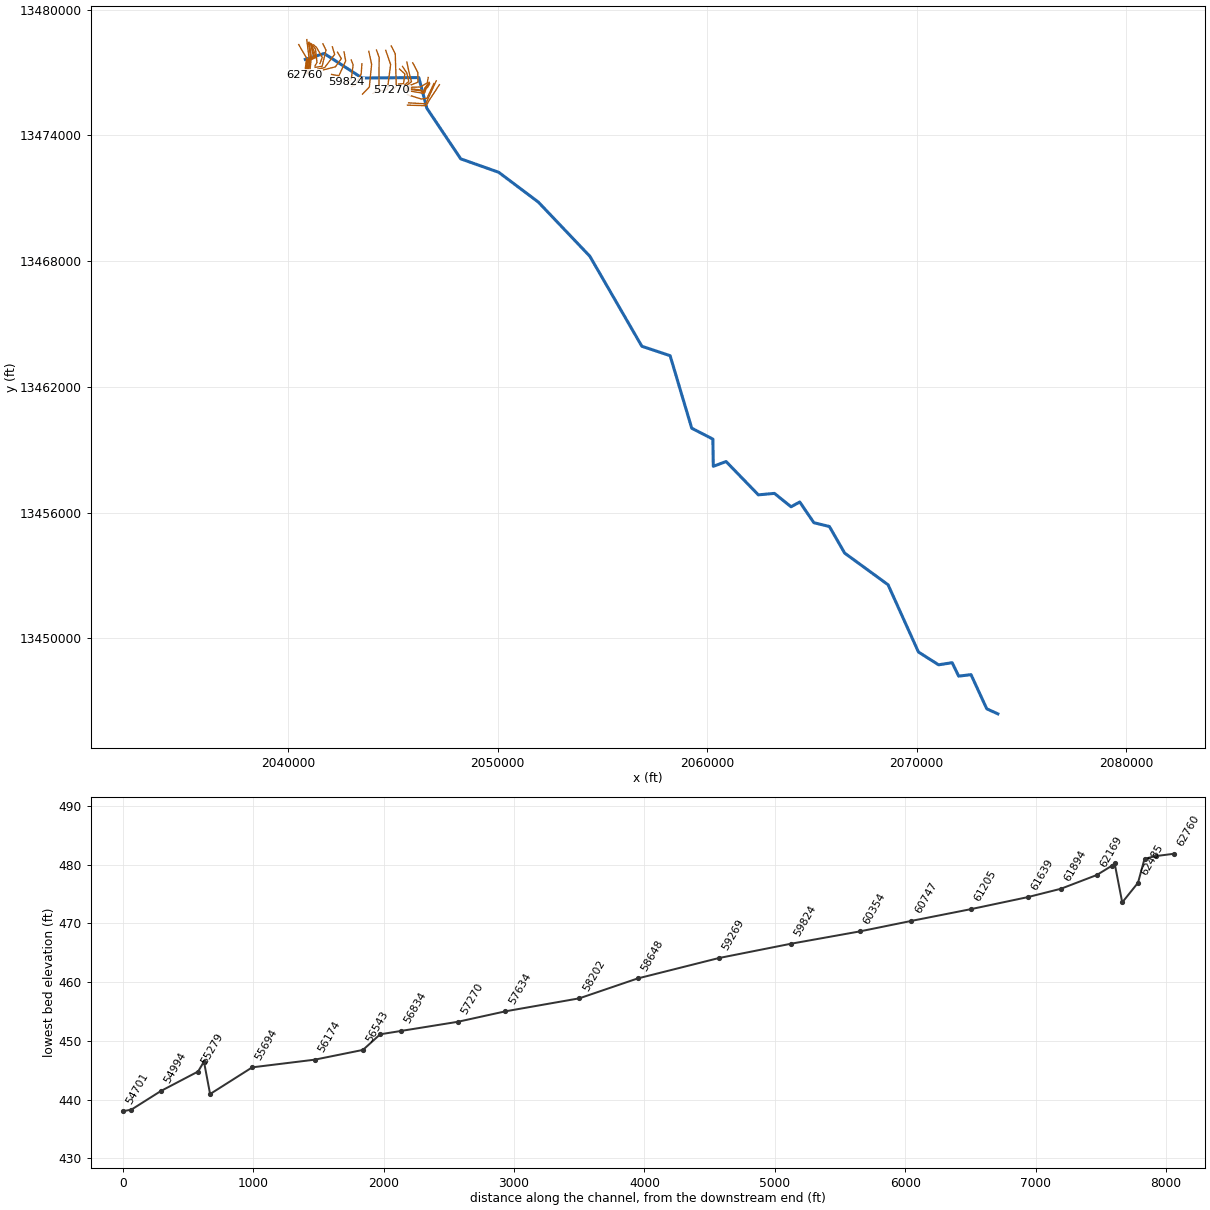
--- LAKE Br.prj (project) ---

Proj Title=LAKE Br Base Level Engineering
Current Plan=p01
Default Exp/Contr=0.3,0.1
English Units
Geom File=g01
Flow File=f01
Plan File=p01
Y Axis Title=Elevation
X Axis Title(PF)=Main Channel Distance
X Axis Title(XS)=Station
BEGIN DESCRIPTION:
LAKE Br
END DESCRIPTION:
DSS Export Rating Curves= 0
DSS Export Rating Curve Sorted= 0
DSS Export Volume Flow Curves= 0
DXF OffsetX= 0
DXF OffsetY= 0
DXF ScaleX= 1
DXF ScaleY= 10

--- LAKE Br.p01 (plan) ---

Plan Title=Multiple Run
Short Identifier=Multiple
Geom File=g01
Flow File=f01
Subcritical Flow
K Sum by GR= 0
Std Step Tol= 0.01
Critical Tol= 0.01
Num of Std Step Trials= 20
Max Error Tol= 0.3
Flow Tol Ratio= 0.001
Split Flow NTrial= 30
Split Flow Tol= 0.02
Split Flow Ratio= 0.02
Log Output Level= 0
Friction Slope Method= 1
Unsteady Friction Slope Method= 2
Unsteady Bridges Friction Slope Method= 1
Parabolic Critical Depth
Global Vel Dist=  1 , 1 , 1
Global Log Level= 0
CheckData=True
Encroach Param= -1, 0, 0, 0
BEGIN DESCRIPTION:
Multiple Run
END DESCRIPTION:

--- LAKE Br.f01 (steady flow) ---

Flow Title=Multiple
Program Version=5.05
Number of Profiles= 7
Profile Names=10-year,25-year,50-year,1pct_min,100-year,1pct_plu,500-year
River Rch & RM=LAKE Br,Reach-1         ,62760
     151     202     243     146     291     580     423
River Rch & RM=LAKE Br,Reach-1         ,57634
     190     257     312     188     376     750     556
River Rch & RM=LAKE Br,Reach-1         ,50957
     339     475     588     362     723    1443    1112
River Rch & RM=LAKE Br,Reach-1         ,50759
     479     681     852     530    1058    2111    1657
River Rch & RM=LAKE Br,Reach-1         ,45801
     536     764     957     596    1190    2374    1868
River Rch & RM=LAKE Br,Reach-1         ,41725
     678     973    1226     767    1531    3054    2424
River Rch & RM=LAKE Br,Reach-1         ,41535
     678     973    1226     767    1531    3054    2424
River Rch & RM=LAKE Br,Reach-1         ,36231
     691     991    1248     781    1558    3108    2464
River Rch & RM=LAKE Br,Reach-1         ,33809
     803    1158    1461     916    1827    3645    2901
River Rch & RM=LAKE Br,Reach-1         ,26488
     826    1190    1502     940    1877    3744    2977
Boundary for River Rch & Prof#=LAKE Br,Reach-1         , 1
Up Type= 0
Dn Type= 3
Dn Slope=0.00156
Boundary for River Rch & Prof#=LAKE Br,Reach-1         , 2
Up Type= 0
Dn Type= 3
Dn Slope=0.00156
Boundary for River Rch & Prof#=LAKE Br,Reach-1         , 3
Up Type= 0
Dn Type= 3
Dn Slope=0.00156
Boundary for River Rch & Prof#=LAKE Br,Reach-1         , 4
Up Type= 0
Dn Type= 3
Dn Slope=0.00156
Boundary for River Rch & Prof#=LAKE Br,Reach-1         , 5
Up Type= 0
Dn Type= 3
Dn Slope=0.00156
Boundary for River Rch & Prof#=LAKE Br,Reach-1         , 6
Up Type= 0
Dn Type= 3
Dn Slope=0.00156
Boundary for River Rch & Prof#=LAKE Br,Reach-1         , 7
Up Type= 0
Dn Type= 3
Dn Slope=0.00156
DSS Import GetInterval= 0
DSS Import GetPeak= 0
DSS Import FillOption= 0

--- LAKE Br.g01 (geometry) ---

Geom Title=Existing Conditions
Program Version=5.05

River Reach=LAKE Br         ,Reach-1
Reach XY= 30
       2040820.8     13477624.54       2041720.8     13477904.54
       2043530.8     13476734.54      2046236.95     13476756.39
       2046620.8     13475294.54      2048236.51     13472877.91
      2050050.35     13472236.69       2051940.8     13470815.08
      2054400.62     13468228.41       2056880.8     13463934.54
       2058230.8     13463484.54       2059260.8     13460024.54
       2060270.8     13459504.54       2060290.8     13458204.54
       2060900.8     13458434.54       2062440.8     13456844.54
       2063210.8     13456914.54       2064000.8     13456274.54
      2064416.84     13456504.07       2065090.8     13455514.54
       2065830.8     13455334.54       2066560.8     13454064.54
       2068630.8     13452554.54       2070080.8     13449344.54
       2071040.8     13448734.54       2071690.8     13448834.54
       2072000.8     13448194.54       2072590.8     13448264.54
       2073340.8     13446634.54       2073870.8     13446394.54

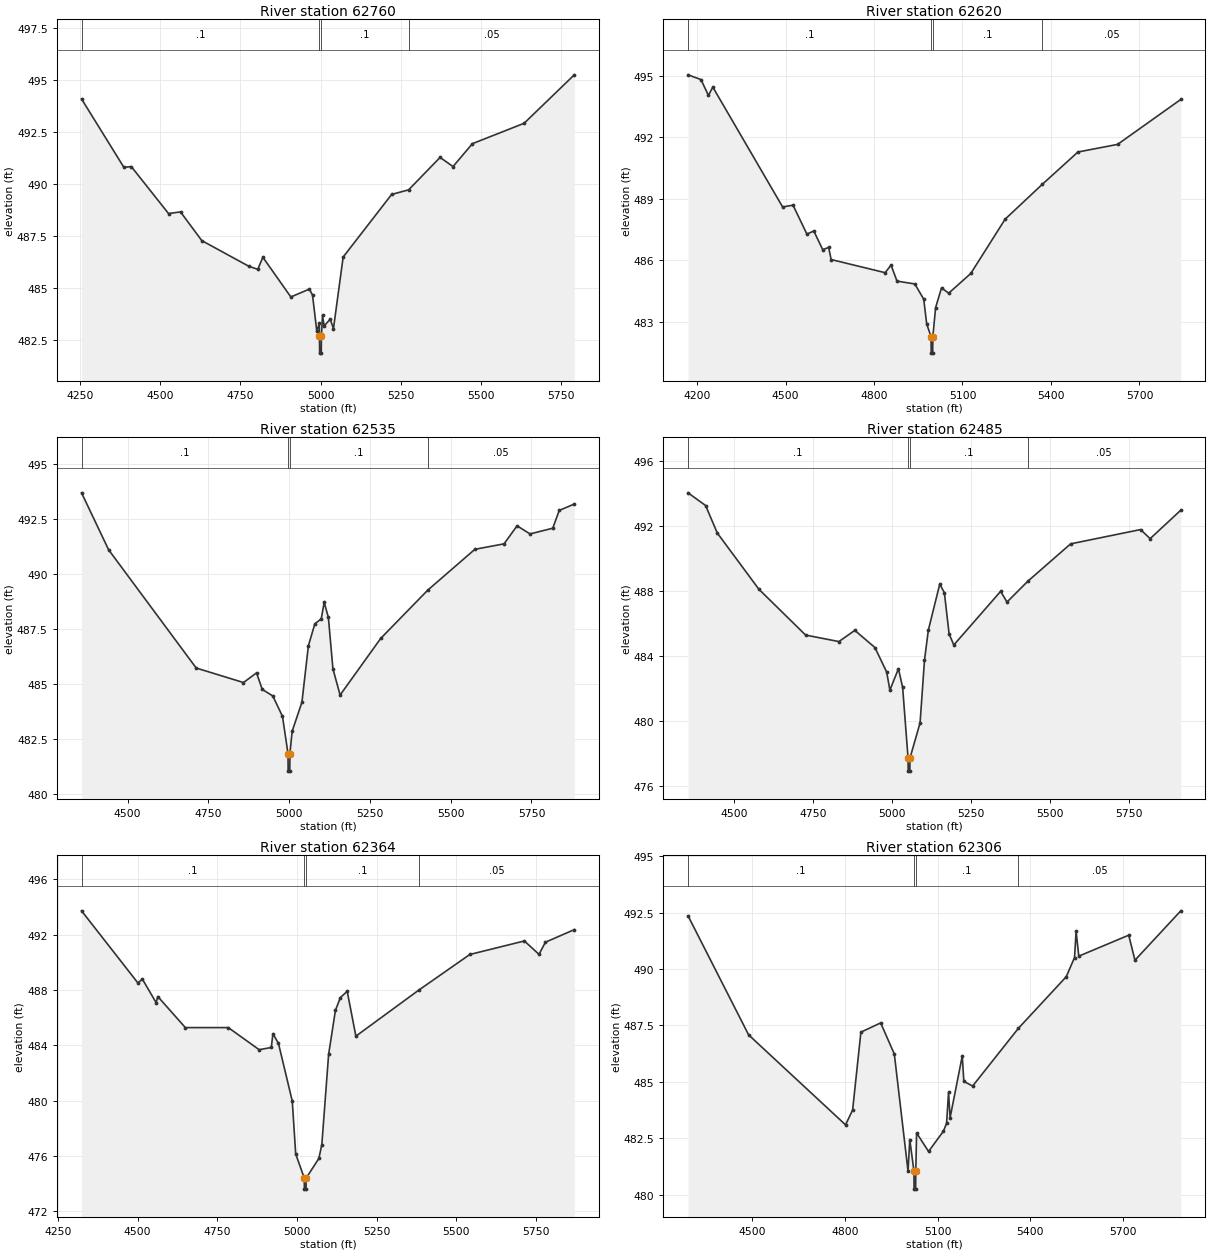
Type RM Length L Ch R = 1 ,62760   ,140,140,140
BEGIN DESCRIPTION:
LAKE Br 20.0
END DESCRIPTION:
XS GIS Cut Line= 3
      2040506.52     13478329.04       2040880.8     13477684.54
      2040787.81     13476899.63
#Sta/Elev= 30
  4254.7   494.1  4386.7  490.81  4409.7  490.85  4525.8  488.59  4563.1  488.67
  4629.4  487.29  4776.7  486.05    4804  485.91  4819.7  486.49    4907  484.58
  4964.8  484.96  4974.5  484.67  4987.9  482.93    4996  483.33  4996.2  482.68
  4996.7  481.88  5001.7  481.88  5002.2  482.68  5005.7  483.69  5010.7  483.19
  5029.7  483.51  5039.8  483.06    5070   486.5  5221.1  489.51    5274  489.73
  5372.1  491.29  5412.4  490.85  5472.8  491.95  5633.9  492.93  5790.4  495.26
#Mann= 4 ,-1 , 0
  4254.7      .1       0  4996.2     .07       0  5002.2      .1       0
    5274     .05       0
Bank Sta=4996.2,5002.2
XS Rating Curve= 0 ,0
Exp/Cntr=0.3,0.1

Type RM Length L Ch R = 1 ,62620   ,85,85,85
BEGIN DESCRIPTION:
Mapping XS e81f033f
END DESCRIPTION:
XS GIS Cut Line= 5
      2040891.72     13478568.47      2040972.45     13477896.63
      2040995.88     13477693.51      2040891.72     13477597.15
      2040844.84     13476951.29
#Sta/Elev= 30
  4169.5  495.04  4213.3  494.81  4238.7  494.04  4253.6  494.44  4490.3   488.6
  4525.5  488.69  4572.5  487.28    4596  487.43  4626.2  486.52  4646.4  486.63
  4654.7  486.04  4837.7   485.4  4857.9  485.77    4878  484.99  4938.4  484.85
  4968.6  484.11  4978.7   482.9  4993.5  482.28    4994  481.48    4999  481.48
  4999.5  482.28  5008.9   483.7    5029  484.66  5053.2   484.4  5128.1  485.36
  5244.8  488.01  5370.2   489.7  5491.5  491.28  5625.8  491.65  5840.1  493.84
#Mann= 4 ,-1 , 0
  4169.5      .1       0  4993.5     .07       0  4999.5      .1       0
  5370.2     .05       0
Bank Sta=4993.5,4999.5
XS Rating Curve= 0 ,0
Exp/Cntr=0.3,0.1

Type RM Length L Ch R = 1 ,62535   ,50,50,50
BEGIN DESCRIPTION:
Mapping XS 09f31770
END DESCRIPTION:
XS GIS Cut Line= 5
      2040967.23     13478430.53      2041050.57      13477875.8
      2041058.38     13477701.32      2040938.59     13477620.59
      2040878.82     13476978.63
#Sta/Elev= 30
  4357.7  493.69  4441.4   491.1  4712.5  485.72  4858.8  485.06  4899.2   485.5
  4916.7  484.75  4949.5  484.45  4979.5  483.52  4996.5  481.83    4997  481.03
    5002  481.03  5002.5  481.83  5009.5  482.85  5039.6  484.16  5059.6  486.73
  5079.6  487.73  5099.5  487.96  5108.5  488.71  5121.5  488.02  5135.5  485.69
  5157.7  484.49  5283.6  487.07  5428.8  489.26  5574.8  491.12  5665.2  491.37
  5705.4  492.19  5745.5  491.82  5815.8  492.08  5835.9  492.89  5882.5  493.18
#Mann= 4 ,-1 , 0
  4357.7      .1       0  4996.5     .07       0  5002.5      .1       0
  5428.8     .05       0
Bank Sta=4996.5,5002.5
XS Rating Curve= 0 ,0
Exp/Cntr=0.3,0.1

Type RM Length L Ch R = 1 ,62485   ,121,121,121
BEGIN DESCRIPTION:
Mapping XS 8f279a3c
END DESCRIPTION:
XS GIS Cut Line= 5
      2041001.52     13478436.37      2041071.84     13477993.64
       2041108.3     13477712.39      2040978.09     13477623.85
      2040905.32     13476958.56
#Sta/Elev= 30
  4354.6  494.06  4410.2  493.28  4447.1  491.59  4578.7  488.13  4726.5  485.31
  4831.8  484.91  4882.2   485.6  4945.9  484.54    4983  483.03  4993.1  481.92
  5020.1  483.24  5033.4   482.1  5050.6  477.74  5051.1  476.94  5056.1  476.94
  5056.6  477.74  5088.6  479.91  5102.5  483.75  5114.7  485.61  5150.9  488.45
  5165.5  487.91  5180.4  485.38  5195.3   484.7  5343.4     488  5363.5  487.34
  5429.3  488.62  5564.7  490.92    5786   491.8  5816.2  491.24  5913.2  492.99
#Mann= 4 ,-1 , 0
  4354.6      .1       0  5050.6     .07       0  5056.6      .1       0
  5429.3     .05       0
Bank Sta=5050.6,5056.6
XS Rating Curve= 0 ,0
Exp/Cntr=0.3,0.1

Type RM Length L Ch R = 1 ,62364   ,58,58,58
BEGIN DESCRIPTION:
Mapping XS 4fcc6cfe
END DESCRIPTION:
XS GIS Cut Line= 6
      2041068.34     13478387.47      2041206.15     13477776.56
      2041203.98     13477741.84       2041136.7     13477699.52
      2041019.76     13477629.05      2040941.63       13476965.
#Sta/Elev= 30
  4324.1  493.73  4500.9  488.51  4514.9  488.79  4558.1  487.08  4563.2  487.53
  4649.7  485.28  4784.5  485.28  4881.2  483.68  4919.3  483.84  4924.4  484.84
  4941.7  484.14  4985.1  479.96  4995.8  476.14  5022.7  474.39  5023.2  473.59
  5028.2  473.59  5028.7  474.39  5068.5  475.81  5077.8  476.81  5099.1  483.34
  5120.5  486.53    5136  487.45  5157.4  487.91  5184.6  484.66  5381.8  487.99
    5542  490.57  5713.2  491.55    5759  490.58  5779.2  491.46  5869.8  492.37
#Mann= 4 ,-1 , 0
  4324.1      .1       0  5022.7     .07       0  5028.7      .1       0
  5381.8     .05       0
Bank Sta=5022.7,5028.7
XS Rating Curve= 0 ,0
Exp/Cntr=0.3,0.1

Type RM Length L Ch R = 1 ,62306   ,23,23,23
BEGIN DESCRIPTION:
Mapping XS e5459397
END DESCRIPTION:
XS GIS Cut Line= 6
      2041103.06     13478346.24      2041163.83     13478070.61
      2041278.85     13477716.88      2041147.55     13477648.52
      2041056.41     13477628.99      2040965.32     13476938.22
#Sta/Elev= 30
  4293.6  492.36  4489.4  487.08  4802.6  483.09  4825.5  483.75  4852.2   487.2
  4916.1  487.61  4960.2  486.23  5004.5  481.04  5010.1  482.44  5023.6  481.04
  5024.1  480.24  5029.1  480.24  5029.6  481.04  5032.2  482.73  5070.8  481.91
  5118.9  482.81  5129.1  483.16  5135.4  484.53  5140.5  483.41  5179.7  486.14
  5184.8  485.02  5213.2  484.81  5361.1  487.37  5515.8  489.66  5542.5  490.51
  5547.6  491.67  5556.2  490.57  5717.6   491.5  5737.7  490.39  5885.8  492.58
#Mann= 4 ,-1 , 0
  4293.6      .1       0  5023.6     .07       0  5029.6      .1       0
  5361.1     .05       0
Bank Sta=5023.6,5029.6
XS Rating Curve= 0 ,0
Exp/Cntr=0.3,0.1

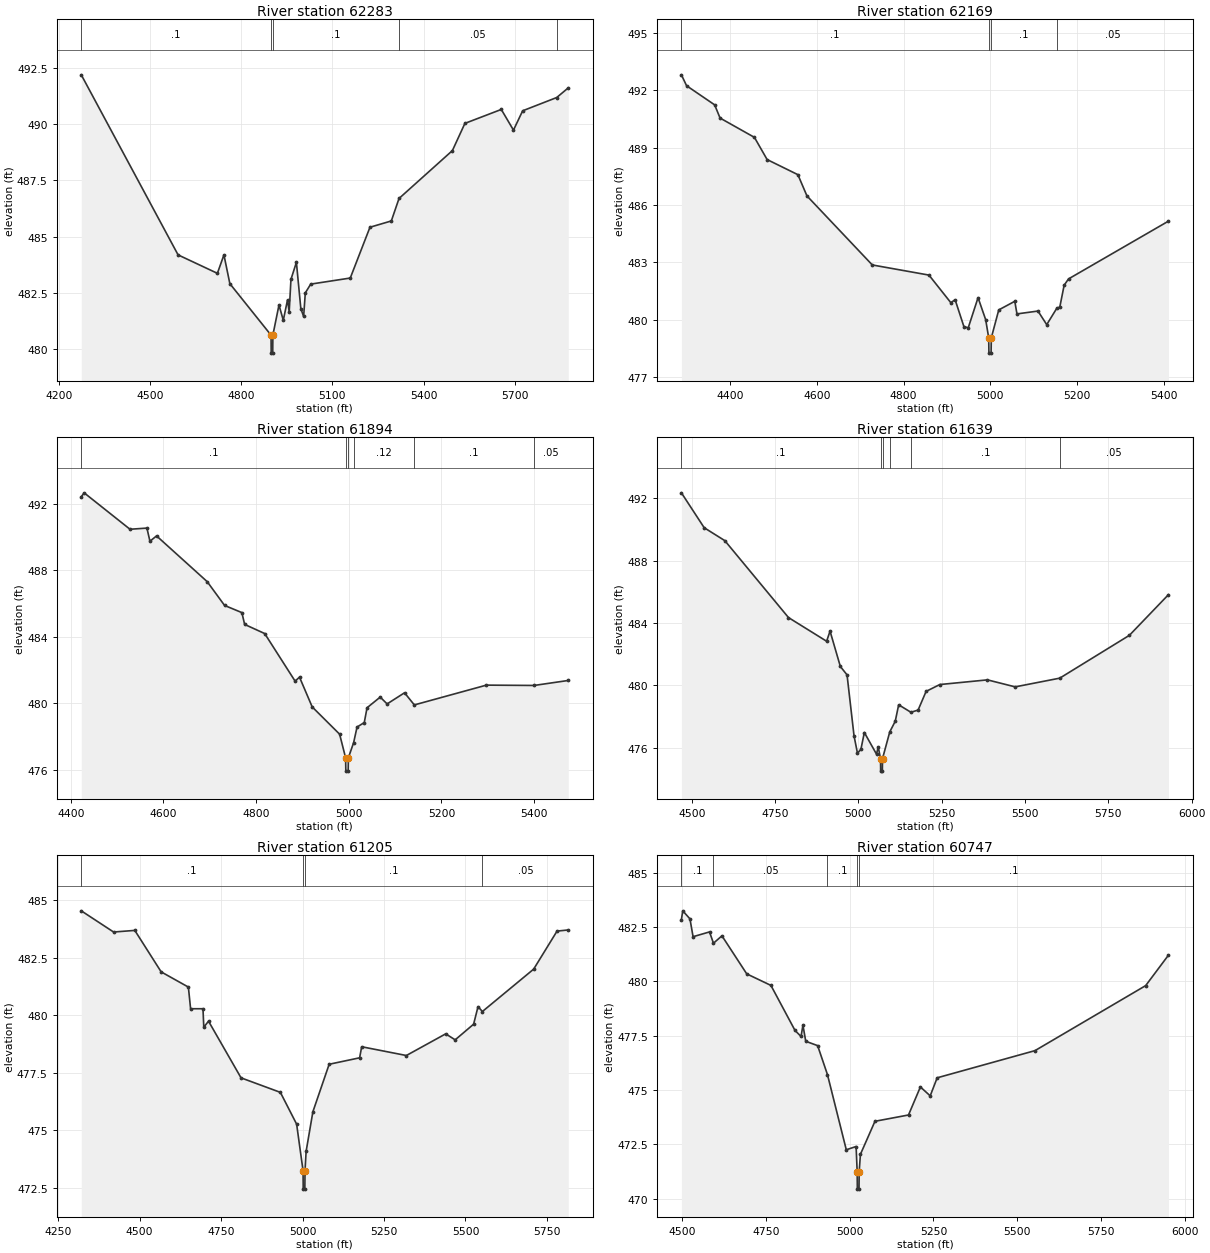
Type RM Length L Ch R = 1 ,62283   ,114,114,114
BEGIN DESCRIPTION:
Mapping XS c55ba3d7
END DESCRIPTION:
XS GIS Cut Line= 5
      2041115.72     13478333.84      2041321.89     13477789.13
       2041306.7     13477706.66      2041094.02     13477617.69
      2041027.57     13476915.53
#Sta/Elev= 30
  4274.1   492.2  4592.6  484.19  4721.9  483.37  4743.4  484.19  4762.9  482.91
  4898.4  480.62  4898.9  479.82  4903.9  479.82  4904.4  480.62  4924.5  481.96
  4938.7  481.28  4952.6  482.19  4958.1  481.66  4963.9   483.1  4981.8  483.86
  4996.4   481.8  5005.6  481.45  5011.1   482.5  5028.9  482.89    5159  483.16
  5223.8  485.42  5294.1   485.7  5319.4   486.7    5495  488.83  5536.1  490.04
  5655.8  490.66  5695.9  489.74  5726.1   490.6  5838.1  491.19  5876.2  491.62
#Mann= 5 ,-1 , 0
  4274.1      .1       0  4898.4     .07       0  4904.4      .1       0
  5319.4     .05       0  5838.1      .1       0
Bank Sta=4898.4,4904.4
XS Rating Curve= 0 ,0
Exp/Cntr=0.3,0.1

Type RM Length L Ch R = 1 ,62169   ,275,275,275
BEGIN DESCRIPTION:
Mapping XS 80dacacb
END DESCRIPTION:
XS GIS Cut Line= 4
      2041130.91     13478346.87       2041306.7     13478108.14
      2041378.31     13477474.46      2041280.65     13477311.69
#Sta/Elev= 30
  4287.3  492.81  4299.2  492.24    4364  491.24  4376.5  490.55  4455.8  489.54
  4485.1  488.38  4556.1  487.59    4577  486.48  4727.8  482.87  4858.6  482.34
    4909   480.9    4919  481.05  4939.2  479.65  4949.2  479.58  4971.9  481.16
  4989.5  480.01  4996.5  479.06    4997  478.26    5002  478.26  5002.5  479.06
  5019.7  480.52  5056.7  480.97  5061.7  480.31  5110.2  480.46  5130.4  479.75
  5153.5   480.6  5160.6  480.67  5170.6  481.81  5180.7  482.14  5411.3  485.16
#Mann= 4 ,-1 , 0
  4287.3      .1       0  4996.5     .07       0  5002.5      .1       0
  5153.5     .05       0
Bank Sta=4996.5,5002.5
XS Rating Curve= 0 ,0
Exp/Cntr=0.3,0.1

Type RM Length L Ch R = 1 ,61894   ,255,255,255
BEGIN DESCRIPTION:
Mapping XS a2d314a9
END DESCRIPTION:
XS GIS Cut Line= 4
      2041215.57     13478314.29      2041356.61     13478197.12
      2041630.05     13477713.17      2041517.21     13477422.41
#Sta/Elev= 30
  4422.7  492.41  4428.9  492.65  4527.9  490.46  4564.4  490.53  4570.9  489.74
  4585.2  490.06  4694.5  487.31    4732  485.88  4769.3  485.45  4775.3  484.74
  4818.6  484.19  4884.2  481.33  4893.7  481.57  4921.1  479.78  4980.3  478.14
  4993.2  476.72  4993.7  475.92  4998.7  475.92  4999.2  476.72  5010.6  477.64
  5017.9  478.57  5033.5  478.84  5039.5  479.73  5067.9  480.37  5082.8  479.96
  5120.4  480.63  5141.5   479.9  5297.1  481.09  5399.9  481.07  5473.8  481.37
#Mann= 6 ,-1 , 0
  4422.7      .1       0  4993.2     .07       0  4999.2      .1       0
  5010.6     .12       0  5141.5      .1       0  5399.9     .05       0
Bank Sta=4993.2,4999.2
XS Rating Curve= 0 ,0
Exp/Cntr=0.3,0.1

Type RM Length L Ch R = 1 ,61639   ,434,434,434
BEGIN DESCRIPTION:
Mapping XS aeed16a5
END DESCRIPTION:
XS GIS Cut Line= 4
      2041660.87     13478363.33       2041809.3     13478061.27
       2041621.8     13477295.64      2041289.25     13477243.68
#Sta/Elev= 30
  4468.9  492.36  4537.2  490.12  4599.1  489.29  4790.2  484.35  4904.6  482.83
  4914.9  483.48  4945.8  481.21  4965.9  480.67  4986.9  476.75  4997.2  475.64
  5007.5  475.89  5017.8  476.97  5054.3  475.58  5059.5  476.05  5066.3  475.29
  5066.8  474.49  5071.8  474.49  5072.3  475.29  5094.1  477.01  5110.5  477.69
  5120.8  478.75  5157.5  478.27  5179.1  478.41  5203.1  479.61  5244.3  480.05
  5387.2  480.35  5470.4   479.9  5604.2  480.46  5813.1  483.21  5930.3  485.82
#Mann= 6 ,-1 , 0
  4468.9      .1       0  5066.3     .07       0  5072.3      .1       0
  5094.1     .12       0  5157.5      .1       0  5604.2     .05       0
Bank Sta=5066.3,5072.3
XS Rating Curve= 0 ,0
Exp/Cntr=0.3,0.1

Type RM Length L Ch R = 1 ,61205   ,458,458,458
BEGIN DESCRIPTION:
Mapping XS 5237915b
END DESCRIPTION:
XS GIS Cut Line= 4
        2042114.     13478220.09      2042220.76     13477860.74
      2041741.59     13477230.54      2041421.28     13477160.22
#Sta/Elev= 30
    4321  484.53  4420.2  483.61  4485.3  483.68  4566.2  481.88  4649.7  481.22
  4656.5  480.28  4694.5  480.28    4697  479.48  4711.5  479.74  4811.3  477.28
    4932  476.65  4981.9  475.27  5001.6  473.25  5002.1  472.45  5007.1  472.45
  5007.6  473.25    5011  474.09  5031.8  475.81  5081.7  477.87  5175.2  478.15
  5181.5  478.63  5318.6  478.25  5439.3  479.19  5468.4  478.93    5525  479.61
  5538.5  480.37    5552  480.16  5709.3     482    5781  483.65  5815.5   483.7
#Mann= 4 ,-1 , 0
    4321      .1       0  5001.6     .07       0  5007.6      .1       0
    5552     .05       0
Bank Sta=5001.6,5007.6
XS Rating Curve= 0 ,0
Exp/Cntr=0.3,0.1

Type RM Length L Ch R = 1 ,60747   ,393,393,393
BEGIN DESCRIPTION:
Mapping XS c2f3f914
END DESCRIPTION:
XS GIS Cut Line= 4
      2042358.78      13477964.9      2042541.07     13477657.62
      2042254.61      13477269.6      2041659.15     13477116.18
#Sta/Elev= 30
  4497.3  482.84  4501.3  483.24  4522.8  482.87  4532.1  482.05  4581.2  482.27
    4593  481.75  4618.3  482.09  4692.4  480.34  4764.6  479.81  4836.5  477.74
  4854.6  477.46  4860.2  477.98  4868.6  477.24  4904.1  477.04  4933.4  475.71
  4989.7  472.25    5019   472.4  5022.2  471.24  5022.7  470.44  5027.7  470.44
  5028.2  471.24  5031.9  472.04  5075.3  473.56  5175.5  473.85    5211  475.14
  5240.3  474.73  5261.1  475.56  5553.3  476.81  5883.8   479.8  5951.8   481.2
#Mann= 5 ,-1 , 0
  4497.3      .1       0    4593     .05       0  4933.4      .1       0
  5022.2     .07       0  5028.2      .1       0
Bank Sta=5022.2,5028.2
XS Rating Curve= 0 ,0
Exp/Cntr=0.3,0.1

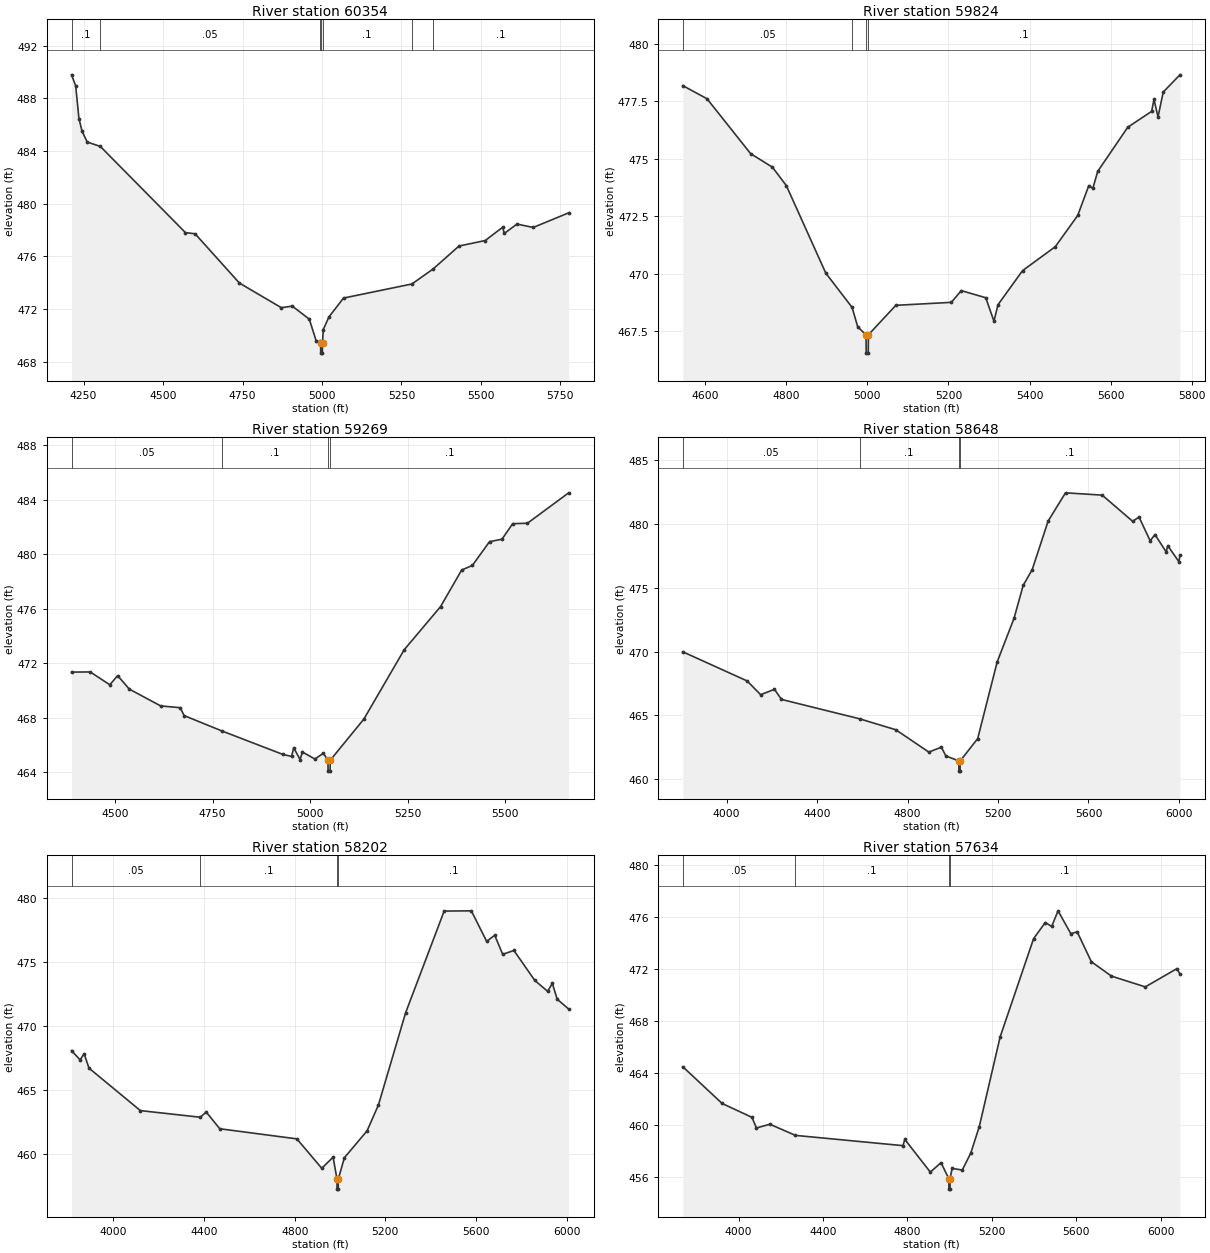
Type RM Length L Ch R = 1 ,60354   ,530,530,530
BEGIN DESCRIPTION:
Mapping XS af0f666d
END DESCRIPTION:
XS GIS Cut Line= 4
      2042671.29      13477977.9       2042746.8     13477550.85
      2042423.88     13476845.12      2042074.96     13476905.01
#Sta/Elev= 30
  4212.1  489.79  4225.2  488.96  4235.4  486.47  4245.5  485.49  4261.4  484.69
  4302.9  484.35  4570.5  477.81  4600.9  477.72  4740.2  473.98  4872.2  472.11
  4906.6  472.23  4960.1  471.24  4982.1  469.56  4993.2  469.55  4995.6  469.46
  4996.1  468.66  5001.1  468.66  5001.6  469.46  5004.1  470.45  5021.6   471.4
  5067.7  472.84  5282.9  473.91  5349.6  475.05  5430.9  476.79  5513.5  477.21
  5568.4  478.22  5573.5  477.75  5613.5  478.46  5664.3   478.2  5775.9  479.31
#Mann= 7 ,-1 , 0
  4212.1      .1       0  4302.9     .05       0  4993.2      .1       0
  4995.6     .07       0  5001.6      .1       0  5282.9     .05       0
  5349.6      .1       0
Bank Sta=4995.6,5001.6
XS Rating Curve= 0 ,0
Exp/Cntr=0.3,0.1

Type RM Length L Ch R = 1 ,59824   ,555,555,555
BEGIN DESCRIPTION:
Mapping XS e4d551ba
END DESCRIPTION:
XS GIS Cut Line= 4
      2043009.81     13477600.35      2043103.57     13477365.95
      2043009.82     13476652.41      2042789.27     13476525.27
#Sta/Elev= 30
  4544.4  478.19  4604.1  477.62  4711.8  475.23  4765.6  474.64  4799.9  473.84
  4897.3  470.03  4962.2  468.54  4976.1  467.69  4996.5  467.35    4997  466.55
    5002  466.55  5002.5  467.35  5070.1  468.63  5207.2  468.76  5231.5  469.27
    5292  468.96  5312.2  467.94  5322.3  468.66  5382.8  470.14  5463.5  471.18
  5518.9  472.54  5546.2  473.84  5556.2  473.72  5568.3  474.46  5642.4  476.38
  5701.3  477.07  5707.1  477.59  5717.1  476.83  5729.9  477.91  5771.1  478.66
#Mann= 4 ,-1 , 0
  4544.4     .05       0  4962.2      .1       0  4996.5     .07       0
  5002.5      .1       0
Bank Sta=4996.5,5002.5
XS Rating Curve= 0 ,0
Exp/Cntr=0.3,0.1

Type RM Length L Ch R = 1 ,59269   ,621,621,621
BEGIN DESCRIPTION:
Mapping XS e9851695
END DESCRIPTION:
XS GIS Cut Line= 4
      2043522.84     13477412.83      2043486.38     13476925.85
      2043212.95     13476423.24      2043026.24     13476319.52
#Sta/Elev= 30
  4388.6  471.36  4436.6  471.37  4486.7  470.43  4506.8   471.1  4536.8  470.11
  4617.1  468.88  4667.2  468.75  4677.2  468.17  4773.6  467.05  4930.6  465.32
  4952.5  465.18  4958.2  465.81  4974.3  464.95  4980.4   465.5  5012.3  464.99
  5034.2  465.41  5045.7   464.9  5046.2   464.1  5051.2   464.1  5051.7   464.9
  5137.7  467.91  5241.3     473  5334.4  476.16  5388.5  478.84    5416  479.18
  5459.9  480.92  5491.9   481.1  5519.3  482.24  5557.1  482.27  5662.7   484.5
#Mann= 4 ,-1 , 0
  4388.6     .05       0  4773.6      .1       0  5045.7     .07       0
  5051.7      .1       0
Bank Sta=5045.7,5051.7
XS Rating Curve= 0 ,0
Exp/Cntr=0.3,0.1

Type RM Length L Ch R = 1 ,58648   ,446,446,446
BEGIN DESCRIPTION:
Mapping XS 32f415b2
END DESCRIPTION:
XS GIS Cut Line= 4
      2043850.91     13478011.44      2043984.81     13477389.47
      2043876.82     13476305.31      2043549.28     13475964.83
#Sta/Elev= 30
  3806.1  469.98  4090.4   467.7  4150.3  466.62  4211.6  467.04  4242.3  466.25
  4587.9  464.73  4748.3  463.87  4894.2  462.12  4949.3  462.51  4969.4  461.82
  5026.7  461.43  5027.2  460.63  5032.2  460.63  5032.7  461.43  5110.1  463.18
  5196.3  469.19  5270.9  472.61  5311.1  475.18  5351.3  476.43  5421.6  480.23
  5498.4  482.44  5660.6  482.26  5795.2  480.21  5823.5  480.54  5872.8  478.68
  5893.9  479.17  5943.6  477.81  5950.5   478.3  6000.2  477.03  6004.3  477.58
#Mann= 4 ,-1 , 0
  3806.1     .05       0  4587.9      .1       0  5026.7     .07       0
  5032.7      .1       0
Bank Sta=5026.7,5032.7
XS Rating Curve= 0 ,0
Exp/Cntr=0.3,0.1

Type RM Length L Ch R = 1 ,58202   ,568,568,568
BEGIN DESCRIPTION:
Mapping XS 9d56e5a4
END DESCRIPTION:
XS GIS Cut Line= 4
      2044218.06     13478067.58      2044343.31     13477717.74
      2044334.68     13476262.11      2044075.54     13476002.98
#Sta/Elev= 30
  3815.2  468.08  3852.9  467.36    3871  467.83  3892.3  466.71  4119.1  463.39
  4383.8  462.87  4409.5  463.28  4469.5  461.97  4809.5  461.18  4919.5  458.88
  4969.5  459.75  4986.5  458.05    4987  457.25    4992  457.25  4992.5  458.05
  5019.5  459.71  5119.5  461.81  5169.5  463.83  5289.5  471.04  5459.5  478.99
  5579.5  479.01  5647.2  476.62  5682.6   477.1  5717.9  475.61  5767.4  475.91
  5859.4  473.57  5915.9  472.72  5937.1  473.33  5958.4   472.1  6008.9  471.33
#Mann= 4 ,-1 , 0
  3815.2     .05       0  4383.8      .1       0  4986.5     .07       0
  4992.5      .1       0
Bank Sta=4986.5,4992.5
XS Rating Curve= 0 ,0
Exp/Cntr=0.3,0.1

Type RM Length L Ch R = 1 ,57634   ,364,364,364
BEGIN DESCRIPTION:
Mapping XS 248e7824
END DESCRIPTION:
XS GIS Cut Line= 4
      2044658.63     13478054.65      2044891.87     13477380.83
      2044736.38     13476180.05      2044313.12     13476097.99
#Sta/Elev= 30
  3735.8  464.46    3922  461.63  4063.5  460.56  4084.6  459.74  4148.1  460.03
  4269.7  459.17  4778.7  458.38  4787.5  458.86  4908.5  456.34  4958.9  457.07
  4996.2  455.83  4996.7  455.03  5001.7  455.03  5002.2  455.83  5011.4  456.63
  5059.7   456.5  5100.1  457.81  5140.4  459.85  5239.2  466.76  5397.7  474.33
    5453  475.57  5483.2  475.27  5513.5  476.47    5574  474.71  5604.2  474.85
  5671.2  472.55  5766.5  471.44  5926.8  470.61  6076.9  472.02  6090.8   471.6
#Mann= 4 ,-1 , 0
  3735.8     .05       0  4269.7      .1       0  4996.2     .07       0
  5002.2      .1       0
Bank Sta=4996.2,5002.2
XS Rating Curve= 0 ,0
Exp/Cntr=0.3,0.1

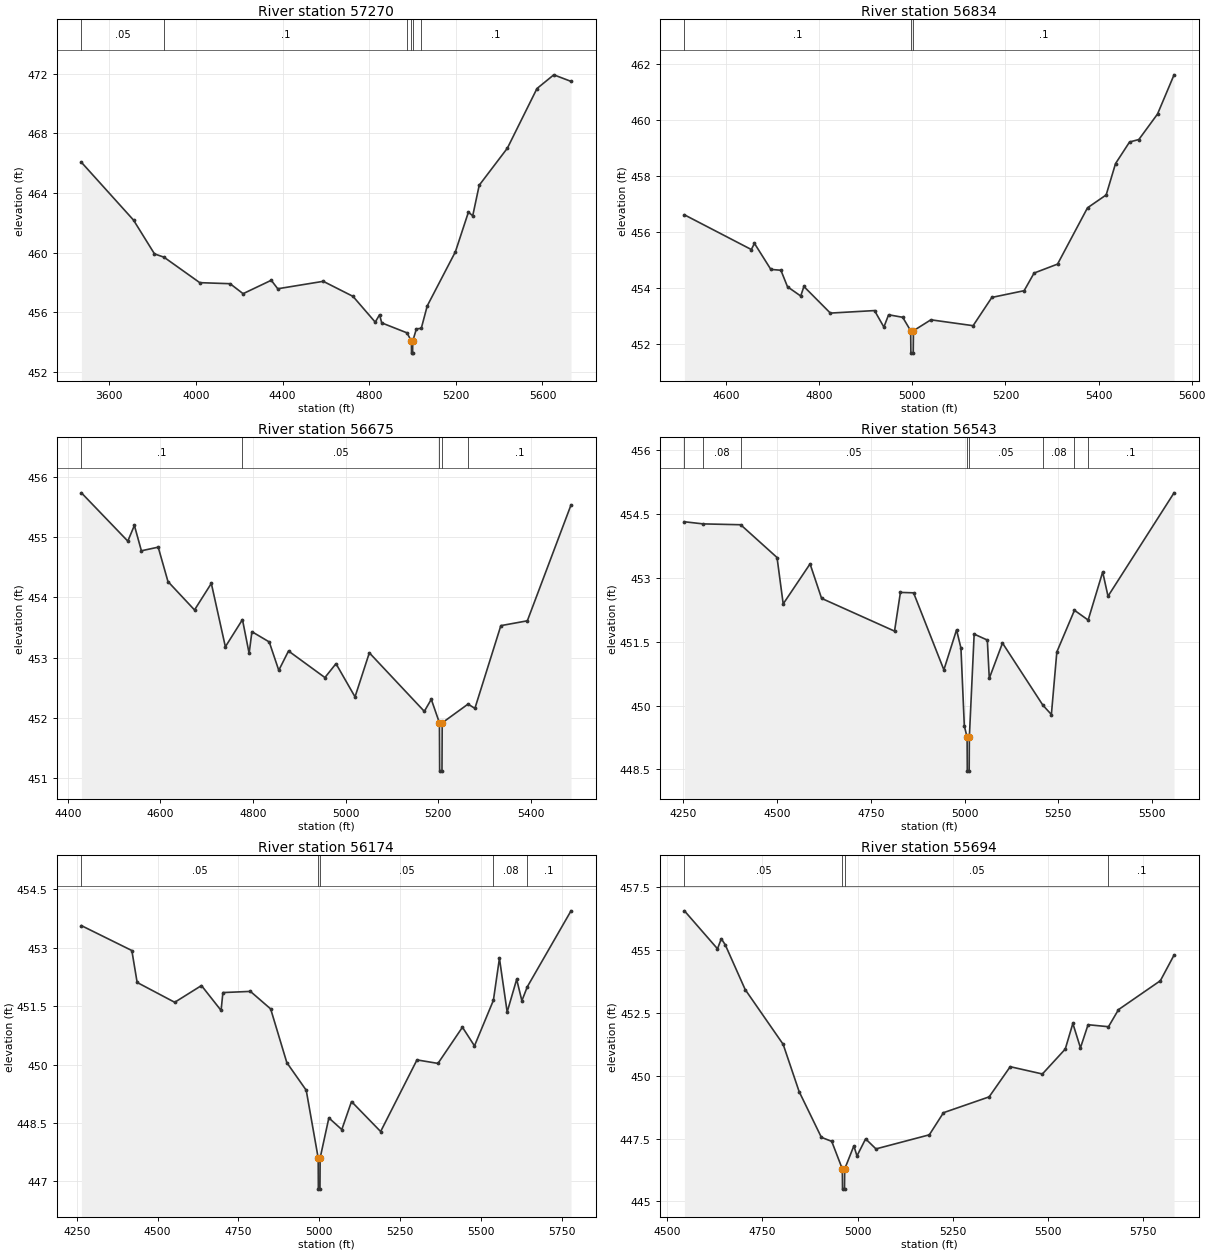
Type RM Length L Ch R = 1 ,57270   ,436,436,436
BEGIN DESCRIPTION:
Mapping XS 6a0834d2
END DESCRIPTION:
XS GIS Cut Line= 4
      2044922.12     13478266.28      2045112.16     13477890.52
      2045163.99     13476335.54      2044952.33     13476145.48
#Sta/Elev= 30
  3470.6  466.06  3711.3  462.18  3808.2  459.91  3852.1  459.69  4017.3  457.98
  4157.4  457.91  4217.4  457.24  4347.5  458.14  4377.5  457.57  4587.6  458.07
    4725  457.06  4827.7  455.33  4847.7  455.83  4857.7  455.28  4974.5  454.61
  4994.8  454.05  4995.3  453.25  5000.3  453.25  5000.8  454.05  5017.8  454.88
  5040.3  454.91  5067.9  456.42  5197.9  460.05    5258  462.71    5278  462.47
    5308  464.52  5438.1  467.01  5574.7  471.01  5652.4  471.93    5732  471.49
#Mann= 6 ,-1 , 0
  3470.6     .05       0  3852.1      .1       0  4974.5     .16       0
  4994.8     .07       0  5000.8     .16       0  5040.3      .1       0
Bank Sta=4994.8,5000.8
XS Rating Curve= 0 ,0
Exp/Cntr=0.3,0.1

Type RM Length L Ch R = 1 ,56834   ,159,159,159
BEGIN DESCRIPTION:
Mapping XS 915e7845
END DESCRIPTION:
XS GIS Cut Line= 4
      2045318.22     13477160.69      2045569.95     13476933.91
      2045510.27     13476466.25      2045269.64     13476447.82
#Sta/Elev= 30
  4510.6  456.63  4654.3  455.39    4661  455.61  4696.2  454.68  4717.8  454.65
    4732  454.06  4760.4  453.73  4767.2  454.07    4824  453.12  4918.9  453.21
    4939  452.62  4949.1  453.06  4979.4  452.97  4996.5  452.49    4997  451.69
    5002  451.69  5002.5  452.49  5039.9  452.88  5130.6  452.67  5170.9  453.68
  5240.2  453.92  5261.6  454.55    5312  454.87  5376.3  456.88  5416.4  457.34
  5436.5  458.46  5466.6  459.23  5486.6  459.32  5526.7  460.23  5562.2  461.63
#Mann= 3 ,-1 , 0
  4510.6      .1       0  4996.5     .07       0  5002.5      .1       0
Bank Sta=4996.5,5002.5
XS Rating Curve= 0 ,0
Exp/Cntr=0.3,0.1

Type RM Length L Ch R = 1 ,56675   ,132,132,132
BEGIN DESCRIPTION:
Mapping XS 0868b5ad
END DESCRIPTION:
XS GIS Cut Line= 4
      2045459.71     13477289.06      2045664.35     13476974.06
      2045761.78     13476570.34      2045558.68     13476398.48
#Sta/Elev= 30
  4429.4  455.73  4529.6  454.93  4543.8  455.19  4558.9  454.77  4595.2  454.83
  4616.3  454.26  4673.6  453.79  4709.9  454.23  4740.2  453.18  4777.1  453.63
  4791.5  453.07  4797.5  453.43  4834.9  453.26  4855.5  452.79  4876.5  453.11
  4955.1  452.67    4979   452.9  5020.1  452.35    5051  453.08  5169.7  452.11
  5184.7  452.31  5202.3  451.92  5202.8  451.12  5207.8  451.12  5208.3  451.92
    5264  452.23  5278.9  452.16  5334.9  453.53  5392.1  453.61  5486.4  455.53
#Mann= 5 ,-1 , 0
  4429.4      .1       0  4777.1     .05       0  5202.3     .04       0
  5208.3     .05       0    5264      .1       0
Bank Sta=5202.3,5208.3
XS Rating Curve= 0 ,0
Exp/Cntr=0.3,0.1

Type RM Length L Ch R = 1 ,56543   ,369,369,369
BEGIN DESCRIPTION:
Mapping XS d879fd7e
END DESCRIPTION:
XS GIS Cut Line= 4
      2045668.02     13477492.25      2045789.13     13476932.83
      2045887.87     13476557.39      2045615.93     13476346.37
#Sta/Elev= 30
  4253.6  454.32  4303.3  454.27  4403.5  454.25  4500.4  453.48  4516.8  452.39
  4588.4  453.33  4619.1  452.52  4813.5  451.75  4829.2  452.66  4864.3  452.65
    4945  450.84  4978.8  451.78  4990.5  451.35  4999.5  449.52  5006.9  449.26
  5007.4  448.46  5012.4  448.46  5012.9  449.26  5025.7  451.68  5060.8  451.54
    5066  450.64  5101.2  451.47  5208.8  450.01  5231.5  449.79    5246  451.26
    5293  452.24  5329.5  452.01  5368.2  453.14  5382.4  452.57  5558.4     455
#Mann= 8 ,-1 , 0
  4253.6     .05       0  4303.3     .08       0  4403.5     .05       0
  5006.9     .03       0  5012.9     .05       0  5208.8     .08       0
    5293     .05       0  5329.5      .1       0
Bank Sta=5006.9,5012.9
XS Rating Curve= 0 ,0
Exp/Cntr=0.3,0.1

Type RM Length L Ch R = 1 ,56174   ,480,480,480
BEGIN DESCRIPTION:
Mapping XS ba9f275e
END DESCRIPTION:
XS GIS Cut Line= 4
      2045949.28     13477460.95      2046191.69     13476995.76
      2046197.12     13476538.95       2045704.5     13476335.97
#Sta/Elev= 30
  4264.2  453.57  4420.2  452.93  4436.6  452.11  4552.8   451.6  4635.5  452.03
  4696.2  451.39  4701.8  451.85  4786.9  451.88  4849.5  451.43  4899.5  450.05
  4959.5  449.34  4996.5   447.6    4997   446.8    5002   446.8  5002.5   447.6
  5029.5  448.63  5069.5  448.33  5099.5  449.05  5189.6  448.28    5302  450.12
  5366.9  450.03  5442.6  450.96  5479.8  450.48  5538.3  451.65    5557  452.73
  5580.9  451.35  5610.3  452.19  5626.4  451.64  5643.3     452  5778.4  453.95
#Mann= 5 ,-1 , 0
  4264.2     .05       0  4996.5     .03       0  5002.5     .05       0
  5538.3     .08       0  5643.3      .1       0
Bank Sta=4996.5,5002.5
XS Rating Curve= 0 ,0
Exp/Cntr=0.3,0.1

Type RM Length L Ch R = 1 ,55694   ,323,323,323
BEGIN DESCRIPTION:
Mapping XS f43567ff
END DESCRIPTION:
XS GIS Cut Line= 4
      2046688.85     13476760.41      2046640.91     13476505.31
      2046314.31     13476306.74      2045669.02     13476286.51
#Sta/Elev= 30
  4544.8  456.56  4631.7  455.05  4641.8  455.45  4652.1  455.21  4704.5  453.43
  4804.4  451.25  4846.4  449.37  4904.9  447.55  4932.1  447.39    4960  446.29
  4960.5  445.49  4965.7  445.49  4966.2  446.29  4990.3  447.21  4998.5  446.81
  5021.2  447.49  5048.4  447.09  5188.7  447.65  5225.9  448.53    5346  449.16
  5401.4  450.36    5486  450.07  5546.1  451.06  5566.1  452.08  5586.1  451.11
  5606.1  452.03  5659.8  451.95  5686.1  452.63  5796.2  453.78  5832.2   454.8
#Mann= 4 ,-1 , 0
  4544.8     .05       0    4960     .03       0  4966.2     .05       0
  5659.8      .1       0
Bank Sta=4960,4966.2
XS Rating Curve= 0 ,0
Exp/Cntr=0.3,0.1

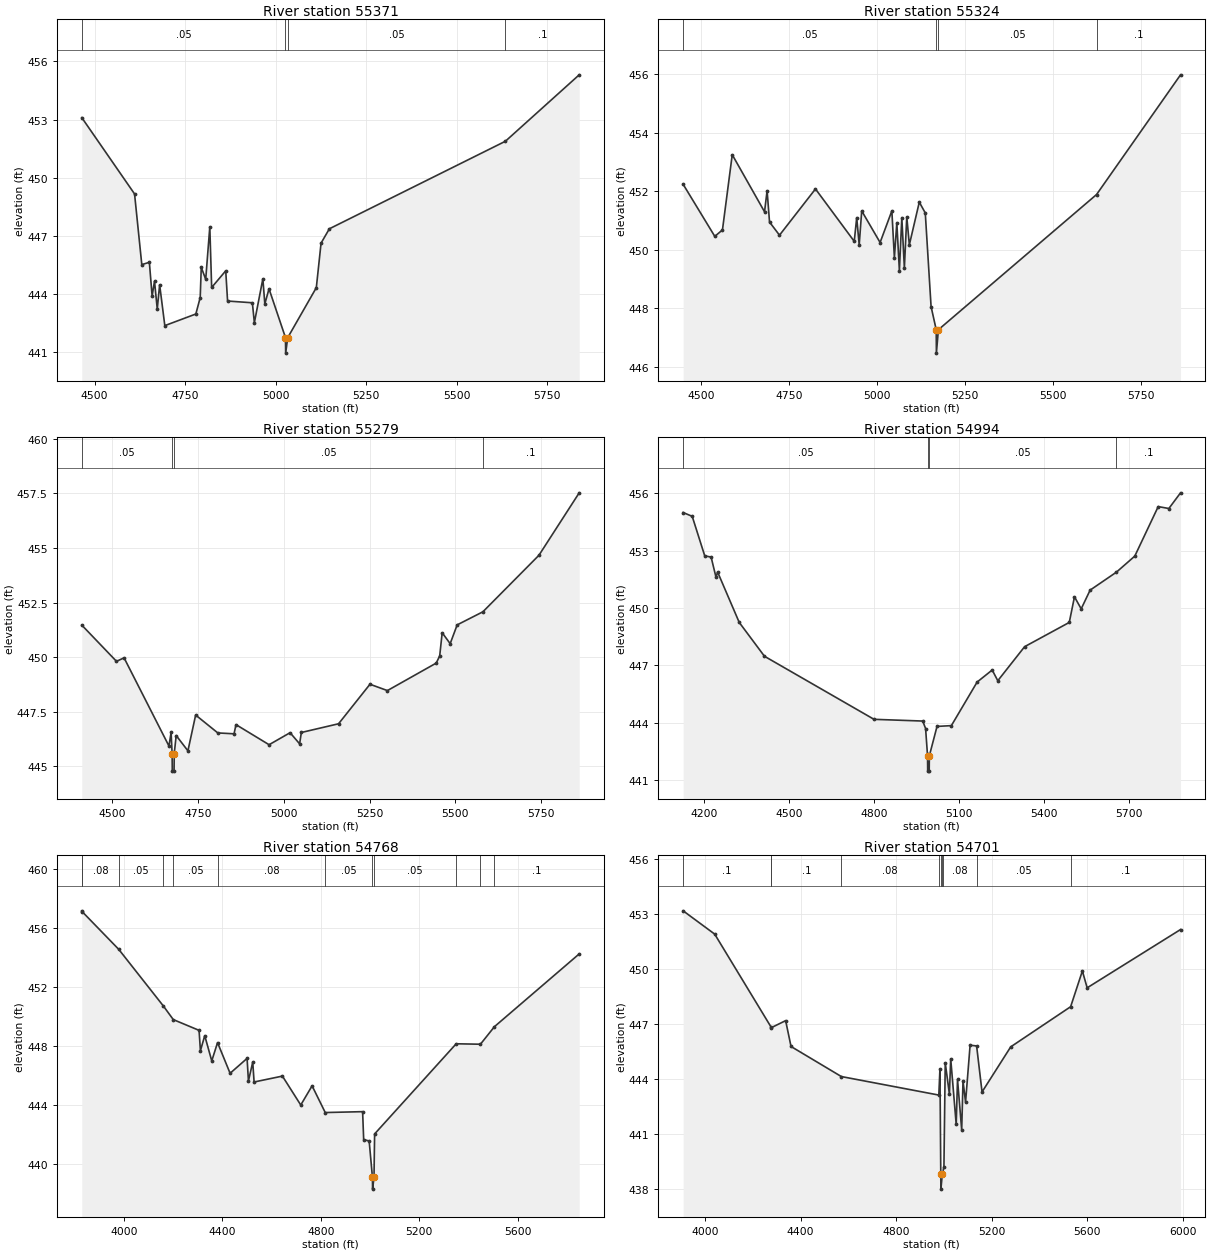
Type RM Length L Ch R = 1 ,55371   ,47,47,47
BEGIN DESCRIPTION:
Mapping XS e4fdacf6
END DESCRIPTION:
XS GIS Cut Line= 6
      2046730.99     13476528.13      2046522.64     13476260.09
       2046474.9     13476095.16      2046411.96     13476101.67
      2046370.73     13476158.09      2045649.89     13476247.41
#Sta/Elev= 30
  4464.7   453.1  4610.5  449.16  4630.5  445.51  4651.4  445.63    4659  443.89
  4665.6  444.65  4673.2  443.22  4679.8  444.47  4694.1  442.36  4779.8  442.96
  4791.9  443.81  4794.8  445.37  4807.1  444.75  4818.4  447.46  4823.5  444.33
  4862.4  445.19  4867.5  443.63    4936  443.54  4941.5  442.51    4965  444.78
  4970.4  443.48    4982  444.26  5027.5  441.74    5028  440.94  5033.7  441.74
  5112.7  444.32  5125.8  446.62  5148.7  447.36  5635.1  451.88    5839  455.31
#Mann= 4 ,-1 , 0
  4464.7     .05       0  5027.5     .03       0  5033.7     .05       0
  5635.1      .1       0
Bank Sta=5027.5,5033.7
XS Rating Curve= 0 ,0
Exp/Cntr=0.3,0.1

Type RM Length L Ch R = 1 ,55324   ,45,45,45
BEGIN DESCRIPTION:
Mapping XS 2fb29b3a
END DESCRIPTION:
XS GIS Cut Line= 6
      2046740.72     13476487.91      2046551.94     13476240.55
      2046468.39     13476052.84      2046414.13      13476048.5
      2046341.43     13476125.54      2045621.16     13476213.57
#Sta/Elev= 30
  4448.4  452.24  4538.4  450.46  4560.2  450.68    4588  453.25  4679.8   451.3
  4687.1  452.02    4694  450.95  4722.3   450.5  4824.6  452.08  4934.8  450.29
  4941.8   451.1  4948.9  450.17    4956  451.33  5008.3  450.25  5041.7  451.33
  5048.9  449.73  5055.8  450.93  5063.1  449.29    5070   451.1  5077.3  449.38
  5084.1  451.13  5091.4  450.17  5119.7  451.63  5136.7  451.26  5153.2  448.06
  5167.8  447.27  5168.3  446.47    5174  447.27  5623.6  451.89  5862.3  455.98
#Mann= 4 ,-1 , 0
  4448.4     .05       0  5167.8     .03       0    5174     .05       0
  5623.6      .1       0
Bank Sta=5167.8,5174
XS Rating Curve= 0 ,0
Exp/Cntr=0.3,0.1

Type RM Length L Ch R = 1 ,55279   ,285,285,285
BEGIN DESCRIPTION:
Mapping XS fa57f35e
END DESCRIPTION:
XS GIS Cut Line= 6
      2046757.03     13476459.77      2046649.59     13476277.45
       2046583.4     13476231.87      2046524.81     13476036.56
      2046452.11     13476005.09      2045595.11     13476151.07
#Sta/Elev= 30
  4411.5  451.47  4512.6  449.81  4534.7  449.97  4665.5  445.93  4671.8  446.55
  4674.7  445.58  4675.2  444.78  4680.4  444.78  4680.9  445.58  4686.6  446.41
  4720.8  445.71  4743.3  447.35  4807.9  446.53  4855.2  446.49  4860.9  446.91
  4957.3  445.99  5018.5  446.54  5046.3  446.03  5051.3  446.55  5159.8  446.95
  5251.3  448.76  5302.1  448.47  5444.4  449.73  5454.5  450.06  5461.7  451.12
    5485  450.62  5505.4  451.48  5580.4  452.08  5743.7  454.67    5861  457.53
#Mann= 4 ,-1 , 0
  4411.5     .05       0  4674.7     .03       0  4680.9     .05       0
  5580.4      .1       0
Bank Sta=4674.7,4680.9
XS Rating Curve= 0 ,0
Exp/Cntr=0.3,0.1

Type RM Length L Ch R = 1 ,54994   ,226,226,226
BEGIN DESCRIPTION:
Mapping XS 5c53764b
END DESCRIPTION:
XS GIS Cut Line= 4
      2046959.68     13476473.95      2046627.72     13475767.03
      2046358.27     13475730.22      2045691.45     13475942.74
#Sta/Elev= 30
  4127.3  454.99  4159.3  454.79  4203.5  452.72  4225.9  452.66  4243.2   451.6
  4248.7  451.88    4325  449.24  4413.9  447.47    4800  444.17  4971.6  444.08
  4981.7  443.69  4988.6  442.26  4989.1  441.46  4994.4  441.46  4994.9  442.26
    5022   443.8  5072.5  443.84  5163.3  446.12  5216.4  446.75  5236.1  446.19
  5330.6  447.97    5488  449.24  5506.3  450.58    5530  449.95  5561.5  450.93
  5654.2  451.87  5718.9  452.71  5801.4   455.3  5838.9   455.2  5880.1  456.02
#Mann= 4 ,-1 , 0
  4127.3     .05       0  4988.6     .03       0  4994.9     .05       0
  5654.2      .1       0
Bank Sta=4988.6,4994.9
XS Rating Curve= 0 ,0
Exp/Cntr=0.3,0.1

Type RM Length L Ch R = 1 ,54768   ,67,67,67
BEGIN DESCRIPTION:
Mapping XS a76cc14b
END DESCRIPTION:
XS GIS Cut Line= 5
      2047069.09     13476601.63      2046676.59     13475741.38
      2046593.95     13475567.77      2046560.62     13475502.49
      2045750.04       13475550.
#Sta/Elev= 30
  3827.7  457.15  3830.1  457.08    3978  454.54    4160  450.69  4199.8  449.78
  4304.7  449.05  4310.2  447.67  4327.8  448.69  4356.3  446.98  4379.9  448.22
  4430.9  446.14    4500  447.15  4505.5  445.62    4523   446.9  4528.5  445.55
  4643.7  445.95  4718.3  443.99  4764.4  445.29  4817.9  443.48  4969.9  443.54
  4974.2  441.65  4996.5  441.55  5009.9  439.09  5010.4  438.29  5016.2  439.09
  5018.7  442.03  5350.5  448.14  5449.1  448.11  5506.1   449.3  5850.8  454.23
#Mann= 12 ,-1 , 0
  3827.7     .05       0  3830.1     .08       0    3978     .05       0
    4160     .08       0  4199.8     .05       0  4379.9     .08       0
  4817.9     .05       0  5009.9     .04       0  5016.2     .05       0
  5350.5     .08       0  5449.1     .05       0  5506.1      .1       0
Bank Sta=5009.9,5016.2
XS Rating Curve= 0 ,0
Exp/Cntr=0.3,0.1

Type RM Length L Ch R = 1 ,54701   ,347,347,347
BEGIN DESCRIPTION:
Mapping XS 0ed2683e
END DESCRIPTION:
XS GIS Cut Line= 6
      2047220.13     13476414.12      2046709.92     13475635.13
       2046650.9     13475519.85       2046638.4     13475510.13
      2046593.95      13475413.6      2045694.06     13475440.13
#Sta/Elev= 30
    3908  453.18  4040.2  451.91  4277.2  446.82  4277.8  446.81  4337.3  447.19
  4359.9  445.78  4570.7  444.14  4978.8  443.13  4983.5  444.55    4987   438.8
  4987.5     438  4993.3   438.8  4994.5  438.87  5000.2  439.22  5005.7  444.89
  5023.1  443.19  5028.6  445.11  5051.6  441.53  5057.1  443.98  5074.6  441.23
  5080.1   443.9  5090.8  442.75  5109.8  445.85  5137.1  445.81  5159.8   443.3
  5279.9  445.76  5530.8  447.95    5580   449.9    5600  448.98  5991.1  452.16
#Mann= 10 ,-1 , 0
    3908      .1       0  4277.2     .08       0  4277.8      .1       0
  4570.7     .08       0  4978.8     .05       0    4987     .07       0
  4993.3     .05       0  4994.5     .08       0  5137.1     .05       0
  5530.8      .1       0
Bank Sta=4987,4993.3
XS Rating Curve= 0 ,0
Exp/Cntr=0.3,0.1