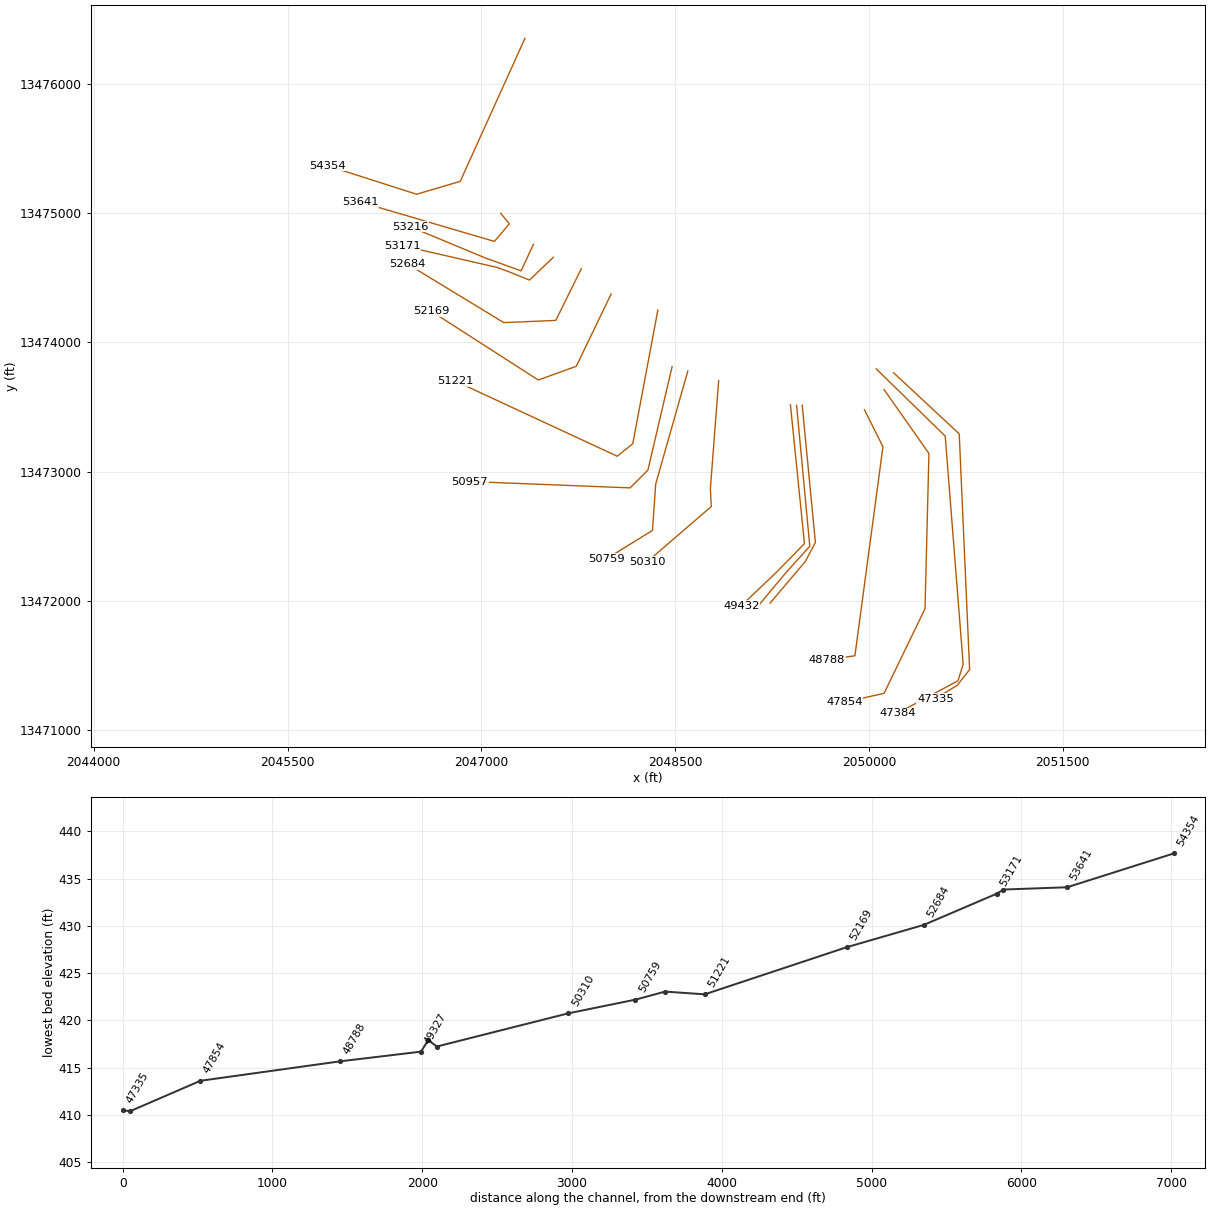
HEC-RAS study LAKE Br.prj: LAKE Br Base Level Engineering

--- LAKE Br.g01 (geometry) --- (continued)

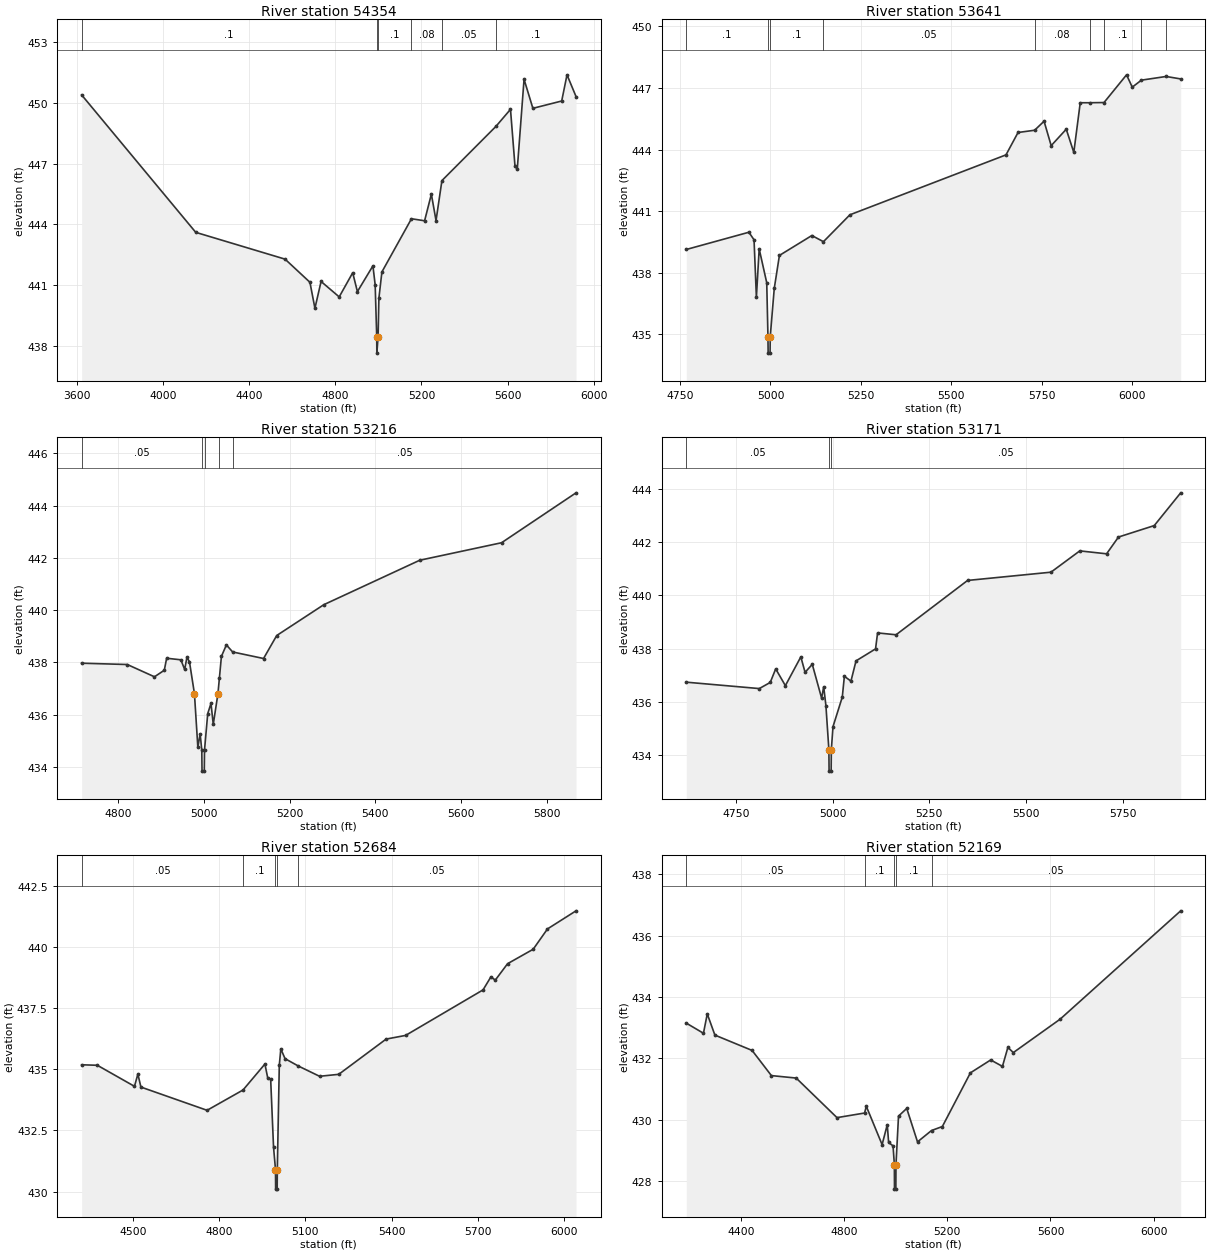
Type RM Length L Ch R = 1 ,54354   ,713,713,713
BEGIN DESCRIPTION:
Mapping XS 7aff3538
END DESCRIPTION:
XS GIS Cut Line= 4
      2047337.31     13476355.09      2046836.62     13475247.28
      2046499.16     13475147.46      2045805.14     13475369.83
#Sta/Elev= 30
  3621.8  450.38  4151.8  443.61  4566.7  442.29  4682.2  441.15  4705.4  439.87
    4734  441.19  4818.1  440.43  4880.9  441.62  4902.7  440.69  4974.8  441.96
  4985.2  441.03  4992.5  438.46    4993  437.66  4998.8  438.46  5002.5  440.36
  5016.5  441.66  5153.8  444.28  5214.8  444.18  5246.3  445.49  5267.9  444.19
  5295.3  446.16  5546.2  448.83  5613.8  449.67  5634.8  446.86  5645.3  446.73
  5676.8  451.15  5717.8  449.72  5851.6  450.08  5876.3  451.37  5918.2   450.3
#Mann= 6 ,-1 , 0
  3621.8      .1       0  4992.5     .07       0  4998.8      .1       0
  5153.8     .08       0  5295.3     .05       0  5546.2      .1       0
Bank Sta=4992.5,4998.8
XS Rating Curve= 0 ,0
Exp/Cntr=0.3,0.1

Type RM Length L Ch R = 1 ,53641   ,425,425,425
BEGIN DESCRIPTION:
Mapping XS c0520531
END DESCRIPTION:
XS GIS Cut Line= 4
        2047150.     13474999.99      2047216.61     13474918.51
      2047101.16     13474782.22      2046061.25      13475087.7
#Sta/Elev= 30
  4767.2  439.13  4940.3  439.97  4954.6   439.6  4961.1   436.8  4968.8  439.16
  4989.7  437.51  4993.1  434.88  4993.6  434.08  4998.9  434.08  4999.4  434.88
  5010.5  437.23  5024.8  438.84  5114.5  439.81  5146.6  439.51  5219.8  440.82
  5651.6  443.74  5684.9  444.83  5730.8  444.94  5756.9  445.38  5776.6  444.19
  5818.3  444.99  5839.2  443.86    5857  446.28  5883.2  446.28  5922.8  446.29
  5985.1  447.64  6000.9  447.04  6026.2  447.38  6094.6  447.56  6134.9  447.44
#Mann= 9 ,-1 , 0
  4767.2      .1       0  4993.1     .07       0  4999.4      .1       0
  5146.6     .05       0  5730.8     .08       0  5883.2     .05       0
  5922.8      .1       0  6026.2     .05       0  6094.6      .1       0
Bank Sta=4993.1,4999.4
XS Rating Curve= 0 ,0
Exp/Cntr=0.3,0.1

Type RM Length L Ch R = 1 ,53216   ,45,45,45
BEGIN DESCRIPTION:
Mapping XS 7e1c98e6
END DESCRIPTION:
XS GIS Cut Line= 4
      2047403.08     13474760.02      2047307.75     13474553.92
      2047027.37     13474655.49      2046448.74     13474896.23
#Sta/Elev= 30
  4715.5  437.97  4821.9  437.92  4885.2  437.45  4908.1   437.7  4913.6  438.16
  4946.7   438.1  4955.6  437.73  4960.9   438.2  4966.8  438.02 4978.35436.8044
  4986.3  434.75  4991.6  435.27  4995.5  434.64    4996  433.84  5001.3  433.84
  5001.8  434.64  5009.3  436.04  5016.9  436.43  5022.2  435.63 5033.12436.8042
  5036.5   437.4  5041.2  438.23  5052.8  438.67  5067.4   438.4  5139.4  438.15
  5170.1  439.03  5279.9  440.21  5503.3  441.91    5694  442.58  5867.5  444.49
#Mann= 5 ,-1 , 0
  4715.5     .05       0  4995.5     .03       0  5001.8     .05       0
  5036.5      .1       0  5067.4     .05       0
Bank Sta=4978.35,5033.12
XS Rating Curve= 0 ,0
Exp/Cntr=0.3,0.1

Type RM Length L Ch R = 1 ,53171   ,487,487,487
BEGIN DESCRIPTION:
Mapping XS 1dd6ecb3
END DESCRIPTION:
XS GIS Cut Line= 5
      2047557.15     13474659.33      2047371.99     13474482.74
      2047220.95     13474544.37      2047121.12     13474580.83
       2046388.4     13474748.78
#Sta/Elev= 30
  4622.2  436.74  4810.7   436.5    4839  436.73  4853.1  437.24  4878.1  436.61
    4918  437.69    4929  437.11  4947.6  437.41  4971.7  436.14  4977.1  436.57
  4982.8  435.86  4990.5   434.2    4991   433.4  4996.3   433.4  4996.8   434.2
  5001.1  435.07  5025.1  436.18  5030.5  436.96  5047.5  436.78  5060.6  437.54
    5111  437.99  5116.3  438.59    5164  438.52  5348.7  440.56  5564.1  440.87
  5638.6  441.67  5707.8  441.56  5738.5  442.19  5830.9  442.62  5899.2  443.85
#Mann= 3 ,-1 , 0
  4622.2     .05       0  4990.5     .03       0  4996.8     .05       0
Bank Sta=4990.5,4996.8
XS Rating Curve= 0 ,0
Exp/Cntr=0.3,0.1

Type RM Length L Ch R = 1 ,52684   ,515,515,515
BEGIN DESCRIPTION:
Mapping XS d51e5c03
END DESCRIPTION:
XS GIS Cut Line= 4
      2047773.41     13474570.42      2047575.98     13474170.37
      2047173.64     13474153.45      2046430.21     13474605.91
#Sta/Elev= 30
  4322.4  435.18    4377  435.16  4506.1   434.3    4518   434.8  4528.5  434.27
  4758.6  433.32  4883.6  434.15  4959.7  435.21  4969.7  434.63  4979.7  434.59
  4989.7  431.81  4996.5   430.9    4997   430.1  5002.3   430.1  5002.8   430.9
  5009.7  435.16    5015  435.83  5029.7  435.43  5075.8  435.13  5149.8  434.71
  5216.4  434.79  5381.2  436.23  5448.9  436.38  5718.2  438.24  5745.4  438.77
  5760.8  438.64  5803.5  439.31  5892.5   439.9  5942.2  440.73  6041.5  441.47
#Mann= 5 ,-1 , 0
  4322.4     .05       0  4883.6      .1       0  4996.5     .07       0
  5002.8      .1       0  5075.8     .05       0
Bank Sta=4996.5,5002.8
XS Rating Curve= 0 ,0
Exp/Cntr=0.3,0.1

Type RM Length L Ch R = 1 ,52169   ,948,948,948
BEGIN DESCRIPTION:
Mapping XS 5b5d83a2
END DESCRIPTION:
XS GIS Cut Line= 4
      2048004.49     13474374.88      2047734.66     13473815.16
      2047440.61     13473708.83       2046613.5     13474240.68
#Sta/Elev= 30
  4187.7  433.15  4254.2  432.82    4269  433.45  4298.6  432.76  4442.9  432.26
  4517.7  431.44  4613.8  431.36  4772.1  430.07  4879.1  430.22  4885.8  430.44
  4947.1  429.19  4967.1  429.84  4972.4  429.26  4989.5  429.15  4994.6  428.54
  4995.1  427.74  5000.4  427.74  5000.9  428.54  5010.7  430.12  5042.6  430.37
  5084.4  429.28  5138.7  429.65  5180.7  429.78  5289.6  431.53  5368.2  431.95
  5413.8  431.74  5434.9  432.36    5456  432.19  5637.7  433.28  6105.1  436.81
#Mann= 5 ,-1 , 0
  4187.7     .05       0  4879.1      .1       0  4994.6     .07       0
  5000.9      .1       0  5138.7     .05       0
Bank Sta=4994.6,5000.9
XS Rating Curve= 0 ,0
Exp/Cntr=0.3,0.1

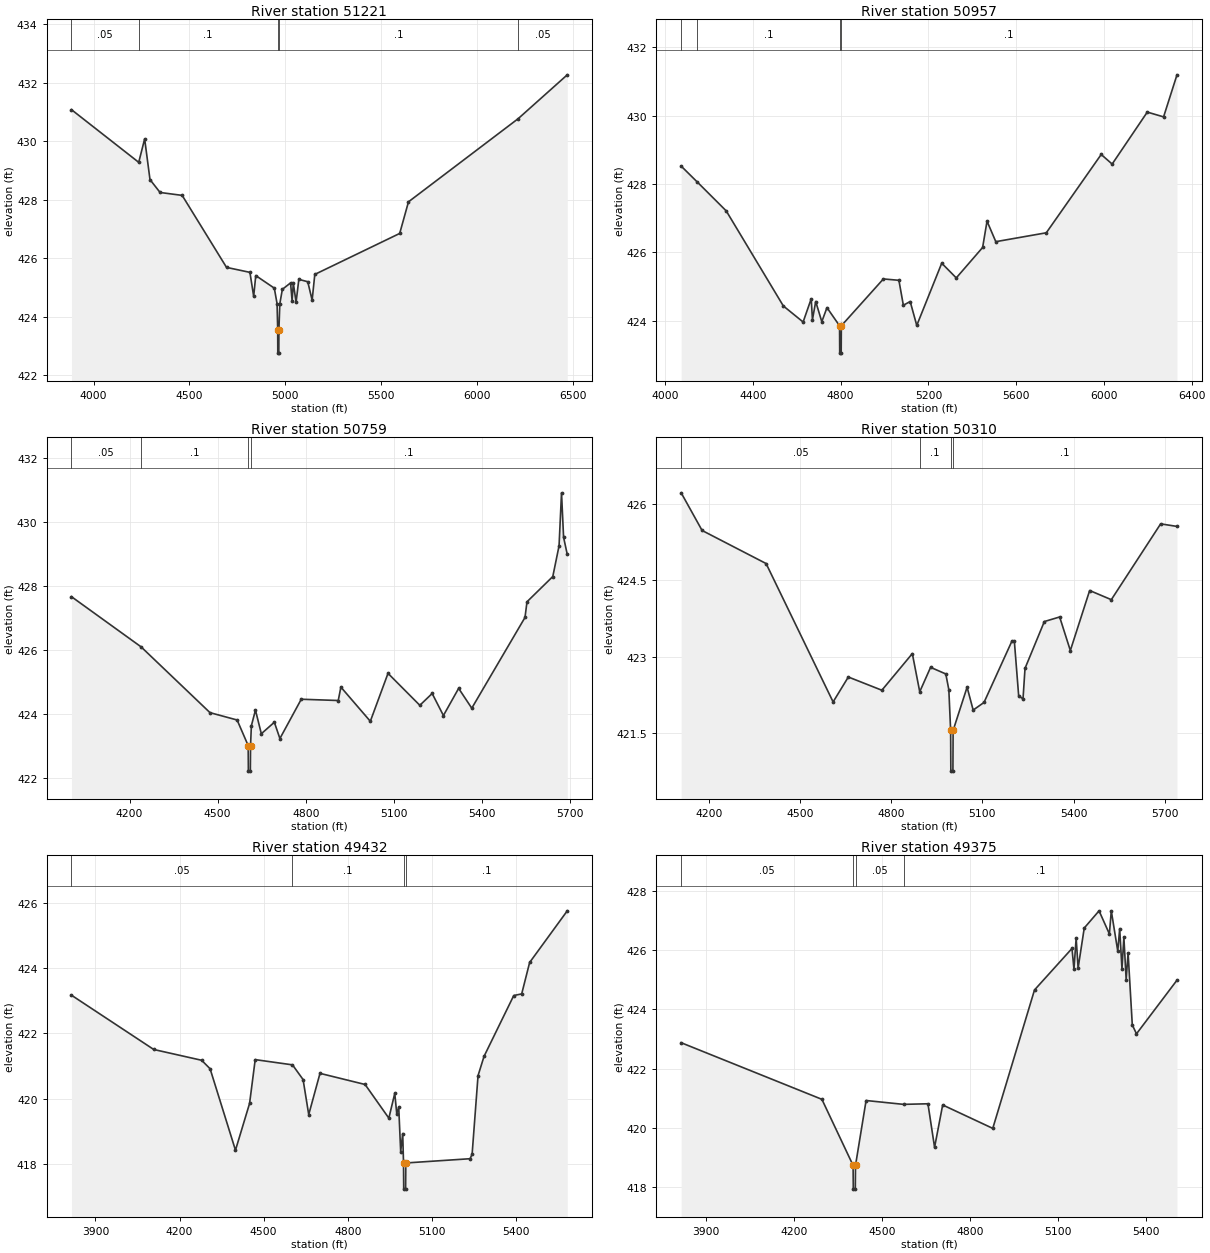
Type RM Length L Ch R = 1 ,51221   ,264,264,264
BEGIN DESCRIPTION:
Mapping XS 985c1df9
END DESCRIPTION:
XS GIS Cut Line= 4
      2048365.94     13474250.47      2048171.95     13473215.12
       2048051.5     13473118.55      2046800.02     13473699.99
#Sta/Elev= 30
  3884.7  431.08  4235.8  429.28  4266.7  430.08  4294.6  428.69  4347.2  428.25
  4462.5  428.15    4694  425.69  4816.1  425.52  4835.7   424.7  4846.6  425.41
  4943.4  424.98  4957.8  424.45  4961.1  423.56  4961.6  422.76  4966.9  422.76
  4967.4  423.56  4972.2  424.45  4985.4  424.94  5028.2  425.16  5036.2  424.55
  5042.6  425.15    5057   424.5  5071.4  425.28  5117.9   425.2  5140.8  424.57
  5154.7  425.45  5597.8  426.85  5643.6  427.93  6215.8  430.77  6472.4  432.27
#Mann= 5 ,-1 , 0
  3884.7     .05       0  4235.8      .1       0  4961.1     .07       0
  4967.4      .1       0  6215.8     .05       0
Bank Sta=4961.1,4967.4
XS Rating Curve= 0 ,0
Exp/Cntr=0.3,0.1

Type RM Length L Ch R = 1 ,50957   ,198,198,198
BEGIN DESCRIPTION:
Mapping XS 619e11b6
END DESCRIPTION:
XS GIS Cut Line= 4
      2048476.21     13473812.22      2048289.13     13473011.13
      2048151.33     13472873.32      2046909.73     13472922.44
#Sta/Elev= 30
  4073.1  428.52  4147.3  428.05  4278.5  427.21  4538.8  424.43    4629  423.96
  4665.9  424.64  4671.5  424.03  4686.4  424.56  4714.1  423.97  4737.7  424.38
  4795.1  423.85  4795.8  423.05  4802.5  423.05  4803.2  423.85  4994.9  425.22
  5065.6  425.18  5085.9  424.45    5117  424.56    5147  423.86  5260.8  425.68
  5327.1  425.25  5447.2  426.14  5467.3  426.91  5507.3  426.31  5737.5  426.57
  5987.7  428.86  6037.7  428.58  6197.8   430.1  6272.1  429.96  6333.2  431.19
#Mann= 4 ,-1 , 0
  4073.1     .05       0  4147.3      .1       0  4795.1     .07       0
  4803.2      .1       0
Bank Sta=4795.1,4803.2
XS Rating Curve= 0 ,0
Exp/Cntr=0.3,0.1

Type RM Length L Ch R = 1 ,50759   ,449,449,449
BEGIN DESCRIPTION:
Mapping XS 50100ddf
END DESCRIPTION:
XS GIS Cut Line= 4
      2048597.73     13473777.48      2048349.39     13472902.84
      2048324.43     13472543.68      2047968.29     13472323.96
#Sta/Elev= 30
  4002.3  427.66  4239.2  426.09  4473.9  424.03  4566.2   423.8  4603.8     423
  4604.5   422.2  4611.2   422.2  4611.9     423  4614.7  423.62  4628.6  424.11
  4648.6  423.37  4692.9  423.73  4711.8  423.22  4784.5  424.45  4910.4  424.41
  4919.4  424.83  5019.6  423.76  5079.8  425.26  5188.1  424.26  5230.1  424.63
  5268.4  423.94  5320.2  424.79  5364.9  424.17  5546.1  427.01  5552.9   427.5
  5640.7  428.29    5662  429.25  5670.4  430.91  5677.4  429.52    5690  428.98
#Mann= 4 ,-1 , 0
  4002.3     .05       0  4239.2      .1       0  4603.8     .07       0
  4611.9      .1       0
Bank Sta=4603.8,4611.9
XS Rating Curve= 0 ,0
Exp/Cntr=0.3,0.1

Type RM Length L Ch R = 1 ,50310   ,878,878,878
BEGIN DESCRIPTION:
Mapping XS 93ab246c
END DESCRIPTION:
XS GIS Cut Line= 4
      2048836.45     13473703.74      2048772.57     13472867.03
      2048779.08     13472728.14      2048283.48     13472301.24
#Sta/Elev= 30
  4108.3  426.22  4177.2  425.48  4387.9  424.83  4608.5  422.11  4658.6   422.6
    4769  422.34  4869.3  423.06  4893.7  422.31  4929.4  422.79  4979.5  422.66
  4989.5  422.35  4995.4  421.55  4996.1  420.75  5002.9  420.75  5003.6  421.55
  5049.6   422.4  5069.6  421.95  5105.3   422.1  5197.5  423.31  5205.1  423.31
  5219.4  422.23  5233.7  422.17  5240.3  422.77  5303.9  423.69  5354.3  423.78
  5389.5  423.12  5453.1   424.3  5524.4  424.12  5686.8  425.61  5740.6  425.56
#Mann= 4 ,-1 , 0
  4108.3     .05       0  4893.7      .1       0  4995.4     .07       0
  5003.6      .1       0
Bank Sta=4995.4,5003.6
XS Rating Curve= 0 ,0
Exp/Cntr=0.3,0.1

Type RM Length L Ch R = 1 ,49432   ,57,57,57
BEGIN DESCRIPTION:
Mapping XS 3f8c5014
END DESCRIPTION:
XS GIS Cut Line= 4
      2049392.01     13473517.04      2049500.65     13472441.68
      2049290.15     13472225.75       2049010.6     13471959.42
#Sta/Elev= 30
  3814.6  423.17  4108.1  421.51    4279  421.18  4309.1  420.92  4399.6  418.43
  4449.9  419.86    4470   421.2    4603  421.04  4640.8  420.59  4660.9  419.52
  4701.1  420.78  4861.9  420.44  4946.7  419.41  4967.8  420.17  4974.8  419.55
  4981.9  419.74  4988.9  418.39  4996.1  418.94    4999  418.04  4999.7  417.24
  5006.5  417.24  5007.2  418.04  5236.5  418.17  5243.7  418.31  5264.8  420.71
  5286.2   421.3  5392.2  423.16  5420.5  423.21  5448.8  424.17  5583.1  425.75
#Mann= 4 ,-1 , 0
  3814.6     .05       0    4603      .1       0    4999     .07       0
  5007.2      .1       0
Bank Sta=4999,5007.2
XS Rating Curve= 0 ,0
Exp/Cntr=0.3,0.1

Type RM Length L Ch R = 1 ,49375   ,48,48,48
BEGIN DESCRIPTION:
Mapping XS 02172303
END DESCRIPTION:
XS GIS Cut Line= 4
      2049439.75     13473512.75      2049541.88     13472421.07
      2049350.91     13472209.48      2049153.27     13471971.91
#Sta/Elev= 30
  3815.9  422.87  4295.7  420.96  4402.1  418.73  4402.8  417.93  4409.6  417.93
  4410.3  418.73  4446.4  420.92    4574  420.79  4657.3  420.81  4679.9  419.34
  4707.5  420.77  4878.3  419.98  5020.6  424.65  5148.4  426.05  5155.1  425.35
  5162.6   426.4  5169.3  425.39  5190.2  426.74  5240.7  427.32  5275.9  426.54
  5282.4  427.32  5304.5  425.96    5311  426.72  5318.8  425.36  5325.3  426.43
  5333.1     425  5339.7   425.9    5354  423.47  5368.3  423.17  5506.4  424.98
#Mann= 4 ,-1 , 0
  3815.9     .05       0  4402.1     .07       0  4410.3     .05       0
    4574      .1       0
Bank Sta=4402.1,4410.3
XS Rating Curve= 0 ,0
Exp/Cntr=0.3,0.1

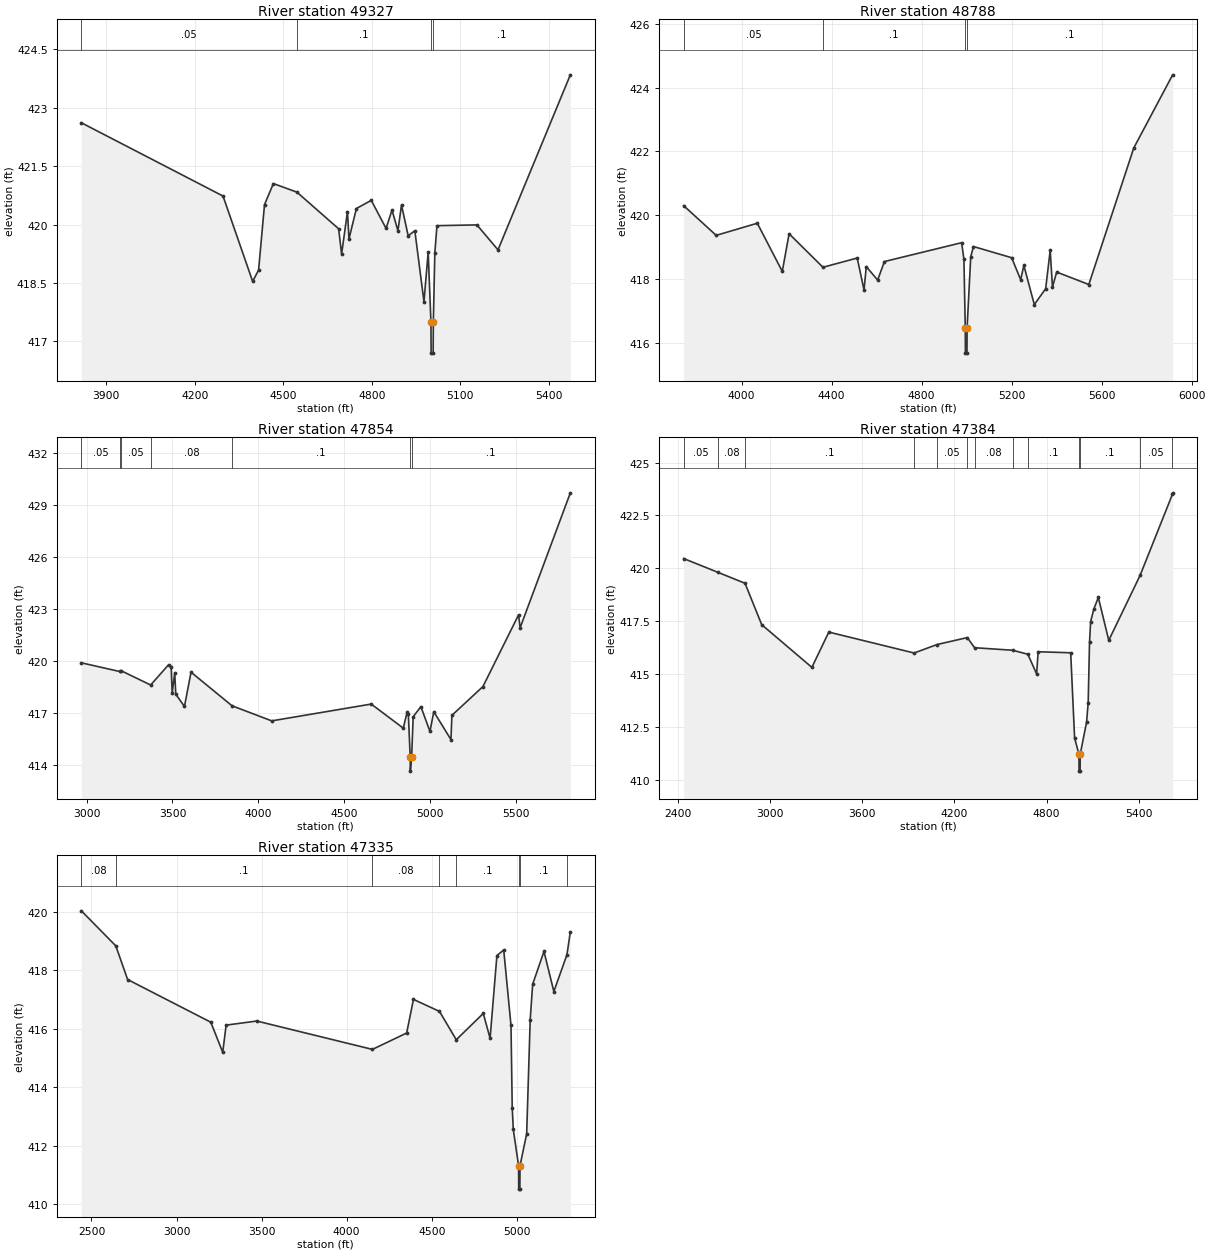
Type RM Length L Ch R = 1 ,49327   ,539,539,539
BEGIN DESCRIPTION:
Mapping XS 695a29d3
END DESCRIPTION:
XS GIS Cut Line= 4
      2049483.15     13473512.74      2049585.28     13472451.45
      2049507.16     13472302.79      2049234.03      13471980.1
#Sta/Elev= 30
  3815.6  422.61  4295.6  420.73    4396  418.54  4416.1  418.83  4436.2  420.51
  4466.3  421.05    4546  420.83  4687.4  419.89  4697.4  419.24  4717.3  420.33
  4722.4  419.63  4747.6  420.41  4797.9  420.62  4848.1   419.9  4868.2  420.37
  4888.3  419.84  4900.4   420.5    4923  419.71  4945.6  419.84  4976.5  418.02
  4990.8  419.29  5000.1   417.5  5000.8   416.7  5007.6   416.7  5008.3   417.5
  5013.3  419.27  5020.6  419.97  5155.9  419.99  5227.4  419.35  5472.5  423.84
#Mann= 4 ,-1 , 0
  3815.6     .05       0    4546      .1       0  5000.1     .07       0
  5008.3      .1       0
Bank Sta=5000.1,5008.3
XS Rating Curve= 0 ,0
Exp/Cntr=0.3,0.1

Type RM Length L Ch R = 1 ,48788   ,934,934,934
BEGIN DESCRIPTION:
Mapping XS 5942e709
END DESCRIPTION:
XS GIS Cut Line= 4
       2049964.9     13473478.33      2050108.13     13473191.87
      2049891.12     13471572.94      2049674.11     13471542.56
#Sta/Elev= 30
  3742.7   420.3  3887.2  419.37  4069.9  419.75  4180.9  418.24  4211.2  419.42
  4361.7  418.37  4513.8  418.66  4544.1  417.66  4554.2  418.39  4604.6  417.97
  4634.9  418.55  4977.9  419.14    4988  418.62    4994  416.48  4994.7  415.68
  5001.5  415.68  5002.2  416.48  5018.3   418.7  5030.4  419.02  5199.9  418.67
  5240.3  417.98  5254.3  418.43  5300.8   417.2  5351.3   417.7  5371.4   418.9
  5381.5  417.75  5400.2  418.22    5543  417.83  5742.9  422.11  5915.5   424.4
#Mann= 4 ,-1 , 0
  3742.7     .05       0  4361.7      .1       0    4994     .07       0
  5002.2      .1       0
Bank Sta=4994,5002.2
XS Rating Curve= 0 ,0
Exp/Cntr=0.3,0.1

Type RM Length L Ch R = 1 ,47854   ,470,470,470
BEGIN DESCRIPTION:
Mapping XS 2485fb95
END DESCRIPTION:
XS GIS Cut Line= 5
      2050116.79     13473634.61      2050464.03     13473139.78
      2050433.65     13471937.52      2050116.81     13471282.14
      2049809.32     13471212.85
#Sta/Elev= 30
  2968.9  419.87  3191.8  419.37  3201.5  419.41  3372.7  418.59  3477.4  419.76
  3492.2  419.65  3498.3  418.13  3513.1  419.29  3519.2  418.06  3569.8  417.35
  3608.2  419.33  3847.3  417.39  4078.4  416.52  4658.5  417.49  4845.5   416.1
  4867.7  417.03  4874.8  416.93  4885.8  414.42  4886.5  413.62  4894.1  414.42
    4903  416.76  4948.1  417.34    5001  415.91  5023.2  417.05  5123.2  415.44
  5128.9  416.84  5309.7   418.5  5517.5  422.64  5526.4  421.89  5819.2  429.68
#Mann= 7 ,-1 , 0
  2968.9     .05       0  3191.8     .08       0  3201.5     .05       0
  3372.7     .08       0  3847.3      .1       0  4885.8     .07       0
  4894.1      .1       0
Bank Sta=4885.8,4894.1
XS Rating Curve= 0 ,0
Exp/Cntr=0.3,0.1

Type RM Length L Ch R = 1 ,47384   ,49,49,49
BEGIN DESCRIPTION:
Mapping XS 6407b8cd
END DESCRIPTION:
XS GIS Cut Line= 5
      2050056.03     13473795.18       2050589.9     13473274.33
      2050728.95     13471507.44       2050688.8      13471379.4
      2050218.32      13471126.8
#Sta/Elev= 30
  2435.5  420.46    2658  419.81  2835.3  419.29  2944.1  417.33    3271  415.31
  3381.3  416.98  3937.2  415.99  4086.3  416.39  4283.7  416.72  4331.1  416.24
  4579.8  416.12  4678.5  415.93  4735.5     415  4745.5  416.05  4957.6     416
    4983  411.97  5011.3   411.2  5012.1   410.4  5018.9   410.4  5019.6   411.2
  5061.1  412.72  5071.5  413.64  5080.3   416.5  5087.6  417.48  5108.5  418.07
  5137.6  418.62  5205.7  416.59  5409.6  419.66  5620.5   423.5  5621.9  423.57
#Mann= 13 ,-1 , 0
  2435.5     .05       0    2658     .08       0  2835.3      .1       0
  3937.2     .08       0  4086.3     .05       0  4283.7      .1       0
  4331.1     .08       0  4579.8     .05       0  4678.5      .1       0
  5011.3     .07       0  5019.6      .1       0  5409.6     .05       0
  5620.5     .08       0
Bank Sta=5011.3,5019.6
XS Rating Curve= 0 ,0
Exp/Cntr=0.3,0.1

Type RM Length L Ch R = 1 ,47335   ,34,34,34
BEGIN DESCRIPTION:
Mapping XS 90eaa2d6
END DESCRIPTION:
XS GIS Cut Line= 5
      2050190.56     13473764.82      2050698.41     13473291.69
      2050778.86     13471466.21      2050682.29     13471343.59
      2050514.12     13471241.61
#Sta/Elev= 30
  2440.5  420.03    2643  418.83  2712.4  417.68  3201.3  416.22  3271.4  415.19
  3291.4  416.12  3471.6  416.26  4151.2  415.29  4352.5  415.85  4392.5     417
  4545.5  416.59  4644.1  415.62  4802.9  416.52  4842.9  415.67    4883   418.5
    4923  418.69  4965.8  416.11    4973   413.3  4979.3  412.55  5010.4  411.31
  5011.2  410.51    5018  410.51  5018.7  411.31  5057.9   412.4  5078.7  416.31
  5093.2  417.52  5159.6  418.64  5217.7  417.27  5294.7  418.53  5314.6  419.31
#Mann= 8 ,-1 , 0
  2440.5     .08       0    2643      .1       0  4151.2     .08       0
  4545.5     .05       0  4644.1      .1       0  5010.4     .07       0
  5018.7      .1       0  5294.7     .05       0
Bank Sta=5010.4,5018.7
XS Rating Curve= 0 ,0
Exp/Cntr=0.3,0.1