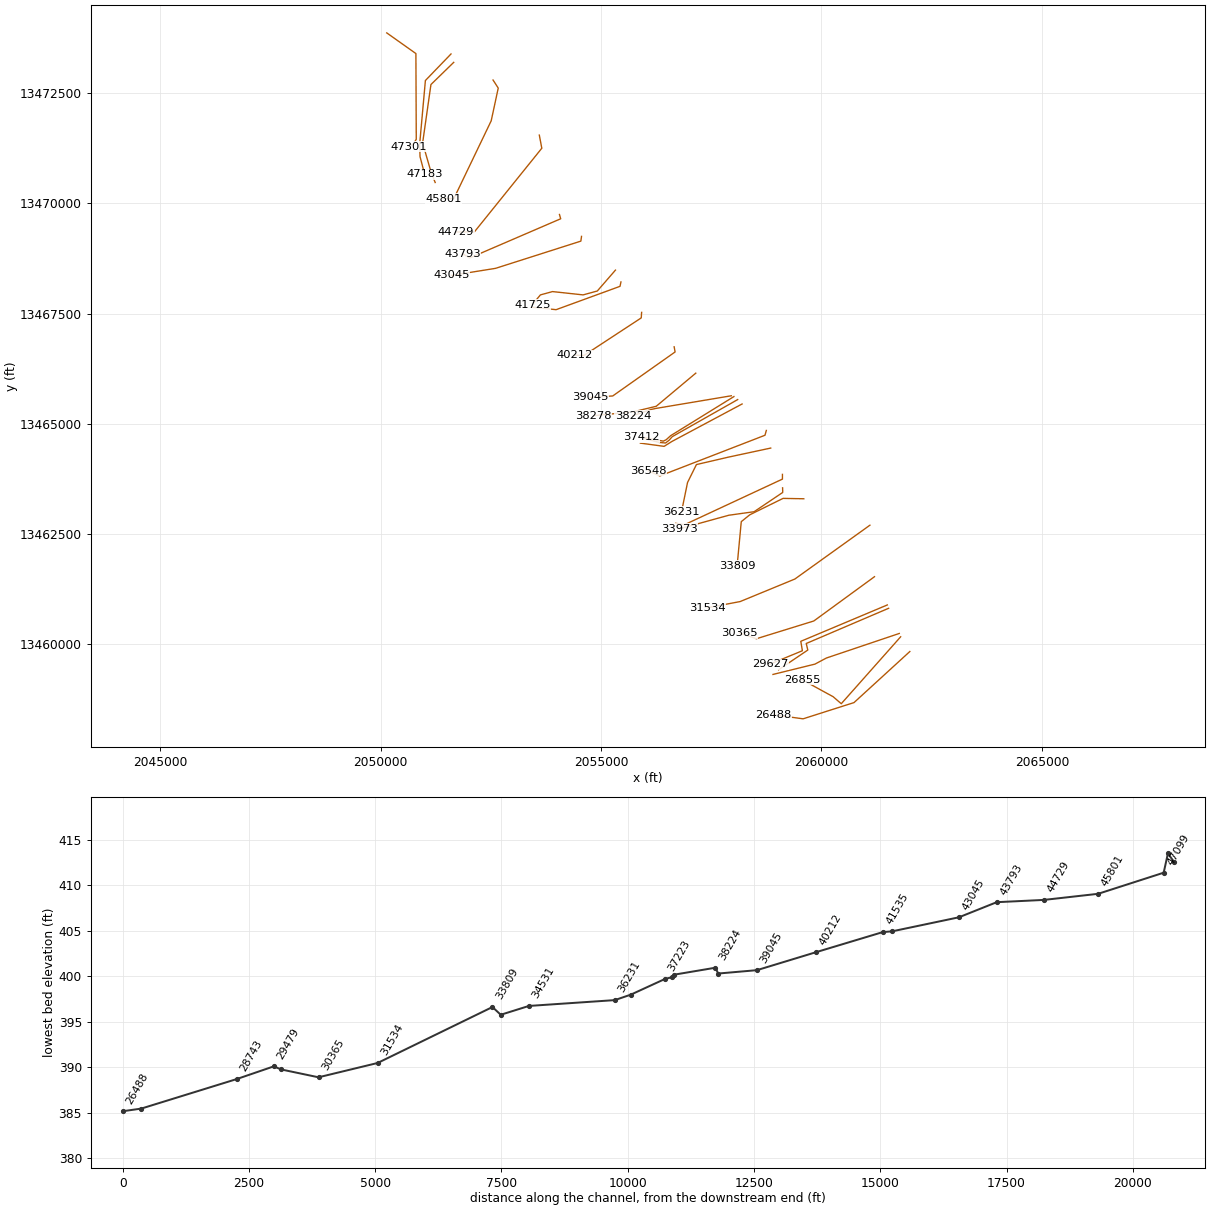
HEC-RAS study LAKE Br.prj: LAKE Br Base Level Engineering

--- LAKE Br.g01 (geometry) --- (continued)

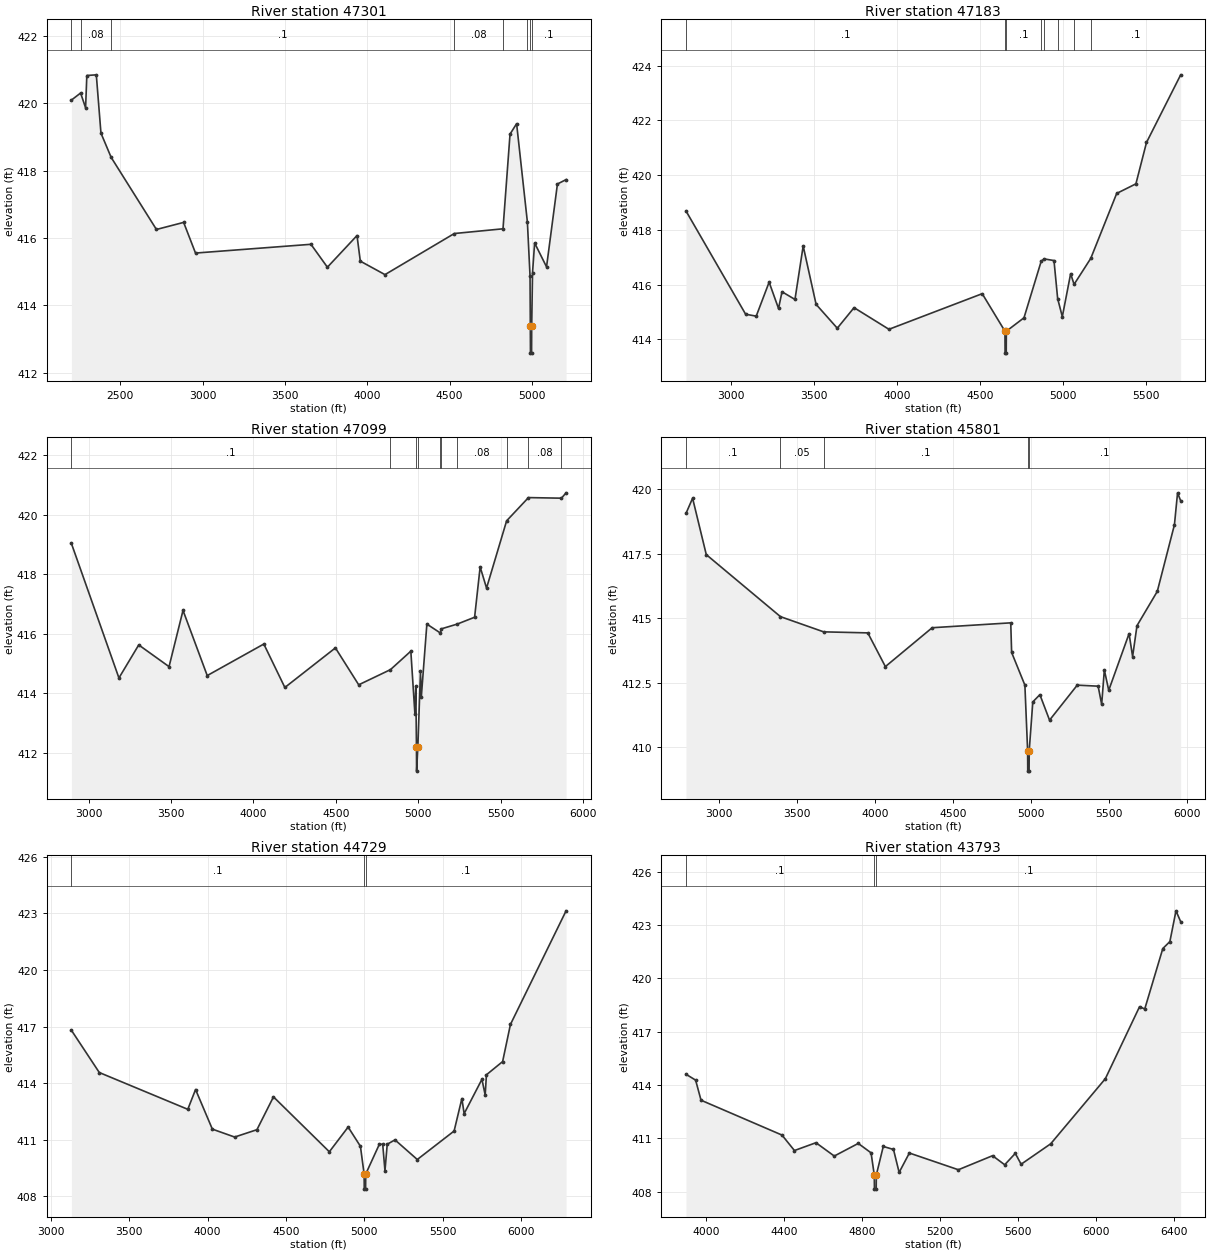
Type RM Length L Ch R = 1 ,47301   ,118,118,118
BEGIN DESCRIPTION:
Mapping XS f2ca20e7
END DESCRIPTION:
XS GIS Cut Line= 5
      2050138.49     13473868.97        2050800.       13473400.
      2050808.16     13471455.36      2050745.22     13471356.61
      2050633.42      13471282.8
#Sta/Elev= 30
    2202  420.09    2258   420.3  2288.2  419.86  2295.8  420.82  2353.4  420.84
  2381.6  419.11  2443.6  418.39  2718.8  416.25  2884.2  416.46  2956.3  415.55
  3657.9  415.81  3757.9  415.13  3937.9  416.07  3957.9  415.31  4107.9  414.91
  4529.3  416.13  4825.2  416.27  4867.9  419.08  4907.9  419.39  4973.4  416.47
  4989.5  414.87  4991.2  413.38    4992  412.58  4998.8  412.58  4999.5  413.38
  5004.7  414.97  5017.3  415.85  5089.8  415.14    5156   417.6  5208.6  417.73
#Mann= 8 ,-1 , 0
    2202     .05       0    2258     .08       0  2443.6      .1       0
  4529.3     .08       0  4825.2     .05       0  4973.4      .1       0
  4991.2     .07       0  4999.5      .1       0
Bank Sta=4991.2,4999.5
XS Rating Curve= 0 ,0
Exp/Cntr=0.3,0.1

Type RM Length L Ch R = 1 ,47183   ,84,84,84
BEGIN DESCRIPTION:
Mapping XS 5fd670a6
END DESCRIPTION:
XS GIS Cut Line= 5
      2051596.86      13473391.2      2051015.25     13472788.22
       2050885.2     13471343.59      2050893.72     13471060.79
      2050997.88     13470665.86
#Sta/Elev= 30
  2728.3  418.69  3087.5  414.92  3151.3  414.85    3229  416.09  3285.6  415.13
  3306.7  415.74  3384.7  415.46  3434.1  417.41    3512  415.28  3639.6  414.41
  3740.6  415.16  3950.8  414.37  4512.5  415.67  4649.5   414.3  4650.2   413.5
  4657.1   413.5  4657.8   414.3  4764.1  414.79  4867.6  416.85  4885.3  416.94
  4944.8  416.88  4966.9  415.49    4995  414.83  5045.1   416.4  5065.8  416.01
  5166.4  416.96  5322.5  419.33  5438.2  419.68    5502  421.19  5707.9  423.66
#Mann= 8 ,-1 , 0
  2728.3      .1       0  4649.5     .07       0  4657.8      .1       0
  4867.6     .08       0  4885.3     .05       0  4966.9     .08       0
  5065.8     .05       0  5166.4      .1       0
Bank Sta=4649.5,4657.8
XS Rating Curve= 0 ,0
Exp/Cntr=0.3,0.1

Type RM Length L Ch R = 1 ,47099   ,1298,1298,1298
BEGIN DESCRIPTION:
Mapping XS 15e2f653
END DESCRIPTION:
XS GIS Cut Line= 5
      2051657.64     13473200.24      2051141.12     13472697.07
      2050952.47      13471371.8      2051145.46     13470704.89
      2051237.49     13470474.81
#Sta/Elev= 30
  2895.2  419.03  3183.6  414.51  3303.8  415.62  3487.7  414.89  3572.5  416.78
  3719.4  414.59  4062.8  415.65  4190.5  414.19  4497.2  415.52  4638.6  414.28
  4831.3  414.79  4954.9  415.41  4979.8  413.29    4985  414.23  4989.1  412.18
  4989.8  411.38  4997.4  412.18  5013.4  414.73  5018.6  413.88  5052.2  416.32
  5134.5  416.02  5140.1  416.16  5236.3  416.32  5341.9  416.55  5375.5  418.24
  5414.3  417.53  5536.2  419.79  5668.7  420.57  5868.8  420.55    5897  420.73
#Mann= 10 ,-1 , 0
  2895.2      .1       0  4831.3     .08       0  4989.1     .07       0
  4997.4     .08       0  5134.5     .05       0  5140.1      .1       0
  5236.3     .08       0  5536.2      .1       0  5668.7     .08       0
  5868.8      .1       0
Bank Sta=4989.1,4997.4
XS Rating Curve= 0 ,0
Exp/Cntr=0.3,0.1

Type RM Length L Ch R = 1 ,45801   ,1072,1072,1072
BEGIN DESCRIPTION:
Mapping XS 2c32f6e2
END DESCRIPTION:
XS GIS Cut Line= 5
      2052549.99     13472800.01      2052668.03     13472617.21
       2052508.3     13471874.16      2051661.08     13470110.27
      2051425.01     13470110.27
#Sta/Elev= 30
    2788  419.07  2830.3  419.66    2918  417.47  3393.6  415.06  3670.2  414.47
  3953.3  414.43  4065.9  413.12  4365.8  414.63  4869.4  414.82    4875  413.67
    4960   412.4  4977.5  409.86  4978.4  409.06  4986.9  409.06  4987.8  409.86
  5010.8  411.75  5056.1  412.03  5118.1  411.04  5295.6   412.4  5429.5  412.36
  5452.1  411.65  5469.2  412.99  5497.4   412.2  5627.7   414.4  5650.4  413.51
  5678.5  414.71  5808.5  416.04  5918.5  418.63  5938.5  419.87  5958.5  419.56
#Mann= 5 ,-1 , 0
    2788      .1       0  3393.6     .05       0  3670.2      .1       0
  4977.5     .07       0  4987.8      .1       0
Bank Sta=4977.5,4987.8
XS Rating Curve= 0 ,0
Exp/Cntr=0.3,0.1

Type RM Length L Ch R = 1 ,44729   ,936,936,936
BEGIN DESCRIPTION:
Mapping XS 01a43849
END DESCRIPTION:
XS GIS Cut Line= 4
        2053600.       13471550.      2053656.31     13471251.97
      2052126.36     13469353.32      2051709.82     13469353.32
#Sta/Elev= 30
    3130  416.81  3308.1  414.57  3873.1  412.62  3922.7  413.67  4029.8  411.57
  4172.2  411.15  4314.5  411.54  4420.1  413.28  4776.8  410.37  4896.8  411.68
  4975.2  410.66  4998.8  409.19  4999.7  408.39  5008.2  408.39  5009.1  409.19
  5096.7  410.78  5117.5  410.76  5131.9  409.36  5146.3  410.77  5195.9     411
  5338.2  409.96  5573.3  411.47  5622.9  413.19  5637.3  412.39  5750.9  414.21
  5771.7  413.38  5779.6  414.45    5883  415.15    5933  417.12  6288.2  423.14
#Mann= 3 ,-1 , 0
    3130      .1       0  4998.8     .07       0  5009.1      .1       0
Bank Sta=4998.8,5009.1
XS Rating Curve= 0 ,0
Exp/Cntr=0.3,0.1

Type RM Length L Ch R = 1 ,43793   ,748,748,748
BEGIN DESCRIPTION:
Mapping XS 1a7e2134
END DESCRIPTION:
XS GIS Cut Line= 4
      2054056.91     13469749.19      2054084.69     13469651.93
      2052022.19     13468763.05      2051855.77     13468860.12
#Sta/Elev= 30
  3896.9   414.6  3946.3  414.27  3974.1  413.14  4389.7  411.18  4453.7  410.31
  4564.1  410.75  4658.2     410  4781.2  410.71  4847.1  410.18  4863.5  408.94
  4864.4  408.14  4873.3  408.14  4874.1  408.94  4909.7  410.54  4962.2  410.37
  4991.2  409.08  5043.7  410.17  5295.2  409.23  5470.8  410.02  5533.1  409.51
  5587.5  410.15  5617.4  409.54  5769.4  410.69  6049.9  414.35  6225.5   418.4
  6252.1  418.27  6344.9  421.67  6381.1  422.06  6412.5  423.79  6436.6  423.18
#Mann= 3 ,-1 , 0
  3896.9      .1       0  4863.5     .07       0  4874.1      .1       0
Bank Sta=4863.5,4874.1
XS Rating Curve= 0 ,0
Exp/Cntr=0.3,0.1

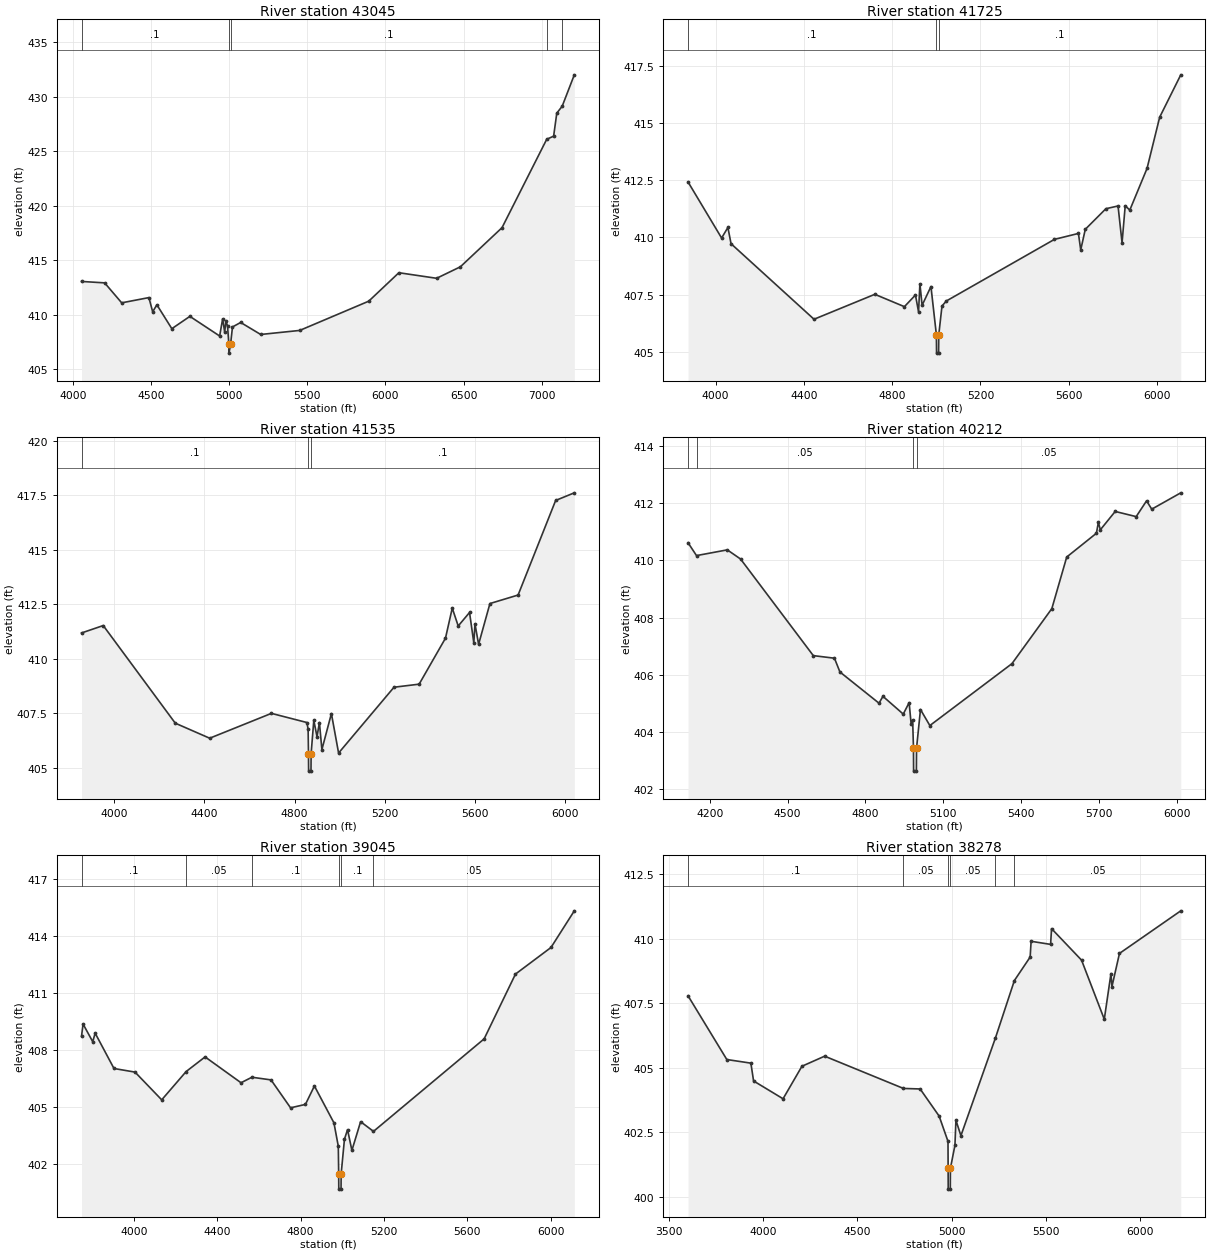
Type RM Length L Ch R = 1 ,43045   ,1320,1320,1320
BEGIN DESCRIPTION:
Mapping XS e1dc4611
END DESCRIPTION:
XS GIS Cut Line= 4
      2054557.35       13469252.      2054543.03     13469144.99
      2052607.22     13468527.26      2051604.26     13468366.56
#Sta/Elev= 30
  4053.8  413.05  4201.7  412.92  4310.8  411.09  4485.1  411.57  4509.2  410.27
  4536.2  410.91    4632  408.72  4747.5  409.85  4938.2  408.05  4957.4  409.63
  4970.4  408.41  4978.4  409.44  4988.9  408.94  4997.2  407.28    4998  406.48
    5008  407.28  5020.4  408.88  5072.9  409.29    5201  408.19  5450.8  408.56
  5892.8  411.24    6086  413.85  6327.6  413.34  6479.6  414.39  6746.6  417.98
  7032.7  426.08  7077.1  426.37  7097.3  428.48  7131.8  429.11  7209.5  431.99
#Mann= 5 ,-1 , 0
  4053.8      .1       0  4997.2     .07       0    5008      .1       0
  7032.7     .08       0  7131.8      .1       0
Bank Sta=4997.2,5008
XS Rating Curve= 0 ,0
Exp/Cntr=0.3,0.1

Type RM Length L Ch R = 1 ,41725   ,190,190,190
BEGIN DESCRIPTION:
Mapping XS fbaef4c7
END DESCRIPTION:
XS GIS Cut Line= 6
       2055327.5     13468487.57      2054916.06     13468013.62
      2054593.14     13467925.08        2053900.       13468000.
        2053625.       13467925.      2053440.57     13467704.37
#Sta/Elev= 30
  3874.9  412.42  4027.1  409.97  4055.6  410.43  4069.9  409.72  4445.9  406.42
  4721.4  407.51  4855.5  406.97  4905.6  407.48  4919.6  406.74  4925.7  407.97
  4935.7  407.03  4975.8  407.85  5000.4  405.74  5001.2  404.94  5010.4  404.94
  5011.2  405.74  5025.8     407  5045.9  407.22  5535.3  409.91  5644.1  410.17
  5654.5  409.45  5675.2  410.35  5768.5  411.25  5823.6  411.37  5841.8  409.76
  5856.1  411.38  5876.9  411.19    5955  413.01  6012.3  415.25  6107.9   417.1
#Mann= 3 ,-1 , 0
  3874.9      .1       0  5000.4     .07       0  5011.2      .1       0
Bank Sta=5000.4,5011.2
XS Rating Curve= 0 ,0
Exp/Cntr=0.3,0.1

Type RM Length L Ch R = 1 ,41535   ,1323,1323,1323
BEGIN DESCRIPTION:
Mapping XS cf69ffda
END DESCRIPTION:
XS GIS Cut Line= 4
      2055452.16     13468218.97      2055430.47     13468119.18
      2053980.82     13467589.67      2053442.62     13467646.09
#Sta/Elev= 30
  3854.9  411.19  3951.1  411.53  4270.8  407.05  4423.5  406.36  4697.4   407.5
    4855  407.08  4860.3  406.77  4861.9  405.65  4862.5  404.85    4873  404.85
  4873.6  405.65  4885.5  407.18  4899.7  406.43  4910.4  407.08  4921.4  405.84
  4963.6  407.49  4995.5  405.68  5241.4   408.7  5352.9  408.84  5469.8  410.95
  5499.9  412.33  5526.3  411.51  5576.6  412.13  5595.6  410.73  5600.6  411.61
  5616.8  410.67  5667.1  412.54    5792  412.93  5958.7  417.27  6041.5  417.62
#Mann= 3 ,-1 , 0
  3854.9      .1       0  4861.9     .07       0  4873.6      .1       0
Bank Sta=4861.9,4873.6
XS Rating Curve= 0 ,0
Exp/Cntr=0.3,0.1

Type RM Length L Ch R = 1 ,40212   ,1167,1167,1167
BEGIN DESCRIPTION:
Mapping XS f0cd8766
END DESCRIPTION:
XS GIS Cut Line= 4
      2055920.92     13467528.91      2055912.24     13467403.03
       2054614.5     13466552.34      2054393.13     13466556.68
#Sta/Elev= 30
  4116.4  410.61  4149.1  410.16  4267.8  410.36    4319  410.04  4599.3  406.67
  4680.8  406.58  4701.9   406.1  4852.6  405.01  4867.7  405.25    4946  404.63
  4968.7  405.03  4976.2   404.3  4982.2  404.43  4985.4  403.44  4985.9  402.64
  4996.6  402.64  4997.2  403.44  5012.4  404.79  5048.5  404.23    5365  406.39
  5518.7  408.31  5576.1  410.11  5690.6  410.94    5698  411.32  5705.7  411.06
  5762.9   411.7  5843.8  411.52  5883.8  412.07  5903.8  411.78  6015.7  412.35
#Mann= 4 ,-1 , 0
  4116.4      .1       0  4149.1     .05       0  4985.4     .03       0
  4997.2     .05       0
Bank Sta=4985.4,4997.2
XS Rating Curve= 0 ,0
Exp/Cntr=0.3,0.1

Type RM Length L Ch R = 1 ,39045   ,767,767,767
BEGIN DESCRIPTION:
Mapping XS 5731be36
END DESCRIPTION:
XS GIS Cut Line= 4
      2056658.76     13466747.67      2056680.47     13466630.46
      2055265.54      13465632.2      2054753.35     13465597.48
#Sta/Elev= 30
  3748.8  408.73  3756.1  409.36  3802.4  408.43  3814.1  408.88  3904.4  407.02
  4005.4  406.83  4133.4  405.37  4250.6  406.86  4341.5  407.63  4513.9  406.27
  4566.1  406.56  4657.9  406.42  4751.6  404.95    4823  405.13    4866   406.1
  4959.7  404.16  4980.6  402.93  4982.5  401.47    4983  400.67  4993.8  400.67
  4994.3  401.47  5010.2   403.3    5025   403.8  5045.9  402.71  5087.7  404.22
  5149.5  403.71  5680.4  408.58  5830.7  411.99  6001.1  413.39    6113  415.32
#Mann= 6 ,-1 , 0
  3748.8      .1       0  4250.6     .05       0  4566.1      .1       0
  4982.5     .07       0  4994.3      .1       0  5149.5     .05       0
Bank Sta=4982.5,4994.3
XS Rating Curve= 0 ,0
Exp/Cntr=0.3,0.1

Type RM Length L Ch R = 1 ,38278   ,54,54,54
BEGIN DESCRIPTION:
Mapping XS 86a70471
END DESCRIPTION:
XS GIS Cut Line= 4
      2057150.02     13466150.01       2056252.3     13465398.02
      2055716.27      13465268.9      2054831.55     13465185.16
#Sta/Elev= 30
  3603.1  407.79  3808.7  405.32  3936.2  405.18  3950.5  404.49  4106.7   403.8
  4206.8  405.06  4327.1  405.45  4744.7   404.2  4833.1  404.18  4933.7  403.13
  4980.7  402.15  4981.4   401.1  4981.9   400.3  4992.9   400.3  4993.4   401.1
  5017.5     402  5022.7  402.97  5049.1  402.37  5232.3  406.16  5332.5  408.38
  5416.1  409.29  5421.1   409.9  5524.4  409.78  5529.4  410.39  5688.4  409.17
  5808.9  406.88  5844.3  408.65  5849.3  408.14  5889.3  409.43  6214.2  411.08
#Mann= 6 ,-1 , 0
  3603.1      .1       0  4744.7     .05       0  4981.4     .04       0
  4993.4     .05       0  5232.3     .08       0  5332.5     .05       0
Bank Sta=4981.4,4993.4
XS Rating Curve= 0 ,0
Exp/Cntr=0.3,0.1

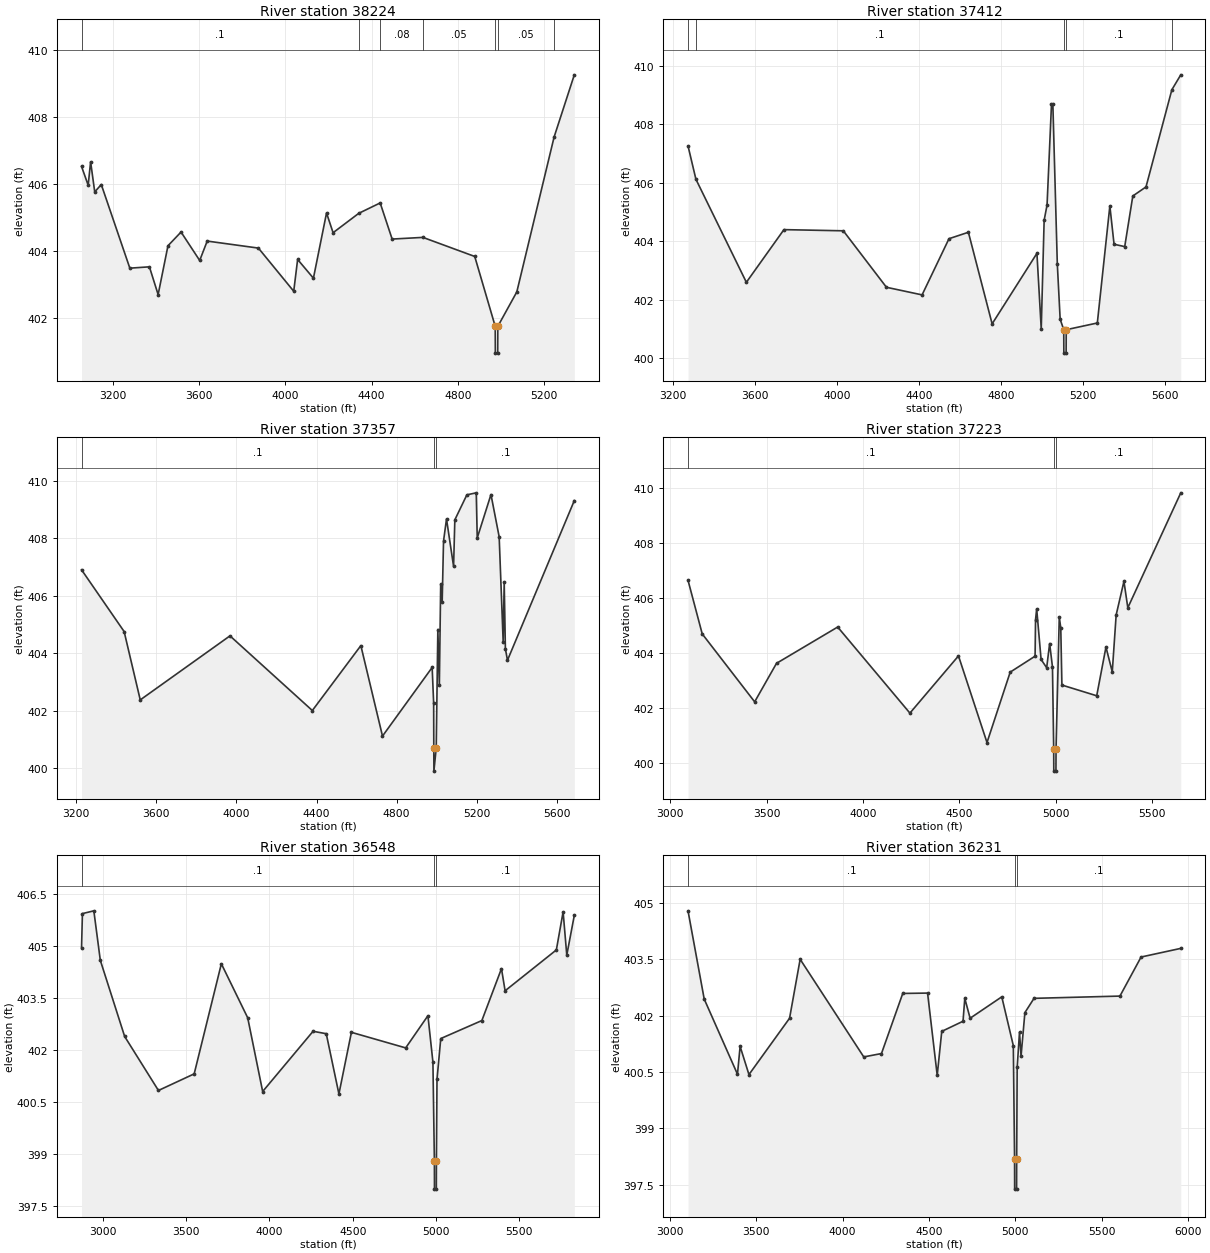
Type RM Length L Ch R = 1 ,38224   ,812,812,812
BEGIN DESCRIPTION:
Mapping XS c5595b9c
END DESCRIPTION:
XS GIS Cut Line= 4
      2057955.23     13465636.33      2056238.19     13465348.11
      2056144.88     13465327.49      2055720.58     13465183.16
#Sta/Elev= 30
  3054.8  406.52  3085.5  405.96  3096.8  406.66  3115.9  405.76  3146.3  405.98
  3278.7  403.48  3369.4  403.52  3409.9  402.69  3455.5  404.15  3516.1  404.56
  3602.6  403.71  3637.4  404.29  3874.8  404.08  4038.6  402.79  4056.7  403.74
  4129.9  403.18  4190.7  405.13  4221.1  404.54  4340.3  405.12  4439.4  405.43
  4494.9  404.35  4637.7   404.4  4877.9  403.83  4972.9  401.74  4973.4  400.94
  4984.4  400.94  4984.9  401.74    5073  402.77  5245.9   407.4  5339.6  409.26
#Mann= 7 ,-1 , 0
  3054.8      .1       0  4340.3     .05       0  4439.4     .08       0
  4637.7     .05       0  4972.9     .04       0  4984.9     .05       0
  5245.9     .08       0
Bank Sta=4972.9,4984.9
XS Rating Curve= 0 ,0
Exp/Cntr=0.3,0.1

Type RM Length L Ch R = 1 ,37412   ,55,55,55
BEGIN DESCRIPTION:
Mapping XS 4327bc96
END DESCRIPTION:
XS GIS Cut Line= 5
      2058014.65     13465618.05       2056578.5     13464730.17
      2056479.54     13464639.89      2056411.83      13464606.9
      2055915.35     13464702.38
#Sta/Elev= 30
  3273.8  407.26  3312.4  406.12  3558.4   402.6  3741.6   404.4  4031.2  404.36
  4241.6  402.43  4415.4  402.17  4546.6  404.09  4641.2  404.31    4757  401.18
  4975.5  403.59  4996.5  401.01  5010.7  404.72  5024.9  405.24  5046.5  408.68
  5053.2  408.69  5074.9  403.23  5088.8  401.34  5106.3  400.98  5106.8  400.18
  5117.9  400.18  5118.4  400.98  5270.1  401.21  5331.2  405.21  5351.7   403.9
  5403.7  403.82  5443.2  405.55  5507.5  405.86  5633.6  409.18  5677.1  409.69
#Mann= 5 ,-1 , 0
  3273.8     .12       0  3312.4      .1       0  5106.3     .07       0
  5118.4      .1       0  5633.6     .05       0
Bank Sta=5106.3,5118.4
XS Rating Curve= 0 ,0
Exp/Cntr=0.3,0.1

Type RM Length L Ch R = 1 ,37357   ,134,134,134
BEGIN DESCRIPTION:
Mapping XS 13c110cd
END DESCRIPTION:
XS GIS Cut Line= 6
      2058100.04     13465550.02      2056616.69     13464709.33
      2056542.04       13464626.      2056463.92     13464565.24
      2056318.08     13464577.39      2055932.62     13464681.57
#Sta/Elev= 30
  3226.2   406.9  3438.9  404.75  3519.4  402.37  3967.6   404.6    4379     402
  4621.4  404.26  4729.5  401.11  4977.6   403.5  4985.1  402.25  4985.8  400.69
  4986.3  399.89  4997.9  400.69    5006  404.82  5013.5  402.88  5020.2  406.39
  5027.7  405.79  5034.4   407.9  5049.3  408.67  5084.6  407.02  5090.9  408.64
    5151  409.51  5197.8  409.58  5202.8  408.01  5271.4  409.52  5312.3  408.05
  5332.3   404.4  5337.5  406.47  5343.4  404.15  5353.8  403.75  5687.7  409.31
#Mann= 3 ,-1 , 0
  3226.2      .1       0  4985.8     .07       0  4997.9      .1       0
Bank Sta=4985.8,4997.9
XS Rating Curve= 0 ,0
Exp/Cntr=0.3,0.1

Type RM Length L Ch R = 1 ,37223   ,675,675,675
BEGIN DESCRIPTION:
Mapping XS 3740e080
END DESCRIPTION:
XS GIS Cut Line= 4
      2058200.02     13465450.01      2056611.49     13464601.69
      2056430.93     13464488.85      2055892.72     13464561.77
#Sta/Elev= 30
  3092.2  406.64  3165.9  404.69    3438  402.22  3551.4  403.62  3868.8  404.94
  4243.6  401.81  4495.6  403.89  4643.6  400.74    4764   403.3  4893.1  403.88
  4895.5  405.21  4901.4   405.6  4924.3  403.76  4953.3  403.46  4968.6  404.34
  4983.3  403.49  4989.7   400.5  4990.2   399.7  5001.3   399.7  5001.8   400.5
  5018.6   405.3  5026.4  404.91  5032.3  402.83  5212.9  402.44  5260.9  404.21
  5293.6  403.31  5313.8  405.38  5354.2   406.6  5374.3  405.64  5649.1  409.82
#Mann= 3 ,-1 , 0
  3092.2      .1       0  4989.7     .07       0  5001.8      .1       0
Bank Sta=4989.7,5001.8
XS Rating Curve= 0 ,0
Exp/Cntr=0.3,0.1

Type RM Length L Ch R = 1 ,36548   ,317,317,317
BEGIN DESCRIPTION:
Mapping XS 22972692
END DESCRIPTION:
XS GIS Cut Line= 4
      2058750.01     13464850.04      2058719.68     13464740.92
      2056334.26     13463817.31       2056073.8     13463935.39
#Sta/Elev= 30
  2872.8  404.96    2878  405.94  2946.5  406.02  2985.4  404.59  3131.5  402.39
  3334.2  400.83  3548.7  401.31  3711.8  404.49  3869.9  402.93  3959.7   400.8
  4262.2  402.54  4341.3  402.47  4417.3  400.73  4492.3  402.51    4818  402.06
  4951.5  402.99  4981.5  401.65  4990.3  398.78  4990.8  397.98  5001.9  397.98
  5002.4  398.78    5006  401.15  5028.5  402.33  5275.2  402.85  5392.9  404.35
  5414.6  403.71  5722.2  404.89  5762.8  405.99  5784.8  404.74    5830  405.89
#Mann= 3 ,-1 , 0
  2872.8      .1       0  4990.3     .07       0  5002.4      .1       0
Bank Sta=4990.3,5002.4
XS Rating Curve= 0 ,0
Exp/Cntr=0.3,0.1

Type RM Length L Ch R = 1 ,36231   ,1700,1700,1700
BEGIN DESCRIPTION:
Mapping XS 202aa75f
END DESCRIPTION:
XS GIS Cut Line= 5
      2058850.04     13464450.01      2057896.76     13464245.79
      2057164.12     13464075.65      2056962.73      13463669.4
      2056827.34     13463009.82
#Sta/Elev= 30
  3104.3  404.79  3198.1  402.44  3390.7  400.44    3406  401.18  3457.2  400.43
  3692.4  401.93  3753.7   403.5  4122.1   400.9  4224.7  400.99  4347.9  402.59
  4491.7   402.6  4547.5  400.41  4573.8  401.58    4697  401.85  4707.2  402.46
    4738  401.93  4921.4   402.5  4988.3   401.2  4995.5  398.18    4996  397.38
  5007.2  397.38  5007.7  398.18  5010.6  400.62  5024.1  401.56    5033  400.92
  5055.3  402.08  5108.2  402.46  5605.7  402.52  5728.2  403.56  5958.1  403.79
#Mann= 3 ,-1 , 0
  3104.3      .1       0  4995.5     .07       0  5007.7      .1       0
Bank Sta=4995.5,5007.7
XS Rating Curve= 0 ,0
Exp/Cntr=0.3,0.1

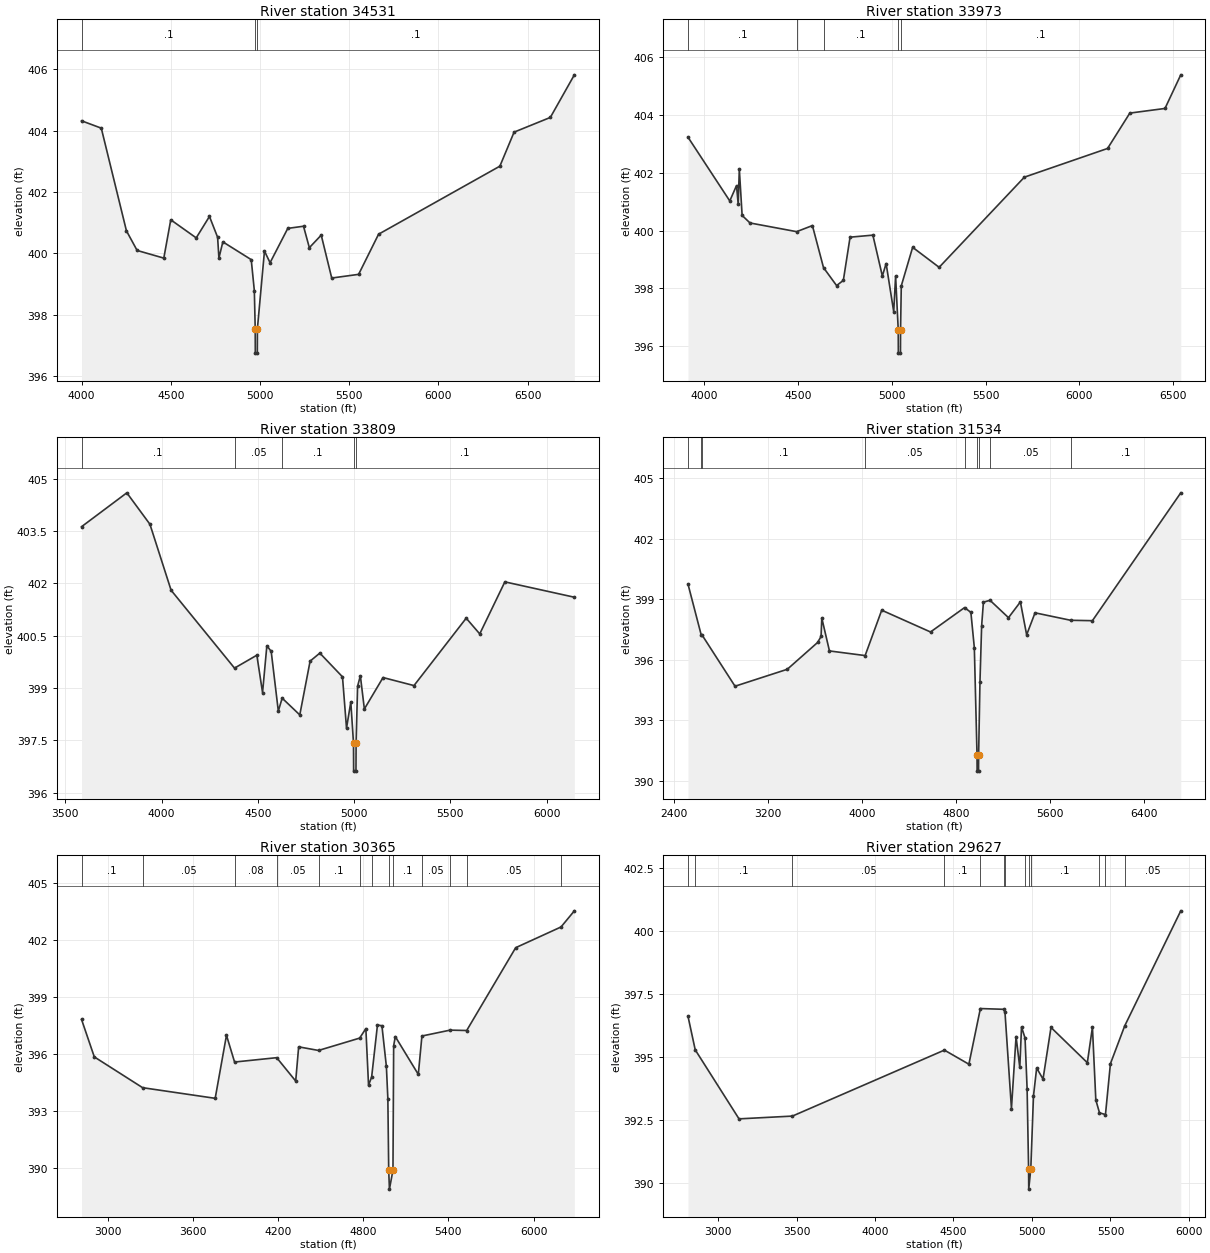
Type RM Length L Ch R = 1 ,34531   ,558,558,558
BEGIN DESCRIPTION:
Mapping XS a4717f84
END DESCRIPTION:
XS GIS Cut Line= 4
      2059115.51     13463853.38      2059115.51     13463745.79
      2056893.29     13462711.06      2056691.91     13462742.31
#Sta/Elev= 30
  3999.8  404.32  4110.4  404.08  4251.4  400.73  4311.3  400.09  4460.9  399.84
  4499.9  401.09  4642.6   400.5  4716.8   401.2  4762.5  400.52  4769.8  399.84
  4791.9  400.37    4951  399.79  4968.4  398.78  4973.3  397.54  4973.8  396.74
  4985.1  396.74  4985.6  397.54  5025.2  400.07  5056.6  399.69  5155.9  400.81
  5244.1  400.88  5276.8  400.18  5343.4  400.59  5402.2  399.19    5553  399.31
  5664.9  400.62  6344.9  402.84  6424.5  403.95  6627.8  404.43  6762.5  405.82
#Mann= 3 ,-1 , 0
  3999.8      .1       0  4973.3     .07       0  4985.6      .1       0
Bank Sta=4973.3,4985.6
XS Rating Curve= 0 ,0
Exp/Cntr=0.3,0.1

Type RM Length L Ch R = 1 ,33973   ,164,164,164
BEGIN DESCRIPTION:
Mapping XS 563c883b
END DESCRIPTION:
XS GIS Cut Line= 5
      2059118.98     13463547.85      2059122.45      13463443.7
      2058473.15      13463006.2      2057900.23     13462926.34
      2056779.31     13462617.48
#Sta/Elev= 30
  3912.6  403.22  4135.6  401.02  4171.6  401.55  4180.5  400.91  4186.5  402.12
  4201.5  400.52  4243.5  400.26  4492.2  399.96  4576.3  400.17  4635.5  398.72
  4705.3   398.1  4741.3  398.28  4777.2  399.77  4898.8  399.84  4949.3  398.43
  4969.5  398.86  5009.9   397.2    5020  398.43  5034.1  396.57  5034.6  395.77
  5045.9  395.77  5046.4  396.57  5050.3  398.09  5110.9  399.42  5252.2  398.73
  5706.8  401.84  6150.5  402.83  6269.2  404.05  6456.7  404.21  6540.9  405.37
#Mann= 5 ,-1 , 0
  3912.6      .1       0  4492.2     .05       0  4635.5      .1       0
  5034.1     .07       0  5046.4      .1       0
Bank Sta=5034.1,5046.4
XS Rating Curve= 0 ,0
Exp/Cntr=0.3,0.1

Type RM Length L Ch R = 1 ,33809   ,2275,2275,2275
BEGIN DESCRIPTION:
Mapping XS f7ec1740
END DESCRIPTION:
XS GIS Cut Line= 5
      2059600.03       13463300.       2059129.4     13463308.29
      2058375.93     13462936.76      2058181.48     13462780.51
      2058087.93     13461785.64
#Sta/Elev= 30
  3584.4  403.62  3819.5  404.59  3939.5  403.69  4049.5   401.8  4378.8  399.57
  4494.8  399.94  4524.4  398.87  4546.8  400.21  4569.3  400.05  4606.3  398.34
  4626.3  398.71  4717.8  398.23  4771.4  399.77  4821.9     400  4939.6  399.32
  4960.5  397.85  4982.8   398.6  4996.8  397.42  4997.5  396.62  5009.6  396.62
  5010.3  397.42    5018  399.05  5032.4  399.35  5053.2   398.4  5150.2   399.3
  5310.9  399.07  5582.1     401  5652.4  400.55  5782.9  402.04  6143.9   401.6
#Mann= 5 ,-1 , 0
  3584.4      .1       0  4378.8     .05       0  4626.3      .1       0
  4996.8     .07       0  5010.3      .1       0
Bank Sta=4996.8,5010.3
XS Rating Curve= 0 ,0
Exp/Cntr=0.3,0.1

Type RM Length L Ch R = 1 ,31534   ,1169,1169,1169
BEGIN DESCRIPTION:
Mapping XS f320648f
END DESCRIPTION:
XS GIS Cut Line= 4
      2061099.99     13462699.99      2059396.76     13461478.42
      2058157.18     13460968.01      2057415.22     13460826.42
#Sta/Elev= 30
  2521.1  399.75  2633.5  397.23  2643.2   397.2  2921.5  394.68    3366  395.52
  3623.9  396.85  3653.4  397.15  3659.5  398.06  3724.6  396.43  4028.1   396.2
  4169.2  398.45  4584.3  397.37  4874.1  398.58  4927.7  398.34    4957  396.59
  4979.9  391.27  4980.6  390.47  4992.7  390.47  4993.5  391.27  5004.9  394.89
  5019.1  397.67  5034.3  398.85  5090.6  398.94  5247.5  398.08  5348.7  398.86
    5402  397.23  5473.4  398.32  5776.2  397.95  5961.3  397.93    6713  404.27
#Mann= 9 ,-1 , 0
  2521.1     .12       0  2633.5     .07       0  2643.2      .1       0
  4028.1     .05       0  4874.1      .1       0  4979.9     .07       0
  4993.5      .1       0  5090.6     .05       0  5776.2      .1       0
Bank Sta=4979.9,4993.5
XS Rating Curve= 0 ,0
Exp/Cntr=0.3,0.1

Type RM Length L Ch R = 1 ,30365   ,738,738,738
BEGIN DESCRIPTION:
Mapping XS 18c3309f
END DESCRIPTION:
XS GIS Cut Line= 4
       2061204.1     13461531.77      2059827.31     13460527.04
      2058525.23     13460124.26      2058143.33     13460252.72
#Sta/Elev= 30
  2816.7  397.83  2906.5  395.86  3246.7  394.24  3757.7  393.68  3837.2     397
  3894.2  395.59  4190.8  395.82  4324.6  394.59  4345.5  396.39  4485.4   396.2
  4774.9  396.85  4818.7  397.35  4837.6  394.37  4859.4   394.8  4900.4  397.54
  4931.8   397.5  4963.2  395.36  4973.6  393.67  4979.6   389.9  4984.7   388.9
  5009.6   389.9  5014.5  396.45    5026  396.93    5188  394.94  5213.5  396.96
    5412  397.27  5528.7  397.25  5873.8  401.61  6192.9   402.7    6287  403.55
#Mann= 13 ,-1 , 0
  2816.7      .1       0  3246.7     .05       0  3894.2     .08       0
  4190.8     .05       0  4485.4      .1       0  4774.9     .05       0
  4859.4      .1       0  4979.6     .07       0  5009.6      .1       0
  5213.5     .05       0    5412      .1       0  5528.7     .05       0
  6192.9      .1       0
Bank Sta=4979.6,5009.6
XS Rating Curve= 0 ,0
Exp/Cntr=0.3,0.1

Type RM Length L Ch R = 1 ,29627   ,148,148,148
BEGIN DESCRIPTION:
Mapping XS 958245d9
END DESCRIPTION:
XS GIS Cut Line= 4
      2061494.86     13460890.86      2059531.78     13460065.69
      2059568.24     13459852.15      2058834.81     13459549.28
#Sta/Elev= 30
  2808.5  396.63  2854.8  395.29  3133.8  392.55  3473.9  392.66  4442.2  395.28
  4598.2  394.72  4671.4  396.93  4819.3   396.9  4828.2  396.78  4869.4  392.96
  4898.8  395.82  4922.5  394.59  4933.5   396.2    4956  395.76  4969.1  393.75
  4978.6  390.56  4979.5  389.76  4992.6  390.56  5009.7  393.46    5030  394.57
  5070.5  394.13  5121.3  396.18  5352.8  394.78  5385.3  396.19  5406.9   393.3
  5430.3  392.79  5468.3  392.72  5499.9  394.74  5590.8  396.24  5948.1  400.81
#Mann= 13 ,-1 , 0
  2808.5     .12       0  2854.8      .1       0  3473.9     .05       0
  4442.2      .1       0  4671.4     .05       0  4819.3      .1       0
  4828.2     .05       0    4956      .1       0  4978.6     .07       0
  4992.6      .1       0  5430.3     .07       0  5468.3      .1       0
  5590.8     .05       0
Bank Sta=4978.6,4992.6
XS Rating Curve= 0 ,0
Exp/Cntr=0.3,0.1

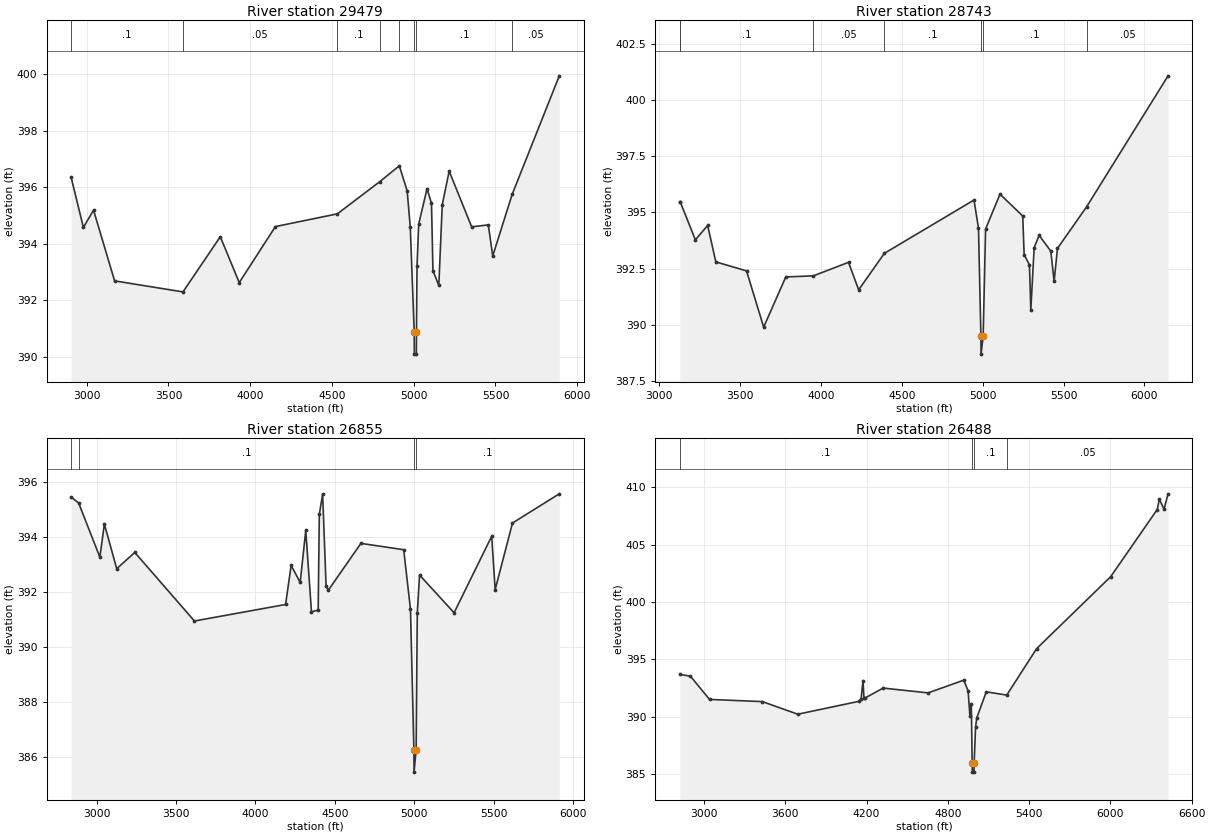
Type RM Length L Ch R = 1 ,29479   ,736,736,736
BEGIN DESCRIPTION:
Mapping XS a82997bb
END DESCRIPTION:
XS GIS Cut Line= 4
      2061524.17     13460814.91      2059655.48     13460016.21
      2059690.63     13459867.78        2059027.     13459419.17
#Sta/Elev= 30
  2904.4  396.36  2979.6  394.58  3041.8  395.19  3170.6  392.69  3588.6   392.3
    3817  394.25  3932.9  392.63  4154.1  394.61  4532.9  395.06  4792.8   396.2
  4911.9  396.76  4959.9  395.87    4979  394.58  5002.8   390.9  5003.7   390.1
  5015.9   390.1  5016.8   390.9  5020.1  393.21  5030.4   394.7  5081.5  395.95
  5108.6  395.43  5117.5  393.05  5153.4  392.53  5174.4  395.38  5216.7  396.57
  5354.3   394.6  5456.1  394.67  5483.1  393.57  5602.1  395.75  5890.2  399.94
#Mann= 8 ,-1 , 0
  2904.4      .1       0  3588.6     .05       0  4532.9      .1       0
  4792.8     .05       0  4911.9      .1       0  5002.8     .07       0
  5016.8      .1       0  5602.1     .05       0
Bank Sta=5002.8,5016.8
XS Rating Curve= 0 ,0
Exp/Cntr=0.3,0.1

Type RM Length L Ch R = 1 ,28743   ,1888,1888,1888
BEGIN DESCRIPTION:
Mapping XS 14e469f3
END DESCRIPTION:
XS GIS Cut Line= 4
      2061765.84       13460244.      2060112.51     13459686.79
      2059853.39     13459548.77      2058900.83      13459314.2
#Sta/Elev= 30
  3126.7  395.47  3130.1  395.45  3222.6  393.78  3298.7  394.42  3349.2   392.8
  3539.1   392.4  3645.1   389.9  3781.8  392.13  3952.8  392.18  4169.8  392.78
  4232.7  391.56  4391.4  393.18  4945.9  395.55  4973.6   394.3  4988.5   389.5
  4989.4   388.7  5002.5   389.5  5017.5  394.26  5106.5  395.81  5247.2  394.84
    5256  393.12  5288.7  392.67  5297.2  390.67  5317.8  393.43  5348.7  393.98
  5420.8  393.28  5441.4  391.93    5462   393.4  5643.4  395.26    6146  401.07
#Mann= 7 ,-1 , 0
  3126.7     .12       0  3130.1      .1       0  3952.8     .05       0
  4391.4      .1       0  4988.5     .07       0  5002.5      .1       0
  5643.4     .05       0
Bank Sta=4988.5,5002.5
XS Rating Curve= 0 ,0
Exp/Cntr=0.3,0.1

Type RM Length L Ch R = 1 ,26855   ,367,367,367
BEGIN DESCRIPTION:
Mapping XS 6ecdcf74
END DESCRIPTION:
XS GIS Cut Line= 4
      2061797.51     13460168.58        2060450.       13458650.
      2060266.85     13458808.37        2059564.     13459192.65
#Sta/Elev= 30
  2839.5  395.45  2886.9  395.24  3020.7  393.27  3049.1  394.47  3126.9  392.85
  3240.6  393.44  3616.1  390.95  4189.8  391.55  4224.9  392.97  4281.8  392.35
  4316.9  394.24  4352.9  391.28  4395.1  391.35  4402.2  394.82  4423.1  395.56
  4444.9  392.22  4459.1  392.07    4664  393.77  4933.4  393.54  4976.1  391.38
  4997.6  386.26  4998.5  385.46  5011.7  386.26  5018.9  391.24  5033.1  392.62
  5250.7  391.25  5487.4  394.03  5509.2  392.09  5618.3  394.51  5912.9  395.57
#Mann= 4 ,-1 , 0
  2839.5     .12       0  2886.9      .1       0  4997.6     .07       0
  5011.7      .1       0
Bank Sta=4997.6,5011.7
XS Rating Curve= 0 ,0
Exp/Cntr=0.3,0.1

Type RM Length L Ch R = 1 ,26488   ,0,0,0
BEGIN DESCRIPTION:
Mapping XS a869510a
END DESCRIPTION:
XS GIS Cut Line= 4
      2062005.81     13459834.26      2060738.95      13458675.5
      2059584.01     13458307.44      2058915.64     13458398.58
#Sta/Elev= 30
  2822.2  393.69  2900.2  393.54  3041.4  391.51  3431.2  391.32  3692.6  390.22
  4145.9  391.35  4160.1  391.58  4174.3  393.16  4181.1  391.64  4188.5  391.63
  4322.9   392.5  4654.7  392.08  4917.6  393.19  4949.8  392.26    4963   390.1
  4973.5  391.09  4980.1  385.97  4981.2  385.17  4993.5  385.17  4994.5  385.97
    5005  389.12  5014.3  389.92  5083.9  392.17  5235.2  391.89  5456.3  395.95
  6002.6  402.22  6345.7  408.07  6361.6  408.98  6396.2   408.1  6425.8  409.44
#Mann= 4 ,-1 , 0
  2822.2      .1       0  4980.1     .07       0  4994.5      .1       0
  5235.2     .05       0
Bank Sta=4980.1,4994.5
XS Rating Curve= 0 ,0
Exp/Cntr=0.3,0.1
LCMann Table=0

Chan Stop Cuts=-1
Use User Specified Reach Order=0
Composite Channel Slope=5