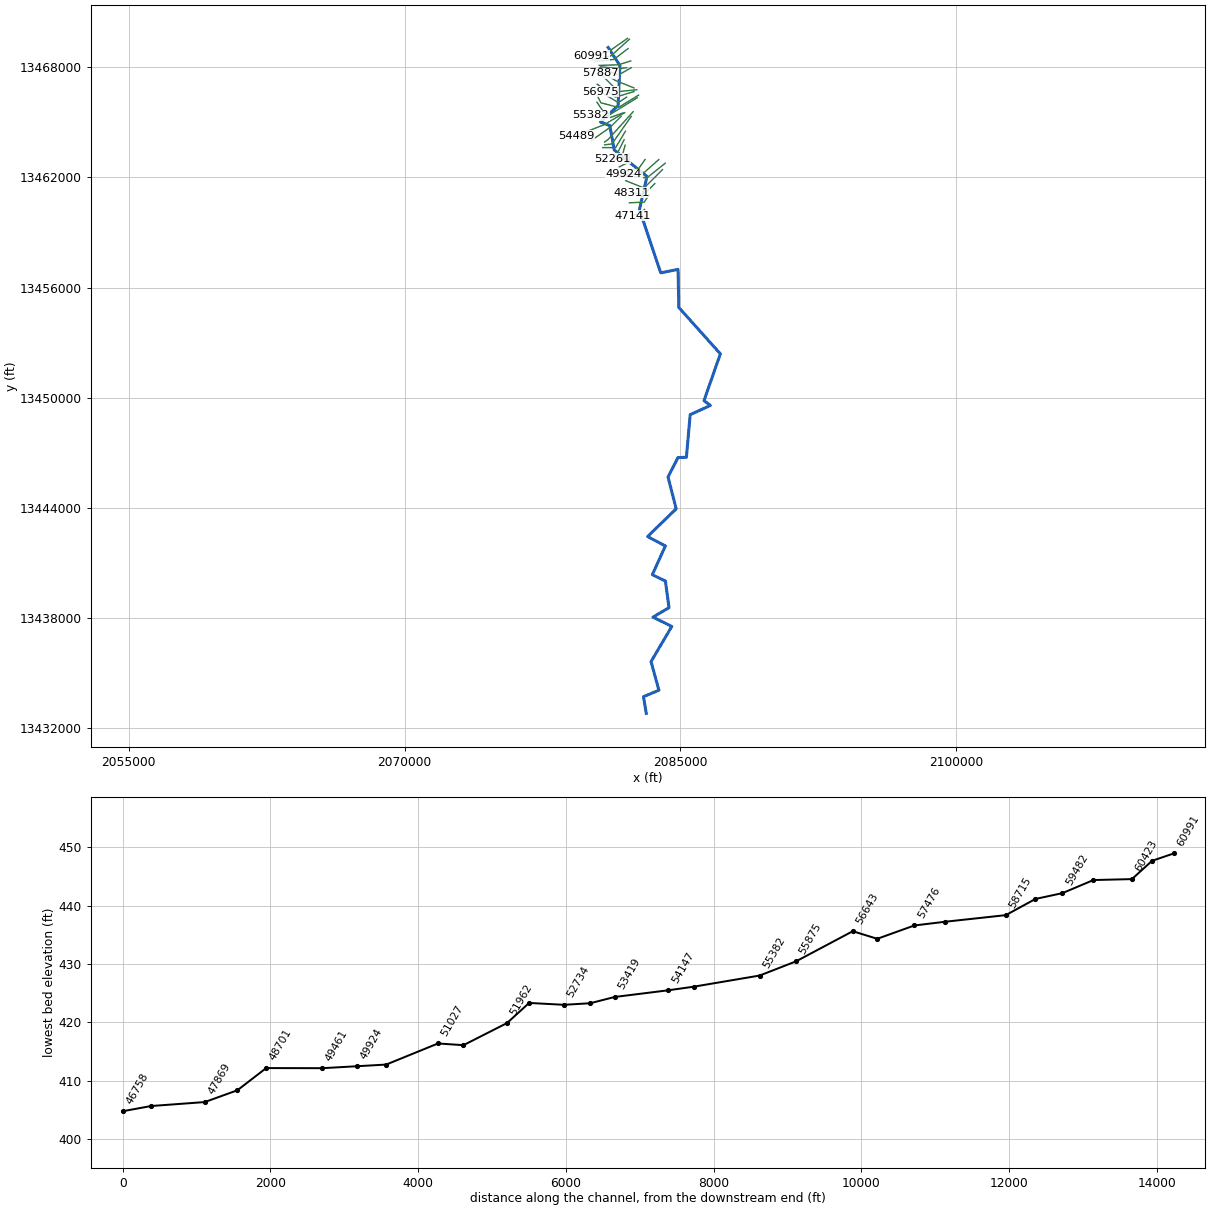
--- MACHO CREEK.prj (project) ---

Proj Title=MACHO CREEK Base Level Engineering
Current Plan=p01
Default Exp/Contr=0.3,0.1
English Units
Geom File=g01
Flow File=f01
Plan File=p01
Y Axis Title=Elevation
X Axis Title(PF)=Main Channel Distance
X Axis Title(XS)=Station
BEGIN DESCRIPTION:
MACHO CREEK
END DESCRIPTION:
DSS Export Rating Curves= 0
DSS Export Rating Curve Sorted= 0
DSS Export Volume Flow Curves= 0
DXF OffsetX= 0
DXF OffsetY= 0
DXF ScaleX= 1
DXF ScaleY= 10

--- MACHO CREEK.p01 (plan) ---

Plan Title=Multiple Run
Short Identifier=Multiple
Geom File=g01
Flow File=f01
Subcritical Flow
K Sum by GR= 0
Std Step Tol= 0.01
Critical Tol= 0.01
Num of Std Step Trials= 20
Max Error Tol= 0.3
Flow Tol Ratio= 0.001
Split Flow NTrial= 30
Split Flow Tol= 0.02
Split Flow Ratio= 0.02
Log Output Level= 0
Friction Slope Method= 1
Unsteady Friction Slope Method= 2
Unsteady Bridges Friction Slope Method= 1
Parabolic Critical Depth
Global Vel Dist=  1 , 1 , 1
Global Log Level= 0
CheckData=True
Encroach Param= -1, 0, 0, 0
BEGIN DESCRIPTION:
Multiple Run
END DESCRIPTION:

--- MACHO CREEK.f01 (steady flow) ---

Flow Title=Multiple
Program Version=5.05
Number of Profiles= 7
Profile Names=10-year,25-year,50-year,1pct_min,100-year,1pct_plu,500-year
River Rch & RM=MACHO CREEK,Reach-1         ,60991
     169     229     277     167     334     666     493
River Rch & RM=MACHO CREEK,Reach-1         ,59902
     193     262     317     192     383     765     567
River Rch & RM=MACHO CREEK,Reach-1         ,55382
     282     390     479     293     585    1167     885
River Rch & RM=MACHO CREEK,Reach-1         ,50326
     339     474     585     360     718    1433    1099
River Rch & RM=MACHO CREEK,Reach-1         ,48701
     380     532     659     406     810    1615    1242
River Rch & RM=MACHO CREEK,Reach-1         ,41543
     401     562     697     430     857    1710    1317
River Rch & RM=MACHO CREEK,Reach-1         ,39579
     450     635     790     489     976    1947    1511
River Rch & RM=MACHO CREEK,Reach-1         ,35104
     470     664     826     511    1020    2035    1580
River Rch & RM=MACHO CREEK,Reach-1         ,31180
     779    1123    1418     889    1774    3539    2820
River Rch & RM=MACHO CREEK,Reach-1         ,27711
     831    1199    1515     950    1896    3783    3016
River Rch & RM=MACHO CREEK,Reach-1         ,26035
     831    1199    1515     950    1896    3783    3016
River Rch & RM=MACHO CREEK,Reach-1         ,19647
     897    1299    1645    1034    2063    4116    3296
River Rch & RM=MACHO CREEK,Reach-1         ,18569
    1006    1461    1854    1167    2329    4646    3733
River Rch & RM=MACHO CREEK,Reach-1         ,10371
    1030    1494    1895    1193    2380    4748    3810
River Rch & RM=MACHO CREEK,Reach-1         ,4223
    1072    1559    1981    1248    2491    4970    4000
Boundary for River Rch & Prof#=MACHO CREEK,Reach-1         , 1
Up Type= 0
Dn Type= 3
Dn Slope=0.00379
Boundary for River Rch & Prof#=MACHO CREEK,Reach-1         , 2
Up Type= 0
Dn Type= 3
Dn Slope=0.00379
Boundary for River Rch & Prof#=MACHO CREEK,Reach-1         , 3
Up Type= 0
Dn Type= 3
Dn Slope=0.00379
Boundary for River Rch & Prof#=MACHO CREEK,Reach-1         , 4
Up Type= 0
Dn Type= 3
Dn Slope=0.00379
Boundary for River Rch & Prof#=MACHO CREEK,Reach-1         , 5
Up Type= 0
Dn Type= 3
Dn Slope=0.00379
Boundary for River Rch & Prof#=MACHO CREEK,Reach-1         , 6
Up Type= 0
Dn Type= 3
Dn Slope=0.00379
Boundary for River Rch & Prof#=MACHO CREEK,Reach-1         , 7
Up Type= 0
Dn Type= 3
Dn Slope=0.00379
DSS Import GetInterval= 0
DSS Import GetPeak= 0
DSS Import FillOption= 0

--- MACHO CREEK.g01 (geometry) ---

Geom Title=Existing Conditions
Program Version=5.05

River Reach=MACHO CREEK     ,Reach-1
Reach XY= 30
       2081070.8     13469074.54       2081710.8     13468094.54
       2081610.8     13465914.54       2080650.8     13465014.54
       2081160.8     13464824.54       2081400.8     13463494.54
       2083180.8     13462054.54       2082770.8     13460244.54
       2083930.8     13456804.54       2084870.8     13456994.54
      2084911.43     13454920.71       2087170.8     13452394.54
       2086280.8     13449844.54       2086630.8     13449584.54
      2085530.51     13449081.31      2085323.65     13446757.63
      2084866.18     13446745.48      2084326.43     13445688.19
      2084768.15     13443950.89       2083210.8     13442444.54
      2084180.77     13441932.36       2083470.8     13440364.54
       2084180.8     13440024.54      2084380.27      13438570.3
      2083505.27     13438056.41      2084528.28      13437547.3
      2083401.61     13435633.03       2083830.8     13434074.54
       2082990.8     13433724.54       2083140.8     13432814.54

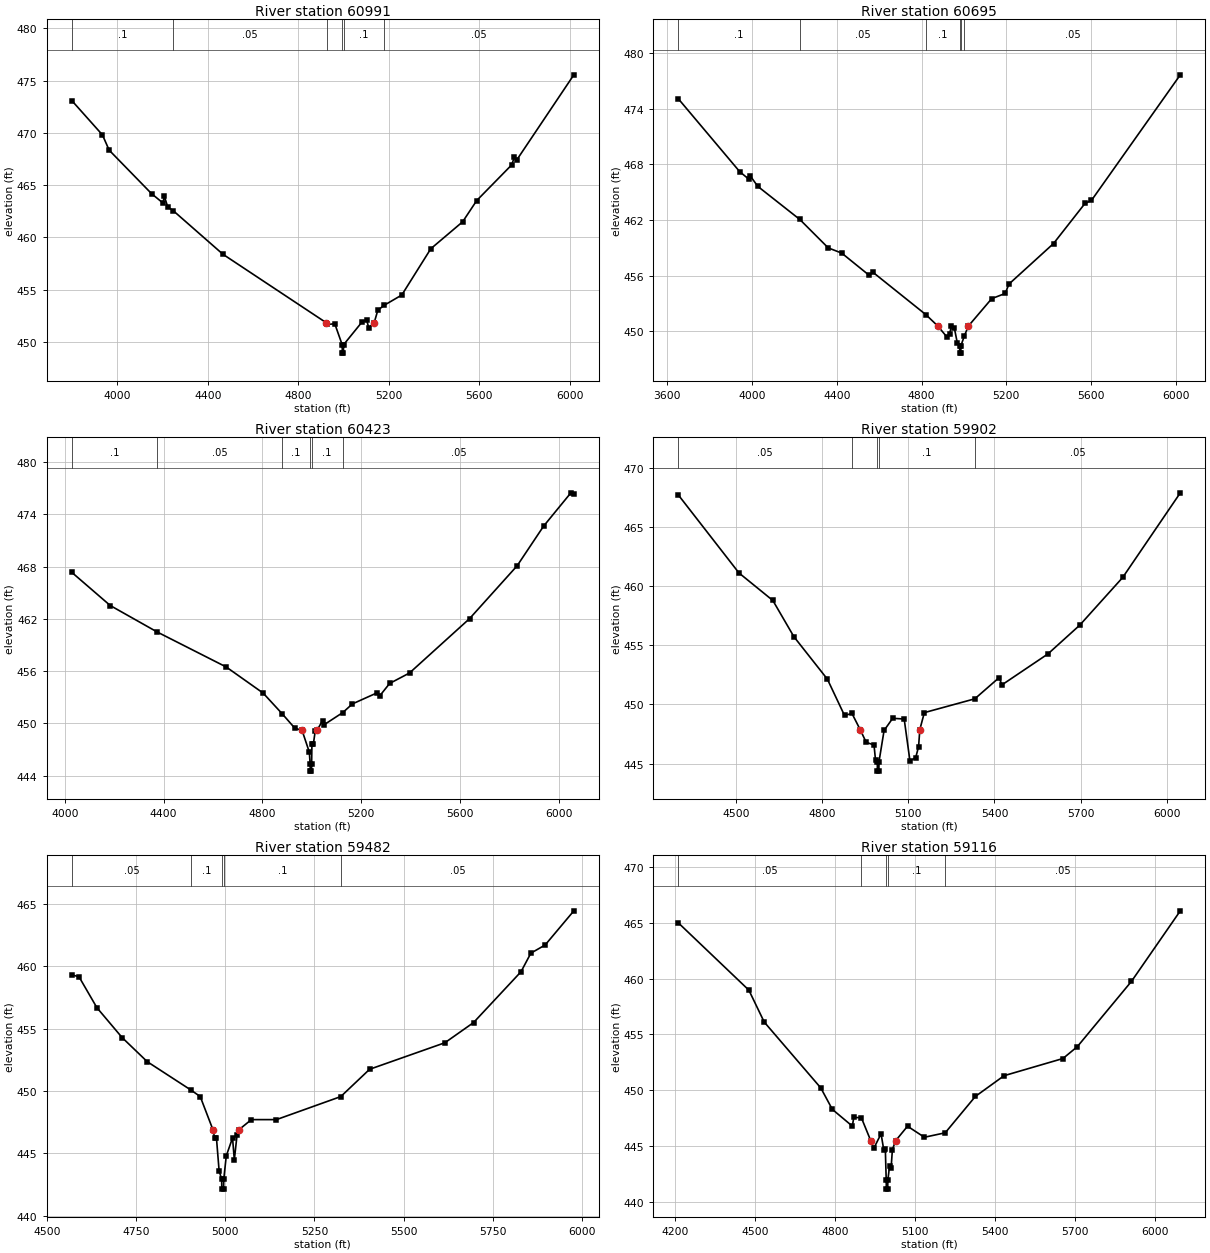
Type RM Length L Ch R = 1 ,60991   ,296,296,296
BEGIN DESCRIPTION:
MACHO CREEK 110.0
END DESCRIPTION:
XS GIS Cut Line= 3
      2082125.02     13469575.02        2081125.       13468875.
       2080160.4     13468615.44
#Sta/Elev= 30
  3798.6  473.09  3934.2   469.8  3963.9  468.34  4151.3  464.18  4201.4  463.29
    4208  463.92  4222.8  462.91  4247.6  462.54  4466.9  458.38 4922.82451.8387
  4926.8  451.66  4961.3  451.73  4994.1  449.72  4994.6  448.92  4999.6  448.92
  5000.1  449.72  5081.8   451.9  5102.1  452.11  5111.4  451.34 5135.64451.8382
  5151.4  453.01  5178.3  453.48  5257.5  454.48  5385.9  458.91  5526.7  461.49
  5588.8  463.52  5744.2  466.95  5754.5  467.67  5764.7  467.37  6018.2  475.55
#Mann= 6 ,-1 , 0
  3798.6      .1       0  4247.6     .05       0  4926.8      .1       0
  4994.1     .07       0  5000.1      .1       0  5178.3     .05       0
Bank Sta=4922.82,5135.64
XS Rating Curve= 0 ,0
Exp/Cntr=0.3,0.1

Type RM Length L Ch R = 1 ,60695   ,272,272,272
BEGIN DESCRIPTION:
MACHO CREEK 109.0
END DESCRIPTION:
XS GIS Cut Line= 3
      2082225.01     13469525.01      2081219.56     13468620.66
      2080225.55     13468400.61
#Sta/Elev= 30
  3651.3  475.07  3941.7   467.2  3984.3   466.4    3991  466.76  4026.9  465.62
  4225.5  462.05  4359.5  458.99  4423.1  458.43  4550.9  456.07  4571.8  456.34
  4820.8  451.79 4877.08450.5653  4918.6  449.42  4932.8  449.72  4940.3  450.55
  4954.5   450.4  4968.7  448.77  4979.9  448.45  4980.4  447.65  4985.4  447.65
  4985.9  448.45  5002.6  449.53 5021.03450.5651  5131.2  453.52  5194.8  454.08
  5213.1   455.1  5423.1  459.46  5571.6  463.78  5602.3  464.11  6021.7  477.64
#Mann= 6 ,-1 , 0
  3651.3      .1       0  4225.5     .05       0  4820.8      .1       0
  4979.9     .07       0  4985.9      .1       0  5002.6     .05       0
Bank Sta=4877.08,5021.03
XS Rating Curve= 0 ,0
Exp/Cntr=0.3,0.1

Type RM Length L Ch R = 1 ,60423   ,521,521,521
BEGIN DESCRIPTION:
MACHO CREEK 108.0
END DESCRIPTION:
XS GIS Cut Line= 3
       2082150.5     13469016.95        2081375.       13468425.
      2080323.02     13468316.21
#Sta/Elev= 30
  4028.2  467.35  4183.9  463.54    4374   460.5  4653.7  456.48  4803.3  453.48
  4880.8  451.09  4932.1  449.43 4960.51449.2251  4990.3  446.69  4993.5  445.32
    4994  444.52    4999  444.52  4999.5  445.32  5000.7  447.59  5006.3  447.59
  5013.9  449.08 5021.53449.2249    5044  450.32  5050.7  449.86  5125.9  451.25
  5164.7  452.24  5265.2  453.52  5275.2  453.16  5315.5  454.59  5395.9  455.79
    5639  462.03  5831.7   468.1  5938.8  472.65  6049.4  476.48  6061.4  476.34
#Mann= 6 ,-1 , 0
  4028.2      .1       0    4374     .05       0  4880.8      .1       0
  4993.5     .07       0  4999.5      .1       0  5125.9     .05       0
Bank Sta=4960.51,5021.53
XS Rating Curve= 0 ,0
Exp/Cntr=0.3,0.1

Type RM Length L Ch R = 1 ,59902   ,420,420,420
BEGIN DESCRIPTION:
MACHO CREEK 107.0
END DESCRIPTION:
XS GIS Cut Line= 3
      2082299.15     13468343.97       2081630.8     13468134.54
      2080584.74     13468100.92
#Sta/Elev= 30
  4299.6  467.74  4510.9  461.13  4628.8   458.8  4702.2  455.73  4818.6  452.14
  4878.2  449.07  4904.1  449.24 4932.78447.8679  4953.7  446.79  4980.8  446.58
    4986  445.31  4992.2  445.16  4992.7  444.36  4997.7  444.36  4998.2  445.16
  5015.8   447.8  5045.8  448.83  5085.8  448.77  5105.9  445.22  5125.9  445.51
  5135.9  446.43 5140.15447.8684  5155.9  449.31  5331.6  450.48    5416  452.27
    5426  451.66  5586.1  454.28  5696.2   456.7  5846.2  460.75  6046.6  467.91
#Mann= 5 ,-1 , 0
  4299.6     .05       0  4904.1      .1       0  4992.2     .07       0
  4998.2      .1       0  5331.6     .05       0
Bank Sta=4932.78,5140.15
XS Rating Curve= 0 ,0
Exp/Cntr=0.3,0.1

Type RM Length L Ch R = 1 ,59482   ,366,366,366
BEGIN DESCRIPTION:
MACHO CREEK 106.0
END DESCRIPTION:
XS GIS Cut Line= 3
      2082075.05     13467975.01        2081675.       13467925.
      2080675.05       13468025.
#Sta/Elev= 30
  4569.3  459.32  4589.5  459.17  4639.9  456.68  4710.4  454.29    4781  452.35
  4903.7  450.07  4929.6  449.55 4965.11446.8951  4969.9  446.25    4975  446.25
  4982.5   443.6  4989.6  442.92  4990.1  442.12  4995.1  442.12  4995.6  442.92
  5002.6  444.79  5020.2  446.23  5025.2  444.47  5032.8  446.46 5038.46446.8958
    5073   447.7  5143.3   447.7  5323.8  449.55  5404.6  451.74  5615.7  453.87
  5696.1  455.49  5829.2  459.57  5856.8  461.06    5897  461.72  5977.4  464.46
#Mann= 5 ,-1 , 0
  4569.3     .05       0  4903.7      .1       0  4989.6     .07       0
  4995.6      .1       0  5323.8     .05       0
Bank Sta=4965.11,5038.46
XS Rating Curve= 0 ,0
Exp/Cntr=0.3,0.1

Type RM Length L Ch R = 1 ,59116   ,401,401,401
BEGIN DESCRIPTION:
MACHO CREEK 105.0
END DESCRIPTION:
XS GIS Cut Line= 3
      2082324.97     13467974.99        2081625.       13467575.
      2080625.03     13467974.99
#Sta/Elev= 30
    4212     465  4476.9  458.96  4534.5   456.1  4746.8  450.19    4790  448.27
  4864.9  446.77  4870.6  447.55  4898.9  447.52 4934.13445.4592  4945.5  444.78
  4972.8  446.08  4982.9  444.64  4988.7  444.76  4992.1  441.92  4992.6  441.12
  4997.7  441.12  4998.2  441.92  5004.5  443.16  5010.3  442.98  5015.3  444.67
 5027.43445.4595    5072  446.76  5135.3  445.77  5213.4  446.17  5326.5  449.43
  5434.2  451.29    5655  452.83  5708.8  453.89  5912.1  459.75  6095.2  466.07
#Mann= 5 ,-1 , 0
    4212     .05       0  4898.9      .1       0  4992.1     .07       0
  4998.2      .1       0  5213.4     .05       0
Bank Sta=4934.13,5027.43
XS Rating Curve= 0 ,0
Exp/Cntr=0.3,0.1

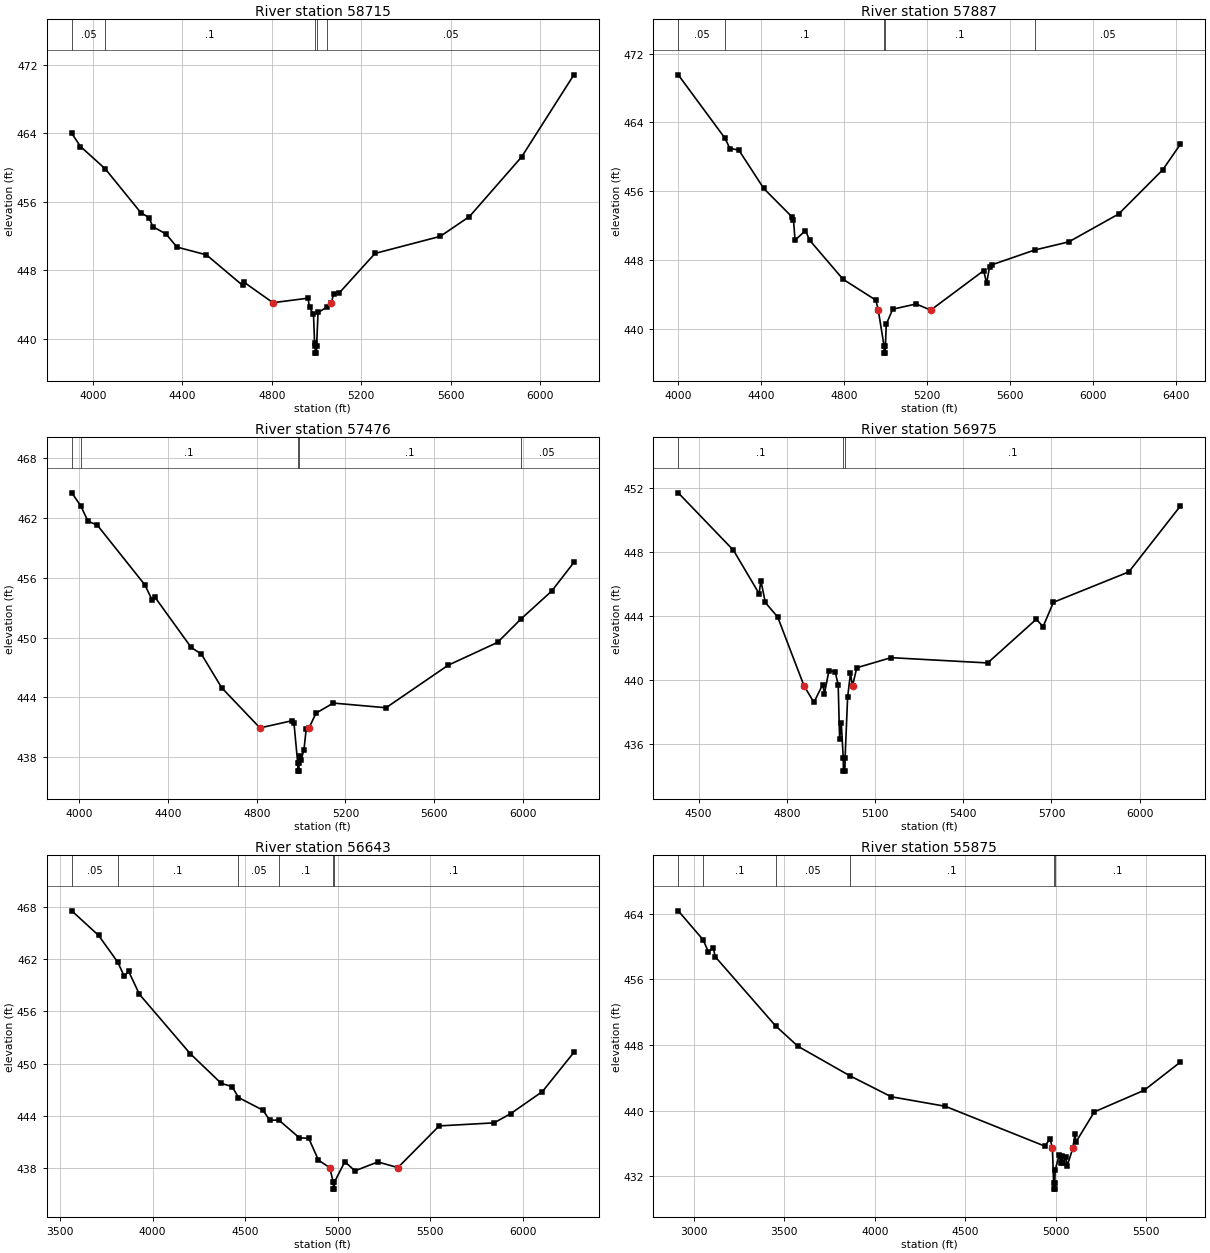
Type RM Length L Ch R = 1 ,58715   ,828,828,828
BEGIN DESCRIPTION:
MACHO CREEK 104.0
END DESCRIPTION:
XS GIS Cut Line= 3
      2082475.01       13466875.        2081475.       13467275.
      2080475.02     13467874.99
#Sta/Elev= 30
  3906.4  463.98  3945.4  462.45  4056.1  459.84  4214.7  454.74  4251.1  454.16
  4268.6   453.1  4327.8  452.24  4376.3  450.72  4508.2  449.81  4669.8  446.25
  4675.1  446.64 4805.26444.2293  4961.9  444.76  4968.6  443.68  4986.4  442.88
  4991.2  439.56    4994  439.15  4994.5  438.35  4999.6  438.35  5000.1  439.15
  5006.8  443.09  5047.8  443.73 5065.54444.2298  5076.7  445.24  5100.1  445.33
  5261.4  449.98  5552.9  451.97  5683.2  454.28  5916.4  461.24  6149.6  470.81
#Mann= 5 ,-1 , 0
  3906.4     .05       0  4056.1      .1       0    4994     .07       0
  5000.1      .1       0  5047.8     .05       0
Bank Sta=4805.26,5065.54
XS Rating Curve= 0 ,0
Exp/Cntr=0.3,0.1

Type RM Length L Ch R = 1 ,57887   ,411,411,411
BEGIN DESCRIPTION:
MACHO CREEK 103.0
END DESCRIPTION:
XS GIS Cut Line= 3
      2082625.04       13466775.        2081625.       13466675.
      2080625.03     13467674.97
#Sta/Elev= 30
  4000.8  469.53  4226.6  462.15  4249.6  460.97  4292.3  460.81  4412.9  456.33
  4551.1  452.98  4556.1   452.7  4563.6  450.33  4613.9  451.44    4634  450.32
  4794.8  445.79  4953.1  443.36 4964.63442.2028  4992.7  438.01  4993.2  437.21
  4998.4  437.21  4998.9  438.01  5003.3  440.57  5034.1  442.31  5147.2  442.92
  5217.2442.2031  5472.5  446.79  5486.7  445.33  5500.8  447.21  5514.9  447.49
  5717.6  449.18  5882.6  450.13  6123.1  453.37  6335.2   458.5    6420  461.45
#Mann= 5 ,-1 , 0
  4000.8     .05       0  4226.6      .1       0  4992.7     .07       0
  4998.9      .1       0  5717.6     .05       0
Bank Sta=4964.63,5217.2
XS Rating Curve= 0 ,0
Exp/Cntr=0.3,0.1

Type RM Length L Ch R = 1 ,57476   ,501,501,501
BEGIN DESCRIPTION:
MACHO CREEK 102.0
END DESCRIPTION:
XS GIS Cut Line= 3
      2082475.01       13466675.        2081475.       13466375.
      2080474.99       13467075.
#Sta/Elev= 30
  3965.3  464.55  4005.8  463.24  4038.4   461.7  4080.2  461.31    4295   455.3
  4328.1  453.76  4341.2  454.04  4503.9  449.01    4550  448.34  4641.3  444.97
 4814.06440.9246  4959.7  441.65  4967.6   441.4  4984.5  437.38    4985  436.58
  4990.2  436.58  4990.7  437.38  4992.8  438.06  4998.9  437.67  5012.4  438.69
  5022.9  440.84 5035.21440.9247  5067.3  442.41  5144.9  443.42  5382.9  442.95
  5662.8  447.22    5886  449.52  5989.5  451.83  6130.2  454.68    6230  457.55
#Mann= 5 ,-1 , 0
  3965.3     .05       0  4005.8      .1       0  4984.5     .07       0
  4990.7      .1       0  5989.5     .05       0
Bank Sta=4814.06,5035.21
XS Rating Curve= 0 ,0
Exp/Cntr=0.3,0.1

Type RM Length L Ch R = 1 ,56975   ,332,332,332
BEGIN DESCRIPTION:
MACHO CREEK 101.0
END DESCRIPTION:
XS GIS Cut Line= 3
      2082075.04     13466375.02        2081625.       13466075.
      2080624.97     13466675.02
#Sta/Elev= 30
  4430.9  451.69  4618.7   448.1  4705.9  445.39  4711.9  446.21  4726.9  444.84
    4769  443.93 4858.73439.6227  4892.2   438.6  4922.2  439.71  4928.2  439.15
  4943.2  440.57  4964.3  440.52  4974.7   439.7  4979.6  436.32  4985.4  437.28
    4992   435.1  4992.5   434.3  4997.7   434.3  4998.2   435.1  5006.8  438.91
  5016.5  440.41 5023.44439.6225  5037.9  440.76  5154.5  441.39    5483  441.06
  5648.2  443.79  5671.5  443.33  5706.5  444.85    5963  446.75    6138  450.86
#Mann= 3 ,-1 , 0
  4430.9      .1       0    4992     .07       0  4998.2      .1       0
Bank Sta=4858.73,5023.44
XS Rating Curve= 0 ,0
Exp/Cntr=0.3,0.1

Type RM Length L Ch R = 1 ,56643   ,768,768,768
BEGIN DESCRIPTION:
MACHO CREEK 100.0
END DESCRIPTION:
XS GIS Cut Line= 4
      2082726.63     13466484.14      2081629.41     13465810.53
      2080671.07     13466067.47      2080480.84     13466457.46
#Sta/Elev= 30
  3563.4  467.56  3708.6  464.73  3812.8  461.64  3846.9  460.04  3870.4  460.63
  3928.8  457.98  4203.4  451.16  4371.6  447.74  4429.6  447.38  4464.4  446.12
  4597.7  444.65  4633.1   443.5    4682  443.54  4793.1   441.5  4844.3  441.43
  4896.9  438.92 4957.56438.0721  4976.6   436.4  4977.1   435.6  4982.3   435.6
  4982.8   436.4  5039.3  438.75  5093.6   437.7  5217.8  438.72 5326.01438.0722
  5549.1  442.86  5845.7  443.21  5935.8  444.27  6107.4  446.81    6277   451.3
#Mann= 6 ,-1 , 0
  3563.4     .05       0  3812.8      .1       0  4464.4     .05       0
    4682      .1       0  4976.6     .07       0  4982.8      .1       0
Bank Sta=4957.56,5326.01
XS Rating Curve= 0 ,0
Exp/Cntr=0.3,0.1

Type RM Length L Ch R = 1 ,55875   ,493,493,493
BEGIN DESCRIPTION:
MACHO CREEK 99.0
END DESCRIPTION:
XS GIS Cut Line= 5
      2082650.22     13466338.29      2081129.41      13465400.8
      2080779.75     13465625.85      2080600.63     13465889.75
        2080460.     13466098.11
#Sta/Elev= 30
  2915.1  464.37  3052.5  460.84  3081.6  459.37  3109.2  459.87  3118.3   458.8
  3453.4  450.33    3576  447.86    3862  444.27  4091.7   441.7  4389.7  440.54
  4939.6  435.68  4968.5  436.59 4981.55435.4245  4987.9  431.24  4988.4  430.44
  4993.7  430.44  4994.2  431.24    4997  432.76  5018.2  434.57  5027.4  433.64
  5033.3  434.48  5039.9  433.59  5054.5  434.38  5063.7   433.3 5094.05 435.425
    5106  437.13  5111.9   436.2  5213.1  439.86  5488.1  442.49  5687.8  445.92
#Mann= 6 ,-1 , 0
  2915.1     .05       0  3052.5      .1       0  3453.4     .05       0
    3862      .1       0  4987.9     .07       0  4994.2      .1       0
Bank Sta=4981.55,5094.05
XS Rating Curve= 0 ,0
Exp/Cntr=0.3,0.1

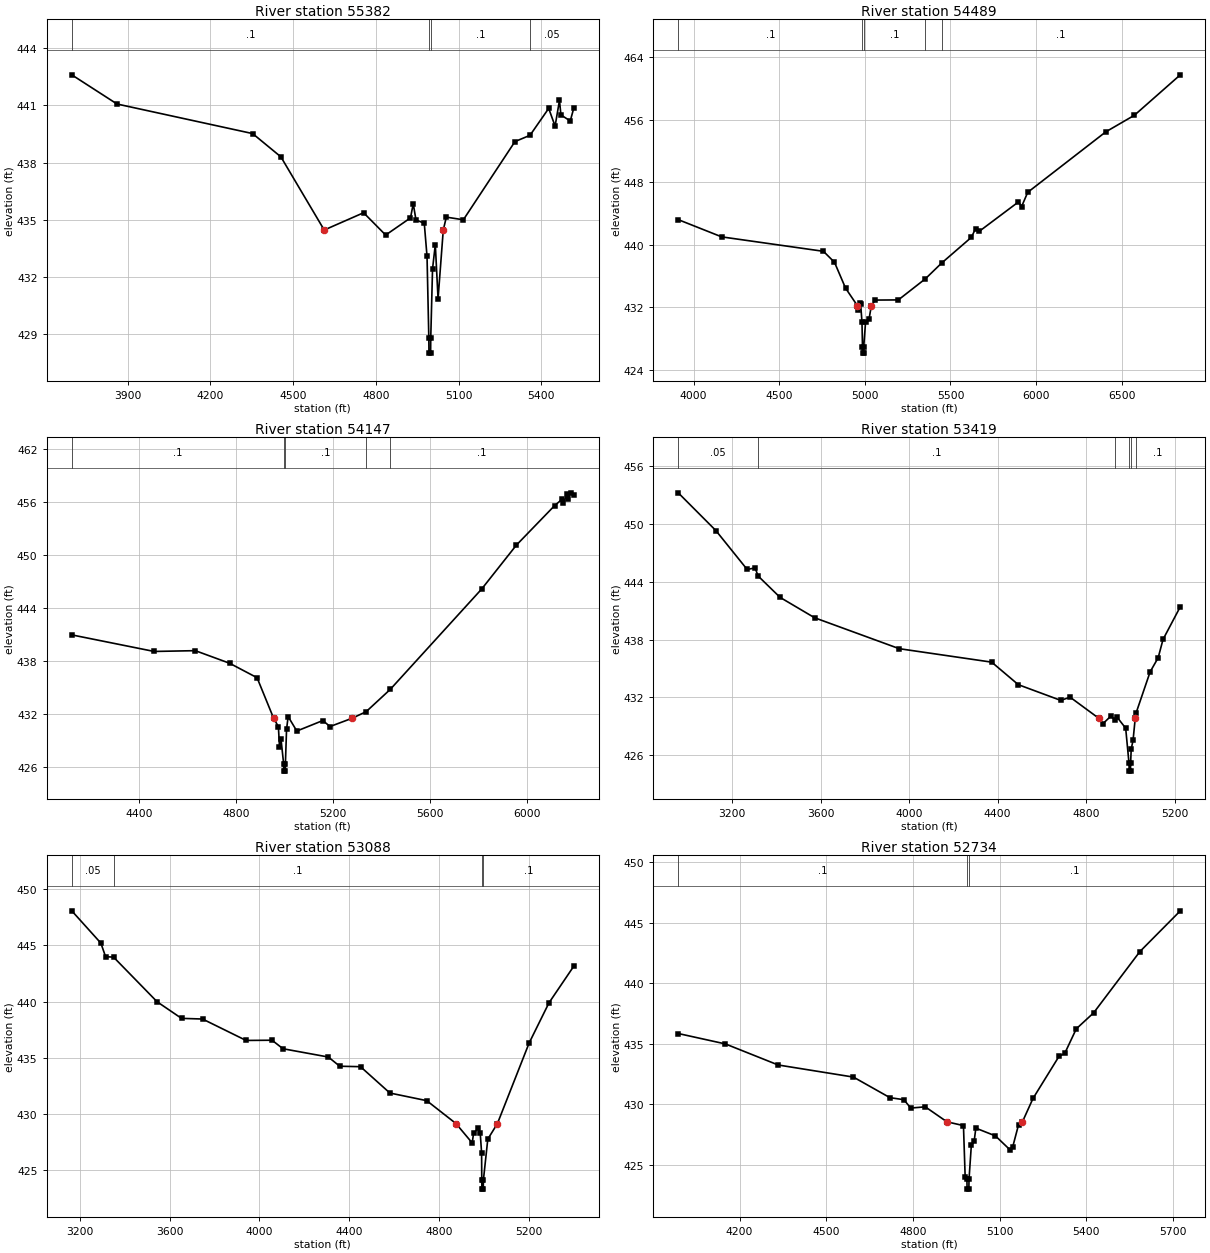
Type RM Length L Ch R = 1 ,55382   ,893,893,893
BEGIN DESCRIPTION:
MACHO CREEK 98.0
END DESCRIPTION:
XS GIS Cut Line= 4
      2081878.56     13465514.92      2081192.82     13465263.19
      2080548.72     13465262.32      2080119.55     13465384.14
#Sta/Elev= 30
  3697.5   442.6  3861.6  441.07  4353.3  439.52  4455.8   438.3 4612.96434.4641
  4755.8  435.37  4835.8   434.2  4925.8   435.1  4935.8  435.84  4945.8  434.99
  4975.8  434.82  4985.8  433.08  4992.3  428.81  4992.8  428.01  4998.8  428.01
  4999.3  428.81  5005.8  432.43  5015.8   433.7  5025.8  430.86 5044.68434.4645
  5055.8  435.14  5117.5     435  5304.6   439.1  5359.3  439.43    5427  440.84
  5450.2  439.91  5466.1  441.26  5471.3   440.5  5505.2  440.18  5518.2  440.87
#Mann= 4 ,-1 , 0
  3697.5      .1       0  4992.3     .07       0  4999.3      .1       0
  5359.3     .05       0
Bank Sta=4612.96,5044.68
XS Rating Curve= 0 ,0
Exp/Cntr=0.3,0.1

Type RM Length L Ch R = 1 ,54489   ,342,342,342
BEGIN DESCRIPTION:
MACHO CREEK 97.0
END DESCRIPTION:
XS GIS Cut Line= 4
       2081970.5     13465526.67      2081072.89     13465007.55
      2080970.46     13464920.74      2079333.71     13464269.86
#Sta/Elev= 30
  3909.8  443.21  4163.7     441  4757.9  439.15  4822.5  437.74  4887.1  434.43
 4956.11432.1876    4961  431.58  4968.7  432.56  4975.3  432.34    4983  430.11
    4986   426.9  4986.5   426.1  4992.6   426.1  4993.1   426.9  5003.9  430.05
  5024.7  430.51  5037.8432.1872    5061   432.9  5195.5  432.92  5353.5  435.63
  5448.1  437.64  5621.9  440.94  5646.2  442.04    5668  441.71  5897.1  445.48
  5915.5  444.89  5951.1  446.71  6407.1  454.46  6574.4  456.59  6842.4  461.77
#Mann= 5 ,-1 , 0
  3909.8      .1       0    4986     .07       0  4993.1      .1       0
  5353.5     .05       0  5448.1      .1       0
Bank Sta=4956.11,5037.8
XS Rating Curve= 0 ,0
Exp/Cntr=0.3,0.1

Type RM Length L Ch R = 1 ,54147   ,728,728,728
BEGIN DESCRIPTION:
MACHO CREEK 96.0
END DESCRIPTION:
XS GIS Cut Line= 3
      2081775.02     13465325.02        2081175.       13464725.
      2080175.01     13464025.01
#Sta/Elev= 30
  4121.9  440.95  4461.3  439.07    4631  439.16  4772.5  437.73  4885.6  436.09
 4954.01431.4751  4973.5  430.54  4977.9  428.28    4984  429.17  4995.2  426.29
  4995.7  425.49  5001.8  425.49  5002.3  426.29  5007.1  430.23  5013.6  431.68
  5049.4  430.04  5156.6  431.23  5186.3  430.55 5275.92431.4753  5334.9  432.23
  5434.3  434.76  5811.4  446.16  5954.4  451.14  6112.2  455.63  6141.9  456.32
    6148  455.87  6162.8  456.97  6168.9   456.4  6177.6  457.07  6191.1  456.84
#Mann= 5 ,-1 , 0
  4121.9      .1       0  4995.2     .07       0  5002.3      .1       0
  5334.9     .05       0  5434.3      .1       0
Bank Sta=4954.01,5275.92
XS Rating Curve= 0 ,0
Exp/Cntr=0.3,0.1

Type RM Length L Ch R = 1 ,53419   ,331,331,331
BEGIN DESCRIPTION:
MACHO CREEK 95.0
END DESCRIPTION:
XS GIS Cut Line= 3
        2082425.       13465575.        2081075.       13464075.
      2080875.03     13463925.02
#Sta/Elev= 30
  2957.2  453.25  3127.2  449.33  3268.5  445.29  3304.4  445.45    3318  444.61
  3417.2  442.39  3573.4  440.27  3955.4  437.06  4373.2  435.66  4493.5  433.32
  4684.9  431.69  4727.5  432.02 4856.46429.8378  4876.2  429.28  4911.3  430.05
  4928.4  429.69  4939.7  429.94  4978.4   428.8  4993.5  425.14  4994.1  424.34
  5000.2  424.34  5000.7  425.14  5003.4  426.64  5011.7  427.53 5021.54429.8383
    5025  430.35  5088.8  434.65  5125.2  436.12  5147.1  438.02  5225.2  441.42
#Mann= 6 ,-1 , 0
  2957.2     .05       0    3318      .1       0  4928.4     .07       0
  4993.5     .07       0  5000.7     .07       0    5025      .1       0
Bank Sta=4856.46,5021.54
XS Rating Curve= 0 ,0
Exp/Cntr=0.3,0.1

Type RM Length L Ch R = 1 ,53088   ,354,354,354
BEGIN DESCRIPTION:
MACHO CREEK 94.0
END DESCRIPTION:
XS GIS Cut Line= 3
      2082325.02     13465325.03        2081275.       13463825.
      2080875.03       13463775.
#Sta/Elev= 30
  3164.8  448.09  3294.3  445.21  3315.2     444  3350.8  443.96  3544.5  439.98
  3653.1   438.5  3746.8  438.44  3940.4  436.53  4055.9  436.55  4104.7  435.79
  4306.6  435.05  4357.2  434.23  4449.6  434.19  4580.4  431.84  4744.3  431.16
 4874.33429.1192  4946.6  427.39  4952.7  428.25  4973.6  428.69  4982.3  428.28
  4988.4  426.51  4989.2  424.07  4989.7  423.27  4995.8  423.27  4996.4  424.07
    5016  427.73 5058.88429.1192  5199.9   436.3  5288.1  439.88  5398.9  443.16
#Mann= 4 ,-1 , 0
  3164.8     .05       0  3350.8      .1       0  4989.2     .07       0
  4996.4      .1       0
Bank Sta=4874.33,5058.88
XS Rating Curve= 0 ,0
Exp/Cntr=0.3,0.1

Type RM Length L Ch R = 1 ,52734   ,473,473,473
BEGIN DESCRIPTION:
MACHO CREEK 93.0
END DESCRIPTION:
XS GIS Cut Line= 3
      2082008.97     13464514.95        2081475.       13463625.
      2080774.96       13463625.
#Sta/Elev= 30
  3987.9  435.86  4151.1     435  4333.8  433.26  4594.3  432.26  4720.6  430.56
  4769.2  430.39  4792.5   429.7  4843.1   429.8 4917.98 428.563  4975.2  428.25
  4981.1  423.98  4987.2   423.8  4987.7     423  4993.9     423  4994.4   423.8
  5002.4  426.61  5012.1  426.94    5018  428.04  5085.8   427.4  5135.8  426.26
  5145.8   426.5  5165.8  428.32 5179.33 428.563  5215.8  430.49  5305.8  433.97
  5325.8  434.22  5365.8  436.25  5425.8  437.57  5585.8  442.63  5725.8     446
#Mann= 3 ,-1 , 0
  3987.9      .1       0  4987.2     .07       0  4994.4      .1       0
Bank Sta=4917.98,5179.33
XS Rating Curve= 0 ,0
Exp/Cntr=0.3,0.1

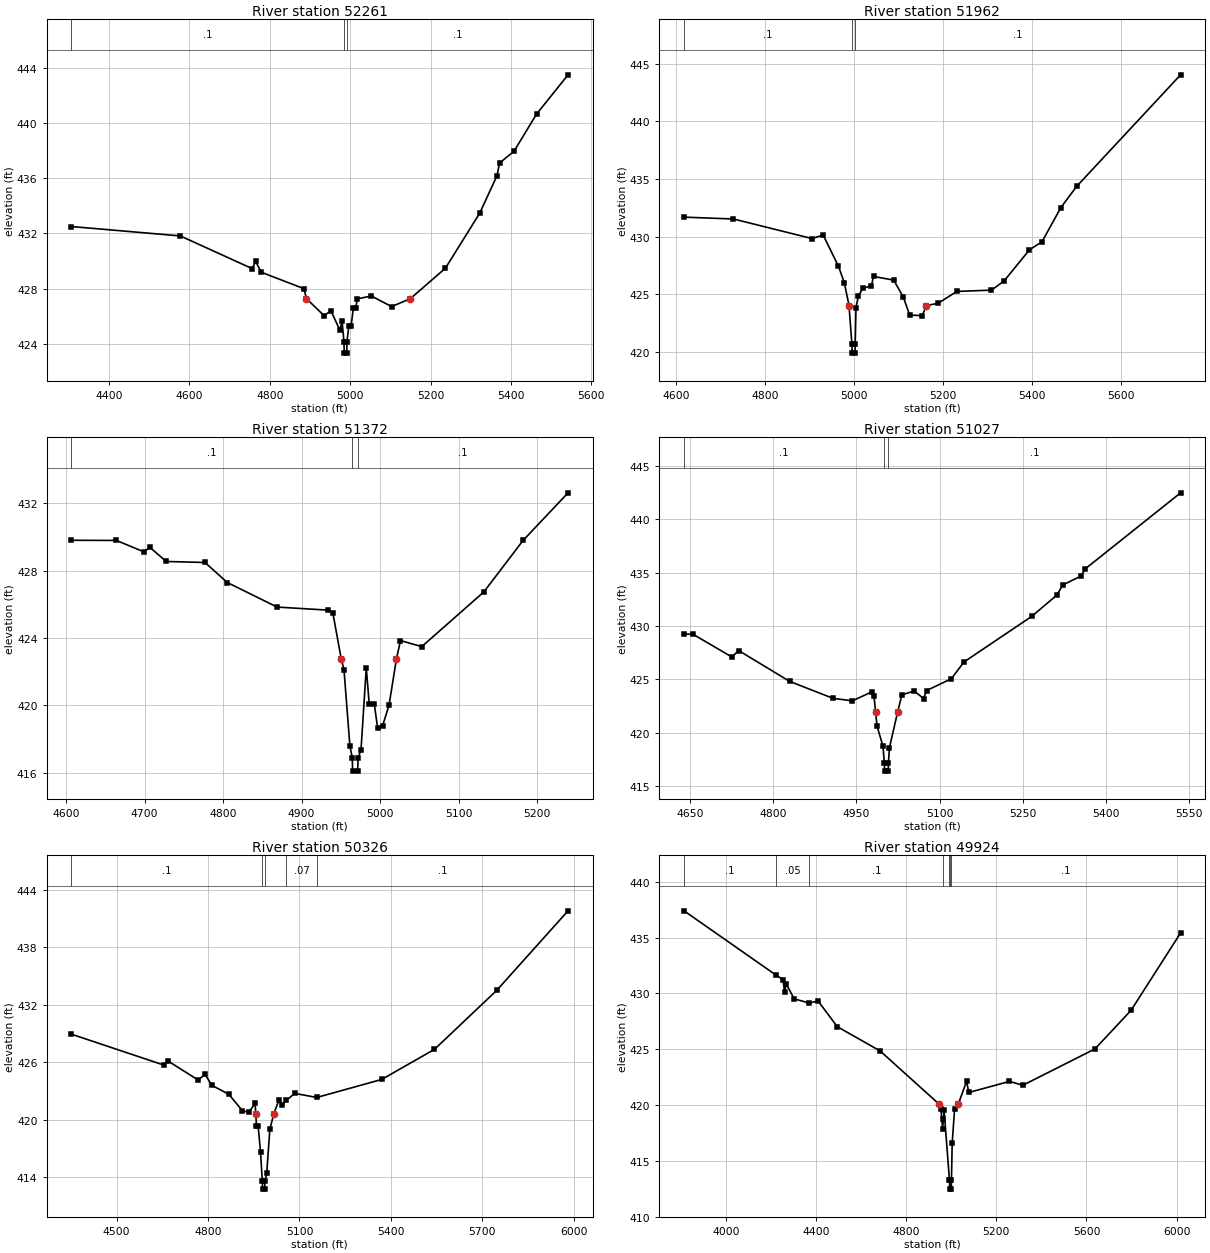
Type RM Length L Ch R = 1 ,52261   ,299,299,299
BEGIN DESCRIPTION:
MACHO CREEK 92.0
END DESCRIPTION:
XS GIS Cut Line= 3
      2081939.91     13464054.82        2081625.       13463425.
      2081274.98     13463024.98
#Sta/Elev= 30
  4306.5  432.49  4577.4  431.81  4756.3  429.44  4764.7  429.97  4778.7  429.18
  4884.9  427.99 4891.14427.2702  4935.2  426.03    4952  426.39  4974.3  424.99
  4979.9  425.63  4984.6  424.12  4985.2  423.32  4991.5  423.32    4992  424.12
  4996.7  425.32  5002.3  425.26  5007.9   426.6    5014   426.6  5017.8  427.25
  5052.9  427.46  5103.2  426.69 5149.89427.2701    5237  429.47  5322.4  433.46
  5365.2  436.16  5371.8  437.09  5407.9  437.95  5463.9  440.64  5542.2  443.48
#Mann= 3 ,-1 , 0
  4306.5      .1       0  4984.6     .07       0    4992      .1       0
Bank Sta=4891.14,5149.89
XS Rating Curve= 0 ,0
Exp/Cntr=0.3,0.1

Type RM Length L Ch R = 1 ,51962   ,590,590,590
BEGIN DESCRIPTION:
MACHO CREEK 91.0
END DESCRIPTION:
XS GIS Cut Line= 3
      2081993.22     13463752.12        2081875.       13463325.
      2081374.97     13462874.97
#Sta/Elev= 30
  4618.6  431.69  4729.7  431.53  4906.1  429.83  4931.3  430.13  4965.6  427.43
  4978.8     426 4989.34424.0162  4995.8  420.68  4996.4  419.88  5002.7  419.88
  5003.2  420.68  5005.1  423.84  5010.3  424.82  5020.3  425.51  5039.4  425.72
  5044.6  426.54  5089.8  426.22  5111.5  424.74  5125.7  423.18  5154.1  423.14
 5163.12424.0145  5189.2   424.2  5231.8  425.24  5309.5  425.35  5337.9  426.15
  5394.8  428.85  5423.2  429.56  5465.4  432.52  5500.9  434.36  5734.5  444.05
#Mann= 3 ,-1 , 0
  4618.6      .1       0  4995.8     .07       0  5003.2      .1       0
Bank Sta=4989.34,5163.12
XS Rating Curve= 0 ,0
Exp/Cntr=0.3,0.1

Type RM Length L Ch R = 1 ,51372   ,345,345,345
BEGIN DESCRIPTION:
double MACHO CREEK 90.0
END DESCRIPTION:
XS GIS Cut Line= 3
      2082209.48     13463281.03        2081925.       13463025.
      2081725.02     13462875.02
#Sta/Elev= 30
  4606.8  429.81    4664   429.8  4699.2  429.12  4706.6  429.39  4727.6  428.55
  4776.9  428.49  4805.3   427.3  4868.8  425.84  4933.1  425.66  4939.8   425.5
 4950.52422.7536    4954  422.12  4961.5  417.61  4964.5  416.89  4965.1  416.09
  4971.4  416.09    4972  416.89  4975.7  417.36  4982.4  422.23  4986.2  420.05
  4992.7  420.05  4996.8  418.67  5003.1  418.77  5011.4  420.01 5020.83422.7537
    5026  423.85  5053.1  423.49  5132.2  426.74  5182.2   429.8  5239.5  432.63
#Mann= 3 ,-1 , 0
  4606.8      .1       0  4964.5     .07       0    4972      .1       0
Bank Sta=4950.52,5020.83
XS Rating Curve= 0 ,0
Exp/Cntr=0.3,0.1

Type RM Length L Ch R = 1 ,51027   ,701,701,701
BEGIN DESCRIPTION:
double MACHO CREEK 89.0
END DESCRIPTION:
XS GIS Cut Line= 3
        2082250.     13463150.95        2082175.     13462822.83
        2081675.     13462572.83
#Sta/Elev= 30
  4639.2  429.24  4655.6  429.21  4725.6  427.08  4737.6  427.69  4829.9  424.79
  4907.7  423.21  4942.8  422.97  4978.6  423.83  4981.7  423.47 4984.67421.9479
  4987.3   420.6  4998.1   418.7  5000.4  417.18    5001  416.38  5007.3  416.38
  5007.9  417.18  5009.7  418.58 5024.55421.9464  5032.1  423.54  5054.4  423.89
  5071.2  423.19  5076.8  423.94  5121.5  425.05  5143.9  426.61  5266.5   430.9
  5311.2  432.87  5322.7  433.85  5355.9  434.69  5361.9  435.31  5534.8  442.48
#Mann= 3 ,-1 , 0
  4639.2      .1       0  5000.4     .07       0  5007.9      .1       0
Bank Sta=4984.67,5024.55
XS Rating Curve= 0 ,0
Exp/Cntr=0.3,0.1

Type RM Length L Ch R = 1 ,50326   ,402,402,402
BEGIN DESCRIPTION:
MACHO CREEK 8070
END DESCRIPTION:
XS GIS Cut Line= 3
      2083075.01     13462975.01        2082725.       13462475.
      2081725.05     13462275.01
#Sta/Elev= 30
  4351.7  428.93  4653.8  425.72  4668.6  426.13  4767.2  424.16  4790.7  424.74
  4811.6  423.61  4868.3  422.66  4912.8  420.95  4933.7  420.77  4954.6  421.71
 4956.56420.6454    4959  419.32  4964.6  419.32  4972.2  416.65  4978.2  413.57
    4979  412.77  4985.9  412.77  4986.6  413.57  4992.6  414.42  5002.8  418.99
 5015.99420.6456  5033.4  422.11  5043.6  421.54  5057.2  422.03  5084.4  422.76
  5156.8  422.33    5370  424.21  5543.3  427.35  5747.3  433.49  5981.8   441.8
#Mann= 5 ,-1 , 0
  4351.7      .1       0  4978.2     .07       0  4986.6      .1       0
  5057.2     .07       0  5156.8      .1       0
Bank Sta=4956.56,5015.99
XS Rating Curve= 0 ,0
Exp/Cntr=0.3,0.1

Type RM Length L Ch R = 1 ,49924   ,463,463,463
BEGIN DESCRIPTION:
MACHO CREEK 86.0
END DESCRIPTION:
XS GIS Cut Line= 3
      2083824.99     13462974.99        2082925.       13462175.
      2081925.05       13462175.
#Sta/Elev= 30
  3813.8  437.39  4220.4  431.66  4253.2  431.24  4259.9  430.14  4267.4  430.85
  4302.6  429.51  4369.2  429.14  4408.8  429.32  4494.1  427.02  4684.7  424.84
 4946.76420.0717    4954  419.66  4961.5  417.88  4965.2  418.79  4968.2  419.52
  4991.9  413.29  4992.4  413.28  4993.1  412.48  5000.1  412.48  5000.8  413.28
  5004.1  416.61  5014.6  419.62 5030.91420.0715  5067.9  422.13  5077.9  421.13
  5257.9  422.12  5317.9  421.78  5637.9  425.03  5797.9  428.48  6017.9  435.41
#Mann= 7 ,-1 , 0
  3813.8      .1       0  4220.4     .05       0  4369.2      .1       0
  4965.2     .12       0  4991.9      .1       0  4992.4     .07       0
  5000.8      .1       0
Bank Sta=4946.76,5030.91
XS Rating Curve= 0 ,0
Exp/Cntr=0.3,0.1

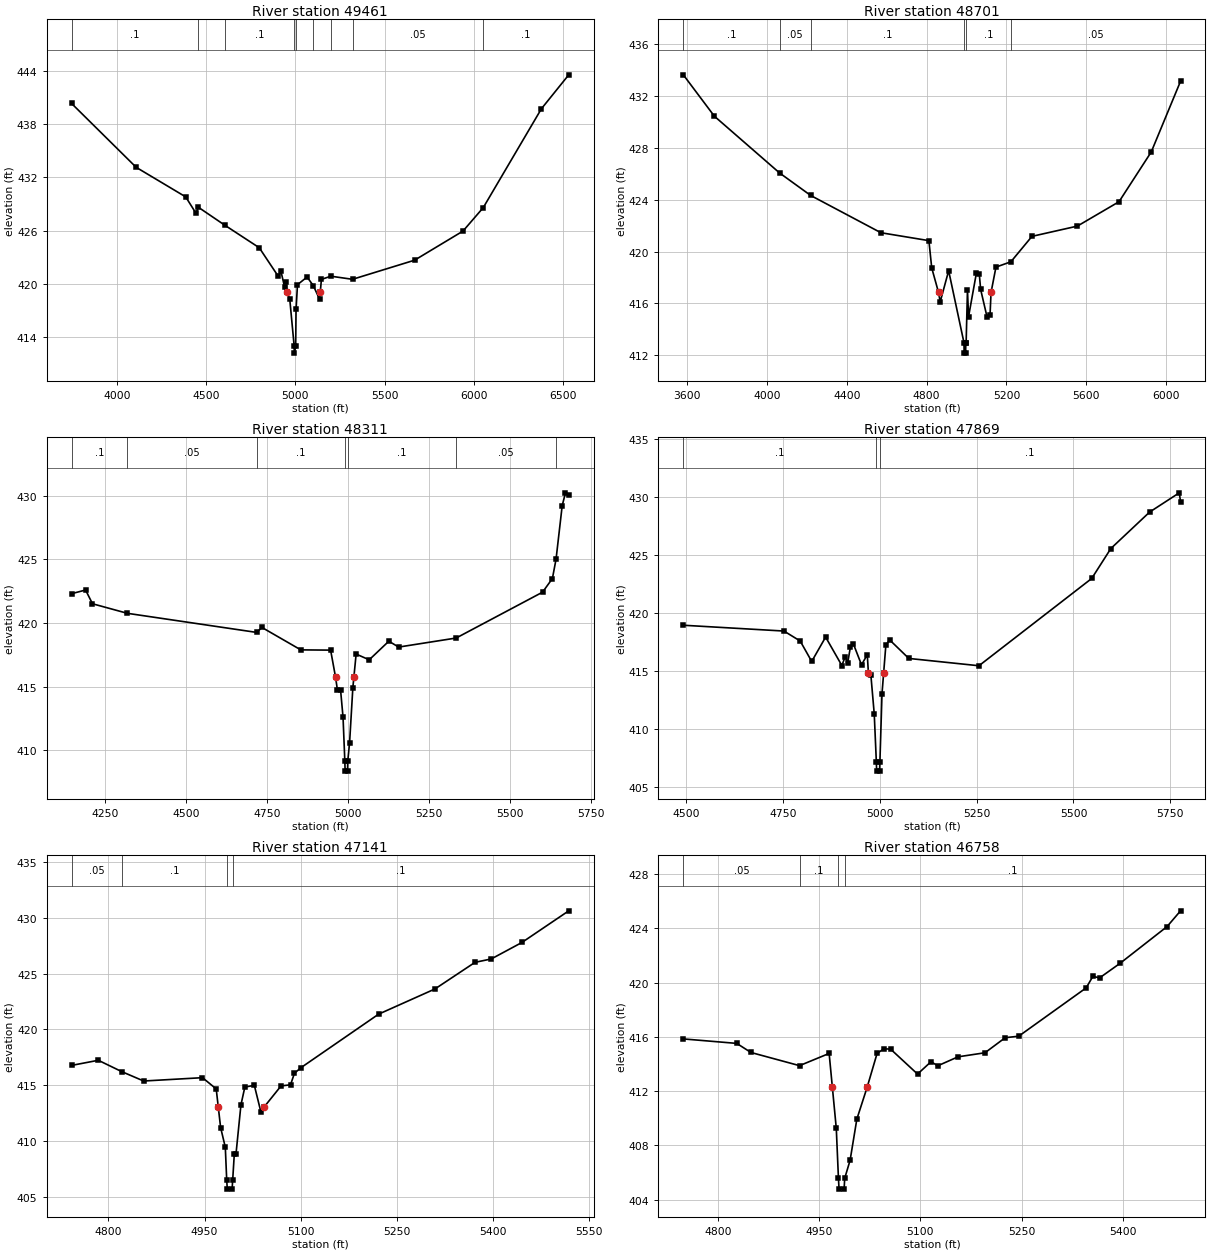
Type RM Length L Ch R = 1 ,49461   ,760,760,760
BEGIN DESCRIPTION:
MACHO CREEK 85.0
END DESCRIPTION:
XS GIS Cut Line= 3
      2084175.01     13462775.01        2083175.       13461975.
      2081675.02       13462125.
#Sta/Elev= 30
  3744.5  440.36  4107.1  433.14  4384.8   429.8  4441.7  427.97  4456.4  428.62
  4602.6  426.62    4797  424.06  4904.3  420.81  4918.7   421.4  4939.5   419.6
  4947.5  420.22 4951.86419.1096  4968.3  418.23  4992.9  412.95  4993.6  412.15
  5001.4  412.95  5003.5  417.08  5011.5  419.88  5065.3  420.75  5100.3  419.77
  5135.7  418.23 5139.61419.1097  5145.7  420.48  5198.7  420.84  5320.1  420.49
  5668.3  422.65  5939.7  425.94  6053.3  428.59  6379.4  439.76  6532.6  443.59
#Mann= 9 ,-1 , 0
  3744.5      .1       0  4456.4     .05       0  4602.6      .1       0
  4992.9     .07       0  5001.4      .1       0  5100.3     .12       0
  5198.7      .1       0  5320.1     .05       0  6053.3      .1       0
Bank Sta=4951.86,5139.61
XS Rating Curve= 0 ,0
Exp/Cntr=0.3,0.1

Type RM Length L Ch R = 1 ,48701   ,390,390,390
BEGIN DESCRIPTION:
MACHO CREEK 84.0
END DESCRIPTION:
XS GIS Cut Line= 3
      2084024.97     13462424.97        2083025.       13461425.
      2082025.01       13461825.
#Sta/Elev= 30
  3581.3  433.62  3736.8  430.43    4064  426.05  4219.6  424.32  4571.2  421.45
  4811.6  420.84  4825.8  418.74 4859.98416.8429  4868.2  416.12  4910.6  418.52
  4987.4  412.97  4988.2  412.17  4995.6  412.17  4996.5  412.97  4998.2  412.97
  5004.9  417.05  5010.3  414.97  5049.3  418.32  5064.1  418.27  5070.9  417.08
  5103.2  414.94    5118  415.12    5123416.8438  5147.6   418.8  5222.4  419.21
    5328  421.17  5555.5  421.96  5764.2  423.84  5925.8  427.68  6072.5  433.13
#Mann= 6 ,-1 , 0
  3581.3      .1       0    4064     .05       0  4219.6      .1       0
  4987.4     .07       0  4996.5      .1       0  5222.4     .05       0
Bank Sta=4859.98,5123
XS Rating Curve= 0 ,0
Exp/Cntr=0.3,0.1

Type RM Length L Ch R = 1 ,48311   ,442,442,442
BEGIN DESCRIPTION:
MACHO CREEK 83.0
END DESCRIPTION:
XS GIS Cut Line= 3
      2083606.92     13461664.53        2083025.       13461075.
      2082324.96     13461175.01
#Sta/Elev= 30
  4147.2   422.3  4190.6  422.59  4211.9  421.51  4319.7  420.76  4719.1  419.26
  4735.2  419.65  4855.3  417.89  4947.3  417.87 4962.53415.7505  4968.5  414.71
  4978.1  414.73  4985.7  412.59  4991.2  409.17  4992.1  408.37  4999.5  408.37
  5000.3  409.17  5005.9   410.6    5016  414.93 5019.15415.7502  5026.1  417.56
  5066.5  417.11  5127.1  418.57  5157.4  418.11    5335  418.82  5601.8  422.42
  5632.2  423.49  5643.5  425.01  5662.5  429.22  5672.6  430.22  5682.7  430.05
#Mann= 7 ,-1 , 0
  4147.2      .1       0  4319.7     .05       0  4719.1      .1       0
  4991.2     .07       0  5000.3      .1       0    5335     .05       0
  5643.5      .1       0
Bank Sta=4962.53,5019.15
XS Rating Curve= 0 ,0
Exp/Cntr=0.3,0.1

Type RM Length L Ch R = 1 ,47869   ,728,728,728
BEGIN DESCRIPTION:
MACHO CREEK 82.0
END DESCRIPTION:
XS GIS Cut Line= 3
        2083300.     13461050.01      2083027.33     13460654.56
      2082225.22     13460619.92
#Sta/Elev= 30
  4493.1  418.92  4752.8  418.42  4794.7  417.56  4824.4   415.8  4860.3   417.9
  4902.2  415.45    4911  416.22  4917.1  415.66  4924.3  417.04    4932  417.31
  4952.9  415.51  4967.8  416.38 4970.81414.7747  4977.1  414.62  4985.8  411.27
  4991.2  407.15    4992  406.35  4999.5  406.35  5000.4  407.15  5005.8  413.02
 5009.97414.7757  5015.8  417.23  5025.8  417.65    5075  416.06    5256  415.43
    5547  422.95  5596.4  425.53  5696.4  428.67    5773  430.33  5776.3  429.56
#Mann= 3 ,-1 , 0
  4493.1      .1       0  4991.2     .07       0  5000.4      .1       0
Bank Sta=4970.81,5009.97
XS Rating Curve= 0 ,0
Exp/Cntr=0.3,0.1

Type RM Length L Ch R = 1 ,47141   ,383,383,383
BEGIN DESCRIPTION:
MACHO CREEK 81.0
END DESCRIPTION:
XS GIS Cut Line= 3
        2083050.     13460259.03        2082875.       13460075.
      2082374.97     13459924.99
#Sta/Elev= 30
  4742.3  416.77  4784.1  417.23  4820.8  416.21  4854.9  415.37  4946.7  415.67
  4968.1  414.66 4971.33413.0356    4975  411.19  4982.3  409.43  4984.5  406.47
  4985.4  405.67  4992.9  405.67  4993.8  406.47  4996.3  408.78  4998.9  408.78
  5006.7  413.23  5012.8  414.83  5027.6  414.98    5038  412.56 5042.81413.0349
  5069.3  414.93  5084.1  415.03  5090.2  416.07  5100.7  416.58  5221.6  421.37
  5309.5  423.63  5372.1  426.02  5397.3  426.32  5445.2   427.8  5518.3  430.64
#Mann= 4 ,-1 , 0
  4742.3     .05       0  4820.8      .1       0  4984.5     .07       0
  4993.8      .1       0
Bank Sta=4971.33,5042.81
XS Rating Curve= 0 ,0
Exp/Cntr=0.3,0.1

Type RM Length L Ch R = 1 ,46758   ,362,362,362
BEGIN DESCRIPTION:
MACHO CREEK 80.0
END DESCRIPTION:
XS GIS Cut Line= 3
      2083150.01     13460000.13        2083075.       13459775.
        2082575.       13459775.
#Sta/Elev= 30
  4748.5  415.85  4827.7  415.52  4848.8  414.85  4920.8  413.88  4964.7  414.78
 4969.47412.2959  4975.3  409.26  4978.5  405.58  4979.4  404.78  4986.9  404.78
  4987.8  405.58  4995.8  406.91  5005.8  409.94  5021.1412.2959  5035.8  414.78
  5045.8  415.12  5055.8   415.1  5095.8  413.26  5115.8  414.17  5125.8  413.87
  5155.8  414.53  5195.8  414.83  5225.8  415.94  5245.8  416.05  5345.8  419.61
  5355.8  420.46  5365.8  420.35  5395.8  421.41  5465.8  424.13  5485.8  425.29
#Mann= 4 ,-1 , 0
  4748.5     .05       0  4920.8      .1       0  4978.5     .07       0
  4987.8      .1       0
Bank Sta=4969.47,5021.1
XS Rating Curve= 0 ,0
Exp/Cntr=0.3,0.1