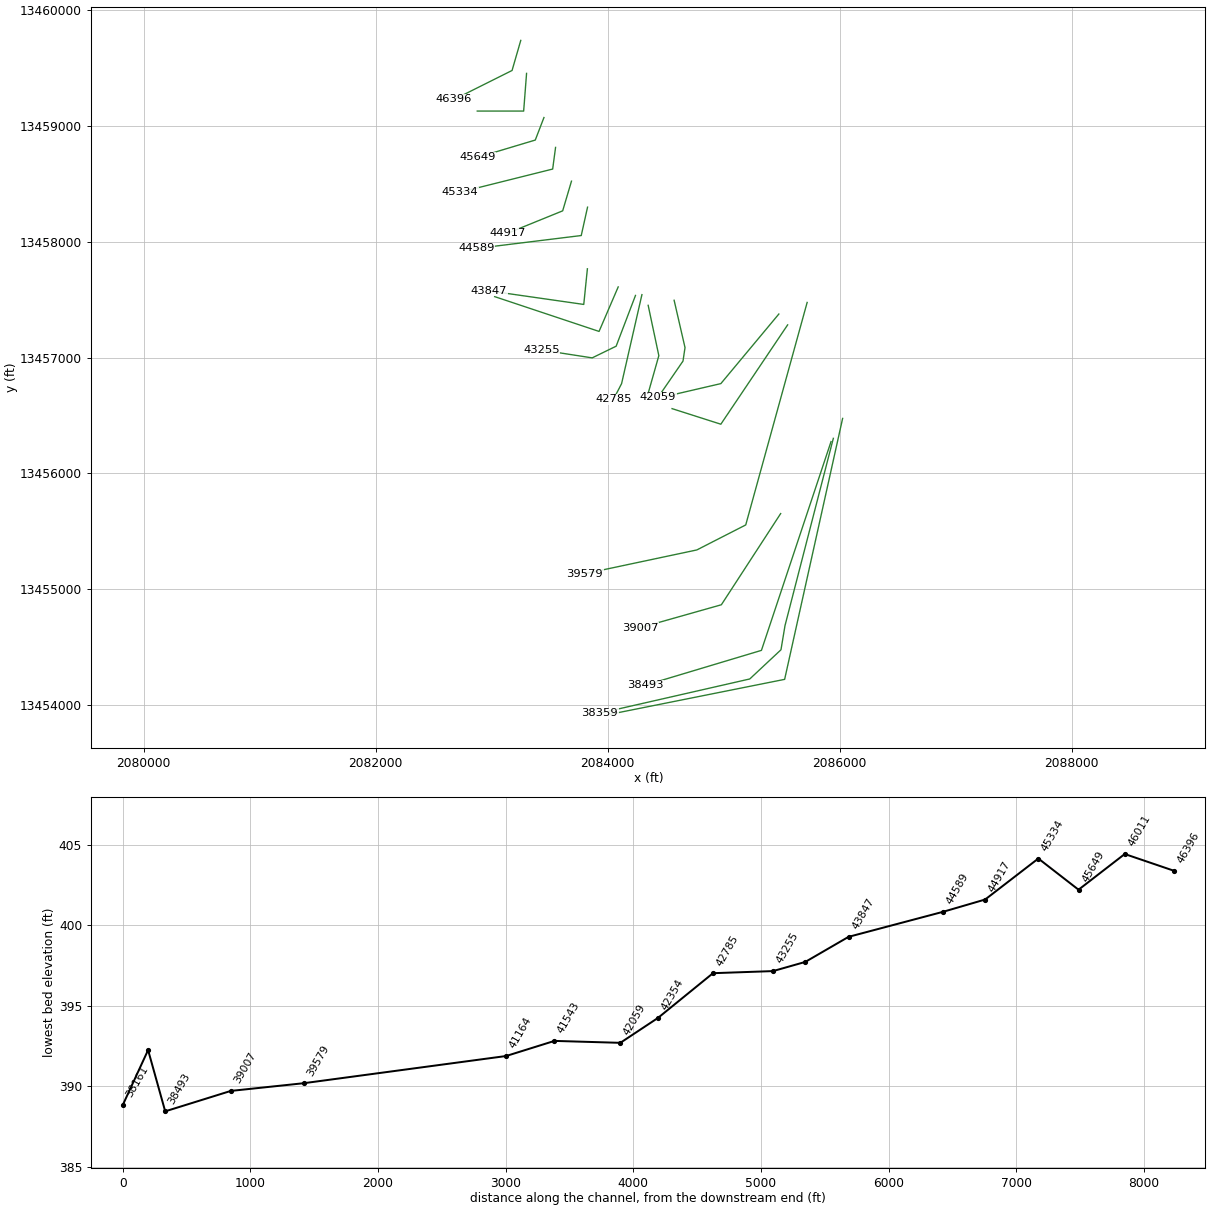
HEC-RAS study MACHO CREEK.prj: MACHO CREEK Base Level Engineering

--- MACHO CREEK.g01 (geometry) --- (continued)

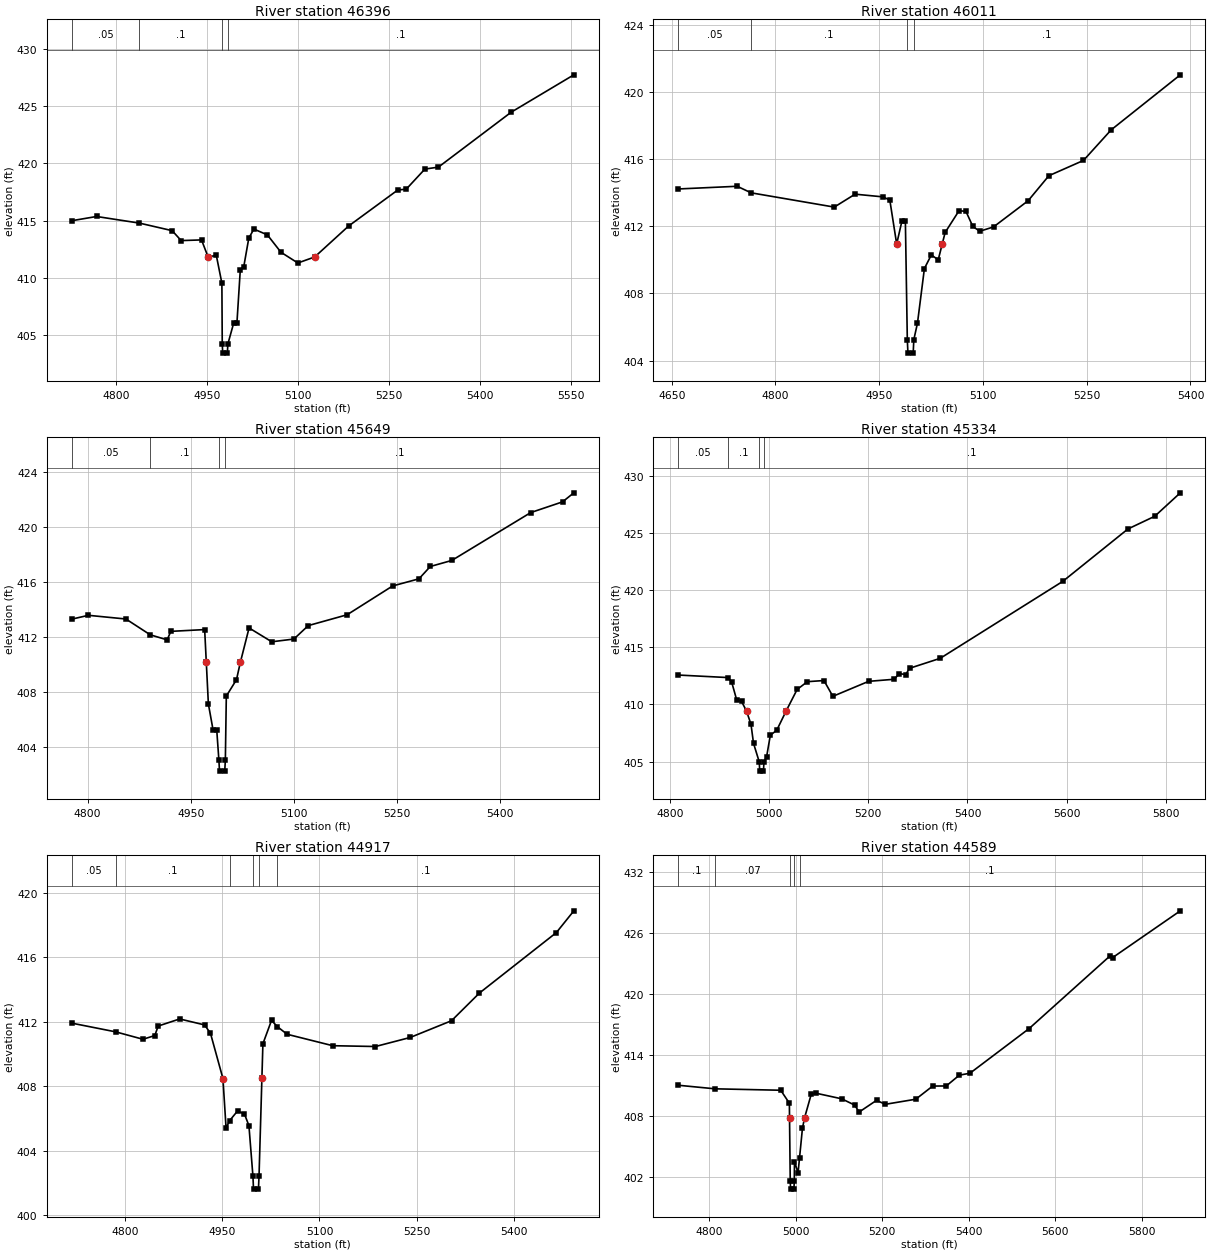
Type RM Length L Ch R = 1 ,46396   ,385,385,385
BEGIN DESCRIPTION:
MACHO CREEK 79.0
END DESCRIPTION:
XS GIS Cut Line= 3
      2083250.01     13459734.19        2083175.       13459475.
      2082675.04     13459225.02
#Sta/Elev= 30
  4726.7  414.99  4767.7  415.36  4838.5  414.78  4892.4  414.12  4907.3  413.25
  4940.9  413.31 4951.73 411.817  4965.3  411.96  4974.5  409.52  4975.1   404.2
  4975.9   403.4  4983.5   403.4  4984.4   404.2  4993.9  406.02  4999.3  406.02
  5004.9   410.7  5010.5  410.93  5018.9  413.46  5027.3  414.26  5049.6  413.75
    5072  412.23  5099.9  411.29 5127.71411.8171  5183.8  414.53  5264.9  417.68
  5278.8  417.75  5309.6  419.51  5331.9  419.68  5452.1  424.49  5555.5  427.76
#Mann= 4 ,-1 , 0
  4726.7     .05       0  4838.5      .1       0  4975.1     .07       0
  4984.4      .1       0
Bank Sta=4951.73,5127.71
XS Rating Curve= 0 ,0
Exp/Cntr=0.3,0.1

Type RM Length L Ch R = 1 ,46011   ,362,362,362
BEGIN DESCRIPTION:
MACHO CREEK 78.0
END DESCRIPTION:
XS GIS Cut Line= 3
        2083300.     13459449.98        2083275.       13459125.
      2082875.04       13459125.
#Sta/Elev= 30
  4659.4  414.22  4744.6  414.38  4764.8  413.99    4885  413.14  4915.1  413.91
  4955.2  413.75  4965.3  413.56 4975.22 410.941  4982.8  412.31  4987.8  412.31
  4990.6  405.24  4991.5  404.44  4999.1  404.44    5000  405.24  5005.3  406.23
  5015.3  409.48  5025.3  410.29  5035.3     410 5041.07410.9405  5045.3  411.63
  5065.3  412.92  5075.3  412.89  5085.3  411.99  5095.3   411.7  5115.3  411.96
  5165.3  413.52  5195.3  415.01  5245.3  415.92  5285.3  417.74  5385.3  421.02
#Mann= 4 ,-1 , 0
  4659.4     .05       0  4764.8      .1       0  4990.6     .07       0
    5000      .1       0
Bank Sta=4975.22,5041.07
XS Rating Curve= 0 ,0
Exp/Cntr=0.3,0.1

Type RM Length L Ch R = 1 ,45649   ,315,315,315
BEGIN DESCRIPTION:
MACHO CREEK 77.0
END DESCRIPTION:
XS GIS Cut Line= 3
        2083450.      13459069.3        2083375.       13458875.
      2082874.99       13458725.
#Sta/Elev= 30
  4776.9   413.3  4801.1  413.58  4855.7  413.31    4891  412.16  4915.6  411.79
    4921  412.41  4970.2  412.54 4972.58410.1513  4975.6  407.12  4982.5   405.2
  4987.8   405.2  4990.9  403.02  4991.8  402.22  4999.4  402.22  5000.3  403.02
  5001.7  407.69  5016.5  408.89 5022.09410.1477  5034.8  412.66  5067.8  411.65
    5100  411.85  5120.9  412.83  5177.4  413.62  5243.6  415.72  5281.9  416.24
  5298.4  417.14  5329.7  417.58  5444.5  421.07  5490.7  421.85  5507.2  422.51
#Mann= 4 ,-1 , 0
  4776.9     .05       0    4891      .1       0  4990.9     .07       0
  5000.3      .1       0
Bank Sta=4972.58,5022.09
XS Rating Curve= 0 ,0
Exp/Cntr=0.3,0.1

Type RM Length L Ch R = 1 ,45334   ,417,417,417
BEGIN DESCRIPTION:
MACHO CREEK 76.0
END DESCRIPTION:
XS GIS Cut Line= 3
      2083550.01     13458811.68        2083525.       13458625.
      2082724.97     13458424.99
#Sta/Elev= 30
  4816.4  412.56  4916.5  412.34    4924  411.98  4934.1  410.42  4944.2  410.25
 4954.16409.4117  4963.2  408.25  4968.3  406.59  4979.9  404.96  4980.8  404.16
  4988.4  404.16  4989.3  404.96  4994.7  405.42  5002.2   407.3  5015.1  407.73
    5034409.4117  5056.3   411.3  5076.9  411.98  5110.4  412.08  5128.4   410.7
  5200.6  412.01  5252.1  412.19  5262.4  412.69  5275.3   412.6  5283.1  413.15
  5344.9  414.02  5592.3  420.75  5723.7  425.33  5777.8  426.44  5829.4  428.49
#Mann= 4 ,-1 , 0
  4816.4     .05       0  4916.5      .1       0  4979.9     .07       0
  4989.3      .1       0
Bank Sta=4954.16,5034
XS Rating Curve= 0 ,0
Exp/Cntr=0.3,0.1

Type RM Length L Ch R = 1 ,44917   ,328,328,328
BEGIN DESCRIPTION:
MACHO CREEK 75.0
END DESCRIPTION:
XS GIS Cut Line= 3
      2083687.21     13458520.49      2083611.35     13458264.68
      2083139.95     13458072.99
#Sta/Elev= 30
  4717.3  411.91  4785.1  411.37  4827.3  410.91  4845.6  411.14  4850.8  411.73
    4884  412.17  4922.5   411.8  4931.6  411.28 4950.84408.4744  4955.7  405.39
  4961.2  405.86  4973.4  406.46  4984.1  406.27    4991  405.55  4997.2  402.41
  4998.1  401.61  5005.7  401.61  5006.6  402.41 5011.03408.4787  5012.6  410.63
  5025.9  412.08    5035  411.69    5050  411.22  5120.5  410.51  5186.5  410.46
  5240.1  411.02    5304  412.06  5347.2  413.78    5466  417.53    5493  418.88
#Mann= 6 ,-1 , 0
  4717.3     .05       0  4785.1      .1       0  4961.2     .07       0
  4997.2     .07       0  5006.6     .07       0    5035      .1       0
Bank Sta=4950.84,5011.03
XS Rating Curve= 0 ,0
Exp/Cntr=0.3,0.1

Type RM Length L Ch R = 1 ,44589   ,742,742,742
BEGIN DESCRIPTION:
MACHO CREEK 74.0
END DESCRIPTION:
XS GIS Cut Line= 3
      2083825.72     13458296.25      2083771.47     13458051.83
      2082868.09     13457940.42
#Sta/Elev= 30
  4728.8  411.04  4813.9  410.69  4965.7  410.55  4985.7  409.28 4986.08407.8307
  4987.7  401.65  4988.6  400.85  4996.2  400.85  4997.1  401.65  4997.5  403.55
  5005.8  402.45  5009.2  403.92  5015.9  406.81 5020.77407.8371  5036.1  410.14
  5046.1  410.27  5106.6  409.71  5136.8  409.09  5146.9  408.41  5187.2  409.56
  5207.4  409.17  5277.9  409.67    5317  410.96  5348.4  410.97  5378.6  412.03
  5403.2  412.22  5539.9   416.6  5727.8  423.76  5732.9  423.56  5889.4  428.15
#Mann= 5 ,-1 , 0
  4728.8      .1       0  4813.9     .07       0  4987.7     .07       0
  4997.1     .07       0  5009.2      .1       0
Bank Sta=4986.08,5020.77
XS Rating Curve= 0 ,0
Exp/Cntr=0.3,0.1

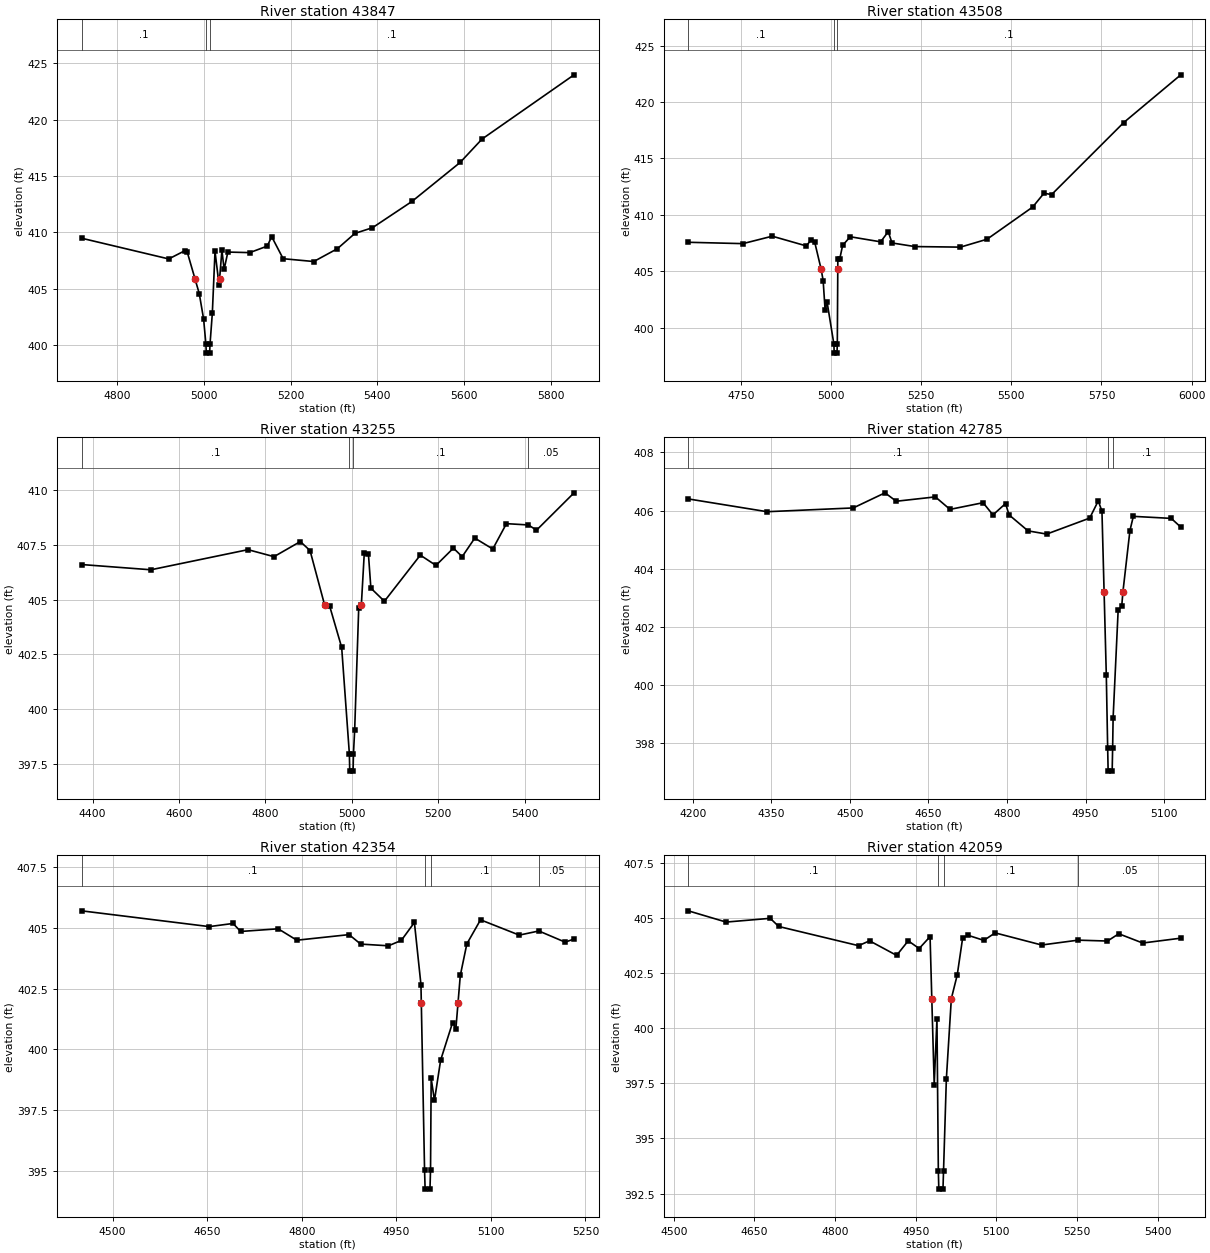
Type RM Length L Ch R = 1 ,43847   ,339,339,339
BEGIN DESCRIPTION:
MACHO CREEK 73.0
END DESCRIPTION:
XS GIS Cut Line= 3
      2083824.41     13457764.99      2083793.16      13457457.7
        2082975.       13457575.
#Sta/Elev= 30
  4718.1  409.49  4919.1  407.65  4956.8  408.39  4961.9  408.24  4979.7405.8799
  4989.5  404.57  4999.5  402.32  5004.8  400.09  5005.7  399.29  5013.4  399.29
  5014.3  400.09  5019.6  402.82  5025.8  408.32  5035.2  405.32 5036.37 405.878
  5041.7  408.42  5046.8  406.72  5055.4  408.26  5105.9  408.21  5146.3  408.79
  5156.4  409.63  5182.9  407.67  5253.5  407.42    5308  408.56  5348.4  409.92
  5388.8  410.42  5479.7  412.75  5590.8  416.21  5641.4  418.29  5853.5  423.99
#Mann= 3 ,-1 , 0
  4718.1      .1       0  5004.8     .07       0  5014.3      .1       0
Bank Sta=4979.7,5036.37
XS Rating Curve= 0 ,0
Exp/Cntr=0.3,0.1

Type RM Length L Ch R = 1 ,43508   ,253,253,253
BEGIN DESCRIPTION:
MACHO CREEK 72.0
END DESCRIPTION:
XS GIS Cut Line= 3
      2084090.05     13457608.78        2083925.       13457225.
      2083024.95     13457525.02
#Sta/Elev= 30
  4603.5  407.56    4755  407.44  4836.5   408.1  4930.7  407.24  4945.1  407.79
  4954.3  407.57 4972.03405.1844  4977.7  404.17  4983.2  401.53  4988.7  402.25
  5007.5  398.53  5008.4  397.73  5016.1  397.73    5017  398.53 5018.32405.1995
  5018.5  406.11  5023.9  406.11  5031.8  407.29  5052.9  408.05  5137.2   407.6
  5158.3   408.5  5168.8   407.5  5232.1  407.18  5358.6  407.13  5432.4  407.83
  5558.9  410.68  5590.5  411.91  5611.6  411.79  5811.8  418.18    5970  422.41
#Mann= 3 ,-1 , 0
  4603.5      .1       0  5007.5     .07       0    5017      .1       0
Bank Sta=4972.03,5018.32
XS Rating Curve= 0 ,0
Exp/Cntr=0.3,0.1

Type RM Length L Ch R = 1 ,43255   ,470,470,470
BEGIN DESCRIPTION:
double MACHO CREEK 71.0
END DESCRIPTION:
XS GIS Cut Line= 4
        2084239.     13457535.12      2084072.34     13457097.65
      2083865.74     13456996.95      2083429.11     13457064.52
#Sta/Elev= 30
  4374.4  406.61  4534.9  406.37  4759.6  407.29  4819.8  406.97  4880.7  407.66
  4903.2  407.25 4936.73404.7761  4948.3  404.73  4976.4  402.82  4994.2  397.96
  4995.1  397.16  5002.8  397.16  5003.7  397.96  5006.5  399.04  5015.9  404.64
    5022 404.775  5028.7  407.12  5038.4  407.07    5044  405.53  5075.3  404.93
  5158.4  407.04  5194.6  406.57    5235  407.36  5255.3  406.97  5284.5  407.82
  5326.1  407.32  5357.7  408.48  5408.7  408.42  5427.3  408.18  5514.2  409.89
#Mann= 4 ,-1 , 0
  4374.4      .1       0  4994.2     .07       0  5003.7      .1       0
  5408.7     .05       0
Bank Sta=4936.73,5022
XS Rating Curve= 0 ,0
Exp/Cntr=0.3,0.1

Type RM Length L Ch R = 1 ,42785   ,431,431,431
BEGIN DESCRIPTION:
MACHO CREEK 111.0
END DESCRIPTION:
XS GIS Cut Line= 3
      2084294.57     13457542.13      2084119.21     13456774.73
      2084048.68     13456638.82
#Sta/Elev= 30
  4191.6   406.4  4342.1  405.96  4506.6  406.09  4567.2  406.61  4588.7  406.32
  4663.3  406.47  4691.3  406.04  4754.4  406.27  4773.3  405.85  4797.3  406.24
  4804.1  405.85  4840.3   405.3  4875.9  405.19    4958  405.74  4974.3  406.33
  4981.4  405.98 4985.48403.2076  4989.7  400.34  4992.3  397.83  4993.2  397.03
  5000.9  397.03  5001.8  397.83  5002.7  398.86  5012.3  402.56  5019.2  402.72
 5021.49403.2108  5034.8  405.31  5041.3   405.8  5113.7  405.73  5131.9  405.43
#Mann= 3 ,-1 , 0
  4191.6      .1       0  4992.3     .07       0  5001.8      .1       0
Bank Sta=4985.48,5021.49
XS Rating Curve= 0 ,0
Exp/Cntr=0.3,0.1

Type RM Length L Ch R = 1 ,42354   ,295,295,295
BEGIN DESCRIPTION:
MACHO CREEK 112.0
END DESCRIPTION:
XS GIS Cut Line= 3
      2084348.38     13457450.09      2084440.39     13457016.05
      2084348.39     13456691.43
#Sta/Elev= 30
  4450.8  405.71  4653.4  405.06  4691.1  405.19  4703.1  404.86  4762.7  404.97
  4792.2   404.5  4875.1  404.73  4893.5  404.34  4937.5  404.27  4957.9  404.49
  4978.7  405.23  4989.1  402.67 4989.66401.9213  4994.8  395.05  4995.7  394.25
  5003.4  394.25  5004.3  395.05  5005.3  398.81  5010.5   397.9  5020.3  399.56
  5039.3  401.11  5044.5  400.86 5047.88401.9174  5051.5  403.05  5061.9  404.35
  5083.6  405.34    5145  404.71  5176.1  404.88  5217.8  404.42  5231.9  404.55
#Mann= 4 ,-1 , 0
  4450.8      .1       0  4994.8     .07       0  5004.3      .1       0
  5176.1     .05       0
Bank Sta=4989.66,5047.88
XS Rating Curve= 0 ,0
Exp/Cntr=0.3,0.1

Type RM Length L Ch R = 1 ,42059   ,516,516,516
BEGIN DESCRIPTION:
double MACHO CREEK 70.0
END DESCRIPTION:
XS GIS Cut Line= 4
      2084572.19     13457493.56      2084666.09     13457085.49
      2084648.73     13456969.17      2084433.46     13456656.68
#Sta/Elev= 30
    4527  405.32  4597.4  404.81  4679.4  404.98  4695.2  404.61  4843.6  403.74
  4864.1  403.96  4914.4   403.3    4936  403.96  4956.3  403.61  4976.6  404.15
 4979.82401.3441  4984.3  397.44  4989.4  400.42    4992   393.5  4992.9   392.7
  5000.6   392.7  5001.6   393.5  5006.9   397.7 5016.16401.3399  5027.1  402.41
  5037.2  404.09  5047.3  404.21  5076.6  403.98  5097.6  404.32  5184.1  403.77
  5251.7  403.99  5306.5  403.95  5327.5  404.28    5372  403.86  5442.8  404.08
#Mann= 4 ,-1 , 0
    4527      .1       0    4992     .07       0  5001.6      .1       0
  5251.7     .05       0
Bank Sta=4979.82,5016.16
XS Rating Curve= 0 ,0
Exp/Cntr=0.3,0.1

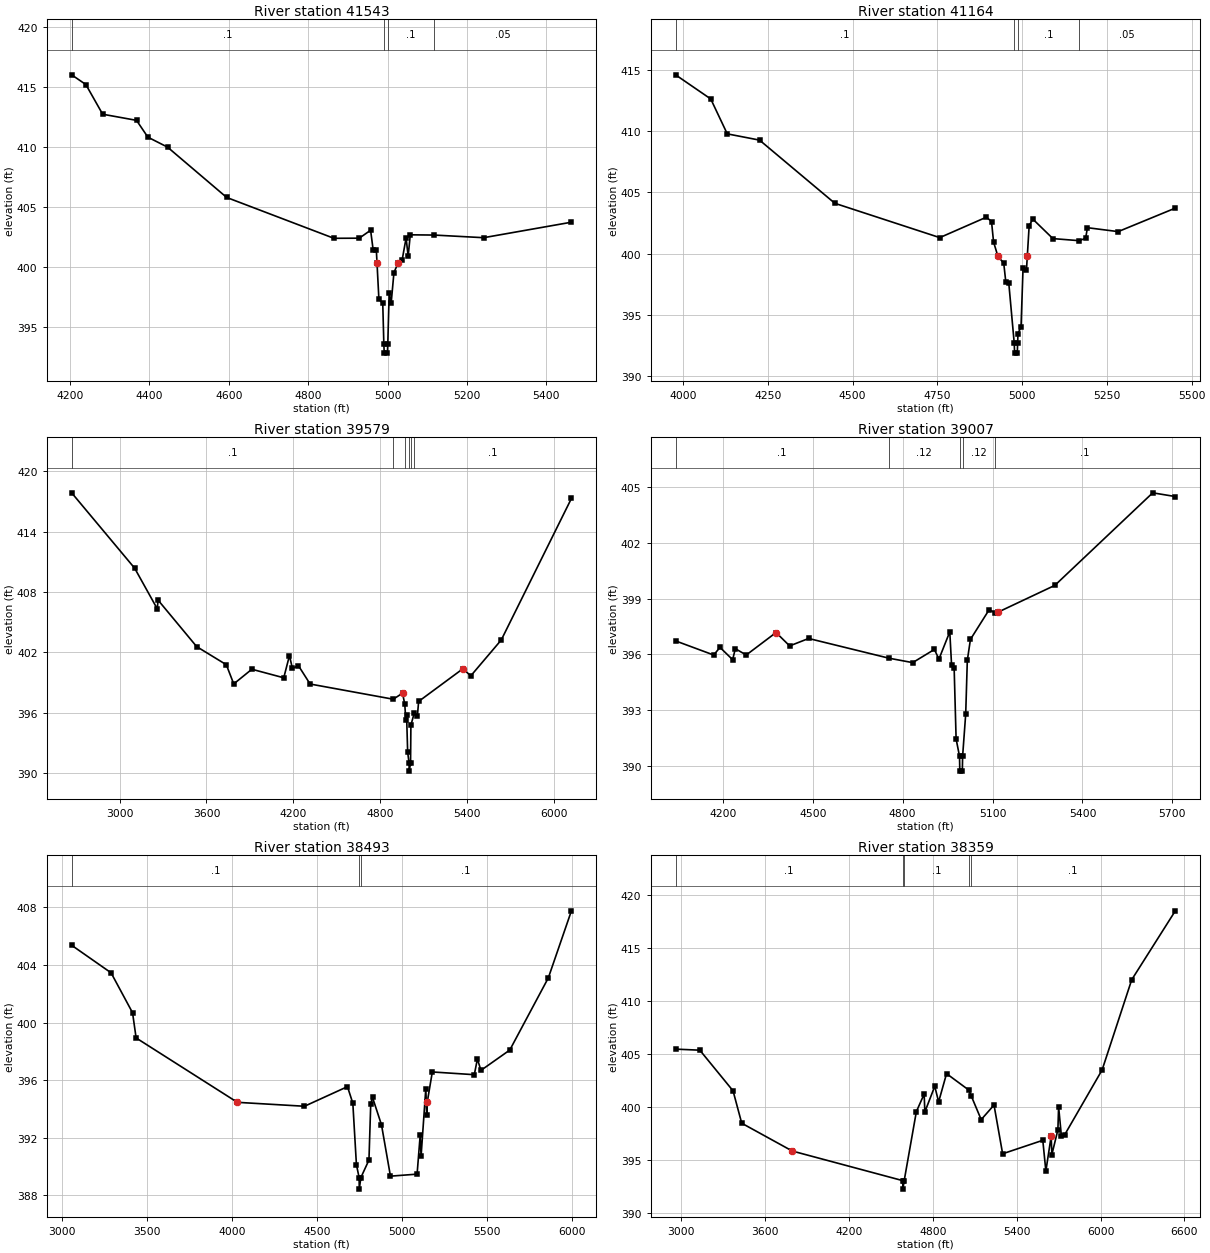
Type RM Length L Ch R = 1 ,41543   ,379,379,379
BEGIN DESCRIPTION:
double MACHO CREEK 69.0
END DESCRIPTION:
XS GIS Cut Line= 3
        2085475.       13457375.        2084975.       13456775.
      2084509.58     13456667.01
#Sta/Elev= 30
  4204.4  415.99  4240.2  415.18  4282.5  412.71  4367.8   412.2  4396.4   410.8
  4445.9  409.97  4594.9  405.78    4865  402.38  4928.8  402.39  4957.4  403.05
  4963.9  401.39  4971.8  401.42 4973.58400.2916  4978.3   397.3    4988  396.97
  4990.7  393.62  4991.7  392.82  4999.7  392.82  5000.7  393.62  5004.2  397.83
  5009.3  397.03  5016.2  399.53 5026.25400.2911  5036.7  400.55  5046.8  402.41
    5052  400.88  5057.3  402.67  5117.5  402.65  5242.1  402.43  5463.2  403.72
#Mann= 4 ,-1 , 0
  4204.4      .1       0  4990.7     .07       0  5000.7      .1       0
  5117.5     .05       0
Bank Sta=4973.58,5026.25
XS Rating Curve= 0 ,0
Exp/Cntr=0.3,0.1

Type RM Length L Ch R = 1 ,41164   ,1585,1585,1585
BEGIN DESCRIPTION:
double MACHO CREEK 68.0
END DESCRIPTION:
XS GIS Cut Line= 3
      2085550.89     13457281.48        2084975.       13456425.
      2084554.41     13456559.29
#Sta/Elev= 30
  3978.3   414.6    4082  412.63  4130.7  409.78  4225.9  409.27    4448  404.11
  4757.3  401.31  4894.9  402.98  4909.9  402.62  4915.9  400.96 4928.85399.7715
  4945.9  399.23  4951.9  397.72  4960.9  397.57  4976.9  392.68  4977.9  391.88
  4985.9  391.88  4986.9  392.68  4987.9  393.48  4996.9  394.02  5002.9  398.86
    5013   398.7 5015.36399.7724  5020.9  402.29  5031.7  402.82  5090.9  401.23
  5168.5  401.06  5187.4  401.26  5192.7  402.12  5283.3   401.8  5451.9  403.72
#Mann= 4 ,-1 , 0
  3978.3      .1       0  4976.9     .07       0  4986.9      .1       0
  5168.5     .05       0
Bank Sta=4928.85,5015.36
XS Rating Curve= 0 ,0
Exp/Cntr=0.3,0.1

Type RM Length L Ch R = 1 ,39579   ,572,572,572
BEGIN DESCRIPTION:
MACHO CREEK 67.0
END DESCRIPTION:
XS GIS Cut Line= 4
       2085719.1     13457474.84      2085189.59     13455556.47
       2084767.9     13455340.83      2083800.95     13455135.69
#Sta/Elev= 30
  2668.8  417.86  3104.3  410.36    3260  406.33  3265.9  407.19  3532.4  402.57
  3737.2  400.77  3788.4  398.86  3913.5  400.32  4133.9  399.47  4173.4  401.68
  4193.6   400.4  4235.1  400.68    4316  398.85    4890  397.34  4954.6  397.94
    4970  396.82  4976.8   395.3  4982.4  395.76  4989.8  392.08  4999.5  390.99
  5000.4  390.19  5009.8  390.99  5012.2  394.75  5034.9  395.95  5057.2   395.7
  5065.6  397.12  5370.6  400.36  5426.3  399.67  5636.4  403.23    6121   417.3
#Mann= 6 ,-1 , 0
  2668.8      .1       0    4890     .07       0    4970     .12       0
  4999.5     .07       0  5009.8     .12       0  5034.9      .1       0
Bank Sta=4954.6,5370.6
XS Rating Curve= 0 ,0
Exp/Cntr=0.3,0.1

Type RM Length L Ch R = 1 ,39007   ,514,514,514
BEGIN DESCRIPTION:
MACHO CREEK 66.0
END DESCRIPTION:
XS GIS Cut Line= 3
      2085490.67     13455654.37      2084979.51     13454868.23
      2084276.97     13454669.55
#Sta/Elev= 30
  4042.2  396.72  4169.3  395.96  4190.4  396.37  4232.6  395.71  4241.7   396.3
    4278  395.96  4377.5  397.17  4422.9  396.45  4486.2  396.85    4754  395.79
  4833.5  395.55  4905.9  396.26  4921.1  395.74  4957.3  397.21  4963.3   395.4
  4971.8  395.28  4978.4  391.44  4989.8  390.51  4990.7  389.71  4999.2  389.71
  5000.1  390.51  5010.4  392.78  5015.8  395.67  5026.2   396.8  5088.7   398.4
  5107.3  398.24  5117.4  398.26    5308  399.71  5634.5  404.69    5710  404.49
#Mann= 5 ,-1 , 0
  4042.2      .1       0    4754     .12       0  4989.8     .07       0
  5000.1     .12       0  5107.3      .1       0
Bank Sta=4377.5,5117.4
XS Rating Curve= 0 ,0
Exp/Cntr=0.3,0.1

Type RM Length L Ch R = 1 ,38493   ,134,134,134
BEGIN DESCRIPTION:
MACHO CREEK 65.0
END DESCRIPTION:
XS GIS Cut Line= 3
      2085924.99     13456274.97        2085325.       13454475.
      2084324.97     13454174.99
#Sta/Elev= 30
  3055.9  405.36  3287.8  403.45  3414.3  400.68  3435.3  398.93 4031.21394.4624
  4426.2  394.19  4679.2  395.55  4710.8   394.4  4731.9  390.14  4747.8  389.24
  4748.7  388.44  4758.1  389.24  4805.7  390.46  4816.2  394.37  4826.7   394.8
  4879.5   392.9  4932.2  389.34    5089  389.48  5107.2  392.18  5112.5  390.73
  5140.3  395.41  5145.5  393.58 5148.65 394.463  5178.6  396.57  5425.7  396.38
  5443.9  397.47  5464.8  396.68  5634.5  398.09  5861.5   403.1  5997.3  407.75
#Mann= 3 ,-1 , 0
  3055.9      .1       0  4747.8     .07       0  4758.1      .1       0
Bank Sta=4031.21,5148.65
XS Rating Curve= 0 ,0
Exp/Cntr=0.3,0.1

Type RM Length L Ch R = 1 ,38359   ,198,198,198
BEGIN DESCRIPTION:
MACHO CREEK 64.0
END DESCRIPTION:
XS GIS Cut Line= 5
      2085944.79     13456302.98      2085528.13     13454688.42
      2085493.41     13454480.09      2085224.31     13454228.35
      2083930.91     13453933.21
#Sta/Elev= 30
  2961.2  405.44  3134.7  405.34  3372.2  401.51  3434.2  398.46  3795.7  395.84
  4585.7  393.05  4586.6  392.25    4596  393.05    4683  399.55  4738.8  401.21
  4743.8  399.52  4814.6  401.94  4842.3  400.47  4898.9  403.13  5057.4  401.59
  5074.6  401.06  5146.6   398.8  5238.4  400.17    5300  395.58  5587.2  396.85
  5609.1  393.95    5647  397.23  5652.1  395.51  5695.1  397.84  5700.3  400.01
  5720.5  397.21  5743.2  397.36  6011.4  403.48  6223.1  411.98    6535  418.47
#Mann= 5 ,-1 , 0
  2961.2      .1       0  4585.7     .07       0    4596      .1       0
  5057.4     .05       0  5074.6      .1       0
Bank Sta=3795.7,5647
XS Rating Curve= 0 ,0
Exp/Cntr=0.3,0.1

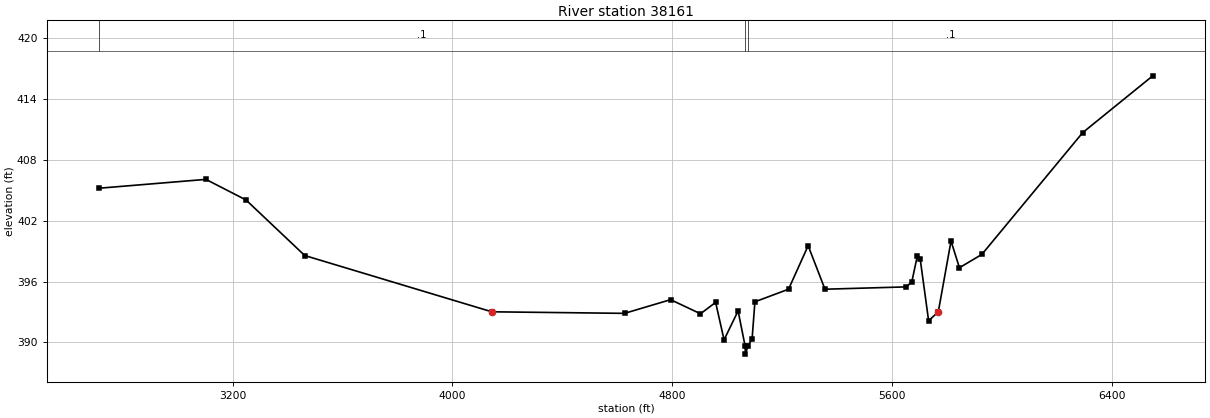
Type RM Length L Ch R = 1 ,38161   ,320,320,320
BEGIN DESCRIPTION:
MACHO CREEK 63.0
END DESCRIPTION:
XS GIS Cut Line= 3
      2086024.99     13456474.97        2085525.       13454225.
      2084024.96     13453924.99
#Sta/Elev= 30
  2714.9   405.2  3102.9  406.07  3248.8  404.04  3462.7  398.56  4143.7393.0135
  4626.6  392.86  4794.4  394.21  4903.2  392.82  4958.3  393.94    4989  390.25
  5040.1   393.1  5065.6  389.64  5066.5  388.84  5075.9  389.64  5091.1  390.35
  5101.3     394  5223.7  395.24  5295.1  399.53  5356.3  395.24    5652  395.47
  5672.4  395.96  5692.8  398.55    5703  398.22  5733.6  392.13 5768.89393.0128
  5815.2  399.99  5845.8  397.36  5927.4  398.67  6294.5  410.68  6549.5  416.28
#Mann= 3 ,-1 , 0
  2714.9      .1       0  5065.6     .07       0  5075.9      .1       0
Bank Sta=4143.7,5768.89
XS Rating Curve= 0 ,0
Exp/Cntr=0.3,0.1