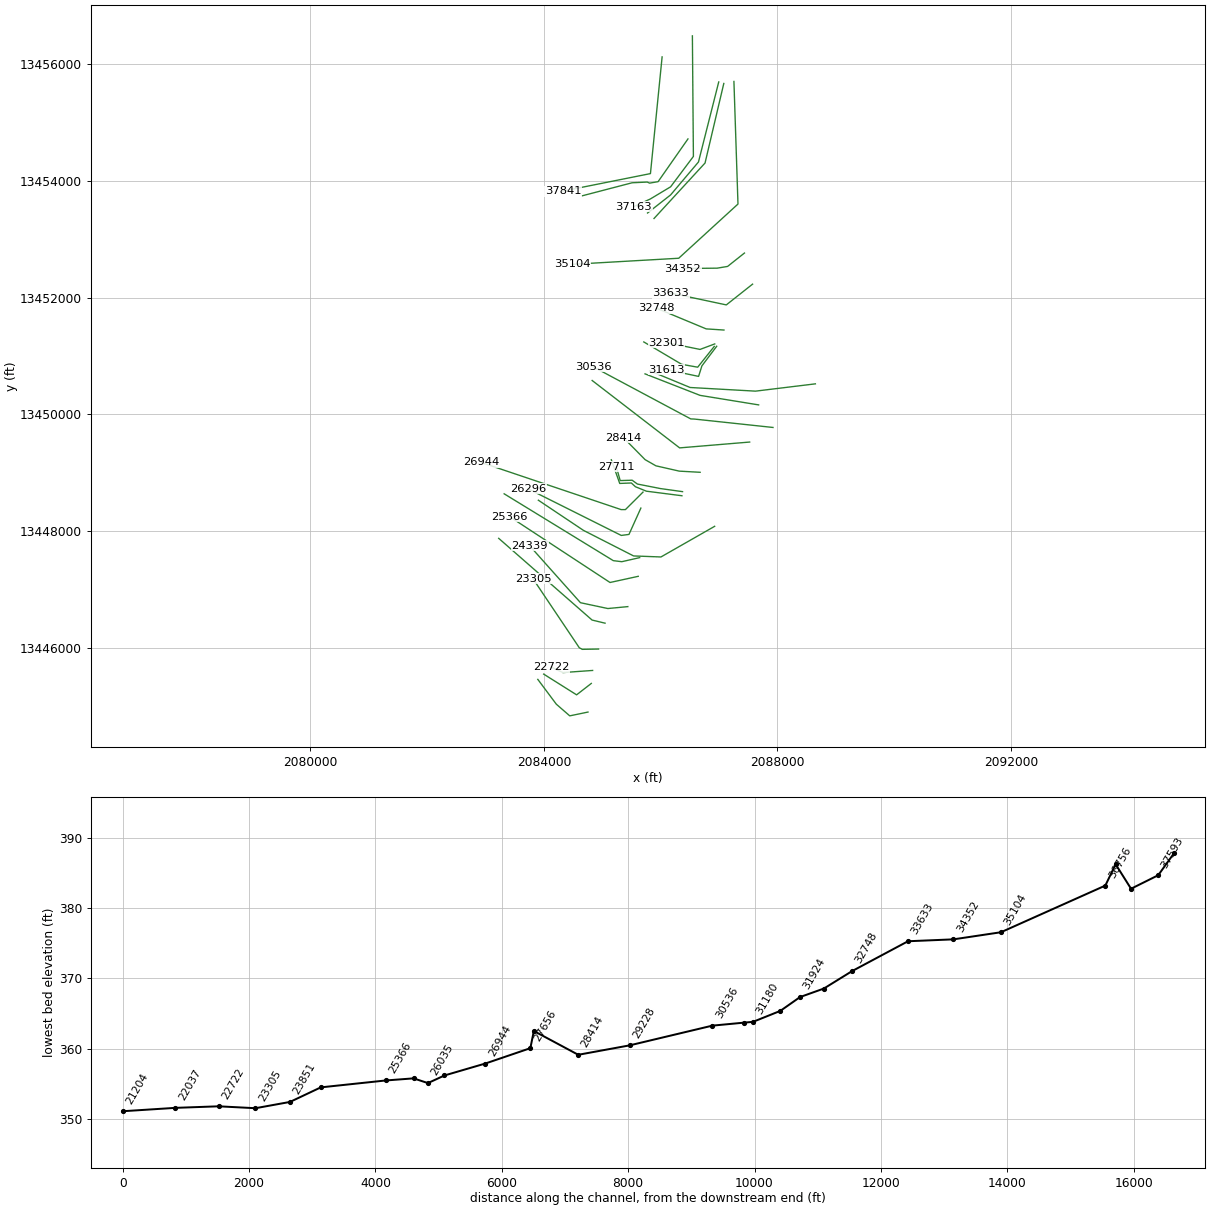
HEC-RAS study MACHO CREEK.prj: MACHO CREEK Base Level Engineering

--- MACHO CREEK.g01 (geometry) --- (continued)

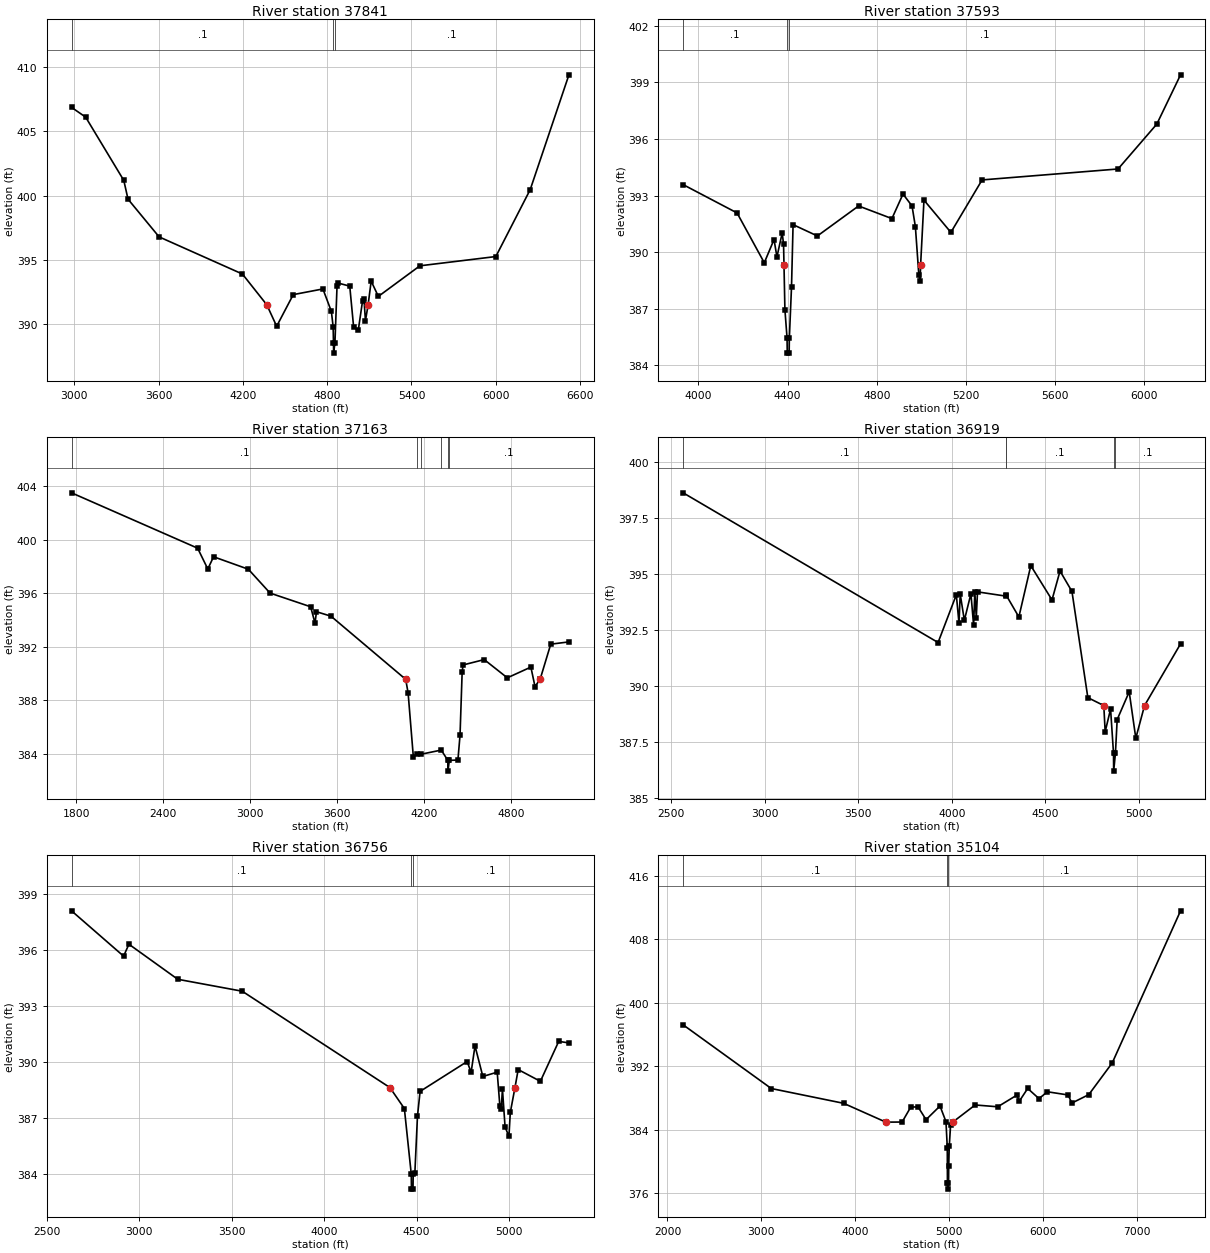
Type RM Length L Ch R = 1 ,37841   ,248,248,248
BEGIN DESCRIPTION:
MACHO CREEK 62.0
END DESCRIPTION:
XS GIS Cut Line= 3
        2086025.     13456125.03        2085825.       13454125.
      2084325.01       13453825.
#Sta/Elev= 30
    2981  406.86  3081.5   406.1  3352.9  401.18    3383  399.72  3604.1  396.79
  4197.1   393.9  4370.4391.5104  4440.8  389.84  4558.9   392.3  4769.9  392.74
  4830.2  390.99  4842.8  389.79  4845.2  388.55  4846.1  387.75  4855.5  388.55
  4870.4  392.96  4880.5  393.19  4960.9  392.96  4988.5  389.78  5021.6  389.53
  5052.2  391.82  5062.4  391.92  5072.6  390.27 5091.69391.5101  5113.4  393.35
  5164.4  392.16  5460.1  394.54  6000.6  395.26  6245.4  400.47  6520.7  409.39
#Mann= 3 ,-1 , 0
    2981      .1       0  4845.2     .07       0  4855.5      .1       0
Bank Sta=4370.4,5091.69
XS Rating Curve= 0 ,0
Exp/Cntr=0.3,0.1

Type RM Length L Ch R = 1 ,37593   ,430,430,430
BEGIN DESCRIPTION:
MACHO CREEK 61.0
END DESCRIPTION:
XS GIS Cut Line= 6
      2086467.94     13454719.09      2085955.76     13453986.42
       2085810.2     13453961.72      2085770.27     13453979.86
      2085510.39     13453967.58      2084653.81     13453743.97
#Sta/Elev= 30
  3931.8  393.58  4173.6  392.08  4295.7  389.44  4339.4  390.67  4352.4  389.75
    4376  391.02  4382.1  390.43 4384.02389.3347  4388.2  386.95  4397.8  385.45
  4398.7  384.65  4407.2  384.65  4408.1  385.45  4417.8  388.16  4424.8  391.46
  4533.8  390.86  4718.7  392.45  4868.1  391.78  4917.8  393.08  4958.4  392.45
  4973.4  391.35    4989  388.77  4994.5  388.49 4996.88389.3374  5011.9  392.76
  5132.6  391.05  5272.6  393.83  5882.4  394.41  6056.3  396.79  6162.7   399.4
#Mann= 3 ,-1 , 0
  3931.8      .1       0  4397.8     .07       0  4408.1      .1       0
Bank Sta=4384.02,4996.88
XS Rating Curve= 0 ,0
Exp/Cntr=0.3,0.1

Type RM Length L Ch R = 1 ,37163   ,244,244,244
BEGIN DESCRIPTION:
MACHO CREEK 60.0
END DESCRIPTION:
XS GIS Cut Line= 5
      2086543.76     13456485.27      2086561.12     13454419.32
      2086170.49     13453898.49      2085823.27     13453690.15
      2085540.89     13453560.78
#Sta/Elev= 30
  1767.8  403.49  2638.1  399.36  2708.1  397.81  2748.1  398.72  2988.1  397.79
  3138.1  396.01  3418.1  394.99  3448.1  393.76  3458.1  394.62  3558.1  394.29
 4073.92389.5774  4090.6  388.56  4126.7  383.79  4153.8  384.03  4179.8  383.99
  4319.4   384.3  4364.6  383.53  4365.5  382.73  4374.9  383.53  4434.3  383.56
  4448.9  385.41  4463.5  390.11  4469.7  390.65  4615.9  391.05  4775.2  389.69
  4937.8  390.49  4966.3  389.04 5001.54389.5777  5074.9   392.2  5200.4  392.37
#Mann= 6 ,-1 , 0
  1767.8      .1       0  4153.8     .05       0  4179.8      .1       0
  4319.4     .05       0  4364.6     .07       0  4374.9      .1       0
Bank Sta=4073.92,5001.54
XS Rating Curve= 0 ,0
Exp/Cntr=0.3,0.1

Type RM Length L Ch R = 1 ,36919   ,163,163,163
BEGIN DESCRIPTION:
MACHO CREEK 59.0
END DESCRIPTION:
XS GIS Cut Line= 4
      2086995.15     13455695.37      2086647.92     13454323.84
      2086170.49      13453759.6      2085775.48     13453449.85
#Sta/Elev= 30
  2565.5  398.63  3926.7  391.95  4024.1  394.08  4038.4  392.81  4044.9  394.11
    4067  392.94  4102.1  394.13  4116.4  392.72  4122.9   394.2  4130.7  393.06
  4137.2  394.21  4288.9  394.02  4290.6  394.06  4358.1  393.09  4421.8  395.38
    4535  393.85  4577.8  395.14  4641.5  394.23  4726.4  389.49 4811.59389.1362
  4818.9  387.97  4847.8  388.98  4863.4  387.01  4864.3  386.21  4873.7  387.01
    4883  388.51  4947.2  389.75  4982.5  387.68 5029.17389.1369  5221.4  391.89
#Mann= 5 ,-1 , 0
  2565.5      .1       0  4288.9     .05       0  4290.6      .1       0
  4863.4     .07       0  4873.7      .1       0
Bank Sta=4811.59,5029.17
XS Rating Curve= 0 ,0
Exp/Cntr=0.3,0.1

Type RM Length L Ch R = 1 ,36756   ,1652,1652,1652
BEGIN DESCRIPTION:
MACHO CREEK 58.0
END DESCRIPTION:
XS GIS Cut Line= 3
      2087081.94     13455669.29      2086760.77     13454306.47
      2085886.13     13453355.47
#Sta/Elev= 30
  2632.6   398.1  2914.4  395.67  2943.2  396.31  3207.5  394.43  3556.5  393.79
 4355.92388.6243  4434.1   387.5  4471.5  383.98  4472.4  383.18  4480.9  383.18
  4481.9  383.98  4490.9  384.04    4505  387.09  4519.2  388.42  4773.9  390.02
  4795.4  389.44  4816.4  390.86  4858.9  389.22  4936.6  389.45  4950.8  387.66
  4958.2  387.47    4965  388.54  4979.2  386.51  5000.1  386.01  5007.5  387.29
 5032.79388.6245  5050.1  389.59  5170.3  388.96  5269.5   391.1  5324.8  391.02
#Mann= 3 ,-1 , 0
  2632.6      .1       0  4471.5     .07       0  4481.9      .1       0
Bank Sta=4355.92,5032.79
XS Rating Curve= 0 ,0
Exp/Cntr=0.3,0.1

Type RM Length L Ch R = 1 ,35104   ,752,752,752
BEGIN DESCRIPTION:
MACHO CREEK 57.0
END DESCRIPTION:
XS GIS Cut Line= 4
      2087255.56     13455704.02      2087325.01     13453603.35
      2086309.38     13452674.53      2084488.27     13452570.47
#Sta/Elev= 30
    2167  397.24  3106.5  389.22    3877  387.36 4328.02384.9864    4501     385
  4593.5  386.89  4671.2   386.9  4756.3   385.3    4905  387.02  4968.5  385.05
  4982.6  381.79  4984.2  377.35  4985.1  376.55  4994.6  377.35  4996.8  379.42
  5003.6  381.93  5017.8  384.57 5040.33384.9865  5279.9  387.15  5520.4  386.92
  5724.6  388.39  5749.7  387.61  5839.8  389.23    5960  387.95  6050.2  388.81
  6270.5  388.41  6310.6  387.39  6490.9  388.45  6741.3  392.45  7469.2   411.6
#Mann= 3 ,-1 , 0
    2167      .1       0  4984.2     .07       0  4994.6      .1       0
Bank Sta=4328.02,5040.33
XS Rating Curve= 0 ,0
Exp/Cntr=0.3,0.1

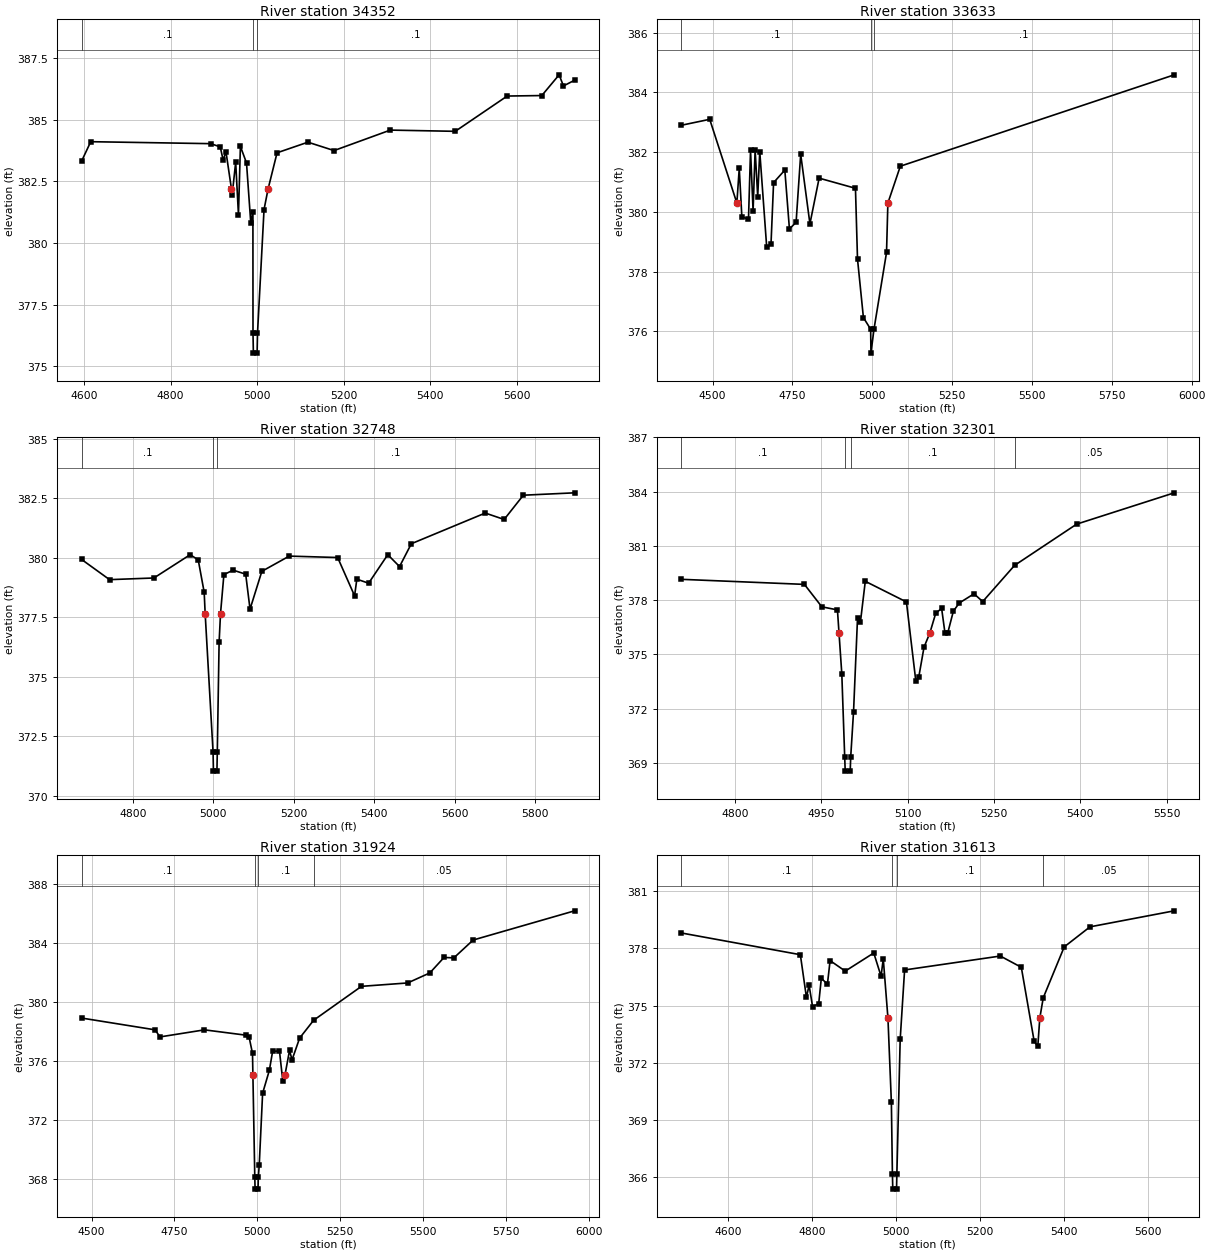
Type RM Length L Ch R = 1 ,34352   ,719,719,719
BEGIN DESCRIPTION:
MACHO CREEK 56.0
END DESCRIPTION:
XS GIS Cut Line= 4
      2087435.95     13452763.71      2087147.08      13452534.4
      2086968.38     13452504.62      2086379.29     13452498.67
#Sta/Elev= 30
  4594.4  383.32  4615.6  384.11  4892.8  384.03  4914.8   383.9  4921.6  383.36
    4928  383.71 4940.75 382.192  4942.4  381.96  4950.5  383.28  4956.9  381.15
  4961.4  383.92  4975.5  383.25  4985.3  380.83  4990.3  381.28  4990.5  376.34
  4991.4  375.54    5000  375.54  5000.9  376.34    5016  381.36 5025.33382.1924
  5046.1  383.66  5117.4  384.09  5177.8  383.75  5307.8  384.58  5457.8  384.53
  5577.8  385.96  5657.8  385.98  5697.8  386.82  5707.8  386.37  5733.5   386.6
#Mann= 3 ,-1 , 0
  4594.4      .1       0  4990.5     .07       0  5000.9      .1       0
Bank Sta=4940.75,5025.33
XS Rating Curve= 0 ,0
Exp/Cntr=0.3,0.1

Type RM Length L Ch R = 1 ,33633   ,885,885,885
BEGIN DESCRIPTION:
double MACHO CREEK 55.0
END DESCRIPTION:
XS GIS Cut Line= 3
      2087574.97     13452230.81        2087125.       13451875.
      2086176.04     13452077.13
#Sta/Elev= 30
  4401.6   382.9  4490.8   383.1 4575.81380.2964  4583.3  381.46  4591.4  379.84
  4612.2  379.75  4618.6  382.06  4626.6  380.03    4633  382.08  4641.1  380.51
  4647.5  382.02  4669.3  378.81  4682.7  378.92  4690.8  380.98    4726   381.4
  4740.4  379.43  4761.3  379.65  4775.7  381.93  4804.6   379.6  4833.4  381.13
  4947.2  380.79  4953.6  378.42  4972.1  376.46  4994.8  376.07  4995.7  375.27
  5005.2  376.07  5044.5  378.64 5048.72 380.295  5087.7  381.53  5945.5  384.59
#Mann= 3 ,-1 , 0
  4401.6      .1       0  4994.8     .07       0  5005.2      .1       0
Bank Sta=4575.81,5048.72
XS Rating Curve= 0 ,0
Exp/Cntr=0.3,0.1

Type RM Length L Ch R = 1 ,32748   ,447,447,447
BEGIN DESCRIPTION:
MACHO CREEK 54.0
END DESCRIPTION:
XS GIS Cut Line= 3
       2087084.5     13451444.38      2086780.24     13451464.03
      2085929.96     13451817.97
#Sta/Elev= 30
  4672.2  379.93  4741.8  379.08  4852.1  379.15  4942.3  380.13  4962.3  379.91
  4977.1  378.55 4979.55377.6474  4999.2  371.83  5000.1  371.03  5008.8  371.03
  5009.7  371.83  5014.2  376.44  5017.7377.6491  5026.1  379.29  5048.9  379.48
  5080.3  379.31  5091.1  377.84  5120.5  379.43  5188.6  380.07    5309  380.01
  5351.1   378.4  5356.7   379.1    5386  378.93  5433.6  380.13  5462.9  379.63
  5492.2  380.59    5676  381.88    5723  381.61  5770.7  382.63  5898.1  382.73
#Mann= 3 ,-1 , 0
  4672.2      .1       0  4999.2     .07       0  5009.7      .1       0
Bank Sta=4979.55,5017.7
XS Rating Curve= 0 ,0
Exp/Cntr=0.3,0.1

Type RM Length L Ch R = 1 ,32301   ,377,377,377
BEGIN DESCRIPTION:
MACHO CREEK 53.0
END DESCRIPTION:
XS GIS Cut Line= 3
      2086926.85     13451206.43        2086675.     13451112.18
      2086098.77      13451229.2
#Sta/Elev= 30
  4706.4  379.15  4920.5  378.87  4950.8  377.63  4977.9  377.46 4980.64376.1836
  4985.5  373.92  4990.5  369.35  4991.4  368.55  5000.1  368.55    5001  369.35
  5005.9  371.84  5012.8     377  5017.9   376.8  5026.3  379.04  5097.8   377.9
  5114.1  373.54  5119.2  373.74  5128.4   375.4  5138.5376.1823  5148.8  377.28
    5159  377.54  5164.7  376.21  5169.8  376.21  5179.4  377.39  5189.6  377.84
  5215.3  378.35  5230.4  377.92  5285.8  379.92  5393.7   382.2  5563.3  383.93
#Mann= 4 ,-1 , 0
  4706.4      .1       0  4990.5     .07       0    5001      .1       0
  5285.8     .05       0
Bank Sta=4980.64,5138.5
XS Rating Curve= 0 ,0
Exp/Cntr=0.3,0.1

Type RM Length L Ch R = 1 ,31924   ,311,311,311
BEGIN DESCRIPTION:
MACHO CREEK 52.0
END DESCRIPTION:
XS GIS Cut Line= 5
      2086918.49     13451163.56      2086634.62     13450807.61
      2086359.75     13450857.17      2085895.61     13451132.05
      2085711.03      13451240.1
#Sta/Elev= 30
  4469.7  378.94  4691.8  378.14  4706.2  377.66  4840.7  378.14  4965.2  377.78
  4975.4  377.64  4985.6  376.54 4986.81 375.067  4992.5  368.14  4993.4  367.34
  5002.3  367.34  5003.1  368.14  5005.9  368.96  5016.1  373.84  5036.4  375.39
  5046.3  376.68  5066.9  376.71    5077  374.69 5083.44375.0625  5097.3  376.74
    5105  376.11  5127.8  377.58  5170.1  378.79  5314.4  381.09  5453.9  381.32
  5520.8     382  5563.7  383.05  5593.3  383.02  5651.5  384.23  5957.6  386.21
#Mann= 4 ,-1 , 0
  4469.7      .1       0  4992.5     .07       0  5003.1      .1       0
  5170.1     .05       0
Bank Sta=4986.81,5083.44
XS Rating Curve= 0 ,0
Exp/Cntr=0.3,0.1

Type RM Length L Ch R = 1 ,31613   ,433,433,433
BEGIN DESCRIPTION:
MACHO CREEK 51.0
END DESCRIPTION:
XS GIS Cut Line= 4
      2086960.51     13451166.74      2086706.94     13450830.61
        2086650.       13450650.      2086098.77     13450766.33
#Sta/Elev= 30
  4488.7  378.81  4772.3  377.67  4786.8  375.43  4793.1  376.07  4801.4  374.95
    4816   375.1  4822.2  376.43  4836.8  376.13  4843.1  377.36  4879.2  376.81
  4947.1  377.76  4964.5  376.54  4969.7  377.46 4980.87374.3379    4989  369.94
  4991.5  366.18  4992.4  365.38  5001.3  365.38  5002.1  366.18    5010  373.23
  5020.5  376.87  5248.4   377.6  5298.4  377.01  5329.1  373.12  5337.7  372.87
 5342.35 374.338  5350.6  375.41  5400.6  378.08  5461.9  379.13  5662.5  379.97
#Mann= 4 ,-1 , 0
  4488.7      .1       0  4991.5     .07       0  5002.1      .1       0
  5350.6     .05       0
Bank Sta=4980.87,5342.35
XS Rating Curve= 0 ,0
Exp/Cntr=0.3,0.1

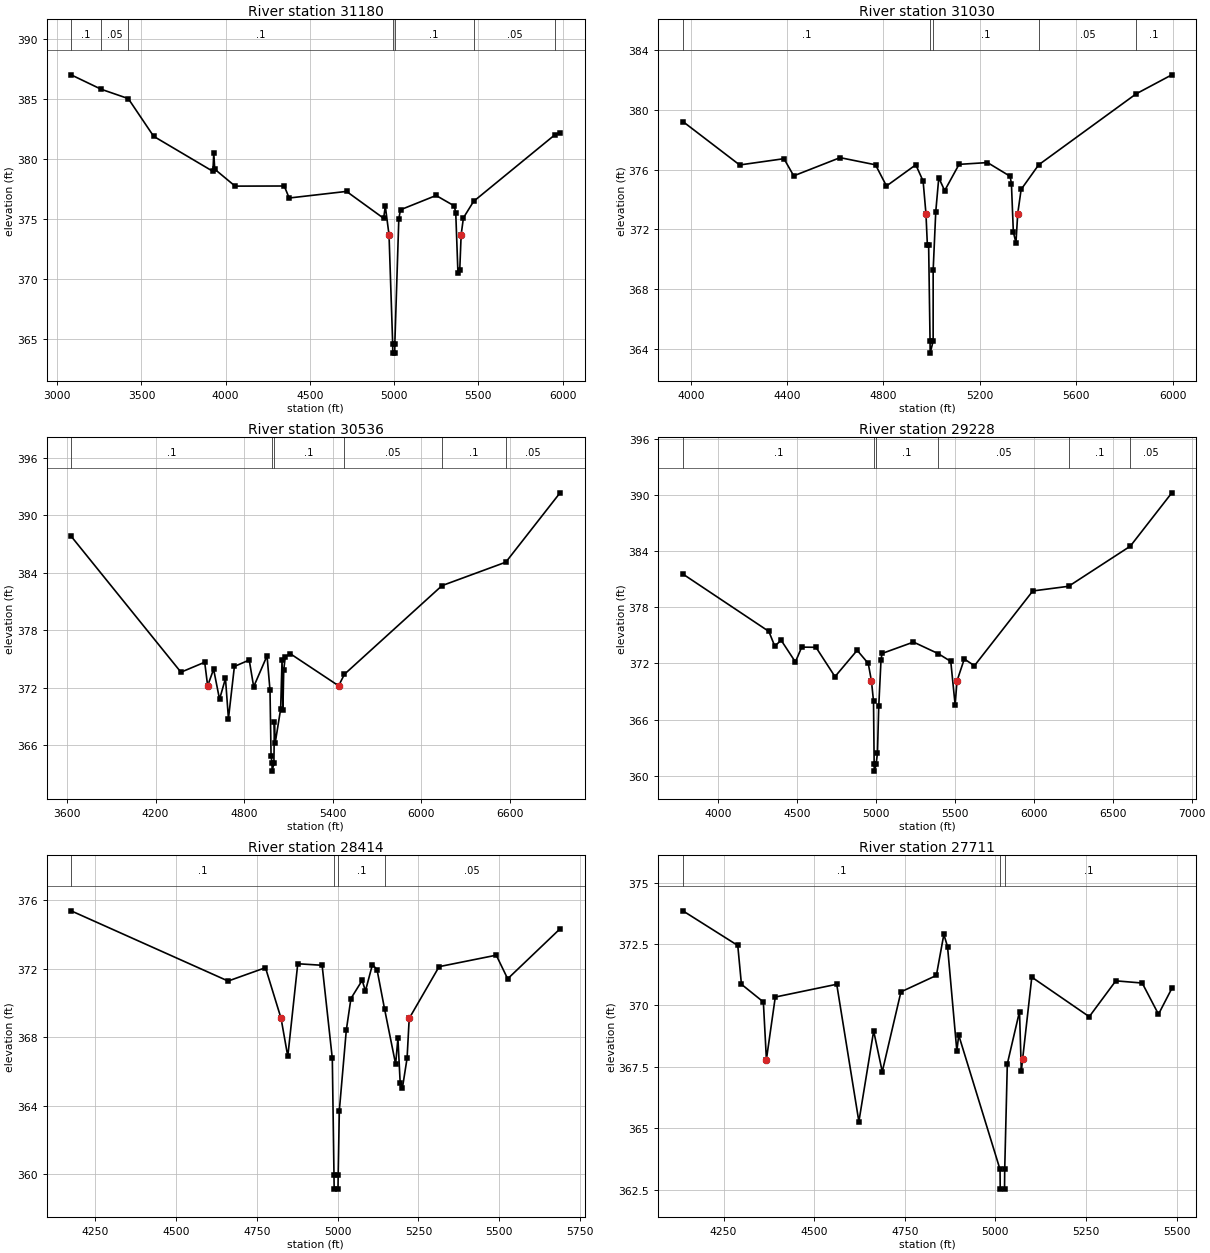
Type RM Length L Ch R = 1 ,31180   ,150,150,150
BEGIN DESCRIPTION:
MACHO CREEK 50.0
END DESCRIPTION:
XS GIS Cut Line= 4
      2088651.27     13450522.32      2087625.22     13450397.32
      2086505.42     13450459.82       2085814.9     13450745.33
#Sta/Elev= 30
  3082.6     387  3260.8   385.8  3421.9  385.02  3572.5  381.88  3924.4  378.96
  3929.4   380.5  3935.1  379.14    4056  377.73  4347.8  377.74  4376.9  376.74
  4717.4  377.29  4937.7  375.05  4947.7  376.05 4969.73373.6737  4991.4  364.62
  4991.9  363.82  5003.7  363.82  5004.2  364.62  5027.9  375.02  5037.9  375.76
  5249.1  376.95  5357.3  376.08  5365.9  375.48  5378.9  370.48  5389.7  370.78
  5397.8373.6747  5411.4  375.09  5471.8  376.46  5955.6  382.02    5985  382.18
#Mann= 7 ,-1 , 0
  3082.6      .1       0  3260.8     .05       0  3421.9      .1       0
  4991.4     .07       0  5004.2      .1       0  5471.8     .05       0
  5955.6      .1       0
Bank Sta=4969.73,5397.8
XS Rating Curve= 0 ,0
Exp/Cntr=0.3,0.1

Type RM Length L Ch R = 1 ,31030   ,494,494,494
BEGIN DESCRIPTION:
MACHO CREEK 49.0
END DESCRIPTION:
XS GIS Cut Line= 3
      2087679.04     13450161.57        2086675.       13450325.
      2085732.44     13450693.25
#Sta/Elev= 30
  3967.5  379.22  4203.1  376.31    4387  376.73  4427.5  375.58    4620   376.8
  4766.9  376.32  4812.5   374.9  4934.1  376.32  4964.5  375.23 4976.26373.0504
  4982.2  370.94  4987.4  370.94  4993.3   364.5  4993.8   363.7  5006.1   364.5
  5006.2  369.26    5017  373.18  5029.5  375.45    5054  374.59  5113.7  376.35
  5231.7  376.47  5325.6  375.55    5331  375.05    5339  371.81  5349.8   371.1
 5357.17373.0484  5371.3  374.67  5444.2  376.32  5849.1  381.08  5996.7  382.35
#Mann= 5 ,-1 , 0
  3967.5      .1       0  4993.3     .07       0  5006.1      .1       0
  5444.2     .05       0  5849.1      .1       0
Bank Sta=4976.26,5357.17
XS Rating Curve= 0 ,0
Exp/Cntr=0.3,0.1

Type RM Length L Ch R = 1 ,30536   ,1308,1308,1308
BEGIN DESCRIPTION:
MACHO CREEK 48.0
END DESCRIPTION:
XS GIS Cut Line= 4
      2087925.01       13449775.      2086575.68     13449919.12
      2086516.65      13449921.2       2084843.3     13450814.42
#Sta/Elev= 30
  3628.1  387.81  4372.3  373.61  4533.2  374.65 4553.19372.1912  4593.6  373.92
  4633.8  370.78    4674  372.96  4694.1  368.75  4734.4  374.21  4834.9  374.88
  4865.1  372.09  4955.6  375.32  4975.7  371.73  4982.9  364.89  4989.4  364.08
  4989.9  363.28  5002.2  364.08  5005.4  368.41  5010.4  366.17  5047.9  369.77
  5057.3  374.89    5063  369.64  5068.7  373.83  5079.2  375.23  5114.1  375.53
 5440.56372.1905  5480.3   373.4  6141.2  382.65  6573.5   385.1    6941  392.34
#Mann= 6 ,-1 , 0
  3628.1      .1       0  4989.4     .07       0  5002.2      .1       0
  5480.3     .05       0  6141.2      .1       0  6573.5     .05       0
Bank Sta=4553.19,5440.56
XS Rating Curve= 0 ,0
Exp/Cntr=0.3,0.1

Type RM Length L Ch R = 1 ,29228   ,814,814,814
BEGIN DESCRIPTION:
MACHO CREEK 47.0
END DESCRIPTION:
XS GIS Cut Line= 3
      2087525.01       13449525.        2086325.       13449425.
      2084826.03     13450579.99
#Sta/Elev= 30
  3777.9  381.57  4322.3  375.43  4359.9  373.85  4400.1  374.49  4490.4  372.16
  4530.5  373.75  4620.8  373.73  4741.2  370.59  4881.7  373.41    4952     372
 4972.09370.1242  4985.2  367.97  4989.2  361.28  4989.7  360.48  5002.1  361.28
  5010.1  362.41  5018.3   367.4  5032.6  372.36  5039.1  373.07  5238.4  374.29
  5395.2  373.05  5474.4  372.22  5502.1  367.56 5513.85 370.127  5560.1  372.48
  5624.4  371.76    5994  379.76  6220.8  380.26  6611.4  384.55  6874.4  390.26
#Mann= 6 ,-1 , 0
  3777.9      .1       0  4989.2     .07       0  5002.1      .1       0
  5395.2     .05       0  6220.8      .1       0  6611.4     .05       0
Bank Sta=4972.09,5513.85
XS Rating Curve= 0 ,0
Exp/Cntr=0.3,0.1

Type RM Length L Ch R = 1 ,28414   ,703,703,703
BEGIN DESCRIPTION:
MACHO CREEK 46.0
END DESCRIPTION:
XS GIS Cut Line= 5
      2086676.53     13449006.88      2086320.65     13449026.41
      2085919.18     13449117.55      2085733.62     13449223.43
       2085361.7     13449600.55
#Sta/Elev= 30
  4176.2  375.39  4661.5  371.29    4777  372.07 4825.19369.1097    4846  366.89
  4876.8   372.3  4952.1  372.21  4983.6  366.77  4988.8  359.94  4989.3  359.14
  5001.2  359.14  5001.7  359.94  5005.3  363.73  5026.9  368.43  5041.2  370.27
  5075.9  371.33    5086  370.71  5107.6  372.25  5121.8  371.96    5145  369.67
  5179.3  366.44  5186.4  367.94  5193.4  365.34  5200.5  365.07  5214.7  366.78
  5221.3369.1087  5313.7  372.13  5490.4   372.8  5525.7  371.42  5687.6  374.34
#Mann= 4 ,-1 , 0
  4176.2      .1       0  4988.8     .07       0  5001.7      .1       0
    5145     .05       0
Bank Sta=4825.19,5221.3
XS Rating Curve= 0 ,0
Exp/Cntr=0.3,0.1

Type RM Length L Ch R = 1 ,27711   ,55,55,55
BEGIN DESCRIPTION:
MACHO CREEK 45.0
END DESCRIPTION:
XS GIS Cut Line= 6
      2086374.93     13448675.28      2085999.91     13448727.36
      2085601.47     13448805.49      2085511.57       13448871.
      2085306.71     13448864.92       2085239.5     13449103.61
#Sta/Elev= 30
  4137.8  373.85  4289.2  372.44  4299.3  370.86  4359.8  370.14 4368.22367.7973
  4392.7  370.34  4562.2  370.86  4623.3  365.27  4664.1  368.96  4687.8   367.3
  4739.3  370.55  4837.1  371.22  4857.7  372.89  4867.9  372.39  4893.6  368.14
  4898.7  368.79  5012.7  363.32  5013.2  362.52  5025.1  362.52  5025.6  363.32
  5032.8  367.62  5066.4  369.75  5071.4  367.33  5074.9 367.798  5100.3  371.15
  5258.8  369.54  5332.1     371  5404.9  370.91  5449.8  369.64  5486.6  370.69
#Mann= 3 ,-1 , 0
  4137.8      .1       0  5012.7     .07       0  5025.6      .1       0
Bank Sta=4368.22,5074.9
XS Rating Curve= 0 ,0
Exp/Cntr=0.3,0.1

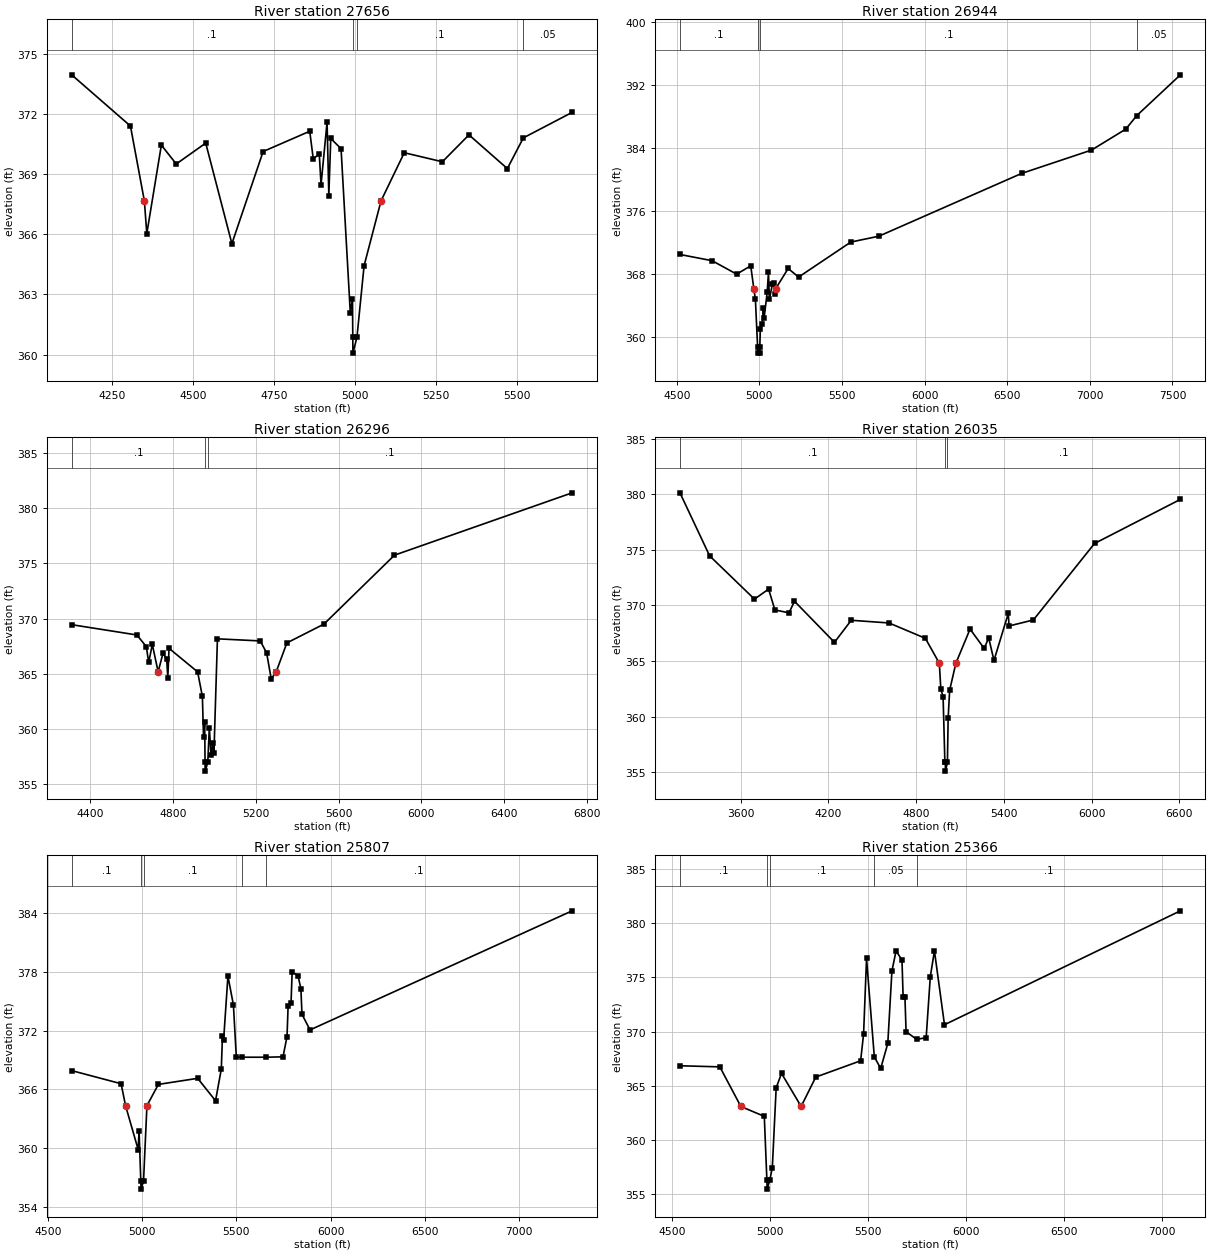
Type RM Length L Ch R = 1 ,27656   ,712,712,712
BEGIN DESCRIPTION:
MACHO CREEK 44.0
END DESCRIPTION:
XS GIS Cut Line= 6
      2086364.53     13448604.96      2085755.11     13448683.09
       2085567.3     13448759.72      2085497.85     13448823.61
      2085298.55     13448815.97      2085154.42     13449221.66
#Sta/Elev= 30
  4126.9  373.94  4307.9  371.39 4350.73367.6639  4358.3  366.03  4403.1  370.44
    4449   369.5  4539.8  370.54  4620.4  365.53  4716.6  370.12  4860.2  371.13
    4871  369.76  4889.6  369.99    4895  368.47  4913.6  371.59    4919  367.93
    4925  370.77  4956.7  370.26  4985.1   362.1  4991.9   362.8  4992.8  360.88
  4993.3  360.08  5005.7  360.88  5027.6  364.43 5079.86367.6645  5151.4  370.06
  5268.8  369.61  5350.7  370.95  5468.9  369.27  5518.2   370.8  5668.5  372.07
#Mann= 4 ,-1 , 0
  4126.9      .1       0  4992.8     .07       0  5005.7      .1       0
  5518.2     .05       0
Bank Sta=4350.73,5079.86
XS Rating Curve= 0 ,0
Exp/Cntr=0.3,0.1

Type RM Length L Ch R = 1 ,26944   ,648,648,648
BEGIN DESCRIPTION:
MACHO CREEK 43.0
END DESCRIPTION:
XS GIS Cut Line= 4
      2085697.86      13448667.5      2085396.34     13448367.47
      2085322.99     13448367.47      2082925.02     13449174.99
#Sta/Elev= 30
  4519.1  370.43  4713.8  369.64  4862.3  367.93  4947.6  368.99  4966.1366.0974
  4975.8  364.72  4989.1   358.7  4989.7   357.9  5001.8   357.9  5002.4   358.7
  5005.8  361.01  5017.8  361.64  5023.4  363.66  5028.6  362.39  5047.3  365.65
  5054.8  368.19  5060.1  364.75    5079  366.68  5086.3  366.76  5091.6   365.4
 5099.02366.0984    5174  368.65  5237.3  367.56  5553.5  372.01  5722.7  372.75
  6587.5  380.73    7010  383.69  7217.4  386.35  7284.1  388.07  7548.1  393.25
#Mann= 4 ,-1 , 0
  4519.1      .1       0  4989.1     .07       0  5002.4      .1       0
  7284.1     .05       0
Bank Sta=4966.1,5099.02
XS Rating Curve= 0 ,0
Exp/Cntr=0.3,0.1

Type RM Length L Ch R = 1 ,26296   ,261,261,261
BEGIN DESCRIPTION:
double MACHO CREEK 42.0
END DESCRIPTION:
XS GIS Cut Line= 4
      2085661.07     13448393.47       2085457.1     13447942.12
        2085325.       13447925.      2083724.96     13448725.02
#Sta/Elev= 30
  4310.9  369.45  4625.6  368.52  4671.4  367.47  4682.8  366.03  4700.4  367.66
 4728.53365.1852  4752.1  366.88  4769.8   366.3  4775.2  364.65  4781.1  367.31
  4919.2  365.18  4942.2  362.96  4947.8  359.25  4953.4  360.66  4955.1     357
  4955.7   356.2  4968.4     357  4975.7  360.14  4984.1  357.64  4992.5   358.7
  4998.1  357.87  5014.9  368.17  5221.7  367.98  5252.5   366.9  5274.8  364.54
 5298.81365.1863  5350.3   367.8  5529.2   369.5  5870.2  375.74  6728.3  381.38
#Mann= 3 ,-1 , 0
  4310.9      .1       0  4955.1     .07       0  4968.4      .1       0
Bank Sta=4728.53,5298.81
XS Rating Curve= 0 ,0
Exp/Cntr=0.3,0.1

Type RM Length L Ch R = 1 ,26035   ,228,228,228
BEGIN DESCRIPTION:
MACHO CREEK 41.0
END DESCRIPTION:
XS GIS Cut Line= 5
      2086925.32     13448081.13      2086005.21     13447555.98
      2085536.46     13447573.34      2084677.08      13448011.7
      2083904.55     13448528.18
#Sta/Elev= 30
  3184.5  380.12  3387.4  374.46  3694.2  370.57  3790.7  371.47  3833.9   369.6
  3930.4  369.34  3967.8  370.38  4241.2  366.69  4355.9  368.67  4614.4  368.43
  4862.9  367.05 4958.44364.8107  4968.5  362.49  4984.1  361.82  4996.3  355.93
  4999.4  355.92  5000.4  355.12  5013.7  355.92  5018.6  359.85    5029  362.39
 5071.51364.8104  5168.5  367.88  5264.7  366.15  5296.3  367.08  5332.1  365.06
  5429.7  369.28  5435.3  368.16  5601.5   368.7  6019.8  375.57    6607  379.53
#Mann= 3 ,-1 , 0
  3184.5      .1       0  4999.4     .07       0  5013.7      .1       0
Bank Sta=4958.44,5071.51
XS Rating Curve= 0 ,0
Exp/Cntr=0.3,0.1

Type RM Length L Ch R = 1 ,25807   ,441,441,441
BEGIN DESCRIPTION:
double MACHO CREEK 40.0
END DESCRIPTION:
XS GIS Cut Line= 4
      2085640.41     13447544.66      2085334.42     13447474.87
      2085189.05     13447492.58      2083318.29     13448638.28
#Sta/Elev= 30
  4627.1  367.91  4889.1  366.57 4912.79364.3277  4979.5  359.84  4984.5  361.75
  4993.7  356.59  4994.7  355.79    5008  356.59 5026.18364.3282  5086.9   366.5
  5295.2  367.12    5390  364.83  5420.5  368.06  5426.7  371.42  5432.6  370.99
  5455.7  377.58  5484.8  374.62  5500.2  369.28  5530.8  369.28  5659.5  369.28
  5747.8  369.32  5769.1  371.39  5774.9  374.56  5790.4  374.83  5796.2  377.99
  5827.1  377.63  5842.6   376.3  5848.4  373.67    5891  372.07  7281.1  384.25
#Mann= 5 ,-1 , 0
  4627.1      .1       0  4993.7     .07       0    5008      .1       0
  5530.8     .05       0  5659.5      .1       0
Bank Sta=4912.79,5026.18
XS Rating Curve= 0 ,0
Exp/Cntr=0.3,0.1

Type RM Length L Ch R = 1 ,25366   ,1027,1027,1027
BEGIN DESCRIPTION:
double MACHO CREEK 39.0
END DESCRIPTION:
XS GIS Cut Line= 3
      2085615.68     13447224.24      2085132.44     13447118.51
      2083409.77     13448248.54
#Sta/Elev= 30
  4540.7  366.85  4744.3  366.75 4851.65363.1033  4971.3  362.19  4984.6  356.29
  4985.6  355.49  4998.9  356.29  5012.3  357.47  5031.9  364.82  5059.3  366.15
 5159.37363.1032  5234.1  365.81  5463.1  367.31  5478.2  369.78  5493.3  376.73
    5533  367.67  5565.6   366.6  5601.8  368.91  5622.9  375.58    5644  377.43
  5674.2  376.59  5680.1  373.18  5689.3  373.17  5695.2  369.99  5749.2  369.28
  5797.7  369.44  5818.8  375.05  5839.9  377.43  5891.2  370.63  7095.6  381.12
#Mann= 5 ,-1 , 0
  4540.7      .1       0  4984.6     .07       0  4998.9      .1       0
    5533     .05       0  5749.2      .1       0
Bank Sta=4851.65,5159.37
XS Rating Curve= 0 ,0
Exp/Cntr=0.3,0.1

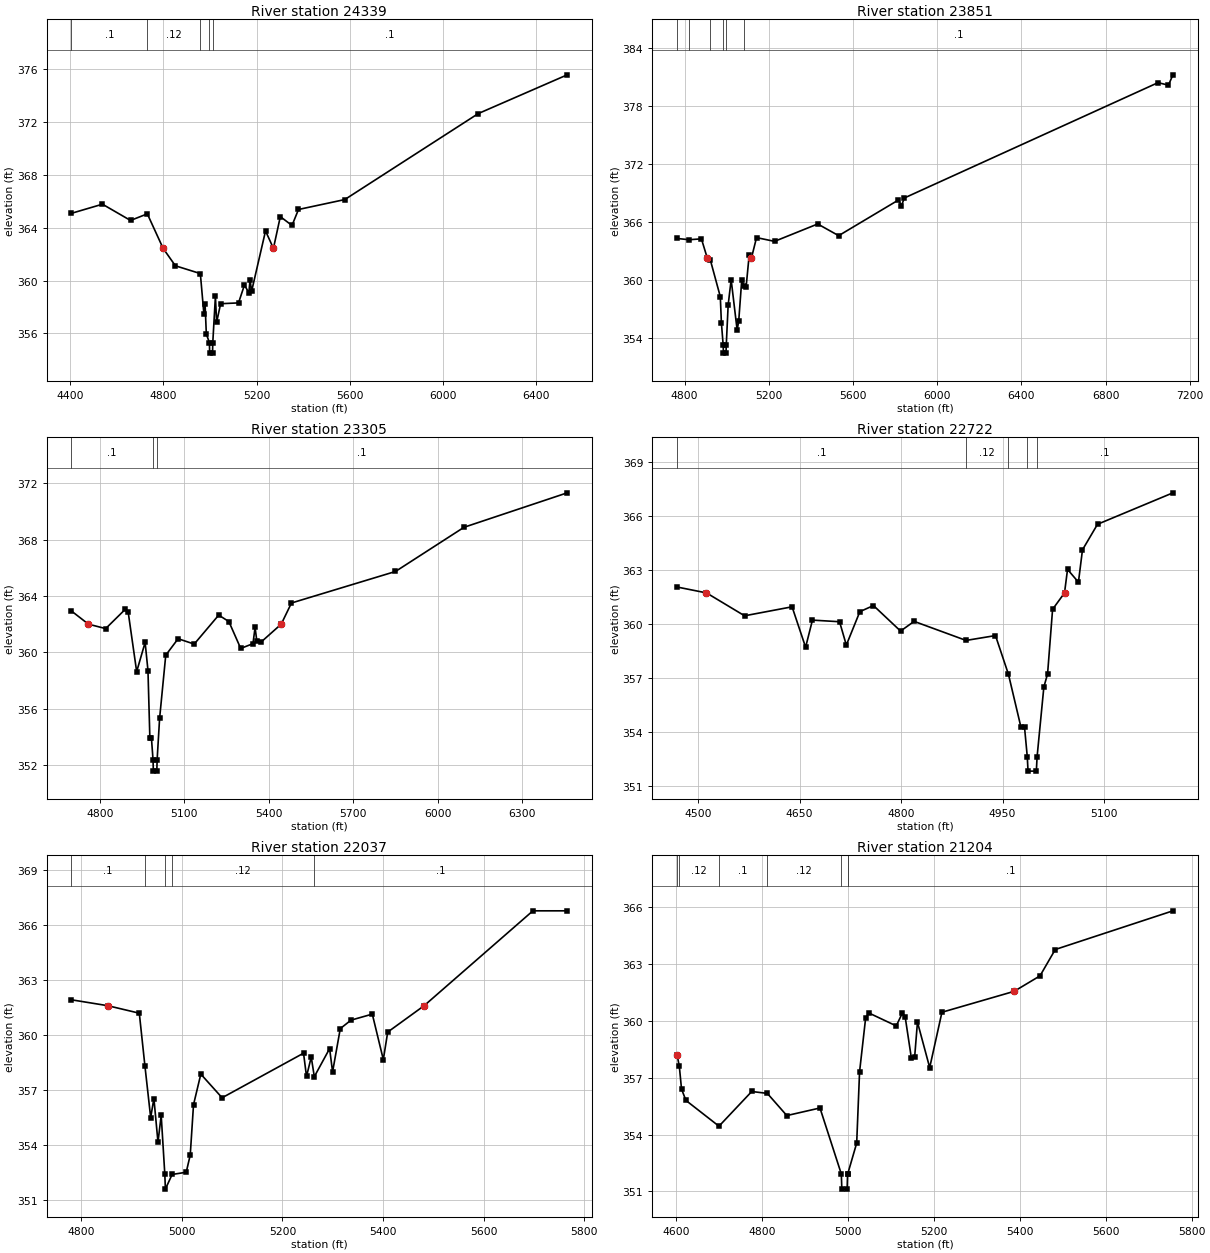
Type RM Length L Ch R = 1 ,24339   ,488,488,488
BEGIN DESCRIPTION:
double MACHO CREEK 38.0
END DESCRIPTION:
XS GIS Cut Line= 4
      2085437.51     13446705.16       2085095.3     13446672.27
      2084626.03     13446772.06      2083756.78     13447746.03
#Sta/Elev= 30
  4405.1  365.09  4538.2  365.78  4658.8  364.55  4730.9  365.05 4798.79362.4354
  4851.4  361.12  4958.6  360.53  4973.7  357.49  4978.8  358.25  4984.3  355.95
  4997.5  355.31  4998.6  354.51  5010.9  354.51    5012  355.31  5023.3  358.81
  5028.4  356.84  5045.7  358.25  5122.5  358.31  5147.9  359.66  5166.9  359.08
  5172.1  360.06  5178.6  359.18  5238.5  363.76 5272.38362.4354    5302  364.84
  5352.2  364.17    5380  365.38  5578.7  366.13  6152.3  372.64  6534.1  375.57
#Mann= 5 ,-1 , 0
  4405.1      .1       0  4730.9     .12       0  4958.6      .1       0
  4997.5     .07       0    5012      .1       0
Bank Sta=4798.79,5272.38
XS Rating Curve= 0 ,0
Exp/Cntr=0.3,0.1

Type RM Length L Ch R = 1 ,23851   ,546,546,546
BEGIN DESCRIPTION:
double MACHO CREEK 37.0
END DESCRIPTION:
XS GIS Cut Line= 3
      2085047.12     13446421.35        2084825.       13446475.
      2083225.03     13447874.97
#Sta/Elev= 30
  4764.7  364.31  4821.1  364.18    4880  364.27 4908.21362.2564  4922.9  362.04
  4969.7  358.28  4974.8   355.6  4983.4  353.24  4984.5  352.44  4996.8  352.44
  4997.9  353.24    5007  357.43  5021.2  360.04  5049.7  354.81  5057.3  355.81
  5071.5  360.02  5082.2  359.43  5092.4  359.32  5106.6  362.55 5117.23362.2568
  5141.7   364.4  5227.2  364.01  5432.2  365.81  5531.8   364.6  5815.6  368.29
  5829.9  367.69  5843.6   368.5  7048.5  380.44  7097.9  380.18  7119.2  381.25
#Mann= 6 ,-1 , 0
  4764.7      .1       0  4821.1     .12       0  4922.9     .07       0
  4983.4     .07       0  4997.9     .07       0  5082.2      .1       0
Bank Sta=4908.21,5117.23
XS Rating Curve= 0 ,0
Exp/Cntr=0.3,0.1

Type RM Length L Ch R = 1 ,23305   ,583,583,583
BEGIN DESCRIPTION:
double MACHO CREEK 36.0
END DESCRIPTION:
XS GIS Cut Line= 4
      2084936.41     13445978.06       2084656.5     13445972.85
      2084605.47     13446001.04      2083813.71     13447181.08
#Sta/Elev= 30
  4699.7  362.93 4759.86 361.996  4821.1  361.68  4891.1  363.06  4901.1  362.84
  4931.1  358.62  4961.1   360.7  4971.2   358.7  4977.9  353.93  4983.4  353.93
  4989.2  352.35  4990.3  351.55  5002.6  351.55  5003.7  352.35  5012.5   355.3
  5034.3  359.79  5078.2  360.96  5135.3  360.58  5222.3  362.64  5258.3  362.18
  5300.3  360.27  5343.8  360.61  5351.3  361.76  5357.4  360.81  5372.4  360.72
 5444.06361.9966  5480.4   363.5  5849.5  365.74  6092.6  368.88    6459  371.33
#Mann= 3 ,-1 , 0
  4699.7      .1       0  4989.2     .07       0  5003.7      .1       0
Bank Sta=4759.86,5444.06
XS Rating Curve= 0 ,0
Exp/Cntr=0.3,0.1

Type RM Length L Ch R = 1 ,22722   ,685,685,685
BEGIN DESCRIPTION:
double MACHO CREEK 35.0
END DESCRIPTION:
XS GIS Cut Line= 3
      2084834.45     13445611.31        2084325.       13445575.
      2084124.18       13445670.
#Sta/Elev= 30
  4468.9  362.06 4512.28361.7337  4568.6  360.46  4638.8  360.96  4658.8  358.71
  4668.9  360.22    4709  360.13    4719  358.83    4739  360.69  4759.1  361.03
  4799.2  359.61  4819.2  360.15    4896  359.09  4939.5  359.36  4958.7   357.2
  4977.1  354.27  4982.4  354.27  4986.5  352.62  4987.6  351.82  4999.9  351.82
    5001  352.62    5011   356.5  5016.5  357.23  5023.9  360.82 5041.53361.7323
    5046  363.04  5062.1  362.33  5068.1  364.13  5090.3  365.55  5201.8   367.3
#Mann= 5 ,-1 , 0
  4468.9      .1       0    4896     .12       0  4958.7      .1       0
  4986.5     .07       0    5001      .1       0
Bank Sta=4512.28,5041.53
XS Rating Curve= 0 ,0
Exp/Cntr=0.3,0.1

Type RM Length L Ch R = 1 ,22037   ,833,833,833
BEGIN DESCRIPTION:
MACHO CREEK 34.0
END DESCRIPTION:
XS GIS Cut Line= 3
      2084811.44      13445388.8      2084559.71      13445193.5
      2083995.72     13445548.46
#Sta/Elev= 30
  4780.9  361.92 4852.94361.5995  4915.7  361.19  4926.8  358.33  4938.3   355.5
  4944.7  356.54  4952.8  354.16  4959.2  355.62  4966.4   352.4  4967.5   351.6
  4980.9   352.4  5008.9  352.52  5016.9  353.46  5023.4   356.2  5037.9  357.87
  5080.2  356.58    5242  359.01  5247.9  357.74  5257.3   358.8  5263.4  357.73
  5293.8  359.26  5299.7  357.99    5315  360.35  5336.2  360.81  5378.6  361.14
  5400.5  358.66  5409.2  360.16 5481.61361.5993  5697.7  366.77  5765.9  366.77
#Mann= 5 ,-1 , 0
  4780.9      .1       0  4926.8     .12       0  4966.4     .07       0
  4980.9     .12       0  5263.4      .1       0
Bank Sta=4852.94,5481.61
XS Rating Curve= 0 ,0
Exp/Cntr=0.3,0.1

Type RM Length L Ch R = 1 ,21204   ,650,650,650
BEGIN DESCRIPTION:
MACHO CREEK 33.0
END DESCRIPTION:
XS GIS Cut Line= 4
      2084755.02     13444898.36      2084442.52     13444833.26
      2084212.49     13445032.91      2083895.03     13445458.19
#Sta/Elev= 30
  4601.9  358.18    4607  357.59  4612.1   356.4  4622.3   355.8  4699.3  354.44
  4775.6  356.27  4811.9  356.17  4857.3     355  4934.5   355.4  4984.2  351.92
  4985.4  351.12  4997.7  351.12  4998.8  351.92  4999.1  351.92    5020  353.55
  5026.7  357.31  5040.9  360.16  5048.5  360.41  5112.1  359.73  5126.4  360.41
    5133  360.19  5147.3  358.04  5154.9  358.07  5161.5  359.93    5190  357.53
  5218.5  360.45 5386.42361.5511  5446.9  362.37  5482.4  363.76  5756.4   365.8
#Mann= 7 ,-1 , 0
  4601.9      .1       0    4607     .12       0  4699.3      .1       0
  4811.9     .12       0  4984.2     .07       0  4998.8     .12       0
  4999.1      .1       0
Bank Sta=4601.9,5386.42
XS Rating Curve= 0 ,0
Exp/Cntr=0.3,0.1