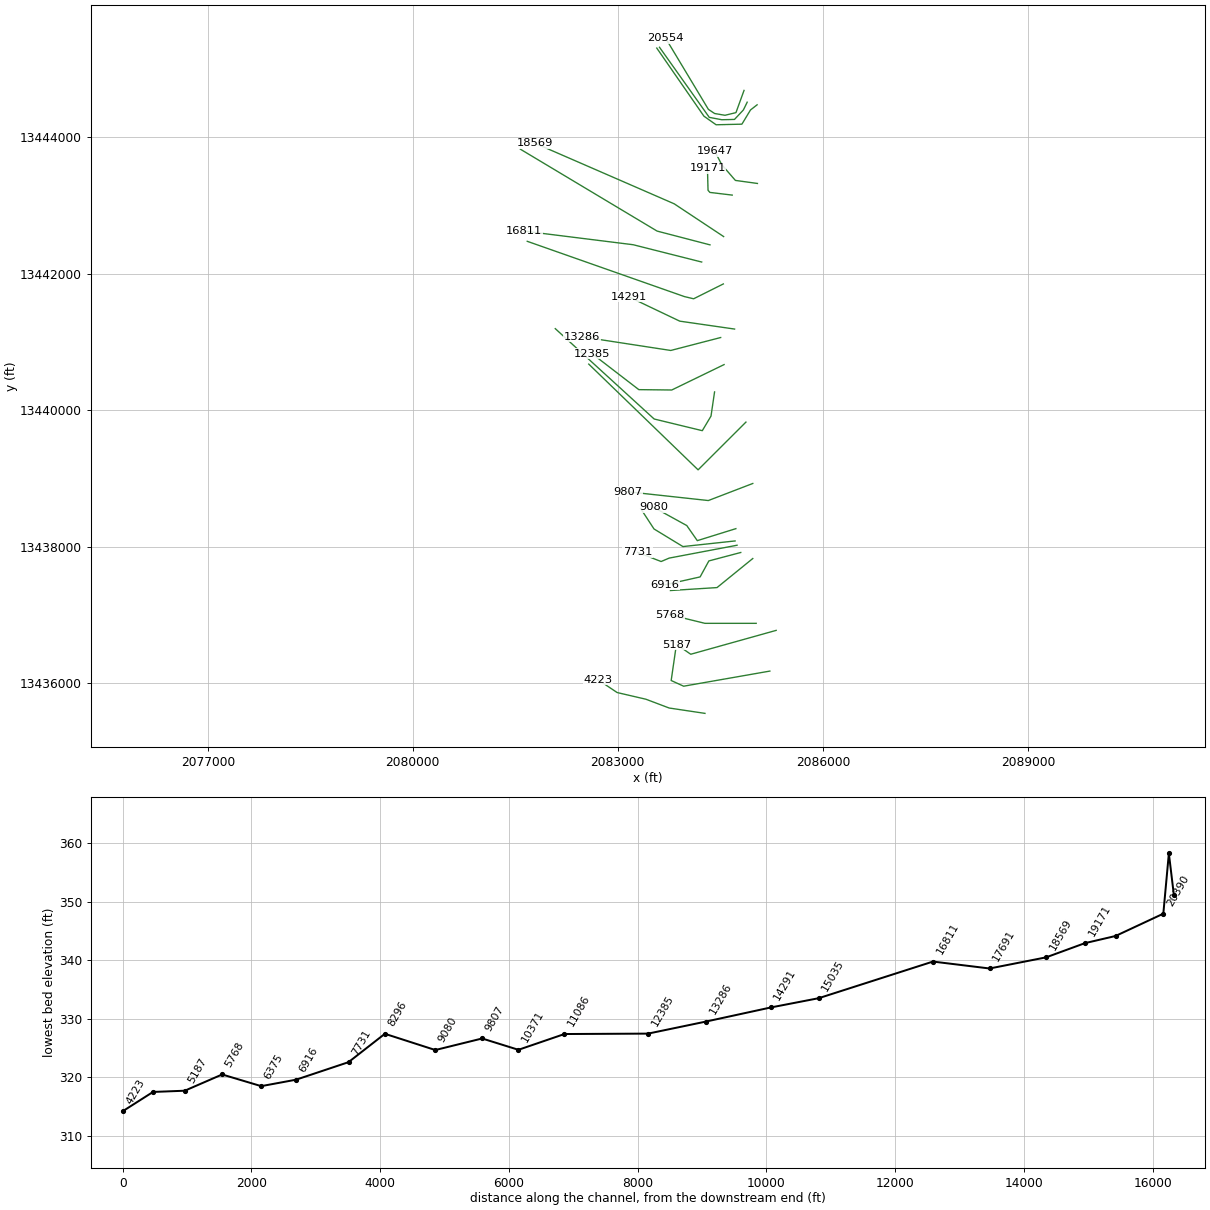
HEC-RAS study MACHO CREEK.prj: MACHO CREEK Base Level Engineering

--- MACHO CREEK.g01 (geometry) --- (continued)

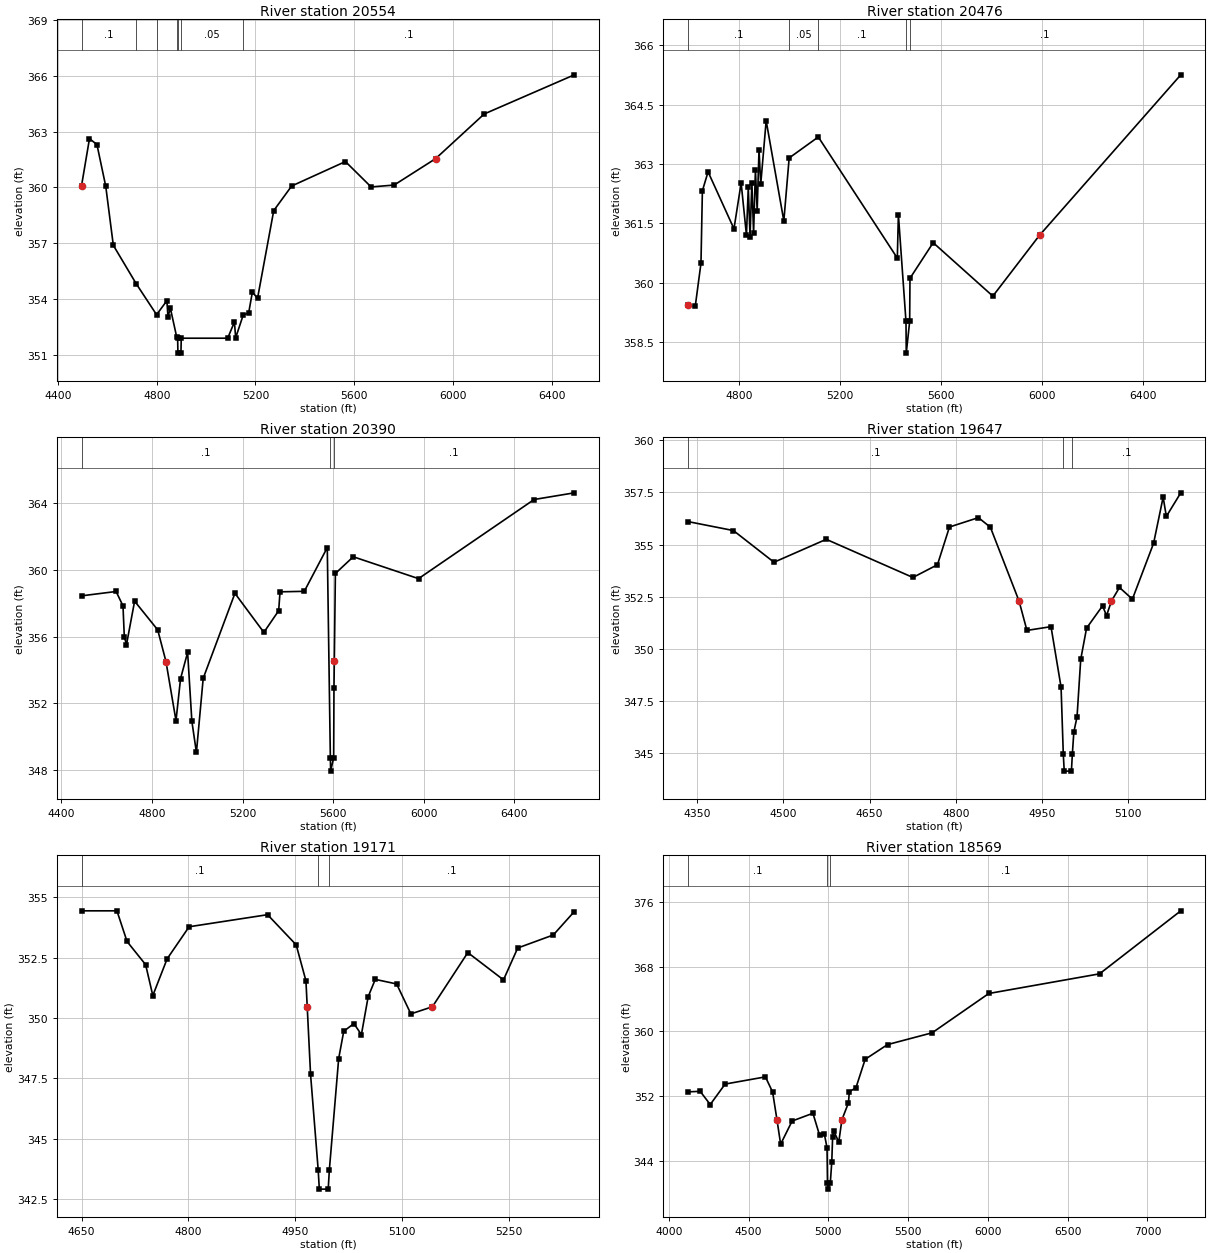
Type RM Length L Ch R = 1 ,20554   ,78,78,78
BEGIN DESCRIPTION:
MACHO CREEK 32.0
END DESCRIPTION:
XS GIS Cut Line= 6
      2084847.18     13444687.33      2084729.17     13444361.53
      2084568.58     13444322.47      2084416.67     13444348.51
      2084325.52     13444409.27      2083700.79     13445450.49
#Sta/Elev= 30
  4495.8   360.1  4527.9  362.62  4558.1   362.3  4593.8  360.06  4624.4   356.9
  4716.6  354.85  4799.5  353.18  4841.2  353.93  4845.6  353.08  4855.5  353.52
  4880.7     352  4884.8  351.92  4885.9  351.12  4898.2  351.12  4899.4  351.92
  5087.4  351.92  5114.7  352.79  5119.7  351.94  5150.4  353.17  5172.3  353.27
  5187.3  354.39  5208.3  354.06  5273.8  358.76  5346.4  360.08  5564.1  361.39
    5668  360.03  5761.3  360.13 5929.38361.5479  6125.8  363.94  6490.7  366.04
#Mann= 7 ,-1 , 0
  4495.8      .1       0  4716.6     .05       0  4799.5      .1       0
  4880.7     .05       0  4884.8    .033       0  4899.4     .05       0
  5150.4      .1       0
Bank Sta=4495.8,5929.38
XS Rating Curve= 0 ,0
Exp/Cntr=0.3,0.1

Type RM Length L Ch R = 1 ,20476   ,86,86,86
BEGIN DESCRIPTION:
MACHO CREEK 31.0
END DESCRIPTION:
XS GIS Cut Line= 6
      2084893.43     13444514.35      2084837.67     13444400.59
      2084707.46      13444261.7      2084520.83     13444257.36
      2084338.54     13444292.09      2083609.97     13445319.92
#Sta/Elev= 30
    4599  359.43  4627.8  359.41  4650.3  360.49  4655.9  362.32  4678.4   362.8
    4781  361.36  4809.4  362.52  4830.4   361.2  4837.7  362.41  4844.6  361.16
  4851.9  362.53  4858.7  361.25    4866  362.85  4872.9  361.82  4880.2  363.36
    4887  362.49  4908.5  364.09  4978.5  361.56  4999.6  363.15    5115  363.68
    5428  360.62  5432.2  361.72  5462.3  359.02  5463.4  358.22  5476.9  359.02
  5478.1  360.11    5570  361.01  5806.3  359.66 5991.21361.1967  6550.7  365.25
#Mann= 5 ,-1 , 0
    4599      .1       0  4999.6     .05       0    5115      .1       0
  5462.3    .033       0  5476.9      .1       0
Bank Sta=4599,5991.21
XS Rating Curve= 0 ,0
Exp/Cntr=0.3,0.1

Type RM Length L Ch R = 1 ,20390   ,743,743,743
BEGIN DESCRIPTION:
MACHO CREEK 30.0
END DESCRIPTION:
XS GIS Cut Line= 6
      2085038.43     13444476.04      2084941.84     13444400.59
      2084815.97     13444192.26      2084438.37     13444183.58
      2084260.42     13444309.45      2083570.32      13445307.7
#Sta/Elev= 30
    4489  358.44  4641.5   358.7  4671.9  357.84  4677.7     356  4687.4  355.52
  4723.2  358.12  4825.2   356.4 4861.65354.5044  4905.9  350.96    4926  353.48
  4957.2  355.05    4976  350.92    4996  349.06    5026   353.5    5166  358.59
  5293.8  356.25  5359.1  357.55  5365.2  358.68  5472.3  358.71  5573.7  361.33
  5587.3  348.74  5588.5  347.94  5601.9  348.74  5603.3  352.94 5604.72 354.507
  5609.5  359.78  5688.4  360.78  5976.5  359.47  6486.8  364.21  6664.2  364.61
#Mann= 3 ,-1 , 0
    4489      .1       0  5587.3     .07       0  5601.9      .1       0
Bank Sta=4861.65,5604.72
XS Rating Curve= 0 ,0
Exp/Cntr=0.3,0.1

Type RM Length L Ch R = 1 ,19647   ,476,476,476
BEGIN DESCRIPTION:
MACHO CREEK 29.0
END DESCRIPTION:
XS GIS Cut Line= 4
      2085043.25     13443323.25      2084720.96     13443367.61
      2084520.31     13443598.96      2084417.37     13443799.96
#Sta/Elev= 30
  4334.2   356.1  4413.2  355.67  4483.8  354.15  4574.7  355.25  4725.5  353.42
  4768.2  354.03  4789.1  355.84  4839.5  356.29  4860.3  355.83 4910.17352.2912
  4923.9  350.88  4965.8  351.06  4983.3  348.16  4987.2  344.93  4988.8  344.13
  5001.3  344.13  5002.9  344.93  5005.5     346  5011.1  346.74  5017.5  349.49
  5027.7  350.99  5055.5  352.06  5062.4  351.59 5071.01352.2912  5084.9  352.94
  5107.4  352.38  5144.3  355.06  5160.9  357.27  5166.5  356.35  5191.6  357.48
#Mann= 3 ,-1 , 0
  4334.2      .1       0  4987.2     .07       0  5002.9      .1       0
Bank Sta=4910.17,5071.01
XS Rating Curve= 0 ,0
Exp/Cntr=0.3,0.1

Type RM Length L Ch R = 1 ,19171   ,602,602,602
BEGIN DESCRIPTION:
MACHO CREEK 28.0
END DESCRIPTION:
XS GIS Cut Line= 4
      2084674.37     13443152.46      2084347.76     13443191.81
       2084320.5     13443222.29      2084311.95     13443544.51
#Sta/Elev= 30
    4650  354.44  4699.7  354.44  4713.9  353.17    4740  352.21  4750.1  350.93
  4770.2  352.45  4801.1  353.78  4911.3  354.28  4951.5  353.03  4965.2  351.54
    4967350.4657  4971.7  347.66  4982.4  343.71    4984  342.91  4996.5  342.91
  4998.1  343.71  5011.2  348.32  5018.3  349.45  5032.6  349.77  5043.1  349.31
  5052.6  350.88  5062.6   351.6  5092.6  351.41  5112.6  350.17 5142.84350.4656
  5192.6  352.71  5242.7  351.58  5262.7   352.9  5312.7  353.44  5342.2  354.41
#Mann= 3 ,-1 , 0
    4650      .1       0  4982.4     .07       0  4998.1      .1       0
Bank Sta=4967,5142.84
XS Rating Curve= 0 ,0
Exp/Cntr=0.3,0.1

Type RM Length L Ch R = 1 ,18569   ,878,878,878
BEGIN DESCRIPTION:
MACHO CREEK 27.0
END DESCRIPTION:
XS GIS Cut Line= 3
      2084548.65     13442544.68        2083825.       13443025.
      2081789.99     13443911.85
#Sta/Elev= 30
  4120.2  352.52  4196.4  352.58  4259.5  350.95  4352.7  353.48  4605.3  354.37
  4650.4  352.49 4677.57349.0798  4700.7  346.05  4772.7  348.91    4903  349.87
  4945.1  347.13  4975.2  347.25  4991.5   345.6  4994.3  341.29  4996.7  340.49
  5012.1  341.29  5021.2  343.86  5026.6  346.98  5032.4  347.73  5065.1  346.31
 5084.82349.0788  5125.8  351.16  5131.2  352.54  5172.6  353.02  5230.4  356.54
  5370.5  358.36  5650.4  359.82  6005.6  364.68  6699.6  367.11  7208.6   374.9
#Mann= 3 ,-1 , 0
  4120.2      .1       0  4994.3     .07       0  5012.1      .1       0
Bank Sta=4677.57,5084.82
XS Rating Curve= 0 ,0
Exp/Cntr=0.3,0.1

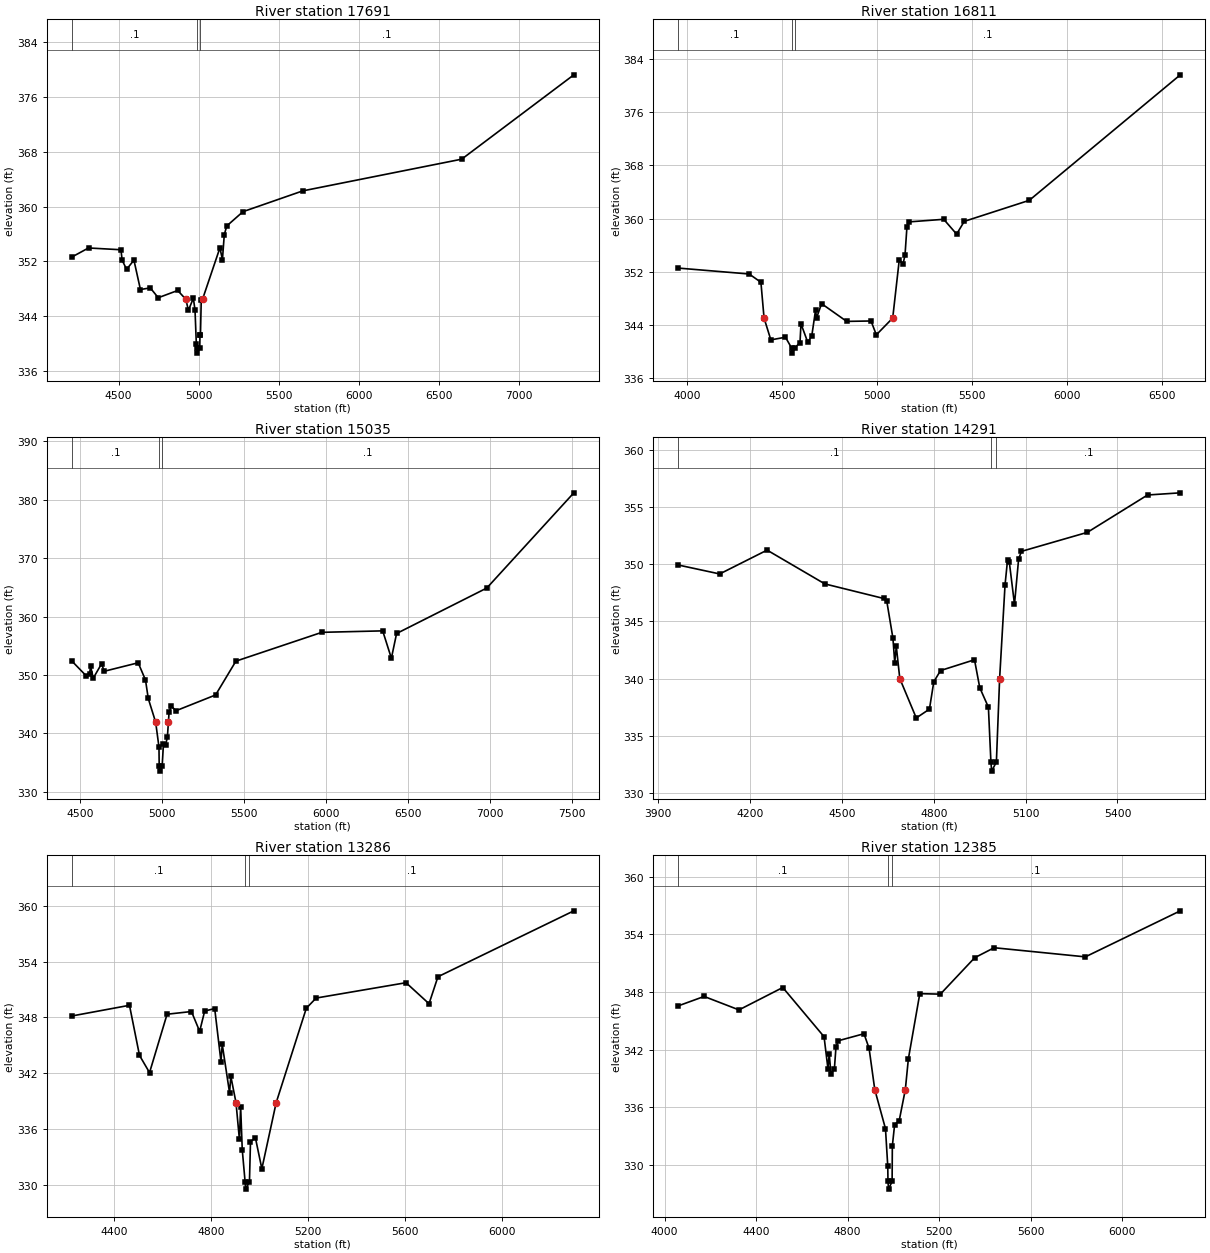
Type RM Length L Ch R = 1 ,17691   ,880,880,880
BEGIN DESCRIPTION:
MACHO CREEK 26.0
END DESCRIPTION:
XS GIS Cut Line= 3
      2084349.03     13442423.13        2083575.       13442625.
        2081575.       13443825.
#Sta/Elev= 30
  4207.9  352.62  4312.3  353.95  4514.7  353.69  4522.1  352.16    4550  350.83
  4595.7  352.17  4636.2  347.88  4697.8  348.12  4747.3  346.68  4868.7  347.74
 4919.56 346.455  4935.5  344.84  4966.5  346.61  4976.8  344.87    4985  339.94
  4988.6  339.39    4991  338.59  5006.4  339.39  5007.8   341.2  5010.7   341.2
  5015.6  346.32 5023.63346.4541  5132.2  353.97  5147.8  352.24  5159.4   355.9
    5175  357.17    5276  359.25  5649.2  362.29  6640.5  366.92  7340.2  379.24
#Mann= 3 ,-1 , 0
  4207.9      .1       0  4988.6     .07       0  5006.4      .1       0
Bank Sta=4919.56,5023.63
XS Rating Curve= 0 ,0
Exp/Cntr=0.3,0.1

Type RM Length L Ch R = 1 ,16811   ,1776,1776,1776
BEGIN DESCRIPTION:
double MACHO CREEK 25.0
END DESCRIPTION:
XS GIS Cut Line= 3
      2084227.51     13442171.39        2083225.       13442425.
      2081625.04       13442625.
#Sta/Elev= 30
  3951.6  352.55  4325.5  351.66  4387.4  350.42 4403.97345.0393  4439.7  341.76
  4516.6  342.16  4548.7  340.57  4551.1  339.77  4566.5  340.57  4593.4  341.35
  4598.6  344.18  4634.5  341.39  4655.6  342.37  4675.5  346.25  4680.6  345.06
  4707.2   347.2  4839.5  344.54  4967.8   344.6  4995.8  342.52 5082.08 345.038
  5116.7  353.79  5136.9  353.21  5146.9   354.5    5157  358.67  5167.1  359.49
    5351  359.88    5419  357.65  5459.3  359.57    5802  362.73  6598.1  381.59
#Mann= 3 ,-1 , 0
  3951.6      .1       0  4548.7     .07       0  4566.5      .1       0
Bank Sta=4403.97,5082.08
XS Rating Curve= 0 ,0
Exp/Cntr=0.3,0.1

Type RM Length L Ch R = 1 ,15035   ,744,744,744
BEGIN DESCRIPTION:
double MACHO CREEK 24.0
END DESCRIPTION:
XS GIS Cut Line= 4
      2084544.34     13441850.22      2084109.27     13441632.53
      2083973.85     13441665.08      2081675.03     13442474.99
#Sta/Elev= 30
  4447.5   352.4    4534  349.89  4556.4  350.21    4562  351.52  4578.7  349.45
    4629   351.9  4645.8  350.63  4852.6  352.08  4897.3  349.13  4914.1  345.97
 4959.34 341.895  4979.5  337.64  4980.9  334.32  4983.3  333.52  4998.8  334.32
    5007   338.2  5020.7  338.06    5031   339.4 5037.05 341.897  5041.2  343.61
  5054.1  344.68  5082.7  343.86    5325  346.57  5448.8  352.36  5973.3   357.3
  6344.4  357.55  6397.4  352.86  6429.2   357.1  6979.6  364.89  7510.6   381.2
#Mann= 3 ,-1 , 0
  4447.5      .1       0  4980.9     .07       0  4998.8      .1       0
Bank Sta=4959.34,5037.05
XS Rating Curve= 0 ,0
Exp/Cntr=0.3,0.1

Type RM Length L Ch R = 1 ,14291   ,1005,1005,1005
BEGIN DESCRIPTION:
MACHO CREEK 23.0
END DESCRIPTION:
XS GIS Cut Line= 3
      2084708.96     13441188.76      2083906.88     13441304.64
      2083158.42     13441661.98
#Sta/Elev= 30
  3965.4  349.93  4100.8  349.15  4255.6  351.23  4444.3  348.28  4636.3  347.01
  4646.4  346.79  4666.6  343.54  4672.5  341.42  4677.6  342.83    4689340.0198
  4742.8  336.58  4785.8  337.35  4800.1  339.74  4822.2  340.72    4933  341.66
  4950.2  339.22  4978.4  337.52  4986.6  332.74  4989.1  331.94  5004.5  332.74
 5015.05340.0175  5032.8  348.21  5040.9  350.35  5046.5  350.23  5063.6   346.5
  5077.1  350.45  5086.3  351.12  5301.6  352.78  5498.2  356.04  5605.2  356.23
#Mann= 3 ,-1 , 0
  3965.4      .1       0  4986.6     .07       0  5004.5      .1       0
Bank Sta=4689,5015.05
XS Rating Curve= 0 ,0
Exp/Cntr=0.3,0.1

Type RM Length L Ch R = 1 ,13286   ,901,901,901
BEGIN DESCRIPTION:
double MACHO CREEK 22.0
END DESCRIPTION:
XS GIS Cut Line= 3
      2084505.27     13441064.63        2083775.       13440875.
      2082474.98       13441075.
#Sta/Elev= 30
  4224.7  348.16  4462.6  349.31  4503.9  343.92  4545.3  342.07  4617.6  348.35
  4718.1  348.64  4751.9  346.51  4772.6  348.69  4813.9  348.96  4839.8  343.26
    4845  345.11  4875.2   339.9  4880.4  341.67 4901.78338.8353  4915.8  334.88
  4920.9  338.39  4927.5  333.78  4939.2  330.34  4941.7  329.54  4957.2  330.34
  4961.5  334.63  4981.7  335.07  5008.3  331.73 5067.36338.8376  5191.7     349
  5232.1  350.09  5602.7  351.74  5697.5  349.48  5734.2  352.38  6294.5  359.47
#Mann= 3 ,-1 , 0
  4224.7      .1       0  4939.2     .07       0  4957.2      .1       0
Bank Sta=4901.78,5067.36
XS Rating Curve= 0 ,0
Exp/Cntr=0.3,0.1

Type RM Length L Ch R = 1 ,12385   ,1299,1299,1299
BEGIN DESCRIPTION:
MACHO CREEK 21.0
END DESCRIPTION:
XS GIS Cut Line= 5
      2084555.14     13440667.89      2083789.55     13440295.52
      2083307.78     13440300.72      2082763.51       13440720.
      2082625.47     13440826.78
#Sta/Elev= 30
  4059.9  346.55  4173.1  347.53  4325.4  346.13  4516.9  348.46  4697.3  343.34
  4714.3  340.02  4719.9  341.57  4727.3  339.49  4742.4  339.97  4749.5  342.29
  4759.4  342.92  4871.8  343.65  4894.1  342.14 4919.01337.8359  4965.8  333.77
  4975.8  329.87  4976.7  328.28  4979.2  327.48  4994.8  328.28  4995.8  331.97
  5005.8   334.2  5025.8  334.61 5052.57337.8353  5065.8  341.02  5115.8  347.82
  5205.8  347.77  5355.8  351.56  5440.9   352.6  5839.5  351.65  6254.6  356.44
#Mann= 3 ,-1 , 0
  4059.9      .1       0  4976.7     .07       0  4994.8      .1       0
Bank Sta=4919.01,5052.57
XS Rating Curve= 0 ,0
Exp/Cntr=0.3,0.1

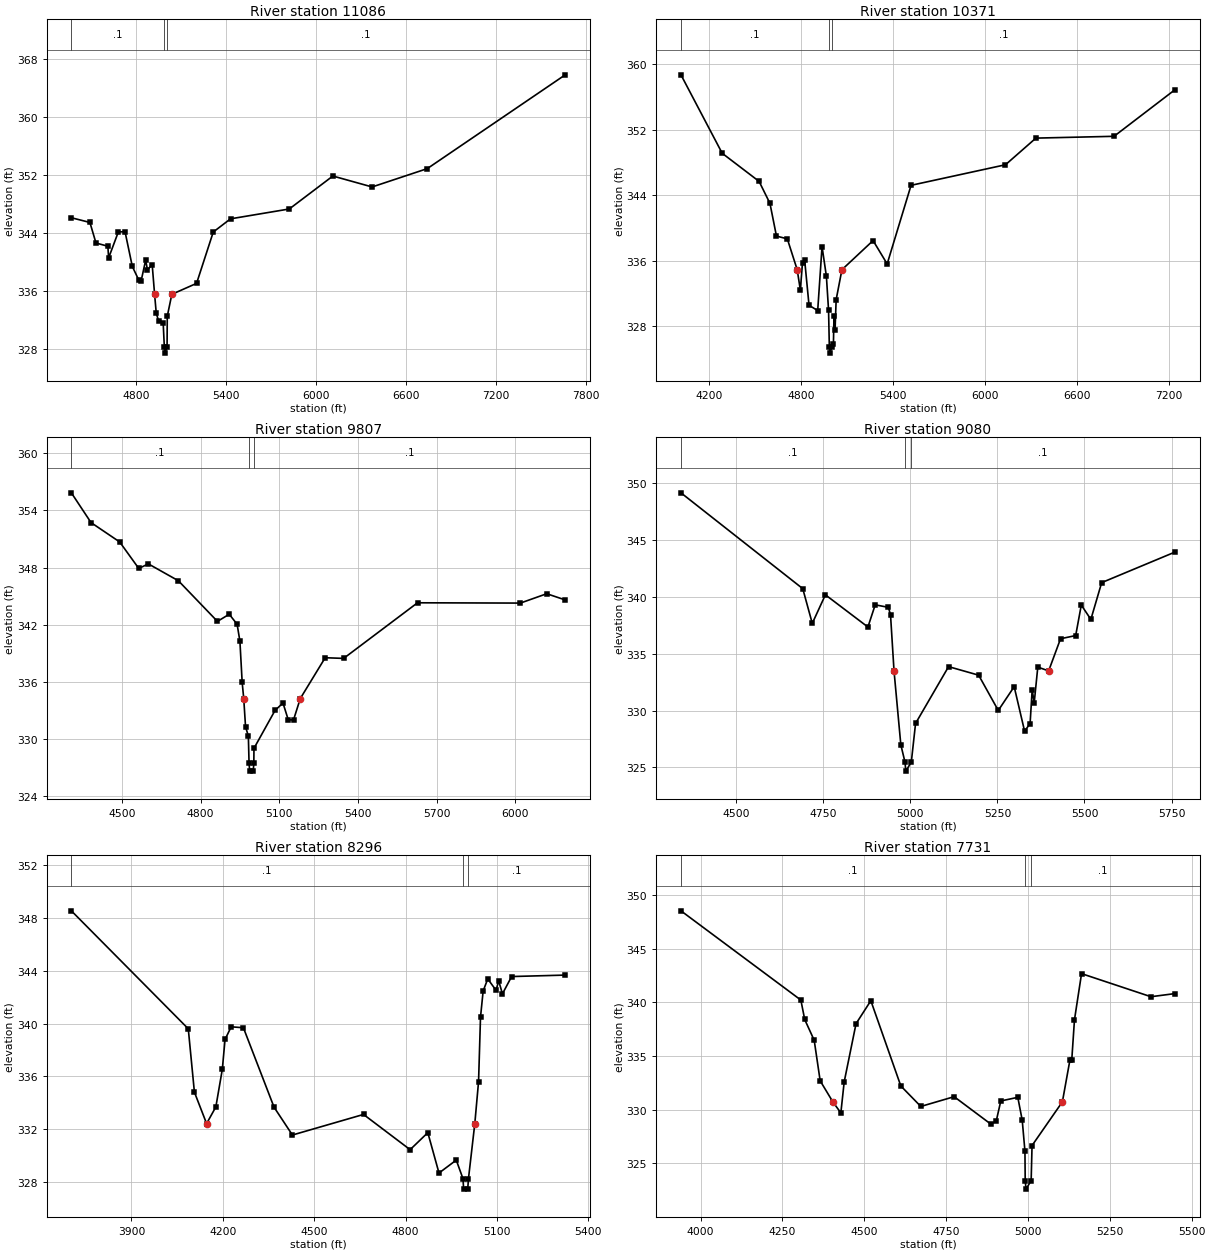
Type RM Length L Ch R = 1 ,11086   ,715,715,715
BEGIN DESCRIPTION:
double MACHO CREEK 20.0
END DESCRIPTION:
XS GIS Cut Line= 5
      2084415.93     13440267.42      2084363.84     13439913.24
      2084236.56     13439699.12      2083531.94     13439870.36
      2082085.06     13441194.87
#Sta/Elev= 30
  4366.4   346.1  4490.1  345.45  4530.6  342.61  4609.9  342.17  4614.9  340.55
  4679.6  344.14  4724.4  344.17  4772.9  339.38  4815.7  337.51  4831.3  337.34
  4861.9  340.24  4874.1   338.9  4905.4  339.64 4921.51335.5307  4932.6  332.92
  4948.2  331.85  4978.7  331.62  4986.6  328.21  4989.1  327.41  5004.7  328.21
    5006  332.49 5036.48335.5299  5201.5  337.04  5312.8  344.13  5427.9  345.95
  5819.9  347.31  6110.4  351.86  6372.3  350.35    6740  352.88  7660.2  365.83
#Mann= 3 ,-1 , 0
  4366.4      .1       0  4986.6     .07       0  5004.7      .1       0
Bank Sta=4921.51,5036.48
XS Rating Curve= 0 ,0
Exp/Cntr=0.3,0.1

Type RM Length L Ch R = 1 ,10371   ,564,564,564
BEGIN DESCRIPTION:
MACHO CREEK 19.0
END DESCRIPTION:
XS GIS Cut Line= 3
      2084874.99     13439824.99        2084175.       13439125.
        2082575.       13440675.
#Sta/Elev= 30
  4018.8  358.67  4287.5   349.1  4527.9  345.67  4598.6  342.99    4641     339
  4711.8  338.66 4776.16334.8954  4796.6  332.42  4810.7  335.73  4824.9  336.03
  4853.2  330.56  4909.7  329.91    4938  337.72  4966.3  334.11  4980.5  329.94
  4985.5  325.52    4988  324.72  5003.6  325.52  5012.2  325.88  5015.8  329.23
  5022.8  327.59    5030  331.25 5067.54334.8965  5270.5  338.45  5362.3   335.6
  5517.9  345.19  6133.2   347.7  6331.3  350.95  6840.4  351.17  7236.4  356.84
#Mann= 3 ,-1 , 0
  4018.8      .1       0  4985.5     .07       0  5003.6      .1       0
Bank Sta=4776.16,5067.54
XS Rating Curve= 0 ,0
Exp/Cntr=0.3,0.1

Type RM Length L Ch R = 1 ,9807    ,727,727,727
BEGIN DESCRIPTION:
MACHO CREEK 18.0
END DESCRIPTION:
XS GIS Cut Line= 3
        2084975.       13438925.        2084325.       13438675.
      2083144.92     13438803.77
#Sta/Elev= 30
  4307.3  355.83  4382.3  352.71  4491.6  350.68  4564.4   347.9  4600.9  348.38
  4715.5  346.61  4864.4  342.35  4909.4   343.1  4939.4  342.05  4950.1  340.28
  4958.7  335.96 4964.68334.2617  4971.6   331.3  4982.3  330.33    4985  327.45
  4987.5  326.65  5000.7  326.65  5003.2  327.45  5003.7  329.04  5084.2  333.02
  5114.4  333.79  5134.5  332.03  5154.6  332.02 5180.33334.2597  5275.3  338.54
  5345.7  338.47  5627.4   344.3  6019.7  344.27  6120.3  345.25  6190.8   344.6
#Mann= 3 ,-1 , 0
  4307.3      .1       0    4985     .07       0  5003.2      .1       0
Bank Sta=4964.68,5180.33
XS Rating Curve= 0 ,0
Exp/Cntr=0.3,0.1

Type RM Length L Ch R = 1 ,9080    ,784,784,784
BEGIN DESCRIPTION:
MACHO CREEK 17.0
END DESCRIPTION:
XS GIS Cut Line= 4
      2084727.57     13438262.91      2084163.31     13438087.12
      2084009.23     13438308.47      2083520.98     13438577.55
#Sta/Elev= 30
  4341.3  349.13  4691.1  340.71  4718.4  337.66  4756.1  340.17  4878.2  337.34
  4899.1  339.29    4937  339.07  4943.1  338.41 4953.13333.4868  4972.7  326.99
  4984.6  325.48  4987.1  324.68  5002.8  325.48    5015  328.87  5109.8  333.86
  5196.2  333.11  5252.5  330.01  5298.2   332.1  5328.1  328.19  5343.9  328.86
  5349.9  331.85  5355.6  330.65    5366  333.82 5397.16333.4861  5431.3  336.31
  5474.8  336.59  5490.9  339.27  5518.4  338.01  5549.4  341.24  5759.5  343.92
#Mann= 3 ,-1 , 0
  4341.3      .1       0  4984.6     .07       0  5002.8      .1       0
Bank Sta=4953.13,5397.16
XS Rating Curve= 0 ,0
Exp/Cntr=0.3,0.1

Type RM Length L Ch R = 1 ,8296    ,565,565,565
BEGIN DESCRIPTION:
MACHO CREEK 16.0
END DESCRIPTION:
XS GIS Cut Line= 4
      2084716.65     13438082.77       2083952.8     13438000.31
      2083529.63     13438258.56       2083334.3     13438558.06
#Sta/Elev= 30
  3702.6  348.54  4086.5   339.6  4106.6   334.8 4146.64332.4159    4177  333.68
  4198.2  336.52  4207.2  338.79  4227.3  339.75  4267.5  339.68  4368.1  333.66
  4428.4  331.55  4661.9  333.11  4814.9  330.44    4873  331.73  4909.7  328.67
  4966.4  329.65  4988.3  328.25  4990.8  327.45    5004  327.45  5006.5  328.25
 5027.28 332.415  5039.6   335.6    5046  340.48  5054.7  342.47  5069.8  343.38
  5096.9  342.52  5105.7  343.23    5118  342.25  5148.2  343.56  5324.2  343.67
#Mann= 3 ,-1 , 0
  3702.6      .1       0  4988.3     .07       0  5006.5      .1       0
Bank Sta=4146.64,5027.28
XS Rating Curve= 0 ,0
Exp/Cntr=0.3,0.1

Type RM Length L Ch R = 1 ,7731    ,815,815,815
BEGIN DESCRIPTION:
MACHO CREEK 15.0
END DESCRIPTION:
XS GIS Cut Line= 4
      2084744.92     13438019.84      2083752.25     13437831.47
      2083633.79     13437781.13      2083289.35     13437915.44
#Sta/Elev= 30
  3939.8  348.53  4306.1  340.22  4317.9  338.41  4346.9  336.47  4365.1   332.7
 4403.78330.7404  4428.3  329.71  4438.5   332.6  4474.7  338.02  4519.9  340.16
  4611.5  332.22  4672.6  330.31  4774.4  331.22  4886.3  328.67    4903  328.95
  4916.9  330.82  4968.9  331.16  4982.4  329.03  4990.7  326.15  4991.5  323.41
    4994  322.61  5009.7  323.41  5012.4  326.67  5105.1330.7395  5128.4  334.68
  5133.7  334.62    5142  338.38  5163.6  342.68  5375.7  340.53  5448.6  340.82
#Mann= 3 ,-1 , 0
  3939.8      .1       0  4991.5     .07       0  5009.7      .1       0
Bank Sta=4403.78,5105.1
XS Rating Curve= 0 ,0
Exp/Cntr=0.3,0.1

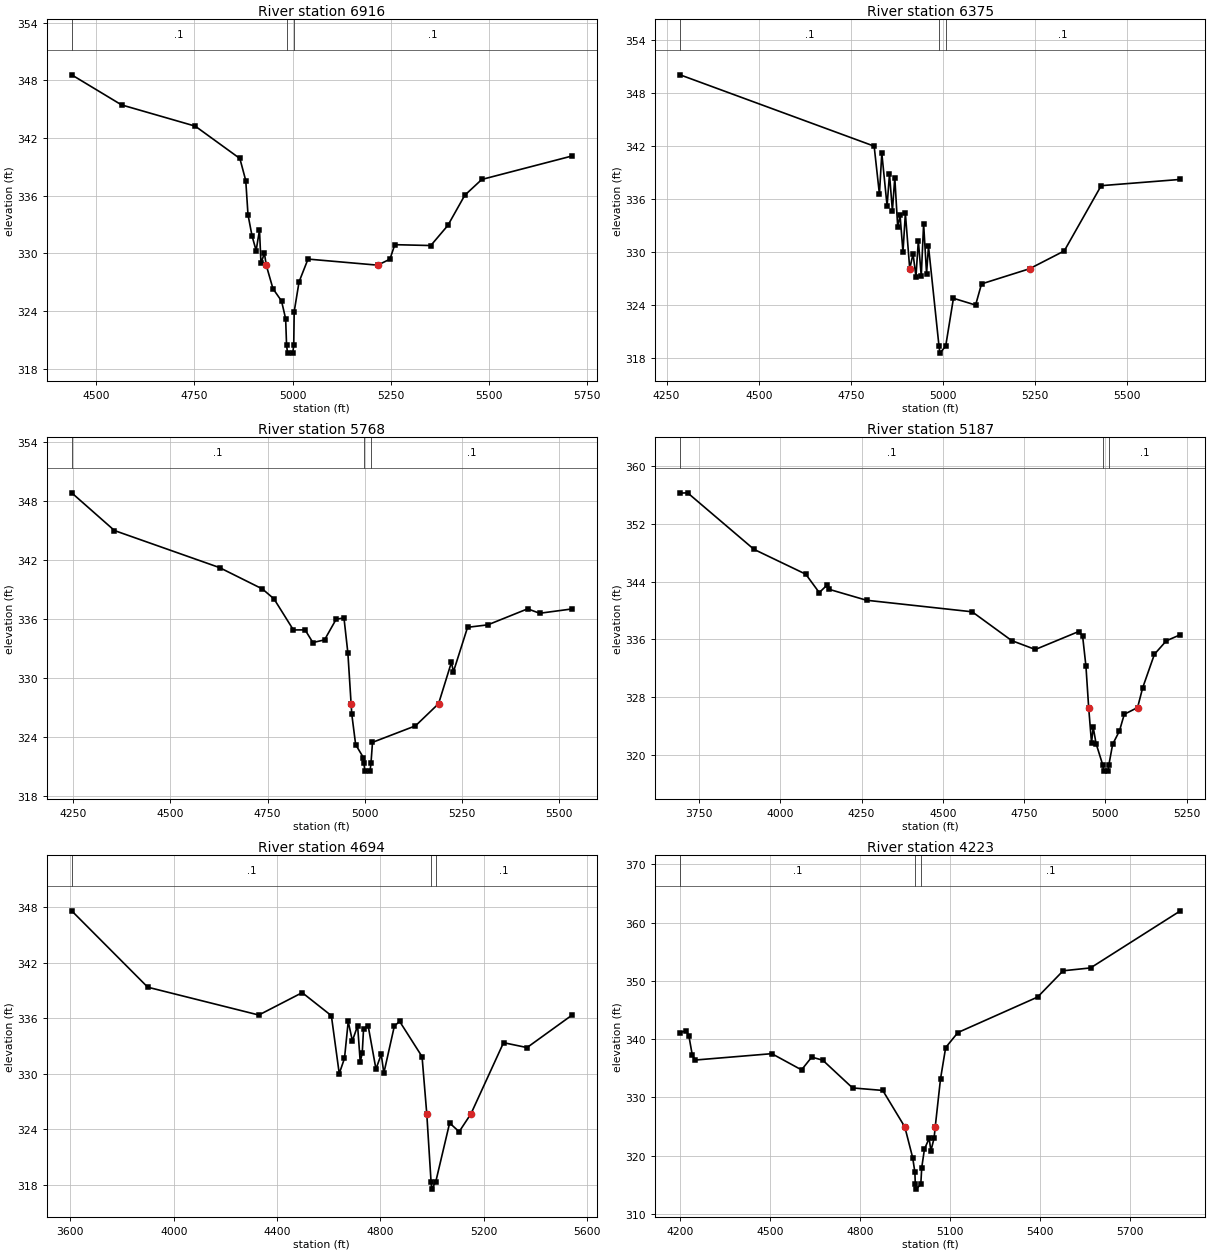
Type RM Length L Ch R = 1 ,6916    ,541,541,541
BEGIN DESCRIPTION:
MACHO CREEK 14.0
END DESCRIPTION:
XS GIS Cut Line= 4
      2084799.16     13437913.51      2084332.58     13437789.81
      2084204.54     13437555.43      2083692.37     13437440.41
#Sta/Elev= 30
  4437.1  348.59  4564.1  345.46  4751.8  343.25  4865.6  339.88  4880.6  337.58
  4886.3  334.03  4896.6  331.82    4907   330.3  4915.6  332.43  4919.4  328.96
  4928.1  330.03 4932.77328.7757  4949.9  326.33  4971.7  325.05  4982.2   323.2
  4984.6  320.42  4987.1  319.62  5000.3  319.62  5002.8  320.42    5004  323.94
  5016.4  327.04  5039.2  329.41 5216.55328.7765  5247.9   329.4  5260.3  330.91
    5352  330.82  5395.4  332.91  5438.7  336.06    5482   337.7  5711.8  340.14
#Mann= 3 ,-1 , 0
  4437.1      .1       0  4984.6     .07       0  5002.8      .1       0
Bank Sta=4932.77,5216.55
XS Rating Curve= 0 ,0
Exp/Cntr=0.3,0.1

Type RM Length L Ch R = 1 ,6375    ,607,607,607
BEGIN DESCRIPTION:
double MACHO CREEK 13.0
END DESCRIPTION:
XS GIS Cut Line= 3
      2084975.03     13437825.02      2084451.94     13437399.18
      2083770.53     13437355.78
#Sta/Elev= 30
  4286.6  350.08  4813.1  341.99  4827.4  336.55  4833.9  341.18  4848.2  335.21
  4854.7  338.82  4862.6  334.68  4869.1  338.42    4877  332.82  4883.4  334.14
  4891.3  329.98  4897.8  334.37 4909.62 328.087  4918.6  329.78  4926.5  327.19
    4933  331.27  4940.9  327.25  4947.3  333.19  4955.3  327.54  4960.5  330.64
    4989  319.32  4991.5  318.52  5007.2  319.32  5028.2  324.74  5088.3  323.97
  5104.4  326.37 5234.64328.0876  5328.8  330.11    5429  337.51  5643.9  338.22
#Mann= 3 ,-1 , 0
  4286.6      .1       0    4989     .07       0  5007.2      .1       0
Bank Sta=4909.62,5234.64
XS Rating Curve= 0 ,0
Exp/Cntr=0.3,0.1

Type RM Length L Ch R = 1 ,5768    ,581,581,581
BEGIN DESCRIPTION:
double MACHO CREEK 12.0
END DESCRIPTION:
XS GIS Cut Line= 3
      2085024.97       13436875.        2084275.       13436875.
      2083754.17     13437002.58
#Sta/Elev= 30
  4246.5  348.84  4356.5     345  4626.5  341.23  4736.5  339.06  4766.5  338.05
  4816.5  334.88  4846.5  334.89  4866.5   333.6  4896.5  333.87  4926.5  335.98
  4946.5   336.1  4956.5  332.54 4964.81327.3712  4966.5  326.32  4976.5  323.21
  4996.5  321.88  4997.7  321.31  5000.2  320.51  5013.4  320.51  5015.9  321.31
  5019.8  323.44  5130.3  325.12 5189.66 327.374  5222.7  331.59  5227.9  330.63
  5264.2  335.15  5316.2   335.4  5418.6  337.03  5449.5  336.58  5532.7  337.02
#Mann= 3 ,-1 , 0
  4246.5      .1       0  4997.7     .07       0  5015.9      .1       0
Bank Sta=4964.81,5189.66
XS Rating Curve= 0 ,0
Exp/Cntr=0.3,0.1

Type RM Length L Ch R = 1 ,5187    ,493,493,493
BEGIN DESCRIPTION:
double MACHO CREEK 11.0
END DESCRIPTION:
XS GIS Cut Line= 3
      2085317.38     13436771.74       2084067.4     13436421.74
      2083869.41     13436559.41
#Sta/Elev= 30
  3691.6  356.25  3714.8  356.29    3919  348.46  4078.3  345.02  4119.8  342.47
  4144.4  343.54    4151  342.91  4265.2  341.41  4590.2  339.81  4711.8  335.82
  4784.5  334.59  4918.1  337.08  4929.8  336.52  4940.2  332.28 4948.61326.5468
  4957.4  321.65  4962.6   323.8  4971.4  321.56  4992.3  318.54  4994.8  317.74
    5008  317.74  5010.5  318.54  5022.3  321.45  5043.3  323.31  5058.1  325.61
 5099.07326.5496  5114.8  329.29  5150.9  333.93  5187.5  335.79  5230.8  336.64
#Mann= 3 ,-1 , 0
  3691.6      .1       0  4992.3     .07       0  5010.5      .1       0
Bank Sta=4948.61,5099.07
XS Rating Curve= 0 ,0
Exp/Cntr=0.3,0.1

Type RM Length L Ch R = 1 ,4694    ,471,471,471
BEGIN DESCRIPTION:
double MACHO CREEK 10.0
END DESCRIPTION:
XS GIS Cut Line= 4
      2085224.99       13436175.      2083963.43     13435953.45
      2083781.14     13436036.78      2083846.25      13436487.3
#Sta/Elev= 30
  3605.1  347.63  3899.5  339.37  4329.4  336.36  4497.3  338.78  4610.2  336.29
  4640.7  330.02    4661  331.68  4675.4  335.67  4691.5  333.57  4711.8   335.2
  4721.9  331.29  4729.7  332.26  4734.8  334.87  4752.4  335.22  4782.8  330.51
  4803.2  332.12  4813.3  330.08  4853.9  335.15  4874.2  335.68  4961.2  331.86
 4979.44325.6804    4996  318.33  4998.5  317.53  5014.3  318.33  5067.9  324.68
  5104.8  323.74 5150.54325.6786  5276.6  333.37  5367.5  332.84  5541.6  336.35
#Mann= 3 ,-1 , 0
  3605.1      .1       0    4996     .07       0  5014.3      .1       0
Bank Sta=4979.44,5150.54
XS Rating Curve= 0 ,0
Exp/Cntr=0.3,0.1

Type RM Length L Ch R = 1 ,4223    ,242,242,242
BEGIN DESCRIPTION:
MACHO CREEK 9.0
END DESCRIPTION:
XS GIS Cut Line= 5
      2084275.41      13435555.1      2083751.67     13435633.66
      2083411.35     13435762.47      2082990.34     13435860.56
      2082706.05     13436050.93
#Sta/Elev= 30
  4198.9  341.11  4219.5  341.43  4228.3  340.54  4239.8  337.19  4249.9   336.4
  4504.7  337.49  4603.8  334.71  4637.8   336.9  4674.6  336.37  4773.9  331.61
  4874.6  331.18 4948.08324.9171  4974.3  319.64  4981.6  317.17  4983.1  315.04
  4985.6  314.24  5001.4  315.04  5004.5  317.94  5013.6  321.11  5029.3  322.96
    5035   320.8  5045.7  322.99 5049.49324.9166  5067.1  333.16  5084.3  338.54
  5125.1  341.12  5390.8  347.21  5475.9  351.72  5567.2  352.21  5866.8  362.01
#Mann= 3 ,-1 , 0
  4198.9      .1       0  4983.1     .07       0  5001.4      .1       0
Bank Sta=4948.08,5049.49
XS Rating Curve= 0 ,0
Exp/Cntr=0.3,0.1