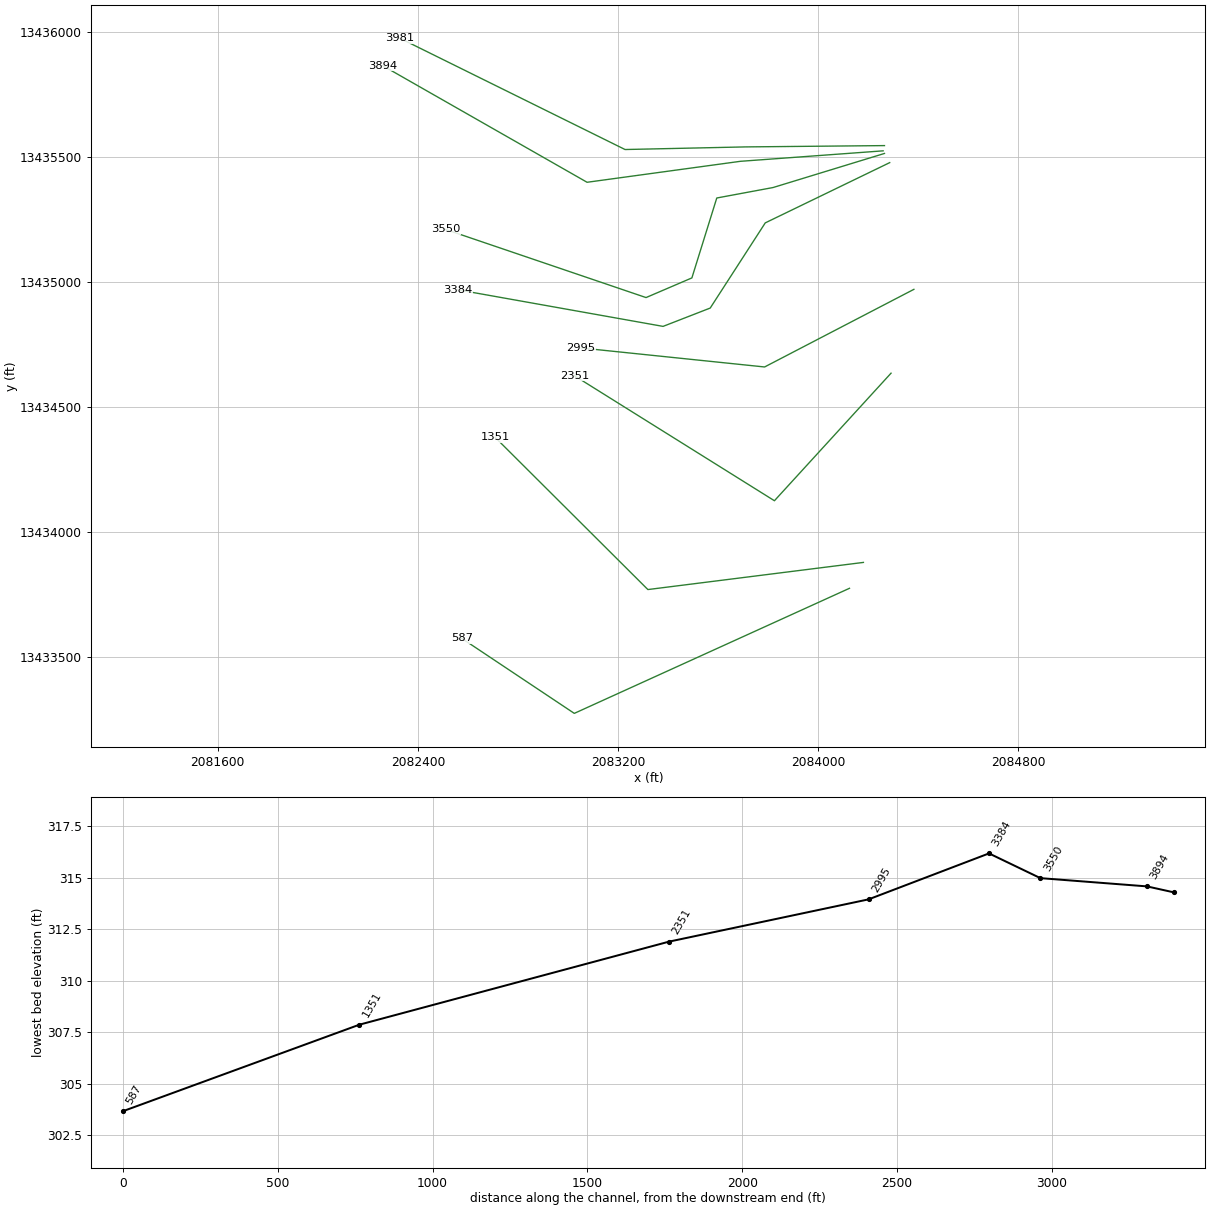
HEC-RAS study MACHO CREEK.prj: MACHO CREEK Base Level Engineering

--- MACHO CREEK.g01 (geometry) --- (continued)

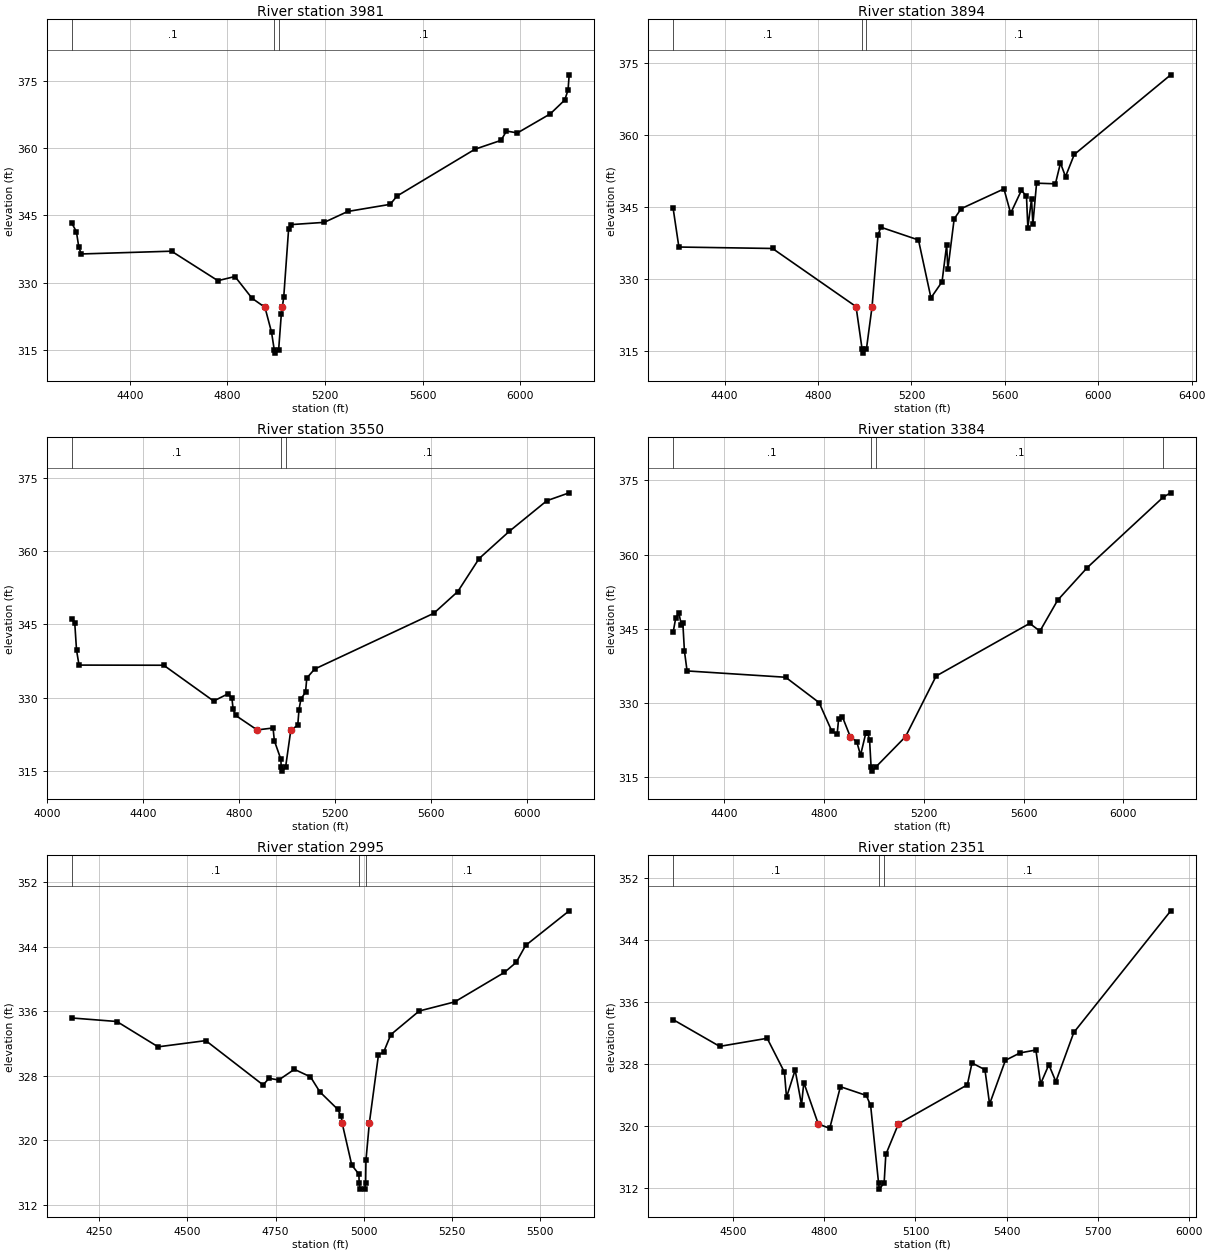
Type RM Length L Ch R = 1 ,3981    ,87,87,87
BEGIN DESCRIPTION:
MACHO CREEK 8.0
END DESCRIPTION:
XS GIS Cut Line= 4
      2084264.93     13435544.63      2083709.78      13435539.4
      2083227.98     13435528.92       2082328.6     13435973.39
#Sta/Elev= 30
    4161  343.38  4180.9  341.38  4190.9  337.89  4200.9  336.41  4570.9  337.03
    4761  330.45    4831  331.38    4901  326.53 4953.97324.5092    4981  318.94
  4991.9  315.09  4994.4  314.29  5010.2  315.09    5021  322.95 5025.06324.5091
    5031  326.79    5051  341.97    5061  342.96  5197.1  343.46  5293.5  345.89
  5467.5  347.48  5495.5  349.33  5815.2  359.78  5921.8  361.75  5944.3  363.83
  5989.2  363.41  6123.8  367.66    6183  370.74  6196.7  372.98  6201.3  376.37
#Mann= 3 ,-1 , 0
    4161      .1       0  4991.9     .07       0  5010.2      .1       0
Bank Sta=4953.97,5025.06
XS Rating Curve= 0 ,0
Exp/Cntr=0.3,0.1

Type RM Length L Ch R = 1 ,3894    ,344,344,344
BEGIN DESCRIPTION:
MACHO CREEK 7.0
END DESCRIPTION:
XS GIS Cut Line= 4
      2084259.61     13435523.68      2083688.83     13435481.79
      2083076.11       13435398.      2082259.58     13435863.84
#Sta/Elev= 30
  4179.6  344.74  4204.3  336.66  4605.3  336.36 4962.88324.2634  4988.9  315.38
  4991.4  314.58  5007.2  315.38 5031.57324.2655  5056.9  339.12  5068.7  340.79
  5230.2  338.13  5283.7  326.08  5331.1  329.42  5350.9  337.11  5355.9  332.01
  5383.1  342.52  5413.3  344.65  5596.2  348.76  5624.9  343.69  5670.9  348.45
  5692.7  347.25  5698.5  340.72  5714.3  346.71  5720.1  341.38  5735.9  349.95
  5816.6  349.82  5838.2  354.15  5859.8  351.31  5897.3  355.92  6310.4   372.5
#Mann= 3 ,-1 , 0
  4179.6      .1       0  4988.9     .07       0  5007.2      .1       0
Bank Sta=4962.88,5031.57
XS Rating Curve= 0 ,0
Exp/Cntr=0.3,0.1

Type RM Length L Ch R = 1 ,3550    ,166,166,166
BEGIN DESCRIPTION:
MACHO CREEK 6.0
END DESCRIPTION:
XS GIS Cut Line= 6
      2084264.88     13435513.21      2083819.75     13435377.05
      2083594.56     13435335.16      2083495.06     13435015.71
      2083311.77     13434937.15      2082510.53     13435209.47
#Sta/Elev= 30
  4102.3  346.13  4115.6  345.32  4123.1   339.7  4133.5  336.66  4486.6  336.63
  4694.7  329.31  4755.7  330.81  4770.7  329.98  4776.1  327.61  4786.2  326.38
 4875.99323.4063  4942.5   323.8  4947.8  321.21  4975.1  317.39  4976.4  315.78
  4978.9  314.98  4994.7  315.78 5016.65 323.407  5045.4  324.33  5050.6  327.53
  5058.9  329.77  5077.9   331.1  5083.1  334.01  5115.6  335.84  5612.6  347.25
  5712.8   351.7  5801.6  358.44  5927.2     364  6084.1  370.27  6177.1  371.88
#Mann= 3 ,-1 , 0
  4102.3      .1       0  4976.4     .07       0  4994.7      .1       0
Bank Sta=4875.99,5016.65
XS Rating Curve= 0 ,0
Exp/Cntr=0.3,0.1

Type RM Length L Ch R = 1 ,3384    ,389,389,389
BEGIN DESCRIPTION:
MACHO CREEK 5.0
END DESCRIPTION:
XS GIS Cut Line= 5
      2084285.81     13435476.54      2083788.33     13435235.66
      2083568.38     13434895.26      2083379.85     13434821.94
       2082558.8     13434968.37
#Sta/Elev= 30
  4195.1  344.25  4205.8  347.21  4218.2  348.11  4228.4  345.72    4234  346.17
  4240.4   340.5    4251  336.45    4646  335.17    4780  330.05  4831.4  324.23
  4852.6   323.7  4858.5   326.8  4873.7  327.15 4905.01323.1532  4931.1  322.11
  4946.3  319.42  4967.4  323.89  4974.8  323.97  4982.5  322.41  4988.6  316.98
  4991.1  316.18  5006.9  316.98 5126.58323.1533  5249.2  335.42  5624.2  346.07
  5665.1   344.5  5736.2  350.76    5855  357.36  6159.9  371.63  6189.4  372.48
#Mann= 4 ,-1 , 0
  4195.1      .1       0  4988.6     .07       0  5006.9      .1       0
  6159.9     .05       0
Bank Sta=4905.01,5126.58
XS Rating Curve= 0 ,0
Exp/Cntr=0.3,0.1

Type RM Length L Ch R = 1 ,2995    ,644,644,644
BEGIN DESCRIPTION:
MACHO CREEK 4.0
END DESCRIPTION:
XS GIS Cut Line= 3
      2084382.51     13434970.01      2083785.76      13434659.7
      2083052.29     13434735.65
#Sta/Elev= 30
  4171.6  335.17    4300  334.73  4416.8  331.59    4552  332.36  4714.5  326.86
  4730.9  327.69  4758.7  327.48  4802.9   328.8  4848.6  327.87  4875.1  326.01
  4925.4  323.86  4935.5     323 4938.35322.1324  4965.6  316.93  4985.7  315.81
  4986.6  314.75  4989.1  313.95  5002.4  313.95  5004.9  314.75  5005.8  317.54
 5015.36322.1307  5041.2  330.58  5056.1  330.95  5076.2   333.1  5156.6  336.03
  5257.2  337.16  5397.9  340.81  5431.4  342.05  5458.2  344.16  5581.6  348.45
#Mann= 3 ,-1 , 0
  4171.6      .1       0  4986.6     .07       0  5004.9      .1       0
Bank Sta=4938.35,5015.36
XS Rating Curve= 0 ,0
Exp/Cntr=0.3,0.1

Type RM Length L Ch R = 1 ,2351    ,1000,1000,1000
BEGIN DESCRIPTION:
MACHO CREEK 3.0
END DESCRIPTION:
XS GIS Cut Line= 3
      2084291.21     13434634.95        2083825.       13434125.
      2083025.04     13434624.98
#Sta/Elev= 30
  4304.1  333.76    4457  330.31    4613  331.35  4669.7  326.98  4676.5  323.74
  4704.9  327.26  4725.9  322.77  4733.3  325.65 4780.67320.3135  4818.4  319.73
  4853.5  325.11  4938.6  323.98  4952.8  322.69  4978.8   312.7  4981.3   311.9
  4997.1   312.7  5002.7  316.37 5044.06320.3134  5270.4  325.35  5285.7  328.17
  5328.2   327.3  5343.5  322.87  5395.4  328.51  5443.7  329.47  5495.6  329.84
    5511  325.48  5538.1  327.94  5561.1  325.77    5620   332.1  5938.4  347.79
#Mann= 3 ,-1 , 0
  4304.1      .1       0  4978.8     .07       0  4997.1      .1       0
Bank Sta=4780.67,5044.06
XS Rating Curve= 0 ,0
Exp/Cntr=0.3,0.1

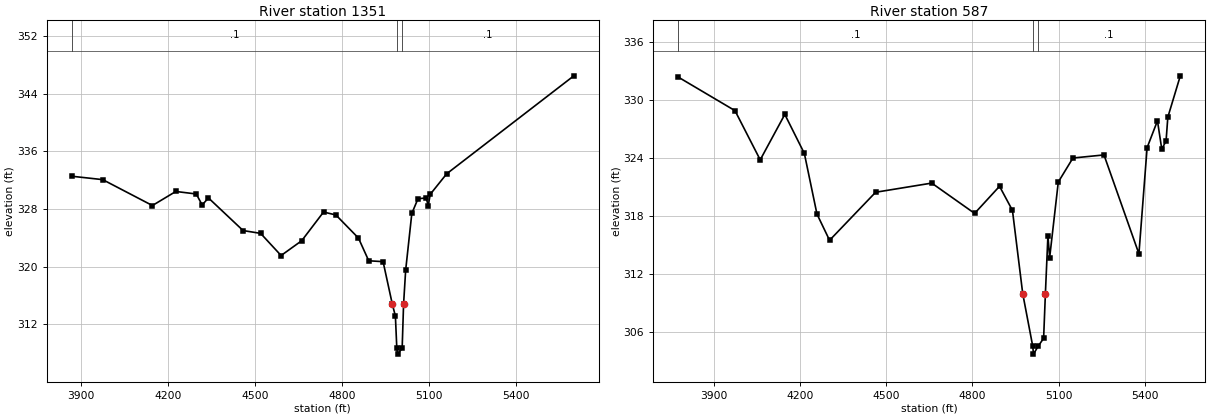
Type RM Length L Ch R = 1 ,1351    ,764,764,764
BEGIN DESCRIPTION:
MACHO CREEK 2.0
END DESCRIPTION:
XS GIS Cut Line= 3
      2084180.74     13433878.45      2083319.18     13433769.94
      2082708.62     13434378.34
#Sta/Elev= 30
  3867.9  332.53  3974.5  332.06  4145.8  328.47  4226.5  330.42    4297  330.07
  4317.2  328.55    4339  329.52  4458.3     325  4518.7  324.61  4589.3  321.54
  4660.3  323.59  4735.6  327.57  4778.2  327.16  4855.9  323.96  4891.3  320.81
  4940.8  320.69 4972.38314.8384  4983.2  313.15  4988.1  308.67  4990.6  307.87
  5006.5  308.67 5011.44314.8351  5018.6  319.51  5039.8  327.37    5061  329.41
  5089.3  329.52  5096.3  328.47  5103.4  330.03    5160  332.87  5598.2  346.45
#Mann= 3 ,-1 , 0
  3867.9      .1       0  4988.1     .07       0  5006.5      .1       0
Bank Sta=4972.38,5011.44
XS Rating Curve= 0 ,0
Exp/Cntr=0.3,0.1

Type RM Length L Ch R = 1 ,587     ,0,0,0
BEGIN DESCRIPTION:
MACHO CREEK 1.0
END DESCRIPTION:
XS GIS Cut Line= 3
      2084124.98     13433774.99        2083025.       13433275.
      2082575.01     13433574.99
#Sta/Elev= 30
  3774.9  332.39  3972.6  328.91  4060.5  323.81  4146.2  328.52  4214.3  324.47
  4258.2  318.19  4302.1  315.47  4462.5  320.45    4658   321.4  4807.4  318.26
  4894.2  321.07  4939.2  318.57 4974.96309.9522    5010  304.47  5012.5  303.67
  5028.4  304.47  5047.8  305.31 5053.98309.9492  5062.8  315.95  5068.8  313.67
  5098.9  321.51  5149.9     324  5258.1  324.32  5379.8  314.07  5408.3  325.07
  5444.4  327.86  5459.4  324.92  5474.4  325.77  5480.5  328.23    5524  332.52
#Mann= 3 ,-1 , 0
  3774.9      .1       0    5010     .07       0  5028.4      .1       0
Bank Sta=4974.96,5053.98
XS Rating Curve= 0 ,0
Exp/Cntr=0.3,0.1
LCMann Table=0

Chan Stop Cuts=-1
Use User Specified Reach Order=0
Composite Channel Slope=5