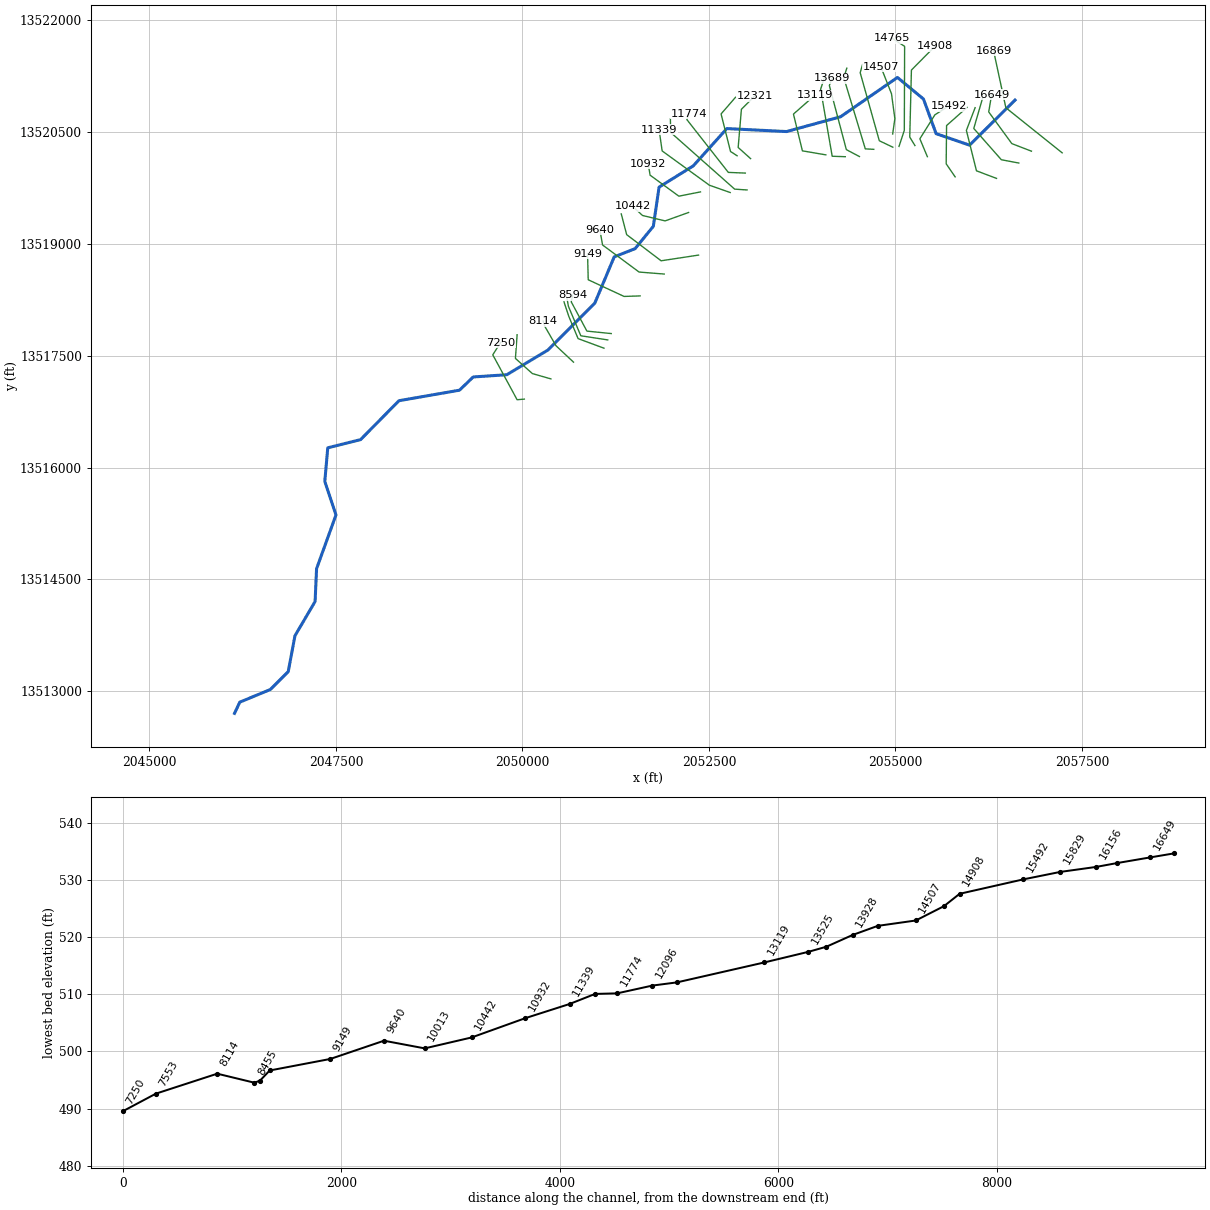
--- PANTHER Cr.prj (project) ---

Proj Title=PANTHER Cr Base Level Engineering
Current Plan=p01
Default Exp/Contr=0.3,0.1
English Units
Geom File=g01
Flow File=f01
Plan File=p01
BEGIN DESCRIPTION:
PANTHER Cr
END DESCRIPTION:

--- PANTHER Cr.p01 (plan) ---

Plan Title=Multiple Run
Short Identifier=Multiple
Geom File=g01
Flow File=f01
Subcritical Flow
K Sum by GR= 0
Std Step Tol= 0.01
Critical Tol= 0.01
Num of Std Step Trials= 20
Max Error Tol= 0.3
Flow Tol Ratio= 0.001
Split Flow NTrial= 30
Split Flow Tol= 0.02
Split Flow Ratio= 0.02
Log Output Level= 0
Friction Slope Method= 1
Unsteady Friction Slope Method= 2
Unsteady Bridges Friction Slope Method= 1
Parabolic Critical Depth
Global Vel Dist=  1 , 1 , 1
Global Log Level= 0
CheckData=True
Encroach Param= -1, 0, 0, 0
BEGIN DESCRIPTION:
Multiple Run
END DESCRIPTION:

--- PANTHER Cr.f01 (steady flow) ---

Flow Title=Multiple
Number of Profiles=7
Profile Names=10-year,25-year,50-year,1pct_min,100-year,1pct_plu,500-year
River Rch & RM= PANTHER Cr,Reach-1,16869
     140     187     225     135     269     537     391
River Rch & RM= PANTHER Cr,Reach-1,14159
     237     326     400     244     487     973     735
River Rch & RM= PANTHER Cr,Reach-1,11339
     346     484     600     370     739    1474    1138
River Rch & RM= PANTHER Cr,Reach-1,5031
     651     940    1189     748    1493    2978    2389
Boundary for River Rch & Prof#=PANTHER Cr,Reach-1,1
Up Type=0
Dn Type=3
Dn Slope=0.005
Boundary for River Rch & Prof#=PANTHER Cr,Reach-1,2
Up Type=0
Dn Type=3
Dn Slope=0.005
Boundary for River Rch & Prof#=PANTHER Cr,Reach-1,3
Up Type=0
Dn Type=3
Dn Slope=0.005
Boundary for River Rch & Prof#=PANTHER Cr,Reach-1,4
Up Type=0
Dn Type=3
Dn Slope=0.005
Boundary for River Rch & Prof#=PANTHER Cr,Reach-1,5
Up Type=0
Dn Type=3
Dn Slope=0.005
Boundary for River Rch & Prof#=PANTHER Cr,Reach-1,6
Up Type=0
Dn Type=3
Dn Slope=0.005
Boundary for River Rch & Prof#=PANTHER Cr,Reach-1,7
Up Type=0
Dn Type=3
Dn Slope=0.005

--- PANTHER Cr.g01 (geometry) ---

Geom Title=Existing Conditions

River Reach=PANTHER Cr,Reach-1
Reach XY= 30
      2056604.36     13520926.21      2055994.46     13520322.04
      2055546.54     13520476.21      2055376.76     13520940.88
      2055027.80     13521229.94      2054265.14     13520702.46
      2053540.80     13520504.54      2052740.80     13520544.54
      2052290.80     13520044.54      2051832.38     13519759.69
      2051755.34     13519234.52      2051510.80     13518934.54
      2051230.80     13518824.54      2050970.80     13518204.54
      2050340.80     13517574.54      2049790.80     13517244.54
      2049340.80     13517214.54      2049156.60     13517037.25
      2048344.97     13516896.20      2047830.80     13516374.54
      2047390.80     13516264.54      2047350.80     13515814.54
      2047500.80     13515364.54      2047240.80     13514644.54
      2047220.80     13514204.54      2046950.80     13513744.54
      2046860.80     13513264.54      2046620.80     13513024.54
      2046210.80     13512854.54      2046140.80     13512704.54

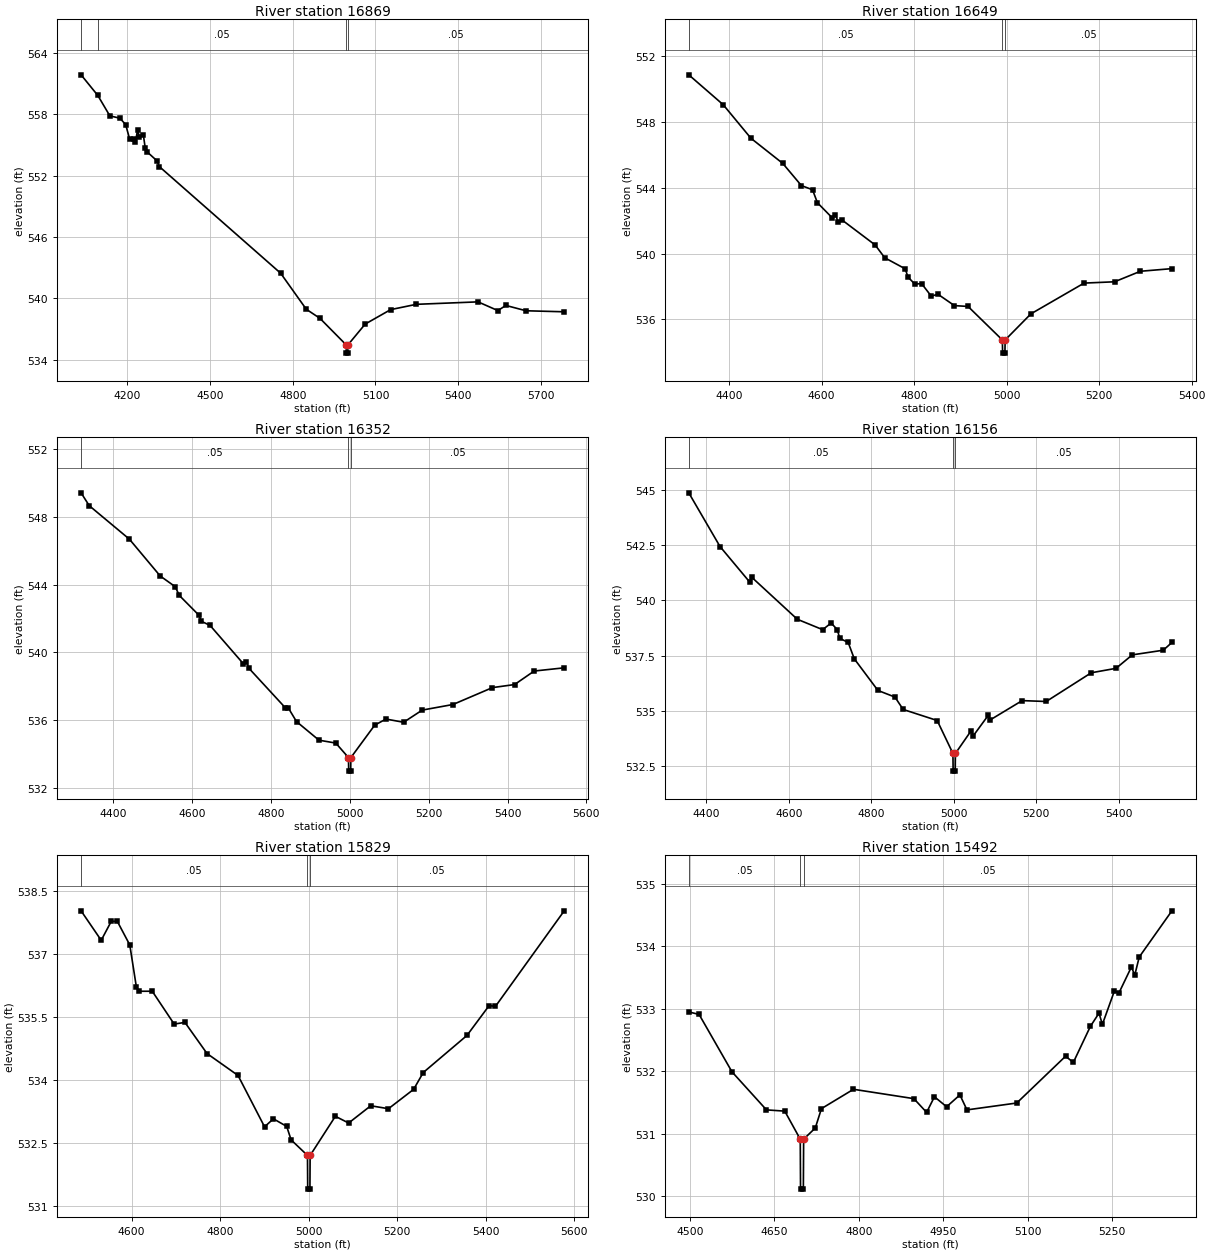
Type RM Length L Ch R = 1,16869,220,220,220
BEGIN DESCRIPTION:
PANTHER Cr 29.0
END DESCRIPTION:
XS GIS Cut Line= 3
      2057236.42     13520219.06      2056481.44     13520823.60
      2056316.34     13521590.33
#Sta/Elev= 30
  4032.8  561.85  4093.6  559.83  4137.1  557.84  4173.7  557.61  4194.5  556.98
  4208.9  555.57  4223.3  555.62  4229.7  555.26  4237.7  556.46  4244.1  555.78
  4258.6  555.97  4265.2  554.73  4273.0  554.30  4308.2  553.44  4316.2  552.89
  4756.3  542.46  4849.2  538.94  4898.8  538.05  4994.1  535.45  4994.6  534.65
  4999.6  534.65  5000.1  535.45  5062.8  537.49  5154.9  538.90  5248.2  539.42
  5472.0  539.66  5543.6  538.81  5573.0  539.31  5645.9  538.79  5784.3  538.69
#Mann=4,-1,0
  4032.8     0.1       0  4093.6    0.05       0  4994.1    0.03       0
  5000.1    0.05       0
Bank Sta=4994.1,5000.1
Exp/Cntr=0.3,0.1

Type RM Length L Ch R = 1,16649,297,297,297
BEGIN DESCRIPTION:
Mapping XS ea9a2835
END DESCRIPTION:
XS GIS Cut Line= 4
      2056824.59     13520241.28      2056561.58     13520342.84
      2056251.68     13520767.32      2056290.60     13521000.80
#Sta/Elev= 30
  4313.1  550.87  4387.6  549.05  4447.5  547.01  4516.3  545.48  4556.6  544.13
  4580.6  543.88  4591.1  543.09  4622.5  542.19  4630.1  542.35  4636.3  541.91
  4644.8  542.03  4715.9  540.52  4736.7  539.74  4780.8  539.07  4786.9  538.57
  4801.6  538.14  4816.3  538.17  4837.1  537.41  4851.8  537.52  4887.3  536.83
  4916.7  536.78  4990.9  534.74  4991.4  533.94  4996.4  533.94  4996.9  534.74
  5052.6  536.33  5167.5  538.20  5233.4  538.28  5289.2  538.92  5357.3  539.08
#Mann=3,-1,0
  4313.1    0.05       0  4990.9    0.03       0  4996.9    0.05       0
Bank Sta=4990.9,4996.9
Exp/Cntr=0.3,0.1

Type RM Length L Ch R = 1,16352,196,196,196
BEGIN DESCRIPTION:
Mapping XS 05213f9e
END DESCRIPTION:
XS GIS Cut Line= 4
      2056655.32     13520082.43      2056420.95     13520126.70
      2056051.16     13520545.97      2056170.48     13520955.79
#Sta/Elev= 30
  4319.3  549.43  4340.0  548.67  4441.7  546.69  4519.9  544.51  4557.8  543.88
  4568.3  543.36  4617.6  542.20  4624.3  541.83  4646.1  541.59  4730.6  539.32
  4738.1  539.45  4744.8  539.05  4836.8  536.72  4844.4  536.71  4865.3  535.90
  4922.2  534.80  4964.8  534.63  4997.0  533.77  4997.5  532.97  5002.5  532.97
  5003.0  533.77  5063.5  535.69  5092.0  536.05  5136.7  535.86  5183.9  536.58
  5261.7  536.91  5361.9  537.91  5417.9  538.09  5467.6  538.89  5543.7  539.08
#Mann=3,-1,0
  4319.3    0.05       0  4997.0    0.03       0  5003.0    0.05       0
Bank Sta=4997,5003
Exp/Cntr=0.3,0.1

Type RM Length L Ch R = 1,16156,327,327,327
BEGIN DESCRIPTION:
Mapping XS 6298171f
END DESCRIPTION:
XS GIS Cut Line= 4
      2056355.89     13519876.68      2056087.62     13519978.26
      2055952.20     13520519.93      2056069.38     13520824.57
#Sta/Elev= 30
  4357.3  544.87  4433.1  542.44  4505.2  540.83  4510.6  541.04  4620.5  539.15
  4682.0  538.68  4702.6  538.98  4717.5  538.68  4723.3  538.29  4743.9  538.10
  4758.7  537.36  4816.0  535.93  4857.3  535.63  4877.2  535.07  4959.7  534.57
  4997.9  533.08  4998.4  532.28  5003.4  532.28  5003.9  533.08  5042.2  534.11
  5047.3  533.88  5083.4  534.80  5088.5  534.60  5165.8  535.47  5224.1  535.43
  5333.4  536.73  5393.4  536.93  5432.9  537.54  5508.0  537.75  5528.9  538.10
#Mann=3,-1,0
  4357.3    0.05       0  4997.9    0.03       0  5003.9    0.05       0
Bank Sta=4997.9,5003.9
Exp/Cntr=0.3,0.1

Type RM Length L Ch R = 1,15829,337,337,337
BEGIN DESCRIPTION:
Mapping XS fd65fa3d
END DESCRIPTION:
XS GIS Cut Line= 4
      2055801.18     13519897.51      2055681.37     13520072.01
      2055686.58     13520585.03      2055961.30     13520828.65
#Sta/Elev= 30
  4485.9  538.02  4531.4  537.32  4554.1  537.77  4567.8  537.77  4596.0  537.21
  4610.9  536.21  4617.0  536.11  4646.8  536.11  4696.3  535.33  4720.6  535.37
  4770.6  534.63  4840.6  534.11  4900.6  532.89  4920.6  533.08  4950.6  532.90
  4960.6  532.58  4997.6  532.21  4998.1  531.41  5003.1  531.41  5003.6  532.21
  5060.6  533.14  5090.6  532.98  5140.6  533.39  5180.6  533.32  5237.5  533.78
  5259.3  534.18  5358.0  535.06  5408.2  535.77  5422.4  535.75  5577.8  538.02
#Mann=3,-1,0
  4485.9    0.05       0  4997.6    0.03       0  5003.6    0.05       0
Bank Sta=4997.6,5003.6
Exp/Cntr=0.3,0.1

Type RM Length L Ch R = 1,15492,584,584,584
BEGIN DESCRIPTION:
Mapping XS 789be39b
END DESCRIPTION:
XS GIS Cut Line= 4
      2055429.12     13520167.87      2055328.43     13520407.43
      2055529.82     13520728.61      2055713.86     13520846.66
#Sta/Elev= 30
  4498.1  532.95  4516.4  532.91  4574.8  531.99  4636.0  531.38  4668.5  531.36
  4696.0  530.91  4696.5  530.11  4701.5  530.11  4702.0  530.91  4722.7  531.09
  4733.6  531.40  4790.5  531.71  4897.7  531.56  4920.3  531.34  4934.2  531.59
  4955.8  531.43  4979.4  531.62  4991.9  531.38  5080.3  531.49  5167.0  532.24
  5180.7  532.14  5211.1  532.72  5226.3  532.93  5232.3  532.75  5253.4  533.28
  5262.0  533.26  5283.8  533.67  5289.8  533.54  5297.7  533.83  5355.7  534.57
#Mann=3,-1,0
  4498.1    0.05       0  4696.0    0.03       0  4702.0    0.05       0
Bank Sta=4696,4702
Exp/Cntr=0.3,0.1

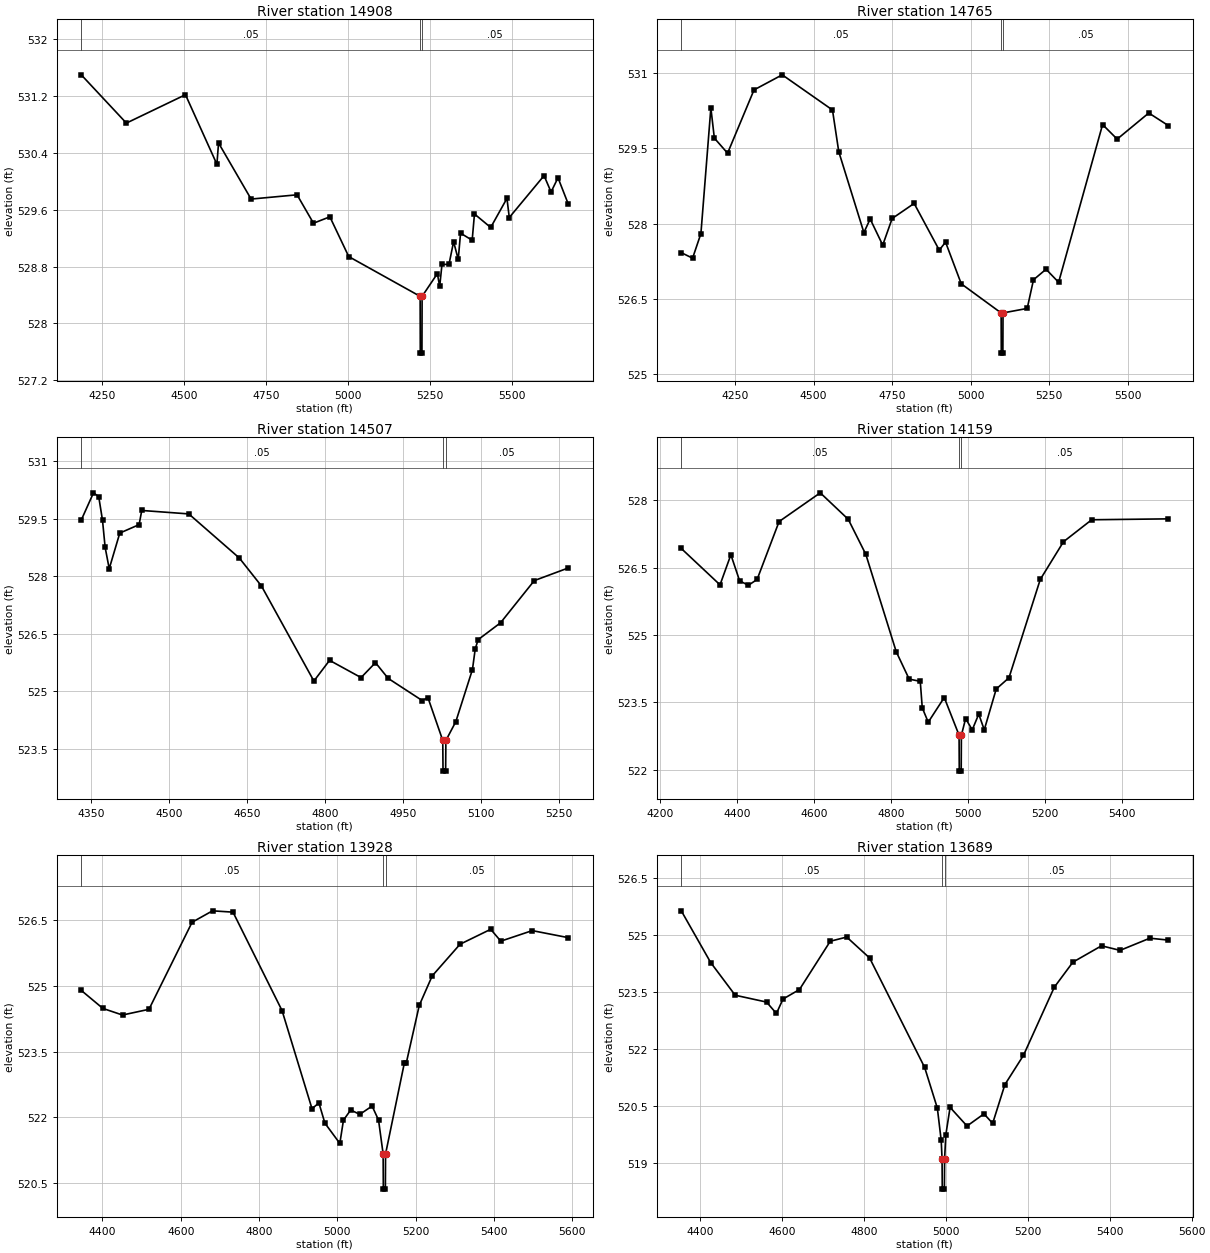
Type RM Length L Ch R = 1,14908,143,143,143
BEGIN DESCRIPTION:
Mapping XS 17d2cd71
END DESCRIPTION:
XS GIS Cut Line= 4
      2055262.46     13520317.14      2055193.02     13520429.99
      2055215.30     13521328.90      2055533.70     13521650.58
#Sta/Elev= 30
  4187.8  531.50  4325.3  530.82  4505.4  531.22  4601.2  530.24  4606.2  530.54
  4705.4  529.75  4845.5  529.81  4895.5  529.41  4945.5  529.50  5003.0  528.94
  5220.6  528.38  5221.1  527.58  5226.1  527.58  5226.6  528.38  5273.1  528.70
  5280.2  528.52  5287.2  528.83  5308.5  528.83  5322.6  529.15  5336.7  528.90
  5343.8  529.27  5379.2  529.17  5386.2  529.54  5435.7  529.35  5485.2  529.76
  5492.3  529.49  5598.3  530.08  5619.6  529.85  5640.8  530.05  5672.1  529.68
#Mann=3,-1,0
  4187.8    0.05       0  5220.6    0.03       0  5226.6    0.05       0
Bank Sta=5220.6,5226.6
Exp/Cntr=0.3,0.1

Type RM Length L Ch R = 1,14765,258,258,258
BEGIN DESCRIPTION:
Mapping XS 57017fa9
END DESCRIPTION:
XS GIS Cut Line= 4
      2055048.93     13520305.03      2055120.10     13520520.27
      2055124.16     13521646.61      2054958.53     13521754.28
#Sta/Elev= 30
  4078.7  527.42  4114.7  527.31  4141.2  527.80  4172.9  530.30  4184.0  529.70
  4226.1  529.40  4310.3  530.66  4400.1  530.96  4560.1  530.26  4580.1  529.43
  4660.1  527.82  4680.1  528.09  4720.1  527.57  4750.1  528.10  4820.1  528.40
  4900.1  527.47  4920.1  527.63  4970.1  526.80  5097.1  526.22  5097.6  525.42
  5102.6  525.42  5103.1  526.22  5180.1  526.31  5200.1  526.88  5240.1  527.09
  5280.1  526.83  5420.1  529.97  5466.5  529.68  5567.2  530.20  5629.3  529.95
#Mann=3,-1,0
  4078.7    0.05       0  5097.1    0.03       0  5103.1    0.05       0
Bank Sta=5097.1,5103.1
Exp/Cntr=0.3,0.1

Type RM Length L Ch R = 1,14507,348,348,348
BEGIN DESCRIPTION:
Mapping XS ef49a1f4
END DESCRIPTION:
XS GIS Cut Line= 4
      2054963.86     13520471.70      2054993.36     13520676.52
      2054948.23     13521011.59      2054804.11     13521376.22
#Sta/Elev= 30
  4330.5  529.46  4354.0  530.17  4364.1  530.07  4371.4  529.45  4376.4  528.75
  4384.3  528.19  4404.6  529.12  4441.8  529.34  4446.9  529.71  4537.4  529.62
  4634.6  528.47  4677.2  527.74  4778.1  525.26  4808.3  525.80  4868.9  525.35
  4896.6  525.74  4921.0  525.33  4986.7  524.75  4997.5  524.83  5026.1  523.71
  5026.6  522.91  5031.6  522.91  5032.1  523.71  5051.2  524.20  5083.2  525.56
  5088.6  526.10  5094.2  526.34  5137.3  526.78  5202.2  527.88  5267.6  528.21
#Mann=3,-1,0
  4330.5    0.05       0  5026.1    0.03       0  5032.1    0.05       0
Bank Sta=5026.1,5032.1
Exp/Cntr=0.3,0.1

Type RM Length L Ch R = 1,14159,231,231,231
BEGIN DESCRIPTION:
Mapping XS cefee682
END DESCRIPTION:
XS GIS Cut Line= 4
      2054966.50     13520294.58      2054784.86     13520381.36
      2054528.59     13521293.46      2054560.45     13521404.97
#Sta/Elev= 30
  4255.0  526.93  4355.6  526.12  4383.8  526.79  4406.5  526.21  4429.2  526.11
  4451.9  526.24  4509.0  527.53  4615.9  528.17  4688.6  527.58  4734.2  526.80
  4813.2  524.63  4846.8  524.02  4875.6  523.97  4880.8  523.38  4896.3  523.06
  4937.9  523.61  4976.4  522.77  4976.9  521.97  4981.9  521.97  4982.4  522.77
  4993.4  523.14  5010.6  522.89  5027.5  523.24  5041.8  522.89  5072.9  523.80
  5106.0  524.05  5187.2  526.24  5247.5  527.08  5320.8  527.57  5519.7  527.59
#Mann=3,-1,0
  4255.0    0.05       0  4976.4    0.03       0  4982.4    0.05       0
Bank Sta=4976.4,4982.4
Exp/Cntr=0.3,0.1

Type RM Length L Ch R = 1,13928,239,239,239
BEGIN DESCRIPTION:
Mapping XS de16e401
END DESCRIPTION:
XS GIS Cut Line= 4
      2054710.17     13520266.34      2054597.20     13520272.39
      2054308.63     13521226.87      2054349.00     13521354.03
#Sta/Elev= 30
  4346.0  524.89  4401.2  524.48  4451.3  524.33  4518.9  524.46  4629.0  526.44
  4681.2  526.70  4733.5  526.67  4858.8  524.43  4935.2  522.20  4952.9  522.33
  4968.2  521.87  5006.3  521.41  5015.6  521.94  5034.1  522.17  5057.3  522.07
  5088.7  522.26  5105.2  521.94  5116.9  521.17  5117.4  520.37  5122.6  520.37
  5123.1  521.17  5171.1  523.24  5176.3  523.25  5209.2  524.55  5242.2  525.22
  5313.3  525.94  5391.6  526.28  5417.4  526.01  5497.7  526.25  5589.7  526.09
#Mann=3,-1,0
  4346.0    0.05       0  5116.9    0.03       0  5123.1    0.05       0
Bank Sta=5116.9,5123.1
Exp/Cntr=0.3,0.1

Type RM Length L Ch R = 1,13689,164,164,164
BEGIN DESCRIPTION:
Mapping XS 8c028327
END DESCRIPTION:
XS GIS Cut Line= 4
      2054518.49     13520169.48      2054342.94     13520262.30
      2054114.91     13521121.93      2054150.61     13521217.12
#Sta/Elev= 30
  4353.3  525.64  4425.1  524.28  4485.0  523.42  4561.6  523.24  4585.7  522.94
  4601.8  523.32  4642.0  523.57  4717.2  524.84  4757.4  524.95  4813.3  524.40
  4947.8  521.52  4978.8  520.45  4988.2  519.60  4990.3  519.12  4990.8  518.32
  4996.0  518.32  4996.5  519.12  4999.5  519.75  5009.9  520.47  5051.3  519.98
  5092.7  520.30  5113.9  520.05  5143.8  521.07  5189.2  521.84  5264.4  523.63
  5309.9  524.29  5379.8  524.72  5425.1  524.60  5497.9  524.92  5542.9  524.87
#Mann=3,-1,0
  4353.3    0.05       0  4990.3    0.03       0  4996.5    0.05       0
Bank Sta=4990.3,4996.5
Exp/Cntr=0.3,0.1

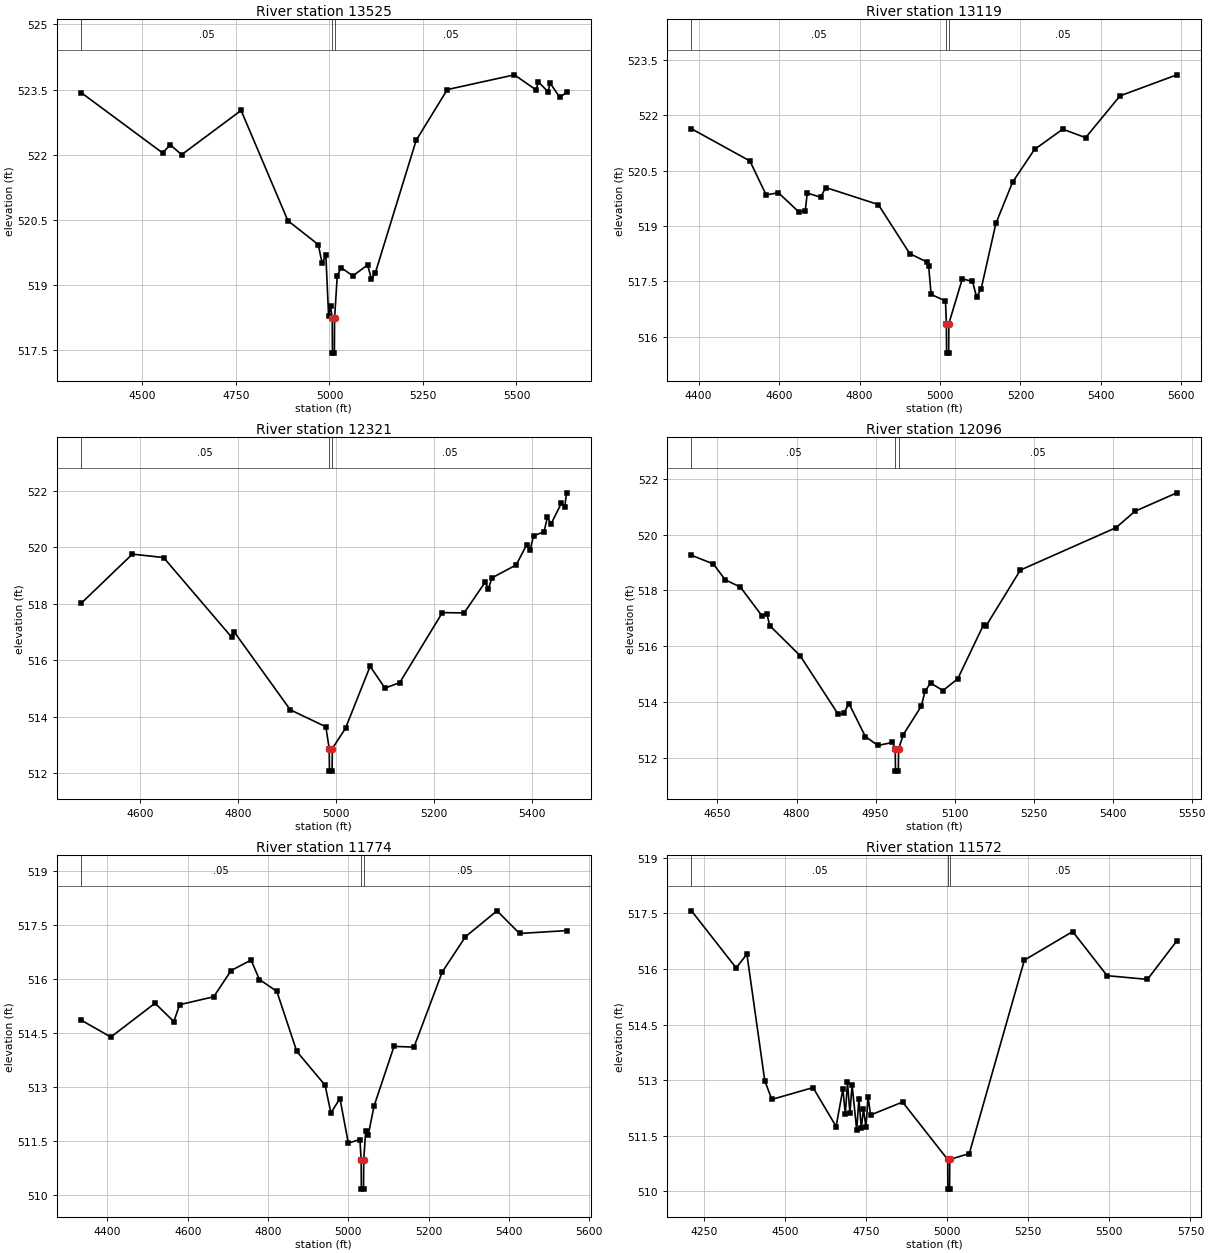
Type RM Length L Ch R = 1,13525,406,406,406
BEGIN DESCRIPTION:
Mapping XS 951a4a6d
END DESCRIPTION:
XS GIS Cut Line= 4
      2054328.81     13520167.46      2054153.25     13520173.51
      2053997.87     13521071.49      2054063.91     13521271.60
#Sta/Elev= 30
  4336.1  523.43  4553.9  522.04  4574.2  522.23  4604.6  522.00  4763.7  523.02
  4888.8  520.48  4970.0  519.93  4980.1  519.51  4990.3  519.68  4997.7  518.28
  5002.8  518.51  5007.4  518.23  5007.9  517.43  5013.1  517.43  5013.6  518.23
  5020.7  519.20  5030.8  519.40  5062.5  519.21  5101.9  519.46  5112.0  519.14
  5122.3  519.27  5231.7  522.33  5315.0  523.50  5494.5  523.84  5552.7  523.49
  5558.0  523.68  5584.4  523.45  5589.7  523.65  5616.2  523.32  5633.8  523.44
#Mann=3,-1,0
  4336.1    0.05       0  5007.4    0.03       0  5013.6    0.05       0
Bank Sta=5007.4,5013.6
Exp/Cntr=0.3,0.1

Type RM Length L Ch R = 1,13119,798,798,798
BEGIN DESCRIPTION:
Mapping XS 690ba5f7
END DESCRIPTION:
XS GIS Cut Line= 4
      2054068.01     13520192.15      2053753.78     13520245.97
      2053633.99     13520739.02      2053919.80     13520990.19
#Sta/Elev= 30
  4382.2  521.63  4527.3  520.76  4567.9  519.84  4598.3  519.90  4649.0  519.38
  4665.0  519.41  4670.0  519.89  4703.1  519.78  4716.2  520.04  4846.7  519.58
  4925.0  518.25  4966.8  518.03  4971.9  517.91  4977.9  517.15  5013.7  516.97
  5015.9  516.36  5016.4  515.56  5021.6  515.56  5022.1  516.36  5055.5  517.57
  5080.8  517.50  5091.1  517.08  5102.4  517.30  5139.0  519.07  5180.7  520.19
  5235.0  521.07  5305.2  521.62  5362.1  521.39  5447.5  522.52  5588.9  523.09
#Mann=3,-1,0
  4382.2    0.05       0  5015.9    0.03       0  5022.1    0.05       0
Bank Sta=5015.9,5022.1
Exp/Cntr=0.3,0.1

Type RM Length L Ch R = 1,12321,225,225,225
BEGIN DESCRIPTION:
Mapping XS 5369a172
END DESCRIPTION:
XS GIS Cut Line= 4
      2053059.33     13520141.81      2052892.67     13520291.11
      2052936.07     13520803.26      2053114.75     13520980.20
#Sta/Elev= 30
  4480.5  518.02  4584.8  519.76  4648.4  519.64  4787.2  516.82  4792.3  517.01
  4906.7  514.25  4979.1  513.65  4986.0  512.88  4986.5  512.08  4991.9  512.08
  4992.4  512.88  5019.3  513.60  5069.4  515.79  5099.6  515.02  5129.7  515.21
  5216.6  517.69  5261.1  517.68  5303.5  518.76  5310.6  518.54  5317.7  518.92
  5367.2  519.38  5388.4  520.09  5395.5  519.91  5402.5  520.41  5423.8  520.55
  5430.8  521.07  5437.9  520.82  5459.1  521.56  5466.2  521.44  5469.7  521.93
#Mann=3,-1,0
  4480.5    0.05       0  4986.0    0.03       0  4992.4    0.05       0
Bank Sta=4986,4992.4
Exp/Cntr=0.3,0.1

Type RM Length L Ch R = 1,12096,322,322,322
BEGIN DESCRIPTION:
Mapping XS 26e1dc5c
END DESCRIPTION:
XS GIS Cut Line= 4
      2052878.77     13520180.00      2052790.24     13520237.29
      2052663.50     13520740.76      2052857.94     13520964.70
#Sta/Elev= 30
  4600.7  519.26  4642.2  518.95  4664.7  518.38  4693.6  518.12  4734.7  517.08
  4744.0  517.15  4749.1  516.74  4806.9  515.66  4879.1  513.56  4889.4  513.59
  4899.7  513.94  4930.7  512.76  4954.7  512.44  4982.2  512.55  4987.4  512.32
  4987.9  511.52  4993.3  511.52  4993.8  512.32  5002.8  512.83  5036.9  513.85
  5044.1  514.39  5054.4  514.68  5078.0  514.41  5106.0  514.83  5155.1  516.77
  5160.2  516.74  5224.9  518.73  5406.4  520.25  5442.5  520.84  5521.9  521.50
#Mann=3,-1,0
  4600.7    0.05       0  4987.4    0.03       0  4993.8    0.05       0
Bank Sta=4987.4,4993.8
Exp/Cntr=0.3,0.1

Type RM Length L Ch R = 1,11774,202,202,202
BEGIN DESCRIPTION:
Mapping XS cb24aa03
END DESCRIPTION:
XS GIS Cut Line= 4
      2052988.85     13519947.91      2052760.74     13519956.96
      2052204.97     13520664.79      2052231.67     13520741.34
#Sta/Elev= 30
  4334.6  514.86  4408.5  514.39  4518.6  515.33  4565.4  514.82  4579.9  515.29
  4664.9  515.51  4708.2  516.24  4757.9  516.53  4778.7  515.99  4822.1  515.66
  4871.8  513.99  4942.3  513.05  4956.8  512.28  4979.4  512.68  5000.2  511.44
  5029.1  511.54  5032.2  510.96  5032.7  510.16  5038.1  510.16  5038.6  510.96
  5043.5  511.78  5049.9  511.67  5064.3  512.47  5114.1  514.13  5163.8  514.11
  5234.3  516.20  5292.1  517.18  5370.7  517.90  5426.8  517.27  5543.9  517.35
#Mann=3,-1,0
  4334.6    0.05       0  5032.2    0.03       0  5038.6    0.05       0
Bank Sta=5032.2,5038.6
Exp/Cntr=0.3,0.1

Type RM Length L Ch R = 1,11572,233,233,233
BEGIN DESCRIPTION:
Mapping XS 3a9b6980
END DESCRIPTION:
XS GIS Cut Line= 4
      2053012.35     13519721.62      2052845.83     13519732.48
      2051987.73     13520492.81      2051984.11     13520675.61
#Sta/Elev= 30
  4211.8  517.57  4349.4  516.03  4382.6  516.40  4437.6  512.99  4459.3  512.48
  4586.5  512.80  4657.6  511.75  4678.5  512.76  4686.0  512.08  4692.7  512.94
  4700.2  512.11  4706.9  512.87  4721.1  511.65  4727.8  512.50  4735.3  511.71
  4742.0  512.22  4749.6  511.73  4756.2  512.55  4763.8  512.06  4862.5  512.41
  5001.5  510.86  5002.0  510.06  5007.4  510.06  5007.9  510.86  5068.2  511.02
  5238.0  516.24  5386.9  517.01  5493.1  515.82  5617.4  515.72  5708.0  516.76
#Mann=3,-1,0
  4211.8    0.05       0  5001.5    0.03       0  5007.9    0.05       0
Bank Sta=5001.5,5007.9
Exp/Cntr=0.3,0.1

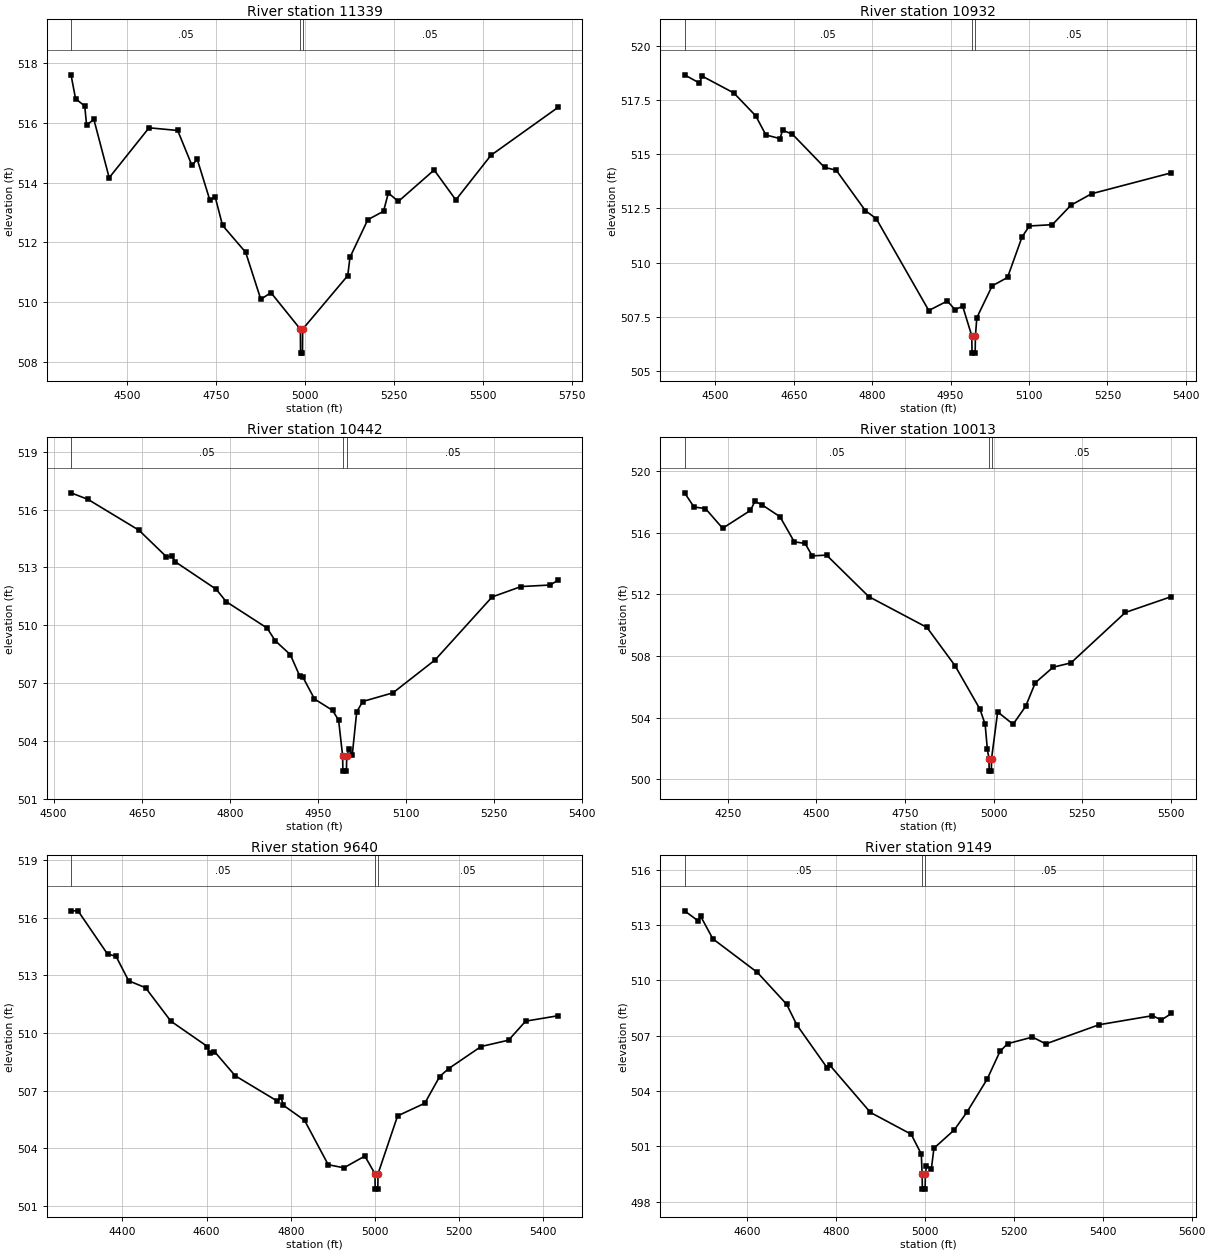
Type RM Length L Ch R = 1,11339,407,407,407
BEGIN DESCRIPTION:
Mapping XS 6256096b
END DESCRIPTION:
XS GIS Cut Line= 4
      2052786.12     13519687.21      2052507.30     13519784.98
      2051873.68     13520244.80      2051832.23     13520531.36
#Sta/Elev= 30
  4342.2  517.60  4355.0  516.80  4380.7  516.56  4386.0  515.92  4406.4  516.11
  4449.4  514.16  4561.4  515.83  4641.9  515.74  4682.0  514.57  4696.7  514.78
  4732.3  513.41  4747.0  513.53  4767.8  512.57  4832.8  511.67  4875.3  510.10
  4903.9  510.32  4986.5  509.10  4987.0  508.30  4992.4  508.30  4992.9  509.10
  5119.6  510.89  5125.8  511.50  5176.0  512.76  5220.1  513.04  5233.6  513.65
  5261.8  513.37  5362.3  514.42  5423.2  513.42  5521.8  514.91  5710.1  516.51
#Mann=3,-1,0
  4342.2    0.05       0  4986.5    0.03       0  4992.9    0.05       0
Bank Sta=4986.5,4992.9
Exp/Cntr=0.3,0.1

Type RM Length L Ch R = 1,10932,490,490,490
BEGIN DESCRIPTION:
Mapping XS 1cba6d49
END DESCRIPTION:
XS GIS Cut Line= 4
      2052387.51     13519695.63      2052097.53     13519638.33
      2051712.11     13519919.58      2051686.08     13520075.81
#Sta/Elev= 30
  4441.3  518.68  4469.8  518.30  4474.9  518.62  4535.6  517.84  4577.5  516.78
  4596.8  515.90  4623.7  515.73  4628.8  516.12  4647.7  515.93  4708.9  514.40
  4731.3  514.27  4787.0  512.40  4807.8  512.03  4908.3  507.78  4943.8  508.22
  4958.5  507.82  4973.1  507.98  4990.5  506.61  4991.0  505.81  4997.0  505.81
  4997.5  506.61  5000.2  507.45  5029.5  508.92  5058.9  509.31  5086.6  511.18
  5100.6  511.69  5144.6  511.75  5180.1  512.65  5219.5  513.18  5372.4  514.15
#Mann=3,-1,0
  4441.3    0.05       0  4990.5    0.03       0  4997.5    0.05       0
Bank Sta=4990.5,4997.5
Exp/Cntr=0.3,0.1

Type RM Length L Ch R = 1,10442,429,429,429
BEGIN DESCRIPTION:
Mapping XS c05070fb
END DESCRIPTION:
XS GIS Cut Line= 4
      2052227.78     13519419.59      2051913.50     13519306.73
      2051609.68     13519379.65      2051476.00     13519504.65
#Sta/Elev= 30
  4529.6  516.87  4558.5  516.53  4645.4  514.93  4691.9  513.56  4701.6  513.57
  4706.9  513.30  4776.9  511.87  4793.8  511.23  4863.5  509.86  4877.5  509.20
  4903.1  508.48  4919.5  507.35  4924.6  507.31  4944.3  506.18  4975.1  505.59
  4985.4  505.08  4992.2  503.24  4992.7  502.44  4998.7  502.44  4999.2  503.24
  5003.5  503.60  5008.6  503.26  5016.2  505.51  5026.5  506.05  5078.0  506.50
  5149.9  508.21  5246.8  511.47  5296.2  512.01  5346.0  512.09  5359.0  512.34
#Mann=3,-1,0
  4529.6    0.05       0  4992.2    0.03       0  4999.2    0.05       0
Bank Sta=4992.2,4999.2
Exp/Cntr=0.3,0.1

Type RM Length L Ch R = 1,10013,373,373,373
BEGIN DESCRIPTION:
Mapping XS 59d48be4
END DESCRIPTION:
XS GIS Cut Line= 4
      2052361.41     13518848.40      2051859.68     13518772.01
      2051397.88     13519122.70      2051325.25     13519401.10
#Sta/Elev= 30
  4127.5  518.58  4154.2  517.66  4186.5  517.56  4235.1  516.28  4313.6  517.44
  4326.2  518.03  4346.4  517.80  4397.0  517.03  4437.4  515.40  4467.8  515.30
  4488.0  514.49  4528.5  514.54  4647.7  511.85  4812.0  509.85  4891.0  507.38
  4961.7  504.55  4976.3  503.57  4982.6  501.95  4987.2  501.33  4987.7  500.53
  4993.9  500.53  4994.4  501.33  5011.7  504.37  5055.3  503.57  5090.7  504.73
  5118.0  506.26  5168.3  507.27  5218.7  507.55  5372.3  510.82  5502.6  511.85
#Mann=3,-1,0
  4127.5    0.05       0  4987.2    0.03       0  4994.4    0.05       0
Bank Sta=4987.2,4994.4
Exp/Cntr=0.3,0.1

Type RM Length L Ch R = 1,9640,491,491,491
BEGIN DESCRIPTION:
Mapping XS 7a290171
END DESCRIPTION:
XS GIS Cut Line= 4
      2051901.57     13518594.26      2051564.55     13518620.97
      2051074.96     13518983.81      2051037.90     13519190.55
#Sta/Elev= 30
  4277.8  516.35  4294.4  516.35  4364.6  514.10  4384.7  513.99  4414.8  512.71
  4454.9  512.35  4515.1  510.61  4602.0  509.29  4607.0  508.93  4618.7  509.03
  4668.0  507.77  4768.2  506.45  4776.6  506.65  4782.8  506.23  4832.9  505.45
  4889.2  503.14  4926.5  502.98  4976.3  503.59  5000.3  502.67  5000.9  501.87
  5007.1  501.87  5007.6  502.67  5054.1  505.68  5118.8  506.34  5154.2  507.73
  5175.4  508.14  5252.6  509.29  5317.9  509.62  5358.5  510.61  5435.3  510.89
#Mann=3,-1,0
  4277.8    0.05       0  5000.3    0.03       0  5007.6    0.05       0
Bank Sta=5000.3,5007.6
Exp/Cntr=0.3,0.1

Type RM Length L Ch R = 1,9149,555,555,555
BEGIN DESCRIPTION:
Mapping XS 442c7fe8
END DESCRIPTION:
XS GIS Cut Line= 4
      2051578.70     13518301.07      2051363.40     13518294.12
      2050882.50     13518517.65      2050873.48     13518867.81
#Sta/Elev= 30
  4458.6  513.78  4489.5  513.23  4494.5  513.50  4522.3  512.26  4622.4  510.44
  4688.4  508.71  4711.3  507.59  4779.9  505.25  4785.4  505.41  4877.0  502.84
  4968.6  501.66  4991.5  500.58  4993.3  499.48  4993.9  498.68  5000.1  498.68
  5000.6  499.48  5003.1  499.95  5014.1  499.77  5019.9  500.90  5065.6  501.89
  5094.0  502.85  5139.8  504.65  5168.5  506.15  5185.6  506.57  5241.7  506.93
  5271.7  506.56  5391.7  507.60  5511.8  508.09  5531.8  507.86  5554.6  508.21
#Mann=3,-1,0
  4458.6    0.05       0  4993.3    0.03       0  5000.6    0.05       0
Bank Sta=4993.3,5000.6
Exp/Cntr=0.3,0.1

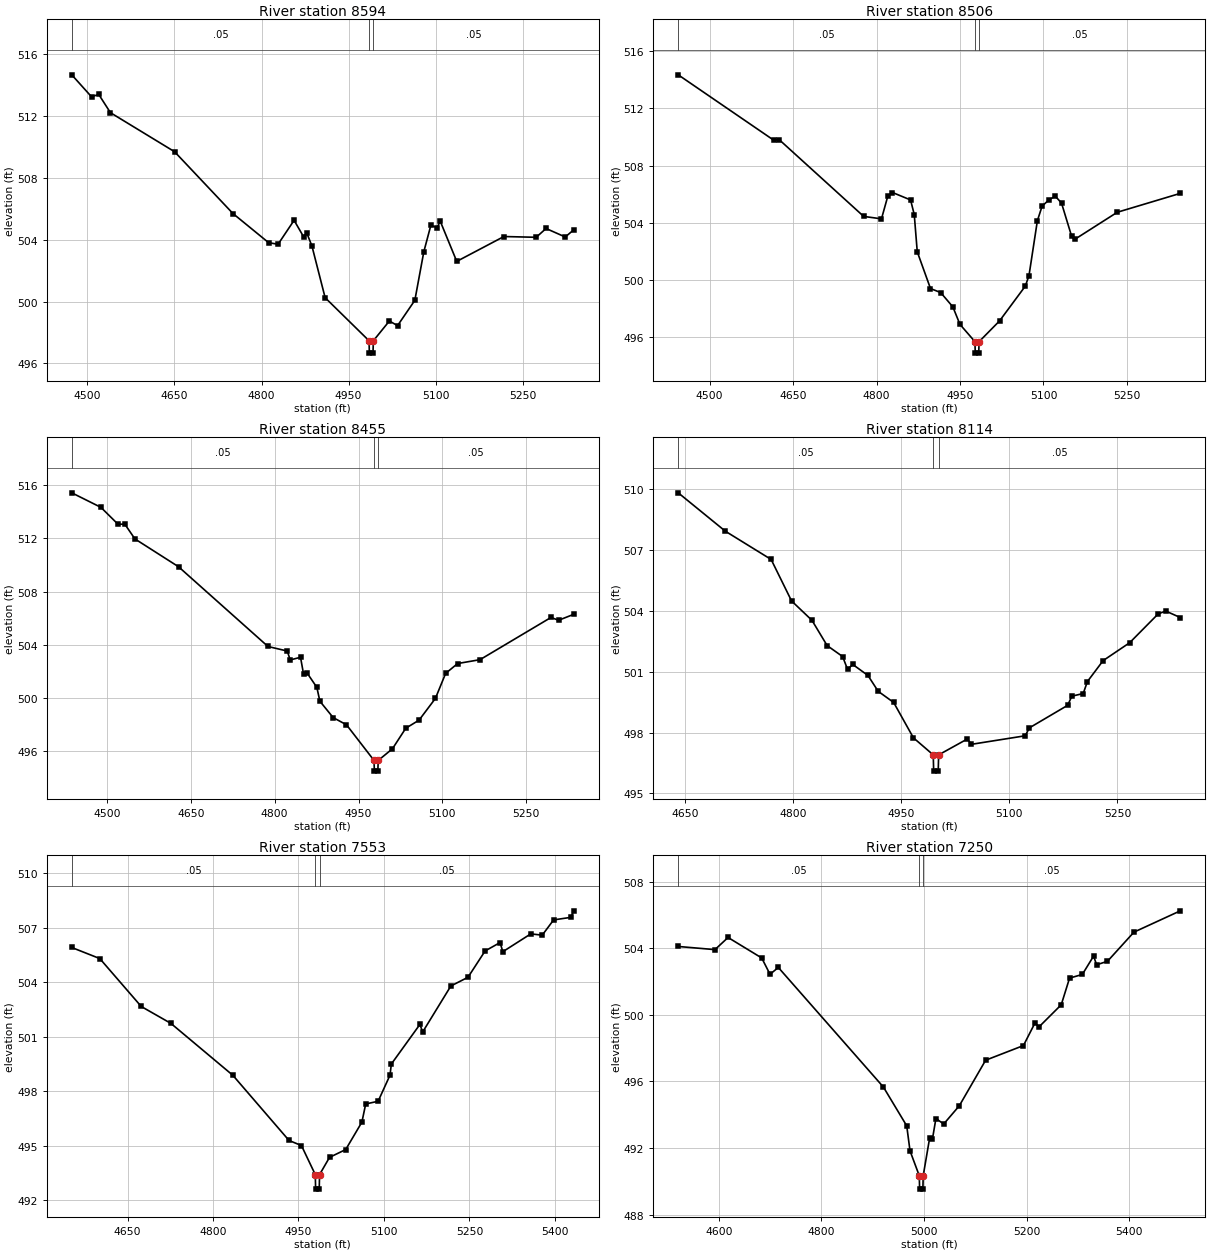
Type RM Length L Ch R = 1,8594,88,88,88
BEGIN DESCRIPTION:
Mapping XS eca009f2
END DESCRIPTION:
XS GIS Cut Line= 4
      2051191.26     13517796.32      2050864.89     13517829.30
      2050654.82     13518221.66      2050673.54     13518311.86
#Sta/Elev= 30
  4473.0  514.68  4507.0  513.26  4519.5  513.41  4539.6  512.23  4650.2  509.70
  4750.7  505.70  4812.3  503.81  4828.5  503.71  4856.1  505.26  4872.4  504.20
  4878.1  504.43  4886.9  503.59  4909.6  500.25  4985.3  497.46  4985.8  496.66
  4992.1  496.66  4992.7  497.46  5020.3  498.74  5034.4  498.44  5064.2  500.08
  5079.7  503.23  5091.8  504.94  5102.4  504.78  5108.0  505.20  5136.4  502.60
  5217.7  504.21  5273.3  504.16  5290.3  504.73  5323.4  504.18  5338.2  504.65
#Mann=3,-1,0
  4473.0    0.05       0  4985.3    0.03       0  4992.7    0.05       0
Bank Sta=4985.3,4992.7
Exp/Cntr=0.3,0.1

Type RM Length L Ch R = 1,8506,51,51,51
BEGIN DESCRIPTION:
Mapping XS 37d57561
END DESCRIPTION:
XS GIS Cut Line= 4
      2051144.38     13517711.25      2050783.30     13517766.80
      2050616.63     13518162.63      2050597.54     13518268.50
#Sta/Elev= 30
  4443.6  514.34  4615.0  509.78  4625.1  509.81  4776.9  504.45  4808.9  504.28
  4820.3  505.87  4828.7  506.12  4861.2  505.60  4867.8  504.58  4873.2  501.98
  4897.0  499.41  4915.3  499.13  4937.2  498.13  4949.9  496.91  4976.9  495.70
  4977.4  494.90  4983.7  494.90  4984.3  495.70  5021.1  497.15  5067.4  499.58
  5074.0  500.31  5089.1  504.15  5097.7  505.18  5110.8  505.63  5121.4  505.86
  5132.5  505.38  5150.6  503.07  5156.0  502.84  5232.7  504.74  5346.0  506.06
#Mann=3,-1,0
  4443.6    0.05       0  4976.9    0.03       0  4984.3    0.05       0
Bank Sta=4976.9,4984.3
Exp/Cntr=0.3,0.1

Type RM Length L Ch R = 1,8455,341,341,341
BEGIN DESCRIPTION:
Mapping XS 20777d50
END DESCRIPTION:
XS GIS Cut Line= 4
      2051094.08     13517600.13      2050746.84     13517728.61
      2050621.84     13518027.22      2050557.87     13518220.86
#Sta/Elev= 30
  4437.2  515.42  4489.3  514.33  4519.7  513.07  4532.2  513.06  4550.1  511.96
  4628.1  509.87  4788.1  503.88  4822.5  503.54  4827.9  502.87  4846.3  503.07
  4851.7  501.81  4857.7  501.91  4875.5  500.81  4880.9  499.77  4904.7  498.54
  4928.5  498.00  4977.8  495.32  4978.3  494.52  4984.6  494.52  4985.2  495.32
  5010.7  496.20  5034.5  497.74  5058.3  498.35  5087.5  499.98  5105.8  501.86
  5127.3  502.60  5167.3  502.89  5294.2  506.06  5307.9  505.85  5335.1  506.30
#Mann=3,-1,0
  4437.2    0.05       0  4977.8    0.03       0  4985.2    0.05       0
Bank Sta=4977.8,4985.2
Exp/Cntr=0.3,0.1

Type RM Length L Ch R = 1,8114,561,561,561
BEGIN DESCRIPTION:
Mapping XS b07d0e2a
END DESCRIPTION:
XS GIS Cut Line= 5
      2050685.38     13517413.11      2050450.98     13517632.32
      2050430.37     13517668.13      2050300.16     13517893.82
      2050278.46     13517964.35
#Sta/Elev= 30
  4640.7  509.80  4706.1  507.91  4769.6  506.52  4797.9  504.48  4826.3  503.52
  4847.3  502.28  4868.8  501.74  4875.6  501.11  4882.9  501.35  4903.9  500.81
  4918.1  500.03  4939.6  499.48  4967.0  497.74  4994.5  496.90  4995.1  496.10
  5001.4  496.10  5002.0  496.90  5041.7  497.68  5047.5  497.42  5122.1  497.84
  5127.9  498.23  5181.0  499.34  5186.8  499.79  5202.6  499.92  5208.4  500.51
  5230.2  501.54  5267.0  502.42  5306.6  503.84  5317.1  503.98  5337.3  503.66
#Mann=3,-1,0
  4640.7    0.05       0  4994.5    0.03       0  5002.0    0.05       0
Bank Sta=4994.5,5002
Exp/Cntr=0.3,0.1

Type RM Length L Ch R = 1,7553,303,303,303
BEGIN DESCRIPTION:
Mapping XS 9ff60ab7
END DESCRIPTION:
XS GIS Cut Line= 4
      2050382.27     13517188.67      2050133.99     13517259.86
      2049906.56     13517462.98      2049929.11     13517780.36
#Sta/Elev= 30
  4552.0  505.92  4601.2  505.31  4674.0  502.67  4726.0  501.74  4834.8  498.88
  4933.4  495.29  4955.2  495.01  4979.5  493.41  4980.1  492.61  4986.4  492.61
  4987.0  493.41  5004.5  494.36  5032.9  494.79  5061.3  496.30  5068.0  497.30
  5089.8  497.45  5110.7  498.89  5113.0  499.50  5163.1  501.68  5168.1  501.27
  5217.5  503.80  5247.6  504.28  5277.6  505.73  5303.8  506.19  5308.8  505.69
  5357.8  506.67  5377.9  506.60  5397.9  507.44  5428.0  507.58  5433.4  507.94
#Mann=3,-1,0
  4552.0    0.05       0  4979.5    0.03       0  4987.0    0.05       0
Bank Sta=4979.5,4987
Exp/Cntr=0.3,0.1

Type RM Length L Ch R = 1,7250,669,669,669
BEGIN DESCRIPTION:
Mapping XS a57992c6
END DESCRIPTION:
XS GIS Cut Line= 4
      2050026.31     13516917.84      2049929.13     13516909.16
      2049602.74     13517511.59      2049708.62     13517676.49
#Sta/Elev= 30
  4521.0  504.10  4592.6  503.91  4618.1  504.64  4683.7  503.41  4699.9  502.43
  4716.1  502.84  4920.9  495.66  4966.4  493.33  4972.8  491.83  4990.9  490.33
  4991.5  489.53  4997.9  489.53  4998.5  490.33  5010.9  492.57  5016.6  492.55
  5023.3  493.77  5038.5  493.44  5068.8  494.53  5120.2  497.27  5193.9  498.15
  5216.6  499.52  5223.9  499.26  5267.6  500.60  5283.8  502.20  5308.7  502.42
  5330.6  503.52  5336.6  503.00  5357.7  503.21  5409.3  504.96  5499.7  506.24
#Mann=3,-1,0
  4521.0    0.05       0  4990.9    0.03       0  4998.5    0.05       0
Bank Sta=4990.9,4998.5
Exp/Cntr=0.3,0.1