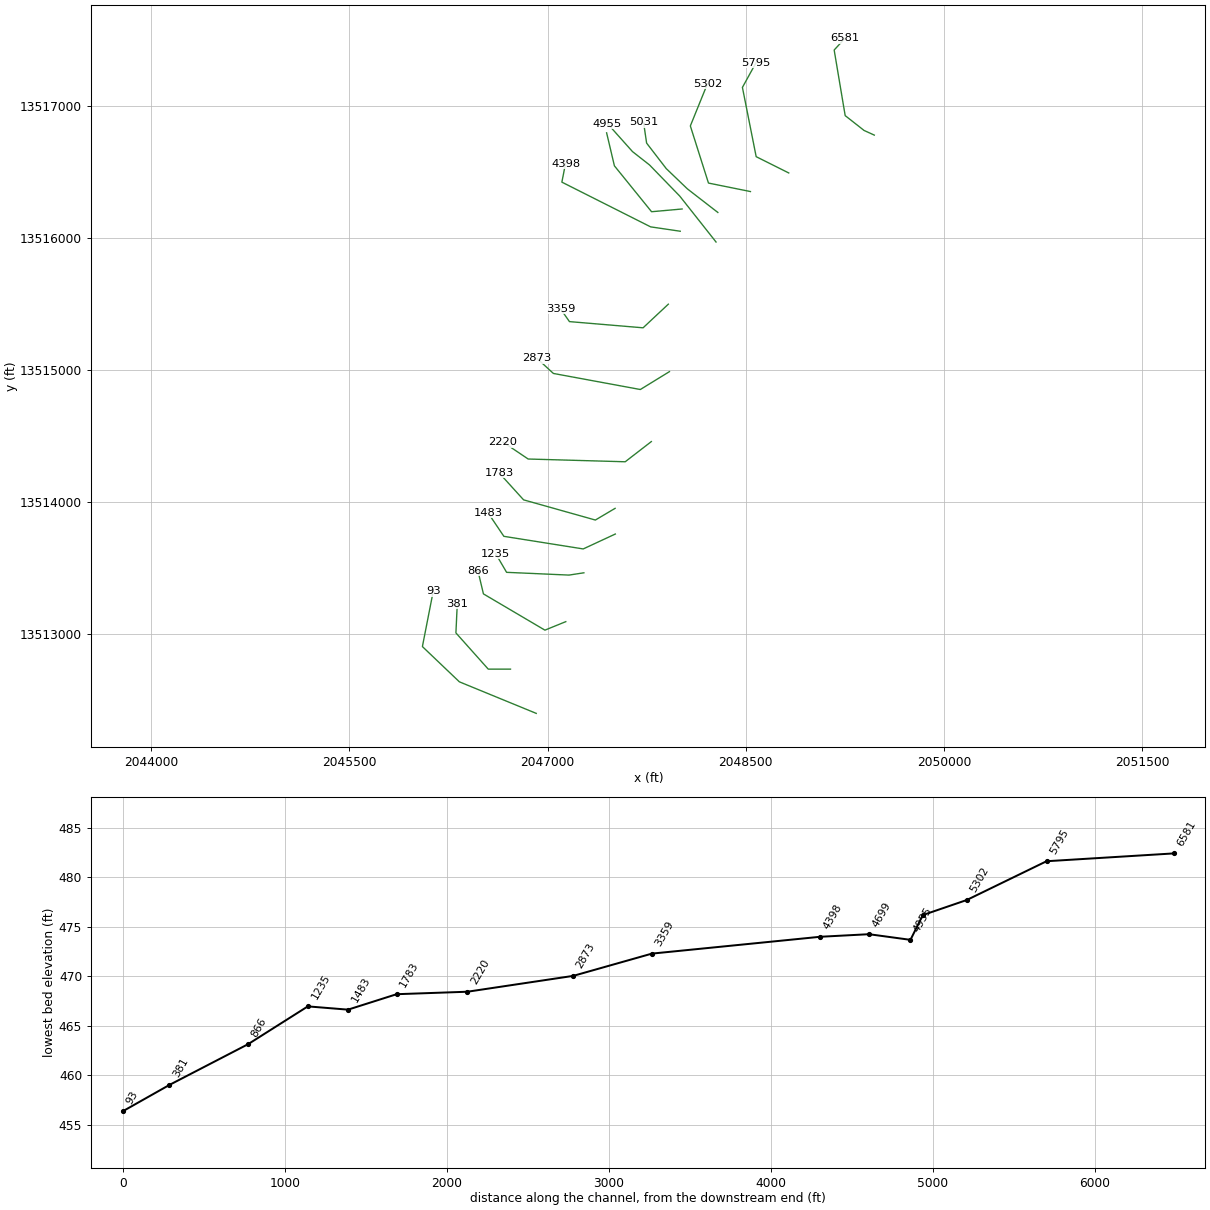
HEC-RAS study PANTHER Cr.prj: PANTHER Cr Base Level Engineering

--- PANTHER Cr.g01 (geometry) --- (continued)

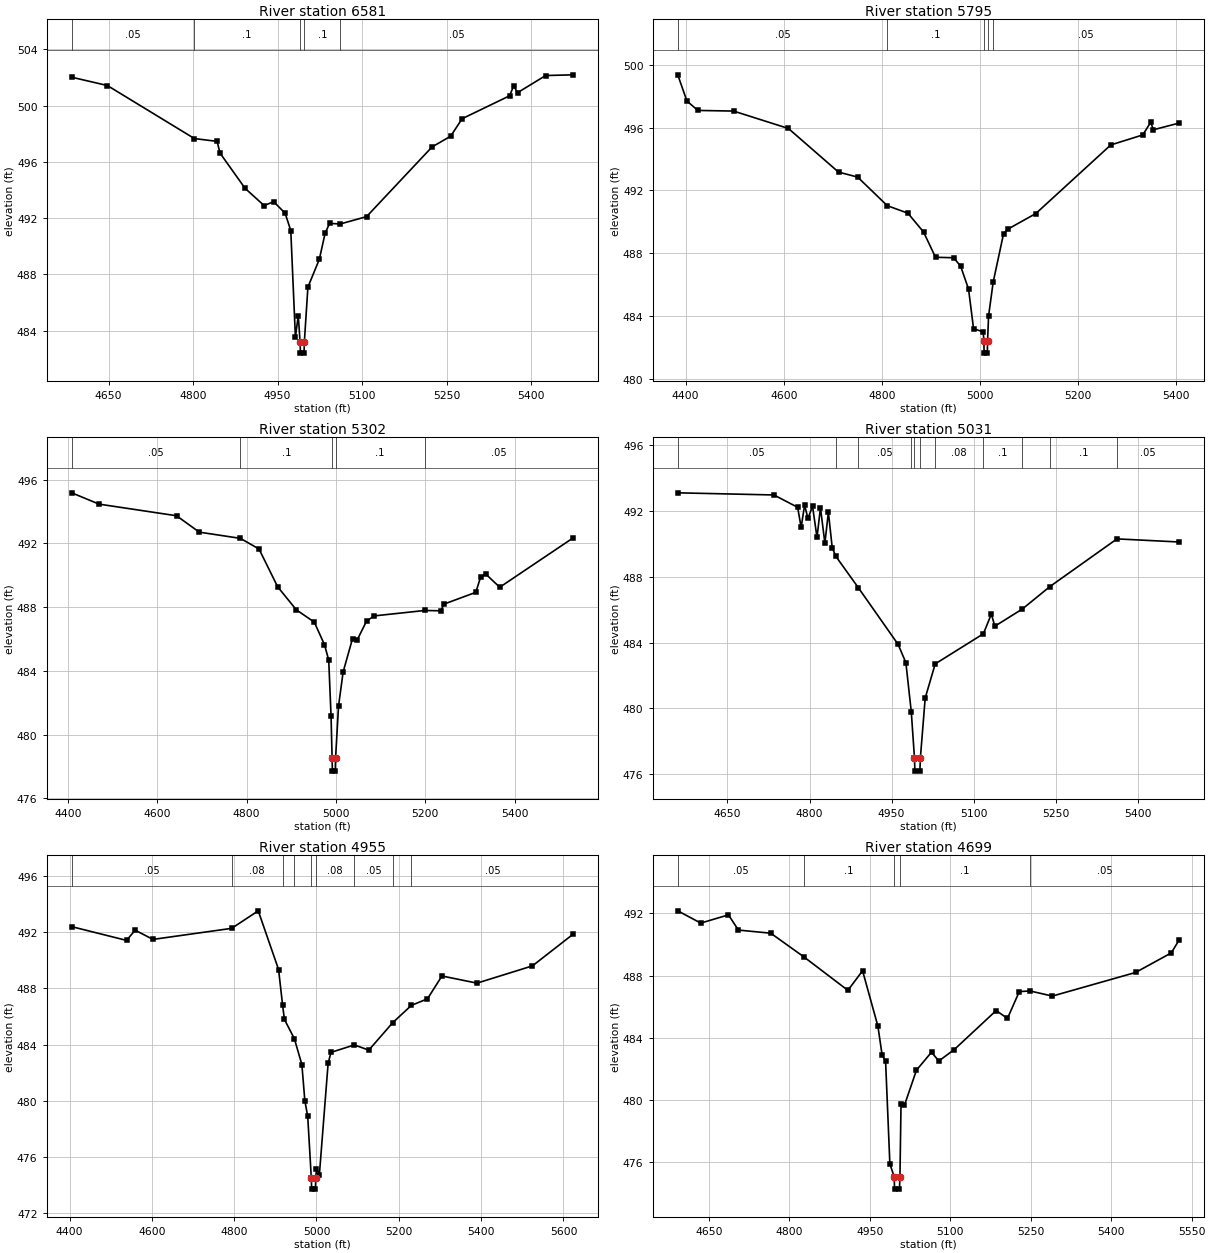
Type RM Length L Ch R = 1,6581,786,786,786
BEGIN DESCRIPTION:
Mapping XS bce0f609
END DESCRIPTION:
XS GIS Cut Line= 6
      2049472.51     13516777.22      2049392.67     13516813.68
      2049389.20     13516817.15      2049252.05     13516924.79
      2049168.71     13517421.31      2049250.17     13517509.70
#Sta/Elev= 30
  4584.5  502.02  4647.7  501.43  4802.3  497.66  4842.6  497.46  4847.7  496.63
  4892.3  494.12  4926.0  492.90  4943.0  493.17  4963.3  492.36  4973.4  491.12
  4981.6  483.55  4986.7  485.08  4989.9  483.21  4990.5  482.41  4996.9  482.41
  4997.5  483.21  5003.8  487.10  5024.1  489.08  5034.3  490.92  5042.2  491.63
  5061.2  491.59  5107.9  492.11  5224.1  497.06  5257.3  497.83  5277.6  499.07
  5361.9  500.70  5369.2  501.41  5376.0  500.92  5425.9  502.14  5475.2  502.19
#Mann=5,-1,0
  4584.5    0.05       0  4802.3     0.1       0  4989.9    0.07       0
  4997.5     0.1       0  5061.2    0.05       0
Bank Sta=4989.9,4997.5
Exp/Cntr=0.3,0.1

Type RM Length L Ch R = 1,5795,493,493,493
BEGIN DESCRIPTION:
Mapping XS 2e6236f2
END DESCRIPTION:
XS GIS Cut Line= 4
      2048824.93     13516490.77      2048578.43     13516614.02
      2048474.27     13517138.33      2048576.71     13517324.11
#Sta/Elev= 30
  4384.1  499.36  4402.8  497.69  4425.1  497.09  4497.8  497.05  4609.6  495.94
  4711.7  493.16  4750.8  492.84  4811.0  491.02  4853.1  490.54  4885.0  489.34
  4909.4  487.73  4946.2  487.70  4960.5  487.17  4976.7  485.70  4986.9  483.18
  5006.6  482.97  5007.8  482.42  5008.5  481.62  5014.9  481.62  5015.5  482.42
  5017.5  483.98  5026.9  486.15  5048.1  489.24  5057.7  489.54  5113.9  490.52
  5266.5  494.89  5331.8  495.53  5347.8  496.33  5353.6  495.86  5406.4  496.29
#Mann=5,-1,0
  4384.1    0.05       0  4811.0     0.1       0  5007.8    0.07       0
  5015.5     0.1       0  5026.9    0.05       0
Bank Sta=5007.8,5015.5
Exp/Cntr=0.3,0.1

Type RM Length L Ch R = 1,5302,271,271,271
BEGIN DESCRIPTION:
Mapping XS 3729daf3
END DESCRIPTION:
XS GIS Cut Line= 4
      2048535.03     13516350.13      2048217.32     13516414.37
      2048080.17     13516846.66      2048210.18     13517167.35
#Sta/Elev= 30
  4408.2  495.18  4469.4  494.47  4642.9  493.74  4693.9  492.71  4786.0  492.32
  4827.7  491.65  4869.4  489.28  4911.3  487.83  4951.5  487.06  4974.3  485.64
  4983.8  484.68  4989.0  481.19  4991.4  478.50  4992.0  477.70  4998.5  477.70
  4999.1  478.50  5005.8  481.79  5016.1  483.93  5037.2  486.03  5047.7  485.95
  5068.7  487.13  5085.8  487.45  5198.9  487.79  5235.6  487.77  5241.0  488.18
  5313.3  488.93  5324.3  489.91  5335.1  490.09  5366.9  489.25  5531.9  492.36
#Mann=5,-1,0
  4408.2    0.05       0  4786.0     0.1       0  4991.4    0.07       0
  4999.1     0.1       0  5198.9    0.05       0
Bank Sta=4991.4,4999.1
Exp/Cntr=0.3,0.1

Type RM Length L Ch R = 1,5031,76,76,76
BEGIN DESCRIPTION:
Mapping XS 4b04a73c
END DESCRIPTION:
XS GIS Cut Line= 5
      2048288.33     13516191.89      2048057.87     13516370.27
      2047897.71     13516523.91      2047749.27     13516716.62
      2047725.83     13516875.48
#Sta/Elev= 30
  4559.1  493.10  4734.9  492.97  4778.3  492.22  4784.7  491.00  4791.0  492.35
  4797.2  491.54  4805.5  492.29  4813.7  490.39  4820.0  492.19  4828.1  490.04
  4834.5  491.92  4841.5  489.77  4847.9  489.25  4889.3  487.33  4962.1  483.88
  4976.2  482.77  4986.1  479.78  4991.9  476.98  4992.7  476.18  5001.8  476.18
  5002.7  476.98  5011.5  480.62  5029.8  482.70  5117.9  484.53  5132.5  485.73
  5138.8  484.99  5189.3  486.04  5239.5  487.40  5362.2  490.30  5476.3  490.11
#Mann=11,-1,0
  4559.1    0.05       0  4847.9     0.1       0  4889.3    0.05       0
  4986.1     0.1       0  4991.9    0.07       0  5002.7     0.1       0
  5029.8    0.08       0  5117.9     0.1       0  5189.3    0.08       0
  5239.5     0.1       0  5362.2    0.05       0
Bank Sta=4991.9,5002.7
Exp/Cntr=0.3,0.1

Type RM Length L Ch R = 1,4955,256,256,256
BEGIN DESCRIPTION:
Mapping XS 8f92675f
END DESCRIPTION:
XS GIS Cut Line= 5
      2048274.63     13515968.17      2048000.31     13516315.41
      2047771.14     13516551.52      2047642.67     13516652.22
      2047453.45     13516864.01
#Sta/Elev= 30
  4405.4  492.41  4538.5  491.43  4559.4  492.16  4602.7  491.50  4794.0  492.29
  4858.5  493.54  4907.9  489.35  4917.5  486.85  4922.1  485.79  4946.2  484.42
  4964.5  482.57  4971.7  479.99  4978.7  478.87  4987.4  474.48  4988.3  473.68
  4997.4  473.68  4998.2  474.48  5000.0  475.13  5007.0  474.70  5028.3  482.67
  5035.3  483.44  5092.0  483.97  5127.1  483.60  5185.3  485.56  5230.4  486.79
  5269.6  487.26  5304.8  488.89  5390.0  488.38  5524.6  489.61  5624.2  491.89
#Mann=9,-1,0
  4405.4    0.05       0  4794.0    0.08       0  4917.5    0.05       0
  4946.2    0.08       0  4987.4    0.07       0  4998.2    0.08       0
  5092.0    0.05       0  5185.3    0.08       0  5230.4    0.05       0
Bank Sta=4987.4,4998.2
Exp/Cntr=0.3,0.1

Type RM Length L Ch R = 1,4699,301,301,301
BEGIN DESCRIPTION:
Mapping XS 15bf0bd3
END DESCRIPTION:
XS GIS Cut Line= 4
      2048017.69     13516218.19      2047786.77     13516197.36
      2047505.52     13516544.58      2047446.48     13516794.60
#Sta/Elev= 30
  4591.6  492.17  4634.5  491.38  4686.2  491.91  4704.7  490.93  4765.0  490.73
  4826.6  489.21  4908.9  487.05  4936.3  488.31  4964.9  484.74  4972.8  482.87
  4979.2  482.50  4987.2  475.88  4995.2  475.05  4996.0  474.25  5005.1  474.25
  5006.0  475.05  5008.0  479.72  5014.4  479.65  5036.8  481.91  5064.9  483.07
  5078.4  482.50  5107.1  483.23  5185.5  485.75  5206.5  485.24  5228.6  486.97
  5248.7  487.01  5290.2  486.68  5445.4  488.20  5512.0  489.46  5527.2  490.32
#Mann=5,-1,0
  4591.6    0.05       0  4826.6     0.1       0  4995.2    0.07       0
  5006.0     0.1       0  5248.7    0.05       0
Bank Sta=4995.2,5006
Exp/Cntr=0.3,0.1

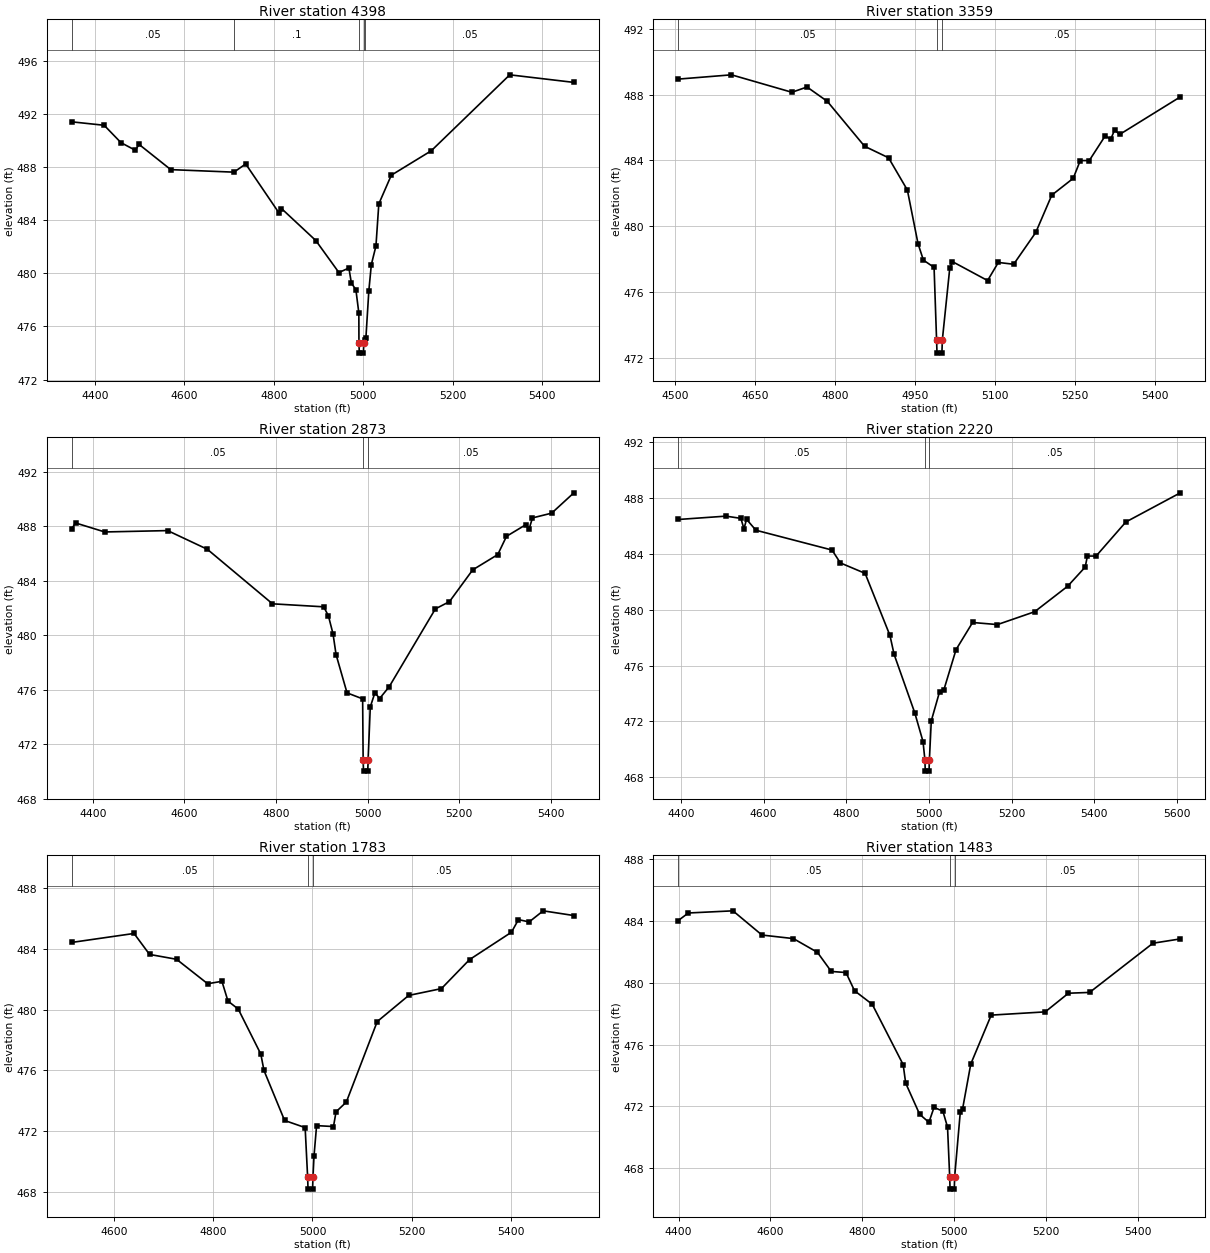
Type RM Length L Ch R = 1,4398,1039,1039,1039
BEGIN DESCRIPTION:
Mapping XS 79e41604
END DESCRIPTION:
XS GIS Cut Line= 4
      2048003.80     13516049.78      2047779.82     13516082.77
      2047107.95     13516421.31      2047135.36     13516561.82
#Sta/Elev= 30
  4348.6  491.41  4421.0  491.15  4458.6  489.84  4490.6  489.27  4499.0  489.71
  4569.8  487.81  4711.1  487.62  4737.2  488.24  4811.6  484.55  4817.2  484.88
  4893.9  482.47  4945.5  480.06  4967.8  480.40  4973.4  479.27  4983.5  478.76
  4990.1  477.00  4990.3  474.79  4991.1  473.99  5000.3  473.99  5001.1  474.79
  5003.6  474.98  5005.9  475.16  5012.4  478.69  5018.0  480.66  5028.3  482.06
  5034.7  485.23  5062.6  487.39  5151.9  489.23  5327.3  494.95  5470.5  494.38
#Mann=5,-1,0
  4348.6    0.05       0  4711.1     0.1       0  4990.3    0.07       0
  5001.1     0.1       0  5003.6    0.05       0
Bank Sta=4990.3,5001.1
Exp/Cntr=0.3,0.1

Type RM Length L Ch R = 1,3359,486,486,486
BEGIN DESCRIPTION:
Mapping XS 06e46c85
END DESCRIPTION:
XS GIS Cut Line= 4
      2047913.52     13515497.72      2047722.53     13515318.88
      2047165.24     13515365.76      2047095.80     13515464.72
#Sta/Elev= 30
  4505.8  488.94  4605.7  489.20  4719.0  488.14  4747.4  488.46  4785.4  487.59
  4855.3  484.86  4900.3  484.16  4935.6  482.20  4955.6  478.94  4965.7  477.94
  4985.7  477.50  4990.4  473.09  4991.2  472.29  5000.4  472.29  5001.2  473.09
  5015.1  477.44  5020.1  477.85  5086.1  476.70  5106.2  477.80  5135.0  477.69
  5176.4  479.62  5206.5  481.89  5246.7  482.91  5259.9  483.99  5276.8  483.99
  5306.9  485.50  5316.9  485.28  5324.3  485.84  5333.9  485.58  5447.6  487.86
#Mann=3,-1,0
  4505.8    0.05       0  4990.4    0.03       0  5001.2    0.05       0
Bank Sta=4990.4,5001.2
Exp/Cntr=0.3,0.1

Type RM Length L Ch R = 1,2873,653,653,653
BEGIN DESCRIPTION:
Mapping XS 477a23fc
END DESCRIPTION:
XS GIS Cut Line= 4
      2047922.19     13514987.29      2047701.70     13514851.87
      2047043.71     13514973.40      2046919.33     13515087.41
#Sta/Elev= 30
  4353.9  487.82  4362.2  488.24  4426.0  487.58  4563.3  487.68  4650.0  486.31
  4792.3  482.31  4904.2  482.09  4914.4  481.43  4924.5  480.11  4931.2  478.58
  4955.1  475.78  4989.2  475.34  4990.3  470.84  4991.1  470.04  5000.3  470.04
  5001.1  470.84  5005.9  474.75  5016.1  475.80  5026.2  475.36  5047.2  476.23
  5148.1  481.94  5178.8  482.47  5229.6  484.80  5284.3  485.92  5303.4  487.26
  5345.9  488.12  5352.7  487.79  5360.1  488.61  5402.1  488.96  5450.5  490.45
#Mann=3,-1,0
  4353.9    0.05       0  4990.3    0.03       0  5001.1    0.05       0
Bank Sta=4990.3,5001.1
Exp/Cntr=0.3,0.1

Type RM Length L Ch R = 1,2220,437,437,437
BEGIN DESCRIPTION:
Mapping XS eeb93258
END DESCRIPTION:
XS GIS Cut Line= 4
      2047785.04     13514457.78      2047587.11     13514304.99
      2046852.74     13514325.83      2046661.75     13514454.31
#Sta/Elev= 30
  4393.5  486.47  4509.0  486.71  4545.1  486.55  4552.5  485.80  4558.8  486.48
  4581.5  485.70  4765.7  484.28  4785.7  483.36  4845.7  482.61  4905.8  478.16
  4915.8  476.81  4965.8  472.62  4985.8  470.56  4990.4  469.24  4991.2  468.44
  5000.4  468.44  5001.2  469.24  5005.8  472.04  5025.8  474.12  5035.8  474.22
  5065.8  477.15  5105.8  479.09  5165.9  478.94  5255.9  479.86  5335.9  481.69
  5378.2  483.06  5383.6  483.85  5404.6  483.85  5476.6  486.29  5608.4  488.38
#Mann=3,-1,0
  4393.5    0.05       0  4990.4    0.03       0  5001.2    0.05       0
Bank Sta=4990.4,5001.2
Exp/Cntr=0.3,0.1

Type RM Length L Ch R = 1,1783,300,300,300
BEGIN DESCRIPTION:
Mapping XS 4f2c0f02
END DESCRIPTION:
XS GIS Cut Line= 4
      2047510.76     13513952.58      2047361.42     13513864.02
      2046818.02     13514016.80      2046633.02     13514220.82
#Sta/Elev= 30
  4514.1  484.43  4639.8  485.02  4671.1  483.64  4725.6  483.32  4788.4  481.71
  4817.2  481.87  4829.4  480.57  4850.2  480.04  4895.7  477.08  4902.1  476.00
  4943.7  472.71  4985.2  472.24  4990.2  468.99  4991.0  468.19  5000.2  468.19
  5001.0  468.99  5003.1  470.38  5008.3  472.37  5042.4  472.31  5047.6  473.28
  5068.3  473.92  5130.7  479.22  5194.2  480.94  5260.3  481.39  5317.1  483.30
  5401.6  485.10  5415.8  485.93  5437.4  485.78  5465.7  486.51  5527.6  486.20
#Mann=3,-1,0
  4514.1    0.05       0  4990.2    0.03       0  5001.0    0.05       0
Bank Sta=4990.2,5001
Exp/Cntr=0.3,0.1

Type RM Length L Ch R = 1,1483,248,248,248
BEGIN DESCRIPTION:
Mapping XS e4a6889e
END DESCRIPTION:
XS GIS Cut Line= 4
      2047512.45     13513758.12      2047269.41     13513645.27
      2046668.71     13513740.76      2046547.60     13513920.69
#Sta/Elev= 30
  4399.3  484.04  4421.3  484.53  4518.4  484.67  4581.6  483.10  4650.1  482.87
  4702.3  481.98  4732.5  480.74  4764.5  480.67  4783.1  479.49  4821.7  478.61
  4889.0  474.70  4894.5  473.50  4924.9  471.48  4945.1  470.96  4956.2  471.93
  4975.5  471.68  4985.6  470.65  4990.3  467.43  4991.1  466.63  5000.3  466.63
  5001.1  467.43  5013.4  471.63  5018.5  471.85  5036.2  474.74  5080.7  477.91
  5198.3  478.12  5248.9  479.33  5294.9  479.38  5432.8  482.57  5492.4  482.85
#Mann=3,-1,0
  4399.3    0.05       0  4990.3    0.03       0  5001.1    0.05       0
Bank Sta=4990.3,5001.1
Exp/Cntr=0.3,0.1

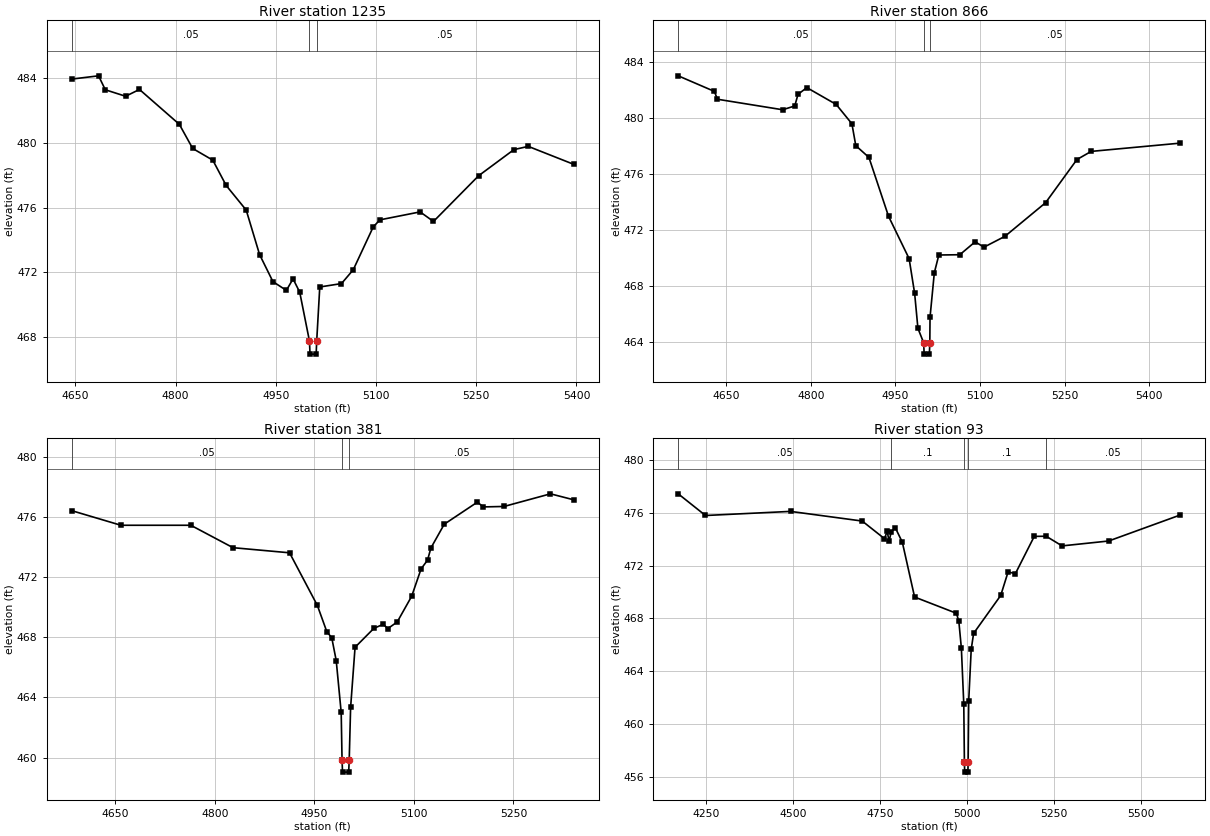
Type RM Length L Ch R = 1,1235,369,369,369
BEGIN DESCRIPTION:
Mapping XS 65d342eb
END DESCRIPTION:
XS GIS Cut Line= 4
      2047274.64     13513464.72      2047161.77     13513447.36
      2046689.55     13513468.19      2046606.38     13513610.26
#Sta/Elev= 30
  4644.6  483.92  4684.7  484.12  4694.8  483.26  4725.2  482.86  4745.9  483.28
  4805.6  481.13  4825.6  479.64  4855.7  478.92  4875.7  477.36  4905.7  475.84
  4925.7  473.10  4945.7  471.43  4965.8  470.89  4975.8  471.60  4985.8  470.78
  5000.4  467.76  5001.2  466.96  5010.4  466.96  5011.2  467.76  5015.8  471.10
  5048.3  471.31  5065.9  472.16  5095.9  474.81  5105.9  475.24  5166.0  475.73
  5186.0  475.14  5253.6  477.96  5306.4  479.57  5327.9  479.77  5396.1  478.66
#Mann=3,-1,0
  4644.6    0.05       0  5000.4    0.03       0  5011.2    0.05       0
Bank Sta=5000.4,5011.2
Exp/Cntr=0.3,0.1

Type RM Length L Ch R = 1,866,485,485,485
BEGIN DESCRIPTION:
Mapping XS 2c2ec97c
END DESCRIPTION:
XS GIS Cut Line= 4
      2047137.46     13513094.93      2046979.48     13513030.69
      2046514.20     13513304.99      2046472.58     13513480.15
#Sta/Elev= 30
  4564.7  482.99  4628.8  481.88  4634.2  481.32  4749.9  480.57  4771.4  480.84
  4777.2  481.67  4792.8  482.15  4844.9  480.95  4872.8  479.57  4879.7  478.01
  4903.0  477.17  4937.8  472.97  4974.3  469.95  4984.1  467.47  4989.9  464.98
  5000.2  463.94  5000.9  463.14  5010.2  463.14  5011.0  463.94  5011.4  465.77
  5019.0  468.94  5027.0  470.21  5064.2  470.23  5091.4  471.15  5107.1  470.77
  5144.2  471.54  5216.4  473.94  5272.0  477.02  5297.3  477.60  5455.4  478.19
#Mann=3,-1,0
  4564.7    0.05       0  5000.2    0.03       0  5011.0    0.05       0
Bank Sta=5000.2,5011
Exp/Cntr=0.3,0.1

Type RM Length L Ch R = 1,381,288,288,288
BEGIN DESCRIPTION:
Mapping XS c2a79ab4
END DESCRIPTION:
XS GIS Cut Line= 4
      2046719.09     13512735.55      2046550.66     13512735.55
      2046305.86     13513009.86      2046316.27     13513230.13
#Sta/Elev= 30
  4584.5  476.41  4658.6  475.44  4763.9  475.44  4827.5  473.95  4912.7  473.61
  4954.6  470.11  4968.8  468.37  4976.3  467.96  4983.0  466.45  4990.5  463.00
  4991.8  459.83  4992.5  459.03  5001.8  459.03  5002.6  459.83  5004.7  463.33
  5011.4  467.33  5039.8  468.59  5054.0  468.86  5060.7  468.57  5074.9  469.01
  5096.7  470.72  5110.9  472.54  5120.6  473.12  5125.7  473.93  5145.8  475.51
  5195.8  476.98  5204.5  476.66  5235.9  476.69  5305.9  477.53  5341.1  477.13
#Mann=3,-1,0
  4584.5    0.05       0  4991.8    0.03       0  5002.6    0.05       0
Bank Sta=4991.8,5002.6
Exp/Cntr=0.3,0.1

Type RM Length L Ch R = 1,93,0,0,0
BEGIN DESCRIPTION:
PANTHER Cr 1.0
END DESCRIPTION:
XS GIS Cut Line= 4
      2046913.77     13512400.73      2046332.20     13512639.43
      2046052.25     13512906.36      2046134.72     13513327.39
#Sta/Elev= 30
  4168.7  477.43  4247.1  475.79  4491.7  476.10  4698.0  475.37  4761.9  474.04
  4769.9  474.59  4775.3  473.84  4781.3  474.53  4793.1  474.87  4813.4  473.77
  4848.7  469.62  4969.1  468.39  4976.0  467.78  4983.3  465.75  4990.2  461.54
  4992.0  457.17  4992.8  456.37  5002.1  456.37  5002.8  457.17  5004.4  461.75
  5011.6  465.66  5018.5  466.87  5096.5  469.74  5117.6  471.51  5138.9  471.40
  5193.0  474.21  5227.3  474.22  5273.0  473.49  5407.0  473.86  5613.2  475.83
#Mann=5,-1,0
  4168.7    0.05       0  4781.3     0.1       0  4992.0    0.07       0
  5002.8     0.1       0  5227.3    0.05       0
Bank Sta=4992,5002.8
Exp/Cntr=0.3,0.1

Chan Stop Cuts=-1