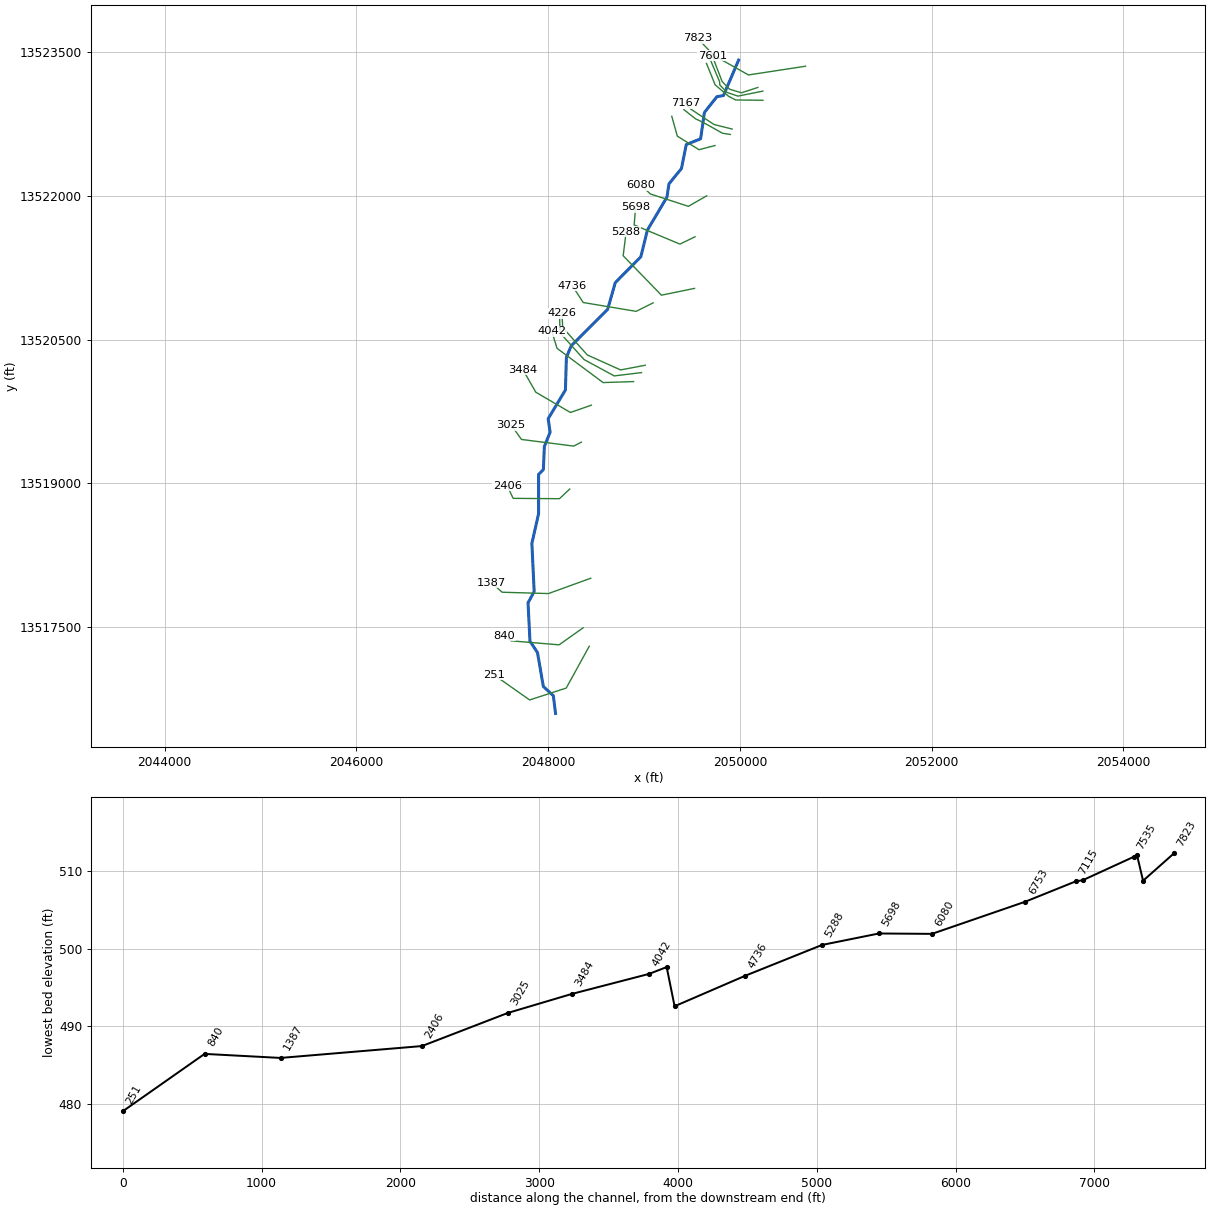
--- UNT 1 in Lagunillas Cr Wtrshd.prj (project) ---

Proj Title=UNT 1 in Lagunillas Cr Wtrshd Base Level Engineering
Current Plan=p01
Default Exp/Contr=0.3,0.1
English Units
Geom File=g01
Flow File=f01
Plan File=p01
BEGIN DESCRIPTION:
UNT 1 in Lagunillas Cr Wtrshd
END DESCRIPTION:

--- UNT 1 in Lagunillas Cr Wtrshd.p01 (plan) ---

Plan Title=Multiple Run
Short Identifier=Multiple
Geom File=g01
Flow File=f01
Subcritical Flow
K Sum by GR= 0
Std Step Tol= 0.01
Critical Tol= 0.01
Num of Std Step Trials= 20
Max Error Tol= 0.3
Flow Tol Ratio= 0.001
Split Flow NTrial= 30
Split Flow Tol= 0.02
Split Flow Ratio= 0.02
Log Output Level= 0
Friction Slope Method= 1
Unsteady Friction Slope Method= 2
Unsteady Bridges Friction Slope Method= 1
Parabolic Critical Depth
Global Vel Dist=  1 , 1 , 1
Global Log Level= 0
CheckData=True
Encroach Param= -1, 0, 0, 0
BEGIN DESCRIPTION:
Multiple Run
END DESCRIPTION:

--- UNT 1 in Lagunillas Cr Wtrshd.f01 (steady flow) ---

Flow Title=Multiple
Number of Profiles=7
Profile Names=10-year,25-year,50-year,1pct_min,100-year,1pct_plu,500-year
River Rch & RM= UNT 1 in Lagunil,Reach-1,7823
     131     174     208     124     248     495     358
River Rch & RM= UNT 1 in Lagunil,Reach-1,5698
     224     307     376     229     458     914     689
River Rch & RM= UNT 1 in Lagunil,Reach-1,4736
     389     547     679     420     838    1672    1295
Boundary for River Rch & Prof#=UNT 1 in Lagunil,Reach-1,1
Up Type=0
Dn Type=3
Dn Slope=0.005
Boundary for River Rch & Prof#=UNT 1 in Lagunil,Reach-1,2
Up Type=0
Dn Type=3
Dn Slope=0.005
Boundary for River Rch & Prof#=UNT 1 in Lagunil,Reach-1,3
Up Type=0
Dn Type=3
Dn Slope=0.005
Boundary for River Rch & Prof#=UNT 1 in Lagunil,Reach-1,4
Up Type=0
Dn Type=3
Dn Slope=0.005
Boundary for River Rch & Prof#=UNT 1 in Lagunil,Reach-1,5
Up Type=0
Dn Type=3
Dn Slope=0.005
Boundary for River Rch & Prof#=UNT 1 in Lagunil,Reach-1,6
Up Type=0
Dn Type=3
Dn Slope=0.005
Boundary for River Rch & Prof#=UNT 1 in Lagunil,Reach-1,7
Up Type=0
Dn Type=3
Dn Slope=0.005

--- UNT 1 in Lagunillas Cr Wtrshd.g01 (geometry) ---

Geom Title=Existing Conditions

River Reach=UNT 1 in Lagunil,Reach-1
Reach XY= 30
      2049987.21     13523415.93      2049829.23     13523046.14
      2049760.80     13523034.54      2049630.44     13522869.06
      2049590.80     13522594.54      2049440.80     13522534.54
      2049390.80     13522284.54      2049260.80     13522124.54
      2049239.82     13521986.25      2049035.82     13521642.50
      2048967.25     13521363.85      2048700.80     13521094.54
      2048620.80     13520814.54      2048240.80     13520434.54
      2048190.80     13520314.54      2048180.80     13519974.54
      2048000.80     13519674.54      2048020.80     13519534.54
      2047960.80     13519384.54      2047950.80     13519144.54
      2047900.80     13519094.54      2047900.80     13518684.54
      2047830.80     13518374.54      2047854.63     13517871.57
      2047790.80     13517754.54      2047810.80     13517354.54
      2047889.29     13517235.40      2047950.40     13516881.23
      2048054.57     13516786.09      2048077.52     13516601.26

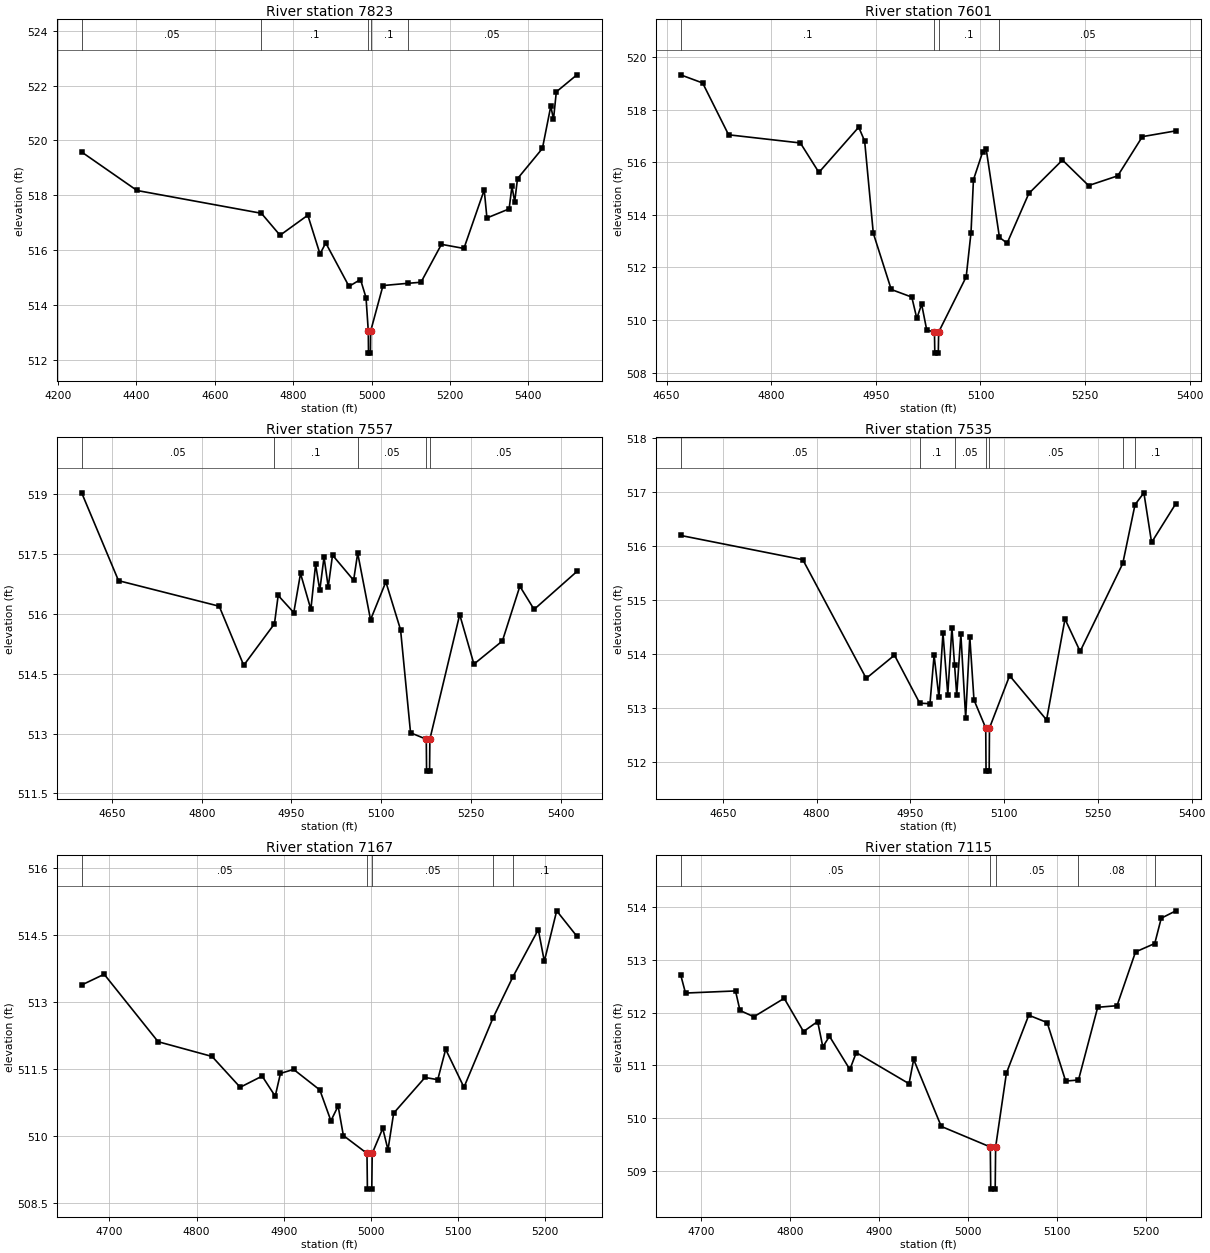
Type RM Length L Ch R = 1,7823,222,222,222
BEGIN DESCRIPTION:
UNT 1 in Lagunillas Cr Wtrshd 18.0
END DESCRIPTION:
XS GIS Cut Line= 4
      2050685.15     13523352.03      2050090.51     13523260.89
      2049731.54     13523462.71      2049558.43     13523642.80
#Sta/Elev= 30
  4260.7  519.58  4401.8  518.18  4719.1  517.35  4766.7  516.55  4837.5  517.28
  4868.6  515.87  4883.3  516.27  4942.6  514.69  4971.9  514.94  4986.0  514.28
  4991.8  513.06  4992.3  512.26  4997.3  512.26  4997.8  513.06  5029.3  514.72
  5091.8  514.80  5126.2  514.84  5178.4  516.22  5235.7  516.07  5287.5  518.20
  5294.4  517.18  5351.0  517.51  5358.2  518.33  5365.2  517.77  5372.4  518.61
  5435.9  519.71  5457.3  521.25  5464.2  520.77  5471.4  521.77  5523.9  522.39
#Mann=5,-1,0
  4260.7    0.05       0  4719.1     0.1       0  4991.8    0.07       0
  4997.8     0.1       0  5091.8    0.05       0
Bank Sta=4991.8,4997.8
Exp/Cntr=0.3,0.1

Type RM Length L Ch R = 1,7601,44,44,44
BEGIN DESCRIPTION:
Mapping XS b6161896
END DESCRIPTION:
XS GIS Cut Line= 5
      2050188.38     13523130.24      2050016.51     13523074.69
      2049891.51     13523112.88      2049815.12     13523192.74
      2049711.64     13523461.79
#Sta/Elev= 30
  4670.0  519.32  4701.6  519.01  4738.8  517.04  4841.7  516.73  4868.3  515.61
  4925.4  517.33  4933.9  516.80  4946.3  513.30  4972.0  511.16  5001.5  510.87
  5008.7  510.06  5015.6  510.60  5022.9  509.62  5034.0  509.54  5034.5  508.74
  5039.5  508.74  5040.0  509.54  5079.5  511.64  5086.4  513.32  5089.9  515.33
  5102.9  516.37  5108.2  516.49  5127.2  513.14  5138.2  512.92  5169.3  514.81
  5217.5  516.08  5255.0  515.11  5296.8  515.48  5332.1  516.97  5380.1  517.19
#Mann=4,-1,0
  4670.0     0.1       0  5034.0    0.07       0  5040.0     0.1       0
  5127.2    0.05       0
Bank Sta=5034,5040
Exp/Cntr=0.3,0.1

Type RM Length L Ch R = 1,7557,22,22,22
BEGIN DESCRIPTION:
Mapping XS f2c6f277
END DESCRIPTION:
XS GIS Cut Line= 6
      2050240.52     13523092.06      2049980.05     13523039.97
      2049867.21     13523078.16      2049790.82     13523156.28
      2049789.08     13523189.27      2049672.76     13523467.05
#Sta/Elev= 30
  4599.2  519.03  4660.8  516.83  4829.2  516.19  4870.2  514.71  4921.6  515.75
  4927.8  516.46  4953.9  516.03  4965.2  517.01  4982.5  516.11  4990.4  517.24
  4997.4  516.59  5004.5  517.42  5011.5  516.67  5018.7  517.47  5054.0  516.84
  5060.8  517.52  5082.3  515.85  5107.9  516.80  5132.5  515.60  5149.2  513.02
  5175.5  512.86  5176.0  512.06  5181.0  512.06  5181.5  512.86  5231.4  515.98
  5255.2  514.74  5302.8  515.32  5332.0  516.69  5355.8  516.11  5427.4  517.06
#Mann=5,-1,0
  4599.2    0.05       0  4921.6     0.1       0  5060.8    0.05       0
  5175.5    0.07       0  5181.5    0.05       0
Bank Sta=5175.5,5181.5
Exp/Cntr=0.3,0.1

Type RM Length L Ch R = 1,7535,368,368,368
BEGIN DESCRIPTION:
Mapping XS cf3b1921
END DESCRIPTION:
XS GIS Cut Line= 5
      2050240.52     13522996.56      2049955.75     13523000.03
      2049882.83     13523038.23      2049742.21     13523158.02
      2049652.34     13523380.96
#Sta/Elev= 30
  4582.5  516.20  4778.0  515.75  4879.4  513.55  4924.6  513.98  4965.0  513.09
  4981.4  513.08  4988.0  513.98  4995.7  513.20  5002.2  514.39  5009.9  513.25
  5016.5  514.49  5020.8  513.79  5024.2  513.24  5030.8  514.37  5038.5  512.82
  5045.1  514.32  5051.8  513.15  5070.6  512.63  5071.1  511.83  5076.1  511.83
  5076.6  512.63  5108.8  513.60  5167.9  512.78  5197.4  514.65  5221.6  514.05
  5289.8  515.68  5309.4  516.77  5323.6  516.99  5335.9  516.07  5374.7  516.79
#Mann=7,-1,0
  4582.5    0.05       0  4965.0     0.1       0  5020.8    0.05       0
  5070.6    0.07       0  5076.6    0.05       0  5289.8    0.08       0
  5309.4     0.1       0
Bank Sta=5070.6,5076.6
Exp/Cntr=0.3,0.1

Type RM Length L Ch R = 1,7167,52,52,52
BEGIN DESCRIPTION:
Mapping XS a9c12891
END DESCRIPTION:
XS GIS Cut Line= 4
      2049920.00     13522696.25      2049729.90     13522744.43
      2049490.32     13522903.28      2049431.72     13522964.48
#Sta/Elev= 30
  4668.1  513.38  4693.9  513.62  4755.8  512.11  4817.7  511.78  4850.0  511.09
  4875.2  511.34  4890.2  510.89  4896.2  511.40  4911.3  511.49  4941.4  511.03
  4954.1  510.34  4962.4  510.67  4968.4  510.01  4995.5  509.61  4996.0  508.81
  5001.0  508.81  5001.5  509.61  5013.6  510.17  5019.6  509.69  5026.1  510.51
  5062.1  511.31  5076.7  511.26  5085.8  511.94  5106.8  511.09  5140.1  512.64
  5162.9  513.56  5192.1  514.62  5199.0  513.91  5213.2  515.04  5236.4  514.47
#Mann=5,-1,0
  4668.1    0.05       0  4995.5    0.03       0  5001.5    0.05       0
  5140.1    0.08       0  5162.9     0.1       0
Bank Sta=4995.5,5001.5
Exp/Cntr=0.3,0.1

Type RM Length L Ch R = 1,7115,362,362,362
BEGIN DESCRIPTION:
Mapping XS 4aee8fe8
END DESCRIPTION:
XS GIS Cut Line= 6
      2049900.47     13522640.26      2049818.44     13522653.28
      2049660.89     13522741.82      2049569.74     13522788.70
      2049539.80     13522801.72      2049416.12     13522899.36
#Sta/Elev= 30
  4677.1  512.72  4682.6  512.37  4738.8  512.41  4743.8  512.04  4759.4  511.92
  4793.5  512.27  4815.2  511.64  4831.1  511.83  4836.9  511.35  4844.4  511.55
  4867.3  510.92  4874.5  511.24  4933.8  510.65  4939.0  511.11  4970.0  509.84
  5025.1  509.45  5025.6  508.65  5030.6  508.65  5031.1  509.45  5043.2  510.85
  5068.3  511.95  5089.0  511.81  5109.8  510.70  5124.2  510.72  5145.8  512.10
  5167.5  512.13  5188.3  513.15  5209.9  513.31  5217.2  513.79  5233.6  513.93
#Mann=5,-1,0
  4677.1    0.05       0  5025.1    0.03       0  5031.1    0.05       0
  5124.2    0.08       0  5209.9     0.1       0
Bank Sta=5025.1,5031.1
Exp/Cntr=0.3,0.1

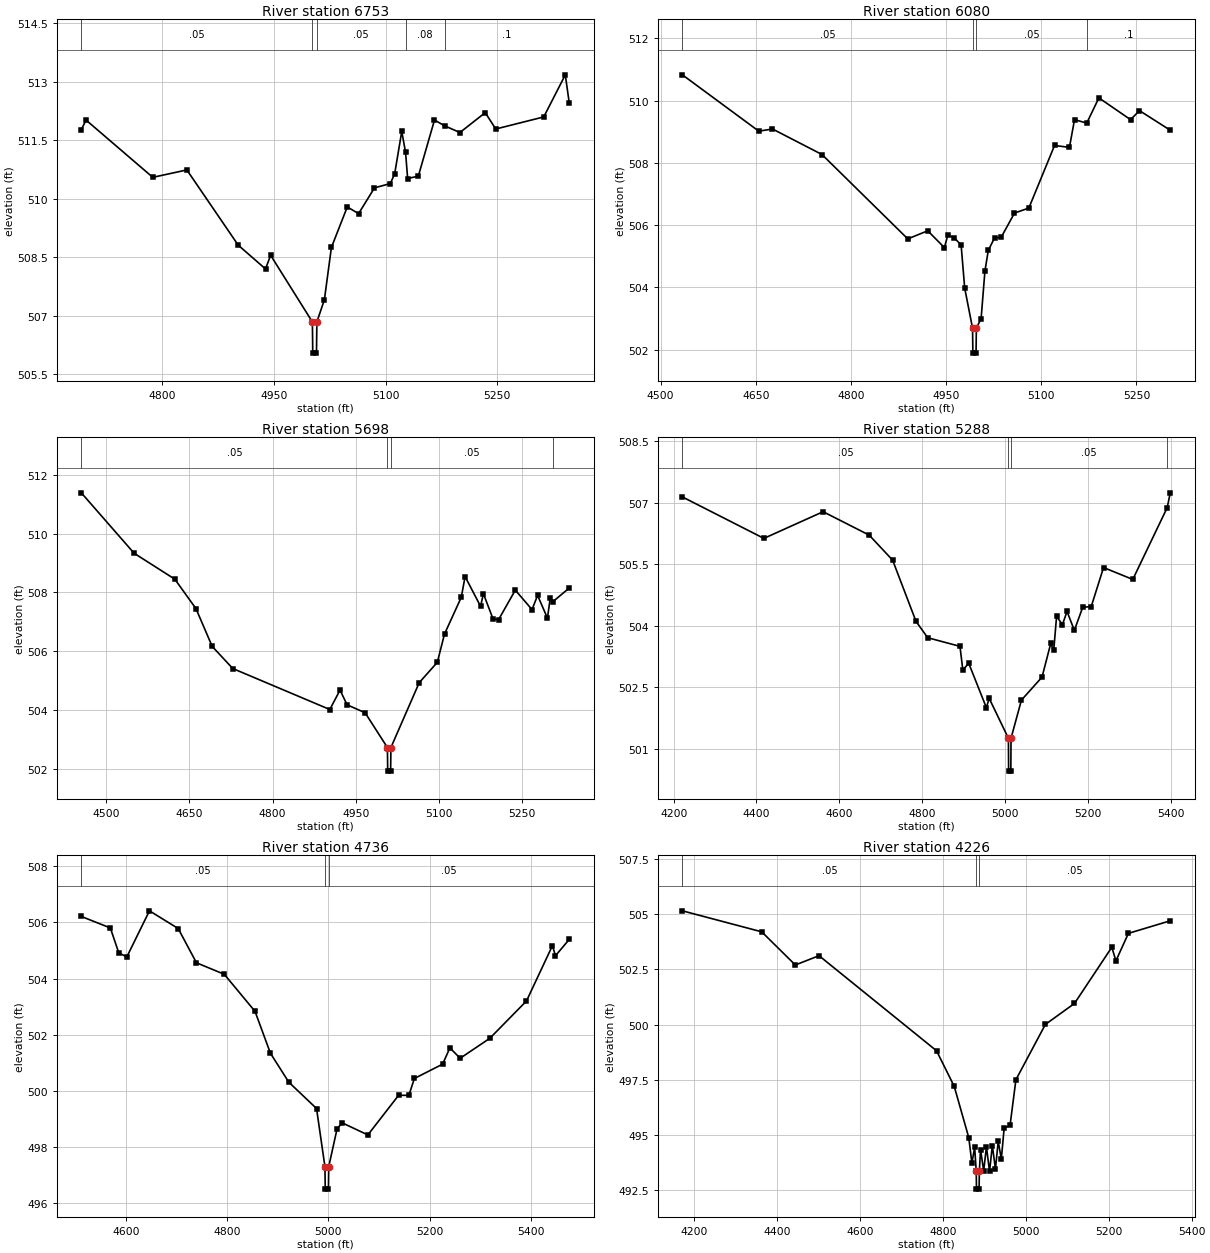
Type RM Length L Ch R = 1,6753,673,673,673
BEGIN DESCRIPTION:
Mapping XS d6b4ef9d
END DESCRIPTION:
XS GIS Cut Line= 4
      2049741.13     13522524.53      2049574.01     13522481.12
      2049348.32     13522622.18      2049289.92     13522829.81
#Sta/Elev= 30
  4691.9  511.77  4698.2  512.02  4787.8  510.55  4833.5  510.74  4902.4  508.81
  4939.0  508.20  4945.9  508.55  5001.9  506.84  5002.4  506.04  5007.4  506.04
  5007.9  506.84  5018.0  507.41  5027.4  508.75  5048.7  509.79  5063.9  509.62
  5085.2  510.28  5106.4  510.39  5112.3  510.64  5121.8  511.73  5126.9  511.19
  5129.7  510.52  5144.0  510.58  5165.7  512.02  5179.5  511.87  5199.8  511.70
  5233.8  512.21  5247.9  511.79  5312.3  512.10  5341.2  513.18  5346.4  512.47
#Mann=5,-1,0
  4691.9    0.05       0  5001.9    0.03       0  5007.9    0.05       0
  5126.9    0.08       0  5179.5     0.1       0
Bank Sta=5001.9,5007.9
Exp/Cntr=0.3,0.1

Type RM Length L Ch R = 1,6080,382,382,382
BEGIN DESCRIPTION:
Mapping XS 2df5f127
END DESCRIPTION:
XS GIS Cut Line= 4
      2049654.48     13521999.85      2049463.54     13521890.49
      2049067.71     13522018.97      2048970.46     13522109.26
#Sta/Elev= 30
  4534.4  510.83  4654.8  509.02  4676.4  509.09  4754.4  508.27  4889.6  505.56
  4921.1  505.82  4947.3  505.28  4952.7  505.68  4963.2  505.59  4973.7  505.36
  4979.3  503.98  4991.7  502.69  4992.2  501.89  4997.2  501.89  4997.7  502.69
  5005.2  503.00  5011.2  504.53  5016.5  505.19  5026.3  505.59  5036.8  505.61
  5057.8  506.39  5080.4  506.55  5120.9  508.56  5144.4  508.50  5152.4  509.39
  5171.7  509.28  5190.8  510.09  5240.7  509.39  5254.8  509.68  5303.3  509.05
#Mann=4,-1,0
  4534.4    0.05       0  4991.7    0.03       0  4997.7    0.05       0
  5171.7     0.1       0
Bank Sta=4991.7,4997.7
Exp/Cntr=0.3,0.1

Type RM Length L Ch R = 1,5698,410,410,410
BEGIN DESCRIPTION:
Mapping XS 647cd3b9
END DESCRIPTION:
XS GIS Cut Line= 4
      2049532.98     13521572.78      2049375.00     13521496.40
      2048897.57     13521696.05      2048913.04     13521881.73
#Sta/Elev= 30
  4455.4  511.38  4550.6  509.33  4624.0  508.45  4662.1  507.45  4691.3  506.17
  4728.4  505.42  4903.3  504.03  4921.7  504.69  4934.4  504.19  4966.9  503.92
  5007.1  502.74  5007.6  501.94  5012.9  501.94  5013.4  502.74  5064.4  504.94
  5097.0  505.63  5110.0  506.59  5140.3  507.84  5147.1  508.54  5175.0  507.53
  5180.1  507.96  5197.5  507.10  5207.5  507.08  5237.6  508.08  5267.7  507.42
  5277.8  507.90  5295.5  507.13  5300.5  507.80  5305.5  507.69  5334.7  508.15
#Mann=4,-1,0
  4455.4    0.05       0  5007.1    0.03       0  5013.4    0.05       0
  5305.5     0.1       0
Bank Sta=5007.1,5013.4
Exp/Cntr=0.3,0.1

Type RM Length L Ch R = 1,5288,552,552,552
BEGIN DESCRIPTION:
Mapping XS 07847144
END DESCRIPTION:
XS GIS Cut Line= 4
      2049527.77     13521034.59      2049182.29     13520963.41
      2048782.98     13521374.87      2048814.23     13521624.83
#Sta/Elev= 30
  4221.1  507.14  4417.9  506.13  4560.9  506.78  4672.1  506.21  4728.7  505.60
  4785.1  504.11  4813.4  503.71  4891.3  503.50  4898.3  502.92  4912.4  503.09
  4954.9  502.01  4962.0  502.23  5008.3  501.26  5008.8  500.46  5014.1  500.46
  5014.6  501.26  5039.7  502.19  5089.4  502.75  5110.5  503.57  5117.7  503.40
  5124.6  504.23  5138.8  504.03  5149.8  504.35  5167.5  503.89  5187.6  504.45
  5208.3  504.47  5238.0  505.42  5308.6  505.13  5391.7  506.88  5399.1  507.24
#Mann=4,-1,0
  4221.1    0.05       0  5008.3    0.03       0  5014.6    0.05       0
  5391.7    0.08       0
Bank Sta=5008.3,5014.6
Exp/Cntr=0.3,0.1

Type RM Length L Ch R = 1,4736,510,510,510
BEGIN DESCRIPTION:
Mapping XS 60b29e18
END DESCRIPTION:
XS GIS Cut Line= 4
      2049095.50     13520883.56      2048918.40     13520795.01
      2048366.32     13520887.02      2048253.67     13521060.33
#Sta/Elev= 30
  4511.7  506.21  4569.1  505.80  4585.8  504.91  4601.7  504.77  4646.4  506.41
  4703.2  505.78  4739.3  504.56  4794.3  504.15  4855.1  502.83  4885.5  501.34
  4921.8  500.31  4976.7  499.37  4993.3  497.30  4993.9  496.50  5000.2  496.50
  5000.8  497.30  5017.3  498.65  5027.4  498.86  5078.1  498.43  5138.9  499.84
  5159.2  499.84  5170.1  500.44  5225.9  500.95  5240.3  501.53  5260.6  501.16
  5319.2  501.87  5391.7  503.20  5443.0  505.17  5449.0  504.81  5476.1  505.39
#Mann=3,-1,0
  4511.7    0.05       0  4993.3    0.03       0  5000.8    0.05       0
Bank Sta=4993.3,5000.8
Exp/Cntr=0.3,0.1

Type RM Length L Ch R = 1,4226,57,57,57
BEGIN DESCRIPTION:
Mapping XS 29fa8d1a
END DESCRIPTION:
XS GIS Cut Line= 5
      2049013.01     13520232.51      2048756.07     13520183.90
      2048408.85     13520340.15      2048151.91     13520626.60
      2048144.96     13520775.88
#Sta/Elev= 30
  4171.9  505.15  4363.2  504.20  4444.2  502.70  4501.4  503.12  4784.7  498.82
  4827.4  497.21  4862.5  494.89  4870.0  493.74  4876.7  494.45  4880.5  493.36
  4881.1  492.56  4887.4  492.56  4888.0  493.36  4890.9  494.35  4898.4  493.39
  4905.1  494.47  4912.6  493.36  4919.3  494.53  4926.8  493.47  4933.5  494.72
  4941.0  493.92  4947.8  495.32  4962.0  495.44  4976.2  497.51  5047.2  500.01
  5117.4  500.96  5207.4  503.50  5217.4  502.89  5247.4  504.13  5348.4  504.70
#Mann=3,-1,0
  4171.9    0.05       0  4880.5    0.03       0  4888.0    0.05       0
Bank Sta=4880.5,4888
Exp/Cntr=0.3,0.1

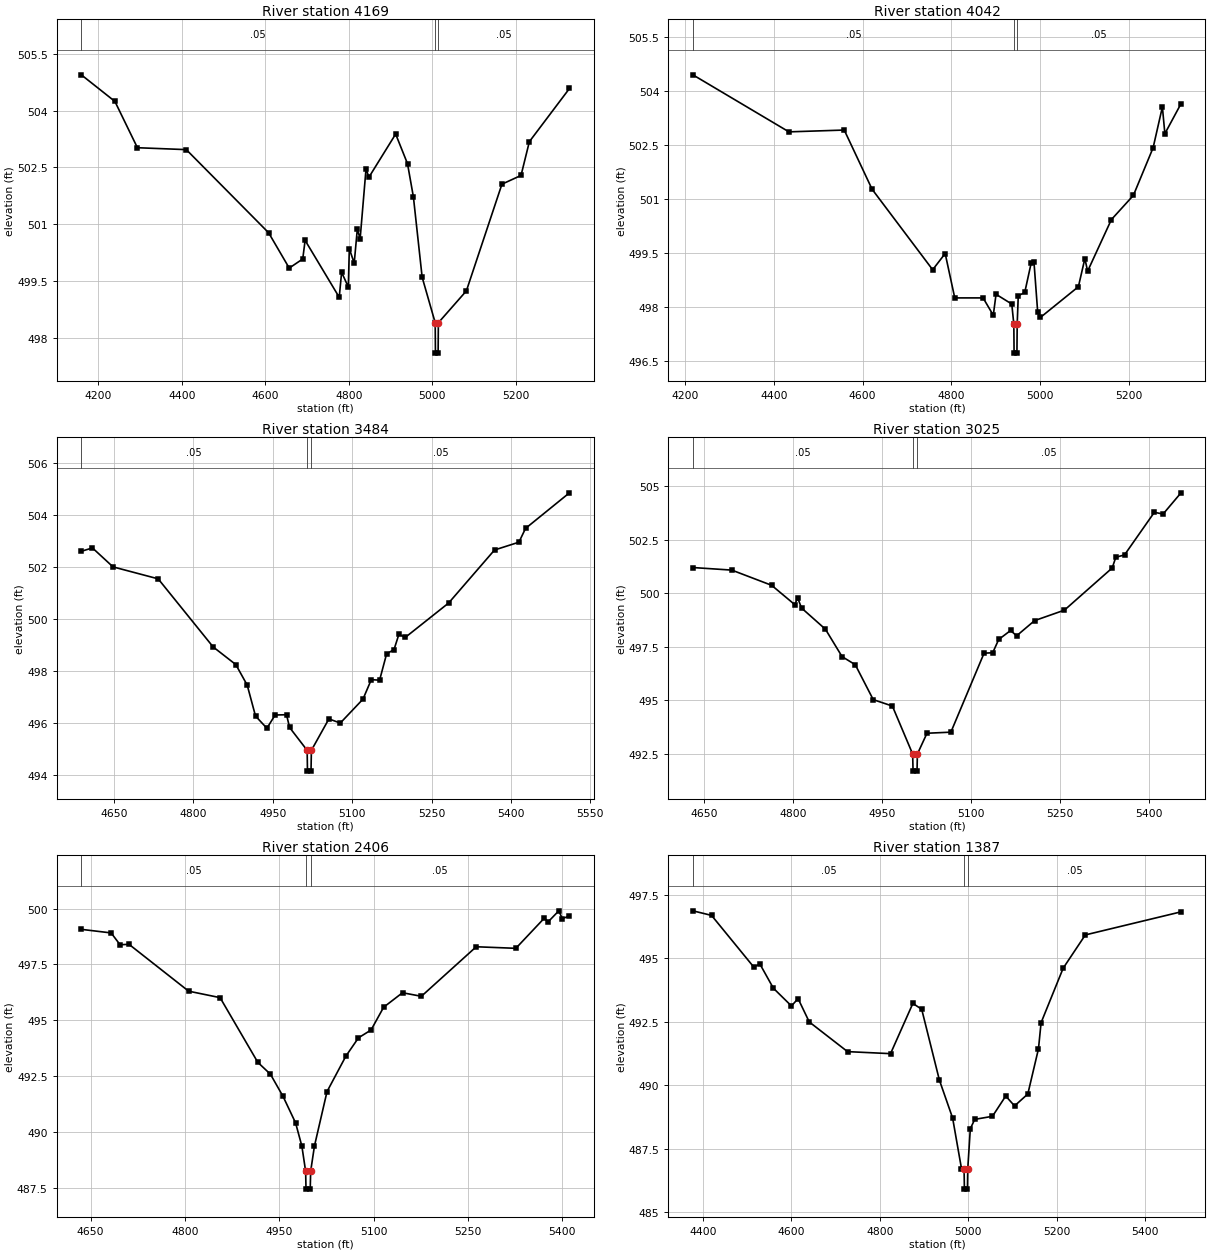
Type RM Length L Ch R = 1,4169,127,127,127
BEGIN DESCRIPTION:
Mapping XS 6a1710c7
END DESCRIPTION:
XS GIS Cut Line= 5
      2048974.86     13520156.12      2048690.10     13520121.40
      2048375.87     13520291.53      2048124.13     13520571.05
      2048120.68     13520721.04
#Sta/Elev= 30
  4158.9  504.94  4239.4  504.24  4293.4  503.02  4410.6  502.97  4608.0  500.78
  4657.4  499.85  4689.8  500.09  4695.5  500.58  4777.3  499.08  4783.0  499.74
  4799.1  499.35  4801.5  500.36  4813.2  499.98  4820.7  500.88  4827.4  500.62
  4841.6  502.47  4848.3  502.24  4912.6  503.38  4941.0  502.60  4955.2  501.72
  4976.1  499.61  5007.4  498.41  5008.0  497.61  5014.4  497.61  5015.0  498.41
  5082.2  499.25  5167.4  502.06  5213.2  502.29  5233.2  503.18  5329.3  504.58
#Mann=3,-1,0
  4158.9    0.05       0  5007.4    0.03       0  5015.0    0.05       0
Bank Sta=5007.4,5015
Exp/Cntr=0.3,0.1

Type RM Length L Ch R = 1,4042,558,558,558
BEGIN DESCRIPTION:
Mapping XS 7097d2e7
END DESCRIPTION:
XS GIS Cut Line= 4
      2048891.49     13520062.37      2048573.78     13520051.95
      2048092.88     13520409.59      2048039.52     13520585.17
#Sta/Elev= 30
  4217.3  504.44  4433.9  502.86  4558.6  502.91  4621.4  501.27  4758.0  499.04
  4786.2  499.49  4807.8  498.26  4871.7  498.26  4894.7  497.78  4900.9  498.36
  4936.4  498.09  4941.0  497.53  4941.6  496.73  4948.0  496.73  4948.6  497.53
  4951.0  498.32  4965.6  498.41  4980.2  499.23  4986.4  499.26  4994.8  497.87
  5001.1  497.72  5086.6  498.57  5101.2  499.35  5107.4  499.00  5161.0  500.43
  5210.6  501.10  5255.1  502.42  5276.0  503.55  5281.6  502.81  5318.0  503.64
#Mann=3,-1,0
  4217.3    0.05       0  4941.0    0.03       0  4948.6    0.05       0
Bank Sta=4941,4948.6
Exp/Cntr=0.3,0.1

Type RM Length L Ch R = 1,3484,459,459,459
BEGIN DESCRIPTION:
Mapping XS a843f6b4
END DESCRIPTION:
XS GIS Cut Line= 4
      2048451.54     13519816.29      2048232.81     13519739.91
      2047871.70     13519951.72      2047736.29     13520187.82
#Sta/Elev= 30
  4588.1  502.60  4609.1  502.73  4648.0  502.00  4733.3  501.54  4837.2  498.92
  4880.1  498.24  4901.6  497.45  4917.3  496.26  4938.8  495.79  4954.4  496.30
  4975.9  496.31  4981.7  495.82  5014.9  494.94  5015.5  494.14  5022.2  494.14
  5022.9  494.94  5056.0  496.15  5077.5  495.99  5120.4  496.91  5136.1  497.66
  5151.8  497.64  5165.0  498.65  5179.1  498.82  5188.2  499.40  5200.6  499.29
  5282.3  500.61  5369.0  502.65  5415.1  502.95  5427.6  503.48  5510.6  504.85
#Mann=3,-1,0
  4588.1    0.05       0  5014.9    0.03       0  5022.9    0.05       0
Bank Sta=5014.9,5022.9
Exp/Cntr=0.3,0.1

Type RM Length L Ch R = 1,3025,619,619,619
BEGIN DESCRIPTION:
Mapping XS ceef288e
END DESCRIPTION:
XS GIS Cut Line= 4
      2048347.35     13519430.86      2048267.53     13519389.22
      2047722.39     13519458.66      2047614.77     13519607.94
#Sta/Elev= 30
  4631.0  501.21  4696.7  501.09  4763.9  500.38  4802.8  499.48  4807.8  499.79
  4814.3  499.32  4854.6  498.33  4882.7  497.05  4905.0  496.67  4935.3  495.04
  4967.6  494.74  5001.8  492.50  5002.5  491.70  5009.2  491.70  5009.8  492.50
  5026.0  493.47  5066.3  493.52  5122.3  497.21  5136.9  497.23  5147.0  497.85
  5167.1  498.27  5177.2  498.02  5207.5  498.73  5257.9  499.22  5338.5  501.19
  5344.6  501.69  5359.3  501.80  5409.6  503.79  5424.4  503.71  5454.6  504.70
#Mann=3,-1,0
  4631.0    0.05       0  5001.8    0.03       0  5009.8    0.05       0
Bank Sta=5001.8,5009.8
Exp/Cntr=0.3,0.1

Type RM Length L Ch R = 1,2406,1019,1019,1019
BEGIN DESCRIPTION:
Mapping XS 30118172
END DESCRIPTION:
XS GIS Cut Line= 4
      2048225.84     13518941.28      2048118.23     13518840.61
      2047635.59     13518844.08      2047573.09     13518976.01
#Sta/Elev= 30
  4635.2  499.07  4682.6  498.91  4696.8  498.38  4711.0  498.40  4805.8  496.30
  4855.8  496.01  4915.8  493.11  4935.8  492.58  4955.8  491.59  4975.8  490.40
  4985.8  489.36  4991.8  488.23  4992.4  487.43  4999.1  487.43  4999.8  488.23
  5005.8  489.36  5025.8  491.80  5055.8  493.39  5075.8  494.21  5095.8  494.56
  5115.8  495.58  5145.8  496.23  5175.8  496.07  5263.0  498.29  5326.0  498.22
  5371.5  499.58  5377.1  499.40  5394.3  499.90  5399.8  499.55  5411.2  499.67
#Mann=3,-1,0
  4635.2    0.05       0  4991.8    0.03       0  4999.8    0.05       0
Bank Sta=4991.8,4999.8
Exp/Cntr=0.3,0.1

Type RM Length L Ch R = 1,1387,547,547,547
BEGIN DESCRIPTION:
Mapping XS f5d8f40c
END DESCRIPTION:
XS GIS Cut Line= 4
      2048444.64     13518010.76      2048003.64     13517851.03
      2047521.00     13517864.91      2047406.43     13517965.60
#Sta/Elev= 30
  4376.9  496.87  4419.1  496.69  4514.8  494.65  4528.3  494.78  4559.0  493.82
  4599.9  493.12  4614.9  493.41  4640.2  492.49  4726.8  491.32  4824.1  491.24
  4874.6  493.22  4894.6  492.99  4934.6  490.20  4964.6  488.70  4984.6  486.71
  4990.5  486.70  4991.2  485.90  4998.1  485.90  4998.8  486.70  5004.6  488.28
  5014.6  488.65  5054.7  488.77  5084.7  489.57  5104.7  489.18  5134.7  489.65
  5158.8  491.43  5164.7  492.46  5214.7  494.61  5264.8  495.92  5481.3  496.83
#Mann=3,-1,0
  4376.9    0.05       0  4990.5    0.03       0  4998.8    0.05       0
Bank Sta=4990.5,4998.8
Exp/Cntr=0.3,0.1

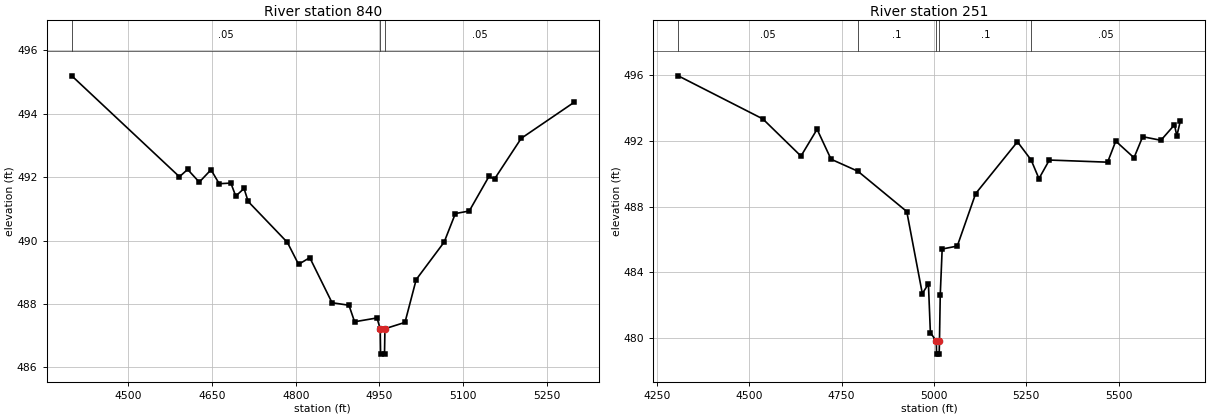
Type RM Length L Ch R = 1,840,589,589,589
BEGIN DESCRIPTION:
Mapping XS ed667275
END DESCRIPTION:
XS GIS Cut Line= 4
      2048364.72     13517493.36      2048114.75     13517316.30
      2047614.75     13517357.97      2047541.86     13517413.51
#Sta/Elev= 30
  4398.7  495.19  4591.6  492.01  4606.3  492.24  4627.2  491.84  4648.2  492.23
  4662.9  491.79  4683.8  491.81  4692.5  491.40  4707.4  491.64  4714.8  491.23
  4785.1  489.94  4805.1  489.25  4825.2  489.46  4865.1  488.04  4895.4  487.96
  4905.5  487.44  4945.6  487.56  4951.4  487.22  4952.1  486.42  4959.1  486.42
  4959.9  487.22  4995.8  487.42  5015.9  488.77  5066.0  489.95  5086.1  490.85
  5111.0  490.93  5146.3  492.02  5156.3  491.94  5204.1  493.22  5298.4  494.35
#Mann=3,-1,0
  4398.7    0.05       0  4951.4    0.03       0  4959.9    0.05       0
Bank Sta=4951.4,4959.9
Exp/Cntr=0.3,0.1

Type RM Length L Ch R = 1,251,0,0,0
BEGIN DESCRIPTION:
UNT 1 in Lagunillas Cr Wtrshd 1.0
END DESCRIPTION:
XS GIS Cut Line= 4
      2048429.52     13517302.03      2048189.31     13516865.52
      2047807.59     13516741.38      2047432.03     13517005.20
#Sta/Elev= 30
  4308.1  495.95  4537.0  493.33  4640.2  491.07  4683.8  492.70  4721.6  490.88
  4794.2  490.15  4926.5  487.70  4968.6  482.71  4985.1  483.30  4990.4  480.33
  5006.4  479.83  5007.2  479.03  5014.2  479.03  5015.0  479.83  5017.1  482.63
  5022.3  485.42  5063.2  485.60  5112.9  488.79  5226.0  491.94  5263.1  490.83
  5284.2  489.70  5312.3  490.83  5470.0  490.70  5492.0  491.98  5541.4  490.97
  5564.9  492.25  5614.2  492.03  5650.9  492.97  5657.3  492.30  5666.7  493.20
#Mann=5,-1,0
  4308.1    0.05       0  4794.2     0.1       0  5006.4    0.07       0
  5015.0     0.1       0  5263.1    0.05       0
Bank Sta=5006.4,5015
Exp/Cntr=0.3,0.1

Chan Stop Cuts=-1