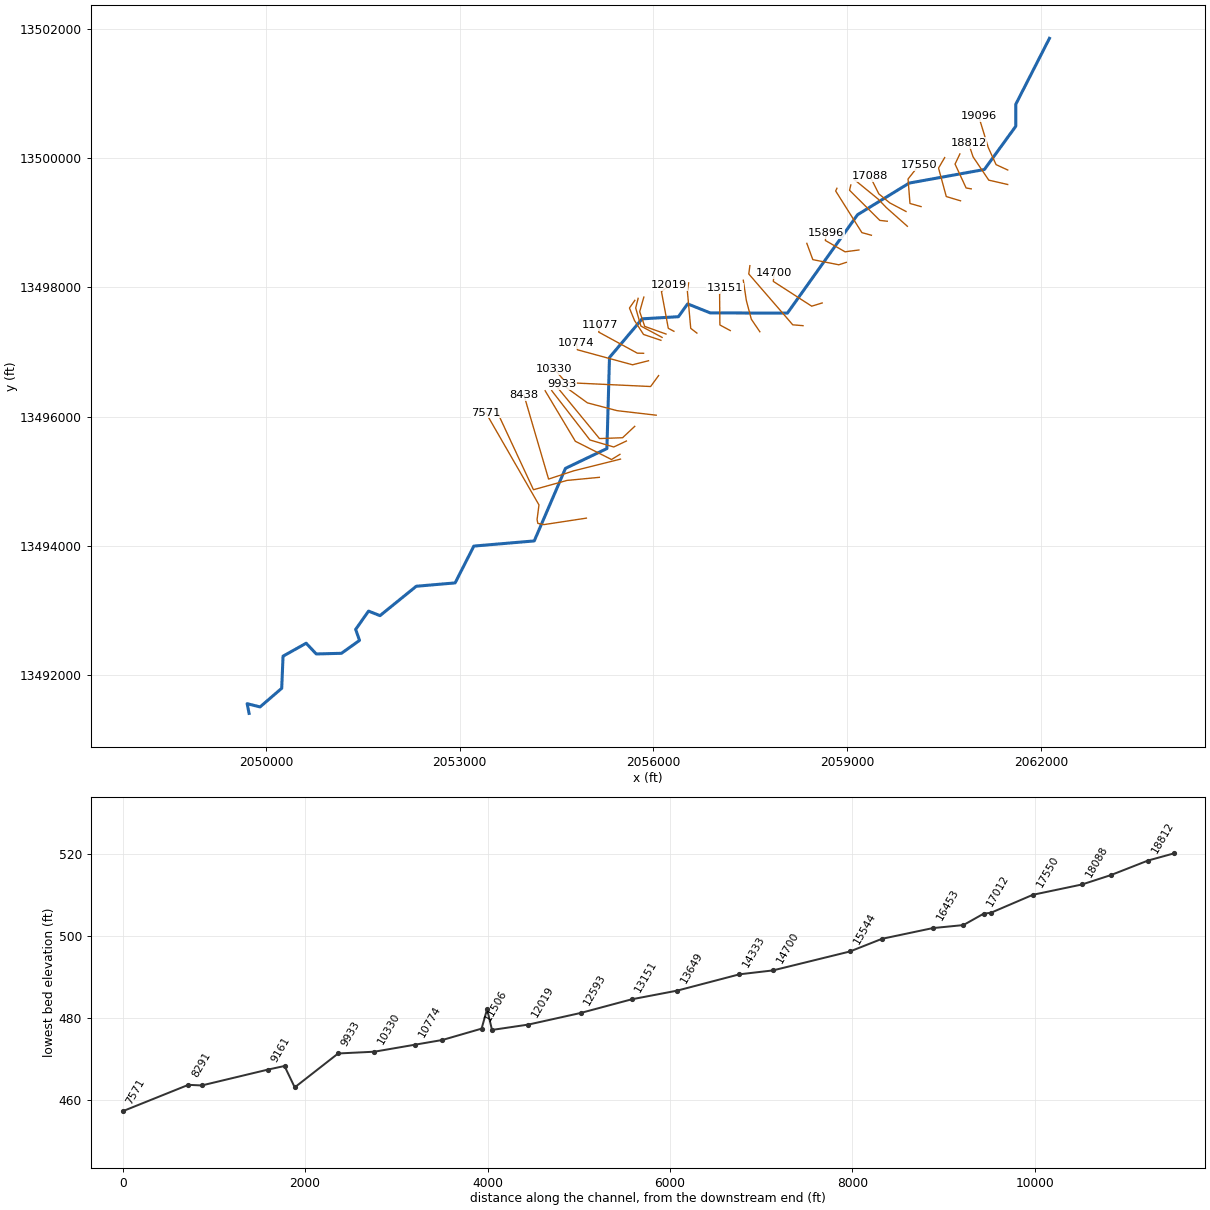
--- UNT 100 in Lagunillas Cr Wtrshd.prj (project) ---

Proj Title=UNT 100 in Lagunillas Cr Wtrshd Base Level Engineering
Current Plan=p01
Default Exp/Contr=0.3,0.1
English Units
Geom File=g01
Flow File=f01
Plan File=p01
BEGIN DESCRIPTION:
UNT 100 in Lagunillas Cr Wtrshd
END DESCRIPTION:

--- UNT 100 in Lagunillas Cr Wtrshd.p01 (plan) ---

Plan Title=Multiple Run
Short Identifier=Multiple
Geom File=g01
Flow File=f01
Subcritical Flow
K Sum by GR= 0
Std Step Tol= 0.01
Critical Tol= 0.01
Num of Std Step Trials= 20
Max Error Tol= 0.3
Flow Tol Ratio= 0.001
Split Flow NTrial= 30
Split Flow Tol= 0.02
Split Flow Ratio= 0.02
Log Output Level= 0
Friction Slope Method= 1
Unsteady Friction Slope Method= 2
Unsteady Bridges Friction Slope Method= 1
Parabolic Critical Depth
Global Vel Dist=  1 , 1 , 1
Global Log Level= 0
CheckData=True
Encroach Param= -1, 0, 0, 0
BEGIN DESCRIPTION:
Multiple Run
END DESCRIPTION:

--- UNT 100 in Lagunillas Cr Wtrshd.f01 (steady flow) ---

Flow Title=Multiple
Number of Profiles=7
Profile Names=10-year,25-year,50-year,1pct_min,100-year,1pct_plu,500-year
River Rch & RM= UNT 100 in Lagun,Reach-1,19096
      75      96     112      66     131     261     180
River Rch & RM= UNT 100 in Lagun,Reach-1,18088
     192     261     316     191     382     762     565
River Rch & RM= UNT 100 in Lagun,Reach-1,7084
     217     297     361     219     438     874     653
River Rch & RM= UNT 100 in Lagun,Reach-1,4003
     265     367     450     275     549    1096     831
Boundary for River Rch & Prof#=UNT 100 in Lagun,Reach-1,1
Up Type=0
Dn Type=3
Dn Slope=0.005
Boundary for River Rch & Prof#=UNT 100 in Lagun,Reach-1,2
Up Type=0
Dn Type=3
Dn Slope=0.005
Boundary for River Rch & Prof#=UNT 100 in Lagun,Reach-1,3
Up Type=0
Dn Type=3
Dn Slope=0.005
Boundary for River Rch & Prof#=UNT 100 in Lagun,Reach-1,4
Up Type=0
Dn Type=3
Dn Slope=0.005
Boundary for River Rch & Prof#=UNT 100 in Lagun,Reach-1,5
Up Type=0
Dn Type=3
Dn Slope=0.005
Boundary for River Rch & Prof#=UNT 100 in Lagun,Reach-1,6
Up Type=0
Dn Type=3
Dn Slope=0.005
Boundary for River Rch & Prof#=UNT 100 in Lagun,Reach-1,7
Up Type=0
Dn Type=3
Dn Slope=0.005

--- UNT 100 in Lagunillas Cr Wtrshd.g01 (geometry) ---

Geom Title=Existing Conditions

River Reach=UNT 100 in Lagun,Reach-1
Reach XY= 30
      2062132.15     13501855.62      2061610.80     13500834.54
      2061610.80     13500494.54      2061125.00     13499825.00
      2059960.80     13499614.54      2059160.80     13499124.54
      2058075.10     13497601.44      2056880.80     13497604.54
      2056530.80     13497744.54      2056387.60     13497545.89
      2055825.97     13497512.90      2055320.80     13496914.54
      2055280.80     13495504.54      2054639.28     13495197.79
      2054155.80     13494074.54      2053220.80     13493994.54
      2052930.80     13493424.54      2052329.30     13493372.56
      2051767.67     13492917.70      2051590.58     13492988.02
      2051390.80     13492704.54      2051450.80     13492534.54
      2051170.80     13492334.54      2050780.80     13492324.54
      2050624.44     13492490.62      2050266.80     13492290.10
      2050245.97     13491792.70      2049910.80     13491504.54
      2049710.80     13491554.54      2049740.80     13491404.54

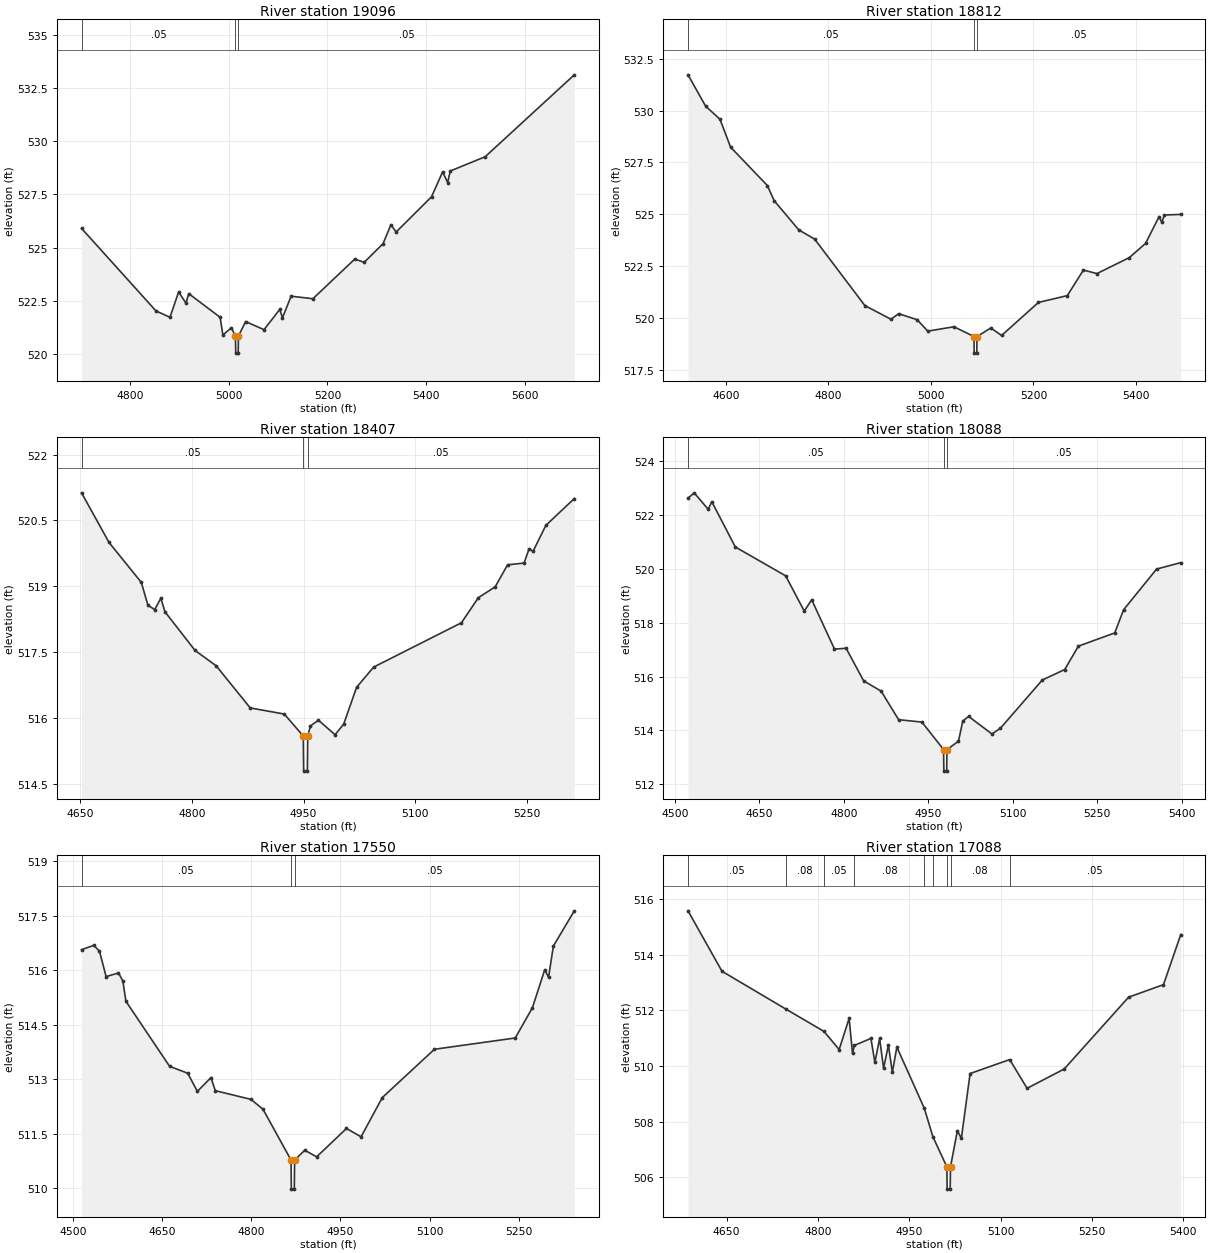
Type RM Length L Ch R = 1,19096,284,284,284
BEGIN DESCRIPTION:
Mapping XS 95ac8bfe
END DESCRIPTION:
XS GIS Cut Line= 4
      2061486.49     13499817.05      2061305.92     13499900.08
      2061185.74     13500163.08      2061036.22     13500649.62
#Sta/Elev= 30
  4702.6  525.91  4853.1  522.04  4881.5  521.74  4899.0  522.93  4913.9  522.40
  4919.4  522.85  4983.0  521.74  4988.5  520.91  5005.7  521.25  5014.0  520.86
  5014.5  520.06  5019.5  520.06  5020.0  520.86  5034.5  521.54  5071.7  521.16
  5103.6  522.11  5109.1  521.72  5126.6  522.73  5170.6  522.61  5255.3  524.47
  5274.5  524.32  5312.5  525.19  5328.5  526.08  5339.0  525.74  5410.6  527.39
  5433.1  528.56  5443.3  528.06  5448.6  528.60  5519.2  529.27  5699.5  533.11
#Mann=3,-1,0
  4702.6    0.05       0  5014.0    0.03       0  5020.0    0.05       0
Bank Sta=5014,5020
Exp/Cntr=0.3,0.1

Type RM Length L Ch R = 1,18812,405,405,405
BEGIN DESCRIPTION:
Mapping XS f3b306e2
END DESCRIPTION:
XS GIS Cut Line= 4
      2061485.86     13499592.85      2061192.91     13499660.12
      2060949.86     13500020.36      2060878.24     13500235.21
#Sta/Elev= 30
  4525.9  531.72  4560.3  530.21  4588.3  529.58  4608.9  528.24  4680.7  526.39
  4694.0  525.66  4742.2  524.25  4773.0  523.81  4871.0  520.61  4922.0  519.95
  4936.9  520.22  4972.9  519.93  4993.9  519.38  5044.8  519.59  5083.9  519.12
  5084.4  518.32  5089.4  518.32  5089.9  519.12  5116.8  519.53  5137.8  519.17
  5209.7  520.76  5266.1  521.09  5297.5  522.32  5323.9  522.15  5387.1  522.92
  5418.7  523.60  5445.1  524.89  5450.4  524.62  5455.7  524.97  5487.5  525.00
#Mann=3,-1,0
  4525.9    0.05       0  5083.9    0.03       0  5089.9    0.05       0
Bank Sta=5083.9,5089.9
Exp/Cntr=0.3,0.1

Type RM Length L Ch R = 1,18407,319,319,319
BEGIN DESCRIPTION:
Mapping XS 4f404a4b
END DESCRIPTION:
XS GIS Cut Line= 5
      2060921.45     13499525.64      2060919.31     13499525.64
      2060842.27     13499538.66      2060670.83     13499908.67
      2060745.70     13500066.00
#Sta/Elev= 30
  4651.6  521.13  4688.5  520.00  4731.9  519.09  4740.8  518.57  4749.9  518.47
  4758.2  518.73  4763.7  518.42  4804.1  517.54  4832.5  517.19  4878.3  516.23
  4924.1  516.09  4949.6  515.59  4950.1  514.79  4955.1  514.79  4955.6  515.59
  4959.3  515.82  4970.0  515.95  4992.3  515.62  5003.9  515.86  5021.3  516.70
  5044.2  517.16  5162.2  518.17  5184.9  518.74  5207.6  518.99  5224.2  519.49
  5246.4  519.53  5253.0  519.85  5258.5  519.80  5275.7  520.39  5313.9  521.00
#Mann=3,-1,0
  4651.6    0.05       0  4949.6    0.03       0  4955.6    0.05       0
Bank Sta=4949.6,4955.6
Exp/Cntr=0.3,0.1

Type RM Length L Ch R = 1,18088,538,538,538
BEGIN DESCRIPTION:
Mapping XS 3aa86fde
END DESCRIPTION:
XS GIS Cut Line= 4
      2060755.50     13499340.09      2060534.98     13499406.07
      2060415.19     13499847.04      2060510.27     13500009.54
#Sta/Elev= 30
  4523.2  522.62  4534.2  522.82  4559.0  522.21  4565.5  522.49  4607.2  520.81
  4696.6  519.74  4729.7  518.43  4742.9  518.85  4783.4  517.02  4804.1  517.05
  4835.2  515.84  4866.3  515.46  4897.3  514.40  4938.8  514.31  4977.2  513.29
  4977.7  512.49  4982.7  512.49  4983.2  513.29  5003.7  513.60  5011.3  514.35
  5021.7  514.52  5063.1  513.87  5078.1  514.08  5152.5  515.87  5192.3  516.26
  5216.8  517.13  5281.3  517.62  5297.0  518.48  5355.6  519.99  5398.6  520.23
#Mann=3,-1,0
  4523.2    0.05       0  4977.2    0.03       0  4983.2    0.05       0
Bank Sta=4977.2,4983.2
Exp/Cntr=0.3,0.1

Type RM Length L Ch R = 1,17550,462,462,462
BEGIN DESCRIPTION:
Mapping XS e7cafcfb
END DESCRIPTION:
XS GIS Cut Line= 4
      2060144.76     13499250.69      2059972.91     13499298.86
      2059942.97     13499677.77      2060110.59     13499889.23
#Sta/Elev= 30
  4514.9  516.57  4535.4  516.69  4545.0  516.53  4556.2  515.83  4577.0  515.93
  4584.3  515.71  4589.5  515.15  4662.9  513.36  4693.4  513.17  4709.6  512.67
  4732.5  513.05  4739.7  512.69  4799.8  512.45  4819.9  512.18  4867.1  510.78
  4867.6  509.98  4872.6  509.98  4873.1  510.78  4890.1  511.05  4910.2  510.87
  4960.3  511.65  4984.8  511.42  5020.5  512.50  5108.2  513.83  5244.0  514.14
  5272.8  514.97  5293.6  516.02  5300.0  515.81  5308.1  516.67  5343.3  517.64
#Mann=3,-1,0
  4514.9    0.05       0  4867.1    0.03       0  4873.1    0.05       0
Bank Sta=4867.1,4873.1
Exp/Cntr=0.3,0.1

Type RM Length L Ch R = 1,17088,76,76,76
BEGIN DESCRIPTION:
Mapping XS dc4c6bf0
END DESCRIPTION:
XS GIS Cut Line= 4
      2059911.67     13499175.19      2059660.41     13499307.98
      2059491.14     13499447.30      2059353.31     13499720.36
#Sta/Elev= 30
  4586.7  515.57  4642.5  513.40  4746.9  512.05  4810.1  511.24  4834.9  510.59
  4851.3  511.71  4856.9  510.45  4859.9  510.74  4887.1  510.99  4893.6  510.13
  4901.4  510.99  4907.9  509.92  4915.8  510.75  4922.3  509.77  4929.7  510.68
  4974.8  508.48  4988.9  507.46  5011.8  506.38  5012.3  505.58  5017.3  505.58
  5017.8  506.38  5029.1  507.68  5035.6  507.40  5050.0  509.73  5115.0  510.23
  5143.6  509.20  5204.4  509.89  5310.3  512.47  5367.6  512.92  5396.0  514.72
#Mann=9,-1,0
  4586.7    0.05       0  4746.9    0.08       0  4810.1    0.05       0
  4859.9    0.08       0  4974.8    0.05       0  4988.9    0.08       0
  5011.8    0.07       0  5017.8    0.08       0  5115.0    0.05       0
Bank Sta=5011.8,5017.8
Exp/Cntr=0.3,0.1

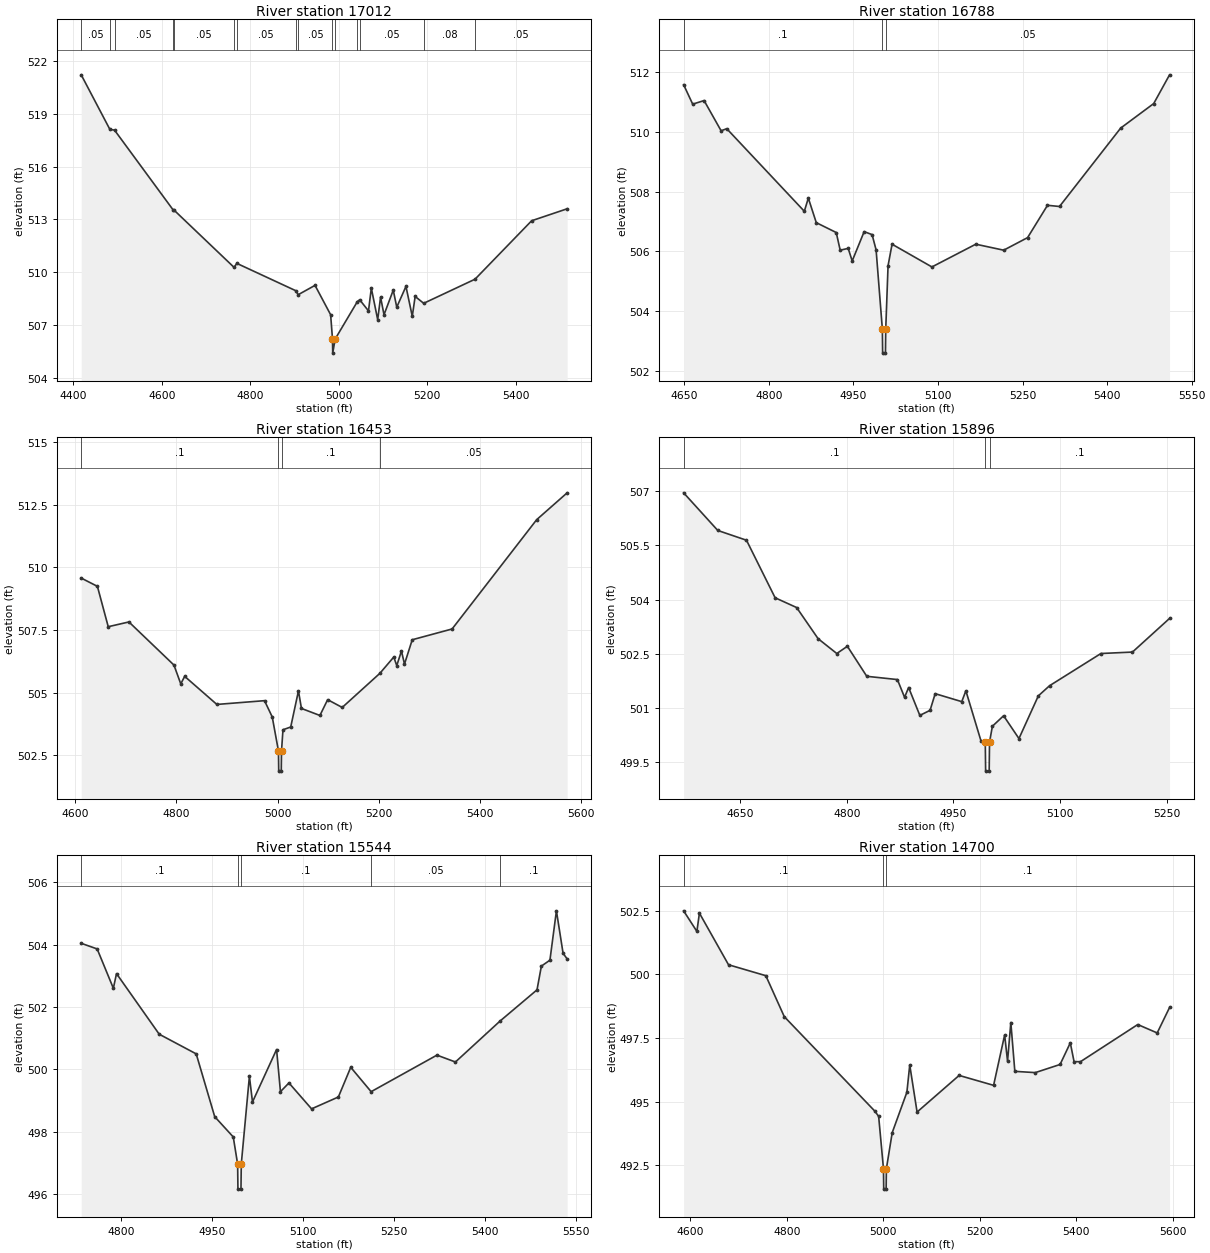
Type RM Length L Ch R = 1,17012,224,224,224
BEGIN DESCRIPTION:
Mapping XS a9c6e3b9
END DESCRIPTION:
XS GIS Cut Line= 4
      2059932.54     13498946.01      2059607.03     13499235.06
      2059482.03     13499365.27      2059108.34     13499671.25
#Sta/Elev= 30
  4417.8  521.21  4482.6  518.11  4493.1  518.07  4626.1  513.52  4628.3  513.51
  4763.5  510.27  4769.6  510.50  4902.6  508.95  4908.5  508.72  4946.5  509.25
  4981.8  507.58  4986.0  506.20  4986.5  505.40  4992.0  506.20  5042.3  508.33
  5047.5  508.43  5067.4  507.80  5073.8  509.09  5088.2  507.30  5094.7  508.58
  5102.5  507.58  5123.4  508.98  5131.3  508.01  5152.1  509.19  5166.4  507.49
  5172.9  508.62  5192.2  508.23  5308.3  509.60  5436.3  512.92  5516.6  513.60
#Mann=15,-1,0
  4417.8    0.05       0  4482.6    0.08       0  4493.1    0.05       0
  4626.1    0.08       0  4628.3    0.05       0  4763.5     0.1       0
  4769.6    0.05       0  4902.6     0.1       0  4908.5    0.05       0
  4986.0    0.04       0  4992.0    0.05       0  5042.3    0.08       0
  5047.5    0.05       0  5192.2    0.08       0  5308.3    0.05       0
Bank Sta=4986,4992
Exp/Cntr=0.3,0.1

Type RM Length L Ch R = 1,16788,335,335,335
BEGIN DESCRIPTION:
Mapping XS 5811a75a
END DESCRIPTION:
XS GIS Cut Line= 4
      2059621.04     13499023.91      2059506.03     13499036.93
      2059037.28     13499503.51      2059056.82     13499586.00
#Sta/Elev= 30
  4648.9  511.57  4665.0  510.92  4685.2  511.04  4715.4  510.03  4725.4  510.10
  4863.0  507.34  4870.1  507.78  4884.2  506.96  4919.6  506.63  4926.6  506.04
  4940.8  506.10  4947.9  505.68  4969.1  506.66  4983.2  506.56  4990.3  506.05
  5001.4  503.40  5001.9  502.60  5006.9  502.60  5007.4  503.40  5011.5  505.52
  5018.6  506.24  5089.3  505.48  5167.1  506.24  5216.6  506.04  5259.0  506.46
  5294.3  507.54  5315.6  507.50  5424.1  510.12  5482.7  510.94  5510.8  511.90
#Mann=3,-1,0
  4648.9     0.1       0  5001.4    0.07       0  5007.4    0.05       0
Bank Sta=5001.4,5007.4
Exp/Cntr=0.3,0.1

Type RM Length L Ch R = 1,16453,557,557,557
BEGIN DESCRIPTION:
Mapping XS 7b45efed
END DESCRIPTION:
XS GIS Cut Line= 4
      2059375.85     13498806.88      2059228.25     13498848.12
      2058822.43     13499492.65      2058841.96     13499533.87
#Sta/Elev= 30
  4611.9  509.57  4643.9  509.24  4665.3  507.63  4706.2  507.82  4795.2  506.10
  4808.7  505.35  4816.4  505.65  4880.0  504.53  4974.2  504.68  4989.5  504.03
  5001.8  502.67  5002.3  501.87  5007.3  501.87  5007.8  502.67  5010.7  503.52
  5026.0  503.63  5041.3  505.07  5047.2  504.37  5083.7  504.09  5099.0  504.72
  5127.8  504.41  5202.2  505.77  5229.7  506.42  5235.6  506.08  5244.9  506.66
  5250.9  506.14  5266.2  507.11  5345.0  507.54  5512.2  511.90  5572.4  512.97
#Mann=4,-1,0
  4611.9     0.1       0  5001.8    0.07       0  5007.8     0.1       0
  5202.2    0.05       0
Bank Sta=5001.8,5007.8
Exp/Cntr=0.3,0.1

Type RM Length L Ch R = 1,15896,352,352,352
BEGIN DESCRIPTION:
Mapping XS a3045633
END DESCRIPTION:
XS GIS Cut Line= 4
      2059182.72     13498579.03      2058967.83     13498550.81
      2058663.02     13498725.95      2058675.94     13498840.95
#Sta/Elev= 30
  4570.3  506.95  4618.4  505.91  4658.8  505.64  4699.1  504.05  4729.4  503.78
  4759.6  502.92  4785.9  502.51  4800.8  502.71  4828.1  501.88  4871.2  501.79
  4881.3  501.30  4887.0  501.57  4902.8  500.80  4917.2  500.94  4924.4  501.40
  4961.8  501.18  4967.6  501.48  4989.1  500.08  4994.9  500.06  4995.4  499.26
  5000.4  499.26  5000.9  500.06  5004.9  500.50  5020.7  500.79  5042.3  500.16
  5069.6  501.34  5085.4  501.62  5157.7  502.51  5202.1  502.55  5254.3  503.48
#Mann=3,-1,0
  4570.3     0.1       0  4994.9    0.07       0  5000.9     0.1       0
Bank Sta=4994.9,5000.9
Exp/Cntr=0.3,0.1

Type RM Length L Ch R = 1,15544,844,844,844
BEGIN DESCRIPTION:
Mapping XS 9452f463
END DESCRIPTION:
XS GIS Cut Line= 4
      2058987.28     13498387.42      2058871.35     13498349.64
      2058468.70     13498429.29      2058375.97     13498681.61
#Sta/Elev= 30
  4734.8  504.04  4761.1  503.86  4787.8  502.60  4793.0  503.07  4863.4  501.13
  4924.4  500.50  4954.9  498.49  4985.5  497.84  4992.7  496.97  4993.2  496.17
  4998.2  496.17  4998.7  496.97  5012.1  499.78  5017.2  498.96  5056.9  500.64
  5063.3  499.29  5077.3  499.57  5114.6  498.74  5158.8  499.12  5179.2  500.07
  5212.8  499.29  5321.3  500.46  5351.8  500.24  5425.3  501.55  5486.3  502.55
  5493.5  503.31  5507.6  503.50  5518.3  505.08  5529.3  503.72  5536.0  503.54
#Mann=5,-1,0
  4734.8     0.1       0  4992.7    0.07       0  4998.7     0.1       0
  5212.8    0.05       0  5425.3     0.1       0
Bank Sta=4992.7,4998.7
Exp/Cntr=0.3,0.1

Type RM Length L Ch R = 1,14700,367,367,367
BEGIN DESCRIPTION:
Mapping XS de4f2a12
END DESCRIPTION:
XS GIS Cut Line= 4
      2058614.13     13497758.72      2058451.34     13497708.80
      2057856.72     13498092.91      2057871.85     13498220.45
#Sta/Elev= 30
  4586.5  502.50  4614.0  501.69  4619.2  502.41  4679.5  500.38  4756.8  499.95
  4795.0  498.34  4982.4  494.63  4990.5  494.42  5000.5  492.36  5001.0  491.56
  5006.0  491.56  5006.5  492.36  5018.6  493.78  5049.0  495.37  5054.9  496.44
  5070.1  494.59  5157.2  496.03  5228.6  495.64  5251.5  497.62  5257.5  496.59
  5264.3  498.11  5272.6  496.19  5314.9  496.14  5366.3  496.46  5387.5  497.31
  5395.3  496.57  5408.6  496.57  5527.2  498.03  5567.5  497.70  5593.1  498.70
#Mann=3,-1,0
  4586.5     0.1       0  5000.5    0.07       0  5006.5     0.1       0
Bank Sta=5000.5,5006.5
Exp/Cntr=0.3,0.1

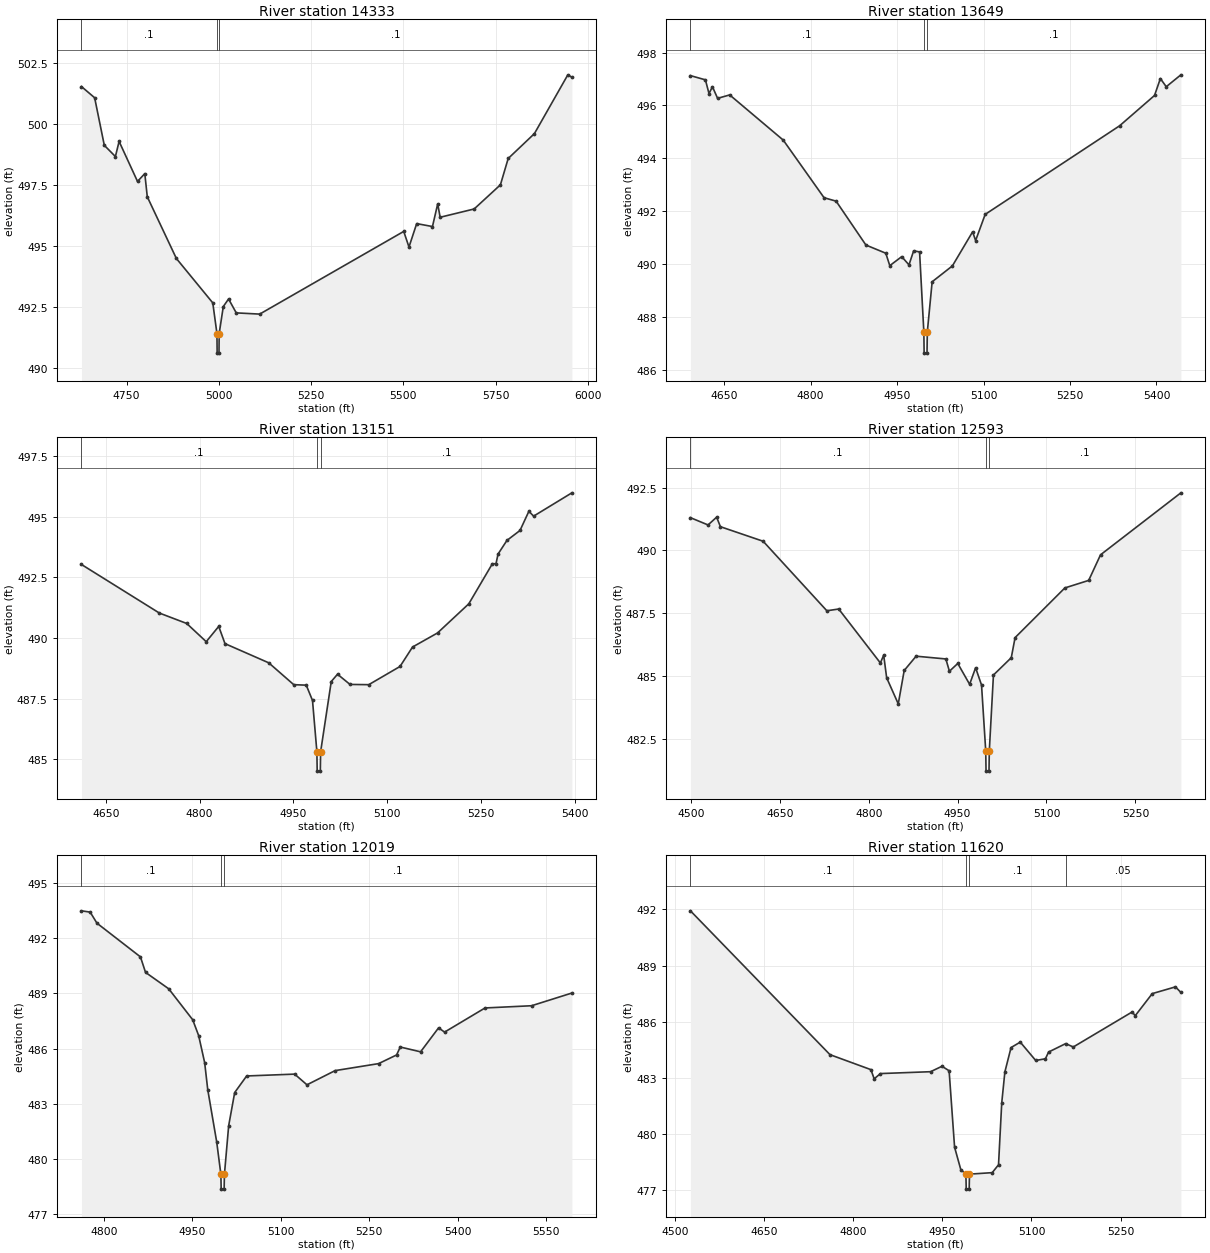
Type RM Length L Ch R = 1,14333,684,684,684
BEGIN DESCRIPTION:
Mapping XS 744e8694
END DESCRIPTION:
XS GIS Cut Line= 4
      2058316.77     13497407.15      2058158.37     13497420.17
      2057476.95     13498207.93      2057494.31     13498335.94
#Sta/Elev= 30
  4627.4  501.54  4663.2  501.08  4689.4  499.13  4719.5  498.67  4729.5  499.29
  4779.4  497.65  4799.2  497.97  4805.9  497.02  4884.8  494.49  4983.5  492.67
  4994.8  491.41  4995.3  490.61  5000.3  490.61  5000.8  491.41  5012.0  492.52
  5026.3  492.83  5047.1  492.26  5110.7  492.21  5501.2  495.60  5515.4  494.96
  5536.3  495.92  5579.1  495.80  5593.3  496.73  5599.9  496.18  5692.1  496.52
  5763.3  497.51  5784.4  498.59  5855.5  499.61  5946.1  502.02  5957.1  501.92
#Mann=3,-1,0
  4627.4     0.1       0  4994.8    0.07       0  5000.8     0.1       0
Bank Sta=4994.8,5000.8
Exp/Cntr=0.3,0.1

Type RM Length L Ch R = 1,13649,498,498,498
BEGIN DESCRIPTION:
Mapping XS 22c48ae0
END DESCRIPTION:
XS GIS Cut Line= 4
      2057648.14     13497313.45      2057516.01     13497508.16
      2057439.53     13497797.39      2057392.27     13498110.16
#Sta/Elev= 30
  4591.6  497.13  4617.6  496.97  4623.8  496.45  4629.8  496.71  4638.7  496.27
  4659.7  496.40  4752.6  494.69  4823.4  492.51  4844.3  492.38  4896.0  490.72
  4930.5  490.41  4937.4  489.94  4958.1  490.28  4970.7  489.97  4978.8  490.50
  4989.1  490.46  4996.5  487.43  4997.0  486.63  5002.0  486.63  5002.5  487.43
  5010.9  489.33  5046.0  489.93  5081.1  491.22  5086.3  490.89  5102.9  491.88
  5336.0  495.23  5396.7  496.38  5406.8  497.02  5417.0  496.71  5442.4  497.16
#Mann=3,-1,0
  4591.6     0.1       0  4996.5    0.07       0  5002.5     0.1       0
Bank Sta=4996.5,5002.5
Exp/Cntr=0.3,0.1

Type RM Length L Ch R = 1,13151,558,558,558
BEGIN DESCRIPTION:
Mapping XS 0ca21e99
END DESCRIPTION:
XS GIS Cut Line= 4
      2057190.50     13497331.19      2057029.90     13497418.00
      2057025.56     13497895.43      2057108.00     13497988.72
#Sta/Elev= 30
  4610.9  493.03  4735.5  491.03  4779.3  490.60  4810.5  489.85  4830.5  490.48
  4840.5  489.77  4910.5  488.98  4950.5  488.08  4970.5  488.06  4980.5  487.43
  4987.5  485.32  4988.0  484.52  4993.0  484.52  4993.5  485.32  5010.5  488.21
  5020.5  488.51  5040.5  488.09  5070.5  488.08  5120.5  488.83  5140.5  489.63
  5180.5  490.21  5230.5  491.41  5268.2  493.06  5274.0  493.06  5277.3  493.46
  5291.5  494.02  5312.4  494.43  5326.6  495.22  5334.2  495.02  5395.4  495.98
#Mann=3,-1,0
  4610.9     0.1       0  4987.5    0.07       0  4993.5     0.1       0
Bank Sta=4987.5,4993.5
Exp/Cntr=0.3,0.1

Type RM Length L Ch R = 1,12593,574,574,574
BEGIN DESCRIPTION:
Mapping XS 729f450a
END DESCRIPTION:
XS GIS Cut Line= 4
      2056673.97     13497292.15      2056578.51     13497365.92
      2056526.43     13497943.18      2056545.96     13498069.02
#Sta/Elev= 30
  4499.2  491.30  4528.9  491.01  4543.4  491.32  4549.8  490.94  4621.9  490.36
  4729.4  487.59  4749.4  487.66  4819.7  485.51  4825.3  485.82  4830.3  484.92
  4849.9  483.88  4859.9  485.21  4880.0  485.78  4930.2  485.67  4936.2  485.18
  4950.3  485.49  4970.3  484.66  4980.4  485.32  4990.4  484.63  4997.5  482.00
  4998.0  481.20  5003.0  481.20  5003.5  482.00  5010.5  485.03  5040.6  485.72
  5047.0  486.52  5131.0  488.50  5171.2  488.80  5191.2  489.82  5326.8  492.29
#Mann=3,-1,0
  4499.2     0.1       0  4997.5    0.07       0  5003.5     0.1       0
Bank Sta=4997.5,5003.5
Exp/Cntr=0.3,0.1

Type RM Length L Ch R = 1,12019,399,399,399
BEGIN DESCRIPTION:
Mapping XS b4f08b09
END DESCRIPTION:
XS GIS Cut Line= 4
      2056318.10     13497320.34      2056231.29     13497365.92
      2056124.95     13497936.66      2056246.45     13498029.96
#Sta/Elev= 30
  4761.9  493.47  4776.7  493.40  4788.2  492.80  4862.0  490.97  4870.6  490.13
  4909.9  489.24  4950.6  487.56  4960.7  486.70  4970.9  485.23  4976.1  483.77
  4991.3  480.93  4998.4  479.17  4998.9  478.37  5003.9  478.37  5004.4  479.17
  5011.6  481.81  5021.8  483.61  5042.1  484.51  5123.5  484.61  5144.4  484.03
  5192.1  484.80  5265.9  485.18  5296.4  485.65  5302.6  486.08  5337.1  485.82
  5367.6  487.12  5377.8  486.89  5446.4  488.20  5525.3  488.32  5593.7  489.01
#Mann=3,-1,0
  4761.9     0.1       0  4998.4    0.07       0  5004.4     0.1       0
Bank Sta=4998.4,5004.4
Exp/Cntr=0.3,0.1

Type RM Length L Ch R = 1,11620,54,54,54
BEGIN DESCRIPTION:
Mapping XS 088bc44e
END DESCRIPTION:
XS GIS Cut Line= 4
      2056196.24     13497277.47      2055866.40     13497395.74
      2055788.28     13497623.60      2055852.30     13497849.32
#Sta/Elev= 30
  4525.7  491.92  4760.7  484.24  4829.6  483.44  4835.1  482.95  4845.7  483.23
  4930.1  483.33  4949.3  483.62  4961.3  483.38  4970.5  479.30  4981.0  478.10
  4989.6  477.86  4990.1  477.06  4995.1  477.06  4995.6  477.86  5033.9  477.94
  5044.5  478.36  5049.9  481.66  5055.2  483.32  5065.6  484.62  5081.1  484.91
  5107.1  483.93  5123.5  484.02  5128.8  484.38  5157.6  484.83  5170.4  484.65
  5269.5  486.52  5274.7  486.32  5303.4  487.50  5342.5  487.86  5351.6  487.56
#Mann=4,-1,0
  4525.7     0.1       0  4989.6    0.07       0  4995.6     0.1       0
  5157.6    0.05       0
Bank Sta=4989.6,4995.6
Exp/Cntr=0.3,0.1

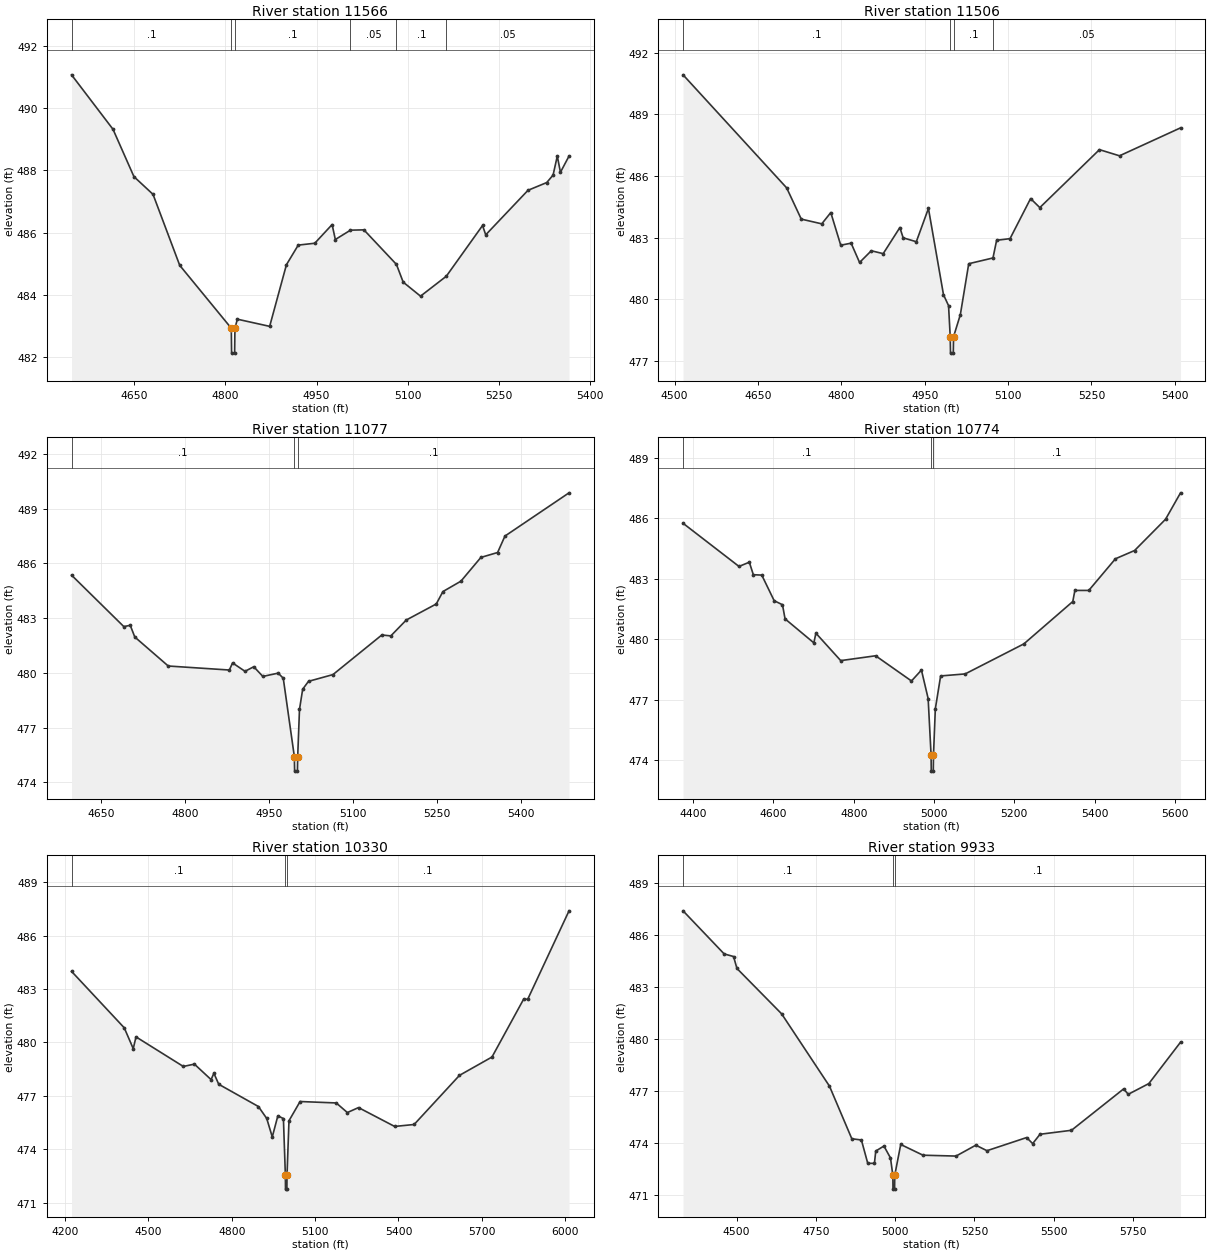
Type RM Length L Ch R = 1,11566,60,60,60
BEGIN DESCRIPTION:
Mapping XS 90929375
END DESCRIPTION:
XS GIS Cut Line= 4
      2056135.50     13497225.38      2055806.73     13497401.16
      2055726.43     13497681.11      2055764.30     13497830.43
#Sta/Elev= 30
  4547.0  491.07  4615.2  489.32  4649.6  487.80  4681.0  487.23  4724.9  484.95
  4809.7  482.93  4810.2  482.13  4815.2  482.13  4815.7  482.93  4819.7  483.22
  4872.8  482.99  4900.4  484.97  4919.8  485.60  4947.0  485.66  4975.5  486.26
  4980.8  485.78  5005.7  486.08  5027.8  486.09  5081.3  484.98  5092.4  484.41
  5120.9  483.96  5163.3  484.60  5222.9  486.23  5228.1  485.93  5297.6  487.36
  5328.5  487.61  5338.9  487.85  5345.8  488.46  5351.0  487.94  5365.1  488.46
#Mann=6,-1,0
  4547.0     0.1       0  4809.7    0.07       0  4815.7     0.1       0
  5005.7    0.05       0  5081.3     0.1       0  5163.3    0.05       0
Bank Sta=4809.7,4815.7
Exp/Cntr=0.3,0.1

Type RM Length L Ch R = 1,11506,429,429,429
BEGIN DESCRIPTION:
Mapping XS b75a66d2
END DESCRIPTION:
XS GIS Cut Line= 5
      2056117.03     13497180.90      2055847.96     13497270.95
      2055707.98     13497486.88      2055629.86     13497680.03
      2055713.40     13497799.38
#Sta/Elev= 30
  4515.2  490.92  4701.6  485.42  4727.9  483.90  4764.8  483.67  4781.0  484.22
  4798.9  482.63  4817.6  482.73  4832.8  481.79  4853.9  482.36  4875.3  482.22
  4905.3  483.49  4911.2  482.99  4934.9  482.80  4956.7  484.42  4983.8  480.22
  4992.9  479.69  4995.9  478.18  4996.4  477.38  5001.4  477.38  5001.9  478.18
  5014.1  479.25  5029.2  481.73  5072.8  482.01  5079.4  482.87  5103.5  482.95
  5140.5  484.90  5157.1  484.46  5264.4  487.28  5300.5  486.98  5410.3  488.34
#Mann=4,-1,0
  4515.2     0.1       0  4995.9    0.07       0  5001.9     0.1       0
  5072.8    0.05       0
Bank Sta=4995.9,5001.9
Exp/Cntr=0.3,0.1

Type RM Length L Ch R = 1,11077,303,303,303
BEGIN DESCRIPTION:
Mapping XS ced600e0
END DESCRIPTION:
XS GIS Cut Line= 4
      2055849.00     13496979.36      2055751.31     13496981.53
      2055154.53     13497307.05      2055167.54     13497417.68
#Sta/Elev= 30
  4597.5  485.36  4690.9  482.54  4702.4  482.61  4710.5  481.97  4770.3  480.38
  4879.5  480.16  4885.2  480.55  4907.4  480.09  4923.1  480.34  4939.3  479.81
  4966.8  479.99  4975.8  479.71  4995.6  475.42  4996.1  474.62  5001.1  474.62
  5001.6  475.42  5004.8  478.00  5010.5  479.11  5020.9  479.54  5064.6  479.91
  5151.9  482.08  5168.0  482.03  5195.6  482.90  5249.2  483.78  5261.1  484.46
  5293.3  485.03  5328.9  486.33  5358.8  486.60  5371.9  487.50  5486.4  489.87
#Mann=3,-1,0
  4597.5     0.1       0  4995.6    0.07       0  5001.6     0.1       0
Bank Sta=4995.6,5001.6
Exp/Cntr=0.3,0.1

Type RM Length L Ch R = 1,10774,444,444,444
BEGIN DESCRIPTION:
Mapping XS fe59aae4
END DESCRIPTION:
XS GIS Cut Line= 4
      2055924.93     13496864.34      2055677.53     13496801.41
      2054824.66     13497033.61      2054807.60     13497131.75
#Sta/Elev= 30
  4375.0  485.75  4514.3  483.61  4540.0  483.82  4550.0  483.20  4571.0  483.18
  4601.9  481.91  4622.6  481.71  4629.0  481.01  4700.7  479.82  4705.8  480.30
  4767.6  478.94  4854.5  479.18  4943.8  477.93  4968.6  478.47  4985.3  477.06
  4992.6  474.26  4993.1  473.46  4998.1  473.46  4998.6  474.26  5003.2  476.55
  5016.4  478.18  5077.5  478.28  5223.7  479.77  5345.5  481.87  5350.7  482.42
  5385.3  482.42  5451.7  483.99  5499.4  484.40  5576.5  485.95  5613.8  487.26
#Mann=3,-1,0
  4375.0     0.1       0  4992.6    0.07       0  4998.6     0.1       0
Bank Sta=4992.6,4998.6
Exp/Cntr=0.3,0.1

Type RM Length L Ch R = 1,10330,397,397,397
BEGIN DESCRIPTION:
Mapping XS 6c1bdf3a
END DESCRIPTION:
XS GIS Cut Line= 4
      2056081.15     13496634.27      2055957.48     13496465.04
      2054648.88     13496525.80      2054469.39     13496729.08
#Sta/Elev= 30
  4223.1  483.99  4412.8  480.82  4445.2  479.65  4455.2  480.31  4625.4  478.65
  4665.4  478.78  4725.5  477.91  4735.5  478.27  4752.9  477.65  4895.7  476.40
  4925.7  475.73  4945.7  474.69  4965.8  475.88  4985.8  475.72  4992.8  472.56
  4993.3  471.76  4998.3  471.76  4998.8  472.56  5005.8  475.60  5045.8  476.68
  5176.0  476.60  5216.0  476.06  5256.1  476.34  5386.2  475.28  5456.3  475.39
  5619.6  478.15  5736.6  479.18  5850.9  482.44  5865.1  482.42  6013.9  487.39
#Mann=3,-1,0
  4223.1     0.1       0  4992.8    0.07       0  4998.8     0.1       0
Bank Sta=4992.8,4998.8
Exp/Cntr=0.3,0.1

Type RM Length L Ch R = 1,9933,476,476,476
BEGIN DESCRIPTION:
Mapping XS 55d7aec0
END DESCRIPTION:
XS GIS Cut Line= 4
      2056043.87     13496021.22      2055439.95     13496090.98
      2054979.21     13496212.13      2054586.37     13496496.66
#Sta/Elev= 30
  4330.9  487.41  4460.6  484.92  4490.2  484.77  4500.9  484.08  4641.8  481.46
  4792.8  477.28  4863.3  474.24  4893.5  474.17  4913.6  472.82  4934.6  472.82
  4938.8  473.53  4964.6  473.82  4985.3  473.13  4992.7  472.13  4993.2  471.33
  4998.2  471.33  4998.7  472.13  5017.6  473.91  5087.9  473.29  5192.1  473.24
  5254.5  473.87  5289.6  473.55  5414.8  474.31  5433.8  473.96  5457.0  474.50
  5556.3  474.73  5720.7  477.12  5735.4  476.81  5800.4  477.43  5900.3  479.82
#Mann=3,-1,0
  4330.9     0.1       0  4992.7    0.07       0  4998.7     0.1       0
Bank Sta=4992.7,4998.7
Exp/Cntr=0.3,0.1

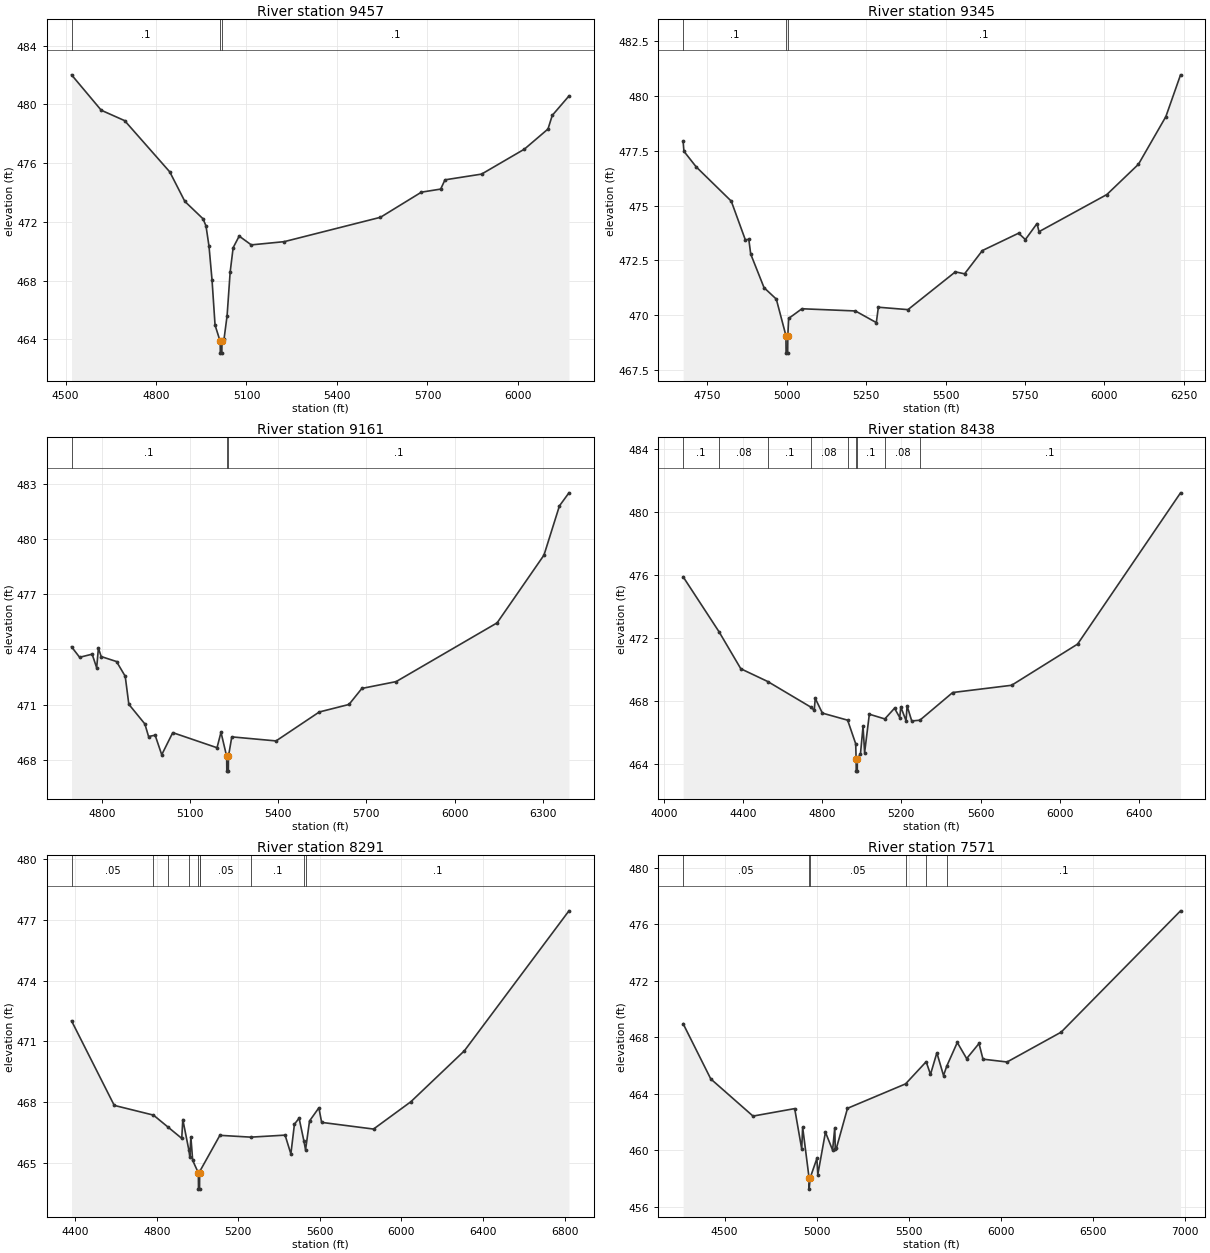
Type RM Length L Ch R = 1,9457,112,112,112
BEGIN DESCRIPTION:
Mapping XS 3037d70b
END DESCRIPTION:
XS GIS Cut Line= 4
      2055711.21     13495847.86      2055523.52     13495672.10
      2055165.45     13495659.08      2054509.21     13496457.71
#Sta/Elev= 30
  4520.0  482.02  4618.4  479.61  4696.1  478.90  4845.7  475.41  4895.7  473.40
  4955.8  472.22  4965.8  471.73  4975.8  470.34  4985.8  468.05  4995.8  464.98
  5012.8  463.87  5013.3  463.07  5018.3  463.07  5018.8  463.87  5025.8  464.06
  5035.8  465.63  5045.8  468.57  5055.8  470.25  5075.8  471.04  5115.9  470.44
  5225.0  470.66  5544.3  472.32  5679.9  474.03  5743.8  474.24  5758.1  474.87
  5879.4  475.26  6021.4  476.96  6099.6  478.33  6113.8  479.26  6169.1  480.58
#Mann=3,-1,0
  4520.0     0.1       0  5012.8    0.07       0  5018.8     0.1       0
Bank Sta=5012.8,5018.8
Exp/Cntr=0.3,0.1

Type RM Length L Ch R = 1,9345,184,184,184
BEGIN DESCRIPTION:
Mapping XS d823ff92
END DESCRIPTION:
XS GIS Cut Line= 4
      2055582.13     13495621.11      2055386.80     13495528.88
      2055017.88     13495637.38      2054426.33     13496401.51
#Sta/Elev= 30
  4673.5  477.92  4676.0  477.47  4714.6  476.76  4825.1  475.20  4869.4  473.44
  4880.4  473.46  4886.4  472.79  4928.4  471.26  4967.0  470.74  4997.3  469.08
  4997.8  468.28  5002.8  468.28  5003.3  469.08  5006.0  469.86  5047.7  470.30
  5216.1  470.20  5282.1  469.67  5288.5  470.37  5381.7  470.26  5531.1  471.98
  5560.1  471.89  5616.2  472.95  5730.3  473.74  5751.6  473.45  5788.3  474.18
  5794.6  473.81  6008.3  475.50  6107.9  476.88  6194.2  479.05  6240.4  480.95
#Mann=3,-1,0
  4673.5     0.1       0  4997.3    0.07       0  5003.3     0.1       0
Bank Sta=4997.3,5003.3
Exp/Cntr=0.3,0.1

Type RM Length L Ch R = 1,9161,723,723,723
BEGIN DESCRIPTION:
Mapping XS d492a8a0
END DESCRIPTION:
XS GIS Cut Line= 4
      2055482.61     13495414.98      2055352.38     13495334.67
      2054792.49     13495616.79      2054324.44     13496399.57
#Sta/Elev= 30
  4697.0  474.14  4724.5  473.57  4767.1  473.74  4782.5  473.00  4788.4  474.07
  4797.9  473.61  4850.0  473.34  4879.6  472.54  4891.9  471.02  4946.5  469.95
  4959.0  469.27  4981.4  469.34  5003.8  468.28  5041.3  469.48  5191.9  468.66
  5205.4  469.50  5224.7  468.19  5225.2  467.39  5230.3  467.39  5230.8  468.19
  5242.1  469.25  5392.7  469.03  5539.6  470.60  5640.8  471.01  5684.6  471.88
  5801.1  472.25  6144.6  475.44  6304.1  479.12  6356.6  481.79  6389.0  482.50
#Mann=3,-1,0
  4697.0     0.1       0  5224.7    0.07       0  5230.8     0.1       0
Bank Sta=5224.7,5230.8
Exp/Cntr=0.3,0.1

Type RM Length L Ch R = 1,8438,147,147,147
BEGIN DESCRIPTION:
Mapping XS 978c76a9
END DESCRIPTION:
XS GIS Cut Line= 4
      2055491.24     13495341.17      2054767.23     13495159.95
      2054377.69     13495031.91      2053996.00     13496334.24
#Sta/Elev= 30
  4097.3  475.90  4278.9  472.40  4388.8  470.05  4524.7  469.24  4742.7  467.61
  4759.7  467.41  4764.9  468.17  4800.9  467.23  4928.6  466.78  4969.3  465.28
  4971.5  464.34  4972.0  463.54  4977.2  463.54  4977.7  464.34  4993.4  464.63
  5006.4  466.39  5014.4  464.72  5038.2  467.16  5116.5  466.86  5165.4  467.54
  5191.9  466.95  5197.2  467.62  5223.7  466.75  5229.0  467.69  5252.5  466.73
  5293.7  466.78  5459.5  468.54  5757.1  469.00  6090.6  471.62  6610.8  481.24
#Mann=9,-1,0
  4097.3     0.1       0  4278.9    0.08       0  4524.7     0.1       0
  4742.7    0.08       0  4928.6     0.1       0  4971.5    0.07       0
  4977.7     0.1       0  5116.5    0.08       0  5293.7     0.1       0
Bank Sta=4971.5,4977.7
Exp/Cntr=0.3,0.1

Type RM Length L Ch R = 1,8291,720,720,720
BEGIN DESCRIPTION:
Mapping XS 689316f9
END DESCRIPTION:
XS GIS Cut Line= 4
      2055163.54     13495059.06      2054664.15     13495011.30
      2054143.56     13494867.26      2053553.28     13496134.63
#Sta/Elev= 30
  4381.9  472.01  4591.4  467.83  4783.6  467.35  4857.3  466.74  4922.5  466.20
  4927.7  467.13  4957.8  465.60  4962.0  465.27  4967.2  466.28  4976.1  465.11
  5004.1  464.49  5004.6  463.69  5009.8  463.69  5010.3  464.49  5011.6  464.58
  5109.6  466.35  5261.2  466.26  5429.4  466.36  5457.8  465.43  5475.2  466.90
  5498.1  467.20  5521.9  466.06  5529.8  465.63  5549.3  467.06  5595.1  467.71
  5608.7  466.99  5863.2  466.66  6046.2  468.01  6308.9  470.53  6821.8  477.45
#Mann=10,-1,0
  4381.9    0.05       0  4783.6    0.08       0  4857.3     0.1       0
  4957.8    0.08       0  5004.1    0.07       0  5010.3    0.08       0
  5011.6    0.05       0  5261.2     0.1       0  5521.9    0.08       0
  5529.8     0.1       0
Bank Sta=5004.1,5010.3
Exp/Cntr=0.3,0.1

Type RM Length L Ch R = 1,7571,60,60,60
BEGIN DESCRIPTION:
Mapping XS e3115d56
END DESCRIPTION:
XS GIS Cut Line= 6
      2054963.28     13494427.38      2054306.23     13494327.21
      2054211.62     13494346.31      2054199.46     13494404.47
      2054228.98     13494631.90      2053405.94     13496060.45
#Sta/Elev= 30
  4275.4  468.97  4425.4  465.06  4654.6  462.43  4880.6  462.96  4918.8  460.10
  4923.8  461.65  4958.6  458.06  4959.1  457.26  4964.8  458.06  5001.0  459.43
  5006.1  458.29  5047.5  461.29  5086.3  460.02  5098.1  461.61  5100.9  460.07
  5106.6  460.14  5167.1  462.98  5482.2  464.71  5594.0  466.28  5617.4  465.38
  5652.0  466.91  5688.1  465.30  5705.7  465.97  5762.8  467.64  5813.6  466.50
  5880.6  467.57  5902.2  466.46  6032.9  466.26  6326.0  468.37  6974.0  476.96
#Mann=6,-1,0
  4275.4    0.05       0  4958.6    0.03       0  4964.8    0.05       0
  5482.2     0.1       0  5594.0    0.08       0  5705.7     0.1       0
Bank Sta=4958.6,4964.8
Exp/Cntr=0.3,0.1