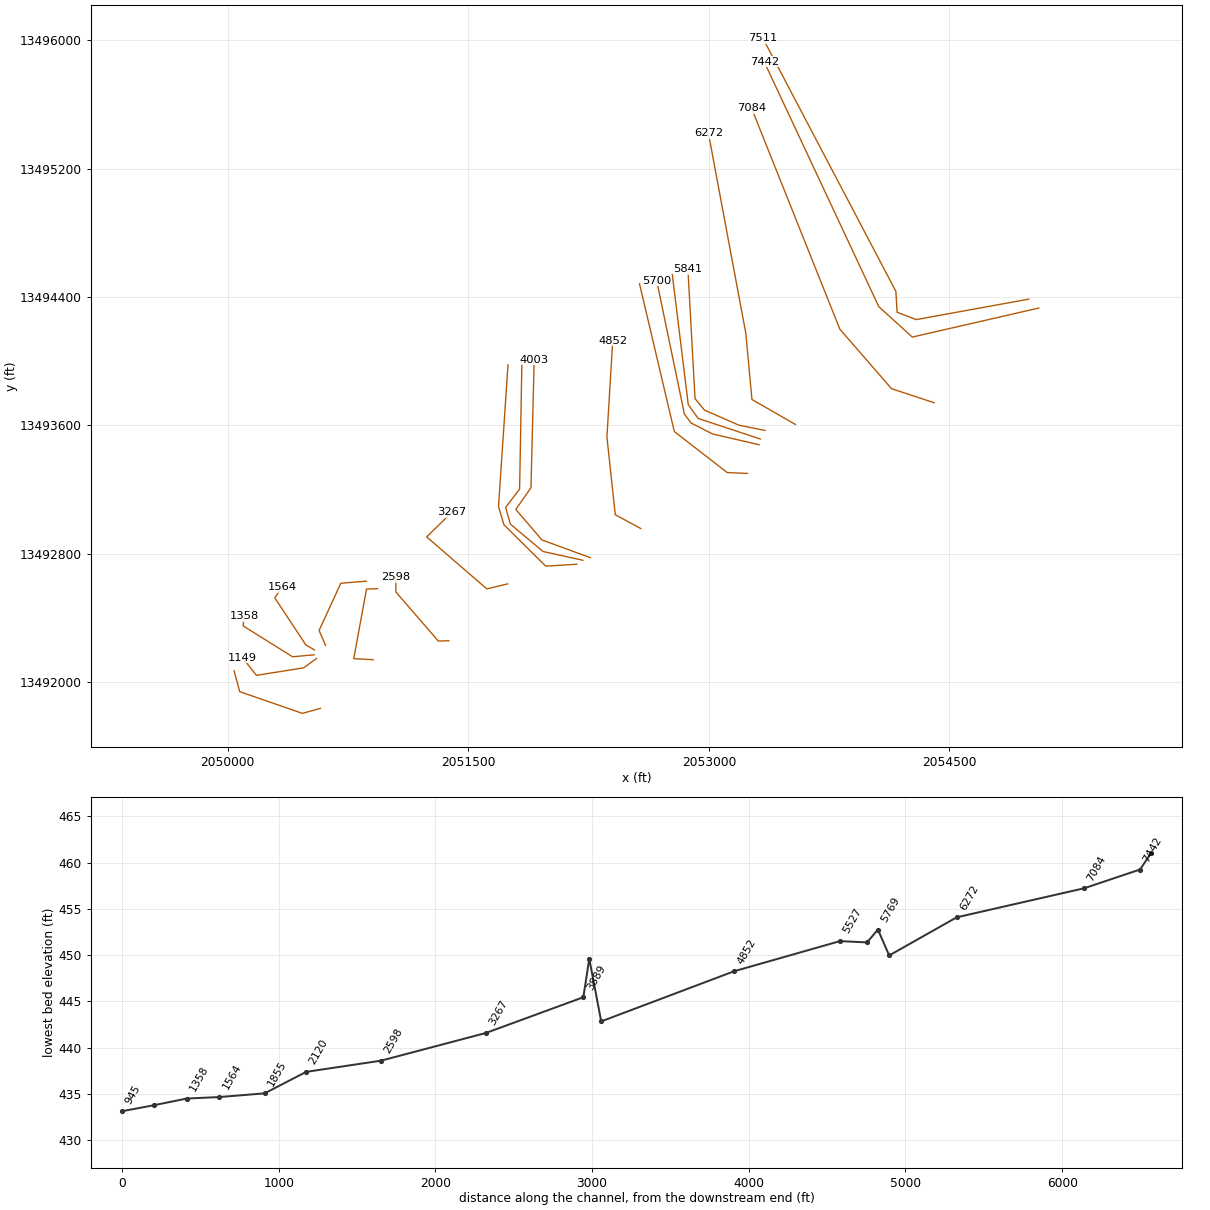
HEC-RAS study UNT 100 in Lagunillas Cr Wtrshd.prj: UNT 100 in Lagunillas Cr Wtrshd Base Level Engineering

--- UNT 100 in Lagunillas Cr Wtrshd.g01 (geometry) --- (continued)

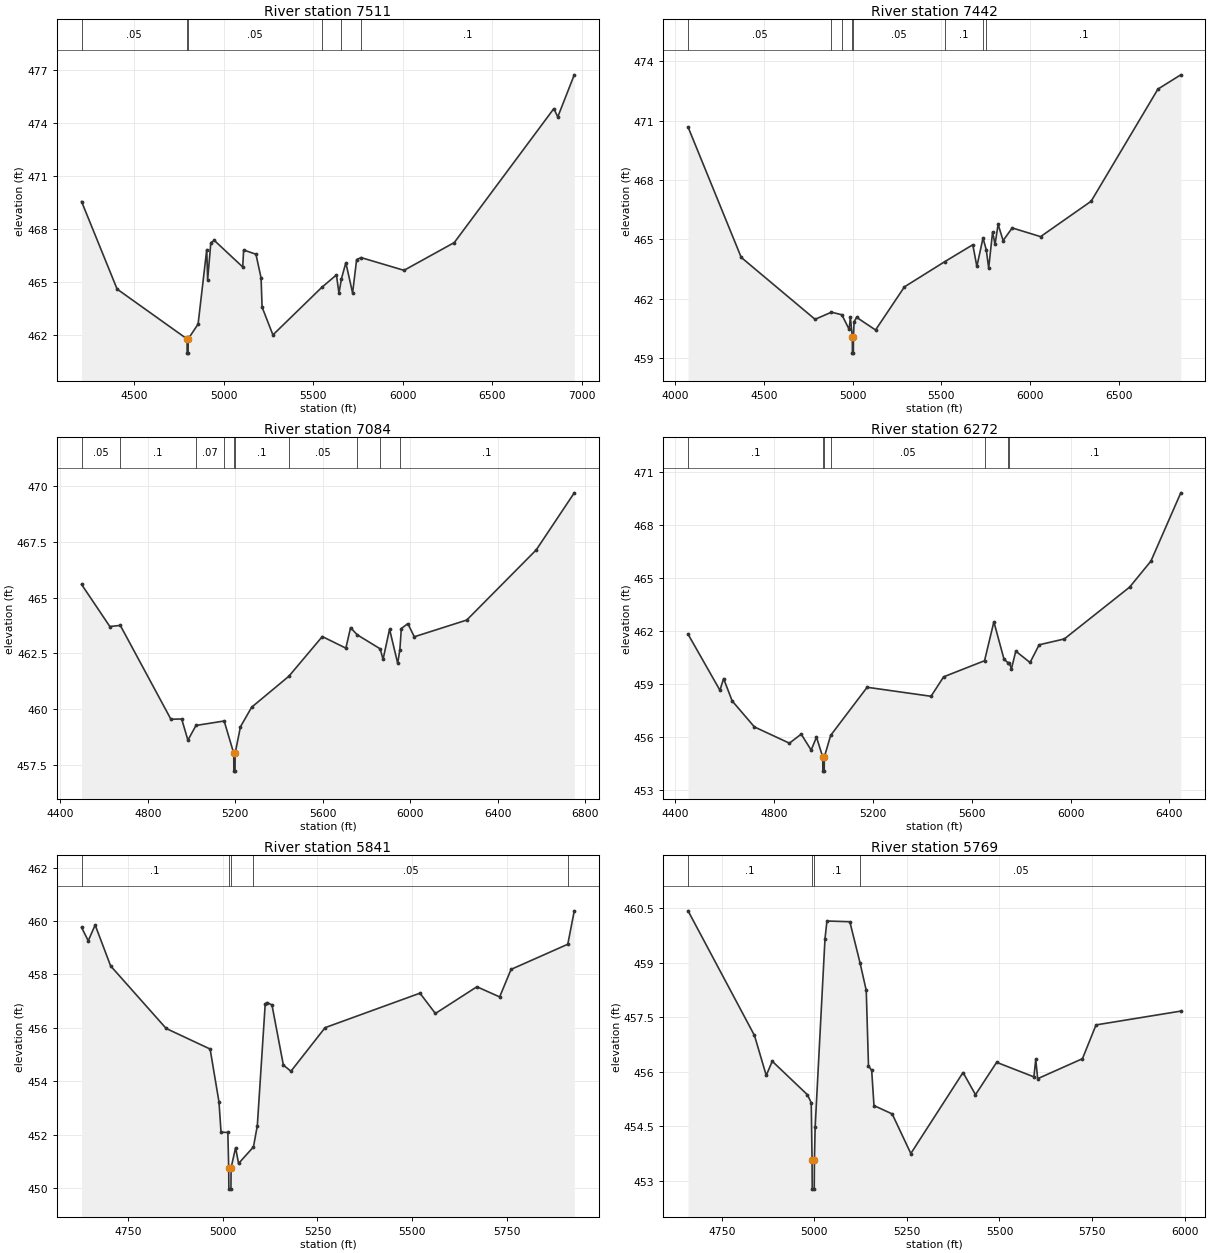
Type RM Length L Ch R = 1,7511,69,69,69
BEGIN DESCRIPTION:
Mapping XS 536f796f
END DESCRIPTION:
XS GIS Cut Line= 5
      2054994.53     13494385.71      2054293.05     13494258.26
      2054173.70     13494303.83      2054166.10     13494434.04
      2053337.10     13496011.52
#Sta/Elev= 30
  4205.1  469.56  4403.8  464.61  4794.7  461.79  4795.2  460.99  4800.4  460.99
  4800.9  461.79  4856.3  462.63  4904.6  466.84  4909.7  465.14  4927.5  467.23
  4946.9  467.36  5105.7  465.86  5110.7  466.82  5179.6  466.58  5208.2  465.24
  5213.9  463.59  5274.4  462.02  5547.8  464.71  5629.2  465.41  5643.5  464.38
  5657.4  465.20  5681.9  466.10  5719.6  464.39  5742.2  466.28  5767.0  466.39
  6006.9  465.67  6287.9  467.24  6844.1  474.81  6866.1  474.34  6958.3  476.72
#Mann=6,-1,0
  4205.1    0.05       0  4794.7    0.03       0  4800.9    0.05       0
  5547.8     0.1       0  5657.4    0.08       0  5767.0     0.1       0
Bank Sta=4794.7,4800.9
Exp/Cntr=0.3,0.1

Type RM Length L Ch R = 1,7442,358,358,358
BEGIN DESCRIPTION:
Mapping XS 1d4b1de5
END DESCRIPTION:
XS GIS Cut Line= 4
      2055057.03     13494330.16      2054268.41     13494149.25
      2054059.76     13494338.55      2053344.97     13495865.50
#Sta/Elev= 30
  4073.0  470.68  4372.6  464.09  4788.7  460.96  4881.3  461.32  4939.6  461.19
  4980.9  460.45  4987.7  461.08  4998.8  460.05  4999.3  459.25  5004.5  459.25
  5005.0  460.05  5008.6  460.83  5022.8  461.06  5129.6  460.42  5292.4  462.60
  5520.6  463.88  5677.8  464.73  5700.6  463.63  5735.2  465.07  5753.5  464.48
  5767.2  463.55  5789.3  465.38  5803.0  464.75  5820.3  465.76  5848.6  464.94
  5899.8  465.58  6059.7  465.14  6344.7  466.93  6721.1  472.60  6849.8  473.32
#Mann=8,-1,0
  4073.0    0.05       0  4881.3     0.1       0  4939.6    0.05       0
  4998.8    0.03       0  5005.0    0.05       0  5520.6     0.1       0
  5735.2    0.08       0  5753.5     0.1       0
Bank Sta=4998.8,5005
Exp/Cntr=0.3,0.1

Type RM Length L Ch R = 1,7084,812,812,812
BEGIN DESCRIPTION:
Mapping XS 7f887ee8
END DESCRIPTION:
XS GIS Cut Line= 4
      2054404.24     13493739.90      2054138.97     13493827.49
      2053816.71     13494198.58      2053266.82     13495574.74
#Sta/Elev= 30
  4497.2  465.60  4626.6  463.71  4674.4  463.76  4905.7  459.55  4955.0  459.56
  4983.5  458.61  5020.5  459.27  5149.2  459.47  5193.1  458.02  5193.6  457.22
  5198.9  457.22  5199.4  458.02  5223.7  459.21  5275.0  460.09  5445.3  461.48
  5598.0  463.26  5705.7  462.74  5727.2  463.66  5757.5  463.34  5862.4  462.71
  5875.8  462.24  5905.5  463.59  5942.6  462.06  5952.6  462.67  5959.3  463.62
  5989.0  463.84  6018.6  463.25  6258.3  464.00  6576.2  467.15  6750.0  469.71
#Mann=10,-1,0
  4497.2    0.05       0  4674.4     0.1       0  5020.5    0.07       0
  5149.2     0.1       0  5193.1    0.07       0  5199.4     0.1       0
  5445.3    0.05       0  5757.5     0.1       0  5862.4    0.08       0
  5952.6     0.1       0
Bank Sta=5193.1,5199.4
Exp/Cntr=0.3,0.1

Type RM Length L Ch R = 1,6272,431,431,431
BEGIN DESCRIPTION:
Mapping XS b6fbe6c2
END DESCRIPTION:
XS GIS Cut Line= 4
      2053539.66     13493604.49      2053268.75     13493760.21
      2053230.77     13494171.45      2052997.73     13495418.50
#Sta/Elev= 30
  4452.2  461.83  4581.2  458.66  4596.0  459.32  4630.6  458.06  4720.6  456.59
  4862.3  455.67  4910.1  456.18  4950.3  455.28  4972.0  456.01  4997.3  454.89
  4997.8  454.09  5003.2  454.09  5003.7  454.89  5029.3  456.11  5176.9  458.83
  5435.6  458.32  5486.5  459.42  5652.1  460.33  5689.9  462.53  5731.0  460.41
  5748.7  460.20  5751.7  460.22  5761.1  459.88  5778.5  460.87  5836.3  460.23
  5873.0  461.23  5974.8  461.56  6239.3  464.49  6325.4  465.96  6446.3  469.82
#Mann=7,-1,0
  4452.2     0.1       0  4997.3    0.07       0  5003.7     0.1       0
  5029.3    0.05       0  5652.1     0.1       0  5748.7    0.08       0
  5751.7     0.1       0
Bank Sta=4997.3,5003.7
Exp/Cntr=0.3,0.1

Type RM Length L Ch R = 1,5841,72,72,72
BEGIN DESCRIPTION:
Mapping XS 6535bf0a
END DESCRIPTION:
XS GIS Cut Line= 5
      2053350.17     13493567.06      2053188.45     13493599.62
      2052972.52     13493694.02      2052913.93     13493765.64
      2052869.65     13494571.57
#Sta/Elev= 30
  4627.5  459.76  4645.2  459.26  4663.4  459.85  4704.2  458.32  4850.8  455.98
  4966.8  455.21  4990.2  453.23  4995.6  452.10  5013.6  452.09  5015.8  450.77
  5016.3  449.97  5021.7  449.97  5022.2  450.77  5034.0  451.52  5041.9  450.93
  5081.2  451.55  5091.4  452.35  5112.2  456.90  5117.0  456.95  5130.0  456.86
  5160.1  454.61  5180.1  454.38  5270.2  456.01  5520.6  457.30  5561.3  456.54
  5670.8  457.54  5730.9  457.16  5761.0  458.19  5910.7  459.13  5927.8  460.38
#Mann=5,-1,0
  4627.5     0.1       0  5015.8    0.07       0  5022.2     0.1       0
  5081.2    0.05       0  5910.7    0.08       0
Bank Sta=5015.8,5022.2
Exp/Cntr=0.3,0.1

Type RM Length L Ch R = 1,5769,69,69,69
BEGIN DESCRIPTION:
Mapping XS e80134fe
END DESCRIPTION:
XS GIS Cut Line= 4
      2053320.83     13493513.90      2052933.46     13493641.94
      2052871.61     13493728.75      2052772.33     13494538.52
#Sta/Elev= 30
  4659.1  460.43  4838.4  457.00  4870.2  455.90  4886.4  456.29  4981.2  455.37
  4991.7  455.15  4993.9  453.57  4994.4  452.77  4999.8  452.77  5000.3  453.57
  5002.3  454.48  5028.8  459.66  5034.1  460.15  5095.9  460.13  5123.4  459.00
  5140.2  458.24  5146.3  456.16  5154.9  456.04  5161.1  455.07  5210.2  454.84
  5260.6  453.75  5401.6  455.98  5435.2  455.37  5492.3  456.26  5592.9  455.86
  5597.9  456.34  5603.1  455.81  5724.0  456.36  5760.7  457.29  5989.5  457.67
#Mann=4,-1,0
  4659.1     0.1       0  4993.9    0.07       0  5000.3     0.1       0
  5123.4    0.05       0
Bank Sta=4993.9,5000.3
Exp/Cntr=0.3,0.1

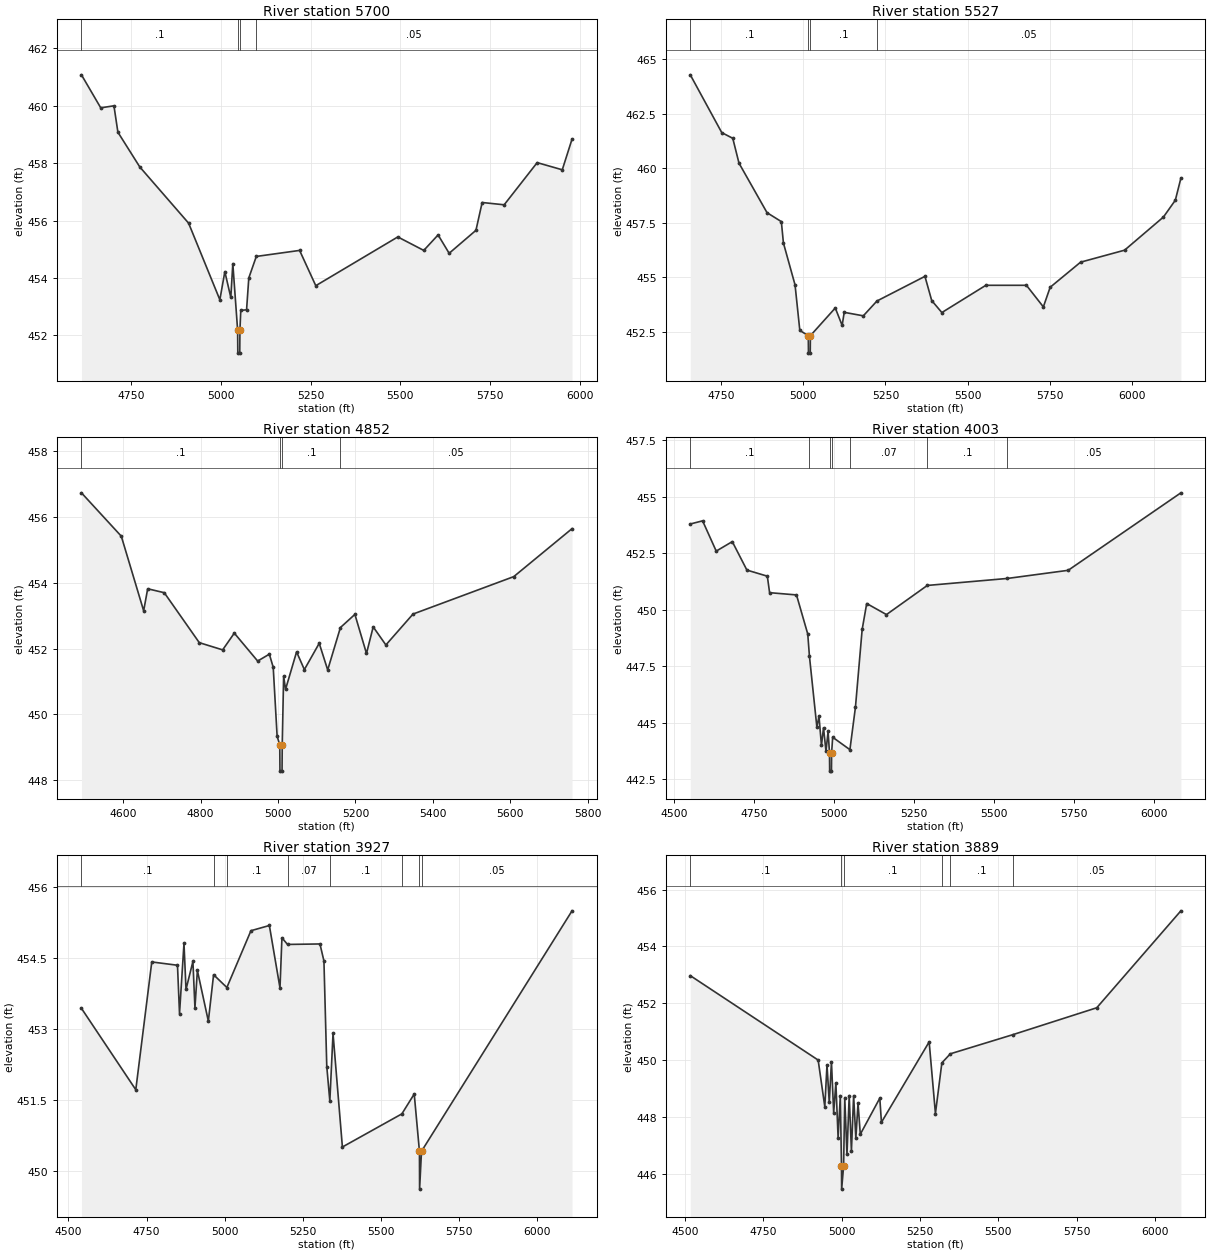
Type RM Length L Ch R = 1,5700,173,173,173
BEGIN DESCRIPTION:
Mapping XS 55e7fb6b
END DESCRIPTION:
XS GIS Cut Line= 5
      2053313.20     13493478.10      2053022.44     13493545.37
      2052888.97     13493613.73      2052847.74     13493669.07
      2052675.17     13494500.03
#Sta/Elev= 30
  4611.8  461.08  4665.5  459.93  4702.3  460.00  4713.3  459.08  4774.2  457.87
  4910.2  455.91  4997.2  453.24  5011.1  454.22  5027.7  453.32  5033.3  454.50
  5046.7  452.18  5047.2  451.38  5052.6  451.38  5053.1  452.18  5055.5  452.87
  5071.6  452.89  5077.8  454.00  5098.7  454.75  5219.3  454.96  5264.3  453.73
  5492.7  455.43  5565.0  454.96  5604.9  455.50  5635.7  454.86  5710.3  455.66
  5727.6  456.63  5788.9  456.55  5880.8  458.02  5950.7  457.77  5977.9  458.84
#Mann=4,-1,0
  4611.8     0.1       0  5046.7    0.07       0  5053.1     0.1       0
  5098.7    0.05       0
Bank Sta=5046.7,5053.1
Exp/Cntr=0.3,0.1

Type RM Length L Ch R = 1,5527,675,675,675
BEGIN DESCRIPTION:
Mapping XS b9848322
END DESCRIPTION:
XS GIS Cut Line= 4
      2053240.55     13493299.06      2053114.67     13493304.48
      2052784.81     13493560.56      2052567.83     13494481.45
#Sta/Elev= 30
  4657.4  464.28  4753.0  461.63  4786.4  461.37  4805.3  460.23  4890.4  457.96
  4933.9  457.55  4940.2  456.57  4975.5  454.65  4990.0  452.56  5015.7  452.32
  5016.2  451.52  5021.6  451.52  5022.1  452.32  5097.7  453.59  5118.5  452.79
  5124.8  453.39  5182.8  453.23  5224.2  453.91  5369.9  455.04  5390.5  453.93
  5421.3  453.38  5554.9  454.63  5678.1  454.63  5729.5  453.64  5750.2  454.54
  5842.5  455.69  5976.1  456.24  6094.1  457.76  6130.2  458.53  6147.1  459.54
#Mann=4,-1,0
  4657.4     0.1       0  5015.7    0.07       0  5022.1     0.1       0
  5224.2    0.05       0
Bank Sta=5015.7,5022.1
Exp/Cntr=0.3,0.1

Type RM Length L Ch R = 1,4852,849,849,849
BEGIN DESCRIPTION:
Mapping XS 490a94c3
END DESCRIPTION:
XS GIS Cut Line= 4
      2052575.59     13492955.75      2052416.75     13493041.68
      2052364.67     13493526.05      2052400.81     13494125.31
#Sta/Elev= 30
  4491.8  456.74  4594.8  455.42  4652.6  453.15  4663.0  453.82  4705.9  453.70
  4796.4  452.18  4856.8  451.96  4886.9  452.47  4947.3  451.62  4977.5  451.83
  4987.5  451.43  4997.6  449.33  5004.4  449.07  5004.9  448.27  5010.3  448.27
  5010.8  449.07  5014.4  451.16  5019.4  450.76  5047.9  451.90  5068.0  451.36
  5106.4  452.16  5128.3  451.35  5161.2  452.64  5198.6  453.04  5228.6  451.85
  5245.9  452.66  5278.7  452.11  5348.8  453.05  5609.3  454.19  5759.9  455.65
#Mann=4,-1,0
  4491.8     0.1       0  5004.4    0.07       0  5010.8     0.1       0
  5161.2    0.05       0
Bank Sta=5004.4,5010.8
Exp/Cntr=0.3,0.1

Type RM Length L Ch R = 1,4003,76,76,76
BEGIN DESCRIPTION:
Mapping XS ca34bec0
END DESCRIPTION:
XS GIS Cut Line= 5
      2052261.16     13492773.99      2051959.50     13492884.67
      2051796.74     13493074.56      2051891.15     13493210.19
      2051911.23     13494007.27
#Sta/Elev= 30
  4549.4  453.79  4587.9  453.93  4630.5  452.59  4680.7  453.01  4726.4  451.75
  4790.3  451.48  4797.4  450.75  4881.5  450.65  4916.7  448.92  4922.0  447.93
  4945.2  444.80  4951.8  445.28  4959.5  443.99  4966.0  444.77  4973.7  443.73
  4980.3  444.61  4984.7  443.65  4985.2  442.85  4990.8  442.85  4991.3  443.65
  4994.6  444.35  5048.5  443.80  5065.9  445.69  5086.8  449.12  5101.0  450.27
  5162.8  449.78  5290.5  451.07  5541.1  451.38  5731.0  451.74  6083.4  455.17
#Mann=7,-1,0
  4549.4     0.1       0  4922.0    0.05       0  4984.7   0.035       0
  4991.3    0.05       0  5048.5    0.07       0  5290.5     0.1       0
  5541.1    0.05       0
Bank Sta=4984.7,4991.3
Exp/Cntr=0.3,0.1

Type RM Length L Ch R = 1,3927,38,38,38
BEGIN DESCRIPTION:
Mapping XS 4d0a702a
END DESCRIPTION:
XS GIS Cut Line= 6
      2052214.95     13492757.82      2051966.23     13492812.51
      2051763.11     13492983.09      2051733.16     13493087.25
      2051820.40     13493201.84      2051834.83     13494000.20
#Sta/Elev= 30
  4541.7  453.44  4715.7  451.72  4766.9  454.42  4849.2  454.35  4855.7  453.33
  4870.0  454.81  4876.5  453.84  4898.6  454.43  4905.1  453.45  4912.9  454.24
  4948.0  453.17  4964.8  454.15  5007.3  453.88  5084.4  455.08  5143.4  455.19
  5177.4  453.87  5183.6  454.93  5201.5  454.79  5305.4  454.80  5318.1  454.44
  5327.2  452.21  5337.0  451.48  5347.2  452.91  5377.2  450.51  5567.6  451.21
  5607.2  451.63  5623.9  450.42  5624.4  449.62  5630.5  450.42  6112.5  455.50
#Mann=8,-1,0
  4541.7     0.1       0  4964.8    0.05       0  5007.3     0.1       0
  5201.5    0.07       0  5337.0     0.1       0  5567.6    0.05       0
  5623.9   0.035       0  5630.5    0.05       0
Bank Sta=5623.9,5630.5
Exp/Cntr=0.3,0.1

Type RM Length L Ch R = 1,3889,622,622,622
BEGIN DESCRIPTION:
Mapping XS edcd2744
END DESCRIPTION:
XS GIS Cut Line= 5
      2052177.18     13492733.09      2051983.16     13492721.37
      2051722.74     13492979.18      2051688.89     13493092.46
      2051748.03     13493976.03
#Sta/Elev= 30
  4517.4  452.97  4925.2  450.00  4946.4  448.36  4953.4  449.83  4960.6  448.51
  4967.6  449.94  4974.7  448.15  4981.7  449.20  4988.8  447.27  4995.9  448.75
  4999.6  446.26  5000.1  445.46  5006.3  446.26  5010.0  448.68  5017.1  446.68
  5024.2  448.75  5031.3  446.80  5038.3  448.75  5045.4  447.26  5052.4  448.48
  5059.6  447.39  5121.8  448.66  5127.0  447.81  5279.2  450.64  5299.2  448.12
  5319.7  449.90  5346.7  450.22  5545.1  450.89  5813.7  451.84  6082.0  455.25
#Mann=6,-1,0
  4517.4     0.1       0  4999.6    0.07       0  5006.3     0.1       0
  5319.7    0.07       0  5346.7     0.1       0  5545.1    0.05       0
Bank Sta=4999.6,5006.3
Exp/Cntr=0.3,0.1

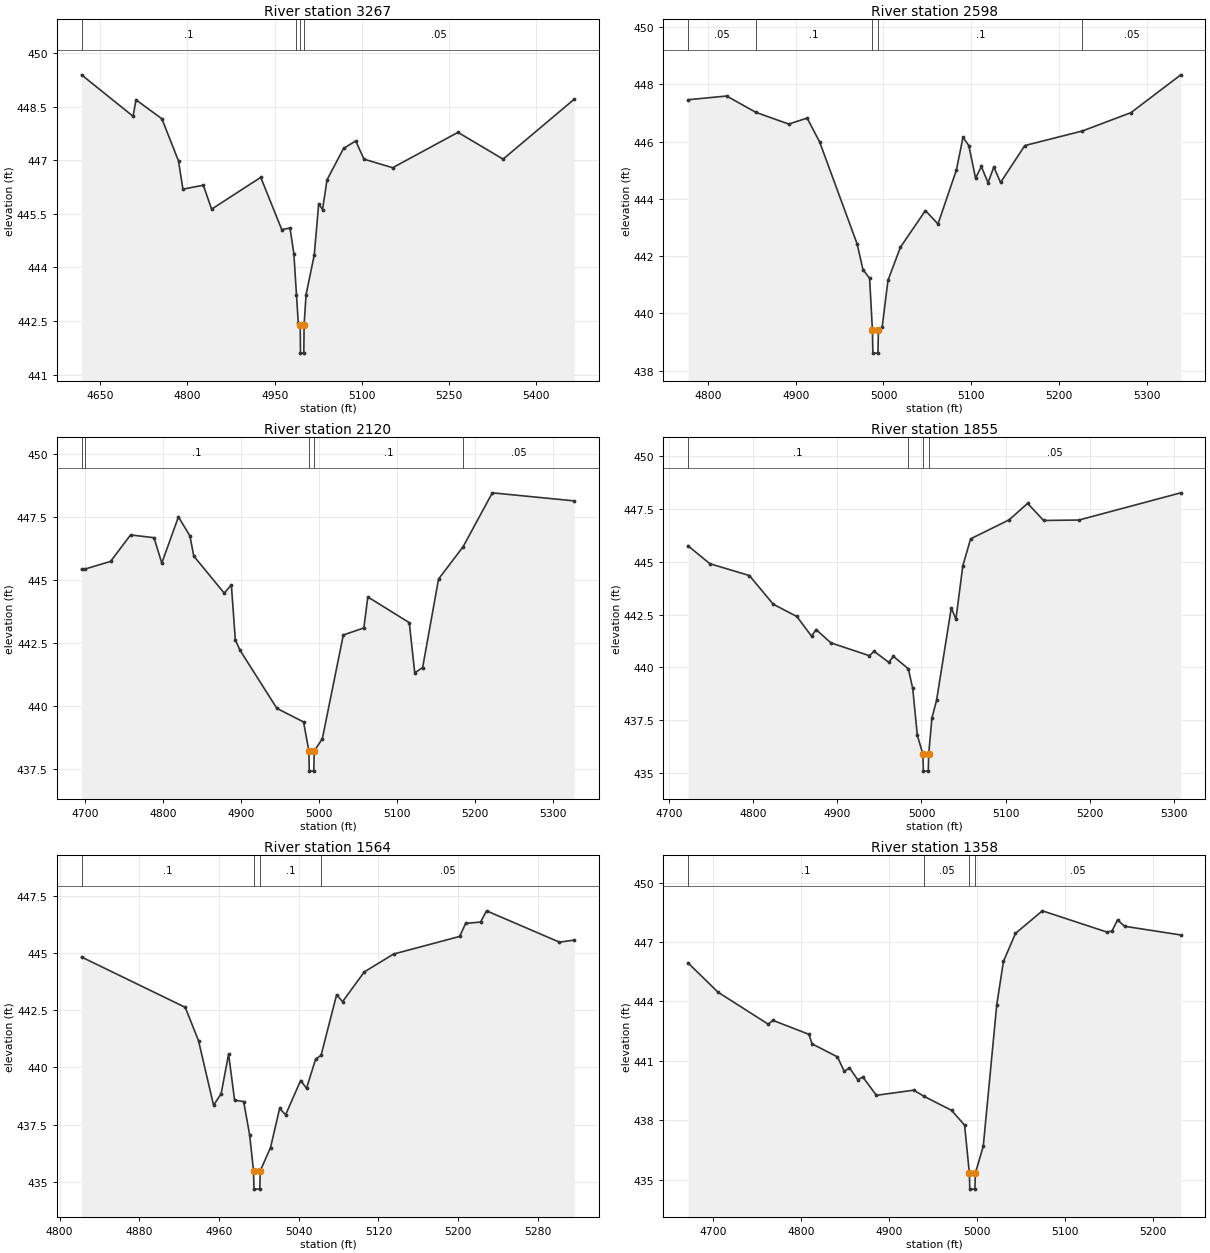
Type RM Length L Ch R = 1,3267,669,669,669
BEGIN DESCRIPTION:
Mapping XS b54f9af7
END DESCRIPTION:
XS GIS Cut Line= 4
      2051746.14     13492610.68      2051615.97     13492579.44
      2051240.97     13492903.66      2051397.20     13493055.99
#Sta/Elev= 30
  4617.8  449.39  4706.4  448.23  4711.5  448.69  4756.0  448.16  4784.6  446.98
  4792.2  446.19  4827.3  446.30  4841.6  445.63  4926.1  446.52  4962.2  445.06
  4976.5  445.10  4983.1  444.38  4987.6  443.23  4990.7  442.43  4994.0  442.40
  4994.5  441.60  5000.2  441.60  5000.7  442.40  5004.1  443.24  5018.2  444.35
  5025.8  445.78  5032.5  445.62  5040.1  446.45  5068.6  447.33  5089.5  447.54
  5103.7  447.03  5153.1  446.79  5265.4  447.78  5343.1  447.03  5465.6  448.71
#Mann=4,-1,0
  4617.8     0.1       0  4987.6    0.05       0  4994.0    0.03       0
  5000.7    0.05       0
Bank Sta=4994,5000.7
Exp/Cntr=0.3,0.1

Type RM Length L Ch R = 1,2598,478,478,478
BEGIN DESCRIPTION:
Mapping XS e46deb71
END DESCRIPTION:
XS GIS Cut Line= 4
      2051379.00     13492256.26      2051313.88     13492254.09
      2051049.12     13492560.08      2051049.12     13492651.69
#Sta/Elev= 30
  4777.3  447.46  4821.3  447.59  4854.6  447.02  4892.1  446.61  4913.0  446.82
  4927.2  445.99  4970.0  442.42  4976.6  441.53  4984.2  441.22  4987.4  439.41
  4987.9  438.61  4993.7  438.61  4994.2  439.41  4998.5  439.52  5005.1  441.15
  5019.3  442.31  5047.8  443.59  5062.1  443.12  5083.0  445.00  5090.6  446.15
  5097.2  445.86  5104.9  444.72  5111.5  445.13  5119.1  444.56  5125.7  445.11
  5133.4  444.57  5161.0  445.86  5226.7  446.37  5282.0  447.01  5338.7  448.33
#Mann=5,-1,0
  4777.3    0.05       0  4854.6     0.1       0  4987.4    0.07       0
  4994.2     0.1       0  5226.7    0.05       0
Bank Sta=4987.4,4994.2
Exp/Cntr=0.3,0.1

Type RM Length L Ch R = 1,2120,265,265,265
BEGIN DESCRIPTION:
Mapping XS 2aa246da
END DESCRIPTION:
XS GIS Cut Line= 4
      2050907.68     13492138.03      2050786.54     13492144.54
      2050865.97     13492578.14      2050935.00     13492580.74
#Sta/Elev= 30
  4695.7  445.40  4700.5  445.42  4732.9  445.72  4758.5  446.77  4788.5  446.66
  4798.5  445.65  4819.8  447.49  4834.5  446.73  4839.5  445.93  4878.5  444.46
  4887.6  444.79  4892.7  442.60  4898.8  442.19  4945.9  439.89  4980.1  439.35
  4986.9  438.20  4987.4  437.40  4993.2  437.40  4993.7  438.20  5004.1  438.68
  5031.0  442.80  5057.3  443.08  5062.4  444.31  5115.5  443.29  5122.5  441.30
  5132.6  441.51  5153.0  445.02  5184.4  446.30  5221.9  448.44  5326.9  448.12
#Mann=5,-1,0
  4695.7    0.05       0  4700.5     0.1       0  4986.9    0.07       0
  4993.7     0.1       0  5184.4    0.05       0
Bank Sta=4986.9,4993.7
Exp/Cntr=0.3,0.1

Type RM Length L Ch R = 1,1855,291,291,291
BEGIN DESCRIPTION:
Mapping XS 950edd90
END DESCRIPTION:
XS GIS Cut Line= 4
      2050610.64     13492227.01      2050570.40     13492320.33
      2050705.81     13492614.60      2050865.93     13492627.61
#Sta/Elev= 30
  4722.3  445.76  4748.3  444.91  4795.3  444.35  4823.7  442.99  4851.7  442.41
  4869.2  441.48  4874.7  441.79  4892.2  441.16  4938.1  440.55  4943.6  440.76
  4961.1  440.24  4966.6  440.52  4984.4  439.93  4989.6  439.00  4995.1  436.77
  5001.8  435.88  5002.3  435.08  5008.1  435.08  5008.6  435.88  5012.5  437.61
  5018.0  438.44  5035.5  442.82  5041.0  442.28  5049.2  444.81  5058.5  446.09
  5104.3  446.99  5126.3  447.77  5145.3  446.96  5187.2  446.98  5308.5  448.27
#Mann=4,-1,0
  4722.3     0.1       0  4984.4    0.05       0  5001.8    0.03       0
  5008.6    0.05       0
Bank Sta=5001.8,5008.6
Exp/Cntr=0.3,0.1

Type RM Length L Ch R = 1,1564,206,206,206
BEGIN DESCRIPTION:
Mapping XS cc5e7d2c
END DESCRIPTION:
XS GIS Cut Line= 4
      2050541.78     13492199.22      2050488.37     13492229.18
      2050294.36     13492523.45      2050339.52     13492590.55
#Sta/Elev= 30
  4822.0  444.83  4926.1  442.63  4939.4  441.17  4954.5  438.35  4962.1  438.85
  4969.6  440.59  4975.6  438.57  4984.7  438.51  4990.7  437.06  4994.6  435.48
  4995.1  434.68  5000.9  434.68  5001.4  435.48  5011.7  436.50  5020.8  438.21
  5026.8  437.93  5041.9  439.43  5047.8  439.09  5056.9  440.36  5062.4  440.53
  5078.0  443.18  5084.0  442.88  5105.8  444.18  5135.2  444.96  5201.5  445.73
  5207.5  446.30  5222.5  446.36  5228.5  446.85  5301.7  445.48  5316.6  445.57
#Mann=4,-1,0
  4822.0     0.1       0  4994.6    0.07       0  5001.4     0.1       0
  5062.4    0.05       0
Bank Sta=4994.6,5001.4
Exp/Cntr=0.3,0.1

Type RM Length L Ch R = 1,1358,209,209,209
BEGIN DESCRIPTION:
Mapping XS 866fd46b
END DESCRIPTION:
XS GIS Cut Line= 4
      2050538.98     13492168.43      2050405.03     13492156.26
      2050096.44     13492348.97      2050105.54     13492410.08
#Sta/Elev= 30
  4671.6  445.95  4705.7  444.47  4762.9  442.85  4767.9  443.05  4809.1  442.34
  4812.6  441.86  4841.5  441.20  4849.2  440.47  4855.1  440.65  4864.5  440.05
  4870.4  440.18  4885.7  439.26  4928.2  439.52  4939.8  439.21  4971.2  438.50
  4986.0  437.75  4991.4  435.32  4991.9  434.52  4997.7  434.52  4998.2  435.32
  5007.2  436.69  5022.5  443.82  5030.1  446.02  5043.8  447.44  5074.4  448.58
  5147.6  447.51  5153.5  447.56  5159.8  448.12  5167.8  447.80  5231.7  447.36
#Mann=4,-1,0
  4671.6     0.1       0  4939.8    0.05       0  4991.4    0.03       0
  4998.2    0.05       0
Bank Sta=4991.4,4998.2
Exp/Cntr=0.3,0.1

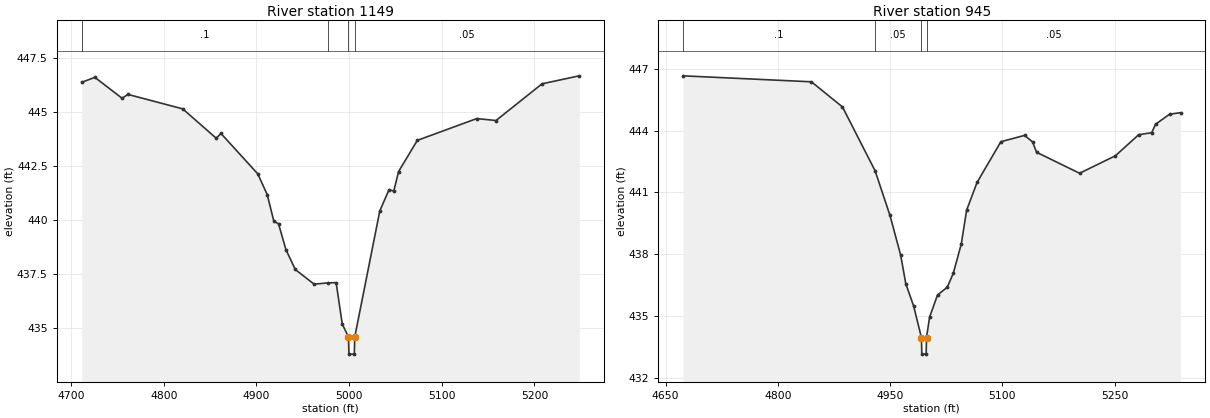
Type RM Length L Ch R = 1,1149,204,204,204
BEGIN DESCRIPTION:
Mapping XS 326fc241
END DESCRIPTION:
XS GIS Cut Line= 4
      2050554.78     13492145.85      2050474.04     13492087.25
      2050179.77     13492040.38      2050093.86     13492149.72
#Sta/Elev= 30
  4711.5  446.39  4725.6  446.62  4755.0  445.65  4761.2  445.83  4820.4  445.16
  4856.6  443.80  4861.7  444.02  4901.4  442.15  4911.6  441.19  4918.8  439.95
  4923.8  439.84  4931.8  438.64  4941.9  437.72  4962.2  437.04  4977.2  437.10
  4986.0  437.11  4992.6  435.19  4999.3  434.60  4999.8  433.80  5005.6  433.80
  5006.1  434.60  5033.1  440.43  5043.1  441.42  5048.2  441.35  5053.3  442.25
  5073.6  443.70  5137.7  444.71  5158.5  444.62  5208.2  446.32  5248.3  446.69
#Mann=4,-1,0
  4711.5     0.1       0  4977.2    0.05       0  4999.3    0.03       0
  5006.1    0.05       0
Bank Sta=4999.3,5006.1
Exp/Cntr=0.3,0.1

Type RM Length L Ch R = 1,945,198,198,198
BEGIN DESCRIPTION:
Mapping XS faf0d962
END DESCRIPTION:
XS GIS Cut Line= 4
      2050578.25     13491834.66      2050466.23     13491803.40
      2050075.61     13491938.81      2050040.45     13492069.02
#Sta/Elev= 30
  4673.5  446.66  4844.9  446.37  4886.4  445.15  4930.0  442.05  4949.9  439.88
  4964.2  437.95  4971.0  436.57  4981.6  435.47  4991.9  433.95  4992.4  433.15
  4998.2  433.15  4998.7  433.95  5002.8  434.95  5013.4  436.02  5026.5  436.40
  5034.5  437.08  5045.1  438.49  5052.3  440.14  5066.3  441.49  5098.0  443.46
  5129.8  443.77  5140.4  443.45  5145.7  442.95  5203.2  441.93  5251.1  442.78
  5282.1  443.80  5299.6  443.90  5304.7  444.31  5323.6  444.80  5338.1  444.87
#Mann=4,-1,0
  4673.5     0.1       0  4930.0    0.05       0  4991.9    0.03       0
  4998.7    0.05       0
Bank Sta=4991.9,4998.7
Exp/Cntr=0.3,0.1