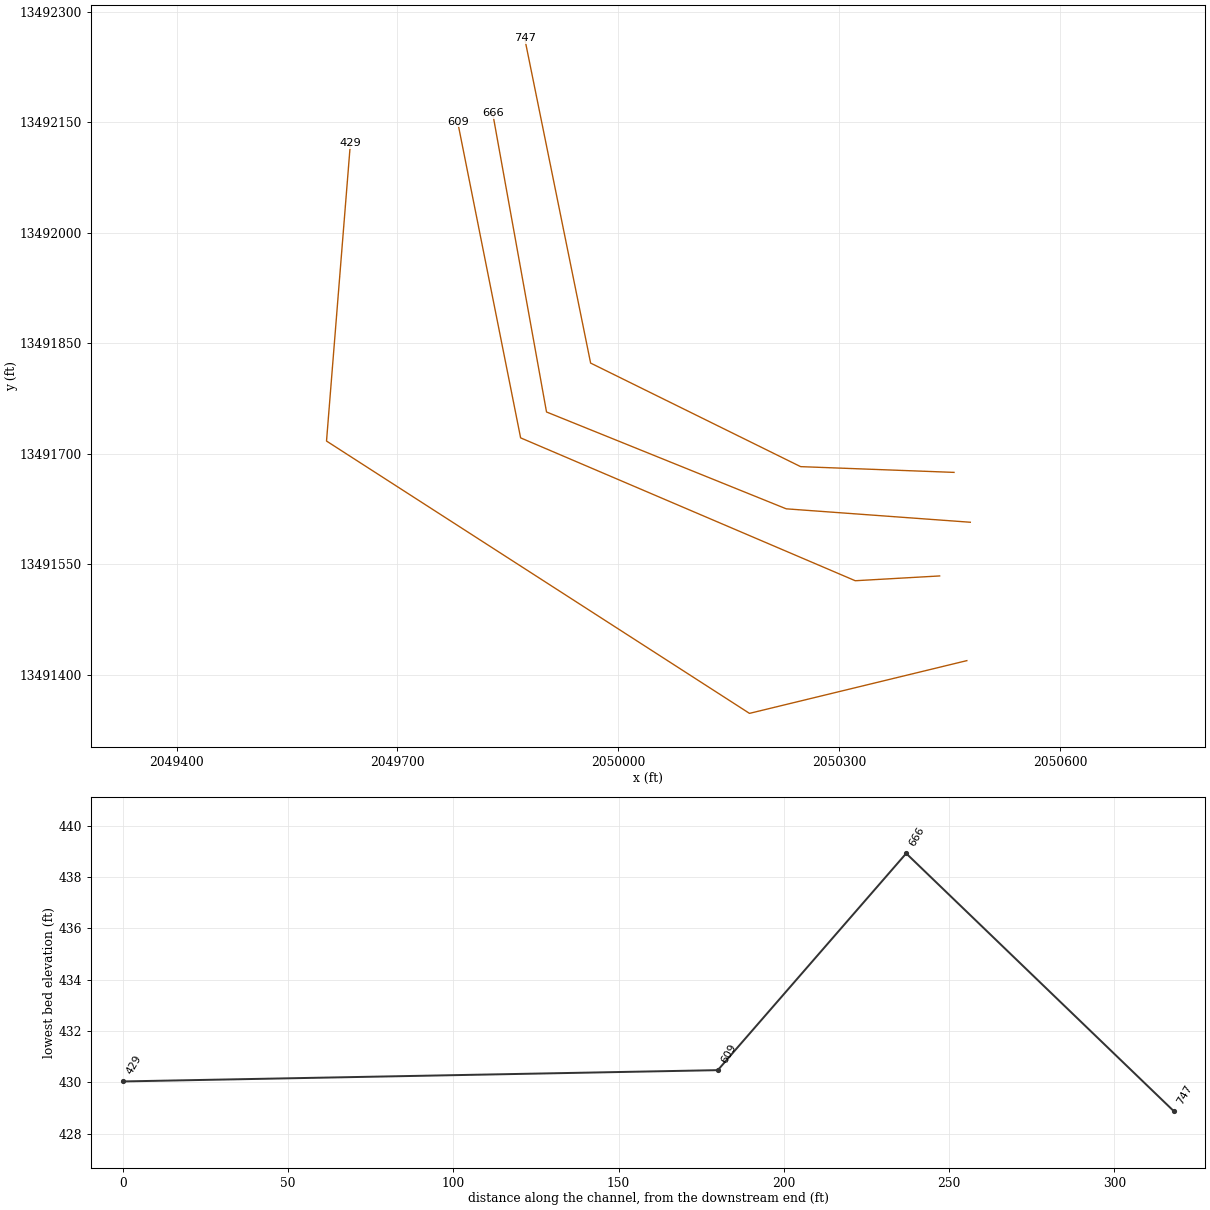
HEC-RAS study UNT 100 in Lagunillas Cr Wtrshd.prj: UNT 100 in Lagunillas Cr Wtrshd Base Level Engineering

--- UNT 100 in Lagunillas Cr Wtrshd.g01 (geometry) --- (continued)

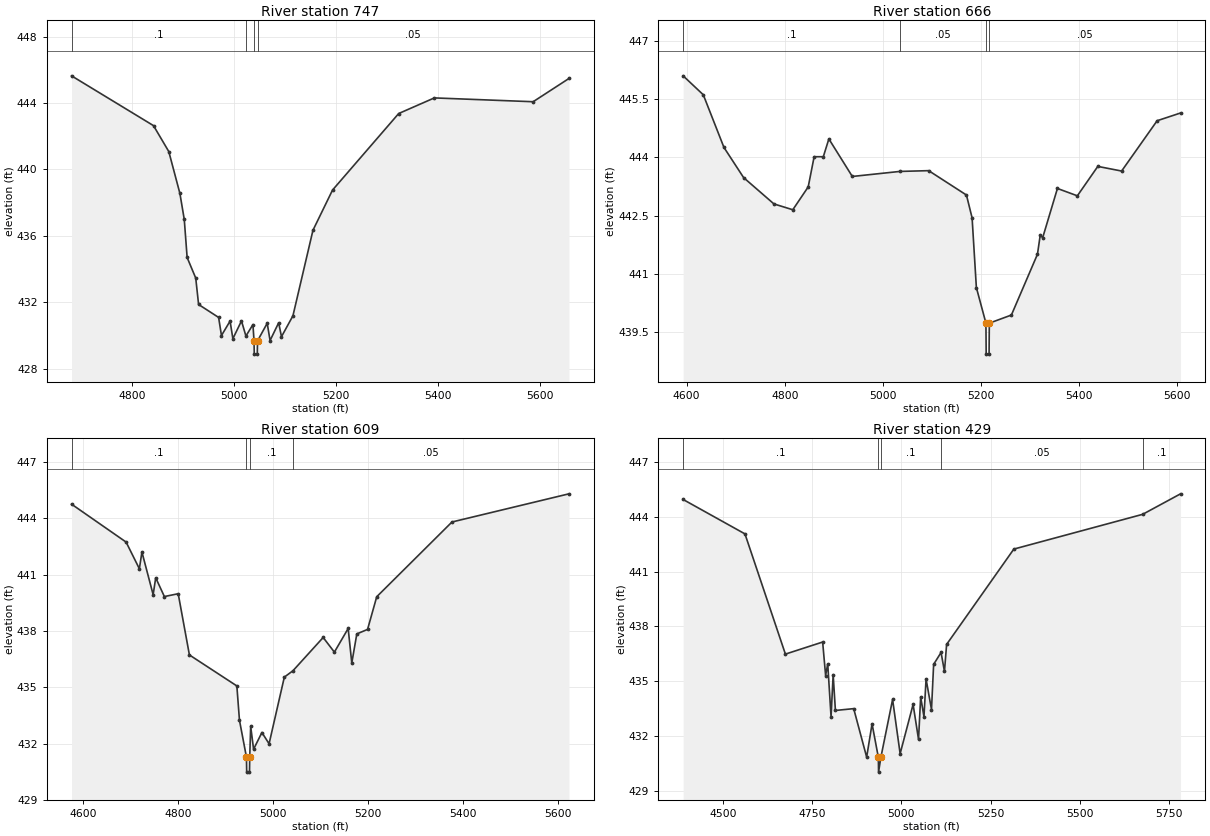
Type RM Length L Ch R = 1,747,81,81,81
BEGIN DESCRIPTION:
Mapping XS c8bb64ac
END DESCRIPTION:
XS GIS Cut Line= 4
      2050455.81     13491674.49      2050247.48     13491682.30
      2049962.32     13491822.93      2049872.79     13492263.91
#Sta/Elev= 30
  4680.8  445.64  4841.7  442.64  4871.7  441.08  4893.5  438.56  4902.1  436.99
  4907.7  434.70  4924.6  433.46  4930.2  431.87  4969.5  431.09  4975.1  430.00
  4992.0  430.87  4997.5  429.81  5014.4  430.88  5023.1  429.97  5036.9  430.66
  5039.0  429.68  5039.5  428.88  5045.4  428.88  5045.9  429.68  5064.9  430.74
  5070.5  429.70  5087.4  430.77  5092.9  429.93  5115.4  431.19  5154.7  436.34
  5193.1  438.76  5323.0  443.37  5393.0  444.31  5586.9  444.08  5657.2  445.48
#Mann=4,-1,0
  4680.8     0.1       0  5023.1    0.05       0  5039.0    0.07       0
  5045.9    0.05       0
Bank Sta=5039,5045.9
Exp/Cntr=0.3,0.1

Type RM Length L Ch R = 1,666,57,57,57
BEGIN DESCRIPTION:
Mapping XS a68856f2
END DESCRIPTION:
XS GIS Cut Line= 4
      2050477.93     13491606.78      2050227.95     13491625.01
      2049902.43     13491756.52      2049829.37     13492161.96
#Sta/Elev= 30
  4593.0  446.11  4634.1  445.62  4676.2  444.26  4716.3  443.48  4778.1  442.80
  4816.5  442.65  4847.9  443.24  4860.0  444.02  4878.7  444.02  4890.0  444.48
  4937.8  443.51  5034.6  443.64  5093.4  443.66  5170.4  443.03  5181.9  442.44
  5190.6  440.64  5210.1  439.72  5210.6  438.92  5216.5  438.92  5217.0  439.72
  5262.0  439.93  5315.1  441.50  5320.7  441.99  5325.8  441.93  5355.8  443.20
  5396.4  443.01  5438.1  443.77  5486.6  443.65  5559.0  444.95  5606.7  445.15
#Mann=4,-1,0
  4593.0     0.1       0  5034.6    0.05       0  5210.1    0.07       0
  5217.0    0.05       0
Bank Sta=5210.1,5217
Exp/Cntr=0.3,0.1

Type RM Length L Ch R = 1,609,180,180,180
BEGIN DESCRIPTION:
Mapping XS 883698be
END DESCRIPTION:
XS GIS Cut Line= 4
      2050436.27     13491533.87      2050321.70     13491527.36
      2049867.27     13491721.37      2049781.74     13492150.56
#Sta/Elev= 30
  4575.9  444.75  4690.7  442.73  4718.6  441.31  4724.0  442.20  4747.6  439.93
  4753.0  440.83  4771.2  439.83  4800.3  439.98  4823.9  436.72  4923.7  435.07
  4929.2  433.24  4943.9  431.28  4944.4  430.48  4950.3  430.48  4950.8  431.28
  4952.8  432.92  4958.9  431.70  4976.4  432.59  4991.5  431.99  5023.6  435.54
  5041.8  435.88  5105.3  437.65  5128.9  436.87  5157.9  438.13  5165.5  436.29
  5176.1  437.84  5198.7  438.08  5218.0  439.82  5376.3  443.80  5622.4  445.30
#Mann=4,-1,0
  4575.9     0.1       0  4943.9    0.07       0  4950.8     0.1       0
  5041.8    0.05       0
Bank Sta=4943.9,4950.8
Exp/Cntr=0.3,0.1

Type RM Length L Ch R = 1,429,0,0,0
BEGIN DESCRIPTION:
UNT 100 in Lagunillas Cr Wtrshd 1.0
END DESCRIPTION:
XS GIS Cut Line= 4
      2050473.21     13491418.86      2050178.04     13491347.24
      2049603.68     13491717.05      2049636.12     13492121.40
#Sta/Elev= 30
  4389.1  444.94  4562.2  443.06  4675.4  436.49  4779.7  437.15  4788.0  435.32
  4793.9  435.96  4803.2  433.07  4809.1  435.37  4815.4  433.41  4866.6  433.51
  4902.9  430.86  4918.0  432.68  4935.7  430.84  4936.2  430.04  4942.6  430.84
  4975.5  434.01  4996.6  431.05  5032.9  433.74  5048.1  431.83  5054.1  434.15
  5063.3  433.07  5069.2  435.13  5084.4  433.46  5090.4  435.93  5111.2  436.58
  5120.7  435.54  5126.7  437.02  5314.9  442.23  5675.6  444.13  5781.6  445.25
#Mann=5,-1,0
  4389.1     0.1       0  4935.7    0.07       0  4942.6     0.1       0
  5111.2    0.05       0  5675.6     0.1       0
Bank Sta=4935.7,4942.6
Exp/Cntr=0.3,0.1

Chan Stop Cuts=-1