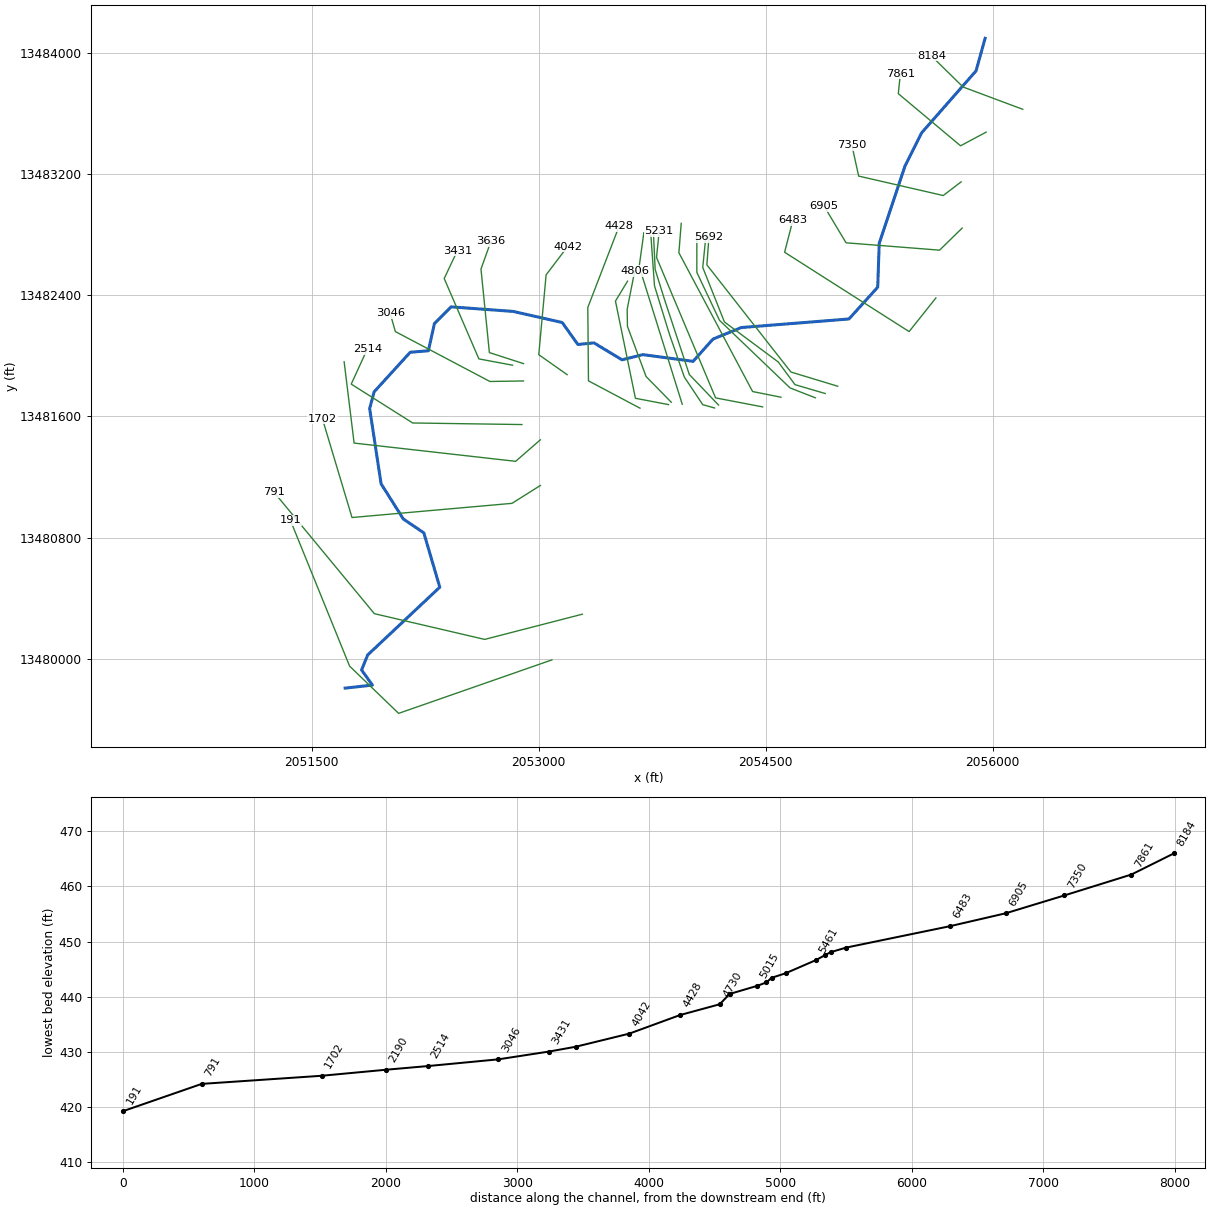
--- UNT 102 in Lagunillas Cr Wtrshd.prj (project) ---

Proj Title=UNT 102 in Lagunillas Cr Wtrshd Base Level Engineering
Current Plan=p01
Default Exp/Contr=0.3,0.1
English Units
Geom File=g01
Flow File=f01
Plan File=p01
BEGIN DESCRIPTION:
UNT 102 in Lagunillas Cr Wtrshd
END DESCRIPTION:

--- UNT 102 in Lagunillas Cr Wtrshd.p01 (plan) ---

Plan Title=Multiple Run
Short Identifier=Multiple
Geom File=g01
Flow File=f01
Subcritical Flow
K Sum by GR= 0
Std Step Tol= 0.01
Critical Tol= 0.01
Num of Std Step Trials= 20
Max Error Tol= 0.3
Flow Tol Ratio= 0.001
Split Flow NTrial= 30
Split Flow Tol= 0.02
Split Flow Ratio= 0.02
Log Output Level= 0
Friction Slope Method= 1
Unsteady Friction Slope Method= 2
Unsteady Bridges Friction Slope Method= 1
Parabolic Critical Depth
Global Vel Dist=  1 , 1 , 1
Global Log Level= 0
CheckData=True
Encroach Param= -1, 0, 0, 0
BEGIN DESCRIPTION:
Multiple Run
END DESCRIPTION:

--- UNT 102 in Lagunillas Cr Wtrshd.f01 (steady flow) ---

Flow Title=Multiple
Number of Profiles=7
Profile Names=10-year,25-year,50-year,1pct_min,100-year,1pct_plu,500-year
River Rch & RM= UNT 102 in Lagun,Reach-1,8184
     101     132     157      93     185     369     261
Boundary for River Rch & Prof#=UNT 102 in Lagun,Reach-1,1
Up Type=0
Dn Type=3
Dn Slope=0.005
Boundary for River Rch & Prof#=UNT 102 in Lagun,Reach-1,2
Up Type=0
Dn Type=3
Dn Slope=0.005
Boundary for River Rch & Prof#=UNT 102 in Lagun,Reach-1,3
Up Type=0
Dn Type=3
Dn Slope=0.005
Boundary for River Rch & Prof#=UNT 102 in Lagun,Reach-1,4
Up Type=0
Dn Type=3
Dn Slope=0.005
Boundary for River Rch & Prof#=UNT 102 in Lagun,Reach-1,5
Up Type=0
Dn Type=3
Dn Slope=0.005
Boundary for River Rch & Prof#=UNT 102 in Lagun,Reach-1,6
Up Type=0
Dn Type=3
Dn Slope=0.005
Boundary for River Rch & Prof#=UNT 102 in Lagun,Reach-1,7
Up Type=0
Dn Type=3
Dn Slope=0.005

--- UNT 102 in Lagunillas Cr Wtrshd.g01 (geometry) ---

Geom Title=Existing Conditions

River Reach=UNT 102 in Lagun,Reach-1
Reach XY= 30
      2055950.80     13484099.54      2055890.80     13483884.54
      2055530.80     13483474.54      2055420.80     13483254.54
      2055250.80     13482744.54      2055240.80     13482454.54
      2055050.80     13482244.54      2054339.27     13482187.85
      2054151.77     13482111.46      2054020.80     13481964.54
      2053688.41     13482008.79      2053550.80     13481974.54
      2053365.59     13482086.39      2053258.82     13482075.97
      2053155.23     13482221.22      2052830.80     13482294.54
      2052420.80     13482324.54      2052310.80     13482214.54
      2052270.80     13482034.54      2052150.80     13482024.54
      2051912.17     13481762.88      2051882.66     13481652.64
      2051958.18     13481155.24      2052105.31     13480922.17
      2052240.73     13480831.02      2052346.20     13480471.65
      2051869.64     13480023.73      2051829.27     13479924.77
      2051900.80     13479824.54      2051720.80     13479804.54

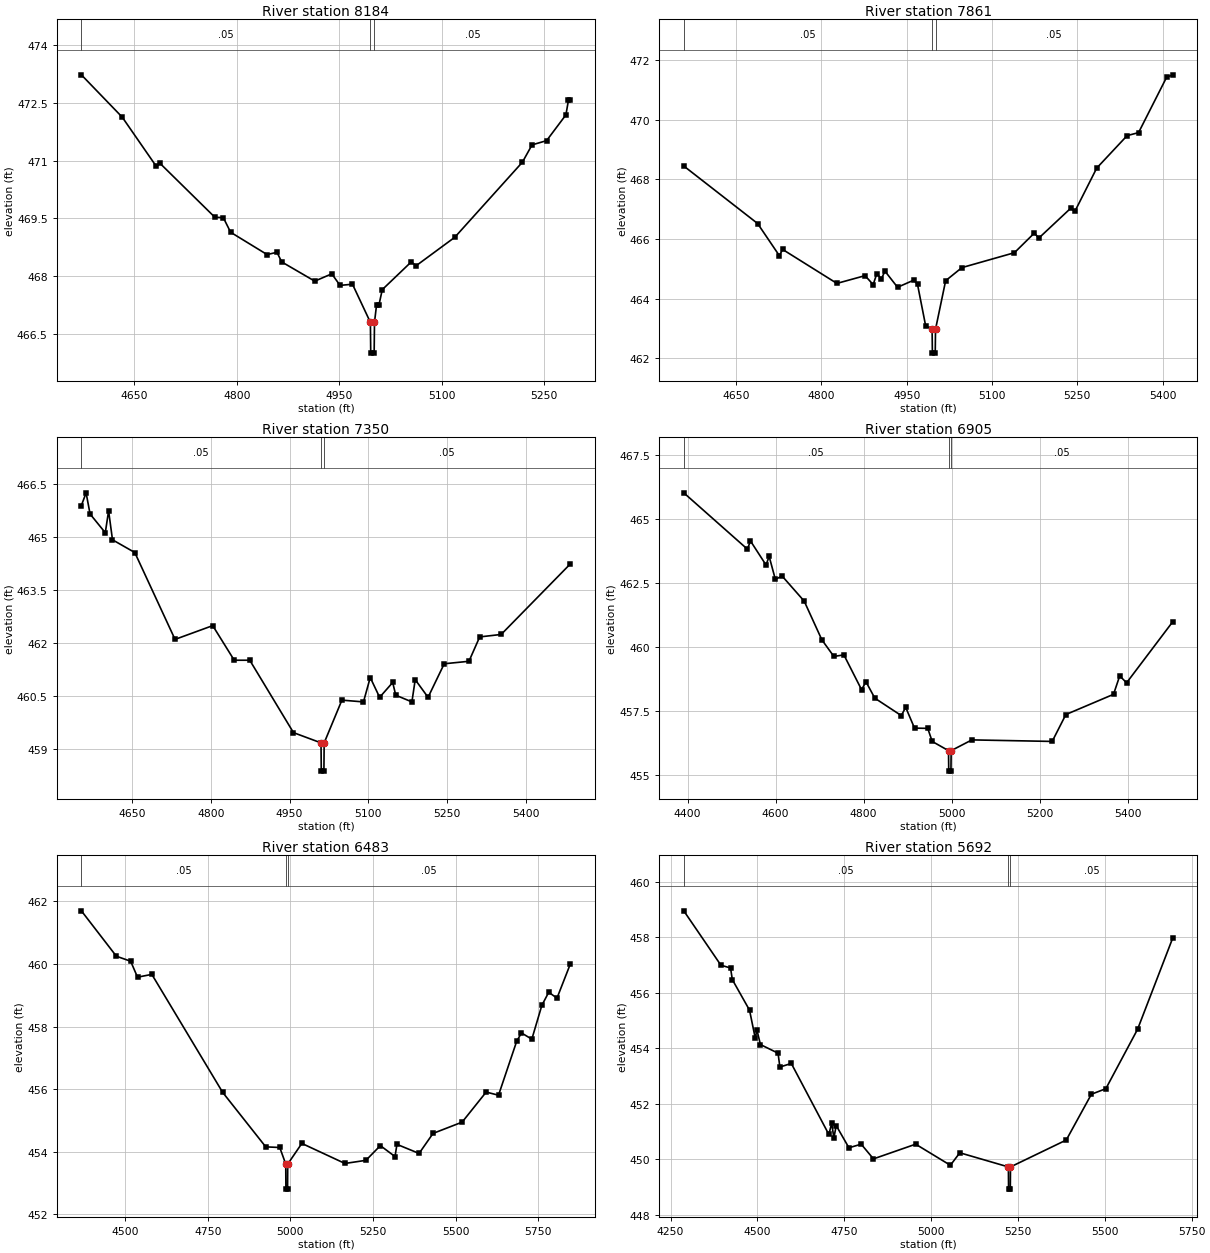
Type RM Length L Ch R = 1,8184,323,323,323
BEGIN DESCRIPTION:
Mapping XS 222bebde
END DESCRIPTION:
XS GIS Cut Line= 4
      2056199.61     13483630.43      2055807.22     13483776.99
      2055794.81     13483787.85      2055594.72     13483984.06
#Sta/Elev= 30
  4572.6  473.23  4632.4  472.13  4682.3  470.85  4687.7  470.93  4767.9  469.53
  4780.3  469.52  4791.0  469.14  4844.4  468.56  4858.8  468.62  4865.7  468.37
  4914.1  467.87  4939.0  468.06  4951.1  467.76  4969.3  467.79  4995.5  466.80
  4996.0  466.00  5001.0  466.00  5001.5  466.80  5004.5  467.25  5008.0  467.25
  5012.9  467.65  5055.3  468.37  5062.4  468.27  5119.0  469.01  5217.9  470.96
  5232.0  471.41  5253.3  471.52  5281.6  472.19  5285.3  472.57  5288.2  472.57
#Mann=3,-1,0
  4572.6    0.05       0  4995.5    0.03       0  5001.5    0.05       0
Bank Sta=4995.5,5001.5
Exp/Cntr=0.3,0.1

Type RM Length L Ch R = 1,7861,511,511,511
BEGIN DESCRIPTION:
Mapping XS 9d4562e2
END DESCRIPTION:
XS GIS Cut Line= 4
      2055957.61     13483479.57      2055788.29     13483389.27
      2055376.83     13483733.89      2055390.72     13483864.96
#Sta/Elev= 30
  4557.7  468.45  4687.6  466.52  4725.9  465.44  4731.6  465.65  4827.1  464.51
  4876.6  464.77  4890.9  464.47  4897.4  464.84  4905.2  464.66  4911.7  464.92
  4933.8  464.38  4962.4  464.62  4968.9  464.48  4983.2  463.09  4994.6  462.97
  4995.1  462.17  5000.1  462.17  5000.6  462.97  5018.4  464.60  5047.0  465.04
  5139.4  465.54  5174.5  466.20  5182.3  466.03  5238.3  467.03  5246.1  466.94
  5284.2  468.38  5337.7  469.47  5357.8  469.57  5407.2  471.43  5418.1  471.51
#Mann=3,-1,0
  4557.7    0.05       0  4994.6    0.03       0  5000.6    0.05       0
Bank Sta=4994.6,5000.6
Exp/Cntr=0.3,0.1

Type RM Length L Ch R = 1,7350,445,445,445
BEGIN DESCRIPTION:
Mapping XS 4506afa9
END DESCRIPTION:
XS GIS Cut Line= 4
      2055792.13     13483150.85      2055674.05     13483060.55
      2055115.02     13483189.02      2055069.89     13483393.86
#Sta/Elev= 30
  4553.3  465.89  4562.3  466.25  4569.9  465.65  4598.9  465.12  4605.2  465.74
  4612.6  464.92  4655.1  464.56  4731.8  462.10  4803.6  462.49  4844.6  461.51
  4874.2  461.51  4957.5  459.46  5010.0  459.17  5010.5  458.37  5015.5  458.37
  5016.0  459.17  5049.8  460.38  5090.9  460.33  5103.8  461.02  5121.7  460.46
  5146.6  460.88  5152.4  460.52  5183.2  460.33  5189.5  460.96  5214.0  460.46
  5244.8  461.41  5291.9  461.48  5312.4  462.17  5353.3  462.24  5485.3  464.24
#Mann=3,-1,0
  4553.3    0.05       0  5010.0    0.03       0  5016.0    0.05       0
Bank Sta=5010,5016
Exp/Cntr=0.3,0.1

Type RM Length L Ch R = 1,6905,422,422,422
BEGIN DESCRIPTION:
Mapping XS edb96418
END DESCRIPTION:
XS GIS Cut Line= 4
      2055799.06     13482845.28      2055649.74     13482699.44
      2055031.69     13482748.05      2054886.18     13482990.56
#Sta/Elev= 30
  4391.1  466.01  4535.7  463.81  4542.7  464.13  4578.1  463.19  4585.1  463.53
  4599.2  462.63  4614.6  462.76  4664.8  461.78  4704.9  460.27  4732.2  459.62
  4755.0  459.68  4795.2  458.32  4805.2  458.63  4825.3  457.99  4885.4  457.31
  4895.5  457.63  4915.5  456.82  4945.6  456.81  4955.7  456.30  4992.8  455.94
  4993.3  455.14  4998.3  455.14  4998.8  455.94  5045.9  456.36  5228.4  456.30
  5259.5  457.35  5367.8  458.14  5381.9  458.86  5397.5  458.59  5502.6  460.98
#Mann=3,-1,0
  4391.1    0.05       0  4992.8    0.03       0  4998.8    0.05       0
Bank Sta=4992.8,4998.8
Exp/Cntr=0.3,0.1

Type RM Length L Ch R = 1,6483,791,791,791
BEGIN DESCRIPTION:
Mapping XS e882d39a
END DESCRIPTION:
XS GIS Cut Line= 4
      2055625.43     13482383.46      2055448.35     13482161.25
      2054625.44     13482685.55      2054680.39     13482898.49
#Sta/Elev= 30
  4367.6  461.70  4473.5  460.25  4516.7  460.09  4537.5  459.58  4580.8  459.67
  4795.2  455.90  4925.5  454.16  4967.9  454.14  4986.0  453.61  4986.5  452.81
  4991.5  452.81  4992.0  453.61  5034.7  454.27  5165.1  453.63  5228.6  453.73
  5272.3  454.20  5316.6  453.85  5322.5  454.24  5389.4  453.95  5431.7  454.59
  5519.7  454.95  5592.4  455.91  5629.8  455.81  5684.7  457.53  5699.2  457.80
  5730.6  457.60  5760.9  458.68  5781.8  459.10  5806.7  458.91  5847.4  460.01
#Mann=3,-1,0
  4367.6    0.05       0  4986.0    0.03       0  4992.0    0.05       0
Bank Sta=4986,4992
Exp/Cntr=0.3,0.1

Type RM Length L Ch R = 1,5692,118,118,118
BEGIN DESCRIPTION:
Mapping XS 9ad4cf8f
END DESCRIPTION:
XS GIS Cut Line= 4
      2054976.16     13481800.13      2054667.10     13481893.88
      2054111.55     13482602.22      2054125.43     13482786.22
#Sta/Elev= 30
  4288.1  458.95  4395.0  456.99  4422.7  456.89  4427.9  456.47  4477.4  455.37
  4493.7  454.37  4498.9  454.64  4508.8  454.13  4559.5  453.82  4564.7  453.32
  4597.6  453.45  4705.7  450.89  4713.8  451.29  4720.2  450.77  4726.9  451.21
  4763.5  450.41  4798.8  450.54  4834.1  450.01  4955.6  450.54  5055.5  449.78
  5082.7  450.23  5222.5  449.72  5223.0  448.92  5228.0  448.92  5228.5  449.72
  5389.1  450.69  5461.4  452.34  5503.0  452.54  5594.3  454.68  5695.8  457.98
#Mann=3,-1,0
  4288.1    0.05       0  5222.5    0.03       0  5228.5    0.05       0
Bank Sta=5222.5,5228.5
Exp/Cntr=0.3,0.1

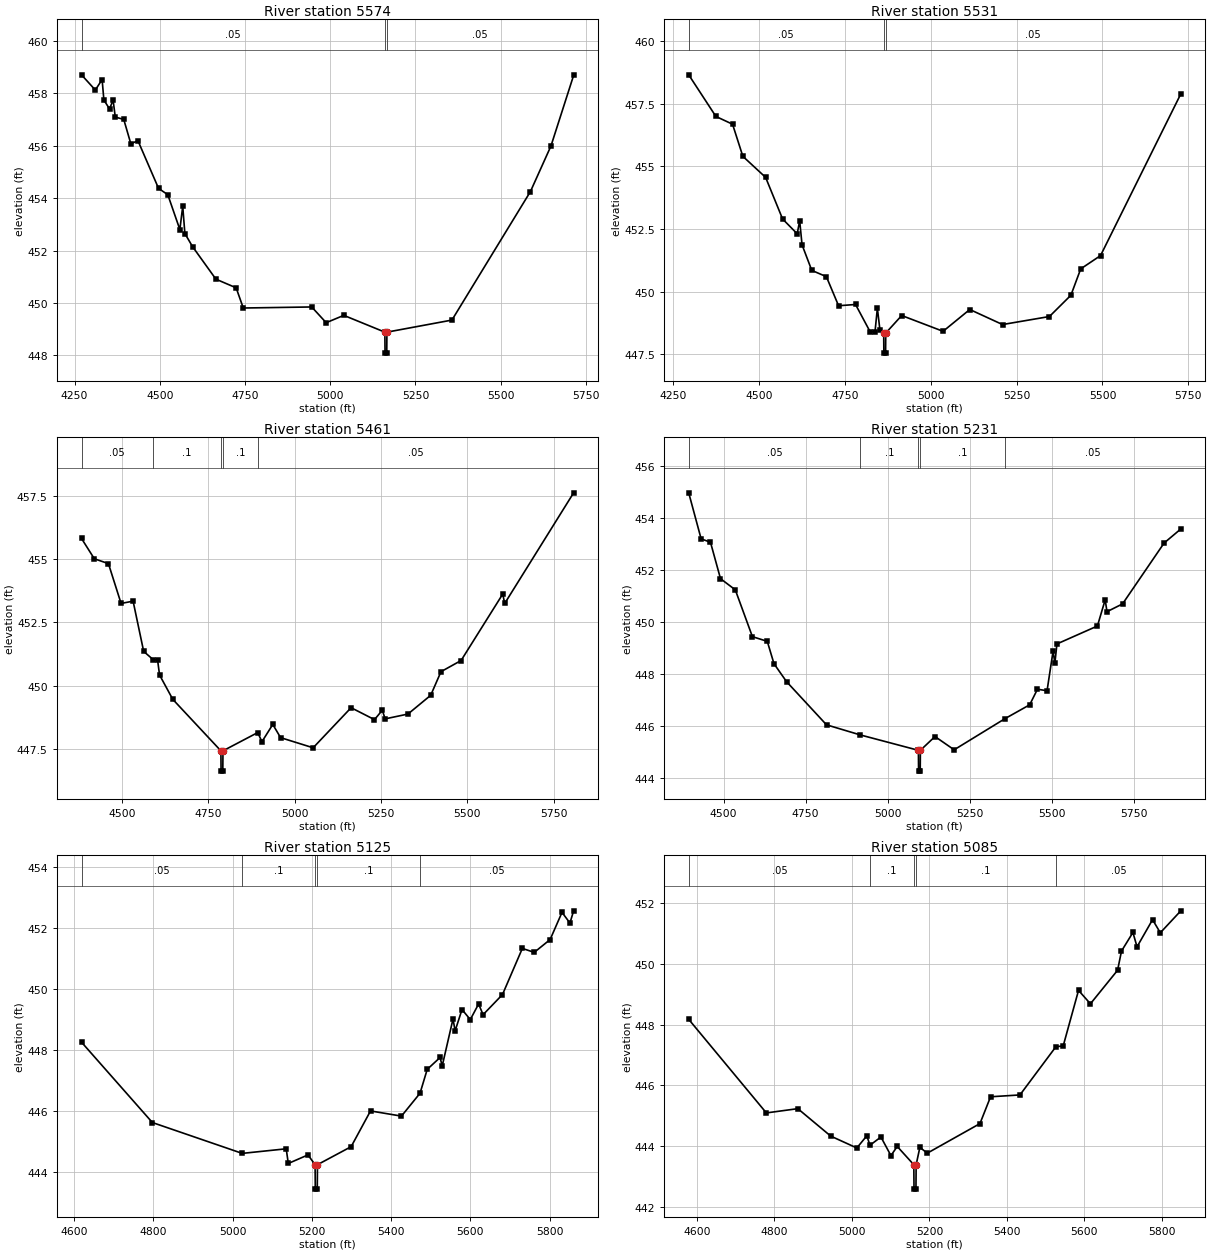
Type RM Length L Ch R = 1,5574,43,43,43
BEGIN DESCRIPTION:
Mapping XS 1a20e25a
END DESCRIPTION:
XS GIS Cut Line= 6
      2054893.84     13481751.78      2054694.19     13481810.37
      2054583.52     13481960.11      2054227.62     13482224.87
      2054084.39     13482585.11      2054105.98     13482801.06
#Sta/Elev= 30
  4270.4  458.70  4310.9  458.12  4330.8  458.52  4336.0  457.74  4352.6  457.40
  4363.0  457.74  4369.4  457.09  4394.3  457.00  4415.1  456.07  4435.9  456.19
  4496.4  454.37  4523.5  454.13  4558.9  452.80  4567.3  453.69  4573.6  452.65
  4596.1  452.15  4664.6  450.91  4724.0  450.58  4744.9  449.81  4945.7  449.85
  4988.1  449.25  5039.8  449.53  5160.3  448.89  5160.8  448.09  5165.8  448.09
  5166.3  448.89  5357.0  449.35  5587.3  454.25  5647.6  455.99  5714.0  458.68
#Mann=3,-1,0
  4270.4    0.05       0  5160.3    0.03       0  5166.3    0.05       0
Bank Sta=5160.3,5166.3
Exp/Cntr=0.3,0.1

Type RM Length L Ch R = 1,5531,70,70,70
BEGIN DESCRIPTION:
Mapping XS 4e714b7a
END DESCRIPTION:
XS GIS Cut Line= 5
      2054828.70     13481723.58      2054661.64     13481788.67
      2054195.06     13482235.72      2054045.32     13482552.56
      2054045.32     13482808.65
#Sta/Elev= 30
  4296.0  458.65  4375.1  456.99  4423.6  456.68  4453.5  455.40  4519.8  454.56
  4569.2  452.90  4611.7  452.31  4618.9  452.83  4625.8  451.87  4654.1  450.85
  4696.6  450.60  4732.1  449.44  4781.5  449.49  4824.0  448.40  4838.1  448.40
  4845.0  449.34  4852.3  448.49  4863.4  448.35  4863.9  447.55  4868.9  447.55
  4869.4  448.35  4915.8  449.05  5036.2  448.42  5113.9  449.29  5209.2  448.69
  5345.7  449.01  5408.2  449.86  5436.7  450.91  5494.4  451.44  5728.0  457.89
#Mann=3,-1,0
  4296.0    0.05       0  4863.4    0.03       0  4869.4    0.05       0
Bank Sta=4863.4,4869.4
Exp/Cntr=0.3,0.1

Type RM Length L Ch R = 1,5461,230,230,230
BEGIN DESCRIPTION:
Mapping XS caf48dcd
END DESCRIPTION:
XS GIS Cut Line= 4
      2054601.41     13481727.38      2054413.95     13481764.87
      2053926.60     13482682.24      2053942.03     13482876.27
#Sta/Elev= 30
  4383.1  455.81  4420.2  455.01  4461.0  454.82  4497.6  453.25  4532.4  453.34
  4563.0  451.36  4590.1  451.04  4603.4  451.01  4609.0  450.43  4647.3  449.47
  4786.6  447.44  4787.1  446.64  4792.1  446.64  4792.6  447.44  4893.2  448.16
  4905.4  447.80  4936.8  448.48  4959.4  447.96  5053.6  447.56  5163.5  449.14
  5231.2  448.67  5253.8  449.04  5262.1  448.70  5328.1  448.89  5394.0  449.63
  5423.7  450.56  5481.9  451.00  5602.5  453.62  5608.2  453.25  5807.7  457.61
#Mann=5,-1,0
  4383.1    0.05       0  4590.1     0.1       0  4786.6    0.03       0
  4792.6     0.1       0  4893.2    0.05       0
Bank Sta=4786.6,4792.6
Exp/Cntr=0.3,0.1

Type RM Length L Ch R = 1,5231,106,106,106
BEGIN DESCRIPTION:
Mapping XS d4122a1d
END DESCRIPTION:
XS GIS Cut Line= 4
      2054480.07     13481663.44      2054169.17     13481722.97
      2053778.85     13482651.37      2053796.49     13482825.62
#Sta/Elev= 30
  4394.0  454.96  4431.8  453.19  4460.3  453.06  4490.8  451.66  4535.9  451.23
  4588.0  449.43  4633.3  449.25  4653.7  448.39  4692.0  447.70  4813.7  446.04
  4917.1  445.65  5093.6  445.06  5094.1  444.26  5099.1  444.26  5099.6  445.06
  5144.1  445.59  5202.5  445.08  5357.6  446.28  5432.5  446.81  5456.2  447.41
  5485.4  447.35  5503.7  448.87  5509.2  448.41  5515.5  449.15  5638.8  449.84
  5662.5  450.85  5667.9  450.39  5715.4  450.69  5841.9  453.03  5892.8  453.57
#Mann=5,-1,0
  4394.0    0.05       0  4917.1     0.1       0  5093.6    0.07       0
  5099.6     0.1       0  5357.6    0.05       0
Bank Sta=5093.6,5099.6
Exp/Cntr=0.3,0.1

Type RM Length L Ch R = 1,5125,40,40,40
BEGIN DESCRIPTION:
Mapping XS c4c51a5b
END DESCRIPTION:
XS GIS Cut Line= 5
      2054188.56     13481675.82      2053995.41     13481877.65
      2053828.31     13482383.29      2053769.72     13482572.09
      2053758.87     13482804.26
#Sta/Elev= 30
  4618.6  448.25  4797.4  445.62  5024.2  444.61  5135.2  444.76  5140.5  444.28
  5190.1  444.56  5208.1  444.24  5208.6  443.44  5213.6  443.44  5214.1  444.24
  5299.1  444.83  5348.0  446.00  5426.1  445.83  5473.0  446.58  5491.1  447.36
  5523.6  447.75  5528.9  447.47  5556.2  449.01  5561.5  448.62  5578.9  449.32
  5599.8  448.99  5620.8  449.50  5632.1  449.15  5681.1  449.81  5731.2  451.32
  5761.2  451.19  5801.3  451.61  5831.3  452.50  5851.3  452.15  5860.6  452.55
#Mann=5,-1,0
  4618.6    0.05       0  5024.2     0.1       0  5208.1    0.03       0
  5214.1     0.1       0  5473.0    0.05       0
Bank Sta=5208.1,5214.1
Exp/Cntr=0.3,0.1

Type RM Length L Ch R = 1,5085,70,70,70
BEGIN DESCRIPTION:
Mapping XS 810de417
END DESCRIPTION:
XS GIS Cut Line= 6
      2054162.53     13481656.28      2054084.39     13481677.99
      2053962.86     13481860.28      2053865.20     13482140.23
      2053765.38     13482463.58      2053741.51     13482797.74
#Sta/Elev= 30
  4578.8  448.17  4779.2  445.10  4860.4  445.24  4945.3  444.34  5012.7  443.95
  5038.5  444.35  5046.6  444.04  5074.9  444.31  5100.7  443.70  5117.0  444.00
  5159.8  443.40  5160.3  442.60  5165.3  442.60  5165.8  443.40  5175.4  443.97
  5194.6  443.78  5330.5  444.75  5357.9  445.63  5433.7  445.69  5526.4  447.27
  5545.4  447.30  5584.9  449.12  5615.6  448.68  5685.7  449.78  5695.8  450.41
  5725.3  451.02  5735.9  450.55  5776.0  451.44  5796.0  451.01  5848.9  451.73
#Mann=5,-1,0
  4578.8    0.05       0  5046.6     0.1       0  5159.8    0.03       0
  5165.8     0.1       0  5526.4    0.05       0
Bank Sta=5159.8,5165.8
Exp/Cntr=0.3,0.1

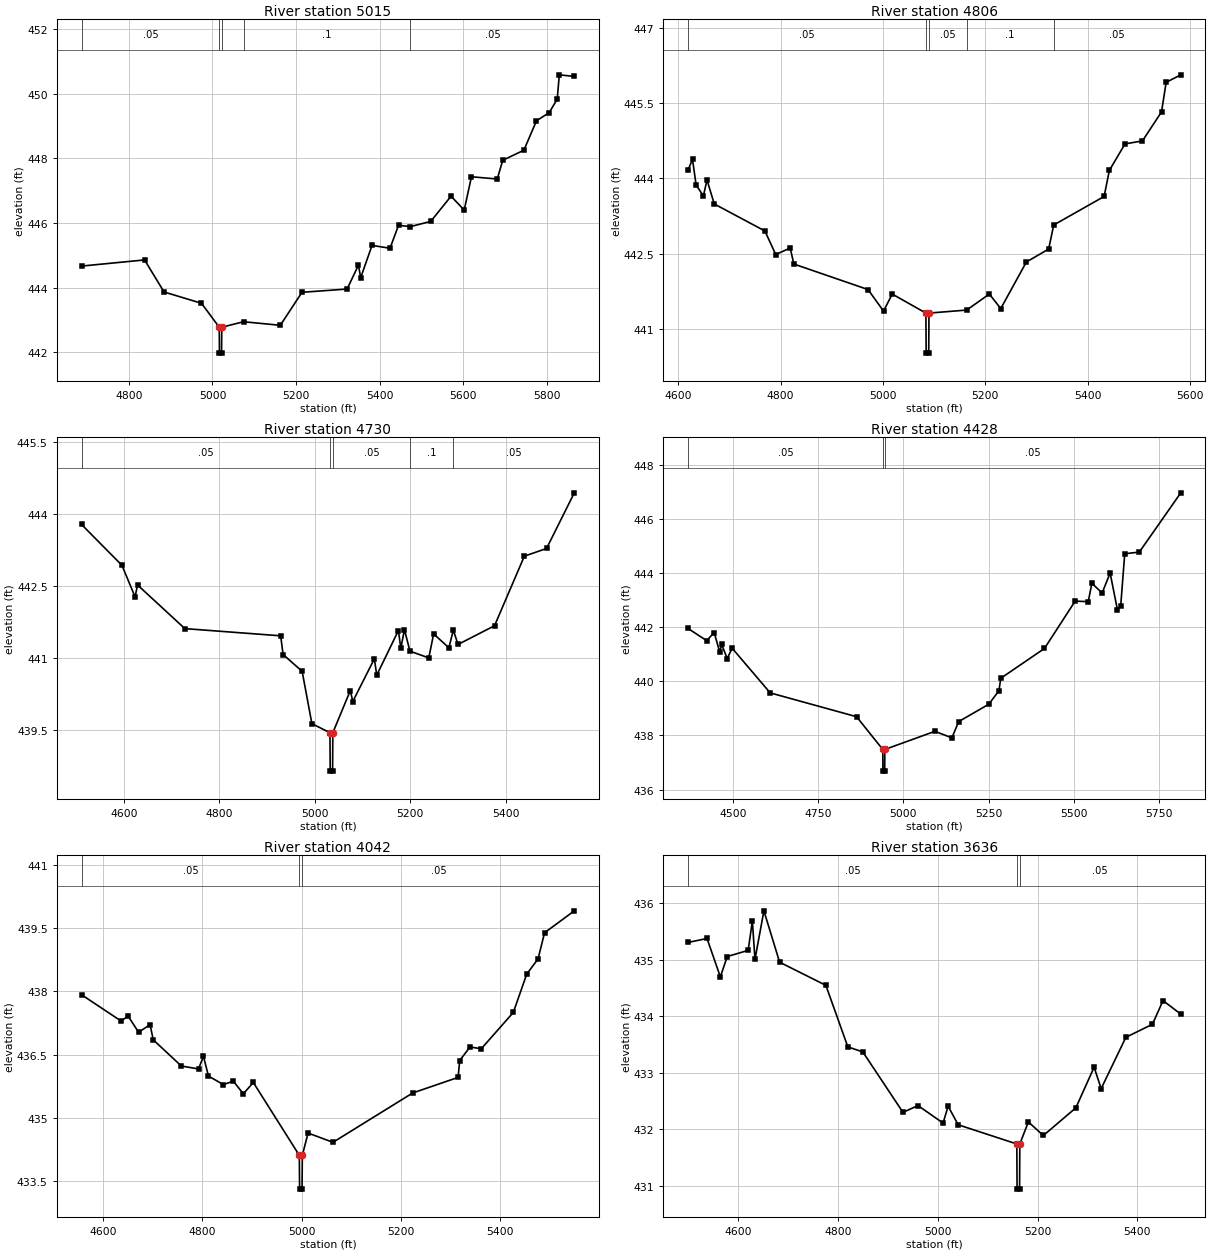
Type RM Length L Ch R = 1,5015,209,209,209
BEGIN DESCRIPTION:
Mapping XS 41231e24
END DESCRIPTION:
XS GIS Cut Line= 3
      2053948.66     13481681.03      2053664.18     13482591.83
      2053695.06     13482814.60
#Sta/Elev= 30
  4686.7  444.67  4837.5  444.86  4884.1  443.87  4973.7  443.52  5016.2  442.78
  5016.7  441.98  5021.7  441.98  5022.2  442.78  5074.3  442.95  5162.3  442.84
  5214.2  443.86  5322.1  443.96  5349.3  444.70  5354.6  444.31  5381.8  445.31
  5424.8  445.22  5445.2  445.93  5473.5  445.89  5522.2  446.05  5570.9  446.83
  5602.3  446.40  5619.7  447.43  5681.4  447.36  5694.6  447.94  5745.1  448.25
  5775.3  449.16  5805.6  449.41  5824.9  449.83  5829.9  450.58  5865.8  450.53
#Mann=5,-1,0
  4686.7    0.05       0  5016.2    0.03       0  5022.2    0.05       0
  5074.3     0.1       0  5473.5    0.05       0
Bank Sta=5016.2,5022.2
Exp/Cntr=0.3,0.1

Type RM Length L Ch R = 1,4806,76,76,76
BEGIN DESCRIPTION:
Mapping XS e2739f18
END DESCRIPTION:
XS GIS Cut Line= 5
      2053876.50     13481694.04      2053709.82     13481864.19
      2053586.56     13482195.79      2053584.82     13482308.64
      2053634.79     13482561.93
#Sta/Elev= 30
  4619.2  444.17  4628.0  444.38  4635.0  443.87  4649.2  443.65  4656.3  443.97
  4670.5  443.49  4769.5  442.95  4790.6  442.48  4818.9  442.61  4826.0  442.29
  4971.0  441.78  5001.3  441.35  5018.3  441.69  5084.1  441.31  5084.6  440.51
  5089.6  440.51  5090.1  441.31  5163.7  441.37  5208.1  441.69  5230.4  441.40
  5280.4  442.33  5324.0  442.59  5333.9  443.07  5432.4  443.64  5442.6  444.16
  5473.2  444.69  5507.3  444.75  5544.6  445.33  5553.6  445.92  5582.2  446.07
#Mann=5,-1,0
  4619.2    0.05       0  5084.1    0.03       0  5090.1    0.05       0
  5163.7     0.1       0  5333.9    0.05       0
Bank Sta=5084.1,5090.1
Exp/Cntr=0.3,0.1

Type RM Length L Ch R = 1,4730,302,302,302
BEGIN DESCRIPTION:
Mapping XS 2d41e521
END DESCRIPTION:
XS GIS Cut Line= 4
      2053858.08     13481678.61      2053639.33     13481720.27
      2053507.38     13482362.63      2053587.25     13482494.59
#Sta/Elev= 30
  4511.1  443.78  4595.7  442.93  4623.3  442.27  4628.4  442.52  4727.6  441.61
  4928.4  441.46  4933.5  441.07  4973.4  440.72  4993.8  439.63  5031.7  439.44
  5032.2  438.64  5037.2  438.64  5037.7  439.44  5074.4  440.32  5079.5  440.09
  5124.7  440.98  5129.8  440.64  5175.1  441.57  5180.2  441.20  5187.8  441.59
  5199.3  441.14  5238.8  441.00  5249.0  441.50  5281.0  441.21  5290.2  441.58
  5300.1  441.28  5376.6  441.67  5439.1  443.12  5485.6  443.28  5543.8  444.44
#Mann=5,-1,0
  4511.1    0.05       0  5031.7    0.03       0  5037.7    0.05       0
  5199.3     0.1       0  5290.2    0.05       0
Bank Sta=5031.7,5037.7
Exp/Cntr=0.3,0.1

Type RM Length L Ch R = 1,4428,386,386,386
BEGIN DESCRIPTION:
Mapping XS 9350a496
END DESCRIPTION:
XS GIS Cut Line= 4
      2053669.52     13481654.91      2053328.99     13481835.44
      2053324.57     13482320.59      2053531.86     13482858.64
#Sta/Elev= 30
  4367.4  441.95  4422.2  441.50  4444.2  441.80  4460.5  441.08  4466.2  441.36
  4482.5  440.84  4497.0  441.22  4608.8  439.57  4862.4  438.69  4939.4  437.48
  4939.9  436.68  4944.9  436.68  4945.4  437.48  5092.4  438.15  5142.4  437.91
  5162.4  438.51  5250.6  439.15  5280.6  439.65  5285.9  440.11  5414.2  441.21
  5504.4  442.96  5542.8  442.94  5553.5  443.62  5583.6  443.26  5607.1  444.00
  5628.5  442.64  5638.2  442.79  5650.0  444.71  5692.8  444.77  5814.6  446.96
#Mann=3,-1,0
  4367.4    0.05       0  4939.4    0.03       0  4945.4    0.05       0
Bank Sta=4939.4,4945.4
Exp/Cntr=0.3,0.1

Type RM Length L Ch R = 1,4042,406,406,406
BEGIN DESCRIPTION:
Mapping XS 5af3a8e9
END DESCRIPTION:
XS GIS Cut Line= 4
      2053187.90     13481876.55      2053000.44     13482008.47
      2053049.05     13482536.25      2053190.71     13482722.82
#Sta/Elev= 30
  4556.4  437.92  4635.7  437.30  4650.5  437.41  4671.4  437.03  4694.5  437.21
  4701.0  436.85  4757.6  436.23  4792.2  436.16  4802.2  436.46  4812.3  435.99
  4842.4  435.79  4862.5  435.87  4882.6  435.57  4902.7  435.84  4995.5  434.11
  4996.0  433.31  5001.0  433.31  5001.5  434.11  5013.1  434.64  5063.3  434.42
  5224.0  435.59  5315.6  435.96  5318.8  436.36  5339.6  436.68  5362.4  436.64
  5426.9  437.50  5454.0  438.41  5476.8  438.77  5489.9  439.39  5549.9  439.91
#Mann=3,-1,0
  4556.4    0.05       0  4995.5    0.03       0  5001.5    0.05       0
Bank Sta=4995.5,5001.5
Exp/Cntr=0.3,0.1

Type RM Length L Ch R = 1,3636,205,205,205
BEGIN DESCRIPTION:
Mapping XS f4667c40
END DESCRIPTION:
XS GIS Cut Line= 4
      2052899.76     13481949.44      2052674.05     13482022.36
      2052618.49     13482574.44      2052684.48     13482758.50
#Sta/Elev= 30
  4499.3  435.31  4537.4  435.38  4564.1  434.70  4577.9  435.06  4619.9  435.17
  4628.2  435.69  4633.5  435.01  4651.4  435.87  4682.9  434.96  4775.6  434.55
  4819.6  433.46  4849.7  433.37  4930.1  432.30  4960.3  432.42  5010.5  432.11
  5020.6  432.41  5040.7  432.08  5158.3  431.74  5158.8  430.94  5163.8  430.94
  5164.3  431.74  5181.4  432.13  5211.5  431.89  5276.6  432.38  5313.2  433.10
  5327.3  432.72  5376.9  433.63  5430.1  433.86  5451.3  434.28  5486.9  434.04
#Mann=3,-1,0
  4499.3    0.05       0  5158.3    0.03       0  5164.3    0.05       0
Bank Sta=5158.3,5164.3
Exp/Cntr=0.3,0.1

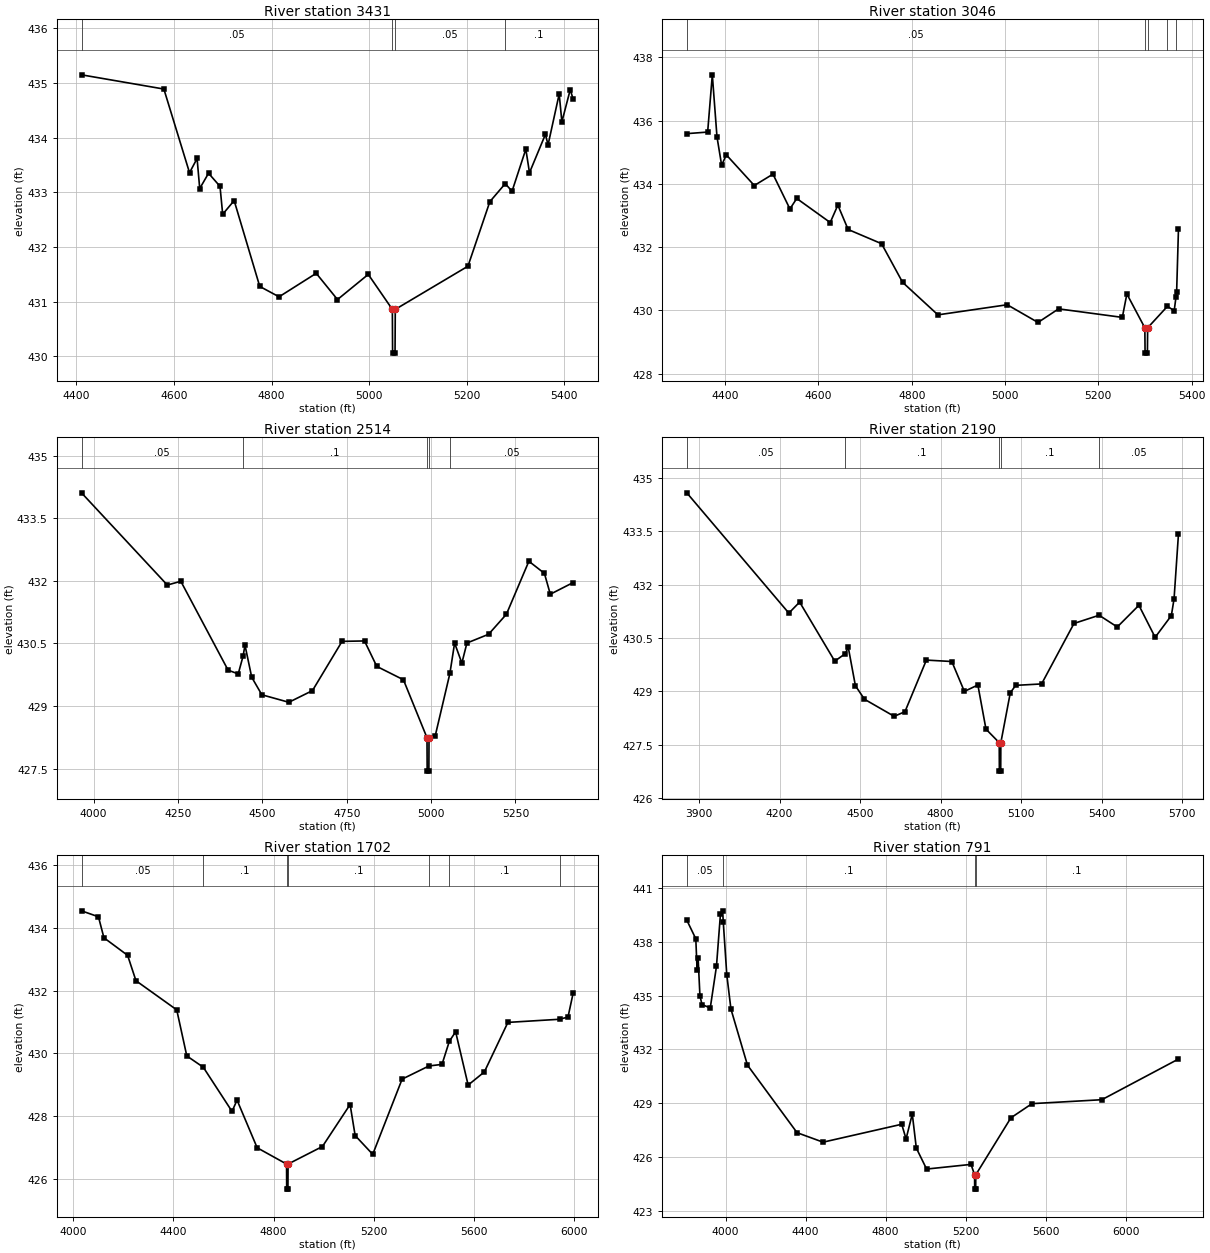
Type RM Length L Ch R = 1,3431,385,385,385
BEGIN DESCRIPTION:
Mapping XS c5c5c5ad
END DESCRIPTION:
XS GIS Cut Line= 4
      2052826.85     13481939.02      2052604.60     13481980.69
      2052375.44     13482511.94      2052462.26     13482696.00
#Sta/Elev= 30
  4410.3  435.15  4579.2  434.89  4631.8  433.36  4647.3  433.62  4652.7  433.07
  4670.8  433.35  4694.3  433.11  4699.8  432.60  4723.3  432.85  4775.8  431.28
  4815.4  431.09  4891.6  431.52  4935.2  431.04  4998.3  431.50  5047.7  430.86
  5048.2  430.06  5053.2  430.06  5053.7  430.86  5202.7  431.65  5247.6  432.83
  5279.2  433.16  5293.1  433.02  5321.4  433.79  5328.9  433.36  5361.5  434.06
  5367.0  433.87  5389.8  434.80  5395.3  434.29  5412.5  434.88  5418.5  434.70
#Mann=4,-1,0
  4410.3    0.05       0  5047.7    0.03       0  5053.7    0.05       0
  5279.2     0.1       0
Bank Sta=5047.7,5053.7
Exp/Cntr=0.3,0.1

Type RM Length L Ch R = 1,3046,532,532,532
BEGIN DESCRIPTION:
Mapping XS aa67e1fc
END DESCRIPTION:
XS GIS Cut Line= 4
      2052899.70     13481834.86      2052677.52     13481831.38
      2052052.52     13482161.25      2052018.18     13482281.42
#Sta/Elev= 30
  4317.9  435.59  4362.6  435.64  4372.6  437.45  4382.6  435.49  4392.6  434.59
  4402.6  434.92  4462.6  433.95  4502.6  434.31  4538.9  433.21  4553.6  433.54
  4625.3  432.78  4641.7  433.33  4663.7  432.56  4735.4  432.11  4780.4  430.89
  4856.2  429.86  5004.7  430.18  5070.7  429.62  5114.8  430.05  5251.4  429.78
  5261.2  430.52  5299.7  429.45  5300.2  428.65  5305.2  428.65  5305.7  429.45
  5348.1  430.13  5362.6  429.99  5366.6  430.44  5367.8  430.57  5371.8  432.59
#Mann=5,-1,0
  4317.9    0.05       0  5299.7    0.03       0  5305.7    0.05       0
  5348.1     0.1       0  5366.6    0.05       0
Bank Sta=5299.7,5305.7
Exp/Cntr=0.3,0.1

Type RM Length L Ch R = 1,2514,324,324,324
BEGIN DESCRIPTION:
Mapping XS cfcfc05e
END DESCRIPTION:
XS GIS Cut Line= 4
      2052889.31     13481546.66      2052167.10     13481557.08
      2051760.85     13481814.02      2051866.74     13482044.93
#Sta/Elev= 30
  3964.0  434.11  4218.3  431.90  4258.3  431.99  4398.4  429.86  4428.4  429.77
  4442.9  430.20  4448.4  430.46  4468.4  429.69  4498.4  429.27  4578.4  429.09
  4648.4  429.37  4736.1  430.55  4802.6  430.56  4839.0  429.95  4917.9  429.63
  4987.8  428.24  4988.3  427.44  4993.3  427.44  4993.8  428.24  5012.0  428.28
  5055.6  429.78  5069.6  430.51  5091.1  430.03  5106.1  430.51  5170.3  430.72
  5223.1  431.20  5289.7  432.47  5335.7  432.18  5353.2  431.68  5421.0  431.96
#Mann=5,-1,0
  3964.0    0.05       0  4442.9     0.1       0  4987.8    0.07       0
  4993.8     0.1       0  5055.6    0.05       0
Bank Sta=4987.8,4993.8
Exp/Cntr=0.3,0.1

Type RM Length L Ch R = 1,2190,488,488,488
BEGIN DESCRIPTION:
Mapping XS d52ed49b
END DESCRIPTION:
XS GIS Cut Line= 4
      2053010.87     13481445.98      2052847.66     13481303.61
      2051779.92     13481424.24      2051713.95     13481961.39
#Sta/Elev= 30
  3854.2  434.58  4234.5  431.20  4274.7  431.51  4405.6  429.85  4444.7  430.06
  4455.9  430.24  4482.5  429.16  4516.3  428.78  4627.0  428.30  4667.2  428.43
  4747.0  429.88  4841.8  429.84  4888.6  429.00  4938.9  429.18  4969.1  427.94
  5018.5  427.56  5019.0  426.76  5024.0  426.76  5024.5  427.56  5059.7  428.96
  5079.8  429.17  5176.3  429.21  5297.2  430.91  5390.8  431.14  5458.4  430.81
  5539.0  431.42  5599.5  430.52  5659.9  431.13  5670.0  431.60  5686.5  433.43
#Mann=5,-1,0
  3854.2    0.05       0  4444.7     0.1       0  5018.5    0.07       0
  5024.5     0.1       0  5390.8    0.05       0
Bank Sta=5018.5,5024.5
Exp/Cntr=0.3,0.1

Type RM Length L Ch R = 1,1702,911,911,911
BEGIN DESCRIPTION:
Mapping XS 1426e7ef
END DESCRIPTION:
XS GIS Cut Line= 4
      2053010.84     13481143.88      2052823.35     13481025.83
      2051766.03     13480932.15      2051570.31     13481584.92
#Sta/Elev= 30
  4032.5  434.55  4100.2  434.36  4122.1  433.69  4216.7  433.13  4250.1  432.32
  4413.0  431.39  4453.2  429.92  4519.0  429.56  4633.9  428.15  4654.0  428.51
  4734.3  426.99  4851.8  426.47  4852.3  425.67  4857.3  425.67  4857.8  426.47
  4995.1  427.03  5105.7  428.37  5125.8  427.38  5196.1  426.78  5313.5  429.18
  5420.7  429.60  5472.8  429.65  5502.3  430.39  5527.3  430.69  5577.3  428.99
  5642.1  429.41  5736.1  430.99  5942.3  431.09  5976.2  431.16  5997.0  431.93
#Mann=7,-1,0
  4032.5    0.05       0  4519.0     0.1       0  4851.8    0.07       0
  4857.8     0.1       0  5420.7    0.05       0  5502.3     0.1       0
  5942.3    0.05       0
Bank Sta=4851.8,4857.8
Exp/Cntr=0.3,0.1

Type RM Length L Ch R = 1,791,600,600,600
BEGIN DESCRIPTION:
Mapping XS 88befa57
END DESCRIPTION:
XS GIS Cut Line= 4
      2053288.59     13480293.18      2052642.80     13480126.52
      2051913.63     13480296.66      2051250.00     13481100.00
#Sta/Elev= 30
  3806.5  439.21  3851.5  438.17  3858.0  436.45  3863.1  437.08  3872.2  434.99
  3882.5  434.50  3923.8  434.31  3954.8  436.63  3974.8  439.56  3985.8  439.73
  3988.7  439.13  4006.4  436.16  4027.1  434.25  4109.7  431.12  4357.6  427.35
  4487.7  426.82  4880.8  427.82  4902.5  427.00  4933.6  428.39  4953.8  426.49
  5005.2  425.32  5227.2  425.58  5245.0  425.00  5245.5  424.20  5250.5  424.20
  5251.0  425.00  5426.6  428.18  5532.0  428.97  5881.2  429.19  6264.2  431.46
#Mann=4,-1,0
  3806.5    0.05       0  3988.7     0.1       0  5245.0    0.07       0
  5251.0     0.1       0
Bank Sta=5245,5251
Exp/Cntr=0.3,0.1

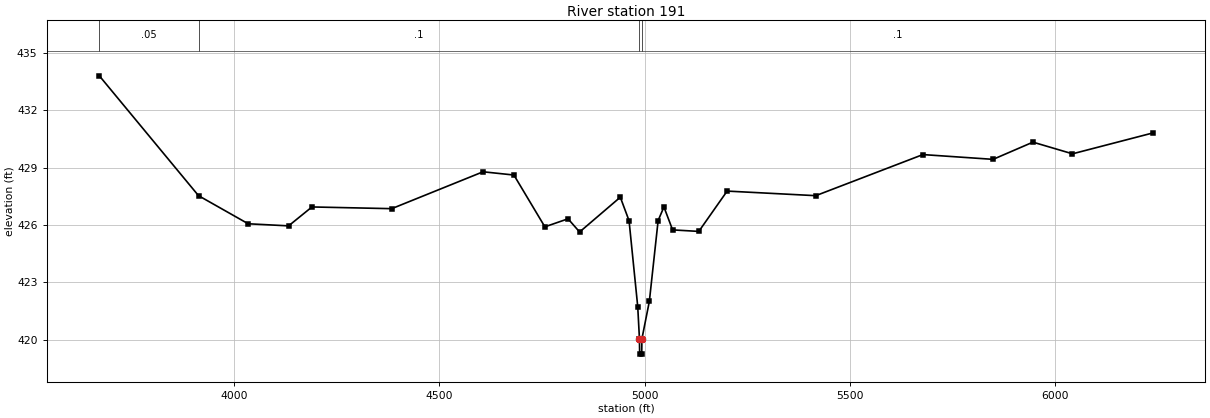
Type RM Length L Ch R = 1,191,0,0,0
BEGIN DESCRIPTION:
UNT 102 in Lagunillas Cr Wtrshd 1.0
END DESCRIPTION:
XS GIS Cut Line= 4
      2053087.20     13479991.09      2052074.05     13479637.59
      2051750.00     13479950.00      2051358.26     13480915.26
#Sta/Elev= 30
  3672.2  433.80  3913.7  427.53  4034.6  426.06  4133.0  425.95  4189.9  426.94
  4384.1  426.85  4606.6  428.78  4681.6  428.61  4757.0  425.90  4813.4  426.32
  4841.6  425.63  4940.7  427.45  4962.0  426.22  4983.1  421.73  4987.3  420.04
  4987.8  419.24  4992.8  419.24  4993.3  420.04  5011.4  422.00  5032.8  426.23
  5046.9  426.94  5068.0  425.74  5131.8  425.66  5200.8  427.77  5416.6  427.53
  5677.5  429.68  5848.3  429.43  5945.4  430.33  6041.7  429.72  6237.1  430.81
#Mann=4,-1,0
  3672.2    0.05       0  3913.7     0.1       0  4987.3    0.07       0
  4993.3     0.1       0
Bank Sta=4987.3,4993.3
Exp/Cntr=0.3,0.1

Chan Stop Cuts=-1