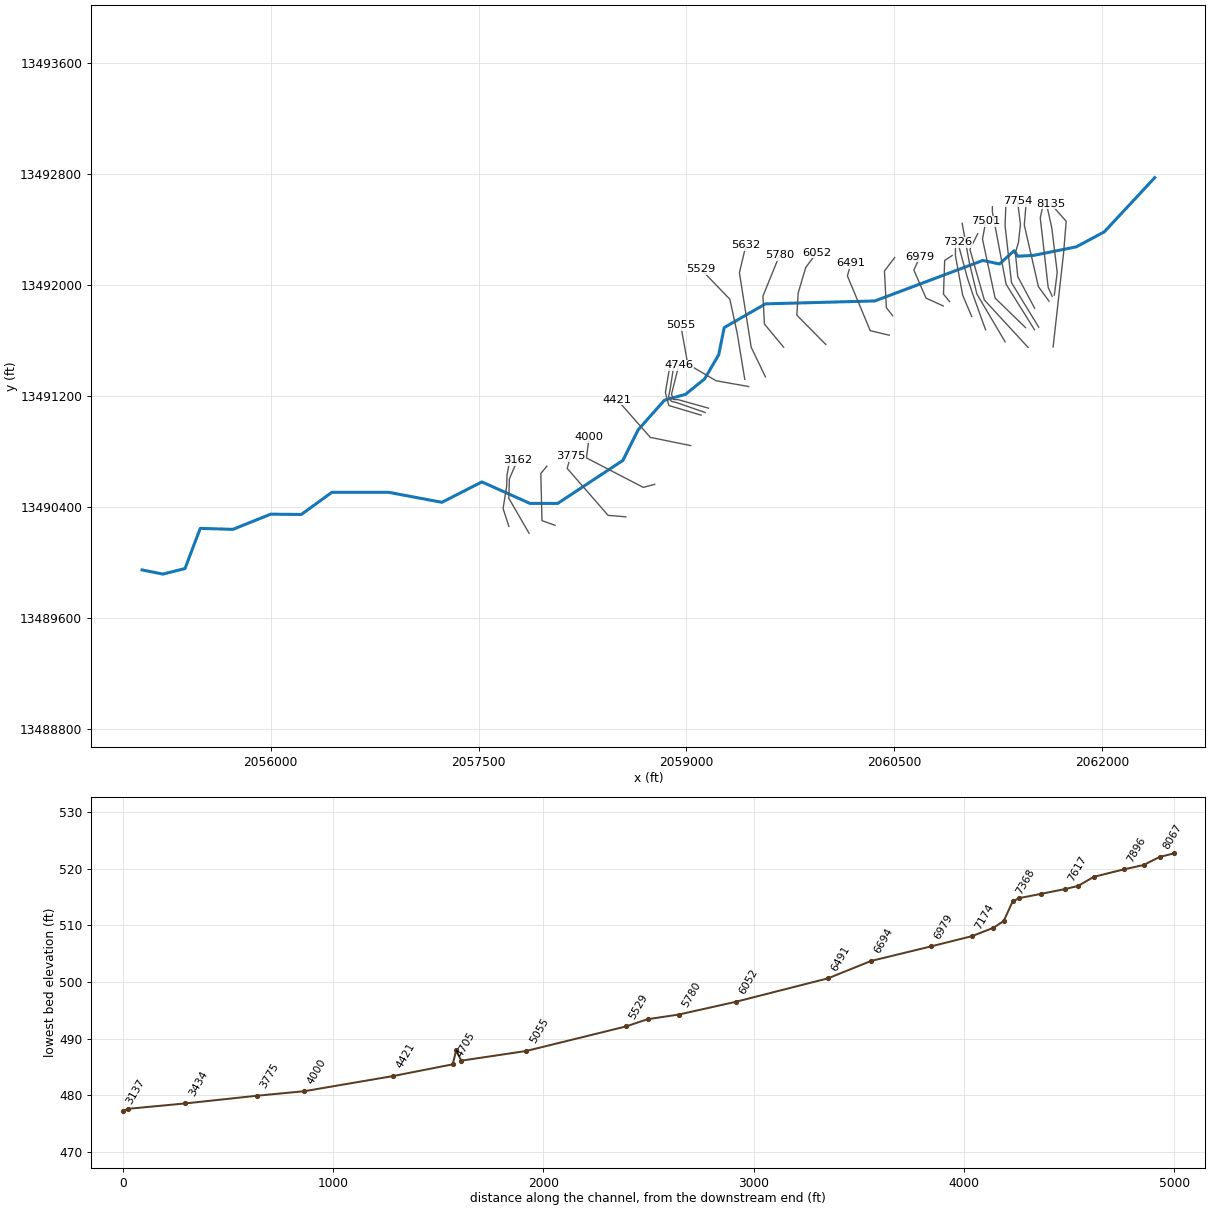
--- UNT 104 in Lagunillas Cr Wtrshd.prj (project) ---

Proj Title=UNT 104 in Lagunillas Cr Wtrshd Base Level Engineering
Current Plan=p01
Default Exp/Contr=0.3,0.1
English Units
Geom File=g01
Flow File=f01
Plan File=p01
Y Axis Title=Elevation
X Axis Title(PF)=Main Channel Distance
X Axis Title(XS)=Station
BEGIN DESCRIPTION:
UNT 104 in Lagunillas Cr Wtrshd
END DESCRIPTION:
DSS Export Rating Curves= 0
DSS Export Rating Curve Sorted= 0
DSS Export Volume Flow Curves= 0
DXF OffsetX= 0
DXF OffsetY= 0
DXF ScaleX= 1
DXF ScaleY= 10

--- UNT 104 in Lagunillas Cr Wtrshd.p01 (plan) ---

Plan Title=Multiple Run
Short Identifier=Multiple
Geom File=g01
Flow File=f01
Subcritical Flow
K Sum by GR= 0
Std Step Tol= 0.01
Critical Tol= 0.01
Num of Std Step Trials= 20
Max Error Tol= 0.3
Flow Tol Ratio= 0.001
Split Flow NTrial= 30
Split Flow Tol= 0.02
Split Flow Ratio= 0.02
Log Output Level= 0
Friction Slope Method= 1
Unsteady Friction Slope Method= 2
Unsteady Bridges Friction Slope Method= 1
Parabolic Critical Depth
Global Vel Dist=  1 , 1 , 1
Global Log Level= 0
CheckData=True
Encroach Param= -1, 0, 0, 0
BEGIN DESCRIPTION:
Multiple Run
END DESCRIPTION:

--- UNT 104 in Lagunillas Cr Wtrshd.f01 (steady flow) ---

Flow Title=Multiple
Number of Profiles=7
Profile Names=10-year,25-year,50-year,1pct_min,100-year,1pct_plu,500-year
River Rch & RM= UNT 104 in Lagun,Reach-1,8135
      38      46      52      30      59     118      77
River Rch & RM= UNT 104 in Lagun,Reach-1,5632
     122     161     193     115     230     459     332
River Rch & RM= UNT 104 in Lagun,Reach-1,1019
     135     180     216     130     258     516     376
Boundary for River Rch & Prof#=UNT 104 in Lagun,Reach-1,1
Up Type=0
Dn Type=3
Dn Slope=0.005
Boundary for River Rch & Prof#=UNT 104 in Lagun,Reach-1,2
Up Type=0
Dn Type=3
Dn Slope=0.005
Boundary for River Rch & Prof#=UNT 104 in Lagun,Reach-1,3
Up Type=0
Dn Type=3
Dn Slope=0.005
Boundary for River Rch & Prof#=UNT 104 in Lagun,Reach-1,4
Up Type=0
Dn Type=3
Dn Slope=0.005
Boundary for River Rch & Prof#=UNT 104 in Lagun,Reach-1,5
Up Type=0
Dn Type=3
Dn Slope=0.005
Boundary for River Rch & Prof#=UNT 104 in Lagun,Reach-1,6
Up Type=0
Dn Type=3
Dn Slope=0.005
Boundary for River Rch & Prof#=UNT 104 in Lagun,Reach-1,7
Up Type=0
Dn Type=3
Dn Slope=0.005

--- UNT 104 in Lagunillas Cr Wtrshd.g01 (geometry) ---

Geom Title=Existing Conditions
Program Version=5.05

River Reach=UNT 104 in Lagun,Reach-1
Reach XY= 30
      2062380.39     13492775.48      2062015.65     13492383.79
      2061814.26     13492276.15      2061508.47     13492214.55
      2061391.24     13492208.15       2061365.2      13492248.3
      2061259.77     13492152.31      2061138.98     13492177.74
      2060359.67     13491885.55       2059570.8     13491864.54
      2059272.73     13491693.34      2059232.69     13491496.82
      2059131.18     13491322.68      2058992.99     13491211.57
       2058840.9     13491169.21       2058650.8     13490954.54
       2058540.8     13490734.54       2058070.8     13490424.54
       2057870.8     13490424.54      2057523.54     13490579.62
      2057235.35      13490432.4       2056850.8     13490504.54
       2056440.8     13490504.54      2056220.22     13490344.77
      2055999.24     13490346.99      2055726.32     13490237.26
       2055490.8     13490244.54       2055380.8     13489954.54
       2055220.8     13489914.54       2055070.8     13489944.54

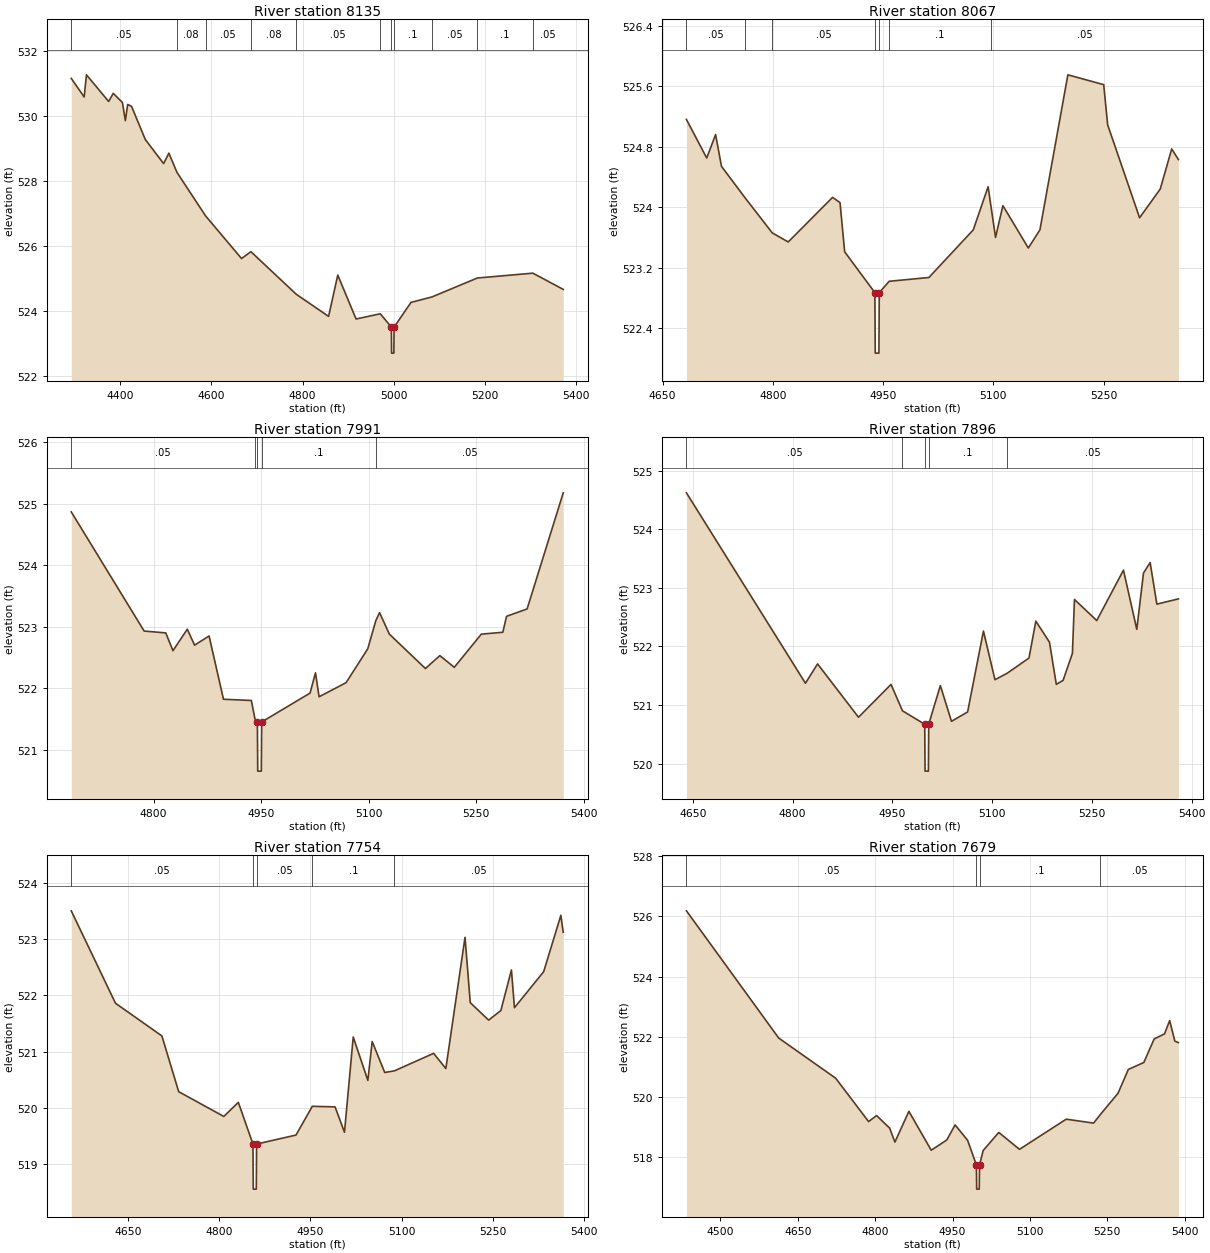
Type RM Length L Ch R = 1 ,8135    ,68,68,68
BEGIN DESCRIPTION:
Mapping XS 02af739d
END DESCRIPTION:
XS GIS Cut Line= 4
      2061646.69      13491553.4      2061722.59     13492235.65
      2061740.82     13492460.48       2061629.4     13492586.58
#Sta/Elev= 30
  4292.2  531.15  4320.5  530.58  4325.6  531.26  4374.3  530.44  4384.4  530.69
  4404.5  530.41    4411  529.85  4416.1  530.35  4424.6  530.29  4454.8  529.27
    4495  528.53  4506.6  528.85  4524.3  528.26  4587.2  526.92  4666.1  525.61
  4686.7  525.82  4786.3  524.51  4857.3  523.83  4877.4   525.1  4917.6  523.75
  4970.8  523.91  4995.1   523.5  4995.6   522.7  5000.6   522.7  5001.1   523.5
  5038.2  524.26  5084.6  524.43  5183.8  525.01  5305.9  525.16  5372.5  524.66
#Mann= 11 ,-1 , 0
  4292.2     .05       0  4524.3     .08       0  4587.2     .05       0
  4686.7     .08       0  4786.3     .05       0  4970.8      .1       0
  4995.1     .07       0  5001.1      .1       0  5084.6     .05       0
  5183.8      .1       0  5305.9     .05       0
Bank Sta=4995.1,5001.1
XS Rating Curve= 0 ,0
Exp/Cntr=0.3,0.1

Type RM Length L Ch R = 1 ,8067    ,76,76,76
BEGIN DESCRIPTION:
Mapping XS 951370fa
END DESCRIPTION:
XS GIS Cut Line= 4
      2061655.37     13491927.63       2061676.2     13492091.71
      2061637.14     13492412.02      2061598.08     13492589.09
#Sta/Elev= 30
  4682.5  525.16  4710.1  524.65  4722.2  524.96  4730.2  524.54  4762.6  524.12
  4799.3  523.66    4821  523.54  4881.4  524.13  4891.5  524.06  4897.8  523.41
  4938.9  522.87  4939.4  522.07  4944.4  522.07  4944.9  522.87  4958.4  523.02
  5012.4  523.07  5072.8   523.7    5093  524.27  5096.6  524.03  5103.1   523.6
  5113.1  524.02  5147.7  523.46  5163.5   523.7  5201.5  525.75  5250.3  525.62
  5255.6  525.09  5299.1  523.86  5327.2  524.24  5342.8  524.77  5351.9  524.63
#Mann= 7 ,-1 , 0
  4682.5     .05       0  4762.6     .08       0  4799.3     .05       0
  4938.9     .07       0  4944.9     .05       0  4958.4      .1       0
  5096.6     .05       0
Bank Sta=4938.9,4944.9
XS Rating Curve= 0 ,0
Exp/Cntr=0.3,0.1

Type RM Length L Ch R = 1 ,7991    ,95,95,95
BEGIN DESCRIPTION:
Mapping XS 75237b4f
END DESCRIPTION:
XS GIS Cut Line= 4
      2061639.76      13491919.8       2061611.1     13491982.33
       2061553.8     13492484.94      2061577.24     13492594.31
#Sta/Elev= 30
  4685.2  524.87  4786.9  522.93  4817.1   522.9  4827.1  522.61  4847.1  522.96
  4857.3   522.7  4877.5  522.85  4897.6  521.82  4936.5   521.8  4941.5   521.5
  4944.9  521.45  4945.4  520.65  4950.4  520.65  4950.9  521.45  5018.4  521.92
    5026  522.25    5031  521.86  5068.7  522.09  5098.9  522.64  5110.2   523.1
  5115.4  523.23  5129.1  522.88  5179.4  522.32  5199.5  522.53  5219.7  522.34
  5257.4  522.88  5287.4  522.91  5292.6  523.17  5321.3  523.29  5371.7  525.18
#Mann= 5 ,-1 , 0
  4685.2     .05       0  4941.5      .1       0  4944.9     .07       0
  4950.9      .1       0  5110.2     .05       0
Bank Sta=4944.9,4950.9
XS Rating Curve= 0 ,0
Exp/Cntr=0.3,0.1

Type RM Length L Ch R = 1 ,7896    ,142,142,142
BEGIN DESCRIPTION:
Mapping XS d8ad3485
END DESCRIPTION:
XS GIS Cut Line= 4
      2061616.53     13491884.27      2061540.59     13491988.42
      2061438.59      13492433.3      2061451.61     13492587.33
#Sta/Elev= 30
  4640.2  524.62  4819.2  521.37  4837.4   521.7    4899  520.79  4947.9  521.35
  4965.1   520.9  4998.6  520.67  4999.1  519.87  5004.1  519.87  5004.6  520.67
  5022.1  521.33  5038.8  520.72  5063.1  520.88  5086.9  522.26  5104.2  521.43
  5122.5  521.54  5155.4   521.8  5165.7  522.43  5186.2  522.07  5196.5  521.35
  5206.7  521.42  5220.7  521.88  5223.8   522.8  5257.3  522.44  5297.5   523.3
  5317.5  522.29  5327.6  523.25  5337.6  523.43  5347.7  522.72  5380.1  522.81
#Mann= 5 ,-1 , 0
  4640.2     .05       0  4965.1      .1       0  4998.6     .07       0
  5004.6      .1       0  5122.5     .05       0
Bank Sta=4998.6,5004.6
XS Rating Curve= 0 ,0
Exp/Cntr=0.3,0.1

Type RM Length L Ch R = 1 ,7754    ,75,75,75
BEGIN DESCRIPTION:
Mapping XS 6c77070e
END DESCRIPTION:
XS GIS Cut Line= 6
      2061513.08     13491833.43      2061391.53     13492060.89
      2061374.17     13492232.76      2061396.74     13492309.15
      2061410.63     13492437.62       2061389.9     13492606.94
#Sta/Elev= 30
  4556.1   523.5  4628.9  521.86  4705.3  521.28    4733  520.29  4807.3  519.85
  4831.2   520.1  4855.3  519.36  4855.8  518.56  4860.8  518.56  4861.3  519.36
  4926.2  519.52    4953  520.03  4990.5  520.02    5006  519.57  5020.4  521.26
  5044.5  520.49  5051.6  521.18  5072.3  520.63  5088.3  520.66  5152.8  520.97
  5172.9   520.7  5204.5  523.03  5213.1  521.87  5243.4  521.56  5263.5  521.73
  5280.9  522.45  5285.9  521.78    5334  522.42  5362.3  523.42  5366.2  523.12
#Mann= 5 ,-1 , 0
  4556.1     .05       0  4855.3     .07       0  4861.3     .05       0
    4953      .1       0  5088.3     .05       0
Bank Sta=4855.3,4861.3
XS Rating Curve= 0 ,0
Exp/Cntr=0.3,0.1

Type RM Length L Ch R = 1 ,7679    ,62,62,62
BEGIN DESCRIPTION:
Mapping XS b716a300
END DESCRIPTION:
XS GIS Cut Line= 4
       2061542.6     13491696.27      2061346.39     13492017.49
       2061299.7     13492428.96      2061306.14     13492591.92
#Sta/Elev= 30
  4434.2  526.18  4613.1  521.96  4723.4  520.63  4787.3  519.19  4802.8  519.39
  4828.2  518.97  4838.3  518.51  4865.4  519.53  4908.7  518.24  4938.9  518.58
    4955  519.08  4979.2  518.57  4996.3  517.75  4996.8  516.95  5001.8  516.95
  5002.3  517.75  5009.4  518.23  5039.6  518.83  5079.8  518.27  5170.4  519.27
  5223.4  519.14  5236.8  519.43  5270.8  520.13  5290.8  520.92  5320.8  521.15
  5340.8  521.93  5360.9   522.1  5370.9  522.54  5380.9  521.86  5387.8  521.81
#Mann= 4 ,-1 , 0
  4434.2     .05       0  4996.3     .03       0  5002.3      .1       0
  5236.8     .05       0
Bank Sta=4996.3,5002.3
XS Rating Curve= 0 ,0
Exp/Cntr=0.3,0.1

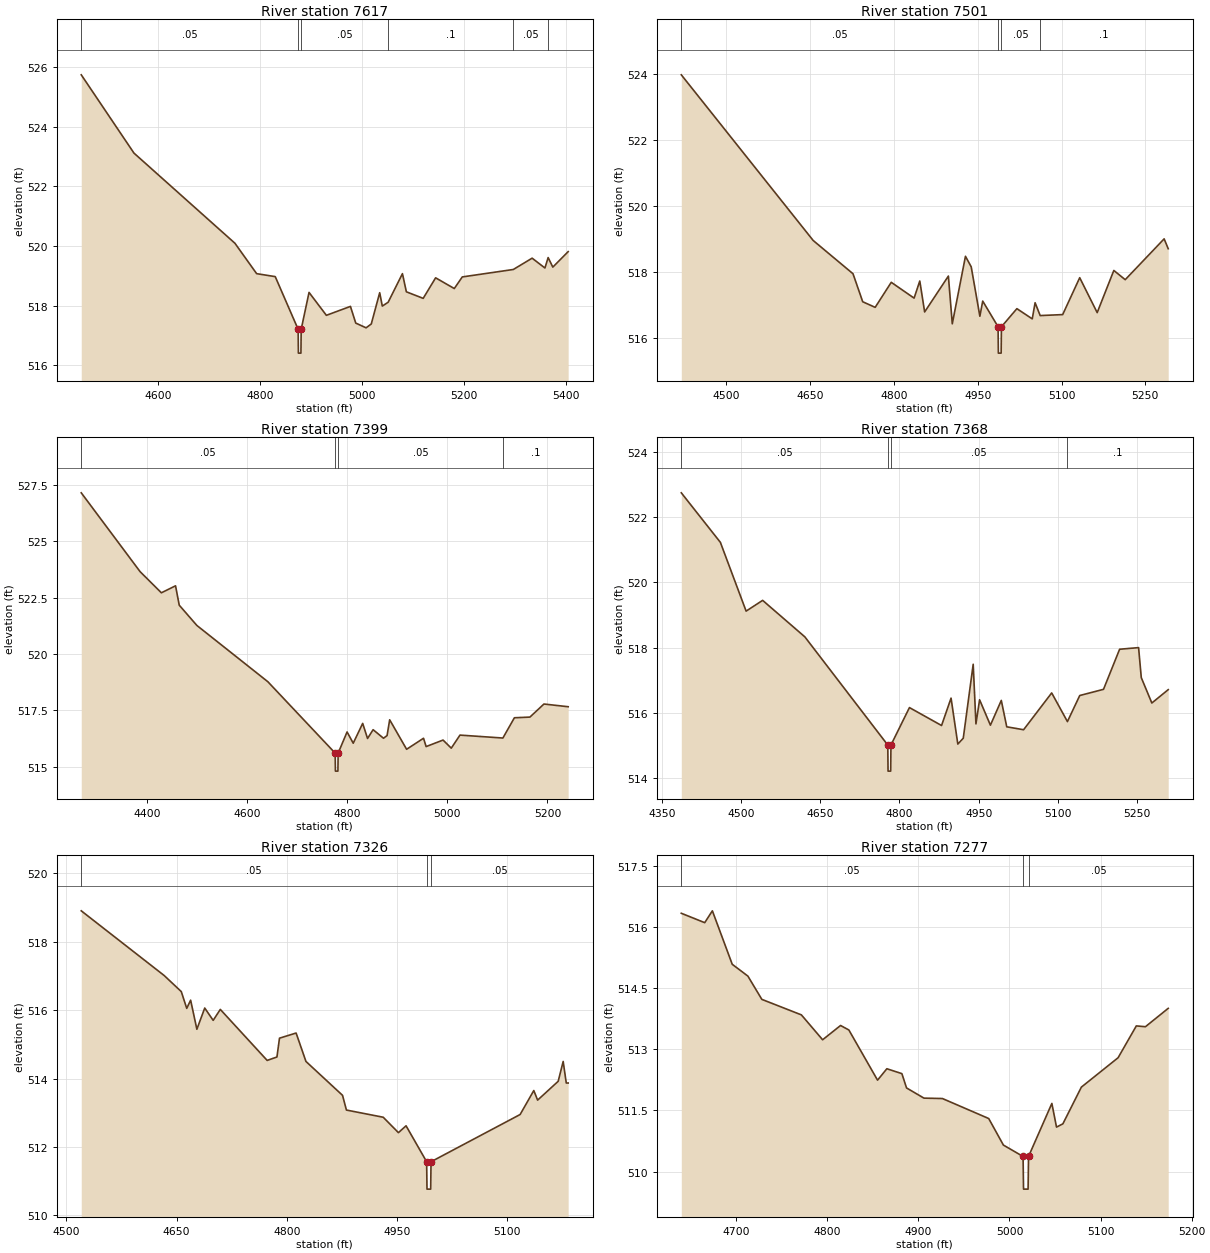
Type RM Length L Ch R = 1 ,7617    ,116,116,116
BEGIN DESCRIPTION:
Mapping XS 1afb8a9b
END DESCRIPTION:
XS GIS Cut Line= 4
      2061512.02     13491677.98      2061307.18     13492006.06
      2061208.22     13492528.63      2061208.22      13492565.1
#Sta/Elev= 30
    4450  525.75  4553.4  523.12  4751.5  520.09    4794  519.07  4830.5  518.97
  4875.4   517.2  4875.9   516.4  4880.9   516.4  4881.4   517.2  4896.8  518.44
  4930.8  517.67    4978  517.97  4988.4  517.41  5008.7  517.25  5018.9  517.38
  5035.4  518.43  5040.5  517.98    5052  518.11    5080  519.07  5087.7  518.46
  5120.7  518.24  5145.1  518.93  5181.7  518.57  5197.4  518.96  5297.5  519.21
  5334.4  519.59  5359.5  519.26  5365.8  519.61    5375  519.29  5405.1  519.81
#Mann= 6 ,-1 , 0
    4450     .05       0  4875.4     .03       0  4881.4     .05       0
    5052      .1       0  5297.5     .05       0  5365.8      .1       0
Bank Sta=4875.4,4881.4
XS Rating Curve= 0 ,0
Exp/Cntr=0.3,0.1

Type RM Length L Ch R = 1 ,7501    ,102,102,102
BEGIN DESCRIPTION:
Mapping XS 18969345
END DESCRIPTION:
XS GIS Cut Line= 4
      2061447.26     13491693.29      2061228.09     13491905.95
      2061136.94      13492331.3      2061160.68     13492460.76
#Sta/Elev= 30
  4419.1  523.99  4655.3  518.96  4726.6  517.95    4744   517.1  4766.3  516.93
  4795.1  517.69    4836  517.21  4846.2  517.73  4854.9  516.79  4897.4  517.88
  4904.4  516.43    4928  518.48  4938.3  518.16  4953.8  516.66  4958.9  517.12
  4986.4  516.34  4986.9  515.54  4991.9  515.54  4992.4  516.34  5020.1  516.89
  5047.6  516.58  5052.7  517.07  5061.8  516.68  5102.1  516.71  5132.6  517.83
  5163.9  516.77  5193.7  518.05  5214.1  517.77  5283.8  519.01  5291.1  518.71
#Mann= 4 ,-1 , 0
  4419.1     .05       0  4986.4     .03       0  4992.4     .05       0
  5061.8      .1       0
Bank Sta=4986.4,4992.4
XS Rating Curve= 0 ,0
Exp/Cntr=0.3,0.1

Type RM Length L Ch R = 1 ,7399    ,31,31,31
BEGIN DESCRIPTION:
Mapping XS 92f00273
END DESCRIPTION:
XS GIS Cut Line= 4
      2061466.15     13491549.89      2061150.17     13491892.93
        2061046.     13492257.51      2061102.77     13492371.05
#Sta/Elev= 30
  4268.9  527.16  4386.4  523.66  4428.9  522.72  4457.2  523.03  4464.6  522.17
  4499.8  521.27  4641.6  518.77    4776   515.6  4776.5   514.8  4781.5   514.8
    4782   515.6  4799.8  516.54  4812.1  516.04    4831  516.92  4840.7  516.25
  4851.8  516.64  4872.6  516.26  4879.7  516.38  4884.9  517.08  4918.7  515.77
  4952.5  516.26  4957.7  515.89  4991.5  516.18  5007.9  515.82  5025.3   516.4
    5111  516.27    5134  517.17    5165   517.2    5193  517.78  5241.4  517.66
#Mann= 4 ,-1 , 0
  4268.9     .05       0    4776     .03       0    4782     .05       0
    5111      .1       0
Bank Sta=4776,4782
XS Rating Curve= 0 ,0
Exp/Cntr=0.3,0.1

Type RM Length L Ch R = 1 ,7368    ,42,42,42
BEGIN DESCRIPTION:
Mapping XS ed32d1fb
END DESCRIPTION:
XS GIS Cut Line= 4
      2061300.26     13491590.67      2061096.27     13491935.73
      2061042.01     13492161.42      2060989.97     13492445.52
#Sta/Elev= 30
  4387.1  522.75  4461.1  521.23  4509.8  519.12  4541.1  519.45    4621  518.33
    4778  515.01  4778.5  514.21  4783.5  514.21    4784  515.01    4819  516.16
  4879.8  515.61  4897.8  516.45  4910.6  515.04  4920.9  515.22  4939.7  517.49
  4944.9  515.66  4951.8   516.4  4972.3  515.62  4992.9  516.38  5003.2  515.57
  5035.1  515.48  5088.3  516.61  5118.1  515.73  5141.4  516.53  5186.4  516.72
  5216.9  517.95  5252.8     518  5257.9  517.08  5277.9   516.3  5308.9  516.71
#Mann= 4 ,-1 , 0
  4387.1     .05       0    4778     .03       0    4784     .05       0
  5118.1      .1       0
Bank Sta=4778,4784
XS Rating Curve= 0 ,0
Exp/Cntr=0.3,0.1

Type RM Length L Ch R = 1 ,7326    ,49,49,49
BEGIN DESCRIPTION:
Mapping XS 0f3172e9
END DESCRIPTION:
XS GIS Cut Line= 4
      2061159.36     13491676.88      2061067.63     13491931.58
       2061027.7     13492051.36      2060958.64     13492308.16
#Sta/Elev= 30
  4520.2   518.9  4633.1  517.01  4656.4  516.54  4663.8  516.05  4669.1  516.29
  4677.6  515.44  4688.3  516.06  4699.8   515.7  4709.5  516.02  4773.3  514.53
  4786.6  514.63  4790.1  515.18  4812.7  515.33  4826.1   514.5  4875.9  513.51
  4881.2  513.08  4931.3  512.87    4952  512.42  4962.4  512.62  4990.4  511.57
  4990.9  510.77  4995.9  510.77  4996.4  511.57  5117.7  512.95  5136.3  513.65
  5141.5  513.37  5169.5  513.92  5176.3   514.5  5180.5  513.87  5183.1  513.87
#Mann= 3 ,-1 , 0
  4520.2     .05       0  4990.4     .03       0  4996.4     .05       0
Bank Sta=4990.4,4996.4
XS Rating Curve= 0 ,0
Exp/Cntr=0.3,0.1

Type RM Length L Ch R = 1 ,7277    ,103,103,103
BEGIN DESCRIPTION:
Mapping XS a43328f8
END DESCRIPTION:
XS GIS Cut Line= 4
      2061058.83     13491773.55      2060993.72     13491927.65
      2060941.63     13492211.94      2060941.63     13492290.03
#Sta/Elev= 30
  4639.8  516.33  4665.5   516.1  4673.9  516.39  4695.7  515.08  4712.9  514.79
  4728.2  514.22  4771.6  513.84  4794.9  513.23  4814.6  513.58  4823.7  513.47
  4855.2  512.24  4865.4  512.52  4881.9   512.4    4887  512.05  4906.1   511.8
  4926.4  511.79  4977.2   511.3  4993.3  510.65  5014.9  510.37  5015.4  509.57
  5020.4  509.57  5020.9  510.37  5046.5  511.67  5051.6  511.09  5058.6  511.17
  5078.9  512.07  5119.2  512.79  5139.2  513.57  5149.2  513.55  5174.2     514
#Mann= 3 ,-1 , 0
  4639.8     .05       0  5014.9     .03       0  5020.9     .05       0
Bank Sta=5014.9,5020.9
XS Rating Curve= 0 ,0
Exp/Cntr=0.3,0.1

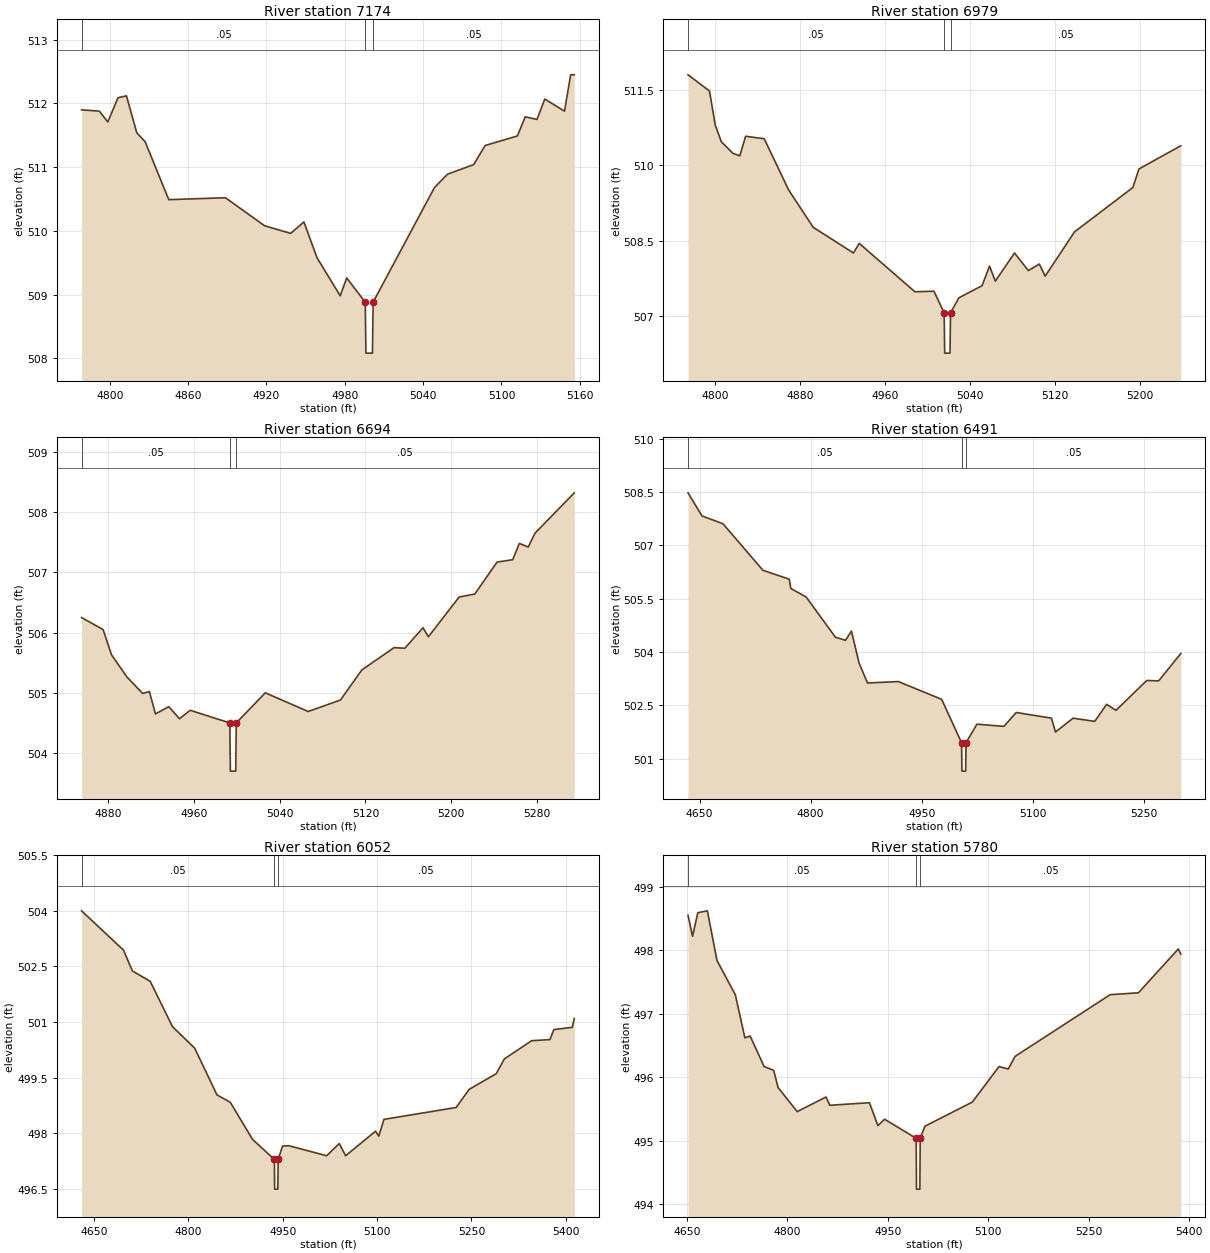
Type RM Length L Ch R = 1 ,7174    ,195,195,195
BEGIN DESCRIPTION:
Mapping XS 4a2e73d8
END DESCRIPTION:
XS GIS Cut Line= 4
      2060899.59     13491880.68      2060855.32      13491934.5
        2060864.     13492177.56       2060917.8     13492213.13
#Sta/Elev= 30
  4778.4   511.9    4792  511.88  4798.5  511.71  4806.3  512.09  4812.8  512.12
  4820.7  511.54  4827.1   511.4  4845.2  510.49  4888.6  510.52  4918.6  510.08
  4938.6  509.96  4948.7  510.14  4958.7  509.58  4976.5  508.98  4981.5  509.26
  4995.7  508.88  4996.2  508.08  5001.2  508.08  5001.7  508.88  5048.7  510.68
  5058.7  510.89  5078.7  511.04  5087.5  511.34  5112.2  511.49  5118.2  511.79
  5127.2  511.75  5133.2  512.07  5148.3  511.88    5153  512.45  5155.8  512.45
#Mann= 3 ,-1 , 0
  4778.4     .05       0  4995.7     .03       0  5001.7     .05       0
Bank Sta=4995.7,5001.7
XS Rating Curve= 0 ,0
Exp/Cntr=0.3,0.1

Type RM Length L Ch R = 1 ,6979    ,285,285,285
BEGIN DESCRIPTION:
Mapping XS d50e9158
END DESCRIPTION:
XS GIS Cut Line= 4
      2060853.57     13491849.44      2060729.45     13491905.86
      2060641.77     13492108.11      2060686.04      13492206.2
#Sta/Elev= 30
  4774.5   511.8  4794.7  511.48  4800.2   510.8  4805.9  510.47  4816.9  510.24
  4823.3  510.19  4828.8  510.58  4846.3  510.53  4869.4  509.51  4892.5  508.77
  4930.4  508.26  4935.9  508.45  4988.3  507.49  5006.3   507.5  5015.9  507.07
  5016.4  506.27  5021.4  506.27  5021.9  507.07  5029.8  507.37  5051.6  507.61
  5058.7     508  5064.1   507.7  5082.2  508.26  5095.2  507.91  5105.6  508.04
  5111.1   507.8  5138.8  508.68  5193.7  509.56  5199.5  509.93  5238.9  510.39
#Mann= 3 ,-1 , 0
  4774.5     .05       0  5015.9     .03       0  5021.9     .05       0
Bank Sta=5015.9,5021.9
XS Rating Curve= 0 ,0
Exp/Cntr=0.3,0.1

Type RM Length L Ch R = 1 ,6694    ,203,203,203
BEGIN DESCRIPTION:
Mapping XS 9eabfee2
END DESCRIPTION:
XS GIS Cut Line= 4
      2060488.14     13491779.11      2060442.99     13491837.28
       2060429.1     13492101.17      2060502.86     13492198.36
#Sta/Elev= 30
  4855.1  506.25  4875.2  506.05  4883.1  505.63  4897.6  505.26  4912.1  504.99
  4918.4  505.02  4924.1  504.65  4936.5  504.77  4946.5  504.57  4956.5  504.71
  4993.5   504.5    4994   503.7    4999   503.7  4999.5   504.5  5026.6     505
  5066.6  504.69  5096.7  504.88  5116.7  505.38  5146.8  505.75  5156.8  505.74
  5173.8  506.08  5178.8  505.93  5207.5  506.59  5222.1  506.64  5242.9  507.17
  5257.5  507.21  5263.7  507.48    5272  507.42  5278.3  507.65    5315  508.32
#Mann= 3 ,-1 , 0
  4855.1     .05       0  4993.5     .03       0  4999.5     .05       0
Bank Sta=4993.5,4999.5
XS Rating Curve= 0 ,0
Exp/Cntr=0.3,0.1

Type RM Length L Ch R = 1 ,6491    ,439,439,439
BEGIN DESCRIPTION:
Mapping XS 7371c815
END DESCRIPTION:
XS GIS Cut Line= 4
      2060463.43     13491638.47      2060326.74     13491671.01
      2060161.81     13492065.98      2060187.84     13492159.28
#Sta/Elev= 30
  4634.4  508.48  4653.3  507.83  4681.6  507.61  4735.6   506.3  4771.1  506.05
  4773.2  505.79  4793.9  505.55  4833.4  504.42    4847  504.33  4855.1  504.59
  4865.4  503.69  4876.8  503.13  4918.4  503.17  4976.9  502.67  5003.8  501.45
  5004.3  500.65  5009.3  500.65  5009.8  501.45  5024.5  501.97    5061  501.91
  5077.6   502.3  5125.2  502.14  5130.6  501.75  5154.4  502.14  5183.6  502.05
  5199.7  502.53  5212.3  502.36  5253.8   503.2    5270  503.19  5299.8  503.96
#Mann= 3 ,-1 , 0
  4634.4     .05       0  5003.8     .03       0  5009.8     .05       0
Bank Sta=5003.8,5009.8
XS Rating Curve= 0 ,0
Exp/Cntr=0.3,0.1

Type RM Length L Ch R = 1 ,6052    ,272,272,272
BEGIN DESCRIPTION:
Mapping XS 2e310a13
END DESCRIPTION:
XS GIS Cut Line= 5
      2060005.87     13491571.59       2059796.8     13491782.88
      2059806.75     13491943.26      2059860.95     13492126.87
      2059940.84     13492234.11
#Sta/Elev= 30
  4630.4     504  4697.1  502.94  4711.2  502.38  4739.5   502.1  4774.9  500.88
  4810.2   500.3  4845.6  499.04  4866.8  498.84  4902.2  497.84  4936.8   497.3
  4937.3   496.5  4942.3   496.5  4942.8   497.3  4949.8  497.66  4959.8  497.67
  5019.9   497.4    5040  497.73    5050   497.4  5097.6  498.06  5102.8  497.93
    5111  498.38  5225.7   498.7  5246.5  499.19  5289.3  499.61  5302.4  500.01
  5345.6   500.5  5374.8  500.53    5381   500.8  5410.2  500.86  5413.5   501.1
#Mann= 3 ,-1 , 0
  4630.4     .05       0  4936.8     .03       0  4942.8     .05       0
Bank Sta=4936.8,4942.8
XS Rating Curve= 0 ,0
Exp/Cntr=0.3,0.1

Type RM Length L Ch R = 1 ,5780    ,148,148,148
BEGIN DESCRIPTION:
Mapping XS a4e20282
END DESCRIPTION:
XS GIS Cut Line= 4
      2059701.73     13491551.67        2059563.     13491718.79
      2059552.15     13491920.61      2059671.36     13492213.57
#Sta/Elev= 30
  4651.7  498.55  4658.5  498.22  4666.3  498.59  4680.6  498.62  4694.9  497.84
  4722.3   497.3  4736.6  496.62  4744.4  496.65  4765.3  496.17  4779.6  496.11
  4786.1  495.84  4814.7  495.46  4857.7  495.69  4863.4  495.56  4922.5   495.6
  4935.2  495.24  4945.2  495.34  4992.3  495.04  4992.8  494.24  4997.8  494.24
  4998.3  495.04  5005.3  495.23  5076.1  495.61    5116  496.17  5129.7  496.13
    5140  496.33  5281.9   497.3  5324.1  497.33  5383.6  498.02  5387.3  497.94
#Mann= 3 ,-1 , 0
  4651.7     .05       0  4992.3     .03       0  4998.3     .05       0
Bank Sta=4992.3,4998.3
XS Rating Curve= 0 ,0
Exp/Cntr=0.3,0.1

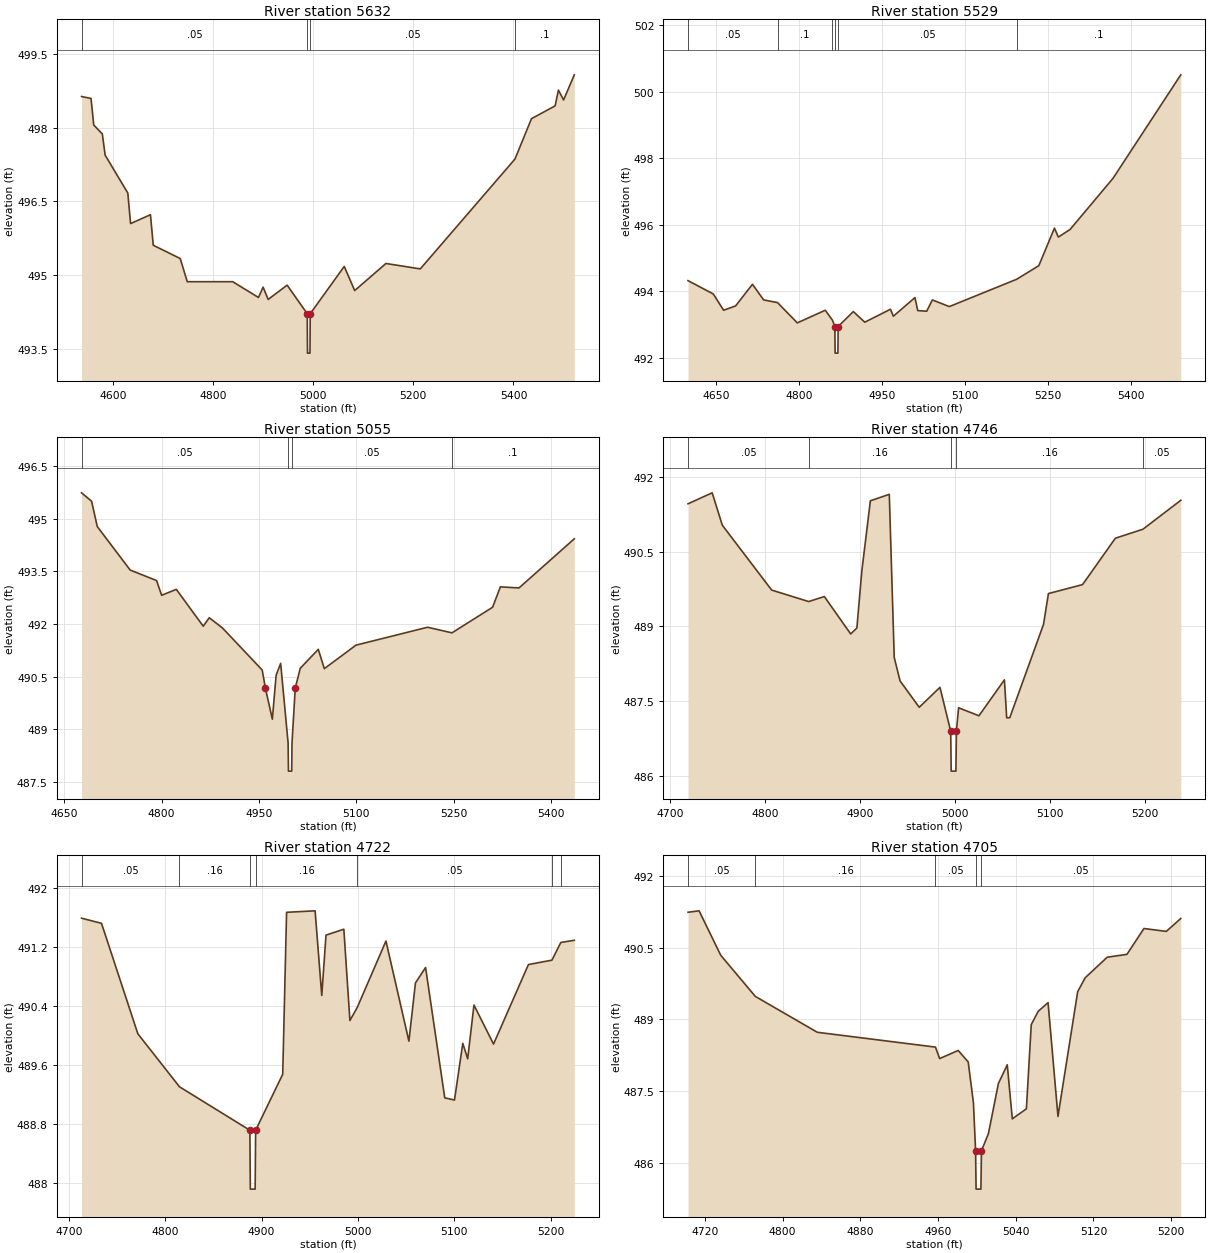
Type RM Length L Ch R = 1 ,5632    ,103,103,103
BEGIN DESCRIPTION:
Mapping XS a0e9ca86
END DESCRIPTION:
XS GIS Cut Line= 4
      2059570.31     13491337.37      2059467.41     13491551.43
      2059382.34     13492089.62      2059429.22     13492285.82
#Sta/Elev= 30
  4537.4  498.63  4556.3  498.59  4561.8  498.05  4578.9  497.87  4584.5  497.44
  4629.8  496.67  4635.3  496.05    4675  496.23  4680.6  495.61  4734.5  495.34
  4748.5  494.87  4839.3  494.87  4890.7  494.55    4900  494.76  4910.1  494.51
    4948   494.8  4988.1  494.22  4988.6  493.42  4993.6  493.42  4994.1  494.22
    5062  495.18  5082.9  494.69  5145.3  495.24  5213.9  495.13    5403  497.36
    5436  498.18  5483.2  498.44  5489.8  498.76  5500.1  498.56  5521.5  499.07
#Mann= 4 ,-1 , 0
  4537.4     .05       0  4988.1     .03       0  4994.1     .05       0
    5403      .1       0
Bank Sta=4988.1,4994.1
XS Rating Curve= 0 ,0
Exp/Cntr=0.3,0.1

Type RM Length L Ch R = 1 ,5529    ,474,474,474
BEGIN DESCRIPTION:
Mapping XS 1f726dfe
END DESCRIPTION:
XS GIS Cut Line= 4
        2059421.     13491320.01       2059366.6     13491651.51
      2059313.43     13491897.83      2059102.95      13492115.9
#Sta/Elev= 30
  4599.3  494.32  4644.9  493.92  4663.7  493.43  4685.4  493.56  4715.8  494.21
  4736.1  493.74  4761.1  493.66  4796.9  493.05  4847.5  493.43  4860.5  493.13
  4864.8  492.94  4865.3  492.14  4870.3  492.14  4870.8  492.94  4898.2  493.39
  4918.9  493.07  4965.4  493.46  4970.6  493.25  5009.6  493.81  5014.7  493.42
  5030.9   493.4  5041.1  493.74  5071.8  493.54  5193.4  494.36  5233.6  494.77
  5261.9   495.9  5268.9  495.63  5290.2  495.86  5367.9   497.4  5490.3  500.51
#Mann= 6 ,-1 , 0
  4599.3     .05       0  4761.1      .1       0  4860.5     .05       0
  4864.8     .04       0  4870.8     .05       0  5193.4      .1       0
Bank Sta=4864.8,4870.8
XS Rating Curve= 0 ,0
Exp/Cntr=0.3,0.1

Type RM Length L Ch R = 1 ,5055    ,309,309,309
BEGIN DESCRIPTION:
Mapping XS d5ef683f
END DESCRIPTION:
XS GIS Cut Line= 4
      2059448.79     13491267.93      2059213.56     13491309.76
      2059009.57     13491429.55       2058959.2     13491708.86
#Sta/Elev= 30
  4676.7  495.74  4692.2   495.5  4700.9  494.78  4751.6  493.54  4792.3  493.24
  4800.1  492.82  4822.7  492.99  4864.2  491.94  4873.5  492.18  4893.8  491.89
  4955.1  490.69 4960.02490.1725  4970.7  489.29  4976.5  490.54  4983.5  490.88
    4995  488.61  4995.5  487.81  5000.5  487.81    5001  488.61 5005.98490.1738
  5013.7  490.74  5041.5  491.28  5050.8  490.73  5099.6   491.4  5209.9  491.91
  5247.5  491.75  5310.1  492.48  5322.1  493.06  5350.8  493.03    5436  494.43
#Mann= 4 ,-1 , 0
  4676.7     .05       0    4995     .03       0    5001     .05       0
  5247.5      .1       0
Bank Sta=4960.02,5005.98
XS Rating Curve= 0 ,0
Exp/Cntr=0.3,0.1

Type RM Length L Ch R = 1 ,4746    ,24,24,24
BEGIN DESCRIPTION:
Mapping XS e78e2966
END DESCRIPTION:
XS GIS Cut Line= 6
      2059159.74     13491111.84      2058939.26     13491173.48
      2058906.27     13491174.34      2058892.38     13491211.67
      2058900.19     13491244.66      2058944.89     13491421.74
#Sta/Elev= 30
    4719  491.46  4744.4  491.68  4755.1  491.03    4807  489.73  4845.9   489.5
  4862.4   489.6  4890.1  488.85  4896.6  488.97  4901.8  490.11  4910.8  491.52
  4930.7  491.65  4935.9  488.38    4942  487.91  4962.2  487.38    4984  487.78
  4995.3   486.9  4995.8   486.1  5000.8   486.1  5001.3   486.9  5003.6  487.37
    5025  487.21  5051.8  487.93  5054.2  487.17  5057.4  487.17  5092.9  489.04
  5098.1  489.66    5134  489.84  5168.5  490.77  5197.5  490.95  5237.3  491.53
#Mann= 5 ,-1 , 0
    4719     .05       0  4845.9     .16       0  4995.3     .07       0
  5001.3     .16       0  5197.5     .05       0
Bank Sta=4995.3,5001.3
XS Rating Curve= 0 ,0
Exp/Cntr=0.3,0.1

Type RM Length L Ch R = 1 ,4722    ,17,17,17
BEGIN DESCRIPTION:
Mapping XS c263b93b
END DESCRIPTION:
XS GIS Cut Line= 6
      2059134.56      13491080.6      2058932.31     13491150.91
      2058891.51     13491161.32      2058871.55     13491195.18
      2058882.83     13491250.73      2058907.14     13491407.84
#Sta/Elev= 30
  4713.3  491.59    4734  491.52  4771.7  490.02  4814.9   489.3  4887.9  488.71
  4888.4  487.91  4893.4  487.91  4893.9  488.71    4922  489.47    4926  491.67
  4955.6  491.69  4962.5  490.54  4966.9  491.36  4985.4  491.44  4991.7   490.2
  4999.4  490.38  5029.1  491.28  5052.9  489.92  5059.7  490.71  5070.2  490.92
  5090.1  489.15  5100.2  489.12  5108.8  489.89  5113.9  489.68  5120.4  490.41
  5140.7  489.88  5176.9  490.96  5201.3  491.02  5210.5  491.26  5224.5  491.29
#Mann= 7 ,-1 , 0
  4713.3     .05       0  4814.9     .16       0  4887.9     .03       0
  4893.9     .16       0  4999.4     .05       0  5201.3     .16       0
  5210.5     .05       0
Bank Sta=4887.9,4893.9
XS Rating Curve= 0 ,0
Exp/Cntr=0.3,0.1

Type RM Length L Ch R = 1 ,4705    ,284,284,284
BEGIN DESCRIPTION:
Mapping XS f80fc9a6
END DESCRIPTION:
XS GIS Cut Line= 4
      2059105.97     13491061.48      2058873.28     13491130.94
      2058848.11     13491224.69       2058875.9     13491389.67
#Sta/Elev= 30
  4702.7  491.24  4714.1  491.27  4736.4  490.34    4772  489.48  4835.8  488.73
  4957.4  488.42  4961.7  488.18  4980.8  488.35  4991.1  488.11  4996.5  487.25
  4998.7  486.25  4999.2  485.45  5004.2  485.45  5004.7  486.25  5011.9  486.61
  5022.2  487.66  5031.3  488.05  5036.5  486.92    5051  487.13    5056  488.89
  5063.2  489.17  5073.3  489.35  5083.5  486.97  5103.8  489.58  5111.5  489.87
  5134.2   490.3  5154.5  490.36    5172   490.9    5195  490.84  5209.9  491.11
#Mann= 5 ,-1 , 0
  4702.7     .05       0    4772     .16       0  4957.4     .05       0
  4998.7     .03       0  5004.7     .05       0
Bank Sta=4998.7,5004.7
XS Rating Curve= 0 ,0
Exp/Cntr=0.3,0.1

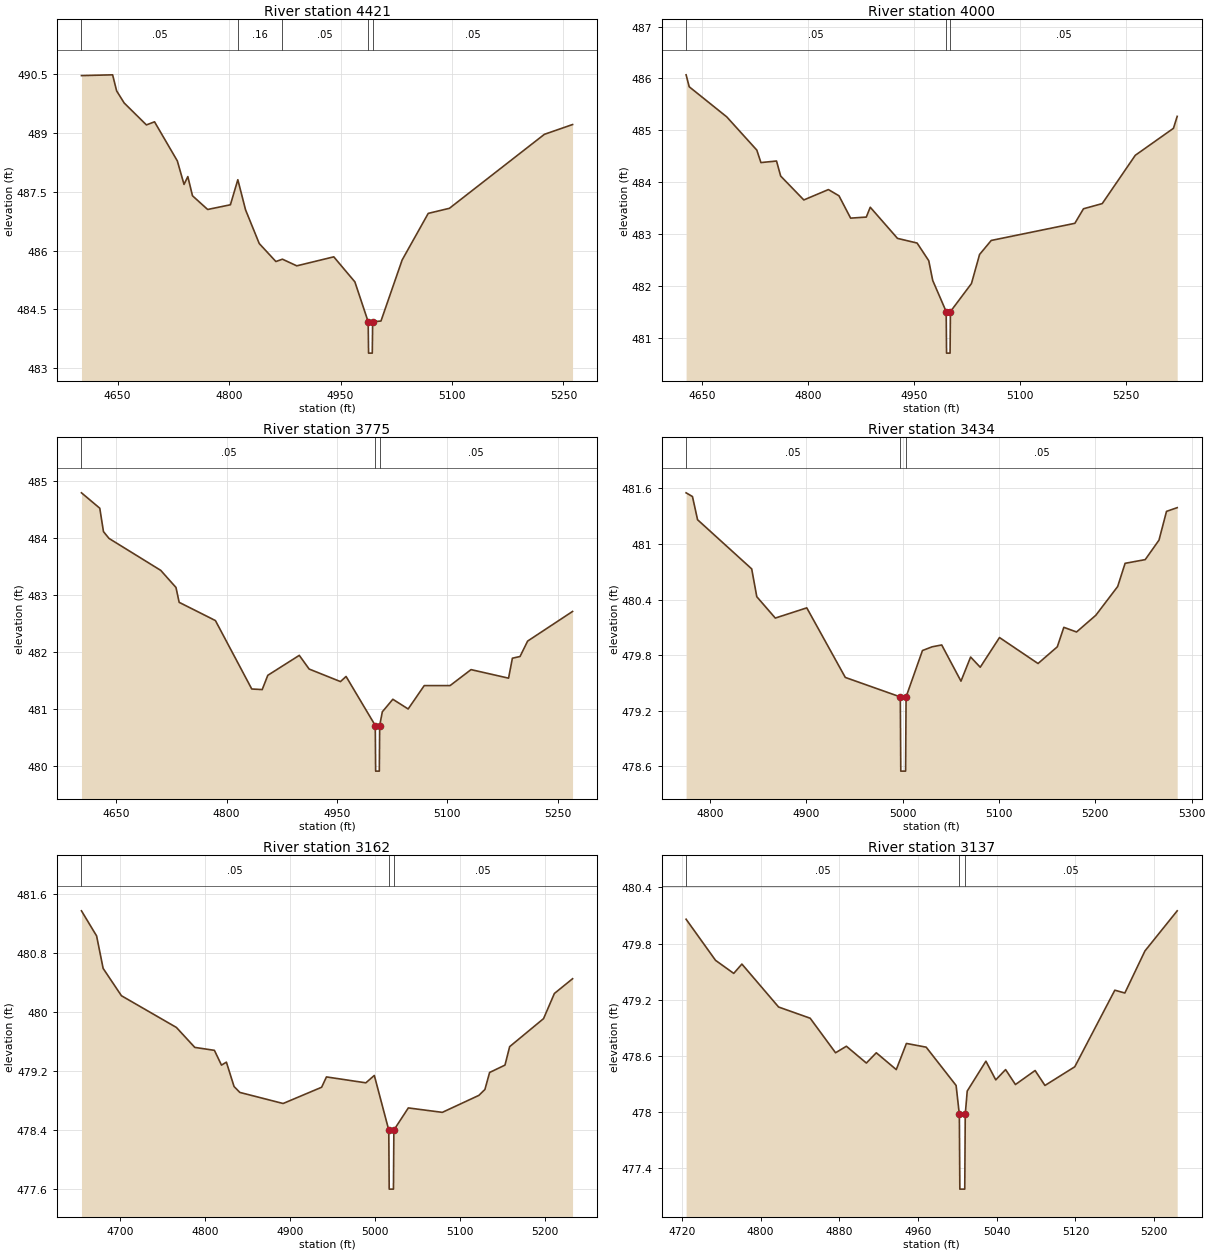
Type RM Length L Ch R = 1 ,4421    ,421,421,421
BEGIN DESCRIPTION:
Mapping XS 6f878423
END DESCRIPTION:
XS GIS Cut Line= 3
      2059031.37     13490841.69       2058739.3     13490901.14
      2058499.65     13491173.44
#Sta/Elev= 30
  4601.4  490.47  4643.3  490.49  4648.7  490.08  4658.9  489.77  4688.8  489.21
  4699.7  489.29  4730.4  488.29  4739.4  487.69  4744.5  487.89  4750.8   487.4
  4771.2  487.05  4801.8  487.17  4811.8  487.81  4822.2  487.04  4840.6  486.18
    4863  485.72  4871.8  485.78  4891.1  485.61  4940.9  485.84  4969.3   485.2
  4987.2  484.18  4987.7  483.38  4992.7  483.38  4993.2  484.18  5004.4   484.2
  5032.9  485.76    5068  486.95  5096.5  487.08  5224.3  488.97  5262.2  489.22
#Mann= 5 ,-1 , 0
  4601.4     .05       0  4811.8     .16       0  4871.8     .05       0
  4987.2     .03       0  4993.2     .05       0
Bank Sta=4987.2,4993.2
XS Rating Curve= 0 ,0
Exp/Cntr=0.3,0.1

Type RM Length L Ch R = 1 ,4000    ,225,225,225
BEGIN DESCRIPTION:
Mapping XS f0f7f39f
END DESCRIPTION:
XS GIS Cut Line= 4
      2058770.72     13490562.07      2058688.28     13490540.37
      2058278.12     13490753.04      2058297.61      13490900.3
#Sta/Elev= 30
  4627.4  486.07  4631.8  485.84    4685  485.26  4727.6  484.62  4733.4  484.38
  4755.5  484.41  4761.4  484.12  4794.2  483.66    4829  483.86    4844  483.74
  4860.5  483.31  4882.7  483.33  4888.3  483.52  4926.9  482.92  4954.7  482.83
  4971.2  482.49  4976.8  482.11  4995.9  481.51  4996.4  480.71  5001.4  480.71
  5001.9  481.51  5031.7  482.05  5043.2  482.61  5059.7  482.88  5178.2  483.21
  5190.4  483.49    5217  483.59  5263.8  484.52  5317.9  485.04  5323.2  485.27
#Mann= 3 ,-1 , 0
  4627.4     .05       0  4995.9     .03       0  5001.9     .05       0
Bank Sta=4995.9,5001.9
XS Rating Curve= 0 ,0
Exp/Cntr=0.3,0.1

Type RM Length L Ch R = 1 ,3775    ,341,341,341
BEGIN DESCRIPTION:
Mapping XS 5148ba46
END DESCRIPTION:
XS GIS Cut Line= 4
      2058562.39      13490327.7      2058434.37     13490338.55
      2058139.24     13490677.09       2058163.1     13490763.87
#Sta/Elev= 30
  4602.6  484.79  4627.5  484.52  4632.5  484.11  4640.1  483.99  4710.4  483.43
  4731.1  483.13  4735.4  482.87  4784.7  482.55  4834.1  481.35  4848.3  481.34
  4855.9  481.59  4898.7  481.94  4912.1   481.7  4954.7  481.48  4962.3  481.57
    5002  480.71  5002.5  479.91  5007.5  479.91    5008  480.71  5011.6  480.95
  5025.9  481.17  5046.7     481  5068.6  481.41  5103.7  481.41  5132.2  481.69
  5183.2  481.54  5188.4  481.89  5198.8  481.92  5209.1  482.19  5270.2  482.71
#Mann= 3 ,-1 , 0
  4602.6     .05       0    5002     .03       0    5008     .05       0
Bank Sta=5002,5008
XS Rating Curve= 0 ,0
Exp/Cntr=0.3,0.1

Type RM Length L Ch R = 1 ,3434    ,272,272,272
BEGIN DESCRIPTION:
Mapping XS 457fa4e8
END DESCRIPTION:
XS GIS Cut Line= 4
      2058052.14     13490266.34      2057957.49     13490300.21
      2057948.81     13490640.49      2057993.05     13490693.41
#Sta/Elev= 30
  4775.1  481.55  4781.7  481.51    4787  481.26  4843.2  480.73  4848.5  480.43
  4867.7   480.2  4900.4  480.31  4940.4  479.56  4997.5  479.35    4998  478.55
    5003  478.55  5003.5  479.35  5020.5  479.85  5030.5  479.89  5040.5  479.91
  5060.5  479.52  5070.5  479.78  5080.5  479.67  5100.5  479.99  5140.5  479.71
  5160.5  479.89  5167.3   480.1  5180.5  480.05  5200.5  480.23  5223.2  480.54
  5230.9  480.79  5251.8  480.83  5266.1  481.04  5273.9  481.35    5285  481.39
#Mann= 3 ,-1 , 0
  4775.1     .05       0  4997.5     .03       0  5003.5     .05       0
Bank Sta=4997.5,5003.5
XS Rating Curve= 0 ,0
Exp/Cntr=0.3,0.1

Type RM Length L Ch R = 1 ,3162    ,25,25,25
BEGIN DESCRIPTION:
Mapping XS b5a6975a
END DESCRIPTION:
XS GIS Cut Line= 4
      2057863.72      13490209.6      2057717.97     13490461.82
      2057722.32     13490601.79      2057779.84     13490736.37
#Sta/Elev= 30
  4654.8  481.37  4672.6  481.03  4680.3  480.59  4701.8  480.22  4766.5  479.79
  4788.1  479.52  4811.2  479.48  4819.5  479.28  4825.3  479.32  4834.3  478.99
  4841.1  478.91    4892  478.76  4937.3  478.98    4943  479.12  4989.3  479.04
  4999.3  479.14  5016.3   478.4  5016.8   477.6  5021.8   477.6  5022.3   478.4
  5039.3   478.7  5079.3  478.64  5122.3  478.87  5129.4  478.95  5134.9  479.18
    5153  479.28  5158.5  479.53  5198.4  479.91  5211.1  480.25  5232.5  480.45
#Mann= 3 ,-1 , 0
  4654.8     .05       0  5016.3     .03       0  5022.3     .05       0
Bank Sta=5016.3,5022.3
XS Rating Curve= 0 ,0
Exp/Cntr=0.3,0.1

Type RM Length L Ch R = 1 ,3137    ,148,148,148
BEGIN DESCRIPTION:
Mapping XS 877822c7
END DESCRIPTION:
XS GIS Cut Line= 6
      2057717.97     13490258.88      2057717.97     13490259.99
      2057676.74     13490388.03      2057702.78     13490549.71
      2057704.95       13490630.      2057727.74     13490747.19
#Sta/Elev= 30
  4724.3  480.06  4754.2  479.62  4772.7  479.48    4781  479.58  4818.3  479.12
  4850.4     479  4876.2  478.63  4887.2   478.7  4907.5  478.52  4917.6  478.63
  4937.9  478.45  4948.2  478.73  4968.3  478.69  4998.7  478.28    5002  477.97
  5002.5  477.17  5007.5  477.17    5008  477.97    5010  478.22    5029  478.54
    5039  478.34    5049  478.45    5059  478.29    5079  478.44    5089  478.28
  5119.3  478.48    5160   479.3  5170.2  479.27  5190.6  479.72  5223.4  480.15
#Mann= 3 ,-1 , 0
  4724.3     .05       0    5002     .03       0    5008     .05       0
Bank Sta=5002,5008
XS Rating Curve= 0 ,0
Exp/Cntr=0.3,0.1