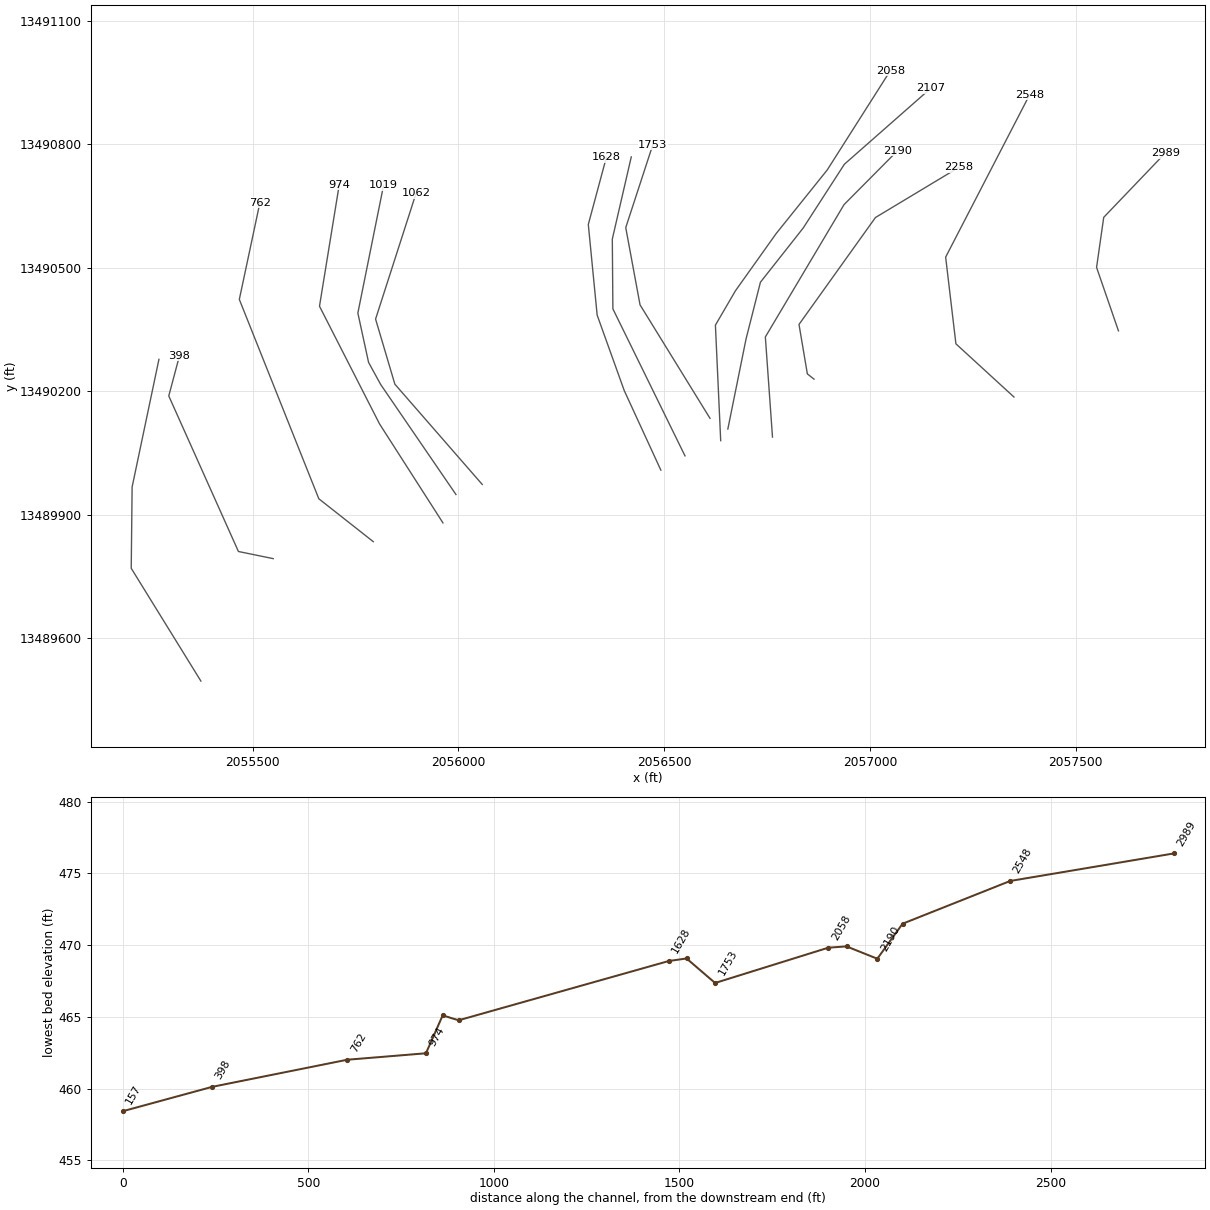
HEC-RAS study UNT 104 in Lagunillas Cr Wtrshd.prj: UNT 104 in Lagunillas Cr Wtrshd Base Level Engineering

--- UNT 104 in Lagunillas Cr Wtrshd.g01 (geometry) --- (continued)

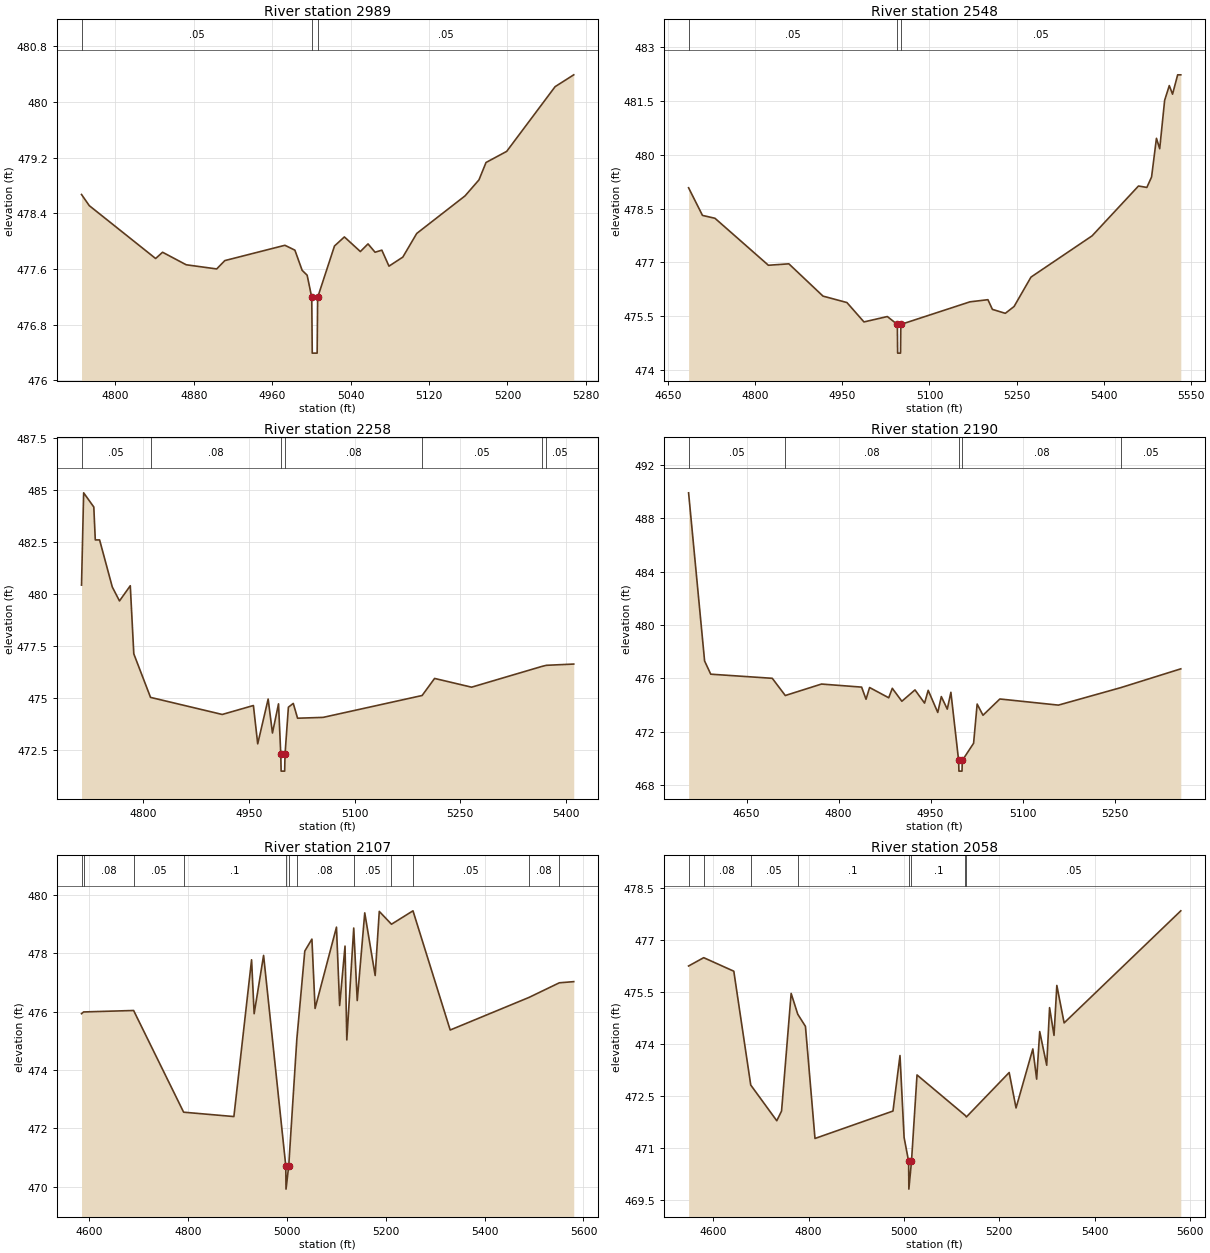
Type RM Length L Ch R = 1 ,2989    ,441,441,441
BEGIN DESCRIPTION:
Mapping XS a6e0f314
END DESCRIPTION:
XS GIS Cut Line= 4
      2057604.04     13490346.81      2057550.87     13490500.88
      2057568.24     13490622.41        2057718.     13490778.69
#Sta/Elev= 30
  4765.5  478.67  4773.4  478.51  4841.1  477.75  4848.2  477.84  4872.3  477.66
  4903.4   477.6  4911.7  477.72    4973  477.94  4983.2  477.87  4990.6  477.58
  4995.7  477.51  5000.4  477.19  5000.9  476.39  5005.9  476.39  5006.4  477.19
  5023.6  477.93  5033.7  478.06    5050  477.85  5057.8  477.96    5065  477.84
  5071.9  477.87  5079.2  477.64  5093.3  477.77  5107.5  478.11  5156.8  478.65
    5171  478.88  5178.2  479.13  5199.3  479.29  5248.7  480.22  5267.7  480.39
#Mann= 3 ,-1 , 0
  4765.5     .05       0  5000.4     .03       0  5006.4     .05       0
Bank Sta=5000.4,5006.4
XS Rating Curve= 0 ,0
Exp/Cntr=0.3,0.1

Type RM Length L Ch R = 1 ,2548    ,290,290,290
BEGIN DESCRIPTION:
Mapping XS b2d98c22
END DESCRIPTION:
XS GIS Cut Line= 4
      2057350.13     13490186.21      2057209.08     13490315.33
      2057184.12     13490525.83        2057388.     13490919.68
#Sta/Elev= 30
  4685.6  479.08  4709.5  478.31    4731  478.23  4822.9  476.92  4858.1  476.96
  4916.8  476.06    4958  475.88  4987.3  475.34  5027.5  475.49  5044.7  475.27
  5045.2  474.47  5050.2  474.47  5050.7  475.27  5169.6   475.9  5200.5  475.96
  5208.2  475.69  5230.4  475.58  5245.5  475.77  5274.6  476.59  5379.7  477.74
  5459.5  479.13  5473.9  479.09    5482  479.38  5490.4  480.46    5496  480.17
  5504.5  481.52  5512.5  481.93  5518.1  481.69  5526.9  482.23  5532.3  482.23
#Mann= 3 ,-1 , 0
  4685.6     .05       0  5044.7     .03       0  5050.7     .05       0
Bank Sta=5044.7,5050.7
XS Rating Curve= 0 ,0
Exp/Cntr=0.3,0.1

Type RM Length L Ch R = 1 ,2258    ,68,68,68
BEGIN DESCRIPTION:
Mapping XS b873af5f
END DESCRIPTION:
XS GIS Cut Line= 6
      2056864.21     13490229.64      2056847.75     13490242.63
      2056847.75     13490244.37      2056827.78     13490362.42
      2057013.55     13490621.97      2057215.83     13490743.52
#Sta/Elev= 30
  4713.1  480.42  4716.1  484.85  4730.5  484.17  4732.6  482.59  4738.7  482.59
  4756.7  480.33  4766.9  479.66  4782.2  480.39  4787.2  477.12  4810.9  475.03
  4912.5  474.21  4956.7  474.64  4962.8   472.8  4977.6  474.95  4983.7  473.32
  4992.3  474.72  4995.5  472.29    4996  471.49    5001  471.49  5001.5  472.29
  5006.3  474.56  5013.2  474.74  5019.3  474.03  5055.5  474.07  5195.8  475.12
  5213.5  475.94  5265.9  475.52  5365.9  476.52    5372  476.57  5410.7  476.63
#Mann= 7 ,-1 , 0
  4713.1     .05       0  4810.9     .08       0  4995.5     .07       0
  5001.5     .08       0  5195.8     .05       0  5365.9     .08       0
    5372     .05       0
Bank Sta=4995.5,5001.5
XS Rating Curve= 0 ,0
Exp/Cntr=0.3,0.1

Type RM Length L Ch R = 1 ,2190    ,83,83,83
BEGIN DESCRIPTION:
Mapping XS 57a39652
END DESCRIPTION:
XS GIS Cut Line= 4
      2056763.37       13490089.      2056746.01     13490332.04
      2056937.16     13490653.22      2057067.38     13490784.31
#Sta/Elev= 30
  4555.6  489.92  4581.7  477.31  4591.7  476.32    4692  476.01  4713.2  474.72
  4772.2  475.58  4837.6  475.35  4844.8  474.44  4850.6  475.32  4881.8  474.55
  4887.6  475.26  4903.2  474.29  4924.6  475.14  4940.2  474.15  4946.1  475.11
  4961.7  473.45  4967.5  474.64  4977.2   473.7  4983.1  474.96  4995.7  469.85
  4996.2  469.05  5001.2  469.05  5001.7  469.85  5020.1  471.14  5025.9  474.08
  5035.4  473.24  5062.9  474.46  5158.3     474  5259.9  475.31  5357.8  476.72
#Mann= 5 ,-1 , 0
  4555.6     .05       0  4713.2     .08       0  4995.7     .07       0
  5001.7     .08       0  5259.9     .05       0
Bank Sta=4995.7,5001.7
XS Rating Curve= 0 ,0
Exp/Cntr=0.3,0.1

Type RM Length L Ch R = 1 ,2107    ,49,49,49
BEGIN DESCRIPTION:
Mapping XS c4a6701b
END DESCRIPTION:
XS GIS Cut Line= 6
      2056654.86     13490108.51      2056699.13     13490327.26
      2056734.03     13490464.85       2056838.2      13490596.8
      2056938.03     13490751.31      2057147.47     13490935.33
#Sta/Elev= 30
  4584.3  475.93  4588.4  475.99  4689.7  476.04  4790.9  472.55  4892.6   472.4
  4928.4  477.78  4933.6  475.93  4952.7  477.93  4997.6  470.71  4998.1  469.91
  5003.6  470.71    5020  475.06  5036.1  478.08  5050.5  478.49  5056.9  476.11
  5100.2   478.9  5106.6  476.21  5117.5  478.25  5121.1  475.03  5135.1  478.87
  5142.2  476.38  5157.4  479.39  5178.5  477.24  5186.8  479.44  5211.5     479
    5255  479.46  5330.3  475.37    5490  476.49  5551.1  476.99  5580.3  477.03
#Mann= 12 ,-1 , 0
  4584.3     .05       0  4588.4     .08       0  4689.7     .05       0
  4790.9      .1       0  4997.6     .07       0  5003.6      .1       0
    5020     .08       0  5135.1     .05       0  5211.5     .08       0
    5255     .05       0    5490     .08       0  5551.1     .05       0
Bank Sta=4997.6,5003.6
XS Rating Curve= 0 ,0
Exp/Cntr=0.3,0.1

Type RM Length L Ch R = 1 ,2058    ,305,305,305
BEGIN DESCRIPTION:
Mapping XS 7fcd4830
END DESCRIPTION:
XS GIS Cut Line= 6
       2056637.5     13490080.26      2056624.66     13490360.69
      2056673.27     13490444.02      2056772.23     13490582.91
      2056896.36     13490737.42      2057049.82     13490978.73
#Sta/Elev= 30
  4548.5  476.25  4580.2  476.49  4643.3   476.1  4678.8  472.82  4733.4  471.79
  4743.4  472.07  4763.5  475.46  4777.4  474.86  4793.5  474.51  4813.5  471.28
    4977  472.07  4991.7  473.67  5000.3  471.31  5009.8  470.62  5010.3  469.82
  5015.8  470.62  5027.4  473.11  5128.8  471.94  5130.9   471.9  5220.6  473.18
    5235  472.16  5270.2  473.86  5278.2  472.99  5284.6  474.36  5299.3  473.39
  5305.3  475.05  5314.6  474.25  5320.5  475.69  5335.8  474.61  5580.4  477.84
#Mann= 8 ,-1 , 0
  4548.5     .05       0  4580.2     .08       0  4678.8     .05       0
  4777.4      .1       0  5009.8     .07       0  5015.8      .1       0
  5128.8     .08       0  5130.9     .05       0
Bank Sta=5009.8,5015.8
XS Rating Curve= 0 ,0
Exp/Cntr=0.3,0.1

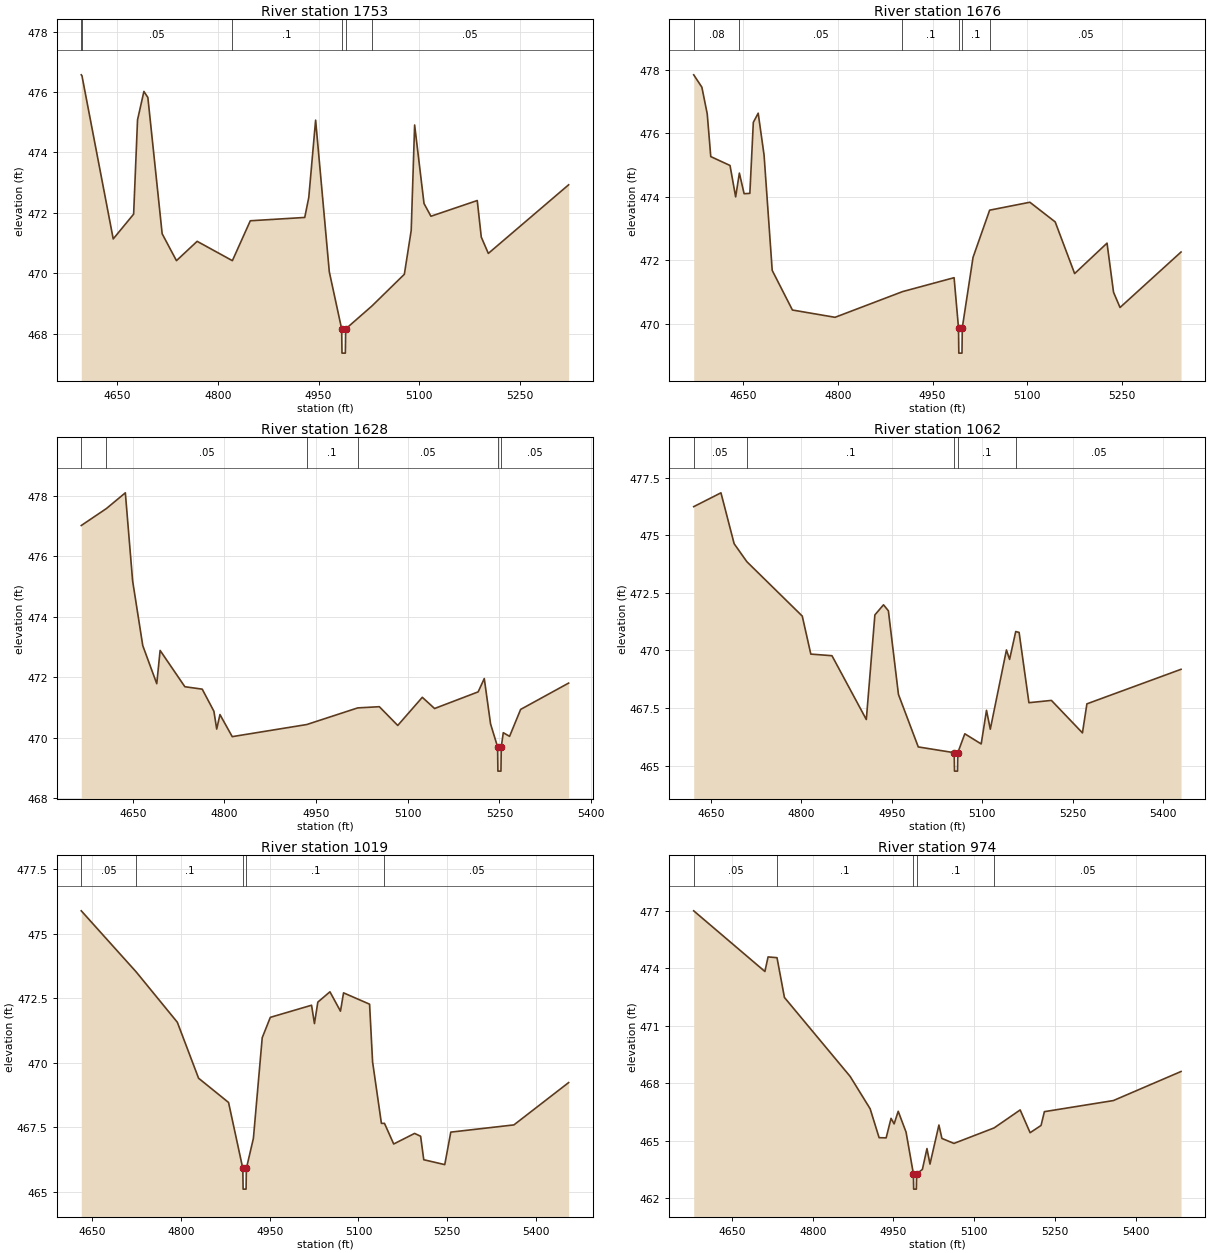
Type RM Length L Ch R = 1 ,1753    ,77,77,77
BEGIN DESCRIPTION:
Mapping XS 3c82c362
END DESCRIPTION:
XS GIS Cut Line= 4
      2056611.47     13490134.53       2056441.5     13490409.99
      2056406.78     13490597.49      2056472.57     13490798.63
#Sta/Elev= 30
  4596.5  476.57  4597.5  476.54  4644.1  471.14  4674.5  471.96  4680.3  475.08
  4689.8  476.02  4695.7  475.82    4717  471.31  4738.3  470.42  4769.1  471.06
  4821.6  470.42  4848.3  471.74  4929.4  471.85  4935.4  472.51  4945.6  475.07
    4966  470.05  4984.4  468.16  4984.9  467.36  4989.9  467.36  4990.4  468.16
  5029.5  468.92  5077.8  469.97    5088  471.42  5093.1  474.91  5107.1  472.31
  5117.4  471.89  5186.4  472.41  5192.4   471.2  5202.9  470.66  5322.5  472.93
#Mann= 6 ,-1 , 0
  4596.5     .08       0  4597.5     .05       0  4821.6      .1       0
  4984.4     .07       0  4990.4      .1       0  5029.5     .05       0
Bank Sta=4984.4,4990.4
XS Rating Curve= 0 ,0
Exp/Cntr=0.3,0.1

Type RM Length L Ch R = 1 ,1676    ,48,48,48
BEGIN DESCRIPTION:
Mapping XS faf1775c
END DESCRIPTION:
XS GIS Cut Line= 4
      2056550.71     13490043.38      2056375.53     13490400.27
      2056374.14     13490569.72       2056420.2     13490769.15
#Sta/Elev= 30
  4571.7  477.85  4584.6  477.46  4593.1  476.62  4598.7  475.27  4629.2  474.99
  4638.1     474    4644  474.75  4651.5   474.1  4660.6  474.11  4666.1  476.35
  4673.8  476.64  4683.1  475.32    4696  471.68    4728  470.43  4795.5   470.2
  4902.3  471.01    4984  471.45    4991  469.87  4991.5  469.07  4996.5  469.07
    4997  469.87    5014  472.09  5040.3  473.58    5104  473.83  5144.1  473.21
  5174.9  471.58  5226.2  472.54  5236.5  470.99  5246.8  470.51  5343.4  472.26
#Mann= 6 ,-1 , 0
  4571.7     .08       0    4644     .05       0  4902.3      .1       0
    4991     .07       0    4997      .1       0  5040.3     .05       0
Bank Sta=4991,4997
XS Rating Curve= 0 ,0
Exp/Cntr=0.3,0.1

Type RM Length L Ch R = 1 ,1628    ,566,566,566
BEGIN DESCRIPTION:
Mapping XS 13b4600e
END DESCRIPTION:
XS GIS Cut Line= 5
       2056492.1     13490008.69      2056403.12     13490201.83
      2056337.33     13490384.99       2056315.8     13490605.13
      2056359.73     13490768.26
#Sta/Elev= 30
  4565.7  477.01  4606.8  477.57  4637.8  478.09  4649.7  475.18  4666.3  473.04
  4689.2  471.78  4694.7  472.88  4735.2  471.68  4763.6   471.6  4782.7  470.87
  4787.3  470.28  4792.6  470.76  4812.7  470.03  4934.6  470.43    5018  470.98
  5053.4  471.02  5083.5   470.4  5123.7  471.33  5143.8  470.96  5215.1  471.51
  5225.1  471.95  5235.4  470.45  5246.9  469.69  5247.4  468.89  5252.4  468.89
  5252.9  469.69  5256.2  470.16  5266.5  470.04  5284.6  470.93  5363.1   471.8
#Mann= 6 ,-1 , 0
  4565.7     .08       0  4606.8     .05       0  4934.6      .1       0
    5018     .05       0  5246.9     .07       0  5252.9     .05       0
Bank Sta=5246.9,5252.9
XS Rating Curve= 0 ,0
Exp/Cntr=0.3,0.1

Type RM Length L Ch R = 1 ,1062    ,43,43,43
BEGIN DESCRIPTION:
Mapping XS 9ccba463
END DESCRIPTION:
XS GIS Cut Line= 4
      2056058.06     13489973.98      2055845.75     13490217.41
      2055798.88      13490375.4      2055897.26     13490680.74
#Sta/Elev= 30
  4621.4  476.24  4666.6  476.84  4688.5  474.63  4709.6  473.85  4801.5  471.49
  4815.7  469.84  4850.8  469.77  4907.8     467    4922  471.54  4936.3  471.98
  4944.4  471.72  4961.1  468.09    4994  465.81  5053.6  465.56  5054.1  464.76
  5059.1  464.76  5059.6  465.56  5071.2  466.38  5098.4  465.94  5107.2   467.4
  5113.5  466.58  5140.3  470.02  5145.5  469.61  5155.7  470.82  5161.3  470.78
  5177.6  467.73  5214.9  467.83  5266.4  466.42  5273.8  467.68    5430  469.18
#Mann= 5 ,-1 , 0
  4621.4     .05       0  4709.6      .1       0  5053.6     .07       0
  5059.6      .1       0  5155.7     .05       0
Bank Sta=5053.6,5059.6
XS Rating Curve= 0 ,0
Exp/Cntr=0.3,0.1

Type RM Length L Ch R = 1 ,1019    ,45,45,45
BEGIN DESCRIPTION:
Mapping XS 40b48229
END DESCRIPTION:
XS GIS Cut Line= 5
      2055994.18     13489949.56      2055811.37     13490216.45
      2055781.86     13490270.27      2055755.82     13490390.06
      2055818.36     13490700.26
#Sta/Elev= 30
  4631.4  475.89  4724.3  473.52  4793.8  471.57  4829.7   469.4  4880.4  468.46
  4904.5   465.9    4905   465.1    4910   465.1  4910.5   465.9  4922.4  467.07
  4937.3  470.97    4951  471.76  5020.7  472.23  5025.6  471.52  5031.3  472.35
  5051.8  472.75  5069.6     472  5074.8  472.71  5118.8  472.27  5123.9  470.03
  5138.8  467.65    5144  467.65  5159.6  466.85  5194.9  467.26  5205.1  467.15
  5210.4  466.24  5245.9  466.05  5256.1  467.31  5362.8  467.59  5455.3  469.23
#Mann= 5 ,-1 , 0
  4631.4     .05       0  4724.3      .1       0  4904.5     .07       0
  4910.5      .1       0    5144     .05       0
Bank Sta=4904.5,4910.5
XS Rating Curve= 0 ,0
Exp/Cntr=0.3,0.1

Type RM Length L Ch R = 1 ,974     ,212,212,212
BEGIN DESCRIPTION:
Mapping XS 6a4f3efc
END DESCRIPTION:
XS GIS Cut Line= 4
      2055962.58     13489880.65      2055808.43     13490121.06
      2055662.59     13490406.65       2055710.6     13490701.61
#Sta/Elev= 30
    4579  477.01  4711.2  473.84  4717.1   474.6  4733.7  474.56  4747.5  472.48
  4869.6  468.35  4906.7  466.66  4923.3  465.15  4936.4  465.14  4945.5  466.16
  4951.2  465.87  4958.8  466.53  4973.4  465.44    4987  463.26  4987.5  462.46
  4992.5  462.46    4993  463.26  5003.7  463.49  5012.2  464.58  5017.8  463.77
  5034.4  465.81    5040  465.11  5062.3  464.85  5136.9  465.66  5185.3   466.6
  5203.8  465.41  5224.1  465.79  5230.3  466.51  5358.4  467.09  5484.1  468.61
#Mann= 5 ,-1 , 0
    4579     .05       0  4733.7      .1       0    4987     .07       0
    4993      .1       0  5136.9     .05       0
Bank Sta=4987,4993
XS Rating Curve= 0 ,0
Exp/Cntr=0.3,0.1

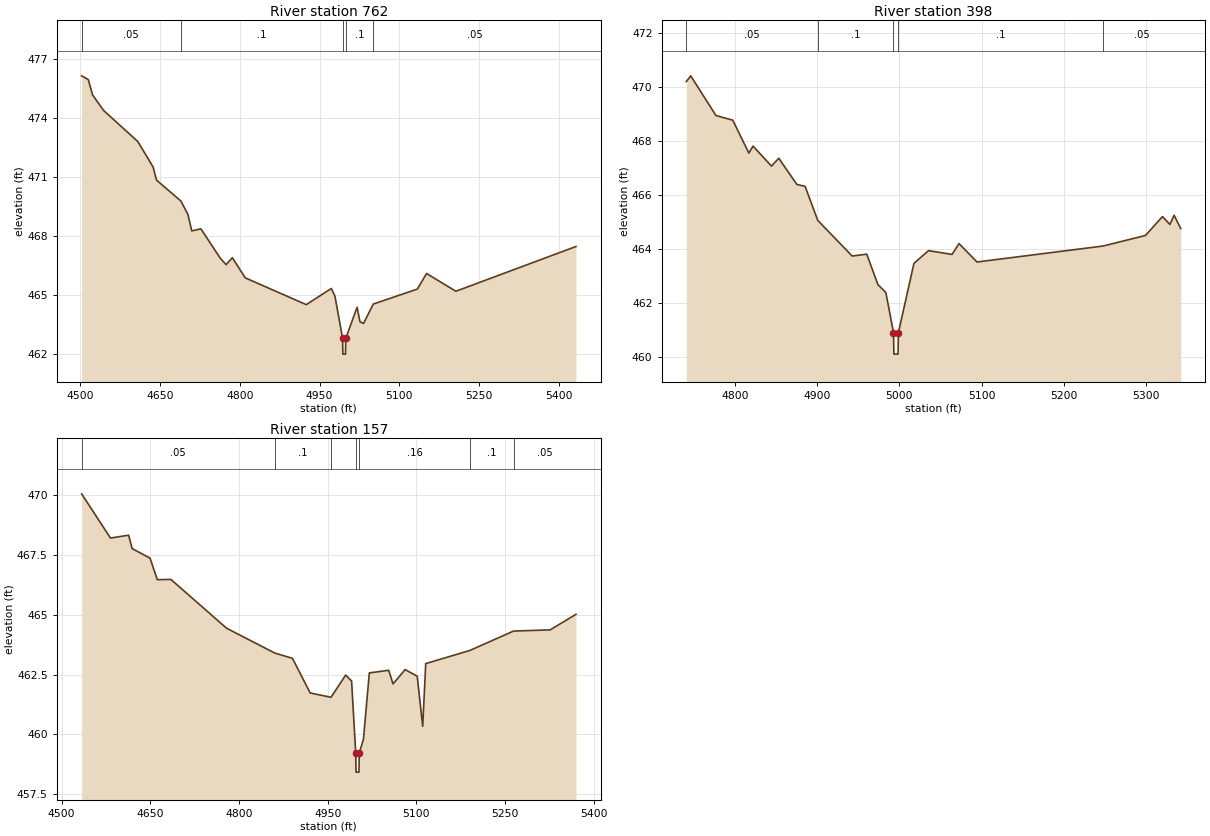
Type RM Length L Ch R = 1 ,762     ,364,364,364
BEGIN DESCRIPTION:
Mapping XS 126498ff
END DESCRIPTION:
XS GIS Cut Line= 4
      2055793.35     13489835.05      2055660.94     13489939.24
      2055467.79     13490423.18      2055517.71     13490657.58
#Sta/Elev= 30
  4502.8  476.13  4515.3  475.94  4523.4  475.16  4544.2  474.37  4608.3   472.8
  4637.2   471.5  4643.6  470.84  4689.3  469.78  4702.6   469.1  4709.8  468.26
  4726.9  468.37  4763.6  466.87  4774.4  466.55  4786.1   466.9  4810.4  465.88
  4925.1  464.52  4972.1  465.34    4979  464.95  4993.3  462.81  4993.8  462.01
  4998.8  462.01  4999.3  462.81  5020.6  464.39    5026  463.65  5032.8  463.57
    5051  464.55  5133.8  465.31  5151.2   466.1  5206.2   465.2    5432  467.47
#Mann= 5 ,-1 , 0
  4502.8     .05       0  4689.3      .1       0  4993.3     .07       0
  4999.3      .1       0    5051     .05       0
Bank Sta=4993.3,4999.3
XS Rating Curve= 0 ,0
Exp/Cntr=0.3,0.1

Type RM Length L Ch R = 1 ,398     ,241,241,241
BEGIN DESCRIPTION:
Mapping XS 7bbf5232
END DESCRIPTION:
XS GIS Cut Line= 4
      2055550.22     13489793.85      2055465.62      13489811.2
      2055296.35     13490188.81      2055322.39     13490286.43
#Sta/Elev= 30
    4741  470.21  4746.3  470.42    4777  468.95  4797.4  468.78    4817  467.56
  4822.1  467.82  4844.5  467.08  4853.4  467.37  4875.4   466.4  4885.4  466.33
  4900.8  465.07  4942.7  463.75  4960.4  463.82    4974  462.69  4983.6   462.4
  4992.9  460.92  4993.4  460.12  4998.4  460.12  4998.9  460.92  5017.8  463.48
  5035.5  463.95  5064.1  463.81  5072.6  464.21  5094.5  463.53  5247.6  464.12
  5299.3  464.51    5320  465.21  5329.1  464.92  5334.2  465.26  5342.2  464.77
#Mann= 5 ,-1 , 0
    4741     .05       0  4900.8      .1       0  4992.9     .07       0
  4998.9      .1       0  5247.6     .05       0
Bank Sta=4992.9,4998.9
XS Rating Curve= 0 ,0
Exp/Cntr=0.3,0.1

Type RM Length L Ch R = 1 ,157     ,0,0,0
BEGIN DESCRIPTION:
UNT 104 in Lagunillas Cr Wtrshd 1.0
END DESCRIPTION:
XS GIS Cut Line= 4
      2055374.45     13489496.58      2055205.13     13489770.37
       2055207.3     13489967.85      2055272.48     13490277.75
#Sta/Elev= 30
  4533.9  470.06  4582.7  468.21  4613.4  468.33  4619.3  467.77  4649.6  467.37
  4661.9  466.47  4684.9  466.48    4779  464.44  4860.6   463.4  4890.5  463.18
  4920.5  461.73  4955.7  461.55  4980.5  462.48  4990.5  462.23  4997.5  459.22
    4998  458.42    5003  458.42  5003.5  459.22  5010.5  459.79  5020.5  462.57
  5053.3  462.68  5060.6  462.11  5081.1  462.71  5101.5  462.43  5110.8  460.34
  5115.9  462.96  5190.7  463.51  5264.4  464.32  5326.3  464.37    5370  465.02
#Mann= 7 ,-1 , 0
  4533.9     .05       0  4860.6      .1       0  4955.7     .16       0
  4997.5     .07       0  5003.5     .16       0  5190.7      .1       0
  5264.4     .05       0
Bank Sta=4997.5,5003.5
XS Rating Curve= 0 ,0
Exp/Cntr=0.3,0.1
LCMann Table=0

Chan Stop Cuts=-1
Use User Specified Reach Order=0
Composite Channel Slope=5