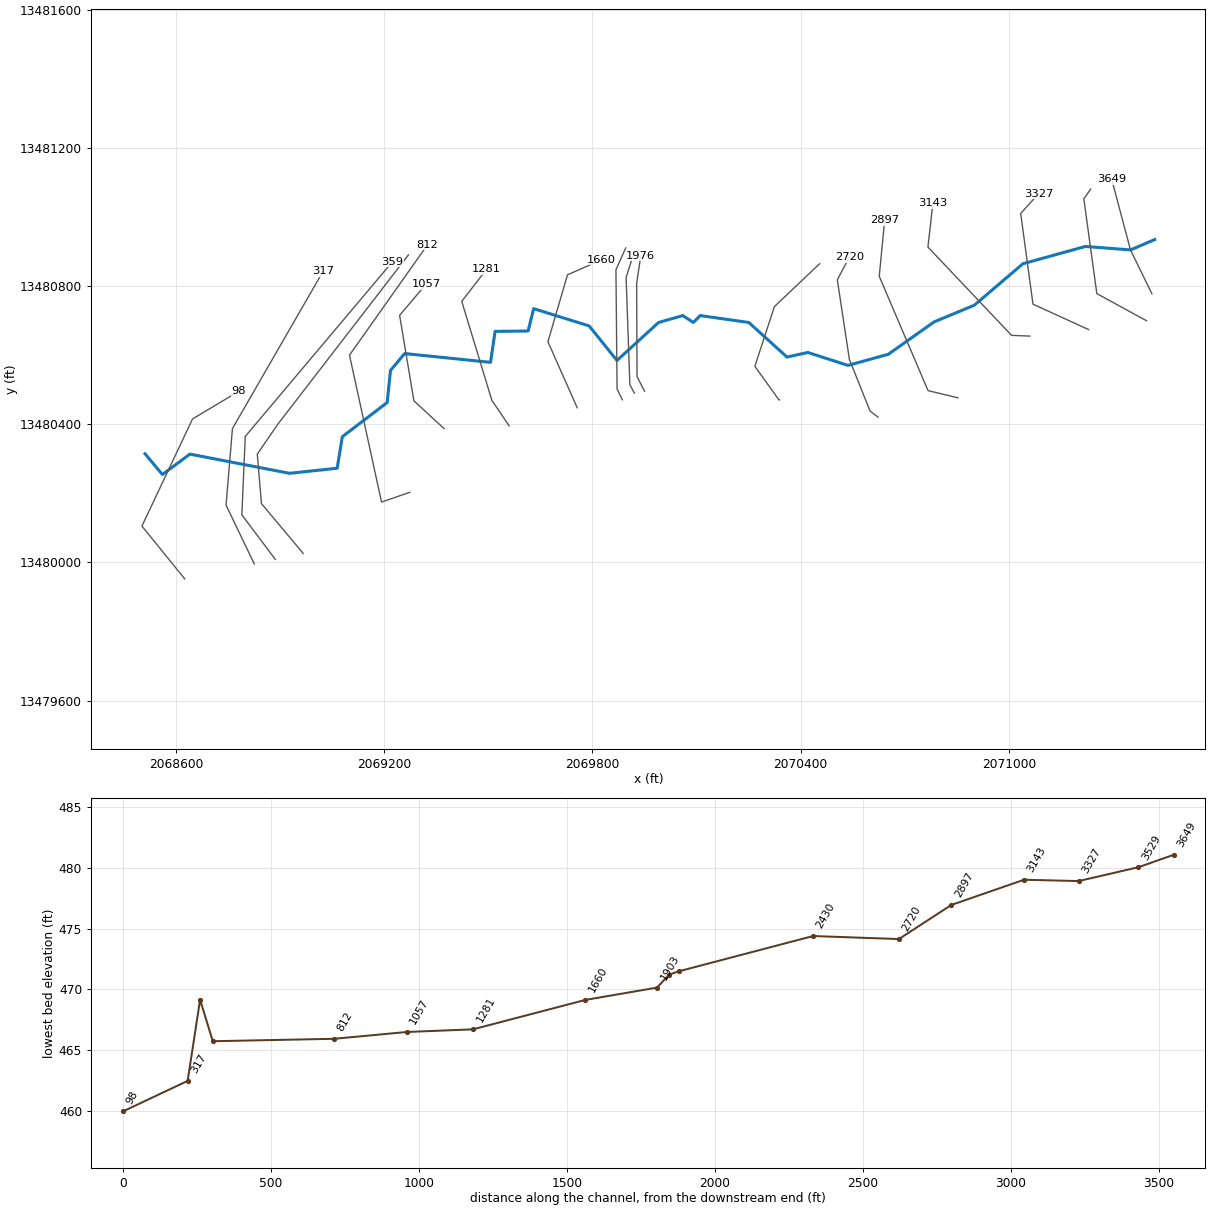
--- UNT 108 in Lagunillas Cr Wtrshd.prj (project) ---

Proj Title=UNT 108 in Lagunillas Cr Wtrshd Base Level Engineering
Current Plan=p01
Default Exp/Contr=0.3,0.1
English Units
Geom File=g01
Flow File=f01
Plan File=p01
BEGIN DESCRIPTION:
UNT 108 in Lagunillas Cr Wtrshd
END DESCRIPTION:

--- UNT 108 in Lagunillas Cr Wtrshd.p01 (plan) ---

Plan Title=Multiple Run
Short Identifier=Multiple
Geom File=g01
Flow File=f01
Subcritical Flow
K Sum by GR= 0
Std Step Tol= 0.01
Critical Tol= 0.01
Num of Std Step Trials= 20
Max Error Tol= 0.3
Flow Tol Ratio= 0.001
Split Flow NTrial= 30
Split Flow Tol= 0.02
Split Flow Ratio= 0.02
Log Output Level= 0
Friction Slope Method= 1
Unsteady Friction Slope Method= 2
Unsteady Bridges Friction Slope Method= 1
Parabolic Critical Depth
Global Vel Dist=  1 , 1 , 1
Global Log Level= 0
CheckData=True
Encroach Param= -1, 0, 0, 0
BEGIN DESCRIPTION:
Multiple Run
END DESCRIPTION:

--- UNT 108 in Lagunillas Cr Wtrshd.f01 (steady flow) ---

Flow Title=Multiple
Number of Profiles=7
Profile Names=10-year,25-year,50-year,1pct_min,100-year,1pct_plu,500-year
River Rch & RM= UNT 108 in Lagun,Reach-1,3649
     165     223     269     163     324     647     477
Boundary for River Rch & Prof#=UNT 108 in Lagun,Reach-1,1
Up Type=0
Dn Type=3
Dn Slope=0.005
Boundary for River Rch & Prof#=UNT 108 in Lagun,Reach-1,2
Up Type=0
Dn Type=3
Dn Slope=0.005
Boundary for River Rch & Prof#=UNT 108 in Lagun,Reach-1,3
Up Type=0
Dn Type=3
Dn Slope=0.005
Boundary for River Rch & Prof#=UNT 108 in Lagun,Reach-1,4
Up Type=0
Dn Type=3
Dn Slope=0.005
Boundary for River Rch & Prof#=UNT 108 in Lagun,Reach-1,5
Up Type=0
Dn Type=3
Dn Slope=0.005
Boundary for River Rch & Prof#=UNT 108 in Lagun,Reach-1,6
Up Type=0
Dn Type=3
Dn Slope=0.005
Boundary for River Rch & Prof#=UNT 108 in Lagun,Reach-1,7
Up Type=0
Dn Type=3
Dn Slope=0.005

--- UNT 108 in Lagunillas Cr Wtrshd.g01 (geometry) ---

Geom Title=Existing Conditions

River Reach=UNT 108 in Lagun,Reach-1
Reach XY= 30
      2071420.80     13480934.54      2071350.80     13480904.54
      2071220.80     13480914.54      2071040.80     13480864.54
      2070900.80     13480744.54      2070784.84     13480696.24
      2070652.89     13480602.49      2070536.57     13480570.37
      2070421.12     13480607.70      2070360.80     13480594.54
      2070250.80     13480694.54      2070110.80     13480714.54
      2070090.80     13480694.54      2070060.80     13480714.54
      2069990.80     13480694.54      2069870.80     13480584.54
      2069790.80     13480684.54      2069630.80     13480734.54
      2069614.87     13480669.85      2069519.56     13480668.81
      2069506.54     13480579.23      2069258.97     13480604.54
      2069218.17     13480555.79      2069208.62     13480462.91
      2069079.28     13480363.95      2069064.52     13480272.80
      2068927.37     13480258.05      2068640.04     13480313.60
      2068560.80     13480254.54      2068510.80     13480314.54

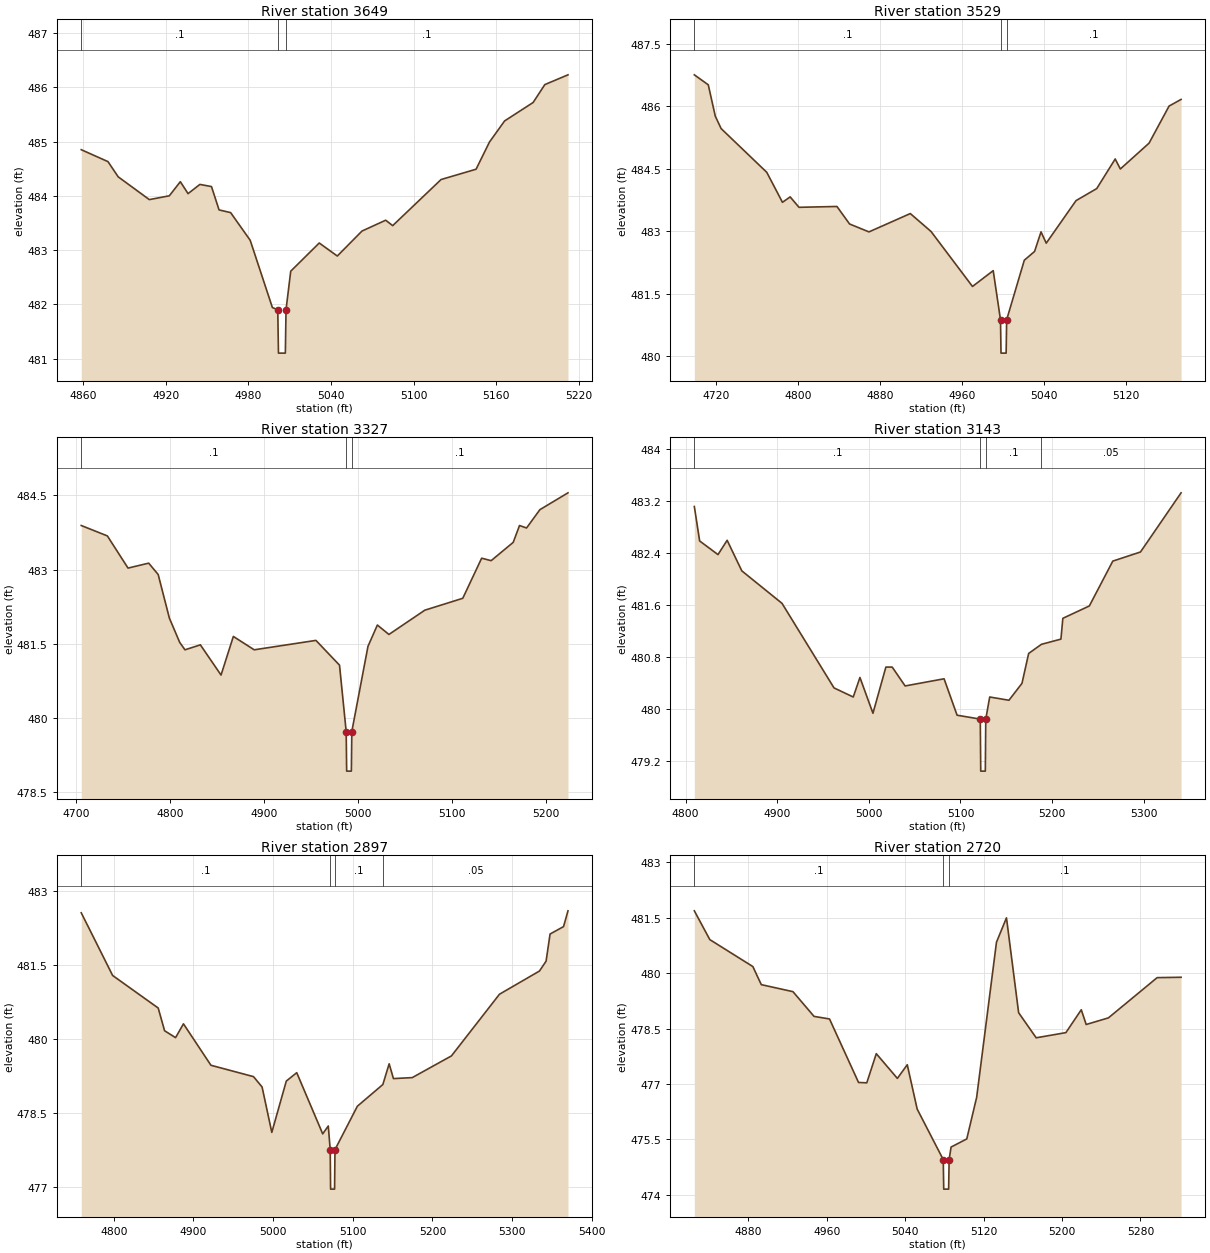
Type RM Length L Ch R = 1,3649,120,120,120
BEGIN DESCRIPTION:
UNT 108 in Lagunillas Cr Wtrshd 7.0
END DESCRIPTION:
XS GIS Cut Line= 3
      2071412.53     13480777.55      2071350.80     13480904.54
      2071296.55     13481109.48
#Sta/Elev= 30
  4858.8  484.85  4878.2  484.63  4885.6  484.35  4908.2  483.93  4922.7  484.00
  4930.7  484.26  4936.3  484.04  4944.9  484.21  4953.3  484.17  4958.8  483.74
  4967.2  483.69  4981.4  483.18  4997.5  481.94  5001.4  481.90  5001.9  481.10
  5006.9  481.10  5007.4  481.90  5010.8  482.61  5031.5  483.13  5044.6  482.89
  5062.5  483.35  5079.7  483.55  5084.8  483.45  5119.9  484.30  5145.3  484.49
  5155.0  484.99  5166.0  485.38  5186.7  485.72  5195.2  486.05  5212.0  486.23
#Mann=3,-1,0
  4858.8     0.1       0  5001.4    0.07       0  5007.4     0.1       0
Bank Sta=5001.4,5007.4
Exp/Cntr=0.3,0.1

Type RM Length L Ch R = 1,3529,202,202,202
BEGIN DESCRIPTION:
Mapping XS 8956c3d2
END DESCRIPTION:
XS GIS Cut Line= 4
      2071396.91     13480699.61      2071253.84     13480778.09
      2071216.34     13481052.39      2071236.18     13481080.45
#Sta/Elev= 30
  4699.1  486.75  4712.7  486.51  4719.5  485.76  4725.2  485.46  4769.7  484.41
  4785.0  483.69  4792.5  483.82  4801.1  483.57  4838.1  483.59  4850.4  483.17
  4869.3  482.98  4909.6  483.42  4929.8  482.99  4970.2  481.67  4990.4  482.05
  4997.5  480.87  4998.0  480.07  5003.0  480.07  5003.5  480.87  5020.7  482.30
  5030.7  482.51  5037.0  482.98  5042.1  482.71  5071.1  483.73  5091.3  484.02
  5109.3  484.73  5114.3  484.49  5142.3  485.11  5161.8  486.00  5173.5  486.16
#Mann=3,-1,0
  4699.1     0.1       0  4997.5    0.07       0  5003.5     0.1       0
Bank Sta=4997.5,5003.5
Exp/Cntr=0.3,0.1

Type RM Length L Ch R = 1,3327,184,184,184
BEGIN DESCRIPTION:
Mapping XS a9a39187
END DESCRIPTION:
XS GIS Cut Line= 4
      2071230.26     13480673.91      2071069.81     13480747.53
      2071034.39     13481010.03      2071085.77     13481066.96
#Sta/Elev= 30
  4705.4  483.89  4733.2  483.68  4755.2  483.03  4777.2  483.13  4787.3  482.90
  4799.2  482.02  4810.2  481.53  4815.8  481.38  4832.2  481.48  4854.2  480.87
  4867.3  481.65  4889.5  481.38  4955.2  481.57  4980.3  481.07  4987.4  479.73
  4987.9  478.93  4992.9  478.93  4993.4  479.73  5010.6  481.45  5020.6  481.88
  5032.9  481.69  5071.1  482.18  5111.5  482.42  5131.6  483.23  5141.7  483.18
  5165.2  483.55  5171.9  483.89  5179.4  483.84  5193.6  484.21  5223.5  484.55
#Mann=3,-1,0
  4705.4     0.1       0  4987.4    0.07       0  4993.4     0.1       0
Bank Sta=4987.4,4993.4
Exp/Cntr=0.3,0.1

Type RM Length L Ch R = 1,3143,246,246,246
BEGIN DESCRIPTION:
Mapping XS a55b2f48
END DESCRIPTION:
XS GIS Cut Line= 4
      2071060.78     13480655.17      2071008.00     13480657.25
      2070767.03     13480912.81      2070781.27     13481039.04
#Sta/Elev= 30
  4809.6  483.11  4815.4  482.58  4835.4  482.37  4845.4  482.59  4861.4  482.12
  4905.3  481.62  4962.0  480.32  4983.0  480.18  4990.3  480.48  5004.5  479.93
  5018.6  480.64  5025.5  480.64  5039.6  480.35  5082.1  480.46  5096.3  479.90
  5121.6  479.84  5122.1  479.04  5127.1  479.04  5127.6  479.84  5131.9  480.18
  5152.9  480.13  5167.1  480.39  5174.4  480.85  5188.3  480.99  5209.6  481.07
  5211.7  481.39  5240.6  481.58  5266.2  482.27  5296.4  482.41  5340.7  483.32
#Mann=4,-1,0
  4809.6     0.1       0  5121.6    0.07       0  5127.6     0.1       0
  5188.3    0.05       0
Bank Sta=5121.6,5127.6
Exp/Cntr=0.3,0.1

Type RM Length L Ch R = 1,2897,177,177,177
BEGIN DESCRIPTION:
Mapping XS 0fc695ed
END DESCRIPTION:
XS GIS Cut Line= 4
      2070853.26     13480476.57      2070767.37     13480497.39
      2070626.75     13480828.12      2070642.31     13480990.62
#Sta/Elev= 30
  4759.1  482.56  4798.5  481.29  4855.7  480.63  4863.7  480.17  4877.5  480.03
  4887.4  480.31  4921.9  479.47  4975.3  479.24  4986.1  479.03  4998.3  478.11
  5016.5  479.15  5029.6  479.32  5062.2  478.08  5069.2  478.24  5071.6  477.76
  5072.1  476.96  5077.1  476.96  5077.6  477.76  5105.7  478.64  5137.7  479.08
  5145.6  479.50  5151.0  479.20  5174.6  479.22  5223.8  479.66  5284.1  480.91
  5334.3  481.38  5342.6  481.58  5347.6  482.13  5364.5  482.28  5370.1  482.60
#Mann=4,-1,0
  4759.1     0.1       0  5071.6    0.07       0  5077.6     0.1       0
  5137.7    0.05       0
Bank Sta=5071.6,5077.6
Exp/Cntr=0.3,0.1

Type RM Length L Ch R = 1,2720,290,290,290
BEGIN DESCRIPTION:
Mapping XS 32247fa4
END DESCRIPTION:
XS GIS Cut Line= 5
      2070623.08     13480420.80      2070600.32     13480438.14
      2070540.64     13480587.88      2070505.92     13480817.92
      2070540.32     13480883.50
#Sta/Elev= 30
  4825.0  481.69  4840.8  480.91  4884.7  480.18  4893.3  479.69  4925.6  479.50
  4947.1  478.83  4962.9  478.76  4992.5  477.04  5000.9  477.03  5010.6  477.82
  5032.1  477.15  5042.2  477.52  5052.3  476.32  5078.9  474.95  5079.4  474.15
  5084.4  474.15  5084.9  474.95  5086.9  475.29  5102.9  475.51  5113.0  476.64
  5133.2  480.84  5143.4  481.50  5155.8  478.93  5173.7  478.25  5204.0  478.39
  5219.7  479.01  5224.7  478.61  5247.4  478.79  5297.1  479.88  5321.5  479.89
#Mann=3,-1,0
  4825.0     0.1       0  5078.9    0.07       0  5084.9     0.1       0
Bank Sta=5078.9,5084.9
Exp/Cntr=0.3,0.1

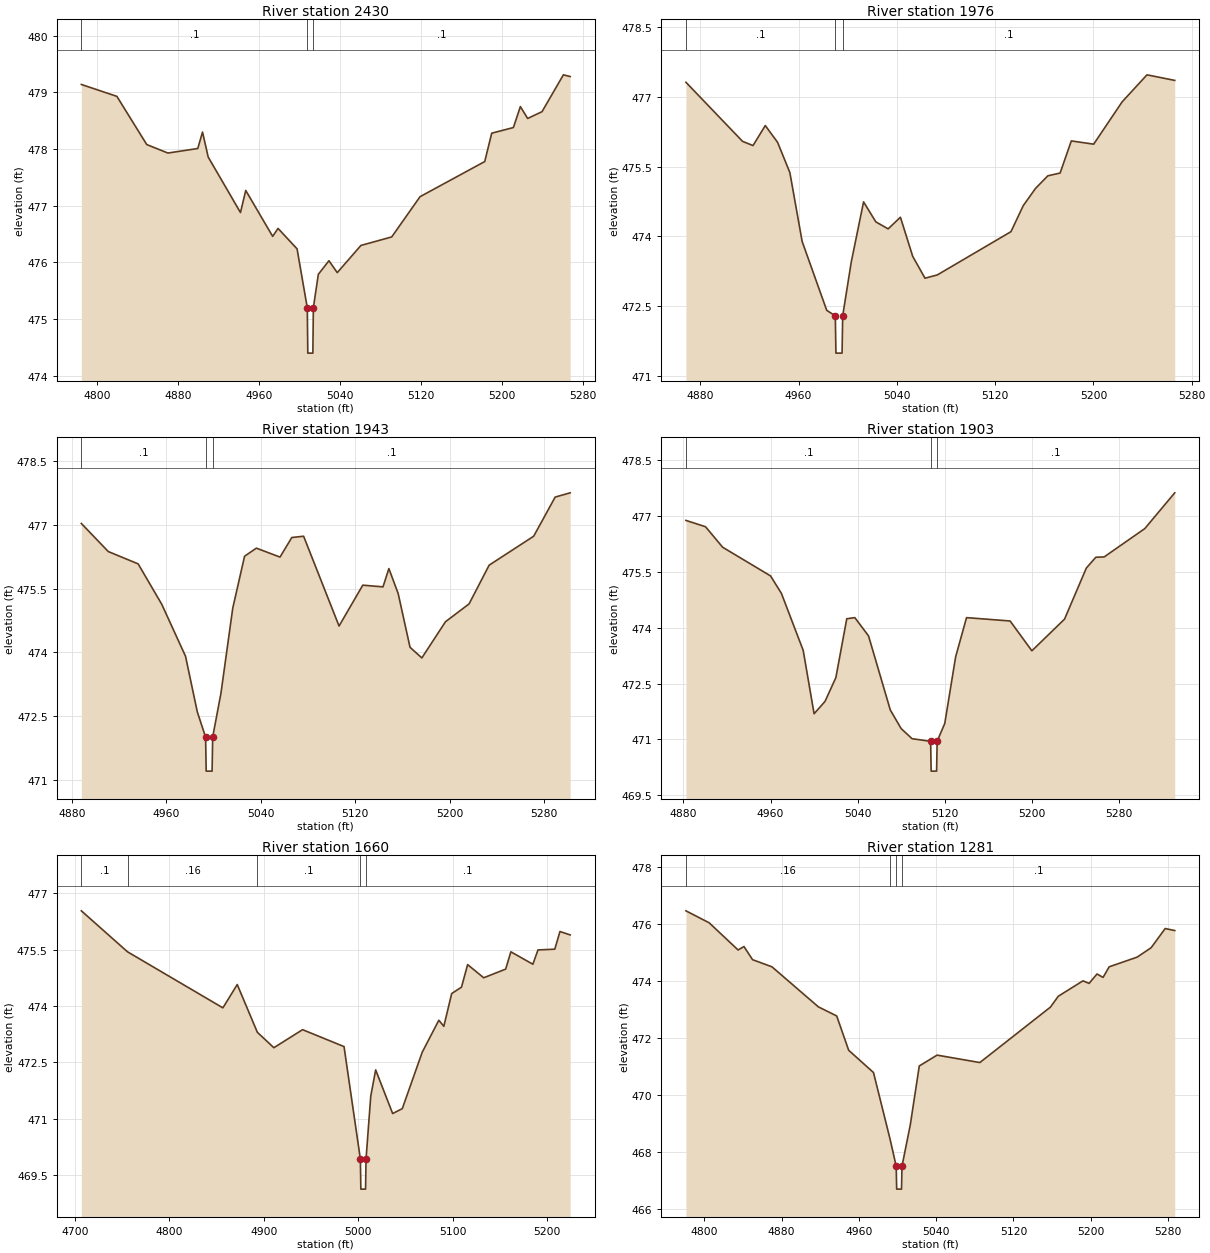
Type RM Length L Ch R = 1,2430,454,454,454
BEGIN DESCRIPTION:
Mapping XS 0f28b7da
END DESCRIPTION:
XS GIS Cut Line= 5
      2070339.43     13480470.48      2070337.68     13480470.48
      2070268.24     13480567.71      2070324.66     13480740.45
      2070454.94     13480864.59
#Sta/Elev= 30
  4784.1  479.14  4819.2  478.93  4848.7  478.08  4869.6  477.93  4899.1  478.01
  4903.8  478.30  4909.4  477.86  4941.3  476.88  4946.5  477.27  4973.1  476.46
  4978.4  476.60  4997.2  476.24  5007.3  475.20  5007.8  474.40  5012.8  474.40
  5013.3  475.20  5018.2  475.79  5028.7  476.03  5036.9  475.82  5060.3  476.30
  5090.7  476.45  5118.7  477.16  5182.6  477.78  5189.5  478.28  5210.9  478.38
  5217.8  478.75  5225.0  478.54  5239.2  478.66  5260.3  479.31  5267.0  479.28
#Mann=3,-1,0
  4784.1     0.1       0  5007.3    0.07       0  5013.3     0.1       0
Bank Sta=5007.3,5013.3
Exp/Cntr=0.3,0.1

Type RM Length L Ch R = 1,1976,33,33,33
BEGIN DESCRIPTION:
Mapping XS 9b9d975b
END DESCRIPTION:
XS GIS Cut Line= 4
      2069950.39     13480495.61      2069928.66     13480537.97
      2069927.58     13480808.15      2069939.52     13480887.37
#Sta/Elev= 30
  4868.3  477.31  4914.4  476.04  4922.9  475.95  4932.9  476.38  4942.9  476.02
  4952.9  475.37  4962.9  473.89  4982.9  472.41  4989.9  472.29  4990.4  471.49
  4995.4  471.49  4995.9  472.29  5002.9  473.45  5012.9  474.74  5022.9  474.31
  5032.9  474.16  5042.9  474.41  5052.9  473.57  5062.9  473.10  5072.9  473.17
  5132.9  474.10  5142.9  474.66  5152.9  475.03  5162.9  475.30  5172.9  475.36
  5182.0  476.05  5200.2  475.98  5223.4  476.89  5243.6  477.47  5266.2  477.35
#Mann=3,-1,0
  4868.3     0.1       0  4989.9    0.07       0  4995.9     0.1       0
Bank Sta=4989.9,4995.9
Exp/Cntr=0.3,0.1

Type RM Length L Ch R = 1,1943,40,40,40
BEGIN DESCRIPTION:
Mapping XS 436b3cd6
END DESCRIPTION:
XS GIS Cut Line= 4
      2069921.08     13480490.20      2069908.05     13480514.10
      2069897.20     13480824.43      2069919.98     13480897.10
#Sta/Elev= 30
  4888.0  477.03  4910.8  476.37  4936.1  476.08  4956.1  475.13  4976.2  473.91
  4986.2  472.60  4993.2  472.01  4993.7  471.21  4998.7  471.21  4999.2  472.01
  5006.2  473.04  5016.2  475.04  5026.2  476.26  5036.2  476.45  5056.2  476.24
  5066.2  476.70  5076.2  476.73  5106.2  474.62  5126.3  475.58  5143.4  475.54
  5148.4  475.97  5156.3  475.38  5166.3  474.12  5176.3  473.87  5196.3  474.72
  5216.3  475.14  5233.3  476.05  5271.0  476.73  5289.2  477.65  5301.9  477.75
#Mann=3,-1,0
  4888.0     0.1       0  4993.2    0.07       0  4999.2     0.1       0
Bank Sta=4993.2,4999.2
Exp/Cntr=0.3,0.1

Type RM Length L Ch R = 1,1903,243,243,243
BEGIN DESCRIPTION:
Mapping XS 531b572d
END DESCRIPTION:
XS GIS Cut Line= 4
      2069886.33     13480470.74      2069871.16     13480502.16
      2069867.90     13480847.21      2069896.10     13480910.12
#Sta/Elev= 30
  4882.3  476.88  4900.3  476.71  4916.0  476.16  4960.0  475.39  4970.0  474.92
  4990.0  473.39  5000.0  471.69  5010.0  472.02  5020.0  472.66  5030.0  474.24
  5037.4  474.27  5050.0  473.78  5070.0  471.79  5080.0  471.29  5090.0  471.02
  5107.0  470.95  5107.5  470.15  5112.5  470.15  5113.0  470.95  5120.0  471.43
  5130.0  473.22  5140.0  474.27  5180.0  474.18  5200.0  473.38  5230.0  474.23
  5250.0  475.60  5258.7  475.89  5266.4  475.90  5303.7  476.66  5331.2  477.62
#Mann=3,-1,0
  4882.3     0.1       0  5107.0    0.07       0  5113.0     0.1       0
Bank Sta=5107,5113
Exp/Cntr=0.3,0.1

Type RM Length L Ch R = 1,1660,379,379,379
BEGIN DESCRIPTION:
Mapping XS 6167850b
END DESCRIPTION:
XS GIS Cut Line= 4
      2069756.15     13480447.88      2069671.89     13480638.89
      2069728.31     13480832.46      2069826.43     13480875.88
#Sta/Elev= 30
  4706.9  476.53  4755.8  475.44  4856.8  473.95  4872.0  474.57  4893.3  473.30
  4910.8  472.89  4941.2  473.37  4985.1  472.92  5002.4  469.93  5002.9  469.13
  5007.9  469.13  5008.4  469.93  5013.4  471.60  5018.6  472.30  5036.6  471.14
  5046.8  471.27  5067.9  472.77  5085.5  473.62  5090.8  473.46  5099.1  474.33
  5109.5  474.50  5116.0  475.10  5133.0  474.75  5156.3  474.98  5161.8  475.44
  5185.1  475.11  5190.5  475.49  5208.3  475.51  5213.8  475.98  5224.6  475.89
#Mann=5,-1,0
  4706.9     0.1       0  4755.8    0.16       0  4893.3     0.1       0
  5002.4    0.07       0  5008.4     0.1       0
Bank Sta=5002.4,5008.4
Exp/Cntr=0.3,0.1

Type RM Length L Ch R = 1,1281,224,224,224
BEGIN DESCRIPTION:
Mapping XS f1107707
END DESCRIPTION:
XS GIS Cut Line= 4
      2069560.30     13480395.26      2069510.37     13480469.07
      2069423.56     13480755.53      2069495.20     13480848.87
#Sta/Elev= 30
  4780.9  476.45  4805.0  476.03  4834.9  475.08  4841.0  475.20  4849.9  474.74
  4870.0  474.49  4918.0  473.09  4937.0  472.77  4949.4  471.57  4975.1  470.79
  4992.4  468.44  4998.6  467.51  4999.1  466.71  5004.1  466.71  5004.6  467.51
  5013.2  468.96  5022.5  471.02  5040.9  471.40  5085.2  471.14  5158.3  473.08
  5166.4  473.46  5192.0  474.00  5198.3  473.91  5206.5  474.24  5212.8  474.12
  5219.1  474.49  5248.1  474.83  5262.6  475.16  5277.1  475.83  5287.0  475.76
#Mann=4,-1,0
  4780.9    0.16       0  4992.4     0.1       0  4998.6    0.07       0
  5004.6     0.1       0
Bank Sta=4998.6,5004.6
Exp/Cntr=0.3,0.1

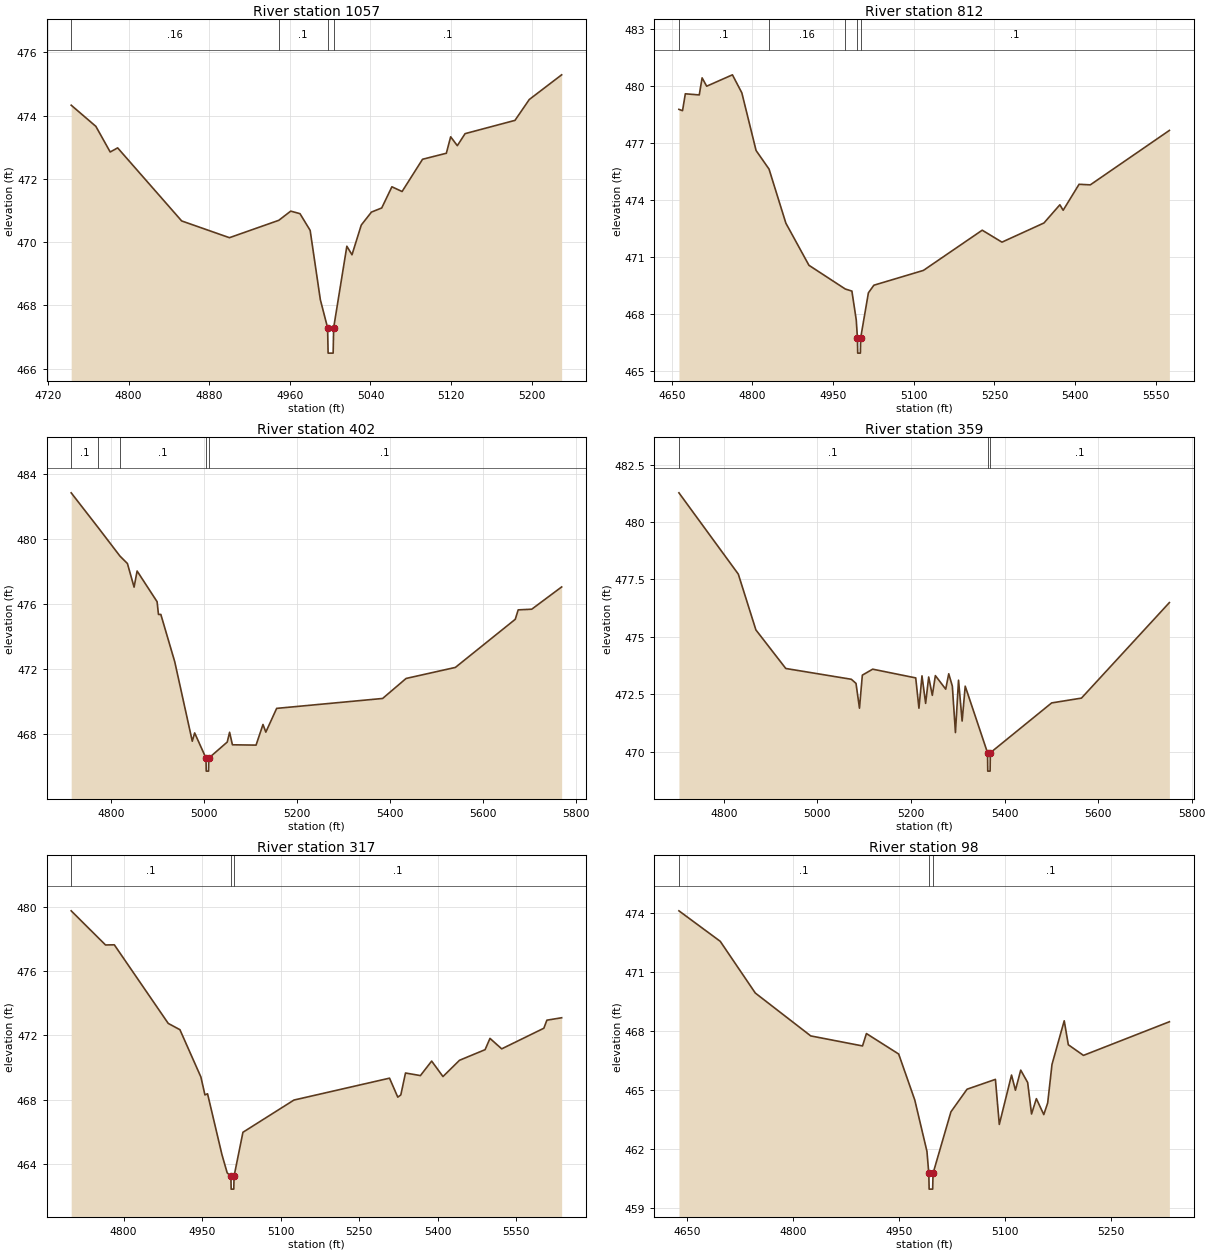
Type RM Length L Ch R = 1,1057,245,245,245
BEGIN DESCRIPTION:
Mapping XS 3169ef44
END DESCRIPTION:
XS GIS Cut Line= 4
      2069372.51     13480387.48      2069285.69     13480467.79
      2069244.45     13480715.19      2069320.22     13480805.03
#Sta/Elev= 30
  4743.1  474.33  4767.6  473.66  4781.8  472.85  4789.2  472.98  4852.7  470.67
  4900.1  470.14  4949.1  470.69  4960.9  470.98  4970.1  470.90  4980.2  470.37
  4990.3  468.18  4997.5  467.29  4998.0  466.49  5003.0  466.49  5003.5  467.29
  5016.6  469.87  5021.7  469.60  5030.9  470.54  5041.0  470.95  5051.2  471.08
  5061.3  471.75  5071.4  471.60  5091.7  472.62  5115.3  472.81  5119.6  473.33
  5126.2  473.05  5133.9  473.43  5183.4  473.85  5197.6  474.51  5229.7  475.29
#Mann=4,-1,0
  4743.1    0.16       0  4949.1     0.1       0  4997.5    0.07       0
  5003.5     0.1       0
Bank Sta=4997.5,5003.5
Exp/Cntr=0.3,0.1

Type RM Length L Ch R = 1,812,410,410,410
BEGIN DESCRIPTION:
Mapping XS 40a4b8c6
END DESCRIPTION:
XS GIS Cut Line= 4
      2069273.78     13480203.05      2069192.37     13480174.82
      2069100.00     13480600.00      2069325.09     13480919.65
#Sta/Elev= 30
  4663.3  478.78  4670.0  478.71  4675.2  479.60  4701.1  479.54  4706.4  480.44
  4714.9  480.00  4762.8  480.60  4780.3  479.65  4806.8  476.61  4830.9  475.63
  4862.2  472.78  4905.1  470.56  4972.7  469.31  4985.0  469.20  4993.1  467.68
  4995.3  466.73  4995.8  465.93  5000.8  465.93  5001.3  466.73  5015.7  469.11
  5025.9  469.51  5118.0  470.29  5227.4  472.41  5264.1  471.78  5342.2  472.79
  5371.8  473.75  5377.9  473.46  5407.5  474.83  5428.4  474.80  5575.5  477.67
#Mann=5,-1,0
  4663.3     0.1       0  4830.9    0.16       0  4972.7     0.1       0
  4995.3    0.07       0  5001.3     0.1       0
Bank Sta=4995.3,5001.3
Exp/Cntr=0.3,0.1

Type RM Length L Ch R = 1,402,43,43,43
BEGIN DESCRIPTION:
Mapping XS b9a22a7c
END DESCRIPTION:
XS GIS Cut Line= 5
      2068966.65     13480026.20      2068846.23     13480170.48
      2068834.30     13480313.71      2068892.89     13480399.43
      2069269.86     13480890.17
#Sta/Elev= 30
  4714.4  482.85  4773.0  480.69  4819.2  478.96  4835.3  478.50  4849.6  477.05
  4856.1  478.04  4899.1  476.15  4902.0  475.37  4907.1  475.37  4937.0  472.46
  4974.7  467.57  4979.8  468.08  5004.2  466.53  5004.7  465.73  5009.7  465.73
  5010.2  466.53  5049.9  467.52  5054.9  468.12  5061.0  467.35  5111.8  467.33
  5126.7  468.60  5132.8  468.13  5156.1  469.59  5383.9  470.20  5434.3  471.43
  5540.3  472.11  5669.0  475.07  5675.3  475.65  5704.4  475.69  5768.7  477.06
#Mann=5,-1,0
  4714.4     0.1       0  4773.0    0.16       0  4819.2     0.1       0
  5004.2    0.07       0  5010.2     0.1       0
Bank Sta=5004.2,5010.2
Exp/Cntr=0.3,0.1

Type RM Length L Ch R = 1,359,42,42,42
BEGIN DESCRIPTION:
Mapping XS 1c8deed6
END DESCRIPTION:
XS GIS Cut Line= 4
      2068886.38     13480008.81      2068789.81     13480137.93
      2068799.58     13480364.71      2069223.82     13480870.39
#Sta/Elev= 30
  4704.1  481.27  4831.0  477.73  4868.6  475.30  4932.5  473.62  5072.6  473.15
  5082.6  472.97  5090.0  471.89  5096.1  473.33  5118.2  473.59  5210.2  473.21
  5217.1  471.89  5223.6  473.30  5231.4  472.10  5237.9  473.25  5245.7  472.45
  5252.2  473.31  5274.3  472.72  5280.8  473.39  5288.5  472.85  5295.1  470.83
  5301.7  473.11  5309.4  471.33  5316.0  472.85  5363.7  469.95  5364.2  469.15
  5369.2  469.15  5369.7  469.95  5500.7  472.12  5564.5  472.33  5752.4  476.49
#Mann=3,-1,0
  4704.1     0.1       0  5363.7    0.07       0  5369.7     0.1       0
Bank Sta=5363.7,5369.7
Exp/Cntr=0.3,0.1

Type RM Length L Ch R = 1,317,219,219,219
BEGIN DESCRIPTION:
Mapping XS 3b50ee49
END DESCRIPTION:
XS GIS Cut Line= 4
      2068825.61     13479995.80      2068744.24     13480166.14
      2068762.68     13480387.50      2069024.52     13480843.69
#Sta/Elev= 30
  4699.9  479.74  4765.5  477.62  4782.3  477.63  4885.3  472.75  4907.6  472.36
  4947.7  469.42  4955.4  468.31  4960.4  468.38  4987.9  464.60  4997.9  463.47
  5005.0  463.26  5005.5  462.46  5010.5  462.46  5011.0  463.26  5028.0  465.99
  5125.4  467.99  5308.0  469.35  5323.8  468.17  5329.6  468.31  5338.5  469.67
  5367.0  469.51  5388.5  470.41  5410.1  469.45  5441.7  470.46  5490.6  471.12
  5499.9  471.82  5522.3  471.17  5602.8  472.45  5608.6  472.95  5636.8  473.10
#Mann=3,-1,0
  4699.9     0.1       0  5005.0    0.07       0  5011.0     0.1       0
Bank Sta=5005,5011
Exp/Cntr=0.3,0.1

Type RM Length L Ch R = 1,98,0,0,0
BEGIN DESCRIPTION:
UNT 108 in Lagunillas Cr Wtrshd 1.0
END DESCRIPTION:
XS GIS Cut Line= 4
      2068625.13     13479952.56      2068501.83     13480105.38
      2068647.67     13480415.28      2068780.20     13480494.97
#Sta/Elev= 30
  4638.8  474.09  4697.2  472.54  4746.8  469.91  4825.2  467.73  4898.4  467.22
  4903.9  467.85  4949.5  466.81  4972.3  464.47  4989.5  461.86  4992.1  460.74
  4992.6  459.94  4997.6  459.94  4998.1  460.74  5023.4  463.87  5046.2  465.02
  5086.3  465.52  5091.8  463.23  5109.1  465.74  5114.6  464.97  5122.1  465.99
  5131.9  465.36  5137.4  463.76  5144.2  464.54  5154.7  463.73  5160.2  464.32
  5166.3  466.28  5183.6  468.50  5189.4  467.28  5210.8  466.74  5332.3  468.45
#Mann=3,-1,0
  4638.8     0.1       0  4992.1    0.07       0  4998.1     0.1       0
Bank Sta=4992.1,4998.1
Exp/Cntr=0.3,0.1

Chan Stop Cuts=-1