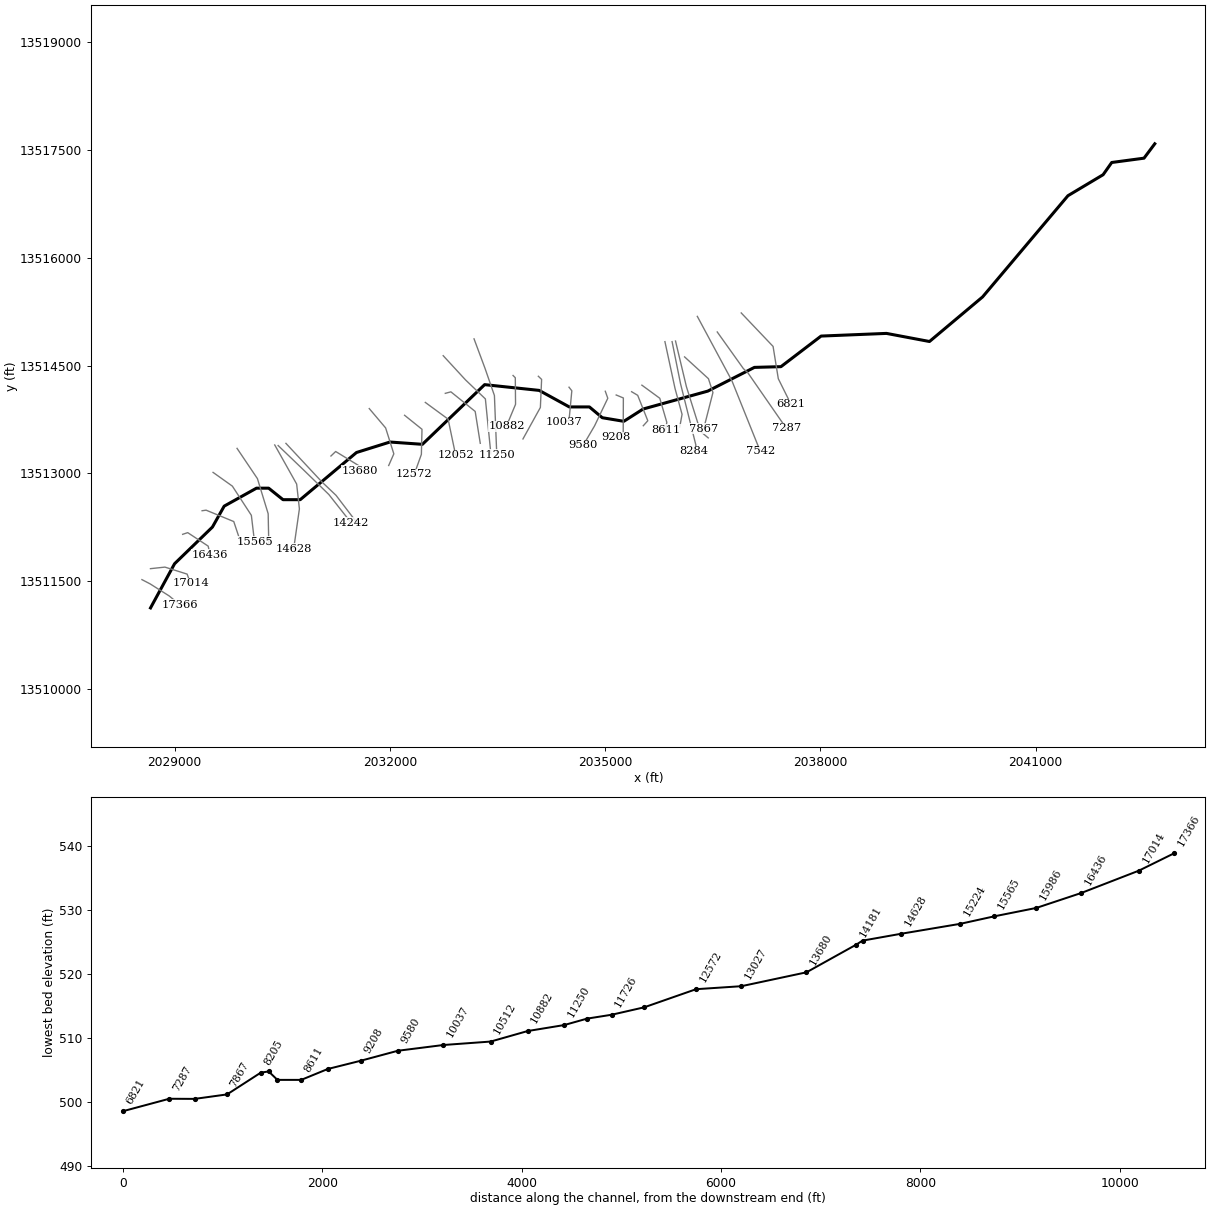
--- UNT 110 in Lagunillas Cr Wtrshd.prj (project) ---

Proj Title=UNT 110 in Lagunillas Cr Wtrshd Base Level Engineering
Current Plan=p01
Default Exp/Contr=0.3,0.1
English Units
Geom File=g01
Flow File=f01
Plan File=p01
BEGIN DESCRIPTION:
UNT 110 in Lagunillas Cr Wtrshd
END DESCRIPTION:

--- UNT 110 in Lagunillas Cr Wtrshd.p01 (plan) ---

Plan Title=Multiple Run
Short Identifier=Multiple
Geom File=g01
Flow File=f01
Subcritical Flow
K Sum by GR= 0
Std Step Tol= 0.01
Critical Tol= 0.01
Num of Std Step Trials= 20
Max Error Tol= 0.3
Flow Tol Ratio= 0.001
Split Flow NTrial= 30
Split Flow Tol= 0.02
Split Flow Ratio= 0.02
Log Output Level= 0
Friction Slope Method= 1
Unsteady Friction Slope Method= 2
Unsteady Bridges Friction Slope Method= 1
Parabolic Critical Depth
Global Vel Dist=  1 , 1 , 1
Global Log Level= 0
CheckData=True
Encroach Param= -1, 0, 0, 0
BEGIN DESCRIPTION:
Multiple Run
END DESCRIPTION:

--- UNT 110 in Lagunillas Cr Wtrshd.f01 (steady flow) ---

Flow Title=Multiple
Number of Profiles=7
Profile Names=10-year,25-year,50-year,1pct_min,100-year,1pct_plu,500-year
River Rch & RM= UNT 110 in Lagun,Reach-1,17366
     120     159     190     113     226     452     325
River Rch & RM= UNT 110 in Lagun,Reach-1,14242
     179     242     294     178     354     707     524
River Rch & RM= UNT 110 in Lagun,Reach-1,11250
     253     349     427     261     521    1039     784
River Rch & RM= UNT 110 in Lagun,Reach-1,7542
     319     445     549     338     674    1344    1030
River Rch & RM= UNT 110 in Lagun,Reach-1,6821
     350     490     606     373     744    1484    1140
River Rch & RM= UNT 110 in Lagun,Reach-1,3081
     413     583     725     448     895    1785    1386
Boundary for River Rch & Prof#=UNT 110 in Lagun,Reach-1,1
Up Type=0
Dn Type=3
Dn Slope=0.005
Boundary for River Rch & Prof#=UNT 110 in Lagun,Reach-1,2
Up Type=0
Dn Type=3
Dn Slope=0.005
Boundary for River Rch & Prof#=UNT 110 in Lagun,Reach-1,3
Up Type=0
Dn Type=3
Dn Slope=0.005
Boundary for River Rch & Prof#=UNT 110 in Lagun,Reach-1,4
Up Type=0
Dn Type=3
Dn Slope=0.005
Boundary for River Rch & Prof#=UNT 110 in Lagun,Reach-1,5
Up Type=0
Dn Type=3
Dn Slope=0.005
Boundary for River Rch & Prof#=UNT 110 in Lagun,Reach-1,6
Up Type=0
Dn Type=3
Dn Slope=0.005
Boundary for River Rch & Prof#=UNT 110 in Lagun,Reach-1,7
Up Type=0
Dn Type=3
Dn Slope=0.005

--- UNT 110 in Lagunillas Cr Wtrshd.g01 (geometry) ---

Geom Title=Existing Conditions

River Reach=UNT 110 in Lagun,Reach-1
Reach XY= 30
      2028664.31     13511128.98      2028999.38     13511743.56
      2029527.16     13512253.98      2029690.80     13512544.54
      2030140.80     13512794.54      2030310.80     13512794.54
      2030510.80     13512634.54      2030750.80     13512634.54
      2031534.92     13513290.71      2032001.30     13513436.32
      2032453.77     13513404.54      2033320.80     13514234.54
      2034080.80     13514154.54      2034500.80     13513924.54
      2034780.80     13513924.54      2034960.80     13513774.54
      2035260.80     13513724.54      2035529.55     13513895.32
      2036430.80     13514144.54      2037080.80     13514474.54
      2037450.80     13514484.54      2038010.01     13514910.17
      2038921.39     13514947.24      2039520.80     13514834.54
      2040260.80     13515454.54      2041450.31     13516862.11
      2041940.80     13517154.54      2042060.80     13517324.54
      2042510.80     13517384.54      2042660.80     13517584.54

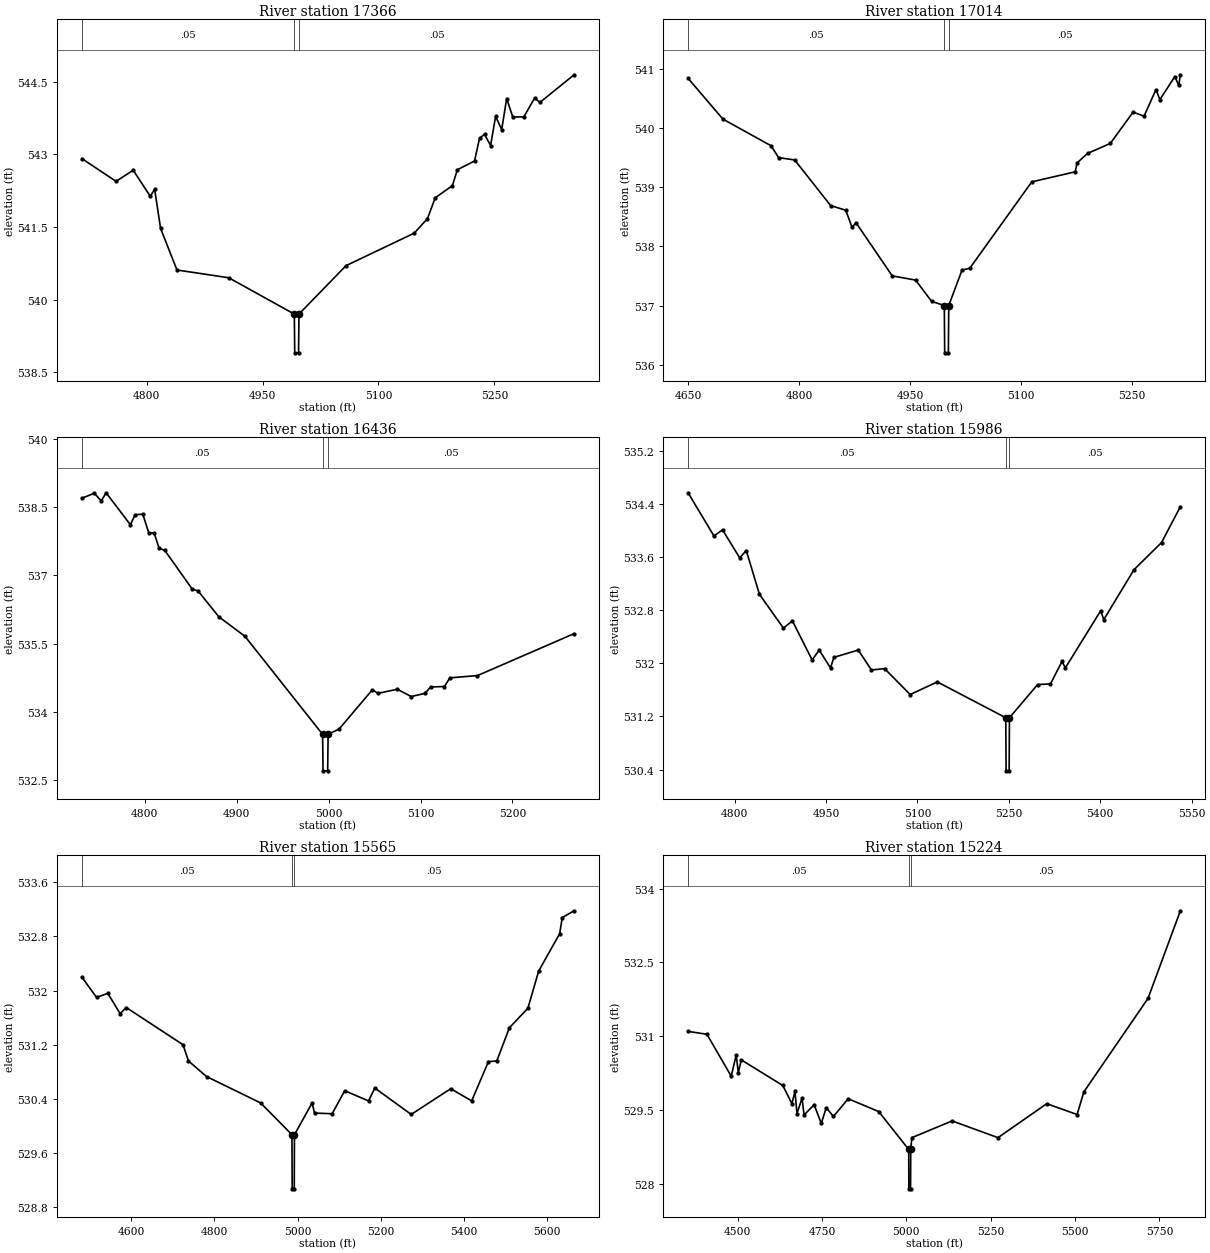
Type RM Length L Ch R = 1,17366,352,352,352
BEGIN DESCRIPTION:
Mapping XS 668839d8
END DESCRIPTION:
XS GIS Cut Line= 4
      2028544.49     13511522.37      2028657.74     13511463.79
      2028925.97     13511294.52      2029074.43     13511172.10
#Sta/Elev= 30
  4716.1  542.91  4760.4  542.44  4782.6  542.67  4804.7  542.13  4810.3  542.28
  4818.0  541.47  4839.2  540.61  4906.2  540.45  4991.1  539.70  4991.6  538.90
  4996.6  538.90  4997.1  539.70  5058.0  540.70  5146.2  541.37  5163.4  541.67
  5173.4  542.10  5195.6  542.35  5202.1  542.68  5224.3  542.86  5230.8  543.33
  5237.3  543.41  5245.1  543.18  5251.6  543.78  5259.5  543.51  5265.9  544.15
  5273.8  543.77  5288.1  543.77  5302.1  544.16  5309.0  544.07  5353.2  544.64
#Mann=3,-1,0
  4716.1    0.05       0  4991.1   0.035       0  4997.1    0.05       0
Bank Sta=4991.1,4997.1
Exp/Cntr=0.3,0.1

Type RM Length L Ch R = 1,17014,578,578,578
BEGIN DESCRIPTION:
Mapping XS 9026eefb
END DESCRIPTION:
XS GIS Cut Line= 4
      2028663.32     13511674.94      2028865.11     13511696.63
      2029174.66     13511599.21      2029221.01     13511468.78
#Sta/Elev= 30
  4649.9  540.84  4697.1  540.15  4762.2  539.70  4772.3  539.50  4794.1  539.46
  4842.7  538.69  4863.2  538.61  4871.7  538.32  4877.0  538.40  4926.1  537.50
  4957.6  537.43  4979.3  537.07  4996.5  537.00  4997.0  536.20  5002.0  536.20
  5002.5  537.00  5020.5  537.60  5031.0  537.63  5114.8  539.09  5173.6  539.26
  5176.1  539.41  5190.2  539.57  5221.1  539.74  5251.9  540.27  5266.7  540.20
  5282.8  540.65  5288.1  540.48  5308.3  540.87  5313.6  540.72  5315.8  540.90
#Mann=3,-1,0
  4649.9    0.05       0  4996.5   0.035       0  5002.5    0.05       0
Bank Sta=4996.5,5002.5
Exp/Cntr=0.3,0.1

Type RM Length L Ch R = 1,16436,450,450,450
BEGIN DESCRIPTION:
Mapping XS 31cc01f7
END DESCRIPTION:
XS GIS Cut Line= 4
      2029112.13     13512152.58      2029182.48     13512176.03
      2029467.63     13511988.53      2029493.68     13511871.31
#Sta/Elev= 30
  4731.6  538.69  4745.2  538.80  4752.7  538.63  4758.0  538.81  4784.4  538.11
  4789.6  538.33  4797.9  538.34  4804.4  537.93  4810.2  537.93  4815.7  537.59
  4821.7  537.55  4851.9  536.69  4857.9  536.66  4880.6  536.09  4909.1  535.66
  4993.5  533.51  4994.0  532.71  4999.0  532.71  4999.5  533.51  5011.6  533.63
  5047.7  534.49  5053.7  534.41  5074.8  534.50  5089.9  534.34  5105.0  534.41
  5110.9  534.55  5126.0  534.56  5132.0  534.75  5162.0  534.80  5267.1  535.72
#Mann=3,-1,0
  4731.6    0.05       0  4993.5   0.035       0  4999.5    0.05       0
Bank Sta=4993.5,4999.5
Exp/Cntr=0.3,0.1

Type RM Length L Ch R = 1,15986,421,421,421
BEGIN DESCRIPTION:
Mapping XS e5d8df64
END DESCRIPTION:
XS GIS Cut Line= 4
      2029382.98     13512480.71      2029438.99     13512488.53
      2029824.31     13512330.31      2029930.47     13512012.78
#Sta/Elev= 30
  4723.6  534.57  4766.0  533.92  4780.2  534.01  4808.3  533.59  4819.1  533.70
  4840.7  533.04  4880.1  532.53  4894.8  532.64  4927.2  532.05  4938.8  532.20
  4957.4  531.93  4962.8  532.09  5002.9  532.20  5024.5  531.90  5046.1  531.92
  5088.1  531.53  5132.6  531.72  5245.0  531.18  5245.5  530.38  5250.5  530.38
  5251.0  531.18  5297.2  531.68  5318.3  531.69  5337.4  532.03  5342.7  531.93
  5400.6  532.79  5405.9  532.66  5455.3  533.41  5500.6  533.82  5531.5  534.36
#Mann=3,-1,0
  4723.6    0.05       0  5245.0   0.035       0  5251.0    0.05       0
Bank Sta=5245,5251
Exp/Cntr=0.3,0.1

Type RM Length L Ch R = 1,15565,341,341,341
BEGIN DESCRIPTION:
Mapping XS 19792b22
END DESCRIPTION:
XS GIS Cut Line= 4
      2029535.97     13513013.97      2029804.78     13512822.94
      2030069.53     13512417.12      2030113.23     13512050.43
#Sta/Elev= 30
  4481.1  532.20  4516.5  531.90  4543.6  531.96  4573.1  531.66  4587.9  531.75
  4724.4  531.20  4737.5  530.96  4780.9  530.73  4910.9  530.34  4986.3  529.87
  4986.8  529.07  4991.8  529.07  4992.3  529.87  5034.7  530.34  5040.6  530.19
  5083.0  530.18  5113.1  530.52  5170.4  530.37  5185.5  530.56  5273.0  530.17
  5368.0  530.55  5418.4  530.37  5458.7  530.95  5478.8  530.96  5509.0  531.45
  5553.6  531.74  5579.5  532.29  5629.9  532.84  5636.2  533.08  5664.7  533.18
#Mann=3,-1,0
  4481.1    0.05       0  4986.3   0.035       0  4992.3    0.05       0
Bank Sta=4986.3,4992.3
Exp/Cntr=0.3,0.1

Type RM Length L Ch R = 1,15224,596,596,596
BEGIN DESCRIPTION:
Mapping XS ae35a062
END DESCRIPTION:
XS GIS Cut Line= 4
      2029870.15     13513348.22      2030154.17     13512927.10
      2030303.91     13512438.82      2030312.87     13511999.18
#Sta/Elev= 30
  4353.4  531.10  4409.2  531.04  4481.1  530.19  4496.1  530.62  4502.1  530.26
  4511.1  530.52  4634.0  530.00  4661.0  529.63  4670.0  529.88  4676.0  529.43
  4691.0  529.74  4697.0  529.40  4726.9  529.61  4747.9  529.23  4762.9  529.55
  4783.9  529.37  4827.7  529.73  4918.2  529.47  5007.0  528.70  5007.5  527.90
  5012.5  527.90  5013.0  528.70  5016.4  528.94  5135.5  529.28  5271.5  528.94
  5415.9  529.63  5505.9  529.41  5525.9  529.87  5716.0  531.77  5811.8  533.55
#Mann=3,-1,0
  4353.4    0.05       0  5007.0   0.035       0  5013.0    0.05       0
Bank Sta=5007,5013
Exp/Cntr=0.3,0.1

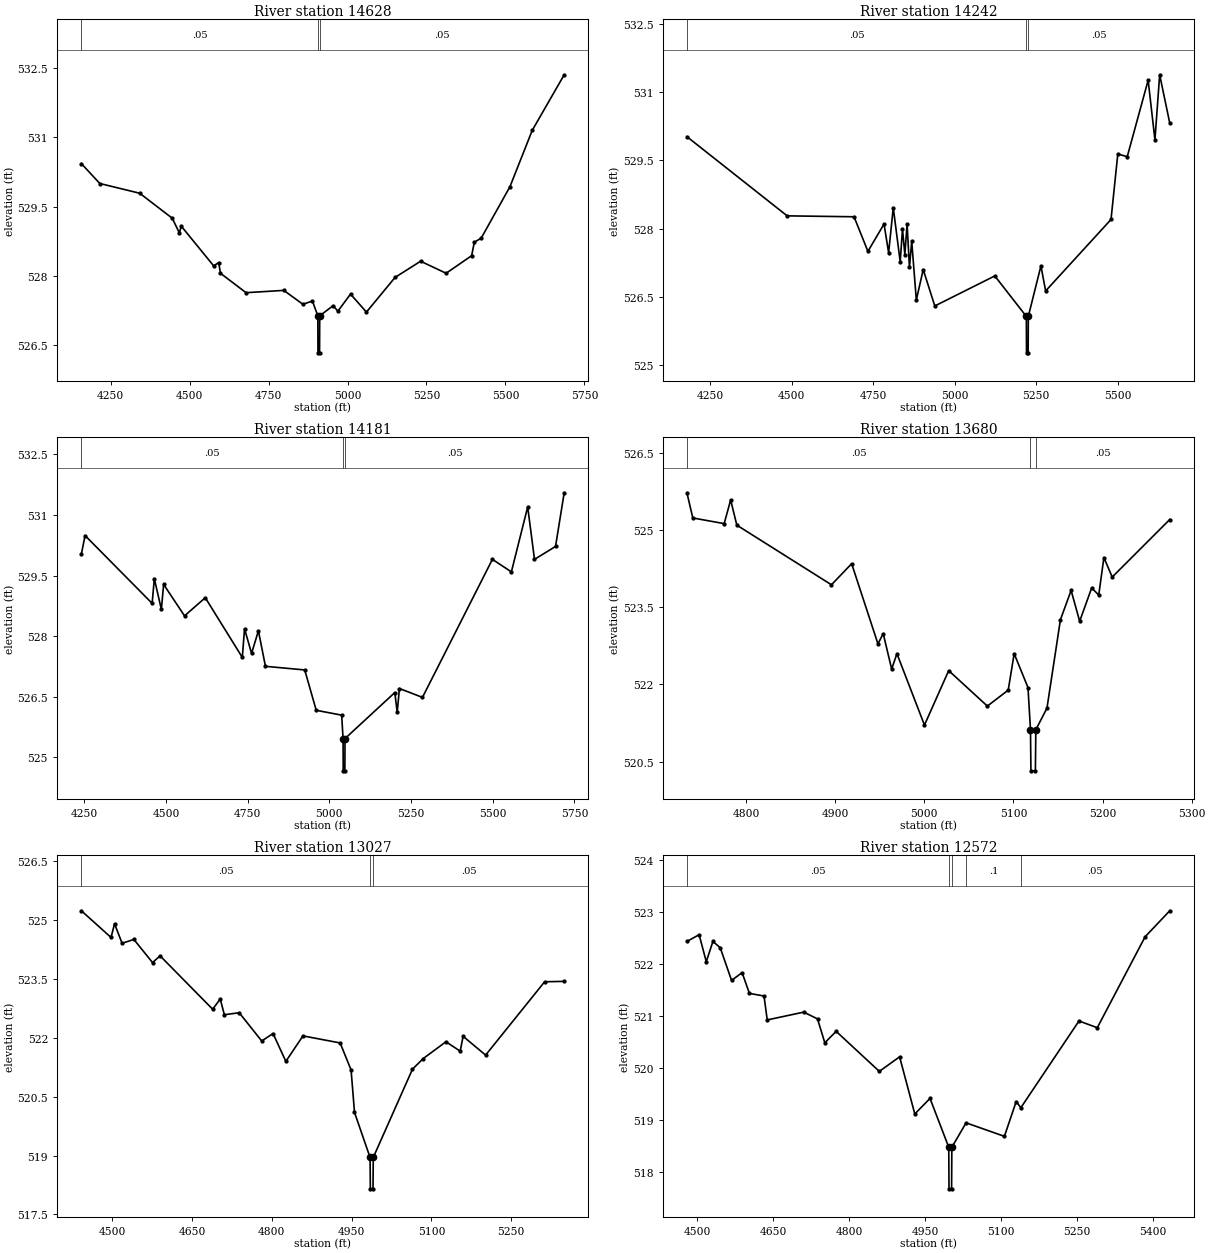
Type RM Length L Ch R = 1,14628,386,386,386
BEGIN DESCRIPTION:
Mapping XS b0692ae4
END DESCRIPTION:
XS GIS Cut Line= 4
      2030395.37     13513395.88      2030700.92     13512851.81
      2030739.12     13512506.32      2030660.11     13511954.95
#Sta/Elev= 30
  4157.4  530.43  4215.8  530.00  4341.9  529.79  4445.1  529.25  4467.8  528.93
  4473.5  529.08  4576.2  528.22  4592.1  528.29  4597.8  528.06  4678.8  527.64
  4798.3  527.69  4858.7  527.39  4888.9  527.46  4906.0  527.14  4906.5  526.34
  4911.5  526.34  4912.0  527.14  4954.6  527.36  4969.4  527.24  5009.6  527.61
  5059.9  527.22  5150.5  527.97  5231.4  528.32  5312.2  528.06  5393.0  528.44
  5401.4  528.73  5423.3  528.82  5514.2  529.93  5584.9  531.15  5686.0  532.35
#Mann=3,-1,0
  4157.4    0.05       0  4906.0   0.035       0  4912.0    0.05       0
Bank Sta=4906,4912
Exp/Cntr=0.3,0.1

Type RM Length L Ch R = 1,14242,61,61,61
BEGIN DESCRIPTION:
Mapping XS 0016387a
END DESCRIPTION:
XS GIS Cut Line= 4
      2030443.08     13513387.25      2030802.92     13513042.78
      2031149.27     13512706.84      2031458.72     13512315.18
#Sta/Elev= 30
  4179.3  530.02  4486.5  528.28  4691.5  528.26  4734.0  527.50  4783.4  528.10
  4797.5  527.47  4811.7  528.46  4833.0  527.27  4840.0  527.99  4847.2  527.43
  4854.1  528.10  4861.3  527.15  4868.3  527.72  4882.4  526.43  4903.5  527.10
  4939.0  526.30  5122.9  526.96  5219.6  526.07  5220.1  525.27  5225.1  525.27
  5225.6  526.07  5264.3  527.18  5278.7  526.63  5479.1  528.20  5499.9  529.64
  5528.8  529.58  5592.9  531.26  5613.7  529.95  5628.2  531.38  5659.1  530.32
#Mann=3,-1,0
  4179.3    0.05       0  5219.6    0.03       0  5225.6    0.05       0
Bank Sta=5219.6,5225.6
Exp/Cntr=0.3,0.1

Type RM Length L Ch R = 1,14181,501,501,501
BEGIN DESCRIPTION:
Mapping XS 02ac5641
END DESCRIPTION:
XS GIS Cut Line= 4
      2030551.62     13513417.59      2031055.52     13512878.72
      2031249.53     13512695.13      2031536.68     13512319.74
#Sta/Elev= 30
  4241.2  530.03  4252.5  530.49  4457.7  528.81  4464.5  529.42  4486.0  528.66
  4492.9  529.28  4556.9  528.50  4620.4  528.95  4733.7  527.47  4740.5  528.18
  4762.0  527.57  4783.0  528.13  4804.5  527.25  4924.7  527.16  4959.9  526.16
  5037.8  526.04  5042.0  525.46  5042.5  524.66  5047.5  524.66  5048.0  525.46
  5200.4  526.60  5207.7  526.11  5214.5  526.70  5285.0  526.48  5499.0  529.90
  5557.1  529.59  5607.0  531.20  5627.8  529.90  5692.2  530.22  5718.7  531.55
#Mann=3,-1,0
  4241.2    0.05       0  5042.0    0.03       0  5048.0    0.05       0
Bank Sta=5042,5048
Exp/Cntr=0.3,0.1

Type RM Length L Ch R = 1,13680,653,653,653
BEGIN DESCRIPTION:
Mapping XS d2c447f5
END DESCRIPTION:
XS GIS Cut Line= 4
      2031178.81     13513242.02      2031244.76     13513304.50
      2031574.62     13513103.11      2031574.62     13513038.54
#Sta/Elev= 30
  4733.5  525.73  4740.1  525.24  4775.3  525.13  4782.6  525.59  4789.5  525.10
  4895.7  523.94  4918.4  524.35  4947.9  522.79  4953.8  522.99  4963.3  522.30
  4969.2  522.60  5000.1  521.21  5027.3  522.27  5070.7  521.58  5094.1  521.89
  5100.8  522.60  5116.3  521.94  5119.1  521.12  5119.6  520.32  5124.6  520.32
  5125.1  521.12  5137.6  521.54  5152.7  523.26  5164.7  523.83  5174.3  523.23
  5187.8  523.88  5195.7  523.74  5201.5  524.47  5210.8  524.09  5275.4  525.21
#Mann=3,-1,0
  4733.5    0.05       0  5119.1    0.03       0  5125.1    0.05       0
Bank Sta=5119.1,5125.1
Exp/Cntr=0.3,0.1

Type RM Length L Ch R = 1,13027,455,455,455
BEGIN DESCRIPTION:
Mapping XS dd3d2709
END DESCRIPTION:
XS GIS Cut Line= 4
      2031712.90     13513901.37      2031940.94     13513632.63
      2032055.21     13513272.15      2031983.73     13513109.70
#Sta/Elev= 30
  4441.7  525.24  4497.5  524.56  4504.1  524.91  4518.3  524.41  4540.4  524.51
  4575.5  523.92  4589.8  524.09  4688.6  522.73  4702.9  522.99  4710.6  522.59
  4738.6  522.64  4780.9  521.92  4802.2  522.11  4826.3  521.40  4858.5  522.05
  4928.4  521.87  4949.0  521.18  4955.4  520.10  4984.7  518.95  4985.2  518.15
  4990.2  518.15  4990.7  518.95  5064.4  521.20  5084.5  521.47  5127.4  521.90
  5154.3  521.66  5159.6  522.04  5202.0  521.56  5313.0  523.43  5349.8  523.44
#Mann=3,-1,0
  4441.7    0.05       0  4984.7    0.03       0  4990.7    0.05       0
Bank Sta=4984.7,4990.7
Exp/Cntr=0.3,0.1

Type RM Length L Ch R = 1,12572,520,520,520
BEGIN DESCRIPTION:
Mapping XS 5c08f708
END DESCRIPTION:
XS GIS Cut Line= 4
      2032205.22     13513808.27      2032447.89     13513613.53
      2032439.20     13513264.57      2032340.25     13512989.22
#Sta/Elev= 30
  4479.8  522.44  4503.9  522.57  4518.0  522.05  4531.1  522.44  4545.5  522.32
  4567.9  521.69  4588.7  521.84  4603.1  521.44  4631.9  521.39  4638.3  520.93
  4710.3  521.08  4737.5  520.95  4751.9  520.49  4774.3  520.71  4859.5  519.94
  4899.5  520.22  4929.5  519.12  4959.5  519.42  4996.5  518.48  4997.0  517.68
  5002.1  517.68  5002.6  518.48  5030.7  518.95  5106.3  518.69  5129.6  519.36
  5138.7  519.24  5253.5  520.91  5289.6  520.78  5384.0  522.53  5432.6  523.03
#Mann=5,-1,0
  4479.8    0.05       0  4996.5    0.03       0  5002.6    0.05       0
  5030.7     0.1       0  5138.7    0.05       0
Bank Sta=4996.5,5002.6
Exp/Cntr=0.3,0.1

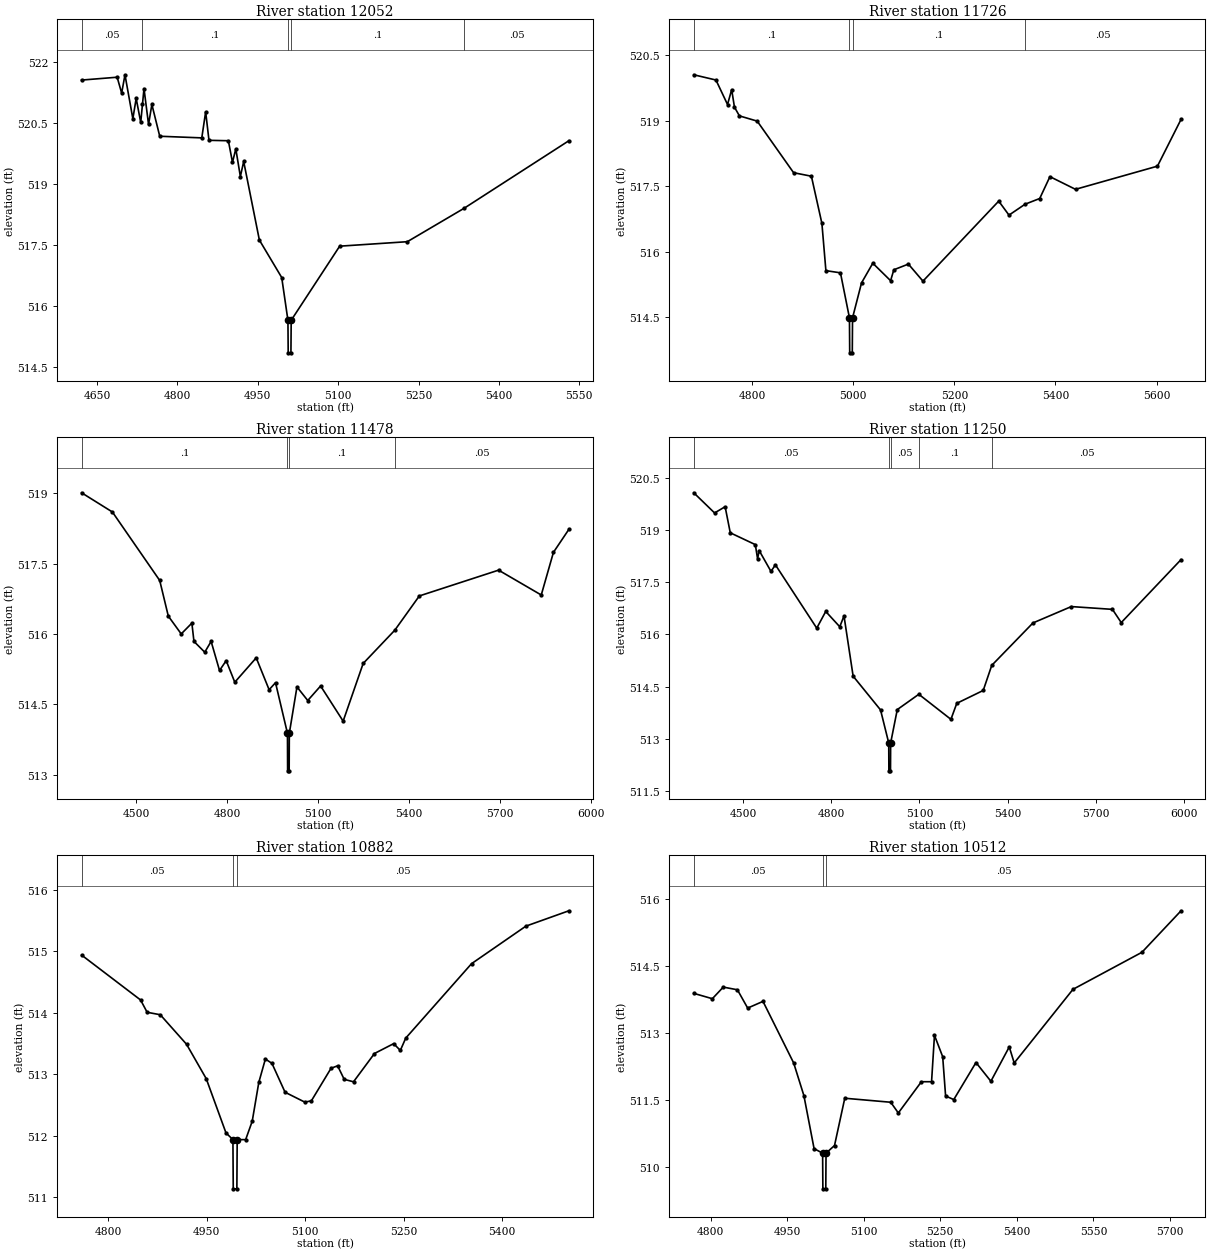
Type RM Length L Ch R = 1,12052,326,326,326
BEGIN DESCRIPTION:
Mapping XS e76c0ae1
END DESCRIPTION:
XS GIS Cut Line= 3
      2032493.94     13513987.37      2032811.66     13513754.72
      2032917.51     13513249.79
#Sta/Elev= 30
  4621.0  521.55  4687.4  521.62  4695.8  521.23  4702.0  521.68  4716.7  520.60
  4722.9  521.10  4731.4  520.51  4734.7  520.96  4737.5  521.34  4746.0  520.46
  4752.2  520.95  4766.9  520.17  4845.4  520.13  4852.6  520.77  4858.8  520.07
  4895.0  520.06  4902.7  519.53  4908.9  519.86  4917.4  519.18  4923.6  519.55
  4952.9  517.62  4994.6  516.70  5006.2  515.65  5006.7  514.85  5011.8  514.85
  5012.3  515.65  5102.8  517.47  5229.1  517.58  5335.0  518.40  5530.7  520.06
#Mann=5,-1,0
  4621.0    0.05       0  4734.7     0.1       0  5006.2    0.07       0
  5012.3     0.1       0  5335.0    0.05       0
Bank Sta=5006.2,5012.3
Exp/Cntr=0.3,0.1

Type RM Length L Ch R = 1,11726,248,248,248
BEGIN DESCRIPTION:
Mapping XS a99b6917
END DESCRIPTION:
XS GIS Cut Line= 4
      2032772.56     13514113.54      2032850.66     13514134.36
      2033189.20     13513861.79      2033259.74     13513418.83
#Sta/Elev= 30
  4684.5  520.05  4728.4  519.93  4751.3  519.37  4759.5  519.71  4765.0  519.31
  4774.8  519.11  4810.0  518.99  4882.0  517.81  4917.2  517.73  4938.0  516.65
  4945.9  515.57  4974.7  515.52  4992.5  514.49  4993.0  513.69  4998.1  513.69
  4998.6  514.49  5016.4  515.29  5038.7  515.74  5073.9  515.34  5080.3  515.59
  5109.1  515.72  5137.9  515.33  5287.8  517.16  5308.1  516.84  5340.0  517.09
  5368.9  517.22  5389.1  517.72  5439.7  517.43  5601.8  517.96  5648.5  519.03
#Mann=4,-1,0
  4684.5     0.1       0  4992.5    0.07       0  4998.6     0.1       0
  5340.0    0.05       0
Bank Sta=4992.5,4998.6
Exp/Cntr=0.3,0.1

Type RM Length L Ch R = 1,11478,228,228,228
BEGIN DESCRIPTION:
Mapping XS 521bdb0f
END DESCRIPTION:
XS GIS Cut Line= 4
      2032743.43     13514637.25      2033053.79     13514301.03
      2033331.25     13514036.04      2033407.50     13513274.38
#Sta/Elev= 30
  4320.7  519.01  4422.3  518.60  4578.3  517.14  4606.6  516.38  4649.2  516.00
  4684.3  516.23  4691.2  515.84  4726.8  515.61  4747.8  515.84  4775.5  515.22
  4797.5  515.43  4825.8  514.97  4896.5  515.49  4939.0  514.81  4960.1  514.96
  4999.5  513.88  5000.0  513.08  5005.1  513.08  5005.6  513.88  5030.8  514.87
  5066.4  514.58  5108.8  514.89  5183.1  514.14  5249.1  515.37  5353.5  516.08
  5434.3  516.81  5695.6  517.36  5836.3  516.83  5876.5  517.74  5927.4  518.23
#Mann=4,-1,0
  4320.7     0.1       0  4999.5    0.07       0  5005.6     0.1       0
  5353.5    0.05       0
Bank Sta=4999.5,5005.6
Exp/Cntr=0.3,0.1

Type RM Length L Ch R = 1,11250,368,368,368
BEGIN DESCRIPTION:
Mapping XS aaa73b92
END DESCRIPTION:
XS GIS Cut Line= 4
      2033173.14     13514871.57      2033326.36     13514460.75
      2033457.12     13514083.79      2033489.96     13513261.40
#Sta/Elev= 30
  4330.9  520.07  4401.9  519.49  4437.8  519.67  4455.3  518.92  4540.7  518.58
  4548.4  518.17  4553.8  518.41  4594.1  517.81  4609.1  518.00  4750.0  516.18
  4780.6  516.66  4828.4  516.22  4842.9  516.53  4874.0  514.80  4967.4  513.83
  4995.3  512.88  4995.8  512.08  5001.3  512.08  5001.8  512.88  5024.4  513.84
  5097.8  514.28  5207.2  513.56  5227.2  514.02  5317.3  514.39  5346.3  515.11
  5486.8  516.33  5617.5  516.80  5757.6  516.72  5787.6  516.34  5991.4  518.15
#Mann=5,-1,0
  4330.9    0.05       0  4995.3    0.03       0  5001.8    0.05       0
  5097.8     0.1       0  5346.3    0.05       0
Bank Sta=4995.3,5001.8
Exp/Cntr=0.3,0.1

Type RM Length L Ch R = 1,10882,370,370,370
BEGIN DESCRIPTION:
Mapping XS 625f4274
END DESCRIPTION:
XS GIS Cut Line= 4
      2033716.97     13514361.80      2033748.23     13514330.54
      2033751.70     13513960.75      2033625.30     13513658.21
#Sta/Elev= 30
  4759.8  514.94  4849.6  514.21  4859.6  514.01  4879.6  513.97  4919.6  513.49
  4949.6  512.93  4979.6  512.05  4990.2  511.94  4990.7  511.14  4996.2  511.14
  4996.7  511.94  5009.6  511.94  5019.6  512.24  5029.6  512.87  5039.6  513.25
  5049.6  513.18  5069.6  512.71  5099.6  512.55  5109.6  512.57  5139.6  513.10
  5149.6  513.14  5159.6  512.92  5173.8  512.88  5205.7  513.34  5234.9  513.50
  5245.1  513.39  5253.3  513.59  5353.5  514.80  5436.2  515.41  5501.7  515.66
#Mann=3,-1,0
  4759.8    0.05       0  4990.2   0.035       0  4996.7    0.05       0
Bank Sta=4990.2,4996.7
Exp/Cntr=0.3,0.1

Type RM Length L Ch R = 1,10512,475,475,475
BEGIN DESCRIPTION:
Mapping XS 03af09b4
END DESCRIPTION:
XS GIS Cut Line= 4
      2034069.38     13514350.98      2034114.99     13514307.54
      2034097.62     13513916.91      2033854.98     13513479.16
#Sta/Elev= 30
  4767.2  513.88  4803.6  513.76  4825.0  514.02  4852.7  513.96  4872.8  513.55
  4902.8  513.70  4962.9  512.32  4982.9  511.59  5002.9  510.40  5019.6  510.30
  5020.1  509.50  5025.8  509.50  5026.3  510.30  5042.9  510.47  5063.0  511.53
  5153.0  511.44  5167.9  511.20  5213.1  511.90  5233.0  511.90  5238.7  512.94
  5254.8  512.46  5260.5  511.58  5276.5  511.50  5320.0  512.33  5349.2  511.91
  5385.2  512.68  5394.9  512.32  5510.0  513.97  5645.1  514.80  5721.7  515.73
#Mann=3,-1,0
  4767.2    0.05       0  5019.6   0.035       0  5026.3    0.05       0
Bank Sta=5019.6,5026.3
Exp/Cntr=0.3,0.1

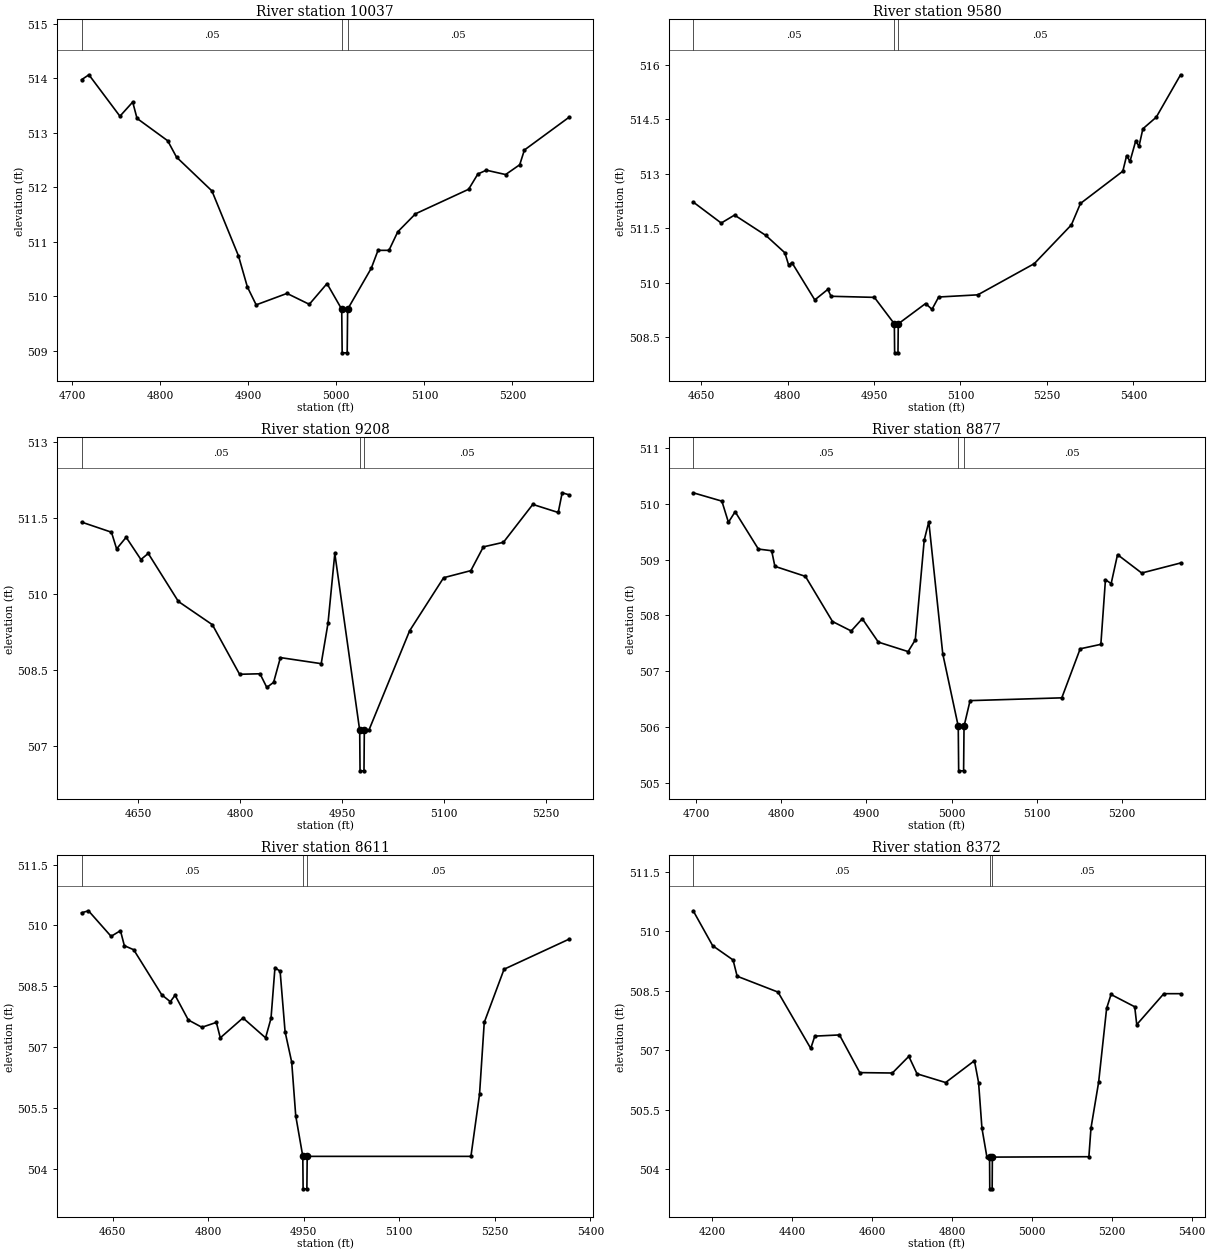
Type RM Length L Ch R = 1,10037,457,457,457
BEGIN DESCRIPTION:
Mapping XS 6afe9ded
END DESCRIPTION:
XS GIS Cut Line= 4
      2034496.91     13514199.06      2034535.99     13514149.12
      2034496.93     13513736.79      2034425.29     13513712.91
#Sta/Elev= 30
  4711.0  513.97  4719.3  514.06  4754.5  513.30  4769.0  513.56  4773.9  513.26
  4808.7  512.85  4818.7  512.55  4858.9  511.93  4889.0  510.74  4899.1  510.17
  4909.1  509.84  4944.1  510.05  4969.4  509.85  4989.5  510.23  5006.2  509.76
  5006.7  508.96  5012.4  508.96  5012.9  509.76  5039.7  510.51  5047.4  510.84
  5059.8  510.84  5069.8  511.18  5089.9  511.51  5150.2  511.96  5160.7  512.24
  5170.3  512.31  5192.2  512.23  5208.2  512.41  5213.5  512.68  5264.1  513.28
#Mann=3,-1,0
  4711.0    0.05       0  5006.2   0.035       0  5012.9    0.05       0
Bank Sta=5006.2,5012.9
Exp/Cntr=0.3,0.1

Type RM Length L Ch R = 1,9580,372,372,372
BEGIN DESCRIPTION:
Mapping XS ef105d17
END DESCRIPTION:
XS GIS Cut Line= 4
      2035002.58     13514142.58      2035037.29     13514044.95
      2034852.83     13513660.84      2034693.02     13513388.60
#Sta/Elev= 30
  4636.4  512.22  4685.0  511.64  4708.1  511.86  4762.3  511.30  4795.4  510.82
  4802.0  510.48  4807.6  510.55  4847.3  509.52  4869.9  509.81  4875.5  509.62
  4950.7  509.59  4985.3  508.86  4985.8  508.06  4991.6  508.06  4992.1  508.86
  5039.5  509.42  5050.6  509.26  5062.2  509.60  5130.1  509.66  5228.0  510.52
  5292.4  511.59  5308.1  512.18  5381.6  513.07  5388.2  513.50  5394.0  513.34
  5403.9  513.90  5409.7  513.76  5416.4  514.24  5439.6  514.56  5481.8  515.73
#Mann=3,-1,0
  4636.4    0.05       0  4985.3   0.035       0  4992.1    0.05       0
Bank Sta=4985.3,4992.1
Exp/Cntr=0.3,0.1

Type RM Length L Ch R = 1,9208,331,331,331
BEGIN DESCRIPTION:
Mapping XS 978baba5
END DESCRIPTION:
XS GIS Cut Line= 4
      2035154.45     13514090.54      2035254.31     13514049.29
      2035252.14     13513563.18      2035145.83     13513502.43
#Sta/Elev= 30
  4567.2  511.42  4611.1  511.22  4618.7  510.89  4632.7  511.12  4654.4  510.68
  4665.2  510.80  4709.5  509.85  4759.5  509.39  4799.5  508.41  4829.5  508.42
  4839.5  508.15  4849.5  508.25  4859.5  508.74  4919.5  508.62  4929.5  509.42
  4939.5  510.80  4976.1  507.30  4976.6  506.50  4982.4  506.50  4982.9  507.30
  4989.5  507.30  5049.5  509.27  5099.5  510.32  5139.5  510.46  5157.9  510.93
  5187.4  511.02  5230.6  511.77  5268.0  511.61  5273.8  512.00  5283.8  511.96
#Mann=3,-1,0
  4567.2    0.05       0  4976.1   0.035       0  4982.9    0.05       0
Bank Sta=4976.1,4982.9
Exp/Cntr=0.3,0.1

Type RM Length L Ch R = 1,8877,266,266,266
BEGIN DESCRIPTION:
Mapping XS 3092e7d7
END DESCRIPTION:
XS GIS Cut Line= 4
      2035369.31     13514136.11      2035453.96     13514086.18
      2035595.02     13513732.45      2035532.10     13513663.02
#Sta/Elev= 30
  4696.4  510.20  4730.1  510.05  4737.8  509.67  4745.7  509.86  4773.0  509.19
  4788.6  509.16  4792.4  508.88  4828.3  508.70  4860.1  507.89  4882.1  507.72
  4895.1  507.94  4914.0  507.52  4949.0  507.35  4957.4  507.56  4967.9  509.35
  4973.3  509.68  4989.7  507.31  5007.9  506.01  5008.4  505.21  5014.2  505.21
  5014.7  506.01  5021.8  506.47  5129.6  506.52  5151.2  507.40  5175.5  507.48
  5180.9  508.64  5187.6  508.57  5195.1  509.09  5223.5  508.76  5269.2  508.94
#Mann=3,-1,0
  4696.4    0.05       0  5007.9   0.035       0  5014.7    0.05       0
Bank Sta=5007.9,5014.7
Exp/Cntr=0.3,0.1

Type RM Length L Ch R = 1,8611,239,239,239
BEGIN DESCRIPTION:
Mapping XS 1dd9899b
END DESCRIPTION:
XS GIS Cut Line= 4
      2035512.55     13514227.25      2035762.12     13514044.95
      2035859.78     13513710.75      2035842.41     13513604.39
#Sta/Elev= 30
  4601.4  510.31  4612.2  510.36  4647.7  509.73  4662.4  509.87  4668.5  509.50
  4683.2  509.40  4727.2  508.29  4740.7  508.12  4748.1  508.28  4768.9  507.67
  4790.2  507.49  4812.9  507.61  4819.1  507.23  4854.7  507.72  4890.2  507.23
  4898.7  507.71  4904.9  508.96  4913.0  508.87  4920.8  507.38  4931.2  506.63
  4937.5  505.31  4948.6  504.31  4949.1  503.51  4955.0  503.51  4955.5  504.31
  5212.5  504.31  5226.0  505.84  5233.4  507.61  5264.5  508.92  5366.4  509.66
#Mann=3,-1,0
  4601.4    0.05       0  4948.6   0.035       0  4955.5    0.05       0
Bank Sta=4948.6,4955.5
Exp/Cntr=0.3,0.1

Type RM Length L Ch R = 1,8372,88,88,88
BEGIN DESCRIPTION:
Mapping XS 929da385
END DESCRIPTION:
XS GIS Cut Line= 4
      2035833.71     13514832.56      2035974.79     13514179.50
      2036072.45     13513821.43      2036039.95     13513643.75
#Sta/Elev= 30
  4152.3  510.52  4201.0  509.64  4252.1  509.28  4262.3  508.87  4364.6  508.47
  4446.5  507.05  4456.7  507.36  4518.4  507.39  4569.3  506.44  4650.8  506.43
  4692.0  506.85  4712.5  506.41  4784.1  506.19  4856.2  506.74  4866.6  506.19
  4875.0  505.04  4887.3  504.32  4894.1  504.31  4894.6  503.51  4900.6  503.51
  4901.1  504.31  5142.7  504.32  5147.9  505.04  5167.1  506.20  5187.1  508.06
  5198.1  508.41  5257.4  508.10  5262.5  507.65  5330.3  508.43  5372.2  508.43
#Mann=3,-1,0
  4152.3    0.05       0  4894.1   0.035       0  4901.1    0.05       0
Bank Sta=4894.1,4901.1
Exp/Cntr=0.3,0.1

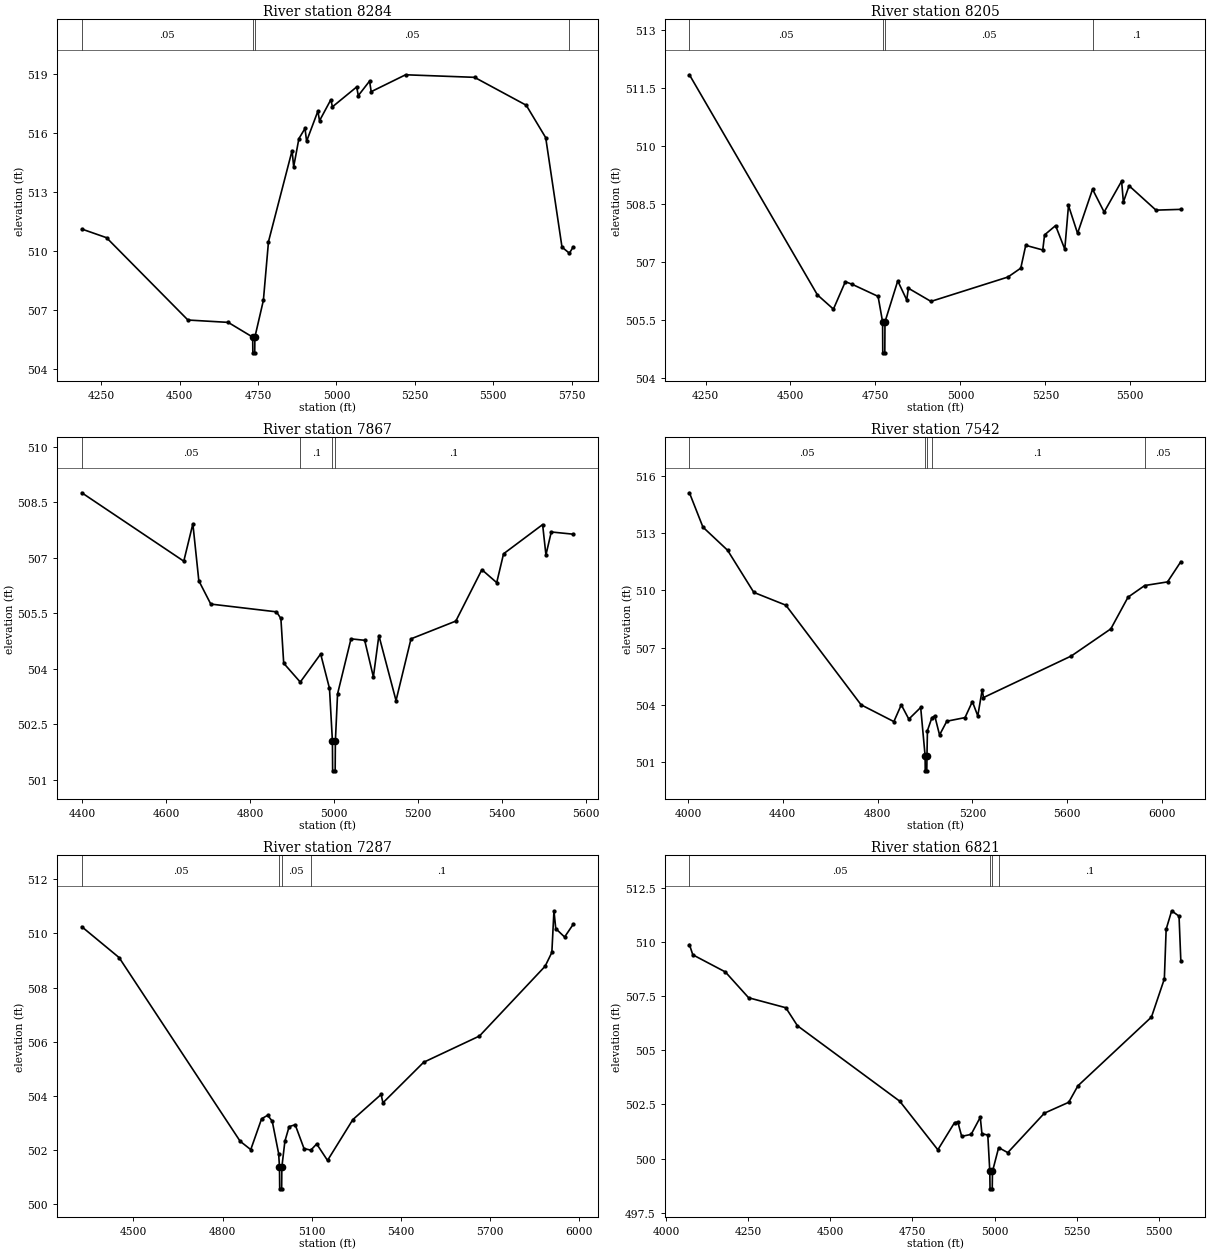
Type RM Length L Ch R = 1,8284,79,79,79
BEGIN DESCRIPTION:
Mapping XS ee81815e
END DESCRIPTION:
XS GIS Cut Line= 4
      2035933.54     13514832.54      2036050.75     13514248.95
      2036265.59     13513391.74      2036237.85     13513308.51
#Sta/Elev= 30
  4188.3  511.13  4267.1  510.69  4526.6  506.50  4655.0  506.38  4733.1  505.63
  4733.6  504.83  4739.6  504.83  4740.1  505.63  4767.2  507.50  4783.5  510.49
  4858.7  515.12  4863.8  514.30  4880.4  515.73  4899.9  516.25  4905.0  515.60
  4941.0  517.13  4946.2  516.64  4982.2  517.71  4987.4  517.35  5064.6  518.36
  5069.8  517.92  5105.8  518.66  5110.9  518.12  5220.6  518.98  5440.4  518.85
  5605.2  517.43  5667.3  515.78  5719.2  510.21  5742.8  509.90  5755.0  510.22
#Mann=4,-1,0
  4188.3    0.05       0  4733.1   0.035       0  4740.1    0.05       0
  5742.8     0.1       0
Bank Sta=4733.1,4740.1
Exp/Cntr=0.3,0.1

Type RM Length L Ch R = 1,8205,338,338,338
BEGIN DESCRIPTION:
Mapping XS 308013b1
END DESCRIPTION:
XS GIS Cut Line= 4
      2035981.28     13514841.24      2036133.21     13514205.54
      2036328.53     13513584.88      2036437.06     13513493.72
#Sta/Elev= 30
  4202.6  511.83  4579.1  506.14  4626.3  505.77  4661.4  506.48  4682.0  506.41
  4757.7  506.10  4771.0  505.44  4771.5  504.64  4777.5  504.64  4778.0  505.44
  4815.6  506.50  4841.9  506.01  4847.0  506.31  4913.3  505.97  5139.8  506.60
  5177.6  506.83  5192.2  507.42  5242.3  507.30  5247.6  507.69  5280.0  507.93
  5307.1  507.32  5318.0  508.45  5344.7  507.73  5388.8  508.87  5422.9  508.28
  5474.3  509.08  5479.5  508.54  5496.3  508.96  5575.4  508.33  5648.6  508.35
#Mann=4,-1,0
  4202.6    0.05       0  4771.0   0.035       0  4778.0    0.05       0
  5388.8     0.1       0
Bank Sta=4771,4778
Exp/Cntr=0.3,0.1

Type RM Length L Ch R = 1,7867,325,325,325
BEGIN DESCRIPTION:
UNT 110 in Lagunillas Cr Wtrshd 1.0
END DESCRIPTION:
XS GIS Cut Line= 4
      2036107.47     13514620.49      2036440.36     13514317.01
      2036502.73     13514124.13      2036374.57     13513624.48
#Sta/Elev= 30
  4399.8  508.76  4642.4  506.91  4664.0  507.92  4678.2  506.38  4706.6  505.75
  4862.9  505.54  4873.4  505.36  4880.1  504.15  4919.5  503.64  4968.0  504.40
  4989.0  503.47  4996.0  502.04  4996.5  501.24  5002.5  501.24  5003.0  502.04
  5008.2  503.32  5040.2  504.81  5072.7  504.77  5093.4  503.78  5106.5  504.90
  5147.3  503.14  5182.9  504.81  5289.5  505.29  5351.5  506.68  5386.8  506.33
  5403.1  507.11  5496.0  507.90  5503.9  507.08  5516.6  507.70  5568.8  507.64
#Mann=4,-1,0
  4399.8    0.05       0  4919.5     0.1       0  4996.0    0.07       0
  5003.0     0.1       0
Bank Sta=4996,5003
Exp/Cntr=0.3,0.1

Type RM Length L Ch R = 1,7542,255,255,255
BEGIN DESCRIPTION:
Mapping XS 9c8989ff
END DESCRIPTION:
XS GIS Cut Line= 4
      2036285.10     13515184.12      2036724.03     13514368.88
      2036772.86     13514274.48      2037161.67     13513309.54
#Sta/Elev= 30
  4006.5  515.11  4063.5  513.31  4167.3  512.10  4278.1  509.89  4413.2  509.22
  4730.4  504.00  4868.7  503.12  4899.9  504.00  4931.8  503.25  4981.8  503.86
  5000.4  501.34  5001.0  500.54  5007.6  500.54  5008.3  501.34  5010.3  502.65
  5029.0  503.32  5041.1  503.42  5061.4  502.42  5092.0  503.14  5168.8  503.33
  5199.8  504.17  5222.6  503.42  5241.3  504.79  5246.7  504.38  5617.3  506.56
  5783.8  507.98  5856.3  509.64  5926.6  510.25  6022.8  510.44  6079.0  511.50
#Mann=5,-1,0
  4006.5    0.05       0  5000.4    0.03       0  5008.3    0.05       0
  5029.0     0.1       0  5926.6    0.05       0
Bank Sta=5000.4,5008.3
Exp/Cntr=0.3,0.1

Type RM Length L Ch R = 1,7287,466,466,466
BEGIN DESCRIPTION:
Mapping XS 35a24f25
END DESCRIPTION:
XS GIS Cut Line= 4
      2036562.87     13514967.12      2036927.59     13514456.84
      2036987.27     13514402.59      2037526.42     13513625.96
#Sta/Elev= 30
  4326.4  510.25  4451.9  509.11  4859.1  502.32  4894.8  502.01  4931.3  503.15
  4951.7  503.28  4967.1  503.06  4988.7  501.86  4991.5  501.36  4992.2  500.56
  4998.8  500.56  4999.4  501.36  5009.7  502.32  5023.9  502.86  5044.3  502.93
  5074.0  502.05  5096.8  501.99  5116.6  502.22  5153.1  501.61  5238.3  503.12
  5333.4  504.05  5339.5  503.74  5476.6  505.24  5664.3  506.21  5885.2  508.79
  5907.8  509.30  5914.9  510.84  5921.0  510.18  5950.7  509.87  5979.7  510.34
#Mann=4,-1,0
  4326.4    0.05       0  4991.5    0.03       0  4999.4    0.05       0
  5096.8     0.1       0
Bank Sta=4991.5,4999.4
Exp/Cntr=0.3,0.1

Type RM Length L Ch R = 1,6821,324,324,324
BEGIN DESCRIPTION:
Mapping XS 92606cf2
END DESCRIPTION:
XS GIS Cut Line= 4
      2036897.11     13515231.83      2037341.00     13514766.09
      2037413.70     13514316.87      2037590.75     13513961.71
#Sta/Elev= 30
  4071.4  509.87  4081.7  509.40  4180.7  508.61  4251.5  507.42  4364.7  506.96
  4400.0  506.13  4711.4  502.65  4827.3  500.41  4878.0  501.66  4888.1  501.69
  4899.8  501.03  4928.6  501.12  4956.4  501.91  4961.5  501.15  4979.3  501.09
  4985.4  499.41  4986.1  498.61  4992.8  498.61  4993.5  499.41  5012.3  500.51
  5040.1  500.28  5151.6  502.10  5225.5  502.60  5253.5  503.36  5477.3  506.53
  5516.5  508.29  5522.0  510.58  5538.8  511.43  5561.2  511.18  5566.7  509.11
#Mann=4,-1,0
  4071.4    0.05       0  4985.4    0.03       0  4993.5    0.05       0
  5012.3     0.1       0
Bank Sta=4985.4,4993.5
Exp/Cntr=0.3,0.1