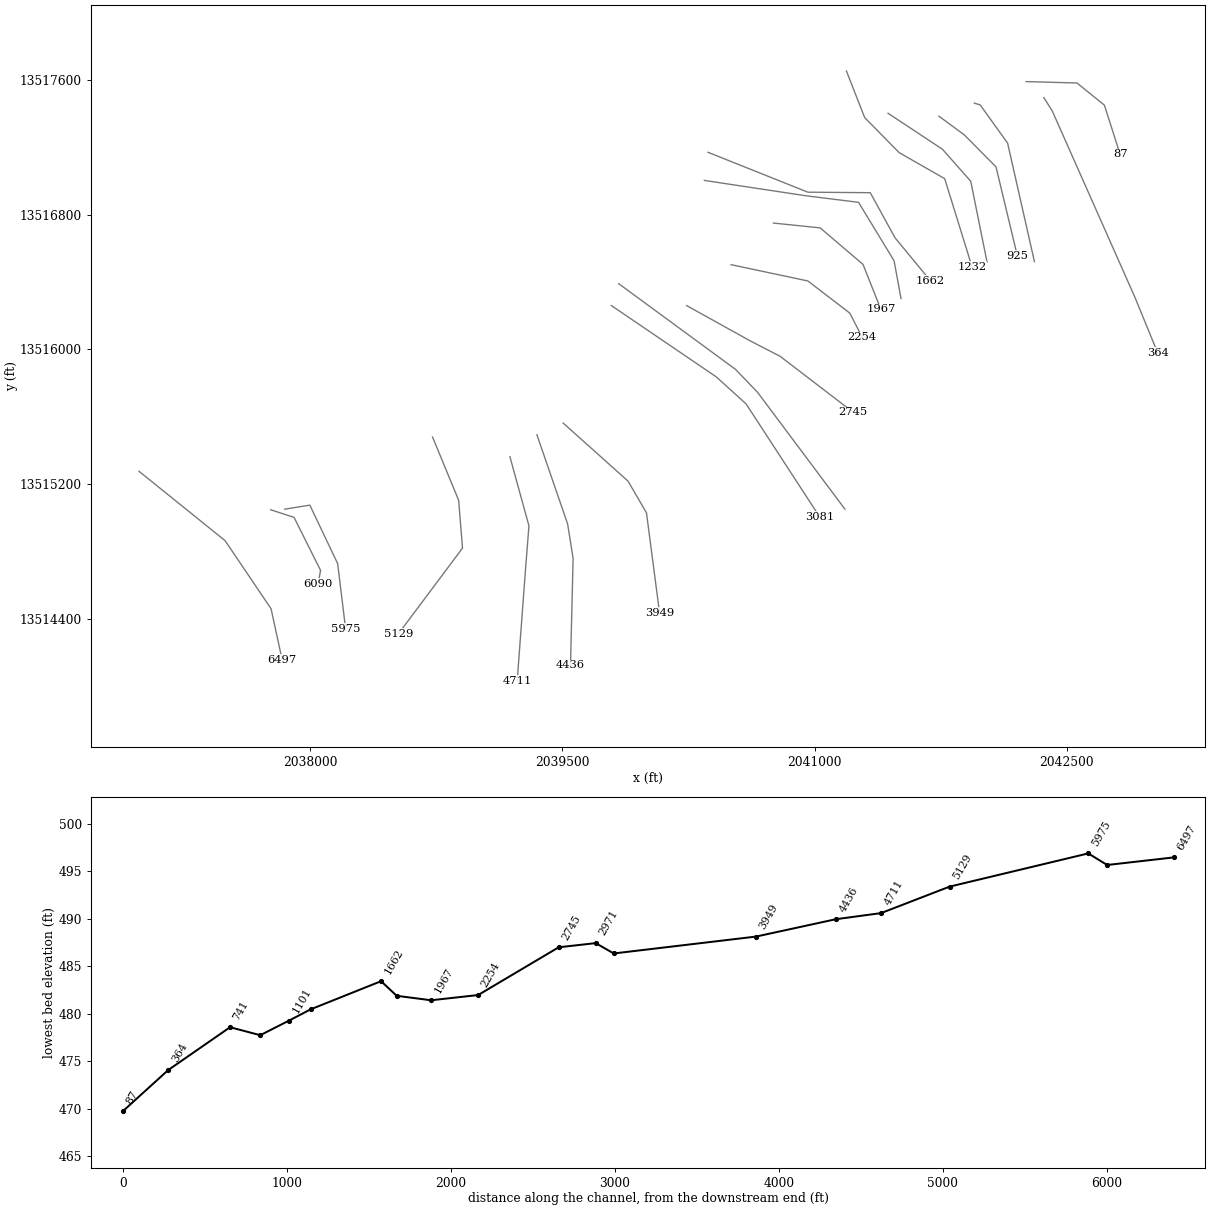
HEC-RAS study UNT 110 in Lagunillas Cr Wtrshd.prj: UNT 110 in Lagunillas Cr Wtrshd Base Level Engineering

--- UNT 110 in Lagunillas Cr Wtrshd.g01 (geometry) --- (continued)

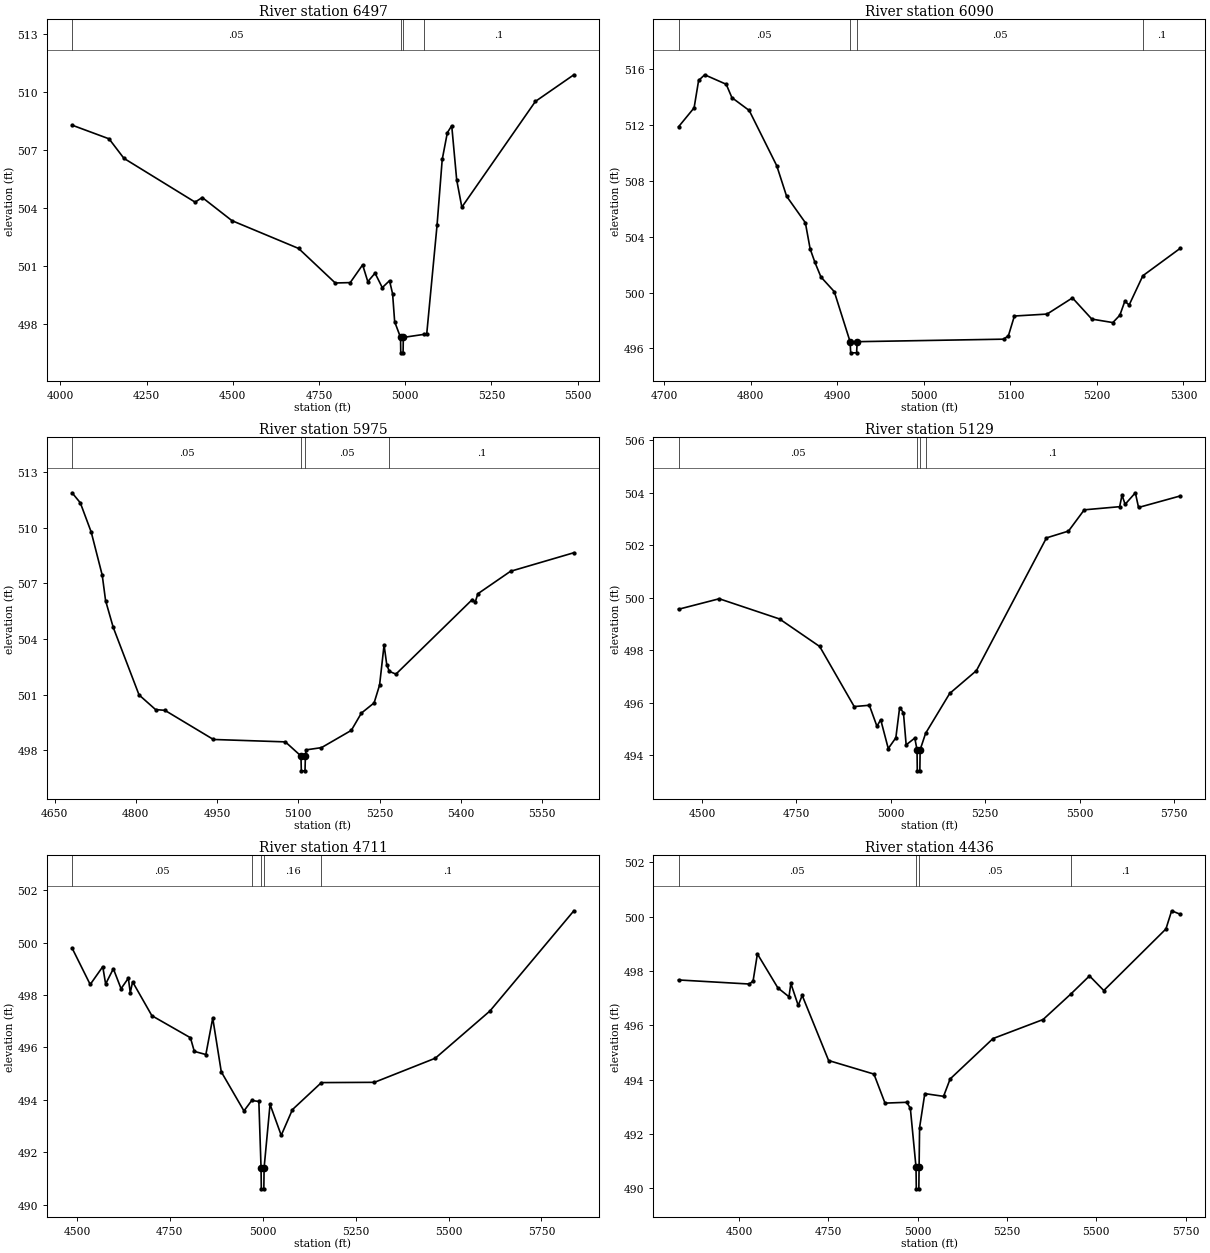
Type RM Length L Ch R = 1,6497,407,407,407
BEGIN DESCRIPTION:
Mapping XS 9b69a8e2
END DESCRIPTION:
XS GIS Cut Line= 4
      2036983.91     13515275.24      2037495.51     13514863.09
      2037768.95     13514458.15      2037834.58     13514155.47
#Sta/Elev= 30
  4034.0  508.28  4141.3  507.57  4184.4  506.56  4390.8  504.29  4411.6  504.53
  4497.7  503.33  4691.0  501.89  4797.3  500.10  4840.7  500.12  4876.7  501.04
  4891.7  500.17  4912.7  500.61  4933.7  499.86  4954.7  500.22  4963.6  499.54
  4969.6  498.09  4986.6  497.28  4987.3  496.48  4994.0  496.48  4994.7  497.28
  5055.8  497.44  5062.7  497.48  5092.5  503.09  5107.5  506.50  5122.4  507.89
  5135.1  508.25  5149.5  505.44  5164.4  504.03  5377.8  509.51  5489.3  510.89
#Mann=4,-1,0
  4034.0    0.05       0  4986.6    0.03       0  4994.7    0.05       0
  5055.8     0.1       0
Bank Sta=4986.6,4994.7
Exp/Cntr=0.3,0.1

Type RM Length L Ch R = 1,6090,115,115,115
BEGIN DESCRIPTION:
Mapping XS 13bef026
END DESCRIPTION:
XS GIS Cut Line= 5
      2037766.33     13515046.69      2037905.67     13515001.12
      2038063.22     13514686.01      2038048.90     13514609.19
      2038047.60     13514606.58
#Sta/Elev= 30
  4716.4  511.89  4734.4  513.25  4739.6  515.21  4746.6  515.62  4771.5  514.94
  4778.1  513.98  4798.1  513.06  4829.9  509.10  4841.3  506.91  4863.0  505.01
  4868.5  503.14  4874.1  502.16  4881.0  501.12  4896.4  500.07  4914.7  496.48
  4915.4  495.68  4922.2  495.68  4922.9  496.48  5092.1  496.66  5097.7  496.91
  5104.6  498.32  5142.4  498.46  5171.7  499.62  5194.1  498.10  5218.4  497.85
  5226.5  498.38  5232.2  499.37  5237.3  499.12  5253.1  501.21  5296.4  503.18
#Mann=4,-1,0
  4716.4    0.05       0  4914.7    0.03       0  4922.9    0.05       0
  5253.1     0.1       0
Bank Sta=4914.7,4922.9
Exp/Cntr=0.3,0.1

Type RM Length L Ch R = 1,5975,846,846,846
BEGIN DESCRIPTION:
Mapping XS 451d43c0
END DESCRIPTION:
XS GIS Cut Line= 4
      2037850.00     13515050.00      2037999.42     13515074.03
      2038164.78     13514726.38      2038212.05     13514338.86
#Sta/Elev= 30
  4682.2  511.88  4697.4  511.34  4717.6  509.76  4737.9  507.44  4744.1  506.07
  4758.2  504.63  4805.9  500.99  4836.4  500.20  4853.6  500.16  4943.2  498.59
  5076.1  498.46  5104.9  497.70  5105.6  496.90  5112.4  496.90  5113.1  497.70
  5114.5  498.03  5142.8  498.15  5197.9  499.08  5216.5  500.01  5240.0  500.56
  5250.1  501.52  5258.4  503.68  5263.4  502.61  5268.1  502.26  5280.3  502.11
  5421.4  506.13  5426.6  505.98  5431.6  506.44  5491.9  507.65  5608.9  508.65
#Mann=4,-1,0
  4682.2    0.05       0  5104.9    0.03       0  5113.1    0.05       0
  5268.1     0.1       0
Bank Sta=5104.9,5113.1
Exp/Cntr=0.3,0.1

Type RM Length L Ch R = 1,5129,418,418,418
BEGIN DESCRIPTION:
Mapping XS 0f5f8751
END DESCRIPTION:
XS GIS Cut Line= 4
      2038728.70     13515479.22      2038884.18     13515102.90
      2038906.97     13514818.61      2038525.67     13514308.69
#Sta/Elev= 30
  4437.7  499.56  4545.5  499.96  4705.2  499.19  4811.6  498.14  4903.0  495.85
  4943.1  495.90  4963.2  495.10  4973.2  495.35  4993.2  494.25  5013.3  494.66
  5023.3  495.81  5033.4  495.62  5040.6  494.39  5063.5  494.65  5069.4  494.20
  5070.1  493.40  5076.9  493.40  5077.6  494.20  5092.1  494.83  5155.9  496.35
  5226.7  497.22  5412.2  502.28  5470.6  502.54  5512.3  503.35  5606.1  503.47
  5612.3  503.91  5620.6  503.56  5647.7  504.00  5656.1  503.44  5766.8  503.88
#Mann=4,-1,0
  4437.7    0.05       0  5069.4    0.03       0  5077.6    0.05       0
  5092.1     0.1       0
Bank Sta=5069.4,5077.6
Exp/Cntr=0.3,0.1

Type RM Length L Ch R = 1,4711,275,275,275
BEGIN DESCRIPTION:
Mapping XS 72c90a57
END DESCRIPTION:
XS GIS Cut Line= 4
      2039188.75     13515362.07      2039301.94     13514950.99
      2039282.41     13514703.59      2039232.17     13514029.81
#Sta/Elev= 30
  4486.9  499.79  4535.7  498.40  4569.5  499.08  4577.2  498.42  4598.0  499.00
  4618.7  498.24  4638.3  498.64  4643.5  498.09  4649.8  498.50  4701.7  497.21
  4805.4  496.37  4815.8  495.85  4846.9  495.73  4865.4  497.12  4888.4  495.07
  4949.4  493.58  4970.4  493.98  4989.5  493.94  4995.4  491.41  4996.1  490.61
  5002.9  490.61  5003.6  491.41  5019.6  493.83  5049.7  492.65  5079.8  493.63
  5157.8  494.66  5300.4  494.67  5464.3  495.59  5611.3  497.39  5837.1  501.21
#Mann=5,-1,0
  4486.9    0.05       0  4970.4    0.16       0  4995.4    0.07       0
  5003.6    0.16       0  5157.8     0.1       0
Bank Sta=4995.4,5003.6
Exp/Cntr=0.3,0.1

Type RM Length L Ch R = 1,4436,487,487,487
BEGIN DESCRIPTION:
Mapping XS b7bb120f
END DESCRIPTION:
XS GIS Cut Line= 4
      2039349.33     13515492.32      2039531.97     13514961.84
      2039564.52     13514757.84      2039548.99     13514120.75
#Sta/Elev= 30
  4330.3  497.67  4528.4  497.52  4539.0  497.63  4551.1  498.63  4608.3  497.38
  4639.5  497.05  4644.8  497.54  4665.4  496.73  4676.5  497.10  4750.5  494.70
  4877.4  494.20  4908.4  493.13  4969.2  493.16  4979.3  492.94  4995.2  490.77
  4996.0  489.97  5003.1  489.97  5003.8  490.77  5005.2  492.23  5019.8  493.48
  5072.3  493.38  5090.7  494.02  5210.8  495.51  5350.8  496.21  5428.5  497.15
  5480.9  497.82  5520.9  497.28  5694.9  499.55  5710.9  500.22  5735.2  500.09
#Mann=4,-1,0
  4330.3    0.05       0  4995.2    0.03       0  5003.8    0.05       0
  5428.5     0.1       0
Bank Sta=4995.2,5003.8
Exp/Cntr=0.3,0.1

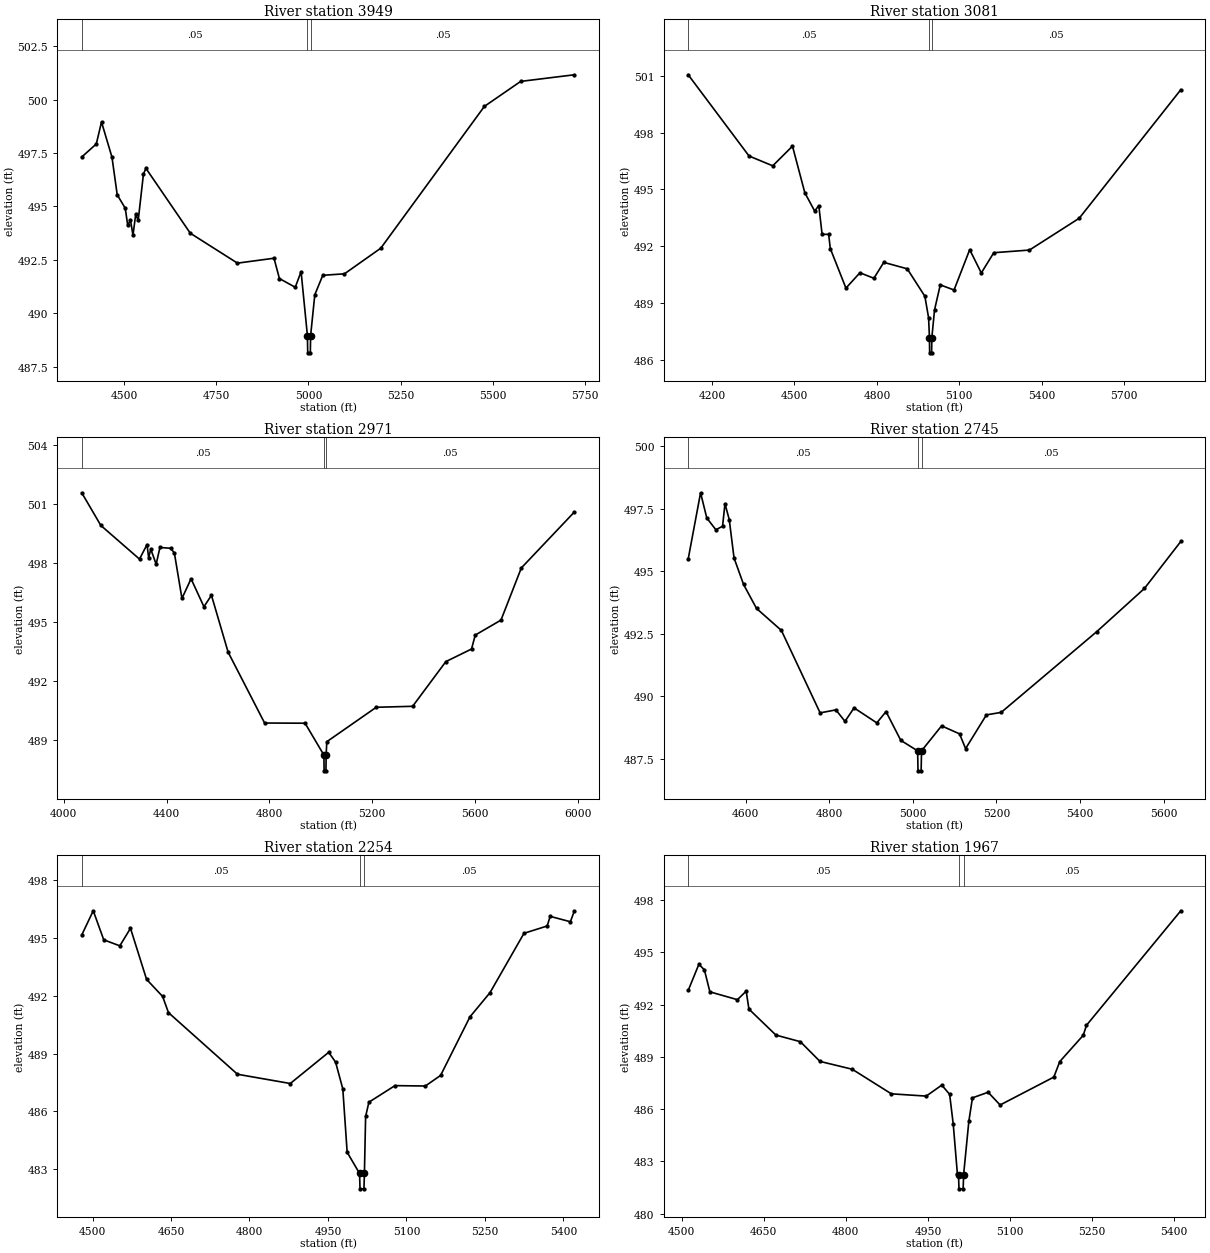
Type RM Length L Ch R = 1,3949,868,868,868
BEGIN DESCRIPTION:
Mapping XS a01a9b3f
END DESCRIPTION:
XS GIS Cut Line= 4
      2039505.56     13515561.74      2039891.13     13515216.83
      2040000.72     13515028.03      2040078.51     13514433.23
#Sta/Elev= 30
  4385.4  497.31  4424.9  497.92  4439.0  498.95  4467.4  497.30  4481.6  495.54
  4503.4  494.91  4510.1  494.11  4517.6  494.35  4524.3  493.65  4531.8  494.63
  4538.5  494.34  4552.7  496.51  4559.4  496.78  4679.8  493.74  4807.6  492.34
  4906.7  492.57  4921.3  491.62  4964.3  491.21  4980.1  491.94  4997.3  488.94
  4998.1  488.14  5005.2  488.14  5005.9  488.94  5017.3  490.86  5038.9  491.77
  5097.7  491.84  5196.2  493.04  5477.1  499.68  5575.5  500.85  5720.9  501.16
#Mann=3,-1,0
  4385.4    0.05       0  4997.3    0.03       0  5005.9    0.05       0
Bank Sta=4997.3,5005.9
Exp/Cntr=0.3,0.1

Type RM Length L Ch R = 1,3081,110,110,110
BEGIN DESCRIPTION:
Mapping XS ca63850a
END DESCRIPTION:
XS GIS Cut Line= 4
      2039792.02     13516260.52      2040415.87     13515836.40
      2040592.95     13515675.81      2041029.01     13515006.19
#Sta/Elev= 30
  4113.4  501.05  4334.7  496.76  4421.0  496.24  4492.9  497.28  4537.7  494.82
  4573.6  493.85  4588.6  494.14  4600.7  492.62  4624.5  492.62  4630.5  491.87
  4687.4  489.78  4738.3  490.59  4789.2  490.30  4825.1  491.14  4910.4  490.80
  4974.6  489.35  4988.2  488.21  4991.3  487.16  4992.0  486.36  4999.2  486.36
  5000.0  487.16  5009.8  488.63  5030.7  489.95  5080.8  489.68  5137.8  491.81
  5180.0  490.58  5225.4  491.65  5355.2  491.79  5536.3  493.47  5905.9  500.26
#Mann=3,-1,0
  4113.4    0.05       0  4991.3    0.03       0  5000.0    0.05       0
Bank Sta=4991.3,5000
Exp/Cntr=0.3,0.1

Type RM Length L Ch R = 1,2971,226,226,226
BEGIN DESCRIPTION:
Mapping XS 885c0ef1
END DESCRIPTION:
XS GIS Cut Line= 4
      2039835.47     13516390.70      2040529.58     13515881.54
      2040660.66     13515745.26      2041180.31     13515050.40
#Sta/Elev= 30
  4069.7  501.58  4144.1  499.92  4294.6  498.21  4323.9  498.95  4330.1  498.28
  4338.6  498.71  4359.4  497.95  4374.1  498.80  4416.4  498.76  4430.5  498.51
  4459.8  496.21  4495.3  497.21  4545.4  495.79  4574.7  496.37  4639.6  493.48
  4781.6  489.88  4939.1  489.87  5012.5  488.25  5013.2  487.45  5020.4  487.45
  5021.2  488.25  5023.7  488.93  5216.2  490.68  5357.9  490.73  5487.1  493.00
  5587.1  493.64  5601.7  494.35  5701.8  495.11  5781.0  497.76  5987.3  500.60
#Mann=3,-1,0
  4069.7    0.05       0  5012.5    0.03       0  5021.2    0.05       0
Bank Sta=5012.5,5021.2
Exp/Cntr=0.3,0.1

Type RM Length L Ch R = 1,2745,491,491,491
BEGIN DESCRIPTION:
Mapping XS 20044b50
END DESCRIPTION:
XS GIS Cut Line= 4
      2040239.12     13516260.49      2040613.79     13516052.55
      2040795.21     13515958.80      2041228.68     13515626.82
#Sta/Elev= 30
  4462.3  495.49  4491.9  498.14  4506.8  497.13  4528.5  496.66  4544.5  496.80
  4550.3  497.70  4560.5  497.07  4572.0  495.53  4594.8  494.47  4625.8  493.51
  4685.3  492.63  4778.0  489.33  4815.7  489.45  4837.5  488.99  4859.2  489.53
  4913.6  488.93  4935.7  489.38  4971.0  488.23  5011.3  487.81  5012.2  487.01
  5019.7  487.01  5020.6  487.81  5068.6  488.81  5111.6  488.49  5126.1  487.90
  5175.9  489.25  5211.3  489.35  5439.8  492.58  5554.0  494.31  5641.0  496.19
#Mann=3,-1,0
  4462.3    0.05       0  5011.3    0.03       0  5020.6    0.05       0
Bank Sta=5011.3,5020.6
Exp/Cntr=0.3,0.1

Type RM Length L Ch R = 1,2254,287,287,287
BEGIN DESCRIPTION:
Mapping XS 6ec32c8d
END DESCRIPTION:
XS GIS Cut Line= 4
      2040503.82     13516503.57      2040960.14     13516406.71
      2041209.27     13516215.74      2041283.05     13516072.52
#Sta/Elev= 30
  4479.4  495.16  4501.4  496.42  4521.5  494.91  4552.2  494.60  4572.6  495.51
  4603.3  492.86  4634.0  491.97  4645.2  491.13  4777.1  487.93  4878.0  487.45
  4951.4  489.07  4964.6  488.56  4978.4  487.17  4986.7  483.88  5010.4  482.78
  5011.3  481.98  5018.8  481.98  5019.7  482.78  5022.0  485.74  5028.3  486.48
  5078.1  487.34  5136.2  487.32  5165.3  487.87  5221.4  490.91  5259.8  492.17
  5324.7  495.25  5369.0  495.63  5374.7  496.13  5413.4  495.85  5420.9  496.41
#Mann=3,-1,0
  4479.4    0.05       0  5010.4    0.03       0  5019.7    0.05       0
Bank Sta=5010.4,5019.7
Exp/Cntr=0.3,0.1

Type RM Length L Ch R = 1,1967,210,210,210
BEGIN DESCRIPTION:
Mapping XS 50734680
END DESCRIPTION:
XS GIS Cut Line= 4
      2040755.60     13516750.95      2041033.23     13516722.34
      2041288.09     13516504.98      2041393.36     13516239.44
#Sta/Elev= 30
  4512.2  492.81  4531.7  494.31  4541.8  493.99  4551.8  492.73  4602.1  492.28
  4618.1  492.77  4623.1  491.74  4672.4  490.25  4717.1  489.87  4752.9  488.74
  4811.8  488.29  4883.2  486.88  4946.9  486.75  4975.4  487.38  4989.7  486.85
  4996.3  485.14  5003.9  482.27  5005.9  482.23  5006.8  481.43  5014.4  481.43
  5015.2  482.23  5024.8  485.31  5031.4  486.65  5060.0  486.97  5081.9  486.24
  5180.0  487.84  5190.9  488.73  5233.8  490.24  5239.6  490.81  5411.9  497.38
#Mann=3,-1,0
  4512.2    0.05       0  5005.9    0.03       0  5015.2    0.05       0
Bank Sta=5005.9,5015.2
Exp/Cntr=0.3,0.1

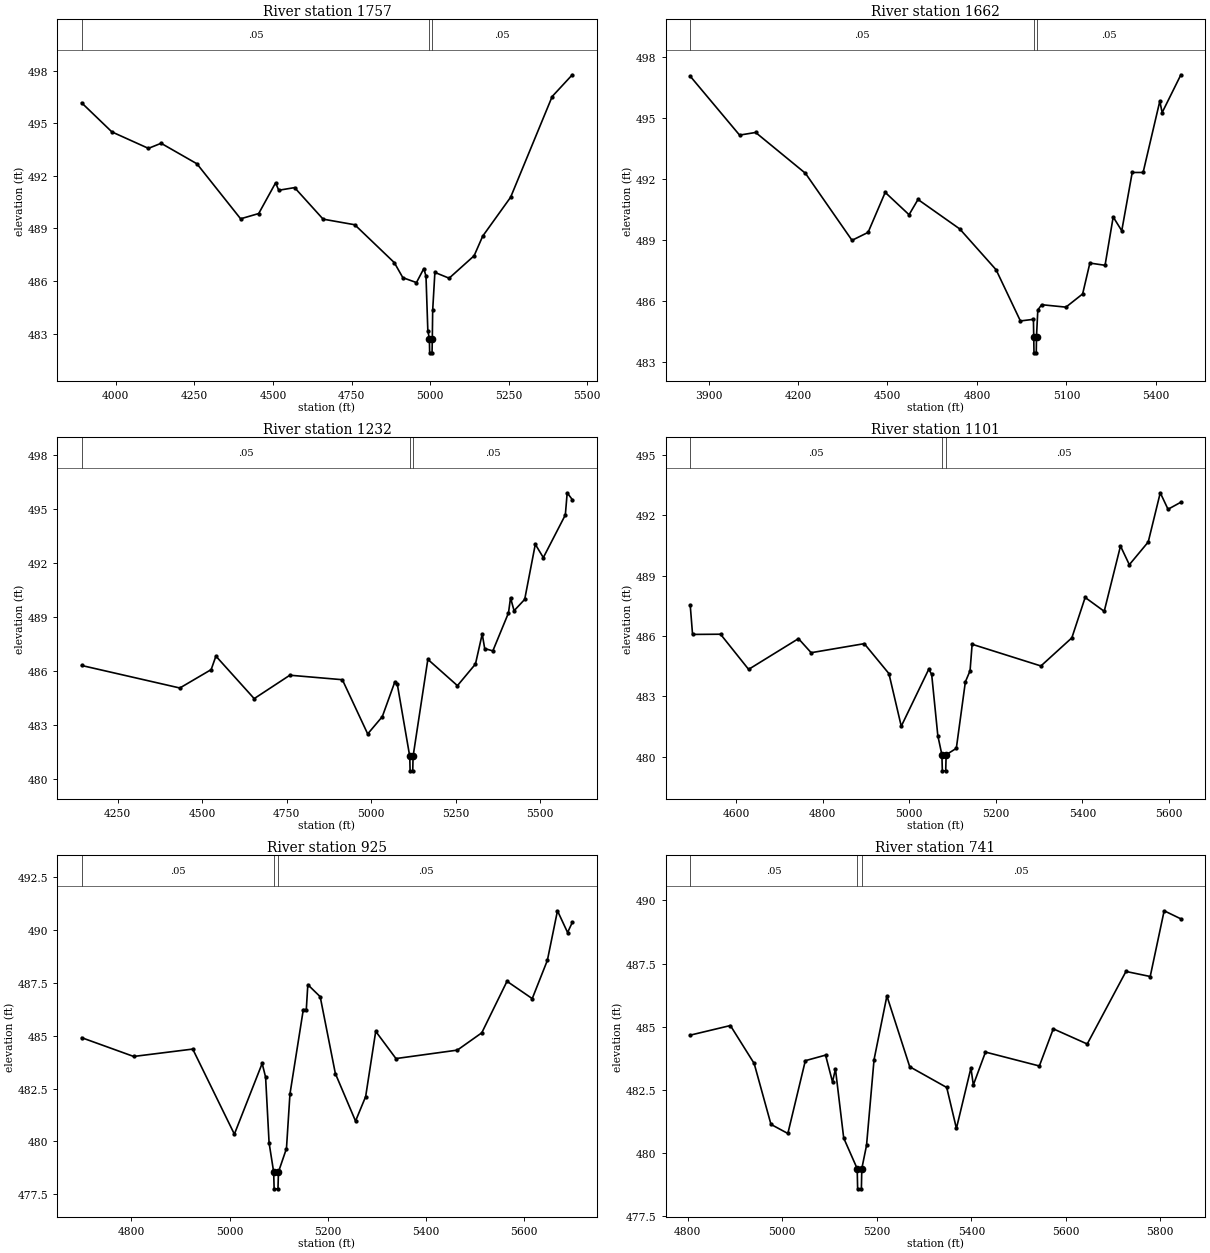
Type RM Length L Ch R = 1,1757,95,95,95
BEGIN DESCRIPTION:
Mapping XS 5084d7f1
END DESCRIPTION:
XS GIS Cut Line= 5
      2040344.99     13517004.40      2040948.30     13516913.25
      2041261.23     13516874.19      2041472.66     13516526.62
      2041513.89     13516302.02
#Sta/Elev= 30
  3891.6  496.17  3987.8  494.51  4104.0  493.57  4144.4  493.86  4258.3  492.69
  4397.3  489.55  4454.8  489.85  4508.5  491.60  4518.6  491.18  4569.0  491.33
  4659.7  489.53  4760.4  489.21  4886.1  487.05  4913.3  486.19  4956.6  485.91
  4980.0  486.71  4986.9  486.28  4992.8  483.16  4997.7  482.70  4998.6  481.90
  5006.2  481.90  5007.0  482.70  5008.2  484.33  5015.2  486.49  5060.5  486.16
  5140.0  487.44  5167.3  488.56  5256.1  490.78  5388.3  496.53  5452.3  497.77
#Mann=3,-1,0
  3891.6    0.05       0  4997.7    0.03       0  5007.0    0.05       0
Bank Sta=4997.7,5007
Exp/Cntr=0.3,0.1

Type RM Length L Ch R = 1,1662,430,430,430
BEGIN DESCRIPTION:
Mapping XS d19d5c39
END DESCRIPTION:
XS GIS Cut Line= 5
      2040366.65     13517171.52      2040959.88     13516934.54
      2041331.11     13516931.48      2041478.24     13516663.25
      2041687.93     13516409.07
#Sta/Elev= 30
  3838.4  497.06  4003.9  494.16  4057.8  494.29  4224.8  492.28  4381.0  488.98
  4434.9  489.37  4492.3  491.34  4572.3  490.24  4602.3  490.99  4742.3  489.54
  4864.2  487.53  4945.7  485.01  4989.4  485.09  4990.4  484.24  4991.3  483.44
  4998.9  483.44  4999.7  484.24  5004.1  485.55  5016.9  485.81  5098.4  485.69
  5154.4  486.34  5178.7  487.86  5229.6  487.75  5256.9  490.13  5285.6  489.45
  5320.7  492.32  5357.2  492.32  5413.2  495.83  5421.1  495.27  5483.9  497.13
#Mann=3,-1,0
  3838.4    0.05       0  4990.4    0.03       0  4999.7    0.05       0
Bank Sta=4990.4,4999.7
Exp/Cntr=0.3,0.1

Type RM Length L Ch R = 1,1232,131,131,131
BEGIN DESCRIPTION:
Mapping XS 6158ee8e
END DESCRIPTION:
XS GIS Cut Line= 5
      2041189.19     13517655.43      2041297.69     13517378.10
      2041502.55     13517169.77      2041773.42     13517015.05
      2041936.15     13516490.54
#Sta/Elev= 30
  4143.6  486.32  4434.0  485.07  4526.6  486.09  4540.7  486.84  4653.9  484.48
  4759.4  485.78  4914.7  485.53  4989.6  482.52  5032.8  483.48  5069.7  485.40
  5077.0  485.30  5114.0  481.27  5115.0  480.47  5122.8  480.47  5123.8  481.27
  5167.5  486.66  5255.0  485.20  5308.3  486.40  5328.3  488.07  5335.6  487.26
  5359.7  487.13  5406.0  489.24  5412.0  490.08  5422.5  489.36  5453.9  489.99
  5485.3  493.05  5509.0  492.31  5574.1  494.68  5579.6  495.91  5594.7  495.53
#Mann=3,-1,0
  4143.6    0.05       0  5114.0    0.03       0  5123.8    0.05       0
Bank Sta=5114,5123.8
Exp/Cntr=0.3,0.1

Type RM Length L Ch R = 1,1101,176,176,176
BEGIN DESCRIPTION:
Mapping XS a610955b
END DESCRIPTION:
XS GIS Cut Line= 4
      2041436.59     13517403.70      2041760.40     13517189.53
      2041928.37     13516999.42      2042025.36     13516518.31
#Sta/Elev= 30
  4494.6  487.54  4500.0  486.08  4564.6  486.09  4629.4  484.34  4744.5  485.87
  4773.8  485.17  4896.4  485.62  4953.3  484.13  4981.8  481.51  5045.3  484.35
  5052.0  484.09  5066.2  481.04  5075.6  480.09  5076.6  479.29  5084.4  479.29
  5085.4  480.09  5108.9  480.41  5129.8  483.72  5140.6  484.27  5145.4  485.59
  5304.2  484.51  5375.6  485.91  5406.3  487.92  5450.3  487.23  5487.9  490.48
  5508.3  489.55  5551.9  490.68  5579.7  493.13  5597.6  492.31  5627.3  492.66
#Mann=3,-1,0
  4494.6    0.05       0  5075.6    0.03       0  5085.4    0.05       0
Bank Sta=5075.6,5085.4
Exp/Cntr=0.3,0.1

Type RM Length L Ch R = 1,925,184,184,184
BEGIN DESCRIPTION:
Mapping XS 89fb6ec1
END DESCRIPTION:
XS GIS Cut Line= 4
      2041739.29     13517386.31      2041890.61     13517274.60
      2042078.56     13517085.00      2042205.40     13516555.64
#Sta/Elev= 30
  4698.6  484.91  4804.6  484.02  4924.9  484.37  5009.7  480.34  5066.3  483.69
  5073.3  483.04  5080.4  479.93  5089.7  478.55  5090.7  477.75  5098.5  477.75
  5099.5  478.55  5115.8  479.66  5122.9  482.24  5150.1  486.24  5156.2  486.24
  5159.3  487.42  5184.5  486.85  5215.4  483.21  5256.5  480.96  5277.1  482.12
  5297.6  485.21  5338.8  483.92  5463.8  484.32  5513.6  485.14  5565.0  487.58
  5616.4  486.76  5647.2  488.57  5667.8  490.92  5688.4  489.89  5698.0  490.37
#Mann=3,-1,0
  4698.6    0.05       0  5089.7    0.03       0  5099.5    0.05       0
Bank Sta=5089.7,5099.5
Exp/Cntr=0.3,0.1

Type RM Length L Ch R = 1,741,377,377,377
BEGIN DESCRIPTION:
Mapping XS 589e3b2c
END DESCRIPTION:
XS GIS Cut Line= 4
      2041949.61     13517463.84      2041984.36     13517453.42
      2042147.55     13517225.99      2042306.98     13516521.70
#Sta/Elev= 30
  4805.1  484.67  4890.1  485.05  4940.4  483.55  4976.0  481.14  5011.7  480.78
  5048.7  483.66  5091.5  483.88  5106.2  482.82  5112.4  483.33  5129.9  480.60
  5158.4  479.39  5159.4  478.59  5167.3  478.59  5168.2  479.39  5178.2  480.31
  5194.1  483.70  5221.3  486.22  5269.6  483.42  5347.9  482.60  5368.4  480.98
  5399.1  483.37  5404.2  482.70  5429.9  484.00  5543.9  483.45  5573.4  484.92
  5645.2  484.32  5727.2  487.19  5778.5  486.99  5808.0  489.59  5843.4  489.27
#Mann=3,-1,0
  4805.1    0.05       0  5158.4    0.03       0  5168.2    0.05       0
Bank Sta=5158.4,5168.2
Exp/Cntr=0.3,0.1

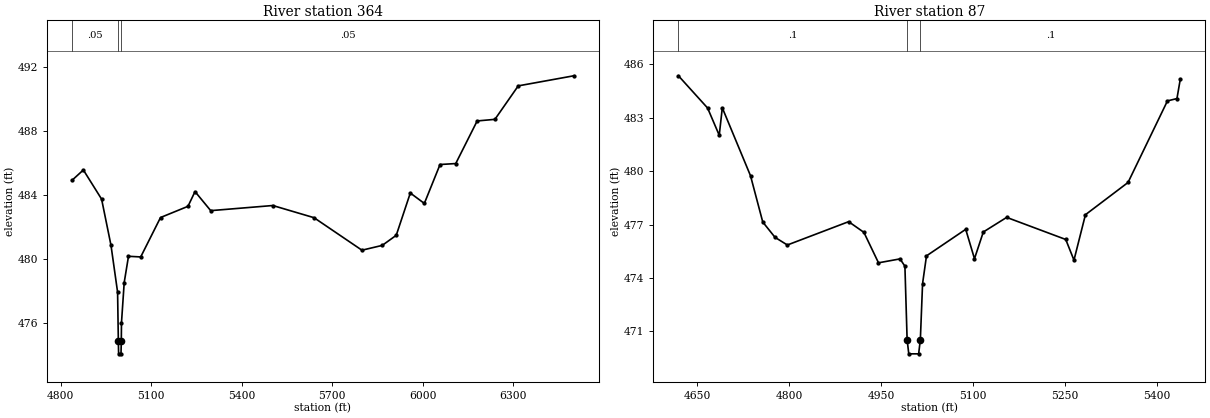
Type RM Length L Ch R = 1,364,277,277,277
BEGIN DESCRIPTION:
Mapping XS 8ae9b624
END DESCRIPTION:
XS GIS Cut Line= 4
      2042362.85     13517496.78      2042413.18     13517416.96
      2042904.50     13516309.32      2043039.72     13515979.33
#Sta/Elev= 30
  4837.4  484.91  4875.2  485.56  4935.6  483.74  4966.7  480.86  4988.6  477.93
  4991.1  474.88  4992.0  474.08  4999.9  474.08  5000.9  474.88  5001.5  476.02
  5010.5  478.53  5024.7  480.17  5065.2  480.13  5130.8  482.59  5221.8  483.29
  5245.1  484.21  5297.1  483.02  5502.8  483.34  5639.3  482.58  5798.1  480.55
  5865.2  480.85  5911.7  481.48  5958.3  484.12  6004.8  483.47  6056.8  485.90
  6108.8  485.96  6179.8  488.62  6238.6  488.72  6315.9  490.81  6500.1  491.44
#Mann=3,-1,0
  4837.4    0.05       0  4991.1    0.03       0  5000.9    0.05       0
Bank Sta=4991.1,5000.9
Exp/Cntr=0.3,0.1

Type RM Length L Ch R = 1,87,0,0,0
BEGIN DESCRIPTION:
UNT 110 in Lagunillas Cr Wtrshd 3.0
END DESCRIPTION:
XS GIS Cut Line= 4
      2042257.42     13517591.94      2042559.88     13517583.62
      2042722.64     13517452.11      2042816.36     13517159.80
#Sta/Elev= 30
  4619.2  485.35  4666.8  483.54  4685.8  482.01  4690.8  483.55  4736.8  479.74
  4756.8  477.14  4776.8  476.28  4796.9  475.85  4896.9  477.16  4921.8  476.56
  4945.6  474.85  4980.7  475.07  4988.7  474.66  4992.3  470.54  4995.0  469.74
  5011.1  469.74  5013.9  470.54  5017.5  473.68  5023.9  475.24  5087.9  476.73
  5102.2  475.08  5116.6  476.58  5154.7  477.40  5251.1  476.16  5264.5  475.00
  5283.2  477.55  5352.7  479.36  5417.0  483.94  5432.5  484.07  5438.0  485.17
#Mann=3,-1,0
  4619.2     0.1       0  4992.3    0.07       0  5013.9     0.1       0
Bank Sta=4992.3,5013.9
Exp/Cntr=0.3,0.1

Chan Stop Cuts=-1