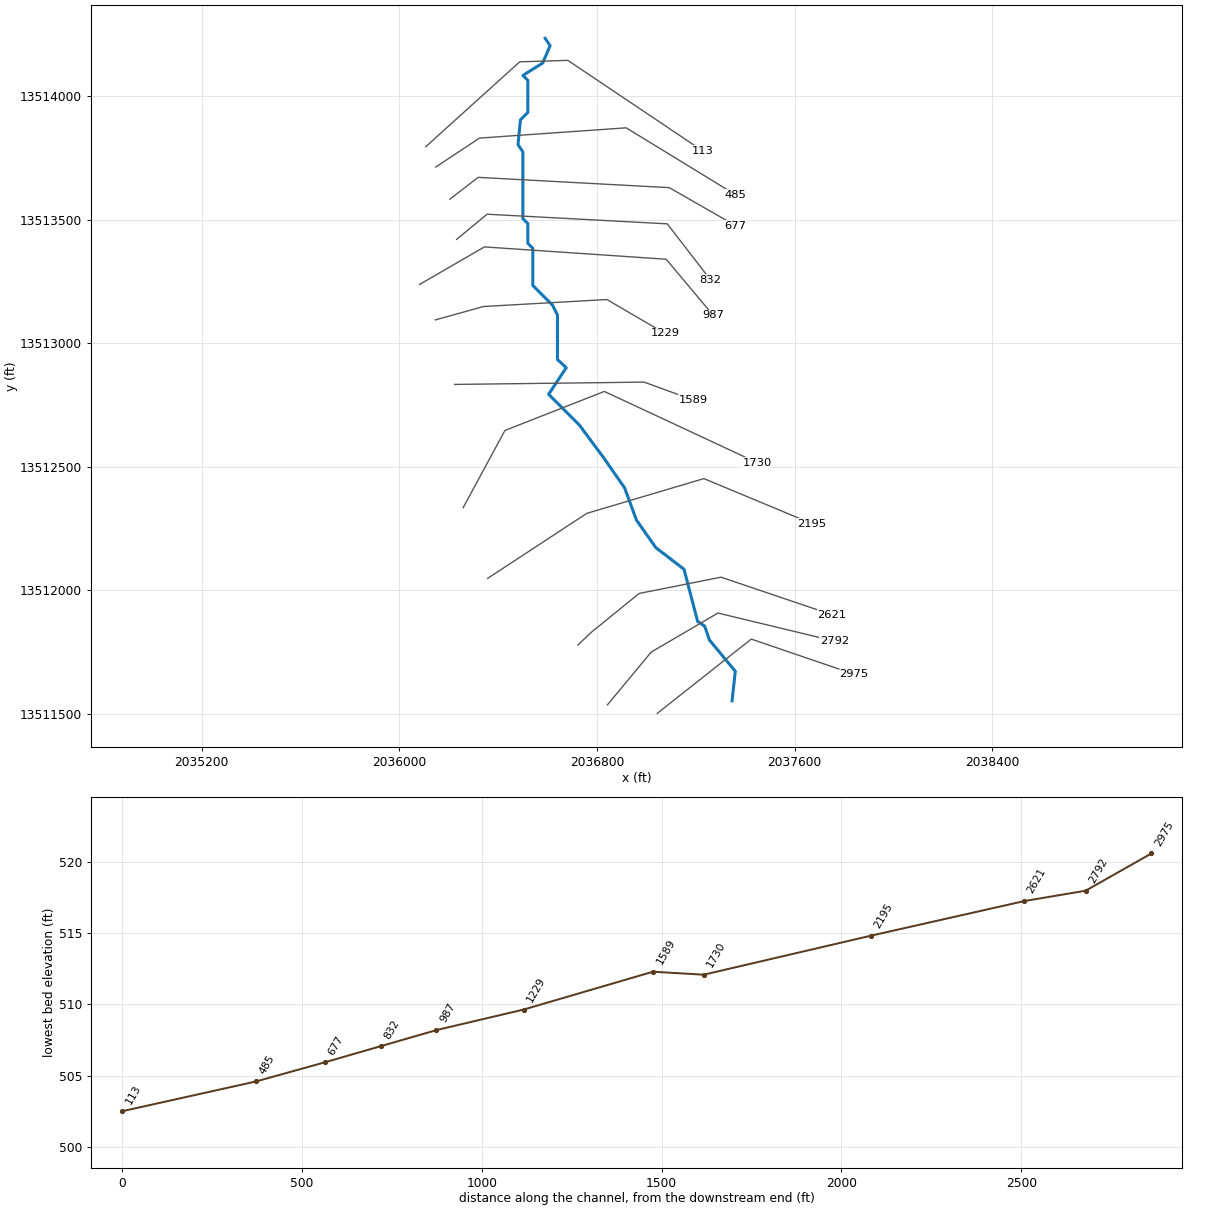
--- UNT 113 in Lagunillas Cr Wtrshd.prj (project) ---

Proj Title=UNT 113 in Lagunillas Cr Wtrshd Base Level Engineering
Current Plan=p01
Default Exp/Contr=0.3,0.1
English Units
Geom File=g01
Flow File=f01
Plan File=p01
BEGIN DESCRIPTION:
UNT 113 in Lagunillas Cr Wtrshd
END DESCRIPTION:

--- UNT 113 in Lagunillas Cr Wtrshd.p01 (plan) ---

Plan Title=Multiple Run
Short Identifier=Multiple
Geom File=g01
Flow File=f01
Subcritical Flow
K Sum by GR= 0
Std Step Tol= 0.01
Critical Tol= 0.01
Num of Std Step Trials= 20
Max Error Tol= 0.3
Flow Tol Ratio= 0.001
Split Flow NTrial= 30
Split Flow Tol= 0.02
Split Flow Ratio= 0.02
Log Output Level= 0
Friction Slope Method= 1
Unsteady Friction Slope Method= 2
Unsteady Bridges Friction Slope Method= 1
Parabolic Critical Depth
Global Vel Dist=  1 , 1 , 1
Global Log Level= 0
CheckData=True
Encroach Param= -1, 0, 0, 0
BEGIN DESCRIPTION:
Multiple Run
END DESCRIPTION:

--- UNT 113 in Lagunillas Cr Wtrshd.f01 (steady flow) ---

Flow Title=Multiple
Number of Profiles=7
Profile Names=10-year,25-year,50-year,1pct_min,100-year,1pct_plu,500-year
River Rch & RM= UNT 113 in Lagun,Reach-1,2975
     101     133     157      93     187     372     265
Boundary for River Rch & Prof#=UNT 113 in Lagun,Reach-1,1
Up Type=0
Dn Type=3
Dn Slope=0.005
Boundary for River Rch & Prof#=UNT 113 in Lagun,Reach-1,2
Up Type=0
Dn Type=3
Dn Slope=0.005
Boundary for River Rch & Prof#=UNT 113 in Lagun,Reach-1,3
Up Type=0
Dn Type=3
Dn Slope=0.005
Boundary for River Rch & Prof#=UNT 113 in Lagun,Reach-1,4
Up Type=0
Dn Type=3
Dn Slope=0.005
Boundary for River Rch & Prof#=UNT 113 in Lagun,Reach-1,5
Up Type=0
Dn Type=3
Dn Slope=0.005
Boundary for River Rch & Prof#=UNT 113 in Lagun,Reach-1,6
Up Type=0
Dn Type=3
Dn Slope=0.005
Boundary for River Rch & Prof#=UNT 113 in Lagun,Reach-1,7
Up Type=0
Dn Type=3
Dn Slope=0.005

--- UNT 113 in Lagunillas Cr Wtrshd.g01 (geometry) ---

Geom Title=Existing Conditions

River Reach=UNT 113 in Lagun,Reach-1
Reach XY= 30
      2037347.28     13511553.14      2037360.30     13511672.94
      2037256.13     13511798.80      2037236.18     13511855.78
      2037207.71     13511875.23      2037152.85     13512085.64
      2037038.96     13512173.14      2036960.49     13512284.25
      2036912.57     13512414.81      2036828.54     13512535.64
      2036728.54     13512670.37      2036604.93     13512793.98
      2036676.15     13512901.48      2036640.80     13512934.54
      2036640.80     13513114.54      2036620.80     13513154.54
      2036540.80     13513234.54      2036540.80     13513384.54
      2036520.80     13513404.54      2036520.80     13513484.54
      2036500.80     13513504.54      2036500.80     13513774.54
      2036480.80     13513804.54      2036490.80     13513904.54
      2036520.80     13513934.54      2036520.80     13514064.54
      2036500.80     13514084.54      2036580.80     13514134.54
      2036610.80     13514204.54      2036590.80     13514234.54

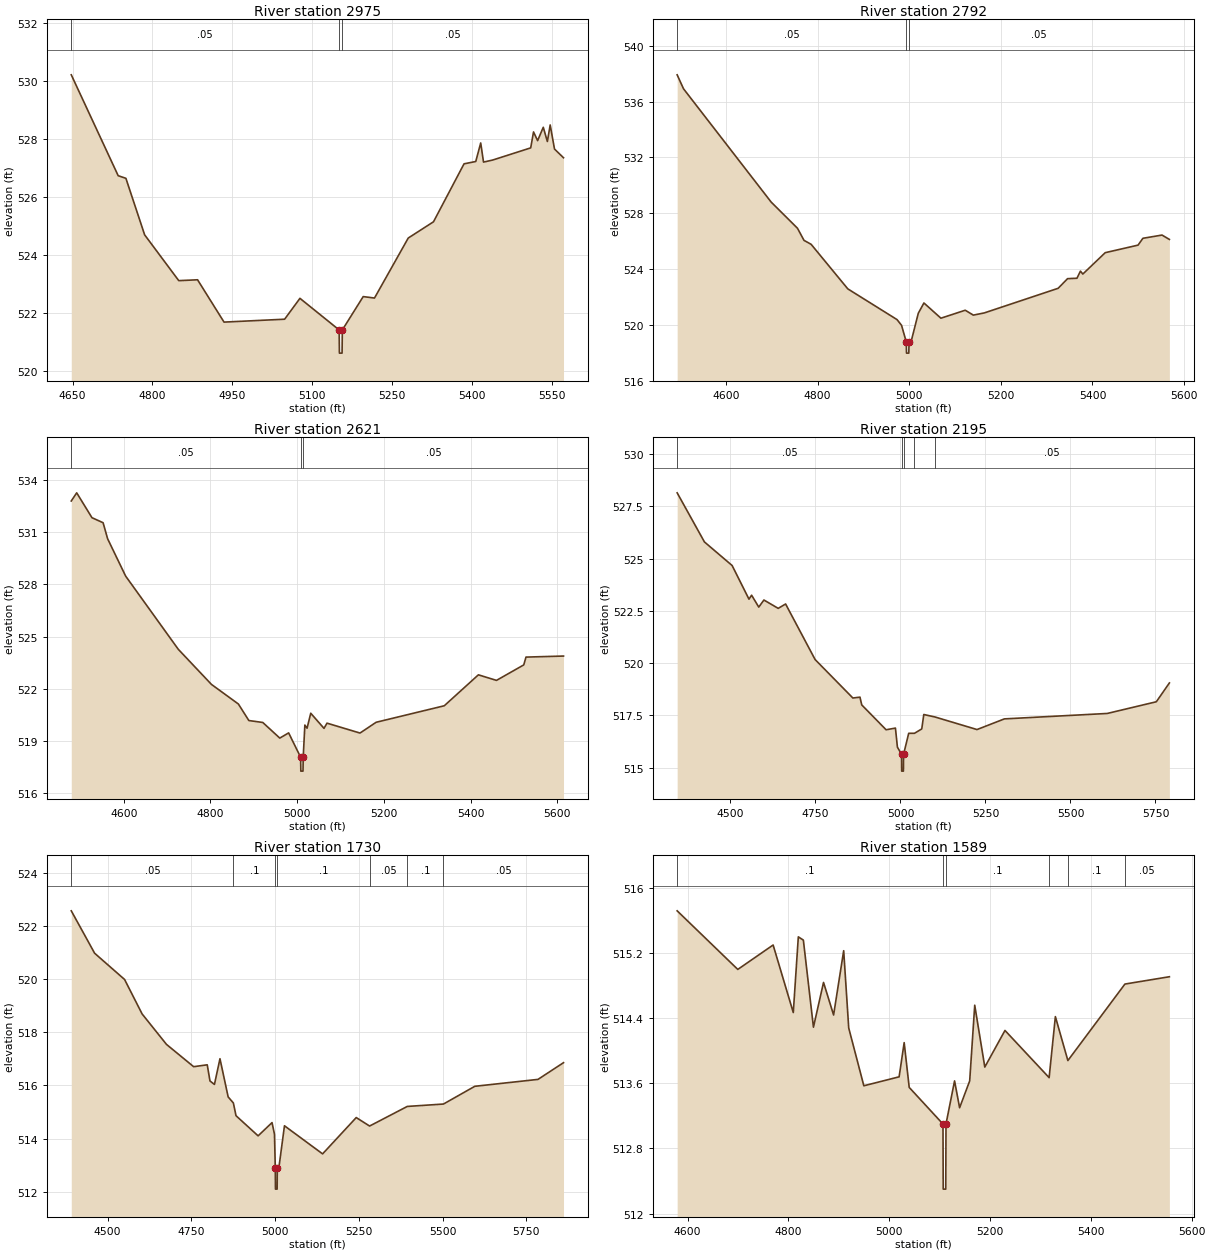
Type RM Length L Ch R = 1,2975,183,183,183
BEGIN DESCRIPTION:
UNT 113 in Lagunillas Cr Wtrshd 2.0
END DESCRIPTION:
XS GIS Cut Line= 3
      2037044.52     13511502.47      2037425.00     13511803.13
      2037840.96     13511661.01
#Sta/Elev= 30
  4647.6  530.21  4735.7  526.73  4750.2  526.64  4785.4  524.69  4849.5  523.11
  4884.8  523.14  4934.5  521.68  5048.3  521.78  5077.1  522.50  5150.7  521.41
  5151.2  520.61  5156.2  520.61  5156.7  521.41  5195.9  522.56  5217.1  522.51
  5280.5  524.58  5327.9  525.14  5385.3  527.14  5407.3  527.22  5416.6  527.86
  5421.9  527.20  5439.0  527.27  5510.5  527.69  5515.8  528.24  5523.5  527.94
  5534.1  528.40  5541.8  527.91  5547.1  528.48  5555.2  527.65  5572.1  527.35
#Mann=3,-1,0
  4647.6    0.05       0  5150.7    0.03       0  5156.7    0.05       0
Bank Sta=5150.7,5156.7
Exp/Cntr=0.3,0.1

Type RM Length L Ch R = 1,2792,171,171,171
BEGIN DESCRIPTION:
Mapping XS 9a3347d8
END DESCRIPTION:
XS GIS Cut Line= 4
      2036842.97     13511537.04      2037020.07     13511750.60
      2037290.00     13511908.53      2037761.17     13511795.13
#Sta/Elev= 30
  4493.2  537.91  4507.1  536.91  4698.5  528.80  4755.9  526.93  4770.2  526.06
  4785.7  525.78  4865.8  522.59  4973.3  520.39  4983.2  519.98  4993.5  518.79
  4994.0  517.99  4999.0  517.99  4999.5  518.79  5004.7  518.90  5019.7  520.84
  5032.0  521.58  5069.1  520.49  5122.2  521.06  5139.9  520.71  5164.1  520.87
  5325.1  522.63  5345.7  523.32  5366.2  523.35  5373.8  523.86  5379.0  523.65
  5427.9  525.18  5499.6  525.72  5510.2  526.21  5551.9  526.44  5568.0  526.13
#Mann=3,-1,0
  4493.2    0.05       0  4993.5    0.03       0  4999.5    0.05       0
Bank Sta=4993.5,4999.5
Exp/Cntr=0.3,0.1

Type RM Length L Ch R = 1,2621,426,426,426
BEGIN DESCRIPTION:
Mapping XS 4a681d4f
END DESCRIPTION:
XS GIS Cut Line= 6
      2036723.21     13511779.26      2036774.81     13511828.02
      2036776.55     13511829.75      2036970.99     13511987.74
      2037302.59     13512053.71      2037750.92     13511901.96
#Sta/Elev= 30
  4478.9  532.80  4491.4  533.27  4526.6  531.84  4552.3  531.55  4562.7  530.63
  4604.3  528.48  4725.7  524.27  4802.2  522.25  4864.4  521.12  4888.5  520.17
  4920.6  520.06  4959.9  519.16  4980.3  519.46  5007.9  518.06  5008.4  517.26
  5013.4  517.26  5013.9  518.06  5017.7  519.91  5022.8  519.73  5031.3  520.59
  5061.9  519.72  5068.8  520.02  5144.9  519.45  5182.1  520.07  5339.3  521.02
  5418.0  522.80  5459.7  522.48  5522.6  523.37  5527.8  523.82  5614.3  523.88
#Mann=3,-1,0
  4478.9    0.05       0  5007.9    0.03       0  5013.9    0.05       0
Bank Sta=5007.9,5013.9
Exp/Cntr=0.3,0.1

Type RM Length L Ch R = 1,2195,465,465,465
BEGIN DESCRIPTION:
Mapping XS c3db7847
END DESCRIPTION:
XS GIS Cut Line= 4
      2036358.36     13512049.03      2036759.37     13512312.03
      2037233.33     13512452.66      2037670.46     13512270.52
#Sta/Elev= 30
  4343.4  528.15  4423.6  525.80  4505.1  524.67  4554.6  523.06  4562.3  523.25
  4583.4  522.68  4598.5  523.02  4640.6  522.62  4662.3  522.83  4749.1  520.17
  4860.1  518.33  4881.0  518.37  4886.2  518.00  4957.8  516.81  4985.3  516.89
  4991.1  515.98  5003.2  515.63  5003.7  514.83  5008.7  514.83  5009.2  515.63
  5024.3  516.64  5041.2  516.64  5062.7  516.85  5068.7  517.54  5101.9  517.42
  5225.2  516.82  5305.7  517.33  5608.2  517.59  5752.5  518.15  5790.9  519.05
#Mann=5,-1,0
  4343.4    0.05       0  5003.2    0.03       0  5009.2    0.05       0
  5041.2     0.1       0  5101.9    0.05       0
Bank Sta=5003.2,5009.2
Exp/Cntr=0.3,0.1

Type RM Length L Ch R = 1,1730,141,141,141
BEGIN DESCRIPTION:
Mapping XS c1572f4e
END DESCRIPTION:
XS GIS Cut Line= 4
      2036258.81     13512335.06      2036428.06     13512647.52
      2036830.36     13512805.45      2037448.02     13512517.32
#Sta/Elev= 30
  4391.6  522.59  4461.3  520.99  4550.7  520.00  4603.0  518.70  4675.8  517.55
  4756.8  516.71  4797.4  516.78  4805.6  516.17  4818.9  516.04  4835.4  517.01
  4859.8  515.57  4875.4  515.34  4883.3  514.86  4949.2  514.10  4990.8  514.60
  4998.1  514.16  5000.5  512.89  5001.0  512.09  5006.0  512.09  5006.5  512.89
  5012.2  512.99  5027.9  514.48  5141.7  513.42  5242.1  514.79  5282.0  514.47
  5394.5  515.21  5502.4  515.30  5596.1  515.97  5784.5  516.23  5860.7  516.86
#Mann=7,-1,0
  4391.6    0.05       0  4875.4     0.1       0  5000.5    0.07       0
  5006.5     0.1       0  5282.0    0.05       0  5394.5     0.1       0
  5502.4    0.05       0
Bank Sta=5000.5,5006.5
Exp/Cntr=0.3,0.1

Type RM Length L Ch R = 1,1589,360,360,360
BEGIN DESCRIPTION:
Mapping XS 4a85fe07
END DESCRIPTION:
XS GIS Cut Line= 3
      2036224.66     13512833.83      2036991.49     13512843.15
      2037188.50     13512771.27
#Sta/Elev= 30
  4579.2  515.72  4699.5  515.00  4769.6  515.30  4809.6  514.47  4819.6  515.40
  4829.6  515.36  4849.6  514.29  4869.6  514.84  4889.6  514.44  4909.6  515.23
  4919.6  514.28  4949.6  513.57  5019.6  513.68  5029.6  514.10  5039.6  513.55
  5106.6  513.10  5107.1  512.30  5112.1  512.30  5112.6  513.10  5129.6  513.63
  5139.6  513.30  5159.6  513.63  5169.6  514.56  5189.6  513.80  5229.6  514.25
  5317.2  513.67  5329.6  514.42  5354.4  513.88  5467.6  514.82  5555.8  514.91
#Mann=6,-1,0
  4579.2     0.1       0  5106.6    0.07       0  5112.6     0.1       0
  5317.2    0.05       0  5354.4     0.1       0  5467.6    0.05       0
Bank Sta=5106.6,5112.6
Exp/Cntr=0.3,0.1

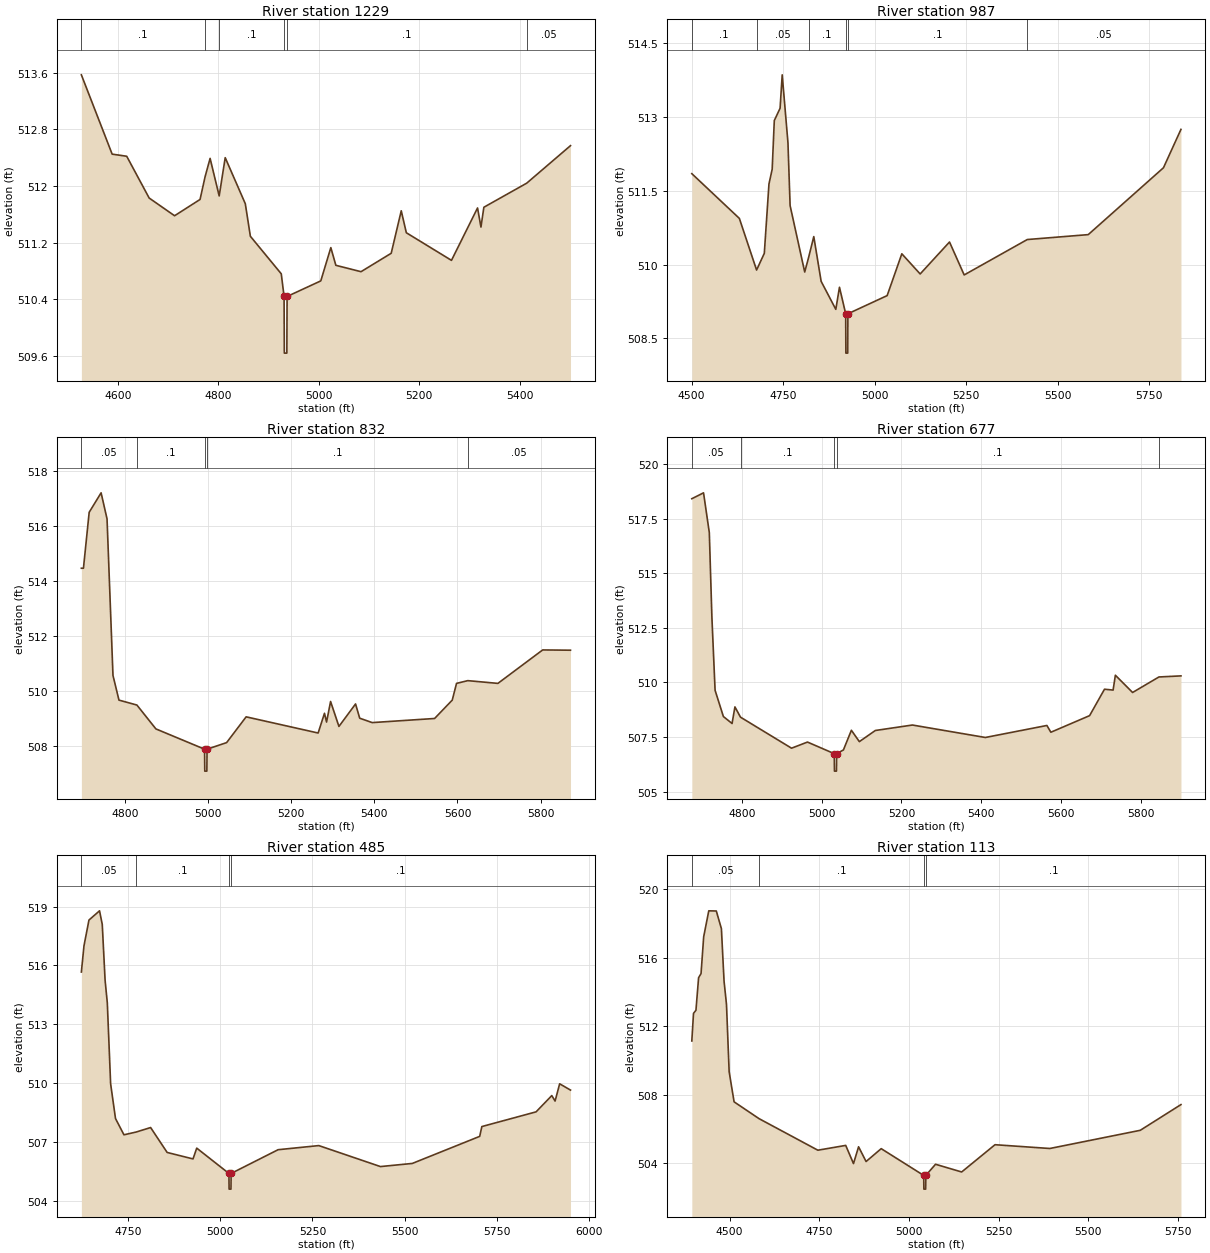
Type RM Length L Ch R = 1,1229,242,242,242
BEGIN DESCRIPTION:
Mapping XS a09f9943
END DESCRIPTION:
XS GIS Cut Line= 4
      2036146.15     13513094.93      2036341.44     13513149.18
      2036840.57     13513177.39      2037074.90     13513040.69
#Sta/Elev= 30
  4527.4  513.57  4588.7  512.45  4617.7  512.42  4662.4  511.83  4713.0  511.58
  4763.7  511.81  4773.7  512.13  4783.7  512.39  4801.8  511.86  4813.8  512.40
  4853.8  511.75  4863.9  511.29  4925.4  510.76  4931.0  510.44  4931.5  509.64
  4936.5  509.64  4937.0  510.44  5004.1  510.66  5024.1  511.13  5034.1  510.88
  5084.2  510.79  5144.3  511.05  5164.3  511.65  5174.4  511.34  5264.3  510.95
  5316.2  511.69  5323.0  511.42  5328.8  511.70  5414.1  512.04  5501.3  512.57
#Mann=6,-1,0
  4527.4     0.1       0  4773.7    0.05       0  4801.8     0.1       0
  4931.0    0.07       0  4937.0     0.1       0  5414.1    0.05       0
Bank Sta=4931,4937
Exp/Cntr=0.3,0.1

Type RM Length L Ch R = 1,987,155,155,155
BEGIN DESCRIPTION:
Mapping XS 188707b1
END DESCRIPTION:
XS GIS Cut Line= 4
      2036082.52     13513238.48      2036345.08     13513390.37
      2037080.75     13513340.46      2037270.89     13513113.59
#Sta/Elev= 30
  4500.5  511.85  4630.4  510.94  4677.5  509.89  4698.6  510.23  4711.3  511.64
  4720.1  511.94  4725.9  512.93  4741.7  513.18  4747.5  513.86  4763.2  512.48
  4769.1  511.20  4809.0  509.85  4819.8  510.15  4833.8  510.57  4853.9  509.66
  4894.0  509.09  4904.0  509.54  4921.0  509.00  4921.5  508.20  4926.5  508.20
  4927.0  509.00  5034.3  509.37  5074.4  510.22  5124.5  509.81  5204.7  510.46
  5244.8  509.79  5417.2  510.51  5583.8  510.61  5789.4  511.97  5837.2  512.75
#Mann=6,-1,0
  4500.5     0.1       0  4677.5    0.05       0  4819.8     0.1       0
  4921.0    0.07       0  4927.0     0.1       0  5417.2    0.05       0
Bank Sta=4921,4927
Exp/Cntr=0.3,0.1

Type RM Length L Ch R = 1,832,155,155,155
BEGIN DESCRIPTION:
Mapping XS f18563c6
END DESCRIPTION:
XS GIS Cut Line= 4
      2036232.23     13513420.76      2036355.93     13513522.75
      2037085.09     13513483.69      2037260.44     13513256.39
#Sta/Elev= 30
  4694.6  514.47  4699.6  514.47  4713.4  516.51  4742.1  517.22  4756.4  516.27
  4770.7  510.56  4785.1  509.66  4828.3  509.48  4874.0  508.61  4991.2  507.87
  4991.7  507.07  4996.7  507.07  4997.2  507.87  5044.3  508.11  5091.3  509.05
  5264.6  508.46  5279.9  509.18  5284.9  508.86  5294.6  509.61  5314.7  508.70
  5354.7  509.52  5364.7  509.00  5394.8  508.84  5545.0  508.99  5587.5  509.66
  5597.8  510.27  5625.0  510.37  5697.4  510.27  5805.2  511.49  5872.2  511.48
#Mann=5,-1,0
  4694.6    0.05       0  4828.3     0.1       0  4991.2    0.07       0
  4997.2     0.1       0  5625.0    0.05       0
Bank Sta=4991.2,4997.2
Exp/Cntr=0.3,0.1

Type RM Length L Ch R = 1,677,192,192,192
BEGIN DESCRIPTION:
Mapping XS 9fac4281
END DESCRIPTION:
XS GIS Cut Line= 4
      2036205.09     13513583.34      2036319.67     13513671.88
      2037093.11     13513630.22      2037360.66     13513476.96
#Sta/Elev= 30
  4673.8  518.41  4703.2  518.68  4717.7  516.86  4724.2  512.98  4732.2  509.64
  4753.0  508.44  4774.8  508.12  4782.0  508.88  4796.0  508.41  4924.1  506.99
  4964.1  507.27  5031.3  506.74  5031.8  505.94  5036.8  505.94  5037.3  506.74
  5054.3  506.91  5074.3  507.81  5094.3  507.29  5134.4  507.80  5227.5  508.05
  5410.5  507.48  5565.0  508.03  5575.0  507.72  5672.2  508.48  5709.6  509.69
  5731.2  509.65  5736.9  510.33  5780.1  509.54  5846.2  510.25  5901.5  510.30
#Mann=5,-1,0
  4673.8    0.05       0  4796.0     0.1       0  5031.3    0.07       0
  5037.3     0.1       0  5846.2    0.05       0
Bank Sta=5031.3,5037.3
Exp/Cntr=0.3,0.1

Type RM Length L Ch R = 1,485,372,372,372
BEGIN DESCRIPTION:
Mapping XS 71553cc7
END DESCRIPTION:
XS GIS Cut Line= 4
      2036147.84     13513713.57      2036324.88     13513830.74
      2036918.63     13513872.40      2037360.66     13513601.98
#Sta/Elev= 30
  4623.7  515.66  4630.8  517.00  4644.3  518.31  4672.9  518.78  4680.3  518.09
  4688.0  515.24  4694.0  514.09  4703.0  509.96  4716.2  508.19  4739.1  507.36
  4772.0  507.50  4811.4  507.73  4856.2  506.46  4926.3  506.13  4936.4  506.68
  5023.6  505.39  5024.1  504.59  5029.1  504.59  5029.6  505.39  5156.9  506.60
  5267.2  506.81  5434.3  505.74  5520.7  505.90  5703.3  507.28  5709.1  507.78
  5856.1  508.53  5898.7  509.36  5907.6  509.08  5920.0  509.96  5949.4  509.64
#Mann=4,-1,0
  4623.7    0.05       0  4772.0     0.1       0  5023.6    0.07       0
  5029.6     0.1       0
Bank Sta=5023.6,5029.6
Exp/Cntr=0.3,0.1

Type RM Length L Ch R = 1,113,0,0,0
BEGIN DESCRIPTION:
UNT 113 in Lagunillas Cr Wtrshd 1.0
END DESCRIPTION:
XS GIS Cut Line= 4
      2036107.54     13513795.86      2036487.83     13514139.41
      2036682.49     13514145.36      2037227.96     13513779.22
#Sta/Elev= 30
  4394.5  511.14  4399.2  512.75  4406.0  512.93  4413.4  514.83  4420.2  515.07
  4427.6  517.22  4441.8  518.73  4462.8  518.72  4477.0  517.69  4484.4  514.63
  4491.2  513.27  4498.6  509.35  4512.4  507.59  4582.0  506.61  4746.0  504.77
  4823.7  505.05  4845.4  503.99  4859.6  504.97  4880.5  504.11  4922.7  504.86
  5041.2  503.30  5041.7  502.50  5046.7  502.50  5047.2  503.30  5074.2  503.95
  5147.1  503.50  5240.1  505.09  5393.1  504.87  5645.2  505.93  5758.7  507.43
#Mann=4,-1,0
  4394.5    0.05       0  4582.0     0.1       0  5041.2    0.07       0
  5047.2     0.1       0
Bank Sta=5041.2,5047.2
Exp/Cntr=0.3,0.1

Chan Stop Cuts=-1