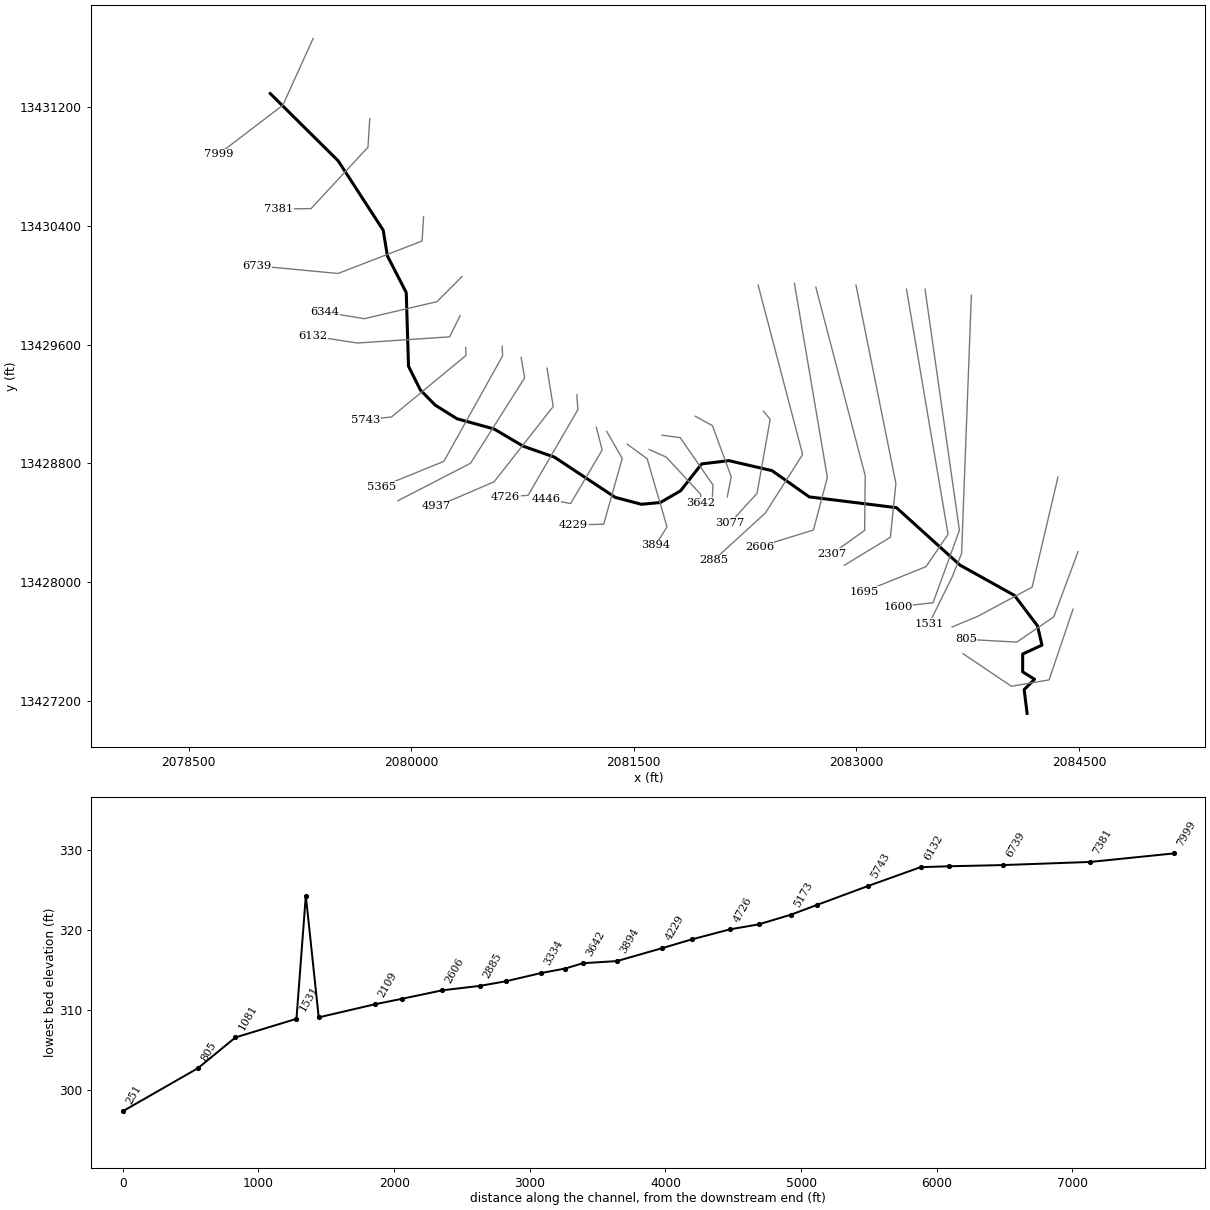
--- UNT 117 in Lagunillas Cr Wtrshd.prj (project) ---

Proj Title=UNT 117 in Lagunillas Cr Wtrshd Base Level Engineering
Current Plan=p01
Default Exp/Contr=0.3,0.1
English Units
Geom File=g01
Flow File=f01
Plan File=p01
BEGIN DESCRIPTION:
UNT 117 in Lagunillas Cr Wtrshd
END DESCRIPTION:

--- UNT 117 in Lagunillas Cr Wtrshd.p01 (plan) ---

Plan Title=Multiple Run
Short Identifier=Multiple
Geom File=g01
Flow File=f01
Subcritical Flow
K Sum by GR= 0
Std Step Tol= 0.01
Critical Tol= 0.01
Num of Std Step Trials= 20
Max Error Tol= 0.3
Flow Tol Ratio= 0.001
Split Flow NTrial= 30
Split Flow Tol= 0.02
Split Flow Ratio= 0.02
Log Output Level= 0
Friction Slope Method= 1
Unsteady Friction Slope Method= 2
Unsteady Bridges Friction Slope Method= 1
Parabolic Critical Depth
Global Vel Dist=  1 , 1 , 1
Global Log Level= 0
CheckData=True
Encroach Param= -1, 0, 0, 0
BEGIN DESCRIPTION:
Multiple Run
END DESCRIPTION:

--- UNT 117 in Lagunillas Cr Wtrshd.f01 (steady flow) ---

Flow Title=Multiple
Number of Profiles=7
Profile Names=10-year,25-year,50-year,1pct_min,100-year,1pct_plu,500-year
River Rch & RM= UNT 117 in Lagun,Reach-1,7999
     155     209     253     153     305     609     451
River Rch & RM= UNT 117 in Lagun,Reach-1,3077
     217     299     366     224     446     891     674
Boundary for River Rch & Prof#=UNT 117 in Lagun,Reach-1,1
Up Type=0
Dn Type=3
Dn Slope=0.005
Boundary for River Rch & Prof#=UNT 117 in Lagun,Reach-1,2
Up Type=0
Dn Type=3
Dn Slope=0.005
Boundary for River Rch & Prof#=UNT 117 in Lagun,Reach-1,3
Up Type=0
Dn Type=3
Dn Slope=0.005
Boundary for River Rch & Prof#=UNT 117 in Lagun,Reach-1,4
Up Type=0
Dn Type=3
Dn Slope=0.005
Boundary for River Rch & Prof#=UNT 117 in Lagun,Reach-1,5
Up Type=0
Dn Type=3
Dn Slope=0.005
Boundary for River Rch & Prof#=UNT 117 in Lagun,Reach-1,6
Up Type=0
Dn Type=3
Dn Slope=0.005
Boundary for River Rch & Prof#=UNT 117 in Lagun,Reach-1,7
Up Type=0
Dn Type=3
Dn Slope=0.005

--- UNT 117 in Lagunillas Cr Wtrshd.g01 (geometry) ---

Geom Title=Existing Conditions

River Reach=UNT 117 in Lagun,Reach-1
Reach XY= 30
      2079048.96     13431292.70      2079507.29     13430838.53
      2079810.07     13430371.87      2079838.54     13430198.26
      2079965.63     13429951.03      2079980.80     13429454.54
      2080060.80     13429294.54      2080160.36     13429192.64
      2080308.28     13429100.28      2080557.41     13429031.79
      2080753.81     13428915.69      2080964.31     13428841.90
      2081374.47     13428570.64      2081550.25     13428523.98
      2081678.29     13428535.91      2081815.00     13428615.12
      2081957.15     13428796.33      2082140.53     13428818.03
      2082431.32     13428750.76      2082681.98     13428573.89
      2083270.08     13428501.19      2083698.69     13428113.82
      2084065.80     13427909.54      2084220.80     13427704.54
      2084250.80     13427574.54      2084120.80     13427514.54
      2084120.80     13427394.54      2084200.80     13427344.54
      2084130.80     13427274.54      2084150.80     13427114.54

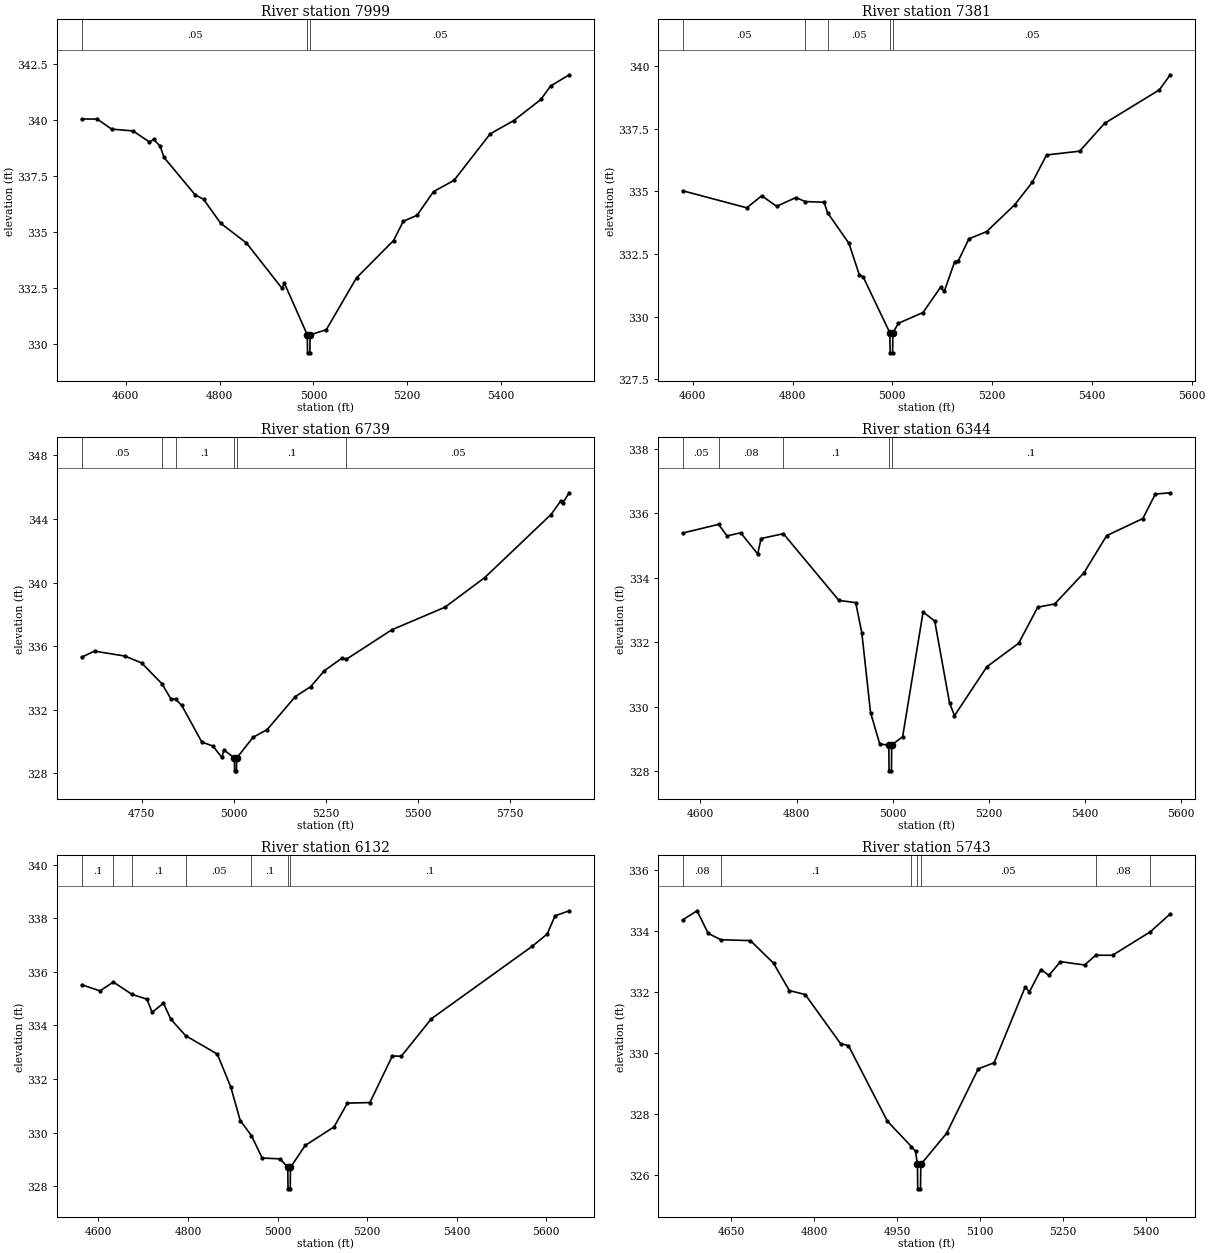
Type RM Length L Ch R = 1,7999,618,618,618
BEGIN DESCRIPTION:
UNT 117 in Lagunillas Cr Wtrshd 7.0
END DESCRIPTION:
XS GIS Cut Line= 3
      2079338.14     13431664.93      2079133.29     13431213.56
      2078700.98     13430884.12
#Sta/Elev= 30
  4505.9  340.03  4538.8  340.03  4570.1  339.58  4615.6  339.50  4650.3  339.01
  4659.6  339.12  4673.4  338.82  4681.5  338.32  4748.1  336.65  4765.7  336.46
  4802.3  335.39  4857.2  334.51  4932.8  332.50  4938.3  332.71  4986.9  330.42
  4987.4  329.62  4992.4  329.62  4992.9  330.42  5027.4  330.65  5091.8  332.96
  5170.8  334.62  5191.6  335.48  5220.7  335.74  5256.0  336.80  5299.7  337.30
  5376.7  339.37  5426.9  339.96  5484.7  340.90  5505.5  341.50  5545.1  342.00
#Mann=3,-1,0
  4505.9    0.05       0  4986.9    0.03       0  4992.9    0.05       0
Bank Sta=4986.9,4992.9
Exp/Cntr=0.3,0.1

Type RM Length L Ch R = 1,7381,642,642,642
BEGIN DESCRIPTION:
Mapping XS d15258b3
END DESCRIPTION:
XS GIS Cut Line= 4
      2079719.60     13431123.22      2079707.45     13430930.53
      2079323.77     13430517.34      2079103.33     13430513.86
#Sta/Elev= 30
  4579.7  335.02  4708.2  334.34  4738.2  334.82  4768.0  334.40  4806.9  334.75
  4825.0  334.59  4863.1  334.56  4870.2  334.14  4913.0  332.92  4934.0  331.65
  4941.3  331.59  4995.0  329.35  4995.5  328.55  5000.5  328.55  5001.0  329.35
  5012.2  329.73  5061.5  330.16  5096.7  331.17  5104.0  331.00  5125.0  332.19
  5132.4  332.23  5153.4  333.10  5189.0  333.39  5245.2  334.46  5280.9  335.37
  5309.2  336.45  5375.4  336.60  5425.4  337.71  5535.4  339.05  5557.1  339.65
#Mann=5,-1,0
  4579.7    0.05       0  4825.0    0.08       0  4870.2    0.05       0
  4995.0    0.03       0  5001.0    0.05       0
Bank Sta=4995,5001
Exp/Cntr=0.3,0.1

Type RM Length L Ch R = 1,6739,395,395,395
BEGIN DESCRIPTION:
Mapping XS 631cb911
END DESCRIPTION:
XS GIS Cut Line= 4
      2080082.45     13430461.80      2080072.03     13430298.59
      2079506.06     13430079.84      2078955.74     13430131.92
#Sta/Elev= 30
  4586.6  335.31  4621.7  335.69  4703.6  335.38  4749.4  334.95  4804.4  333.64
  4828.4  332.70  4842.3  332.65  4858.4  332.27  4912.9  329.97  4942.8  329.72
  4967.4  329.00  4972.8  329.48  5001.3  328.96  5001.8  328.16  5006.8  328.16
  5007.3  328.96  5051.9  330.27  5090.0  330.75  5166.4  332.83  5208.0  333.45
  5245.5  334.46  5293.7  335.26  5305.2  335.18  5428.3  337.03  5572.5  338.45
  5680.8  340.32  5860.2  344.28  5887.3  345.15  5892.4  345.01  5909.7  345.65
#Mann=6,-1,0
  4586.6    0.05       0  4804.4    0.08       0  4842.3     0.1       0
  5001.3    0.07       0  5007.3     0.1       0  5305.2    0.05       0
Bank Sta=5001.3,5007.3
Exp/Cntr=0.3,0.1

Type RM Length L Ch R = 1,6344,212,212,212
BEGIN DESCRIPTION:
Mapping XS 6fa6e11c
END DESCRIPTION:
XS GIS Cut Line= 4
      2080341.57     13430059.01      2080172.29     13429889.73
      2079682.71     13429775.15      2079414.44     13429819.42
#Sta/Elev= 30
  4563.2  335.39  4637.8  335.66  4655.5  335.30  4683.8  335.40  4719.2  334.74
  4726.2  335.22  4772.6  335.37  4888.1  333.30  4923.1  333.23  4935.8  332.29
  4953.9  329.82  4973.1  328.84  4991.9  328.81  4992.4  328.01  4997.4  328.01
  4997.9  328.81  5020.7  329.07  5063.2  332.94  5087.4  332.66  5118.2  330.12
  5128.5  329.72  5195.8  331.24  5262.0  331.97  5301.7  333.09  5336.9  333.19
  5398.0  334.16  5445.0  335.31  5520.2  335.84  5546.3  336.60  5577.3  336.64
#Mann=5,-1,0
  4563.2    0.05       0  4637.8    0.08       0  4772.6     0.1       0
  4991.9    0.07       0  4997.9     0.1       0
Bank Sta=4991.9,4997.9
Exp/Cntr=0.3,0.1

Type RM Length L Ch R = 1,6132,389,389,389
BEGIN DESCRIPTION:
Mapping XS 2cd8cbe5
END DESCRIPTION:
XS GIS Cut Line= 4
      2080328.54     13429795.97      2080258.23     13429652.75
      2079635.83     13429611.09      2079333.79     13429657.95
#Sta/Elev= 30
  4562.4  335.52  4603.5  335.29  4633.3  335.62  4674.8  335.16  4708.3  334.98
  4719.9  334.49  4745.2  334.83  4761.7  334.23  4794.6  333.62  4865.5  332.93
  4895.6  331.70  4916.7  330.45  4941.6  329.89  4965.7  329.05  5005.8  329.02
  5022.9  328.70  5023.4  327.90  5028.4  327.90  5028.9  328.70  5061.8  329.52
  5126.1  330.21  5156.1  331.10  5206.3  331.12  5256.4  332.86  5276.4  332.85
  5343.7  334.25  5569.2  336.96  5602.1  337.41  5619.8  338.09  5651.4  338.28
#Mann=7,-1,0
  4562.4     0.1       0  4633.3    0.05       0  4674.8     0.1       0
  4794.6    0.05       0  4941.6     0.1       0  5022.9    0.07       0
  5028.9     0.1       0
Bank Sta=5022.9,5028.9
Exp/Cntr=0.3,0.1

Type RM Length L Ch R = 1,5743,378,378,378
BEGIN DESCRIPTION:
Mapping XS 0ce528a9
END DESCRIPTION:
XS GIS Cut Line= 4
      2080365.84     13429580.92      2080368.95     13429528.04
      2079866.71     13429112.97      2079691.34     13429093.25
#Sta/Elev= 30
  4562.3  334.36  4588.3  334.66  4608.3  333.92  4631.0  333.71  4684.7  333.68
  4726.4  332.94  4755.0  332.04  4783.7  331.91  4847.5  330.30  4861.9  330.23
  4932.2  327.75  4975.5  326.92  4983.0  326.76  4986.5  326.33  4987.0  325.53
  4992.0  325.53  4992.5  326.33  5039.0  327.35  5096.4  329.47  5125.0  329.67
  5181.0  332.15  5188.9  332.00  5209.7  332.73  5224.0  332.54  5244.8  332.99
  5288.5  332.88  5308.7  333.20  5339.0  333.20  5407.3  333.97  5443.3  334.56
#Mann=7,-1,0
  4562.3    0.08       0  4631.0     0.1       0  4975.5    0.05       0
  4986.5    0.04       0  4992.5    0.05       0  5308.7    0.08       0
  5407.3     0.1       0
Bank Sta=4986.5,4992.5
Exp/Cntr=0.3,0.1

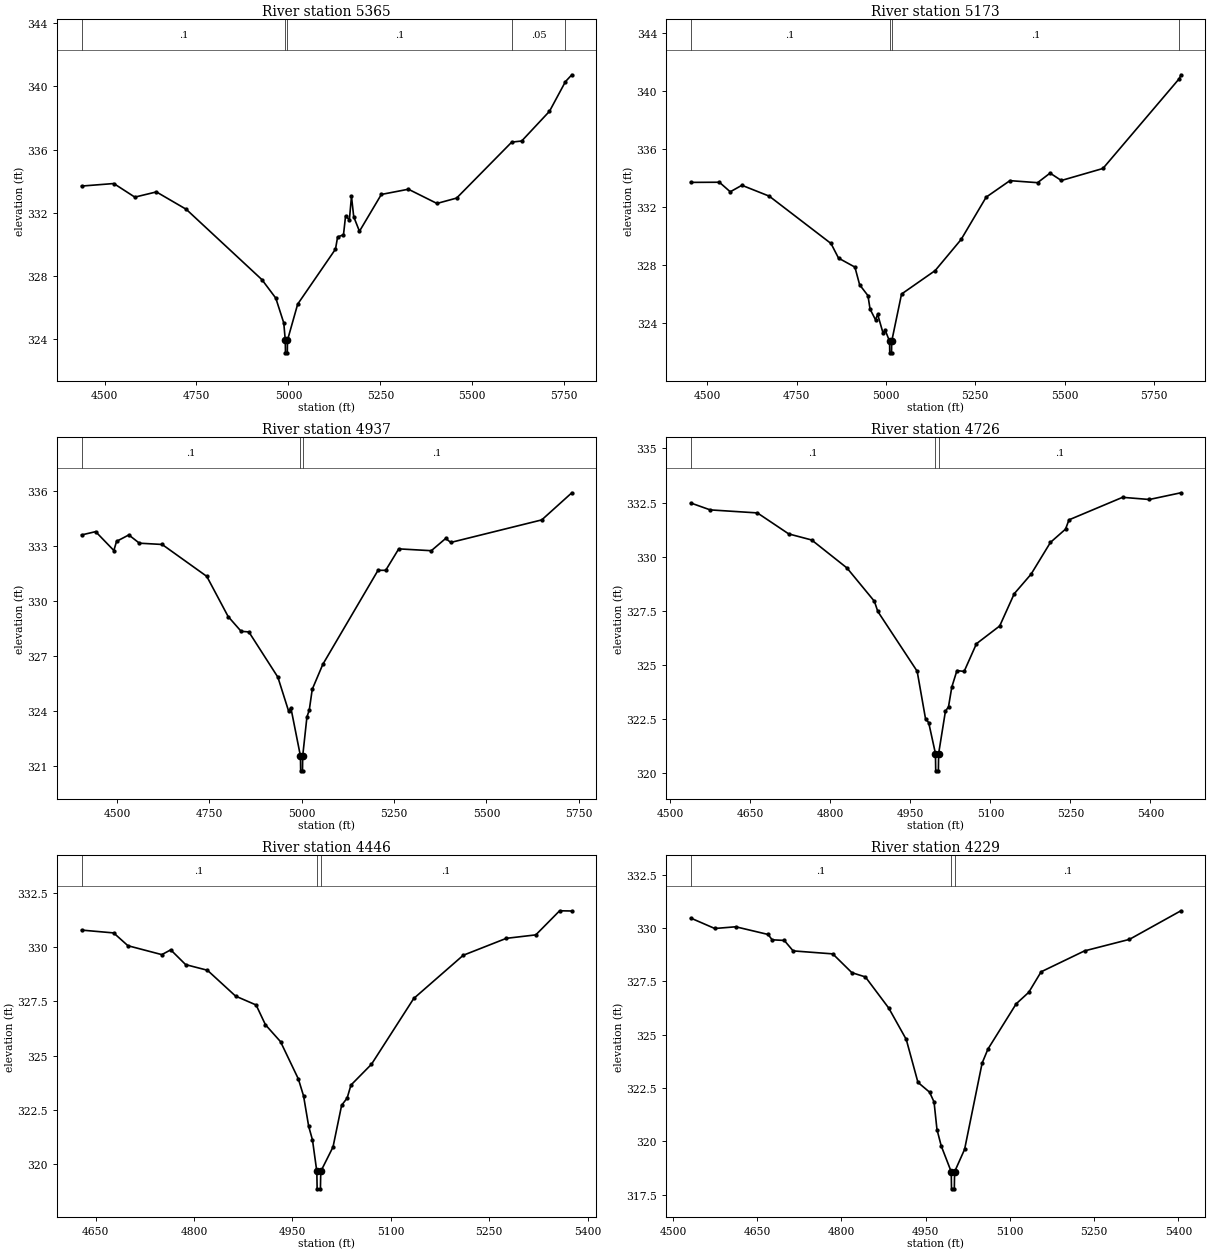
Type RM Length L Ch R = 1,5365,192,192,192
BEGIN DESCRIPTION:
Mapping XS 57510560
END DESCRIPTION:
XS GIS Cut Line= 4
      2080612.46     13429589.64      2080615.07     13429524.52
      2080219.23     13428813.58      2079798.68     13428642.24
#Sta/Elev= 30
  4437.7  333.70  4525.2  333.86  4582.4  333.00  4641.0  333.33  4722.2  332.23
  4928.0  327.78  4965.7  326.61  4987.4  325.04  4991.5  323.95  4992.0  323.15
  4997.0  323.15  4997.5  323.95  5025.2  326.23  5128.0  329.71  5133.8  330.48
  5149.8  330.62  5155.5  331.82  5165.8  331.56  5171.5  333.05  5177.6  331.76
  5193.2  330.84  5252.7  333.17  5326.3  333.50  5403.9  332.60  5457.4  332.94
  5607.3  336.48  5634.3  336.55  5709.9  338.43  5753.4  340.31  5770.7  340.74
#Mann=5,-1,0
  4437.7     0.1       0  4991.5    0.07       0  4997.5     0.1       0
  5607.3    0.05       0  5753.4     0.1       0
Bank Sta=4991.5,4997.5
Exp/Cntr=0.3,0.1

Type RM Length L Ch R = 1,5173,236,236,236
BEGIN DESCRIPTION:
Mapping XS 1e6cda4a
END DESCRIPTION:
XS GIS Cut Line= 4
      2080740.06     13429514.14      2080763.50     13429376.08
      2080398.92     13428800.56      2079909.63     13428548.10
#Sta/Elev= 30
  4453.7  333.70  4534.0  333.71  4564.4  333.05  4597.0  333.50  4673.5  332.75
  4846.4  329.48  4867.5  328.47  4913.3  327.85  4926.5  326.63  4949.8  325.88
  4955.7  324.95  4971.0  324.21  4976.9  324.59  4992.1  323.29  4998.1  323.49
  5010.3  322.73  5010.8  321.93  5015.8  321.93  5016.3  322.73  5043.8  325.99
  5137.9  327.61  5210.6  329.76  5280.6  332.68  5347.1  333.82  5424.5  333.68
  5459.5  334.34  5491.0  333.83  5607.4  334.66  5821.3  340.87  5825.6  341.13
#Mann=4,-1,0
  4453.7     0.1       0  5010.3    0.07       0  5016.3     0.1       0
  5821.3    0.05       0
Bank Sta=5010.3,5016.3
Exp/Cntr=0.3,0.1

Type RM Length L Ch R = 1,4937,211,211,211
BEGIN DESCRIPTION:
Mapping XS bfc6d21b
END DESCRIPTION:
XS GIS Cut Line= 4
      2080914.54     13429441.21      2080956.21     13429183.37
      2080557.77     13428675.56      2080171.18     13428509.51
#Sta/Elev= 30
  4404.0  333.60  4442.0  333.78  4491.3  332.75  4498.6  333.25  4531.8  333.60
  4560.4  333.15  4622.1  333.08  4742.9  331.34  4800.7  329.15  4836.0  328.34
  4856.8  328.31  4935.4  325.84  4964.3  324.00  4970.7  324.16  4996.6  321.53
  4997.1  320.73  5002.1  320.73  5002.6  321.53  5014.1  323.67  5020.4  324.04
  5028.5  325.18  5057.1  326.54  5206.6  331.67  5227.4  331.67  5262.7  332.84
  5350.9  332.74  5389.9  333.41  5403.5  333.19  5649.9  334.42  5731.4  335.90
#Mann=3,-1,0
  4404.0     0.1       0  4996.6    0.07       0  5002.6     0.1       0
Bank Sta=4996.6,5002.6
Exp/Cntr=0.3,0.1

Type RM Length L Ch R = 1,4726,280,280,280
BEGIN DESCRIPTION:
Mapping XS dad2c064
END DESCRIPTION:
XS GIS Cut Line= 4
      2081115.07     13429261.50      2081122.88     13429162.54
      2080786.94     13428584.41      2080635.91     13428574.00
#Sta/Elev= 30
  4537.9  332.48  4574.5  332.16  4663.0  332.02  4721.8  331.05  4764.8  330.77
  4830.9  329.48  4882.4  327.94  4888.8  327.47  4962.6  324.71  4978.4  322.50
  4984.2  322.34  4996.9  320.91  4997.4  320.11  5002.4  320.11  5002.9  320.91
  5015.6  322.86  5021.4  323.07  5027.6  323.98  5037.2  324.74  5050.7  324.70
  5073.8  325.98  5117.4  326.80  5144.7  328.29  5176.2  329.19  5212.6  330.66
  5240.8  331.27  5247.3  331.70  5347.8  332.74  5398.0  332.64  5457.2  332.95
#Mann=3,-1,0
  4537.9     0.1       0  4996.9    0.07       0  5002.9     0.1       0
Bank Sta=4996.9,5002.9
Exp/Cntr=0.3,0.1

Type RM Length L Ch R = 1,4446,217,217,217
BEGIN DESCRIPTION:
Mapping XS b77b0eee
END DESCRIPTION:
XS GIS Cut Line= 4
      2081246.99     13429043.46      2081286.07     13428889.78
      2081073.83     13428529.10      2080906.76     13428560.18
#Sta/Elev= 30
  4628.8  330.78  4677.6  330.65  4699.4  330.06  4751.0  329.65  4764.6  329.87
  4787.3  329.19  4820.5  328.93  4863.4  327.74  4894.7  327.33  4908.9  326.42
  4931.9  325.64  4959.1  323.92  4967.0  323.14  4974.8  321.74  4980.6  321.11
  4987.2  319.66  4987.7  318.86  4992.7  318.86  4993.2  319.66  5011.9  320.79
  5025.0  322.71  5033.4  323.04  5039.2  323.64  5070.5  324.60  5134.9  327.63
  5210.3  329.62  5275.9  330.40  5320.9  330.56  5357.2  331.67  5375.8  331.66
#Mann=3,-1,0
  4628.8     0.1       0  4987.2    0.07       0  4993.2     0.1       0
Bank Sta=4987.2,4993.2
Exp/Cntr=0.3,0.1

Type RM Length L Ch R = 1,4229,335,335,335
BEGIN DESCRIPTION:
Mapping XS 8869cfd9
END DESCRIPTION:
XS GIS Cut Line= 4
      2081317.32     13429014.77      2081421.48     13428832.49
      2081296.48     13428389.78      2081093.31     13428384.57
#Sta/Elev= 30
  4531.4  330.46  4574.3  329.97  4611.7  330.05  4669.3  329.69  4676.5  329.44
  4698.1  329.41  4713.9  328.92  4784.5  328.78  4818.5  327.90  4842.6  327.70
  4884.2  326.24  4915.4  324.77  4936.2  322.76  4956.9  322.30  4964.9  321.84
  4970.1  320.55  4977.7  319.78  4995.5  318.57  4996.0  317.77  5001.0  317.77
  5001.5  318.57  5019.3  319.62  5050.5  323.66  5060.9  324.32  5111.2  326.44
  5133.6  326.98  5155.6  327.94  5232.9  328.92  5312.9  329.46  5404.6  330.80
#Mann=3,-1,0
  4531.4     0.1       0  4995.5    0.07       0  5001.5     0.1       0
Bank Sta=4995.5,5001.5
Exp/Cntr=0.3,0.1

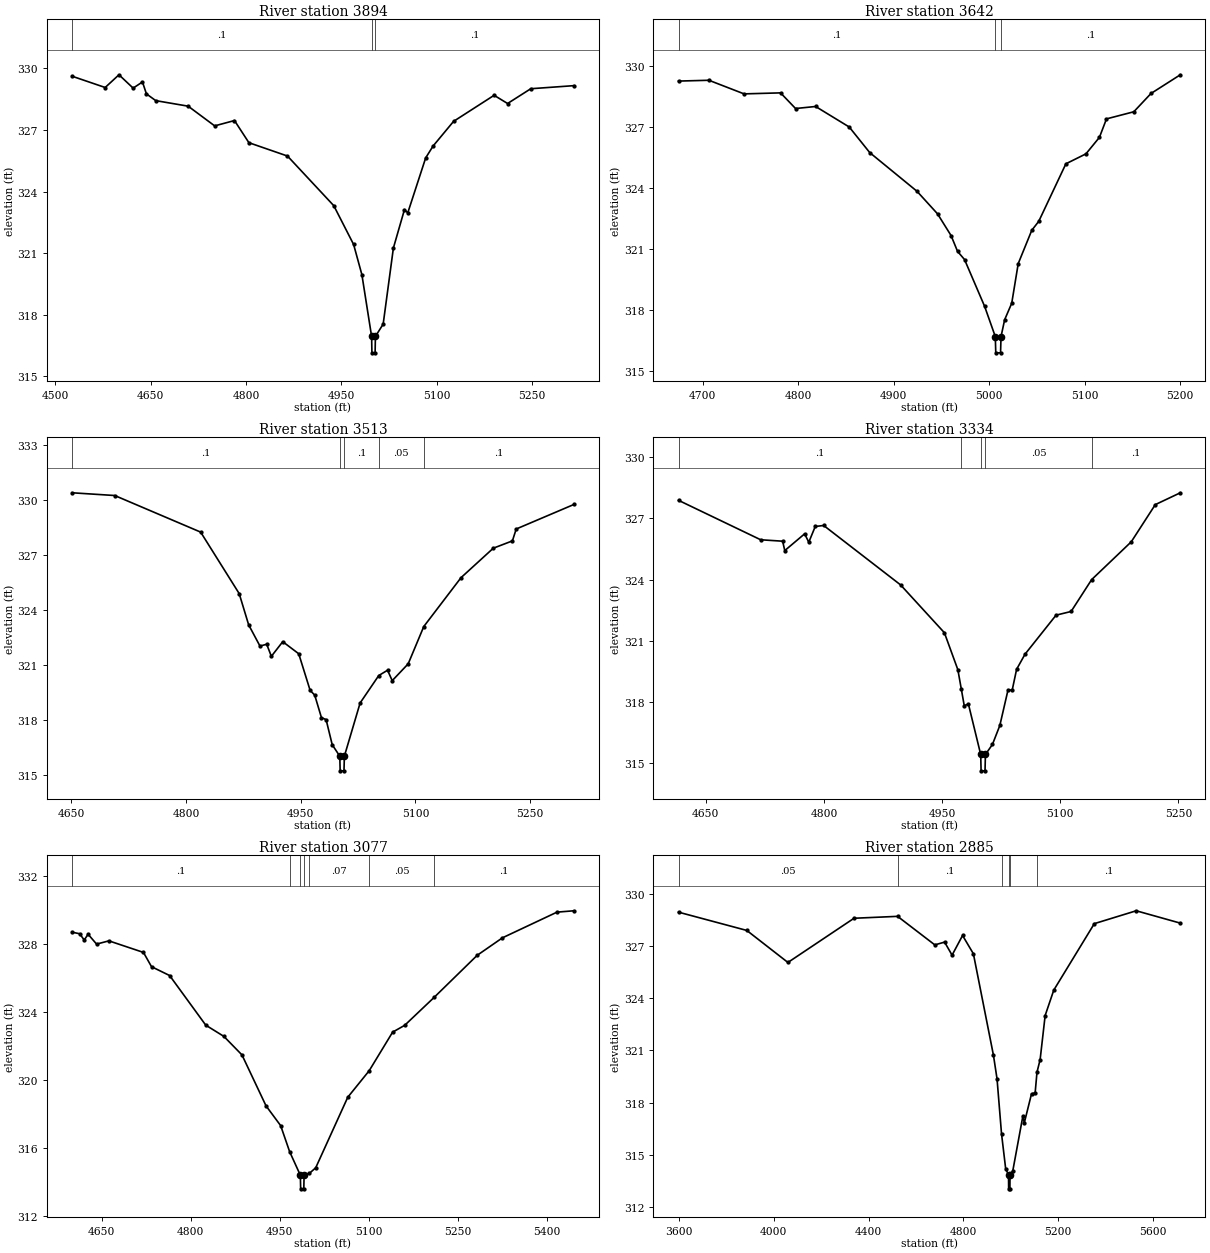
Type RM Length L Ch R = 1,3894,252,252,252
BEGIN DESCRIPTION:
Mapping XS 32b45661
END DESCRIPTION:
XS GIS Cut Line= 4
      2081455.37     13428928.82      2081589.45     13428831.18
      2081723.57     13428371.55      2081646.12     13428248.92
#Sta/Elev= 30
  4526.3  329.62  4578.4  329.07  4600.1  329.69  4622.4  329.04  4637.1  329.34
  4643.3  328.76  4658.0  328.43  4709.0  328.16  4750.7  327.20  4781.9  327.46
  4804.6  326.38  4865.3  325.73  4938.2  323.31  4969.4  321.42  4982.4  319.95
  4997.7  316.94  4998.2  316.14  5003.2  316.14  5003.7  316.94  5015.9  317.54
  5032.0  321.25  5049.4  323.12  5054.6  322.96  5082.8  325.64  5094.5  326.22
  5126.7  327.42  5190.5  328.69  5211.7  328.29  5248.2  329.01  5316.0  329.16
#Mann=3,-1,0
  4526.3     0.1       0  4997.7    0.07       0  5003.7     0.1       0
Bank Sta=4997.7,5003.7
Exp/Cntr=0.3,0.1

Type RM Length L Ch R = 1,3642,129,129,129
BEGIN DESCRIPTION:
Mapping XS 88bb69fa
END DESCRIPTION:
XS GIS Cut Line= 4
      2081602.45     13428893.69      2081718.36     13428841.60
      2081950.13     13428591.60      2081948.83     13428534.30
#Sta/Elev= 30
  4674.8  329.24  4706.6  329.28  4743.4  328.61  4781.6  328.66  4797.3  327.89
  4818.3  327.99  4853.5  326.98  4875.0  325.72  4924.4  323.82  4945.9  322.71
  4960.1  321.64  4966.9  320.86  4974.2  320.46  4995.2  318.16  5006.4  316.67
  5006.9  315.87  5011.9  315.87  5012.4  316.67  5016.2  317.50  5023.6  318.31
  5030.4  320.26  5044.6  321.90  5051.9  322.34  5080.3  325.17  5101.3  325.66
  5115.4  326.47  5122.8  327.38  5151.4  327.73  5169.4  328.63  5200.1  329.55
#Mann=3,-1,0
  4674.8     0.1       0  5006.4    0.07       0  5012.4     0.1       0
Bank Sta=5006.4,5012.4
Exp/Cntr=0.3,0.1

Type RM Length L Ch R = 1,3513,179,179,179
BEGIN DESCRIPTION:
Mapping XS 0b127fbb
END DESCRIPTION:
XS GIS Cut Line= 4
      2081689.73     13428990.04      2081812.11     13428973.11
      2082033.46     13428654.10      2082025.66     13428509.74
#Sta/Elev= 30
  4650.9  330.41  4706.7  330.26  4819.1  328.26  4869.5  324.90  4881.9  323.19
  4896.7  322.03  4905.5  322.13  4911.6  321.47  4926.5  322.27  4947.4  321.61
  4962.3  319.61  4968.3  319.35  4977.1  318.12  4983.2  318.01  4991.2  316.64
  5001.1  316.01  5001.6  315.21  5006.6  315.21  5007.1  316.01  5027.7  318.92
  5052.1  320.42  5063.6  320.71  5069.7  320.14  5090.6  321.06  5111.0  323.10
  5159.7  325.77  5201.9  327.38  5226.9  327.78  5231.9  328.43  5307.3  329.77
#Mann=5,-1,0
  4650.9     0.1       0  5001.1    0.07       0  5007.1     0.1       0
  5052.1    0.05       0  5111.0     0.1       0
Bank Sta=5001.1,5007.1
Exp/Cntr=0.3,0.1

Type RM Length L Ch R = 1,3334,257,257,257
BEGIN DESCRIPTION:
Mapping XS af866767
END DESCRIPTION:
XS GIS Cut Line= 4
      2081913.71     13429117.62      2082029.56     13429053.84
      2082155.86     13428710.09      2082129.90     13428573.81
#Sta/Elev= 30
  4615.3  327.88  4719.6  325.95  4747.5  325.88  4750.2  325.42  4775.4  326.24
  4780.7  325.83  4788.9  326.60  4799.6  326.65  4897.3  323.74  4952.9  321.40
  4970.0  319.59  4974.3  318.66  4978.1  317.83  4983.4  317.91  4999.0  315.44
  4999.5  314.64  5004.5  314.64  5005.0  315.44  5013.9  315.93  5023.3  316.86
  5033.7  318.60  5039.0  318.59  5044.6  319.61  5055.3  320.35  5094.7  322.26
  5113.8  322.44  5139.9  324.00  5190.2  325.85  5220.7  327.67  5252.5  328.25
#Mann=5,-1,0
  4615.3     0.1       0  4974.3    0.05       0  4999.0   0.035       0
  5005.0    0.05       0  5139.9     0.1       0
Bank Sta=4999,5005
Exp/Cntr=0.3,0.1

Type RM Length L Ch R = 1,3077,192,192,192
BEGIN DESCRIPTION:
Mapping XS d2233a6f
END DESCRIPTION:
XS GIS Cut Line= 4
      2082373.32     13429151.47      2082418.88     13429096.81
      2082330.34     13428598.11      2082149.97     13428399.97
#Sta/Elev= 30
  4600.2  328.72  4612.9  328.63  4620.7  328.26  4627.2  328.60  4641.5  328.02
  4662.3  328.21  4720.5  327.53  4734.1  326.69  4764.6  326.17  4825.5  323.25
  4856.0  322.59  4886.5  321.50  4927.1  318.50  4951.7  317.34  4966.8  315.81
  4984.9  314.42  4985.4  313.62  4990.7  313.62  4991.2  314.42  5000.1  314.53
  5010.8  314.86  5064.8  319.01  5100.9  320.57  5140.4  322.84  5160.7  323.24
  5210.2  324.88  5282.9  327.36  5325.5  328.39  5417.4  329.90  5445.8  329.98
#Mann=7,-1,0
  4600.2     0.1       0  4966.8    0.05       0  4984.9   0.035       0
  4991.2    0.05       0  5000.1    0.07       0  5100.9    0.05       0
  5210.2     0.1       0
Bank Sta=4984.9,4991.2
Exp/Cntr=0.3,0.1

Type RM Length L Ch R = 1,2885,279,279,279
BEGIN DESCRIPTION:
Mapping XS e0d4d125
END DESCRIPTION:
XS GIS Cut Line= 4
      2082337.50     13430001.82      2082637.63     13428859.83
      2082386.33     13428465.30      2082038.90     13428147.63
#Sta/Elev= 30
  3597.6  328.94  3885.9  327.89  4059.6  326.05  4338.8  328.59  4522.7  328.70
  4680.0  327.06  4721.3  327.22  4752.9  326.47  4797.2  327.60  4842.9  326.55
  4927.6  320.72  4942.8  319.36  4961.7  316.21  4979.2  314.20  4991.3  313.84
  4991.8  313.04  4997.1  313.04  4997.6  313.84  5009.4  314.08  5052.0  317.23
  5057.9  316.83  5088.4  318.50  5103.7  318.55  5111.5  319.74  5124.8  320.47
  5146.0  323.00  5182.4  324.46  5353.6  328.28  5530.6  329.02  5716.9  328.31
#Mann=6,-1,0
  3597.6    0.05       0  4522.7     0.1       0  4961.7    0.07       0
  4991.3    0.07       0  4997.6    0.07       0  5111.5     0.1       0
Bank Sta=4991.3,4997.6
Exp/Cntr=0.3,0.1

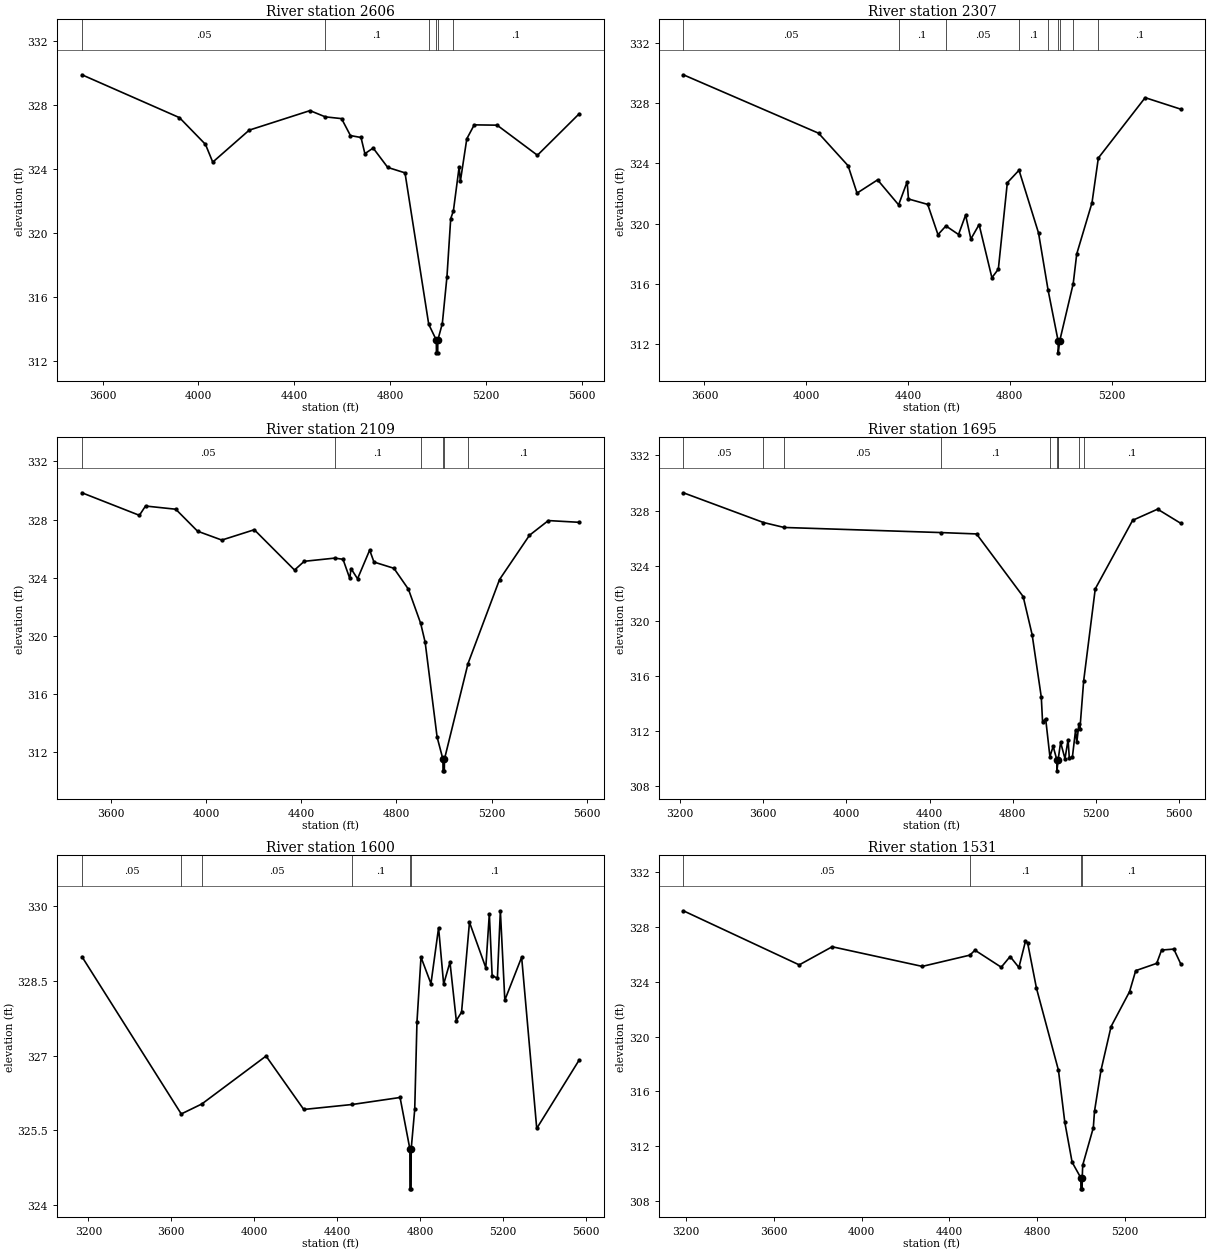
Type RM Length L Ch R = 1,2606,299,299,299
BEGIN DESCRIPTION:
Mapping XS a34502f7
END DESCRIPTION:
XS GIS Cut Line= 4
      2082582.22     13430013.25      2082804.30     13428704.88
      2082710.55     13428350.71      2082345.90     13428237.72
#Sta/Elev= 30
  3514.0  329.86  3921.0  327.18  4029.5  325.51  4059.9  324.40  4212.1  326.40
  4465.7  327.62  4529.7  327.23  4597.5  327.12  4634.6  326.06  4678.7  325.94
  4694.9  324.93  4729.4  325.28  4790.2  324.07  4862.3  323.73  4961.4  314.26
  4993.0  313.28  4993.5  312.48  4998.8  312.48  4999.3  313.28  5018.1  314.31
  5037.5  317.25  5053.1  320.87  5064.3  321.35  5088.2  324.09  5093.4  323.20
  5120.3  325.86  5151.3  326.73  5246.8  326.71  5415.0  324.83  5589.2  327.42
#Mann=6,-1,0
  3514.0    0.05       0  4529.7     0.1       0  4961.4    0.07       0
  4993.0    0.07       0  4999.3    0.07       0  5064.3     0.1       0
Bank Sta=4993,4999.3
Exp/Cntr=0.3,0.1

Type RM Length L Ch R = 1,2307,198,198,198
BEGIN DESCRIPTION:
Mapping XS 345757d6
END DESCRIPTION:
XS GIS Cut Line= 4
      2082726.39     13429987.93      2083059.50     13428716.60
      2083055.60     13428348.11      2082835.04     13428190.39
#Sta/Elev= 30
  3517.3  329.88  4048.6  326.00  4164.6  323.84  4199.8  322.02  4280.6  322.90
  4363.2  321.24  4396.7  322.77  4401.9  321.63  4477.5  321.27  4517.9  319.26
  4549.1  319.84  4598.7  319.27  4626.4  320.56  4647.1  318.97  4679.5  319.93
  4729.8  316.40  4755.1  316.97  4790.4  322.71  4836.4  323.54  4913.1  319.37
  4950.7  315.57  4990.0  312.21  4990.5  311.41  4996.4  312.21  5049.4  316.01
  5063.2  317.98  5123.2  321.38  5148.1  324.35  5332.1  328.36  5471.2  327.60
#Mann=9,-1,0
  3517.3    0.05       0  4363.2     0.1       0  4549.1    0.05       0
  4836.4     0.1       0  4950.7    0.07       0  4990.0    0.07       0
  4996.4    0.07       0  5049.4    0.05       0  5148.1     0.1       0
Bank Sta=4990,4996.4
Exp/Cntr=0.3,0.1

Type RM Length L Ch R = 1,2109,414,414,414
BEGIN DESCRIPTION:
Mapping XS 1648ec01
END DESCRIPTION:
XS GIS Cut Line= 4
      2082997.22     13430001.82      2083266.36     13428663.65
      2083229.03     13428301.67      2082918.75     13428113.01
#Sta/Elev= 30
  3476.7  329.84  3718.3  328.29  3744.1  328.93  3871.3  328.71  3963.1  327.20
  4065.1  326.59  4201.8  327.30  4371.1  324.53  4411.9  325.13  4540.2  325.35
  4575.1  325.27  4603.6  323.95  4608.7  324.63  4636.3  323.93  4687.3  325.90
  4705.3  325.08  4789.3  324.65  4850.4  323.21  4902.0  320.86  4920.7  319.57
  4971.0  313.05  4995.5  311.53  4996.0  310.73  5001.4  310.73  5001.9  311.53
  5101.0  318.10  5233.8  323.88  5359.7  326.92  5439.1  327.93  5568.7  327.81
#Mann=6,-1,0
  3476.7    0.05       0  4540.2     0.1       0  4902.0    0.05       0
  4995.5   0.035       0  5001.9    0.05       0  5101.0     0.1       0
Bank Sta=4995.5,5001.9
Exp/Cntr=0.3,0.1

Type RM Length L Ch R = 1,1695,95,95,95
BEGIN DESCRIPTION:
Mapping XS 504f1c83
END DESCRIPTION:
XS GIS Cut Line= 4
      2083337.50     13429974.06      2083617.92     13428321.63
      2083469.49     13428103.75      2083052.75     13427935.25
#Sta/Elev= 30
  3216.7  329.29  3601.6  327.13  3701.1  326.77  4453.9  326.40  4625.6  326.30
  4849.6  321.75  4892.7  318.98  4936.7  314.44  4942.7  312.67  4957.7  312.87
  4978.1  310.12  4993.6  310.87  5011.4  309.89  5011.9  309.09  5017.8  309.89
  5018.2  309.95  5029.5  311.16  5050.5  309.97  5065.4  311.35  5071.4  309.99
  5086.4  310.13  5101.3  312.03  5107.4  311.17  5117.6  312.52  5122.3  312.13
  5140.2  315.61  5196.0  322.31  5375.7  327.29  5495.6  328.10  5605.9  327.08
#Mann=10,-1,0
  3216.7    0.05       0  3601.6    0.08       0  3701.1    0.05       0
  4453.9     0.1       0  4978.1    0.05       0  5011.4   0.033       0
  5017.8    0.05       0  5018.2    0.07       0  5117.6    0.05       0
  5140.2     0.1       0
Bank Sta=5011.4,5017.8
Exp/Cntr=0.3,0.1

Type RM Length L Ch R = 1,1600,69,69,69
BEGIN DESCRIPTION:
Mapping XS 5edf3119
END DESCRIPTION:
XS GIS Cut Line= 4
      2083462.51     13429973.97      2083694.31     13428348.54
      2083516.36     13427859.83      2083281.55     13427834.95
#Sta/Elev= 30
  3169.3  328.98  3648.2  325.83  3747.4  326.03  4057.2  326.99  4239.0  325.92
  4473.2  326.02  4703.6  326.16  4750.9  325.13  4751.4  324.33  4756.8  324.33
  4757.3  325.13  4774.3  325.92  4785.1  327.67  4804.6  328.97  4852.6  328.44
  4889.4  329.56  4913.8  328.43  4944.3  328.87  4974.9  327.70  5000.2  327.87
  5038.4  329.67  5117.1  328.76  5134.2  329.84  5147.7  328.60  5173.0  328.55
  5187.4  329.90  5208.9  328.11  5290.0  328.97  5362.8  325.54  5567.4  326.91
#Mann=6,-1,0
  3169.3    0.05       0  3648.2    0.08       0  3747.4    0.05       0
  4473.2     0.1       0  4750.9    0.07       0  4757.3     0.1       0
Bank Sta=4750.9,4757.3
Exp/Cntr=0.3,0.1

Type RM Length L Ch R = 1,1531,450,450,450
BEGIN DESCRIPTION:
Mapping XS 8fc972a6
END DESCRIPTION:
XS GIS Cut Line= 4
      2083775.01     13429932.39      2083709.07     13428192.29
      2083643.97     13428030.84      2083489.21     13427717.51
#Sta/Elev= 30
  3188.3  329.16  3716.1  325.22  3866.2  326.54  4276.5  325.11  4493.6  325.93
  4516.6  326.29  4636.4  325.05  4676.8  325.83  4716.8  325.03  4746.8  326.95
  4756.8  326.80  4796.8  323.52  4896.9  317.55  4925.8  313.77  4959.2  310.85
  4998.9  309.71  4999.4  308.91  5004.8  308.91  5005.3  309.71  5007.5  310.64
  5055.8  313.36  5061.2  314.56  5090.7  317.54  5136.7  320.73  5220.9  323.27
  5248.9  324.80  5344.5  325.33  5366.8  326.30  5422.5  326.37  5453.2  325.32
#Mann=4,-1,0
  3188.3    0.05       0  4493.6     0.1       0  4998.9    0.07       0
  5005.3     0.1       0
Bank Sta=4998.9,5005.3
Exp/Cntr=0.3,0.1

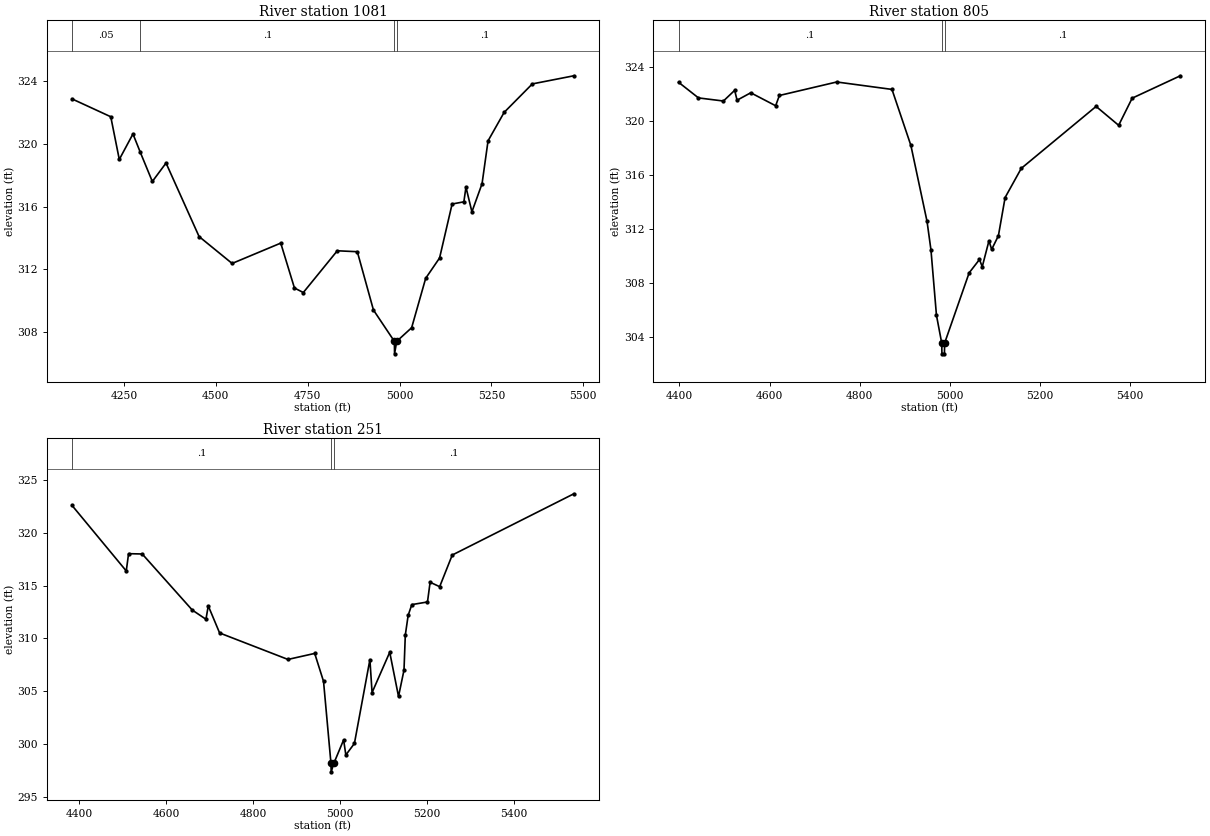
Type RM Length L Ch R = 1,1081,276,276,276
BEGIN DESCRIPTION:
Mapping XS b2e75dd0
END DESCRIPTION:
XS GIS Cut Line= 4
      2084358.82     13428707.54      2084184.33     13427965.30
      2083815.39     13427767.32      2083645.10     13427697.04
#Sta/Elev= 30
  4108.8  322.88  4214.1  321.74  4237.3  319.01  4274.5  320.64  4294.6  319.46
  4327.2  317.60  4364.5  318.78  4454.4  314.08  4544.3  312.36  4676.6  313.66
  4713.9  310.79  4738.0  310.50  4830.5  313.17  4885.0  313.11  4928.9  309.38
  4985.8  307.38  4986.3  306.58  4992.2  307.38  5032.8  308.25  5071.0  311.41
  5108.8  312.71  5142.9  316.16  5174.9  316.30  5180.6  317.24  5196.8  315.66
  5224.4  317.46  5240.7  320.20  5284.5  322.02  5361.2  323.84  5474.2  324.36
#Mann=4,-1,0
  4108.8    0.05       0  4294.6     0.1       0  4985.8    0.07       0
  4992.2     0.1       0
Bank Sta=4985.8,4992.2
Exp/Cntr=0.3,0.1

Type RM Length L Ch R = 1,805,554,554,554
BEGIN DESCRIPTION:
Mapping XS ee6faa63
END DESCRIPTION:
XS GIS Cut Line= 4
      2084494.23     13428204.89      2084330.60     13427765.21
      2084081.47     13427595.07      2083738.19     13427613.64
#Sta/Elev= 30
  4397.9  322.85  4442.2  321.69  4497.6  321.46  4522.6  322.25  4527.9  321.52
  4558.3  322.07  4613.6  321.11  4621.9  321.87  4749.3  322.87  4872.0  322.32
  4914.0  318.17  4949.9  312.54  4958.6  310.43  4970.8  305.59  4982.5  303.53
  4983.0  302.73  4988.5  302.73  4989.0  303.53  5043.4  308.73  5066.4  309.72
  5072.5  309.18  5087.4  311.10  5093.5  310.47  5108.4  311.48  5123.3  314.31
  5159.2  316.47  5325.4  321.06  5375.5  319.66  5405.5  321.67  5512.5  323.33
#Mann=3,-1,0
  4397.9     0.1       0  4982.5    0.07       0  4989.0     0.1       0
Bank Sta=4982.5,4989
Exp/Cntr=0.3,0.1

Type RM Length L Ch R = 1,251,0,0,0
BEGIN DESCRIPTION:
UNT 117 in Lagunillas Cr Wtrshd 1.0
END DESCRIPTION:
XS GIS Cut Line= 4
      2084460.37     13427816.84      2084298.92     13427340.30
      2084044.99     13427297.33      2083719.08     13427516.79
#Sta/Elev= 30
  4384.1  322.60  4508.7  316.39  4514.0  318.03  4545.4  318.00  4660.5  312.68
  4691.9  311.81  4697.2  313.08  4723.3  310.51  4880.4  308.00  4941.9  308.57
  4962.2  305.92  4979.3  298.14  4979.8  297.34  4985.8  298.14  5008.4  300.37
  5013.5  298.94  5033.2  300.03  5068.8  307.98  5073.8  304.86  5114.4  308.68
  5134.6  304.49  5147.2  306.99  5150.2  310.31  5156.8  312.19  5165.2  313.20
  5201.2  313.45  5207.2  315.32  5229.2  314.90  5258.1  317.90  5537.7  323.71
#Mann=3,-1,0
  4384.1     0.1       0  4979.3    0.07       0  4985.8     0.1       0
Bank Sta=4979.3,4985.8
Exp/Cntr=0.3,0.1

Chan Stop Cuts=-1