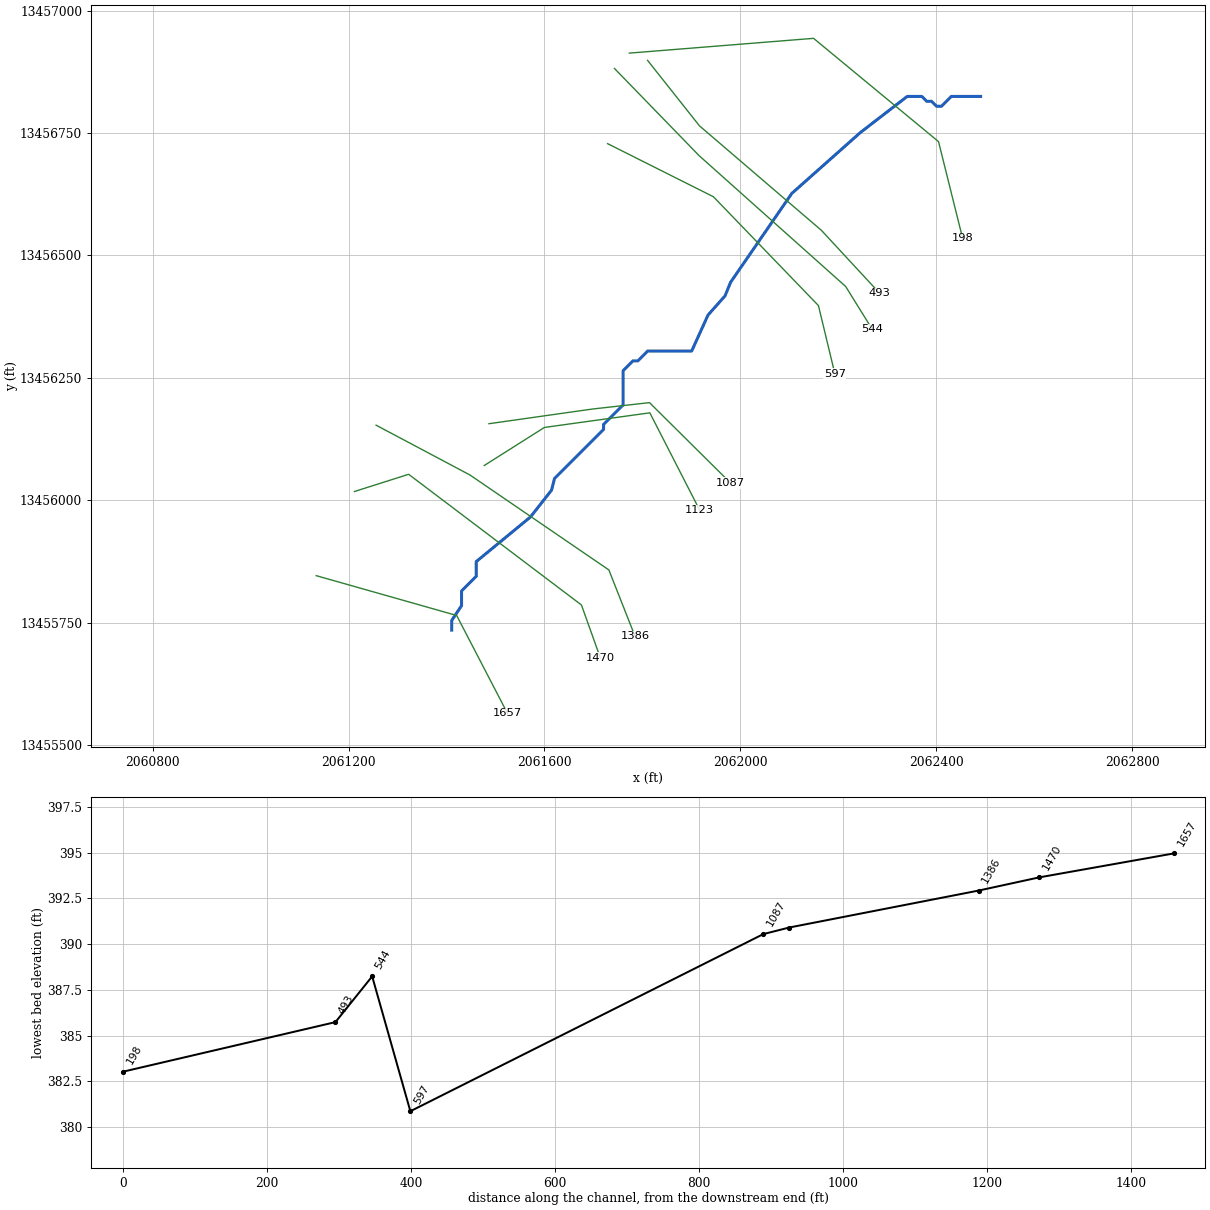
--- UNT 119 in Lagunillas Cr Wtrshd.prj (project) ---

Proj Title=UNT 119 in Lagunillas Cr Wtrshd Base Level Engineering
Current Plan=p01
Default Exp/Contr=0.3,0.1
English Units
Geom File=g01
Flow File=f01
Plan File=p01
BEGIN DESCRIPTION:
UNT 119 in Lagunillas Cr Wtrshd
END DESCRIPTION:

--- UNT 119 in Lagunillas Cr Wtrshd.p01 (plan) ---

Plan Title=Multiple Run
Short Identifier=Multiple
Geom File=g01
Flow File=f01
Subcritical Flow
K Sum by GR= 0
Std Step Tol= 0.01
Critical Tol= 0.01
Num of Std Step Trials= 20
Max Error Tol= 0.3
Flow Tol Ratio= 0.001
Split Flow NTrial= 30
Split Flow Tol= 0.02
Split Flow Ratio= 0.02
Log Output Level= 0
Friction Slope Method= 1
Unsteady Friction Slope Method= 2
Unsteady Bridges Friction Slope Method= 1
Parabolic Critical Depth
Global Vel Dist=  1 , 1 , 1
Global Log Level= 0
CheckData=True
Encroach Param= -1, 0, 0, 0
BEGIN DESCRIPTION:
Multiple Run
END DESCRIPTION:

--- UNT 119 in Lagunillas Cr Wtrshd.f01 (steady flow) ---

Flow Title=Multiple
Number of Profiles=7
Profile Names=10-year,25-year,50-year,1pct_min,100-year,1pct_plu,500-year
River Rch & RM= UNT 119 in Lagun,Reach-1,1657
      64      82      96      56     112     223     155
Boundary for River Rch & Prof#=UNT 119 in Lagun,Reach-1,1
Up Type=0
Dn Type=3
Dn Slope=0.005
Boundary for River Rch & Prof#=UNT 119 in Lagun,Reach-1,2
Up Type=0
Dn Type=3
Dn Slope=0.005
Boundary for River Rch & Prof#=UNT 119 in Lagun,Reach-1,3
Up Type=0
Dn Type=3
Dn Slope=0.005
Boundary for River Rch & Prof#=UNT 119 in Lagun,Reach-1,4
Up Type=0
Dn Type=3
Dn Slope=0.005
Boundary for River Rch & Prof#=UNT 119 in Lagun,Reach-1,5
Up Type=0
Dn Type=3
Dn Slope=0.005
Boundary for River Rch & Prof#=UNT 119 in Lagun,Reach-1,6
Up Type=0
Dn Type=3
Dn Slope=0.005
Boundary for River Rch & Prof#=UNT 119 in Lagun,Reach-1,7
Up Type=0
Dn Type=3
Dn Slope=0.005

--- UNT 119 in Lagunillas Cr Wtrshd.g01 (geometry) ---

Geom Title=Existing Conditions

River Reach=UNT 119 in Lagun,Reach-1
Reach XY= 30
      2061410.80     13455734.54      2061410.80     13455754.54
      2061430.80     13455784.54      2061430.80     13455814.54
      2061460.80     13455844.54      2061460.80     13455874.54
      2061571.49     13455965.62      2061614.46     13456020.30
      2061620.80     13456044.54      2061720.80     13456144.54
      2061720.80     13456154.54      2061760.80     13456194.54
      2061760.80     13456264.54      2061780.80     13456284.54
      2061790.80     13456284.54      2061810.80     13456304.54
      2061900.80     13456304.54      2061934.20     13456378.20
      2061968.92     13456417.26      2061980.20     13456445.04
      2062105.20     13456626.46      2062244.96     13456750.59
      2062340.80     13456824.54      2062370.80     13456824.54
      2062380.80     13456814.54      2062390.80     13456814.54
      2062400.80     13456804.54      2062410.80     13456804.54
      2062430.80     13456824.54      2062490.80     13456824.54

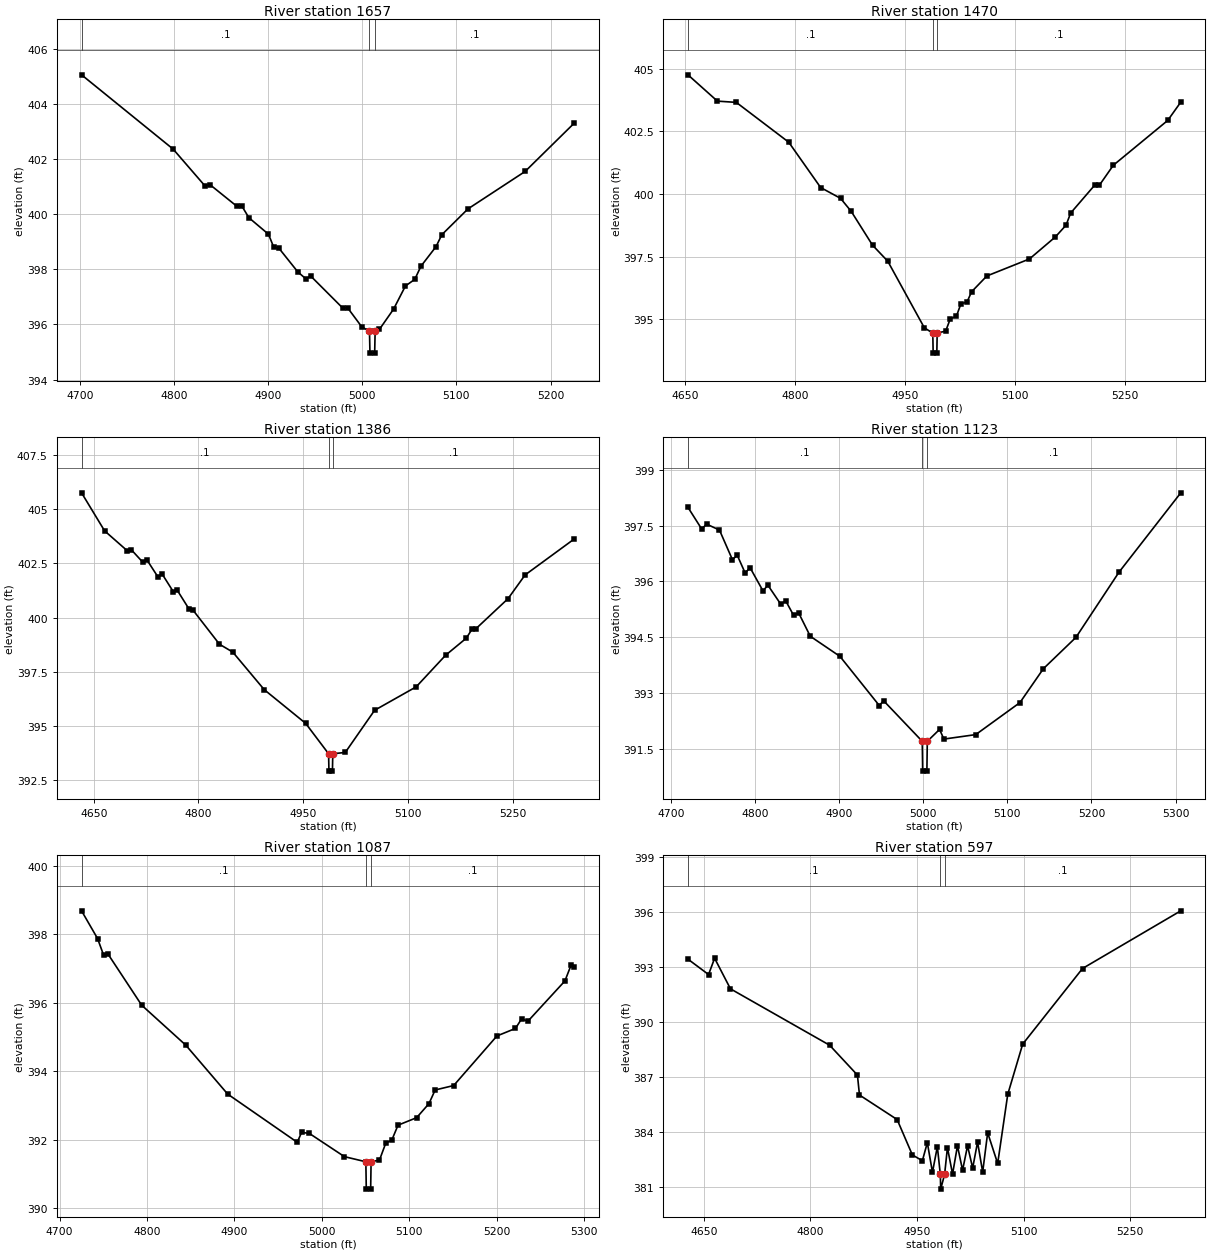
Type RM Length L Ch R = 1,1657,187,187,187
BEGIN DESCRIPTION:
UNT 119 in Lagunillas Cr Wtrshd 2.0
END DESCRIPTION:
XS GIS Cut Line= 3
      2061134.01     13455845.86      2061420.80     13455764.54
      2061524.64     13455564.59
#Sta/Elev= 30
  4701.9  405.07  4799.2  402.37  4833.1  401.03  4838.3  401.08  4867.0  400.29
  4872.2  400.30  4879.6  399.88  4900.4  399.28  4906.1  398.80  4911.3  398.78
  4931.6  397.91  4940.1  397.66  4945.3  397.76  4979.2  396.60  4984.4  396.61
  4999.6  395.91  5007.7  395.76  5008.2  394.96  5013.2  394.96  5013.7  395.76
  5018.2  395.82  5033.3  396.56  5045.9  397.40  5055.8  397.64  5062.4  398.12
  5078.4  398.83  5084.5  399.26  5112.3  400.20  5173.0  401.56  5225.3  403.32
#Mann=3,-1,0
  4701.9     0.1       0  5007.7    0.07       0  5013.7     0.1       0
Bank Sta=5007.7,5013.7
Exp/Cntr=0.3,0.1

Type RM Length L Ch R = 1,1470,84,84,84
BEGIN DESCRIPTION:
Mapping XS a296f10a
END DESCRIPTION:
XS GIS Cut Line= 4
      2061212.11     13456017.70      2061322.79     13456052.85
      2061675.66     13455785.93      2061714.10     13455678.27
#Sta/Elev= 30
  4653.6  404.76  4693.8  403.71  4719.6  403.66  4791.2  402.07  4834.8  400.26
  4861.9  399.83  4876.5  399.31  4905.6  397.96  4926.4  397.32  4976.4  394.66
  4987.9  394.45  4988.4  393.65  4993.4  393.65  4993.9  394.45  5005.5  394.53
  5011.8  395.02  5020.1  395.12  5026.3  395.62  5034.6  395.69  5040.9  396.10
  5061.7  396.73  5119.9  397.41  5155.3  398.29  5169.9  398.76  5176.1  399.24
  5208.8  400.35  5215.3  400.35  5234.4  401.15  5308.7  402.94  5326.5  403.67
#Mann=3,-1,0
  4653.6     0.1       0  4987.9    0.07       0  4993.9     0.1       0
Bank Sta=4987.9,4993.9
Exp/Cntr=0.3,0.1

Type RM Length L Ch R = 1,1386,263,263,263
BEGIN DESCRIPTION:
Mapping XS ca3adedd
END DESCRIPTION:
XS GIS Cut Line= 4
      2061256.43     13456153.09      2061447.79     13456051.55
      2061731.65     13455857.54      2061785.03     13455722.14
#Sta/Elev= 30
  4632.6  405.74  4665.6  403.99  4698.2  403.07  4703.9  403.12  4720.2  402.55
  4725.9  402.67  4742.2  401.86  4747.9  402.01  4764.2  401.18  4769.8  401.25
  4786.2  400.41  4791.8  400.36  4830.2  398.77  4849.2  398.41  4894.3  396.68
  4953.6  395.13  4986.5  393.73  4987.0  392.93  4992.0  392.93  4992.5  393.73
  5010.4  393.79  5052.4  395.73  5112.0  396.81  5154.0  398.26  5183.8  399.05
  5192.1  399.47  5197.1  399.47  5243.6  400.87  5268.0  401.96  5338.6  403.62
#Mann=3,-1,0
  4632.6     0.1       0  4986.5    0.07       0  4992.5     0.1       0
Bank Sta=4986.5,4992.5
Exp/Cntr=0.3,0.1

Type RM Length L Ch R = 1,1123,36,36,36
BEGIN DESCRIPTION:
Mapping XS 7fc488e0
END DESCRIPTION:
XS GIS Cut Line= 4
      2061477.09     13456070.74      2061600.02     13456148.53
      2061815.30     13456178.39      2061917.13     13455979.56
#Sta/Elev= 30
  4720.0  397.99  4736.3  397.41  4742.2  397.54  4757.5  397.38  4772.8  396.59
  4778.7  396.70  4788.0  396.23  4793.9  396.37  4809.2  395.75  4815.1  395.90
  4830.4  395.39  4836.3  395.48  4845.7  395.09  4851.6  395.16  4865.5  394.53
  4900.8  393.99  4947.6  392.67  4952.7  392.80  4998.7  391.71  4999.2  390.91
  5004.2  390.91  5004.7  391.71  5019.3  392.03  5024.4  391.77  5062.3  391.89
  5114.9  392.75  5142.8  393.66  5181.5  394.50  5232.7  396.25  5306.2  398.38
#Mann=3,-1,0
  4720.0     0.1       0  4998.7    0.07       0  5004.7     0.1       0
Bank Sta=4998.7,5004.7
Exp/Cntr=0.3,0.1

Type RM Length L Ch R = 1,1087,490,490,490
BEGIN DESCRIPTION:
Mapping XS 16717272
END DESCRIPTION:
XS GIS Cut Line= 4
      2061486.86     13456156.17      2061697.24     13456186.03
      2061814.60     13456199.22      2061980.27     13456034.94
#Sta/Elev= 30
  4725.1  398.69  4743.4  397.88  4750.4  397.39  4755.5  397.42  4793.9  395.93
  4844.4  394.76  4892.3  393.33  4971.9  391.92  4976.9  392.21  4985.7  392.18
  5025.9  391.50  5050.4  391.35  5050.9  390.55  5055.9  390.55  5056.4  391.35
  5066.0  391.40  5073.1  391.89  5080.2  391.99  5087.2  392.42  5108.5  392.64
  5122.6  393.05  5129.7  393.45  5150.9  393.58  5200.4  395.03  5221.6  395.25
  5228.6  395.53  5235.8  395.46  5278.2  396.64  5285.2  397.10  5289.0  397.04
#Mann=3,-1,0
  4725.1     0.1       0  5050.4    0.07       0  5056.4     0.1       0
Bank Sta=5050.4,5056.4
Exp/Cntr=0.3,0.1

Type RM Length L Ch R = 1,597,53,53,53
BEGIN DESCRIPTION:
Mapping XS 7f0a7d2f
END DESCRIPTION:
XS GIS Cut Line= 4
      2061729.09     13456728.12      2061945.20     13456619.63
      2062159.61     13456397.41      2062193.08     13456258.39
#Sta/Elev= 30
  4627.7  393.43  4656.7  392.59  4665.2  393.48  4687.5  391.81  4827.1  388.73
  4866.2  387.10  4869.1  386.01  4922.1  384.67  4943.5  382.74  4957.6  382.42
  4964.6  383.41  4971.8  381.79  4978.7  383.19  4982.9  381.67  4983.4  380.87
  4988.9  381.67  4992.9  383.14  5000.1  381.69  5007.0  383.24  5014.2  381.90
  5021.2  383.24  5028.4  382.02  5035.3  383.44  5042.5  381.80  5049.5  383.95
  5063.6  382.27  5077.8  386.05  5098.8  388.79  5183.0  392.92  5321.3  396.07
#Mann=3,-1,0
  4627.7     0.1       0  4982.9    0.07       0  4988.9     0.1       0
Bank Sta=4982.9,4988.9
Exp/Cntr=0.3,0.1

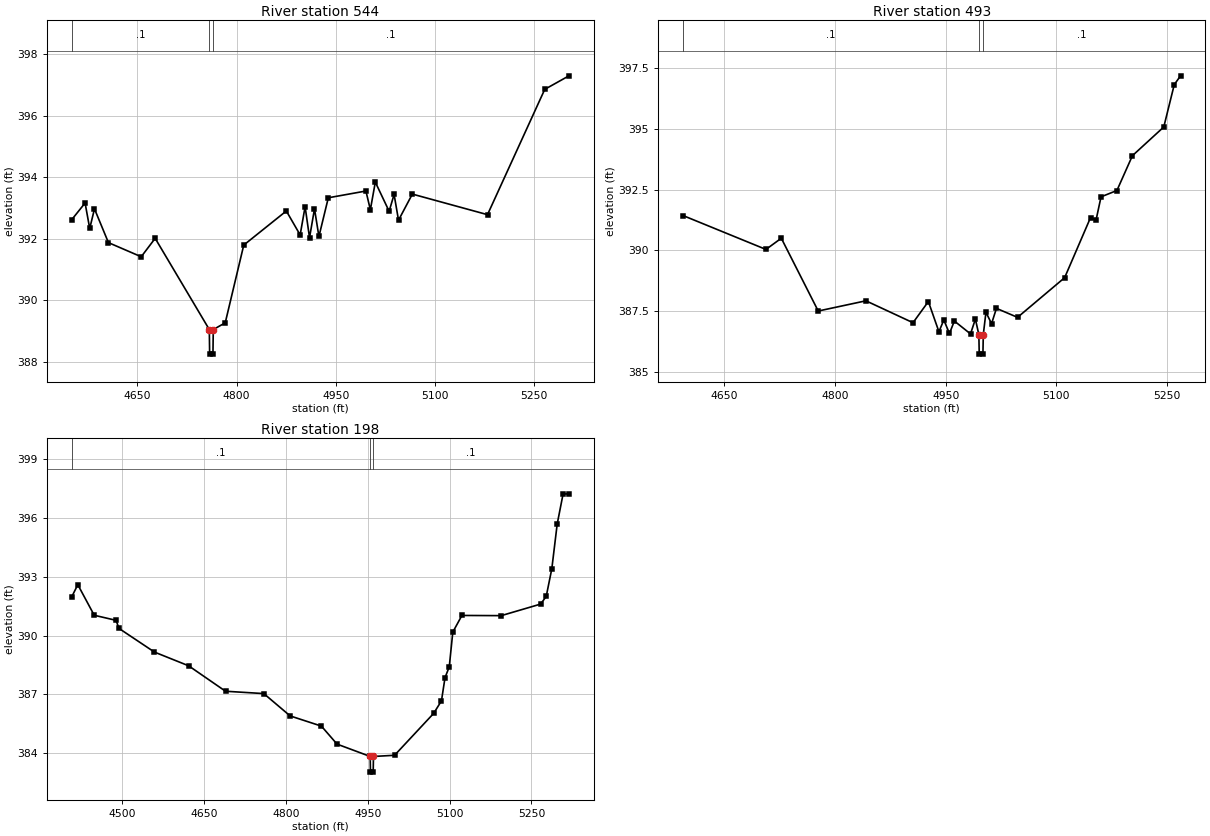
Type RM Length L Ch R = 1,544,51,51,51
BEGIN DESCRIPTION:
Mapping XS b3846c9d
END DESCRIPTION:
XS GIS Cut Line= 4
      2061742.91     13456881.82      2061915.69     13456703.84
      2062215.17     13456436.47      2062269.47     13456349.08
#Sta/Elev= 30
  4550.4  392.61  4570.9  393.16  4577.9  392.33  4585.1  392.97  4606.2  391.87
  4655.8  391.41  4676.9  392.01  4758.8  389.04  4759.3  388.24  4764.3  388.24
  4764.8  389.04  4782.9  389.26  4810.9  391.79  4875.3  392.90  4896.2  392.12
  4903.7  393.04  4910.4  392.03  4917.9  392.97  4924.6  392.07  4938.8  393.33
  4995.7  393.55  5002.4  392.94  5009.9  393.84  5030.8  392.89  5038.3  393.44
  5045.0  392.60  5065.9  393.45  5179.6  392.78  5266.2  396.86  5302.8  397.30
#Mann=3,-1,0
  4550.4     0.1       0  4758.8    0.07       0  4764.8     0.1       0
Bank Sta=4758.8,4764.8
Exp/Cntr=0.3,0.1

Type RM Length L Ch R = 1,493,295,295,295
BEGIN DESCRIPTION:
Mapping XS be1ec6b0
END DESCRIPTION:
XS GIS Cut Line= 4
      2061810.63     13456898.30      2061916.56     13456764.60
      2062165.69     13456551.06      2062284.63     13456422.56
#Sta/Elev= 30
  4594.4  391.43  4706.6  390.04  4727.4  390.50  4777.4  387.51  4842.0  387.93
  4905.8  387.03  4926.6  387.90  4940.9  386.66  4947.5  387.14  4955.2  386.59
  4961.8  387.10  4983.7  386.57  4990.3  387.18  4995.0  386.54  4995.5  385.74
  5000.5  385.74  5001.0  386.54  5004.6  387.46  5012.2  386.99  5018.8  387.62
  5047.4  387.25  5111.2  388.88  5146.3  391.35  5153.7  391.24  5160.5  392.20
  5182.0  392.46  5203.0  393.89  5245.5  395.07  5259.7  396.81  5268.2  397.17
#Mann=3,-1,0
  4594.4     0.1       0  4995.0    0.07       0  5001.0     0.1       0
Bank Sta=4995,5001
Exp/Cntr=0.3,0.1

Type RM Length L Ch R = 1,198,0,0,0
BEGIN DESCRIPTION:
UNT 119 in Lagunillas Cr Wtrshd 1.0
END DESCRIPTION:
XS GIS Cut Line= 4
      2061773.51     13456913.03      2062149.63     13456943.20
      2062404.84     13456732.26      2062454.11     13456534.53
#Sta/Elev= 30
  4406.6  391.96  4418.1  392.60  4448.2  391.04  4488.3  390.78  4493.5  390.37
  4558.6  389.16  4621.3  388.46  4689.0  387.16  4759.2  387.04  4807.5  385.90
  4864.8  385.38  4893.5  384.46  4954.3  383.83  4954.8  383.03  4959.8  383.03
  4960.3  383.83  4999.0  383.89  5070.7  386.03  5085.0  386.67  5091.5  387.85
  5099.3  388.41  5105.8  390.18  5122.5  391.03  5194.6  391.02  5266.8  391.61
  5277.1  392.00  5287.4  393.42  5297.2  395.69  5308.0  397.23  5318.8  397.24
#Mann=3,-1,0
  4406.6     0.1       0  4954.3    0.07       0  4960.3     0.1       0
Bank Sta=4954.3,4960.3
Exp/Cntr=0.3,0.1

Chan Stop Cuts=-1