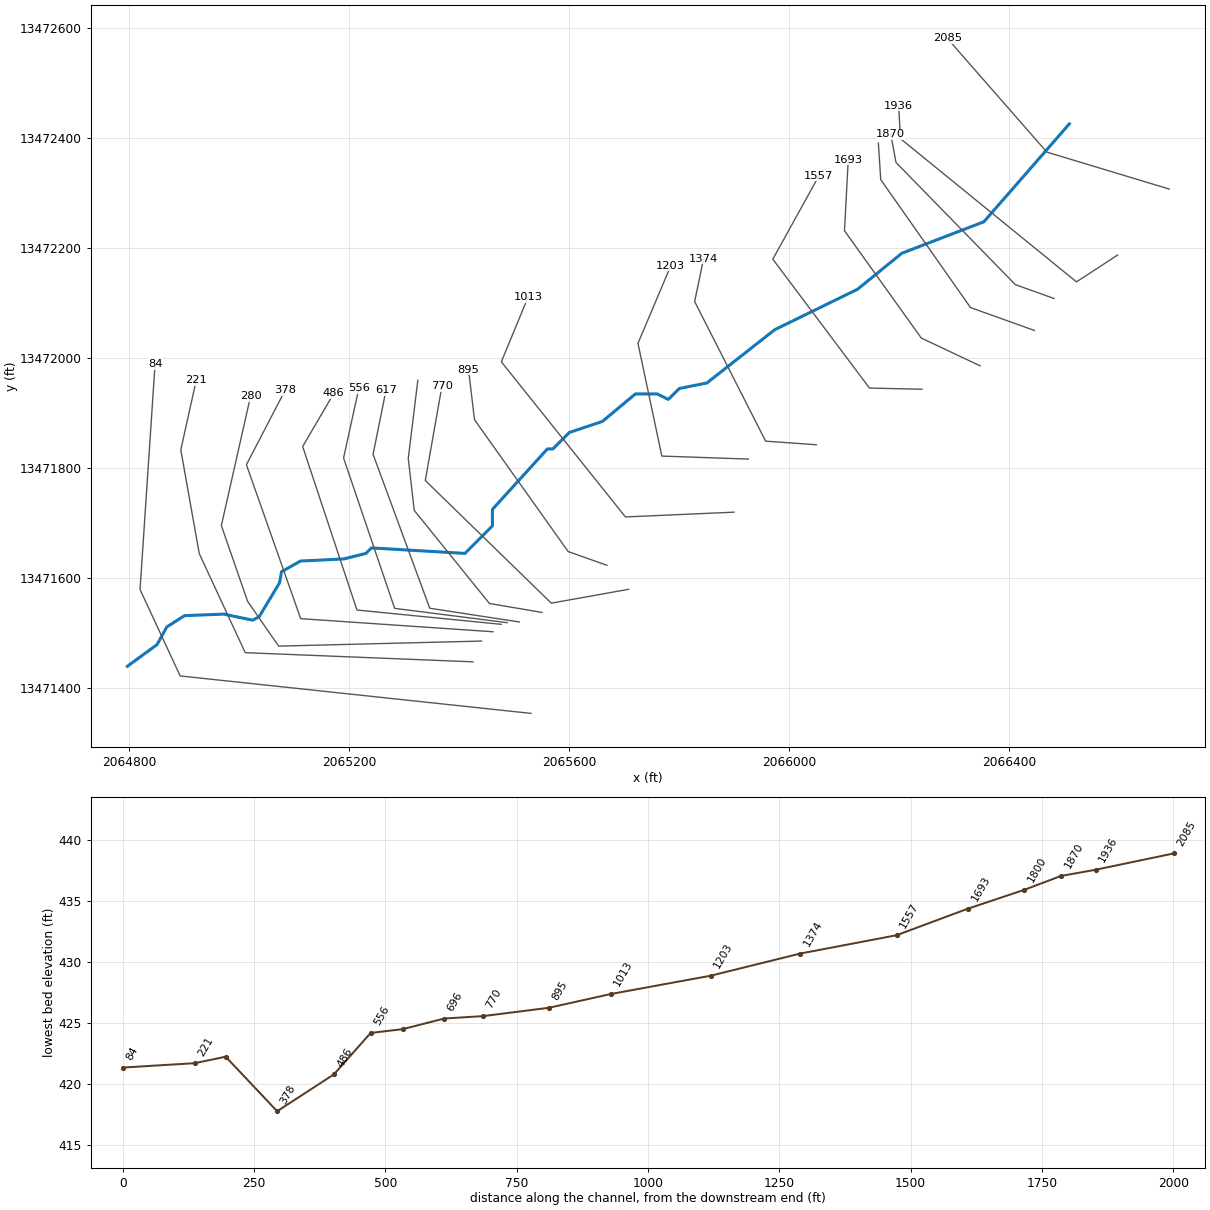
--- UNT 121 in Lagunillas Cr Wtrshd.prj (project) ---

Proj Title=UNT 121 in Lagunillas Cr Wtrshd Base Level Engineering
Current Plan=p01
Default Exp/Contr=0.3,0.1
English Units
Geom File=g01
Flow File=f01
Plan File=p01
Y Axis Title=Elevation
X Axis Title(PF)=Main Channel Distance
X Axis Title(XS)=Station
BEGIN DESCRIPTION:
UNT 121 in Lagunillas Cr Wtrshd
END DESCRIPTION:
DSS Export Rating Curves= 0
DSS Export Rating Curve Sorted= 0
DSS Export Volume Flow Curves= 0
DXF OffsetX= 0
DXF OffsetY= 0
DXF ScaleX= 1
DXF ScaleY= 10

--- UNT 121 in Lagunillas Cr Wtrshd.p01 (plan) ---

Plan Title=Multiple Run
Short Identifier=Multiple
Geom File=g01
Flow File=f01
Subcritical Flow
K Sum by GR= 0
Std Step Tol= 0.01
Critical Tol= 0.01
Num of Std Step Trials= 20
Max Error Tol= 0.3
Flow Tol Ratio= 0.001
Split Flow NTrial= 30
Split Flow Tol= 0.02
Split Flow Ratio= 0.02
Log Output Level= 0
Friction Slope Method= 1
Unsteady Friction Slope Method= 2
Unsteady Bridges Friction Slope Method= 1
Parabolic Critical Depth
Global Vel Dist=  1 , 1 , 1
Global Log Level= 0
CheckData=True
Encroach Param= -1, 0, 0, 0
BEGIN DESCRIPTION:
Multiple Run
END DESCRIPTION:

--- UNT 121 in Lagunillas Cr Wtrshd.f01 (steady flow) ---

Flow Title=Multiple
Number of Profiles=7
Profile Names=10-year,25-year,50-year,1pct_min,100-year,1pct_plu,500-year
River Rch & RM= UNT 121 in Lagun,Reach-1,2085
      44      54      62      35      71     141      94
Boundary for River Rch & Prof#=UNT 121 in Lagun,Reach-1,1
Up Type=0
Dn Type=3
Dn Slope=0.005
Boundary for River Rch & Prof#=UNT 121 in Lagun,Reach-1,2
Up Type=0
Dn Type=3
Dn Slope=0.005
Boundary for River Rch & Prof#=UNT 121 in Lagun,Reach-1,3
Up Type=0
Dn Type=3
Dn Slope=0.005
Boundary for River Rch & Prof#=UNT 121 in Lagun,Reach-1,4
Up Type=0
Dn Type=3
Dn Slope=0.005
Boundary for River Rch & Prof#=UNT 121 in Lagun,Reach-1,5
Up Type=0
Dn Type=3
Dn Slope=0.005
Boundary for River Rch & Prof#=UNT 121 in Lagun,Reach-1,6
Up Type=0
Dn Type=3
Dn Slope=0.005
Boundary for River Rch & Prof#=UNT 121 in Lagun,Reach-1,7
Up Type=0
Dn Type=3
Dn Slope=0.005

--- UNT 121 in Lagunillas Cr Wtrshd.g01 (geometry) ---

Geom Title=Existing Conditions
Program Version=5.05

River Reach=UNT 121 in Lagun,Reach-1
Reach XY= 30
      2066510.03     13472425.65      2066354.64      13472247.7
      2066205.34      13472190.4        2066125.       13472125.
      2065974.44     13472051.52       2065850.8     13471954.54
       2065800.8     13471944.54       2065780.8     13471924.54
       2065760.8     13471934.54       2065720.8     13471934.54
       2065660.8     13471884.54       2065600.8     13471864.54
       2065570.8     13471834.54       2065560.8     13471834.54
       2065460.8     13471724.54       2065460.8     13471694.54
       2065410.8     13471644.54       2065240.8     13471654.54
       2065230.8     13471644.54       2065190.8     13471634.54
       2065111.9     13471630.67      2065077.18     13471611.23
       2065073.7     13471591.09       2065036.9     13471529.98
      2065025.09     13471523.03      2064972.31     13471534.14
      2064900.79     13471531.37      2064868.62     13471510.79
      2064850.79     13471478.59      2064796.83     13471439.23

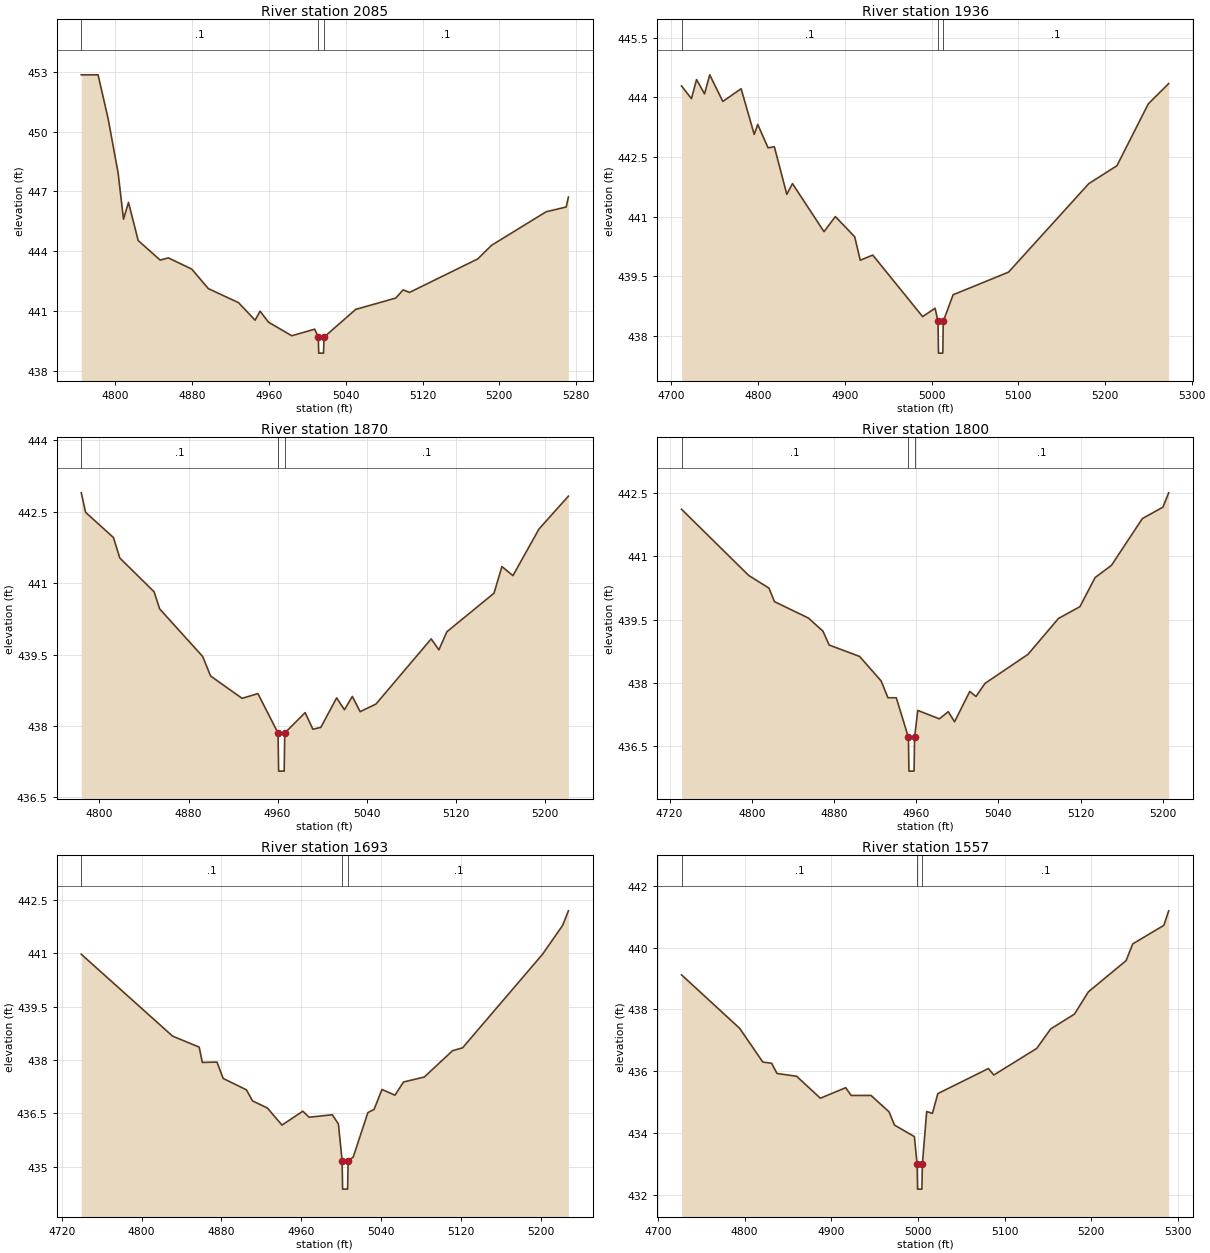
Type RM Length L Ch R = 1 ,2085    ,149,149,149
BEGIN DESCRIPTION:
UNT 121 in Lagunillas Cr Wtrshd 6.0
END DESCRIPTION:
XS GIS Cut Line= 3
      2066691.79     13472307.21      2066469.18     13472374.38
       2066288.1     13472581.32
#Sta/Elev= 30
  4764.5  452.84    4782  452.84  4792.5  450.64  4802.9  447.92  4808.5  445.61
  4813.7  446.45  4823.8  444.54  4846.7  443.56  4855.2  443.67  4879.6  443.11
  4896.9  442.13  4928.3  441.43  4945.6  440.55  4950.8     441  4959.6  440.45
  4983.8  439.77  5007.7   440.1  5011.4   439.7  5011.9   438.9  5016.9   438.9
  5017.4   439.7  5050.4  441.09  5092.2  441.66  5099.8  442.07  5106.4  441.94
  5177.6  443.62  5191.9   444.3  5248.8  445.98  5269.7  446.22    5272  446.72
#Mann= 3 ,-1 , 0
  4764.5      .1       0  5011.4     .07       0  5017.4      .1       0
Bank Sta=5011.4,5017.4
XS Rating Curve= 0 ,0
Exp/Cntr=0.3,0.1

Type RM Length L Ch R = 1 ,1936    ,66,66,66
BEGIN DESCRIPTION:
Mapping XS 56bdfc22
END DESCRIPTION:
XS GIS Cut Line= 4
      2066597.97     13472187.24      2066523.07     13472138.39
      2066202.97     13472398.81      2066199.72     13472458.45
#Sta/Elev= 30
  4711.7  444.29  4723.1  443.97    4729  444.45  4738.2  444.09  4744.2  444.57
  4759.3   443.9  4780.4  444.22  4795.5  443.07  4799.6  443.32  4811.5  442.73
  4818.7  442.76  4833.1  441.56  4839.6  441.83    4876  440.62  4889.1     441
  4911.4  440.49  4917.8   439.9  4932.2  440.03  4989.7  438.48  5004.1  438.69
  5007.5  438.36    5008  437.56    5013  437.56  5013.5  438.36  5024.9  439.03
  5088.8   439.6  5181.4  441.83  5213.8  442.28    5250  443.84  5273.5  444.35
#Mann= 3 ,-1 , 0
  4711.7      .1       0  5007.5     .07       0  5013.5      .1       0
Bank Sta=5007.5,5013.5
XS Rating Curve= 0 ,0
Exp/Cntr=0.3,0.1

Type RM Length L Ch R = 1 ,1870    ,70,70,70
BEGIN DESCRIPTION:
Mapping XS 676120bb
END DESCRIPTION:
XS GIS Cut Line= 4
       2066482.2     13472108.18      2066411.87     13472133.36
      2066194.86     13472355.58      2066185.31     13472406.79
#Sta/Elev= 30
  4783.7   442.9  4787.6  442.49  4812.6  441.96  4818.3  441.53  4849.1  440.82
  4854.1  440.46  4892.7  439.46  4899.8  439.05  4928.1  438.58  4942.3  438.68
  4960.4  437.85  4960.9  437.05  4965.9  437.05  4966.4  437.85  4984.7  438.28
  4991.7  437.93  4998.8  437.97    5013  438.59    5020  438.34  5027.1  438.62
  5034.1   438.3  5048.3  438.46  5097.9  439.83  5104.8   439.6    5112  439.98
  5154.3  440.79  5161.4  441.35  5171.3  441.16  5194.7  442.14  5221.1  442.83
#Mann= 3 ,-1 , 0
  4783.7      .1       0  4960.4     .07       0  4966.4      .1       0
Bank Sta=4960.4,4966.4
XS Rating Curve= 0 ,0
Exp/Cntr=0.3,0.1

Type RM Length L Ch R = 1 ,1800    ,107,107,107
BEGIN DESCRIPTION:
Mapping XS 8d73b1a1
END DESCRIPTION:
XS GIS Cut Line= 4
      2066446.57     13472050.03      2066330.28     13472091.69
      2066167.08     13472324.33      2066162.78     13472390.58
#Sta/Elev= 30
  4731.7  442.12  4797.1  440.55  4816.8  440.25  4822.1  439.93  4855.2  439.54
  4869.3  439.23  4875.4   438.9    4905  438.63  4925.9  438.05  4932.6  437.65
  4940.7  437.65  4952.5  436.71    4953  435.91    4958  435.91  4958.5  436.71
  4961.6  437.35  4982.6  437.15  4991.3  437.32  4997.4  437.08  5012.2   437.8
  5018.3  437.68    5027  437.99  5068.9  438.68  5098.5  439.53  5119.4  439.81
  5134.2   440.5  5150.1  440.79  5180.2   441.9  5200.2  442.17  5205.8  442.51
#Mann= 3 ,-1 , 0
  4731.7      .1       0  4952.5     .07       0  4958.5      .1       0
Bank Sta=4952.5,4958.5
XS Rating Curve= 0 ,0
Exp/Cntr=0.3,0.1

Type RM Length L Ch R = 1 ,1693    ,136,136,136
BEGIN DESCRIPTION:
Mapping XS 2002aa6e
END DESCRIPTION:
XS GIS Cut Line= 4
      2066347.65     13471985.78      2066240.87     13472036.14
      2066101.11     13472231.45      2066108.01     13472360.84
#Sta/Elev= 30
  4739.6  440.97    4831  438.67  4857.7  438.36  4860.8  437.93  4875.5  437.94
  4881.7  437.48    4905  437.16  4911.1  436.85  4925.9  436.65  4940.6  436.17
  4961.5  436.56  4967.7  436.39    4991  436.46  4997.1   436.2  5000.8  435.17
  5001.3  434.37  5006.3  434.37  5006.8  435.17  5011.9  435.27  5026.6  436.52
  5032.8  436.61  5040.7  437.17  5053.7  437.01  5062.3  437.38  5083.1  437.52
  5111.4  438.26  5121.4  438.34  5201.5  440.97  5221.6  441.78  5227.4  442.19
#Mann= 3 ,-1 , 0
  4739.6      .1       0  5000.8     .07       0  5006.8      .1       0
Bank Sta=5000.8,5006.8
XS Rating Curve= 0 ,0
Exp/Cntr=0.3,0.1

Type RM Length L Ch R = 1 ,1557    ,183,183,183
BEGIN DESCRIPTION:
Mapping XS 9b83d546
END DESCRIPTION:
XS GIS Cut Line= 4
      2066241.99     13471943.08      2066146.55     13471945.25
      2065970.77     13472179.62      2066054.69     13472331.32
#Sta/Elev= 30
  4727.4  439.12  4794.4  437.39  4821.1   436.3  4831.3  436.26  4837.5  435.93
  4860.1  435.84  4887.5  435.13  4916.7  435.47    4923  435.22  4945.9  435.22
  4966.7  434.69    4973  434.26  4995.9  433.89  4999.1  432.99  4999.6  432.19
  5004.6  432.19  5005.1  432.99  5010.1   434.7  5016.7  434.64    5023  435.28
  5081.3  436.09  5087.5  435.88    5137  436.74  5153.1  437.37  5180.5  437.85
  5196.6  438.57  5240.1  439.58  5247.7  440.12  5283.6  440.72  5289.2  441.19
#Mann= 3 ,-1 , 0
  4727.4      .1       0  4999.1     .07       0  5005.1      .1       0
Bank Sta=4999.1,5005.1
XS Rating Curve= 0 ,0
Exp/Cntr=0.3,0.1

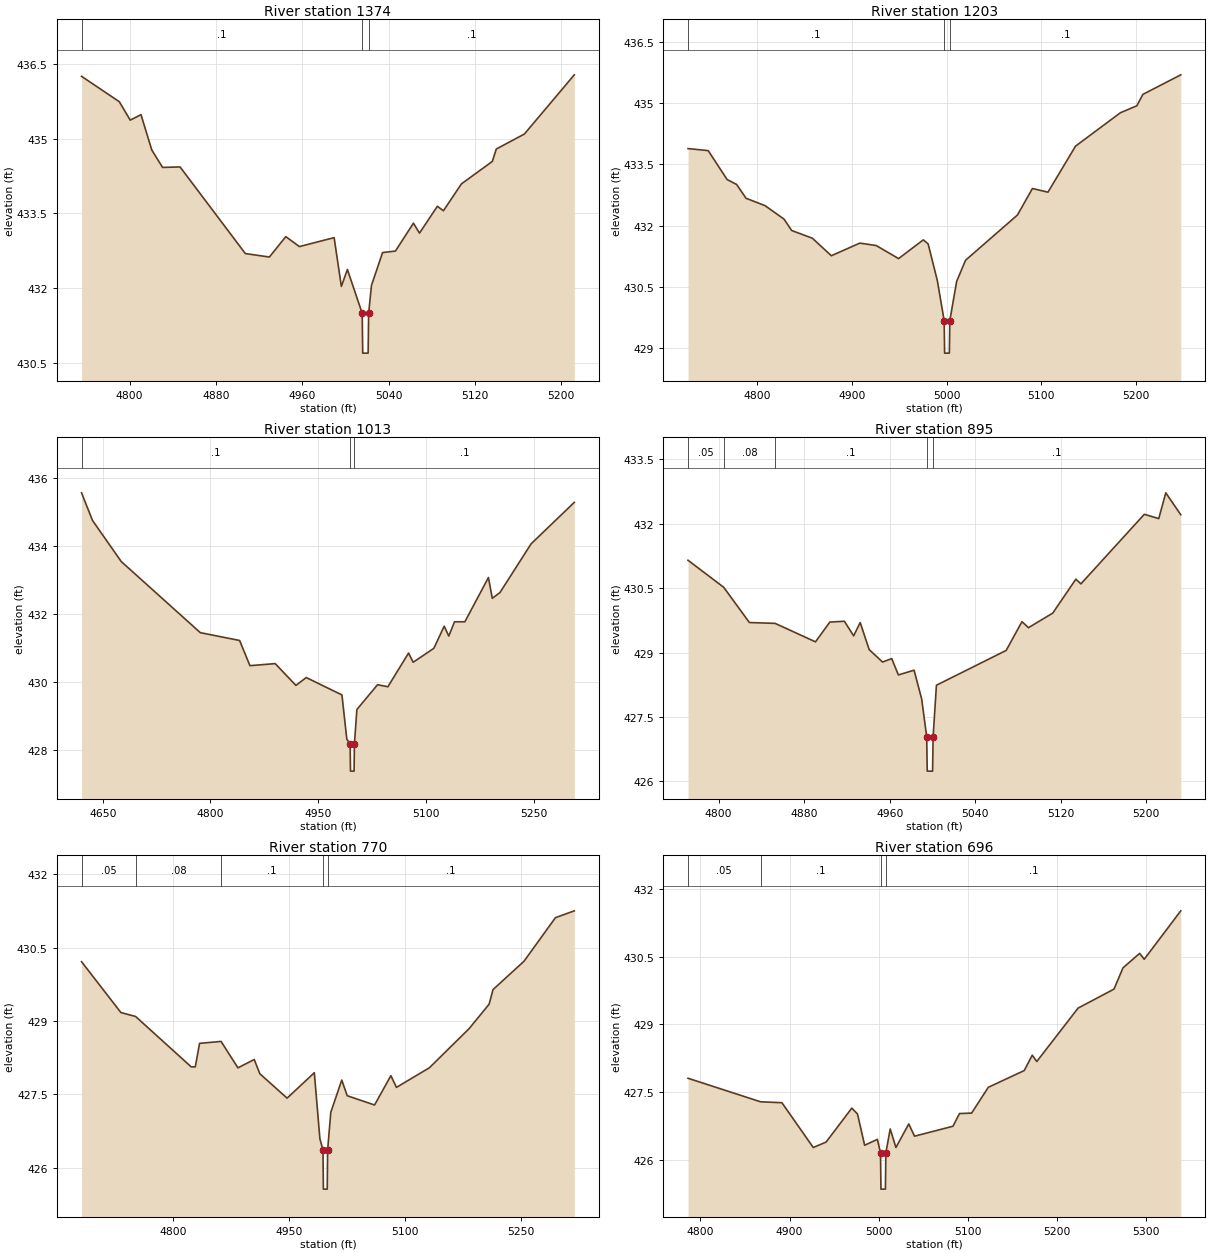
Type RM Length L Ch R = 1 ,1374    ,171,171,171
BEGIN DESCRIPTION:
Mapping XS 319dca8f
END DESCRIPTION:
XS GIS Cut Line= 4
      2066049.94     13471842.17      2065957.75     13471848.68
      2065828.62     13472102.58      2065844.82     13472180.33
#Sta/Elev= 30
  4755.4  436.25  4790.4  435.74  4800.5  435.37  4810.5  435.48  4820.5  434.77
  4830.5  434.42  4846.7  434.43  4907.2  432.69  4929.5  432.62  4944.7  433.03
  4957.3  432.83  4989.5  433.01  4996.2  432.03  5001.8  432.37  5015.5  431.49
    5016  430.69    5021  430.69  5021.5  431.49  5024.1  432.05  5034.4  432.71
  5046.3  432.74    5063   433.3  5068.6   433.1  5085.2  433.64  5090.8  433.55
  5107.5  434.09  5136.1  434.54  5139.8  434.79  5165.8  435.09  5212.1  436.28
#Mann= 3 ,-1 , 0
  4755.4      .1       0  5015.5     .07       0  5021.5      .1       0
Bank Sta=5015.5,5021.5
XS Rating Curve= 0 ,0
Exp/Cntr=0.3,0.1

Type RM Length L Ch R = 1 ,1203    ,190,190,190
BEGIN DESCRIPTION:
Mapping XS f1842d43
END DESCRIPTION:
XS GIS Cut Line= 4
      2065926.26     13471816.12      2065768.94     13471821.55
      2065725.54     13472026.63      2065785.22     13472167.69
#Sta/Elev= 30
  4727.1  433.89  4748.4  433.84  4768.4  433.13  4778.4  433.01  4788.4  432.67
  4808.4  432.49  4828.4  432.16  4836.5  431.88  4858.4  431.69  4878.4  431.26
  4908.5  431.57  4925.8  431.51  4949.4  431.19  4975.5  431.65  4980.6  431.55
  4990.3  430.65  4997.5  429.67    4998  428.87    5003  428.87  5003.5  429.67
  5010.7  430.63  5020.1  431.15  5074.9  432.26  5090.7  432.91  5107.1  432.82
  5136.2  433.95  5183.6  434.77  5200.9  434.94  5207.3  435.22  5247.3   435.7
#Mann= 3 ,-1 , 0
  4727.1      .1       0  4997.5     .07       0  5003.5      .1       0
Bank Sta=4997.5,5003.5
XS Rating Curve= 0 ,0
Exp/Cntr=0.3,0.1

Type RM Length L Ch R = 1 ,1013    ,118,118,118
BEGIN DESCRIPTION:
Mapping XS da648349
END DESCRIPTION:
XS GIS Cut Line= 4
       2065900.2     13471719.55      2065702.75     13471710.87
      2065477.06     13471992.99      2065525.63     13472110.64
#Sta/Elev= 30
  4620.5  435.55  4635.7  434.74  4675.8  433.53  4785.9  431.44  4840.6  431.21
    4855  430.47  4890.2  430.53    4919  429.89  4933.4  430.12  4983.1  429.61
  4989.9  428.31  4994.5  428.17    4995  427.37    5000  427.37  5000.5  428.17
  5003.9  429.18  5032.7  429.91  5047.1  429.85  5075.9  430.84  5082.3  430.57
  5111.1  430.98  5125.5  431.63  5131.9  431.34  5139.9  431.76  5154.3  431.76
  5187.1  433.06  5192.5  432.45  5203.2  432.62  5246.5  434.05  5306.7  435.27
#Mann= 3 ,-1 , 0
  4620.5      .1       0  4994.5     .07       0  5000.5      .1       0
Bank Sta=4994.5,5000.5
XS Rating Curve= 0 ,0
Exp/Cntr=0.3,0.1

Type RM Length L Ch R = 1 ,895     ,125,125,125
BEGIN DESCRIPTION:
Mapping XS 9dfd341c
END DESCRIPTION:
XS GIS Cut Line= 4
      2065669.12     13471622.94      2065598.59      13471647.9
      2065428.23      13471887.7      2065417.37     13471978.88
#Sta/Elev= 30
  4771.4  431.15  4804.8  430.52  4828.8   429.7  4852.9  429.68  4890.6  429.25
    4904  429.71  4917.6  429.73  4926.3  429.39  4932.4   429.7  4940.8  429.07
  4953.3  428.78  4961.9  428.86  4968.1  428.48  4982.8  428.59  4989.9  427.92
  4994.6  427.04  4995.1  426.24  5000.1  426.24  5000.6  427.04  5003.7  428.24
  5068.9  429.05  5083.7  429.72  5089.8  429.58  5112.5  429.92  5134.1  430.71
  5138.8   430.6  5198.1  432.22  5211.6  432.12  5218.2  432.72  5232.2  432.21
#Mann= 5 ,-1 , 0
  4771.4     .05       0  4804.8     .08       0  4852.9      .1       0
  4994.6     .07       0  5000.6      .1       0
Bank Sta=4994.6,5000.6
XS Rating Curve= 0 ,0
Exp/Cntr=0.3,0.1

Type RM Length L Ch R = 1 ,770     ,74,74,74
BEGIN DESCRIPTION:
Mapping XS 83af528a
END DESCRIPTION:
XS GIS Cut Line= 4
      2065708.48     13471579.24      2065567.87     13471554.07
      2065338.71     13471777.16      2065369.09     13471949.03
#Sta/Elev= 30
  4682.1  430.21    4733  429.17    4752  429.09  4823.9  428.06  4829.2  428.06
  4834.7  428.54  4862.5  428.58  4884.3  428.04  4905.4  428.21  4912.6  427.92
  4947.9  427.42  4983.1  427.94  4990.3  426.59  4994.3  426.36  4994.8  425.56
  4999.8  425.56  5000.3  426.36  5004.4  427.13  5018.6  427.79  5025.6  427.47
    5061  427.28  5082.1  427.88  5089.3  427.64  5131.8  428.04  5183.2  428.84
  5209.1  429.34  5214.2  429.64  5254.3  430.22  5294.9  431.11  5319.3  431.25
#Mann= 5 ,-1 , 0
  4682.1     .05       0    4752     .08       0  4862.5      .1       0
  4994.3     .07       0  5000.3      .1       0
Bank Sta=4994.3,5000.3
XS Rating Curve= 0 ,0
Exp/Cntr=0.3,0.1

Type RM Length L Ch R = 1 ,696     ,79,79,79
BEGIN DESCRIPTION:
Mapping XS 47243d22
END DESCRIPTION:
XS GIS Cut Line= 5
      2065550.86     13471537.22      2065455.36      13471553.5
      2065318.64     13471722.77      2065307.79     13471817.17
      2065325.15     13471959.33
#Sta/Elev= 30
  4786.1  427.81  4867.5  427.29  4891.4  427.27  4926.6  426.28    4941   426.4
  4969.8  427.15  4976.2  427.02  4984.2  426.33  4998.5  426.46    5002  426.16
  5002.5  425.36  5007.5  425.36    5008  426.16  5012.9  426.69  5019.3  426.28
  5033.7   426.8  5040.2  426.53  5083.3  426.75  5090.6  427.03  5104.2  427.04
  5122.9  427.61  5163.2  427.98  5172.2  428.32  5177.3  428.18  5223.6  429.36
  5263.9  429.78    5274  430.25  5292.7  430.57  5297.8  430.44  5338.8  431.51
#Mann= 4 ,-1 , 0
  4786.1     .05       0  4867.5      .1       0    5002     .07       0
    5008      .1       0
Bank Sta=5002,5008
XS Rating Curve= 0 ,0
Exp/Cntr=0.3,0.1

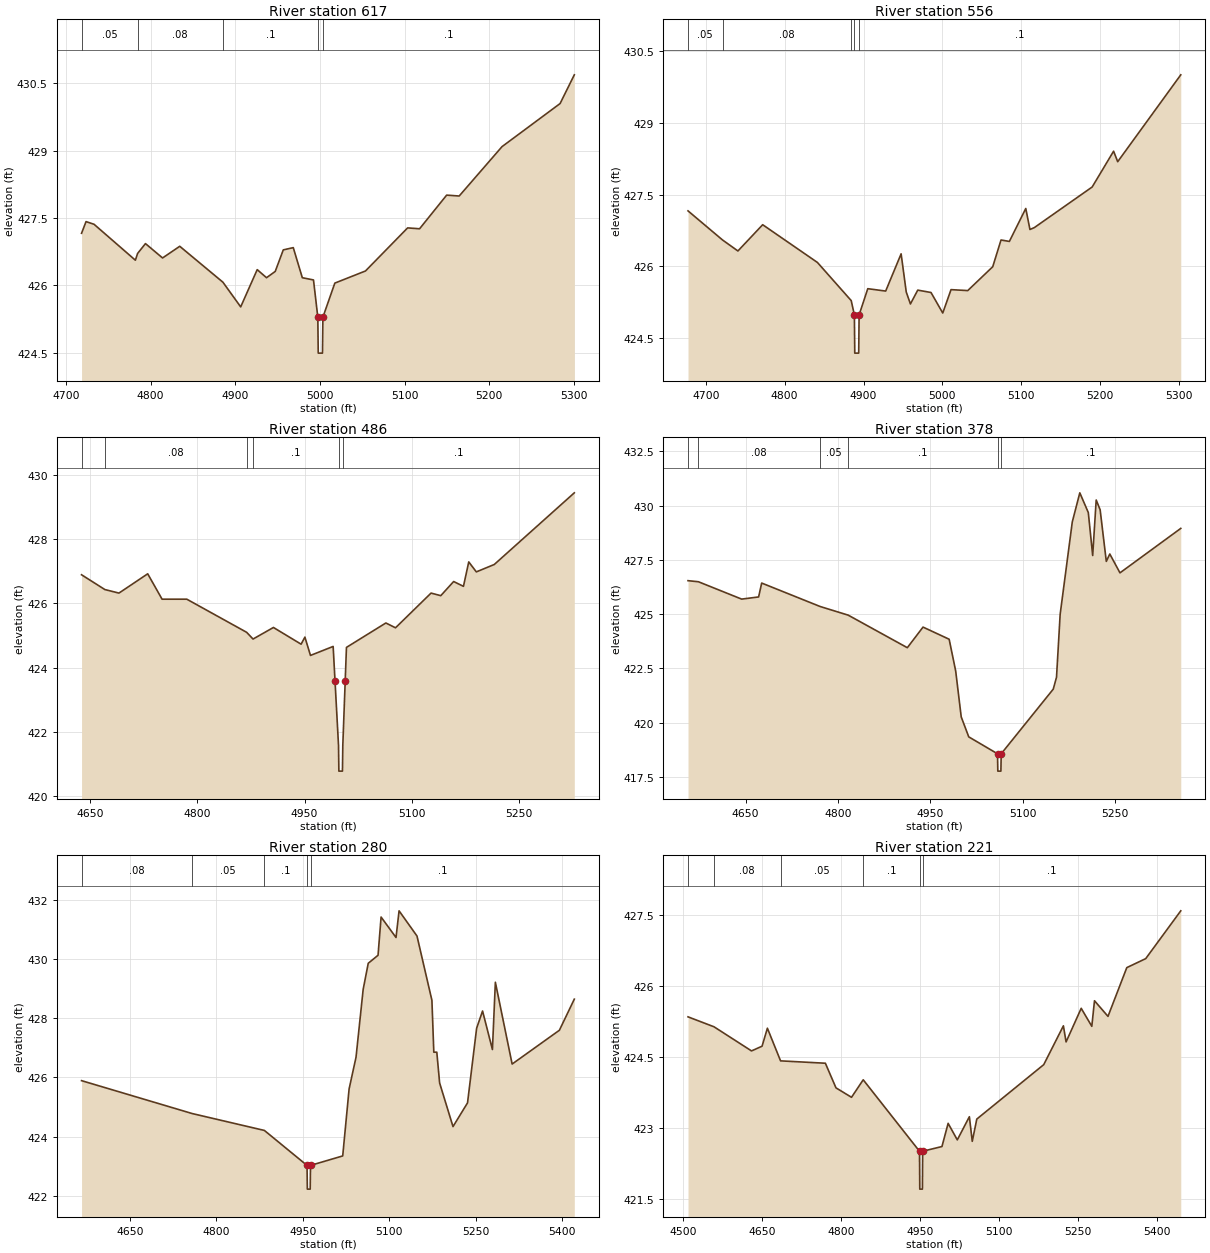
Type RM Length L Ch R = 1 ,617     ,61,61,61
BEGIN DESCRIPTION:
Mapping XS a058300d
END DESCRIPTION:
XS GIS Cut Line= 4
      2065509.63     13471519.86      2065346.85     13471544.82
      2065243.77     13471824.77      2065267.33     13471941.51
#Sta/Elev= 30
  4718.4  427.16  4723.7  427.42  4733.2  427.36    4782  426.56  4784.6  426.71
  4793.9  426.93  4814.1  426.61  4834.4  426.87  4885.4  426.07  4906.4  425.52
  4925.9  426.35  4936.9  426.17  4947.2  426.31  4956.7  426.79  4968.5  426.84
  4979.2  426.17  4992.4  426.12  4997.5  425.29    4998  424.49    5003  424.49
  5003.5  425.29  5017.6  426.05  5053.8  426.32  5103.6  427.28  5117.7  427.26
  5149.7  428.01  5164.5  427.99  5215.1  429.09  5283.7  430.05  5300.5  430.69
#Mann= 5 ,-1 , 0
  4718.4     .05       0  4784.6     .08       0  4885.4      .1       0
  4997.5     .07       0  5003.5      .1       0
Bank Sta=4997.5,5003.5
XS Rating Curve= 0 ,0
Exp/Cntr=0.3,0.1

Type RM Length L Ch R = 1 ,556     ,70,70,70
BEGIN DESCRIPTION:
Mapping XS 26169548
END DESCRIPTION:
XS GIS Cut Line= 4
      2065487.83     13471518.55        2065283.     13471544.59
      2065190.11     13471818.02      2065217.89     13471944.75
#Sta/Elev= 30
  4677.4  427.16  4721.2  426.55  4740.7  426.32  4772.1  426.87  4841.5  426.08
  4884.4  425.28  4888.4  424.98  4888.9  424.18  4893.9  424.18  4894.4  424.98
  4905.4  425.53  4928.1  425.48  4947.7  426.26  4954.2  425.46  4959.5  425.21
  4968.8   425.5  4985.6  425.45  5000.5  425.02    5011  425.51  5032.2  425.49
  5063.9  425.99  5074.4  426.55    5085  426.52  5105.8  427.21  5111.1  426.77
  5116.7  426.81    5190  427.66  5217.2  428.41  5222.4  428.19  5302.4  430.01
#Mann= 5 ,-1 , 0
  4677.4     .05       0  4721.2     .08       0  4884.4      .1       0
  4888.4     .07       0  4894.4      .1       0
Bank Sta=4888.4,4894.4
XS Rating Curve= 0 ,0
Exp/Cntr=0.3,0.1

Type RM Length L Ch R = 1 ,486     ,108,108,108
BEGIN DESCRIPTION:
Mapping XS be463887
END DESCRIPTION:
XS GIS Cut Line= 4
      2065477.02     13471515.53      2065214.47     13471541.57
      2065115.73     13471838.87      2065172.17     13471935.48
#Sta/Elev= 30
  4638.2  426.89  4670.8  426.43  4690.5  426.32  4730.7  426.92  4750.8  426.13
  4785.4  426.13    4869   425.1    4878  424.89  4906.5  425.25  4945.2  424.73
  4950.5  424.95  4958.3  424.38    4990  424.66 4992.61423.5882  4997.5  421.58
    4998  420.78    5003  420.78  5003.5  421.58 5006.86423.5893  5008.6  424.63
  5063.7  425.39  5077.2  425.24  5126.9  426.32  5140.5  426.24  5158.5  426.68
  5172.2  426.53  5179.6  427.29  5190.2  426.98  5215.3  427.21  5327.2  429.44
#Mann= 6 ,-1 , 0
  4638.2     .05       0  4670.8     .08       0    4869     .05       0
    4878      .1       0  4997.5     .07       0  5003.5      .1       0
Bank Sta=4992.61,5006.86
XS Rating Curve= 0 ,0
Exp/Cntr=0.3,0.1

Type RM Length L Ch R = 1 ,378     ,98,98,98
BEGIN DESCRIPTION:
Mapping XS 9361927c
END DESCRIPTION:
XS GIS Cut Line= 4
       2065461.9     13471502.05      2065112.14     13471525.86
       2065013.4     13471805.81      2065083.71     13471941.11
#Sta/Elev= 30
  4556.5  426.54  4573.4  426.49  4643.6  425.69  4671.1  425.79  4676.1  426.43
  4770.9  425.35  4816.6  424.95  4912.5  423.45    4938   424.4  4980.4  423.84
    4991  422.38    5000  420.26  5012.2  419.34  5058.9  418.56  5059.4  417.76
  5064.4  417.76  5064.9  418.56  5149.4  421.54  5154.7  422.09  5160.6  424.99
  5180.3  429.25  5192.5  430.59  5206.3  429.68  5213.4   427.7  5219.1  430.26
  5225.5  429.81  5235.5  427.43  5241.2  427.77  5257.7   426.9  5356.4  428.95
#Mann= 6 ,-1 , 0
  4556.5     .05       0  4573.4     .08       0  4770.9     .05       0
  4816.6      .1       0  5058.9     .07       0  5064.9      .1       0
Bank Sta=5058.9,5064.9
XS Rating Curve= 0 ,0
Exp/Cntr=0.3,0.1

Type RM Length L Ch R = 1 ,280     ,59,59,59
BEGIN DESCRIPTION:
Mapping XS b4957dc7
END DESCRIPTION:
XS GIS Cut Line= 5
      2065441.04     13471485.12        2065072.     13471475.95
      2065015.57     13471557.33      2064967.83     13471695.13
      2065020.93     13471930.29
#Sta/Elev= 30
  4566.3  425.89  4758.3  424.78  4883.6  424.21  4957.6  423.03  4958.1  422.23
  4963.1  422.23  4963.6  423.03  5019.5  423.35  5030.6  425.61  5042.6  426.68
    5055  428.97  5063.8  429.85  5080.8  430.12  5086.1  431.41    5112  430.72
  5117.3  431.62  5148.4  430.77  5174.3   428.6  5177.6  426.85  5182.8  426.85
  5187.7  425.81  5210.9  424.34  5236.1  425.14  5251.9  427.66  5262.2  428.24
  5279.3  426.94  5284.4  429.21  5313.5  426.45  5395.5  427.59  5421.4  428.64
#Mann= 5 ,-1 , 0
  4566.3     .08       0  4758.3     .05       0  4883.6      .1       0
  4957.6     .07       0  4963.6      .1       0
Bank Sta=4957.6,4963.6
XS Rating Curve= 0 ,0
Exp/Cntr=0.3,0.1

Type RM Length L Ch R = 1 ,221     ,137,137,137
BEGIN DESCRIPTION:
Mapping XS c27d286c
END DESCRIPTION:
XS GIS Cut Line= 5
      2065425.43     13471447.36      2065011.23     13471464.01
      2064927.68     13471644.13      2064894.05     13471832.93
      2064922.25     13471959.88
#Sta/Elev= 30
  4509.8  425.34  4559.1  425.13  4630.3  424.62  4650.3  424.72  4660.4   425.1
  4685.4  424.41  4770.4  424.36  4790.5  423.84    4820  423.64  4842.2  424.01
    4949   422.5  4949.5   421.7  4954.5   421.7    4955   422.5  4991.6   422.6
  5003.3  423.09  5020.7  422.74  5043.6  423.23  5049.1  422.71  5057.7  423.18
  5184.7  424.33    5222  425.15  5227.1  424.81  5255.8  425.52  5275.9  425.14
    5281  425.68  5306.6  425.35  5342.3  426.38  5378.2  426.57  5444.7  427.58
#Mann= 6 ,-1 , 0
  4509.8      .1       0  4559.1     .08       0  4685.4     .05       0
  4842.2      .1       0    4949     .07       0    4955      .1       0
Bank Sta=4949,4955
XS Rating Curve= 0 ,0
Exp/Cntr=0.3,0.1

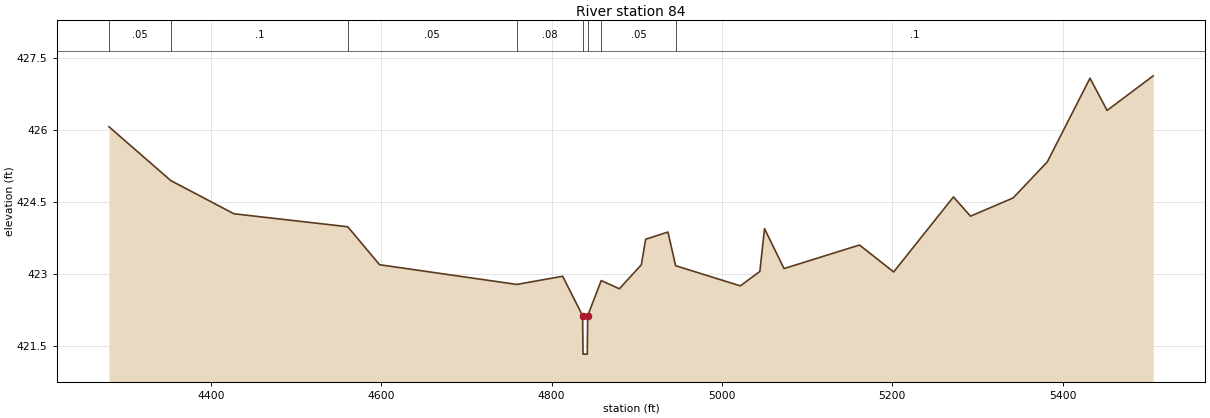
Type RM Length L Ch R = 1 ,84      ,0,0,0
BEGIN DESCRIPTION:
UNT 121 in Lagunillas Cr Wtrshd 1.0
END DESCRIPTION:
XS GIS Cut Line= 4
      2065530.86     13471353.61      2064892.96     13471421.69
      2064819.94     13471578.87      2064847.28     13471989.03
#Sta/Elev= 30
  4280.4  426.07    4353  424.95  4427.1  424.26  4560.7  423.99  4598.1   423.2
  4759.1  422.79    4813  422.96  4836.4  422.14  4836.9  421.34  4841.9  421.34
  4842.4  422.14  4858.3  422.87  4879.6   422.7  4905.4   423.2  4910.4  423.73
  4936.6  423.88  4945.6  423.18  5021.6  422.76  5044.5  423.06    5050  423.95
  5072.9  423.12  5161.5  423.61  5201.6  423.05  5271.8  424.61  5291.8  424.21
  5341.9  424.59    5382  425.34  5432.1  427.08  5452.2  426.41  5506.3  427.13
#Mann= 8 ,-1 , 0
  4280.4     .05       0    4353      .1       0  4560.7     .05       0
  4759.1     .08       0  4836.4     .07       0  4842.4     .08       0
  4858.3     .05       0  4945.6      .1       0
Bank Sta=4836.4,4842.4
XS Rating Curve= 0 ,0
Exp/Cntr=0.3,0.1
LCMann Table=0

Chan Stop Cuts=-1
Use User Specified Reach Order=0
Composite Channel Slope=5