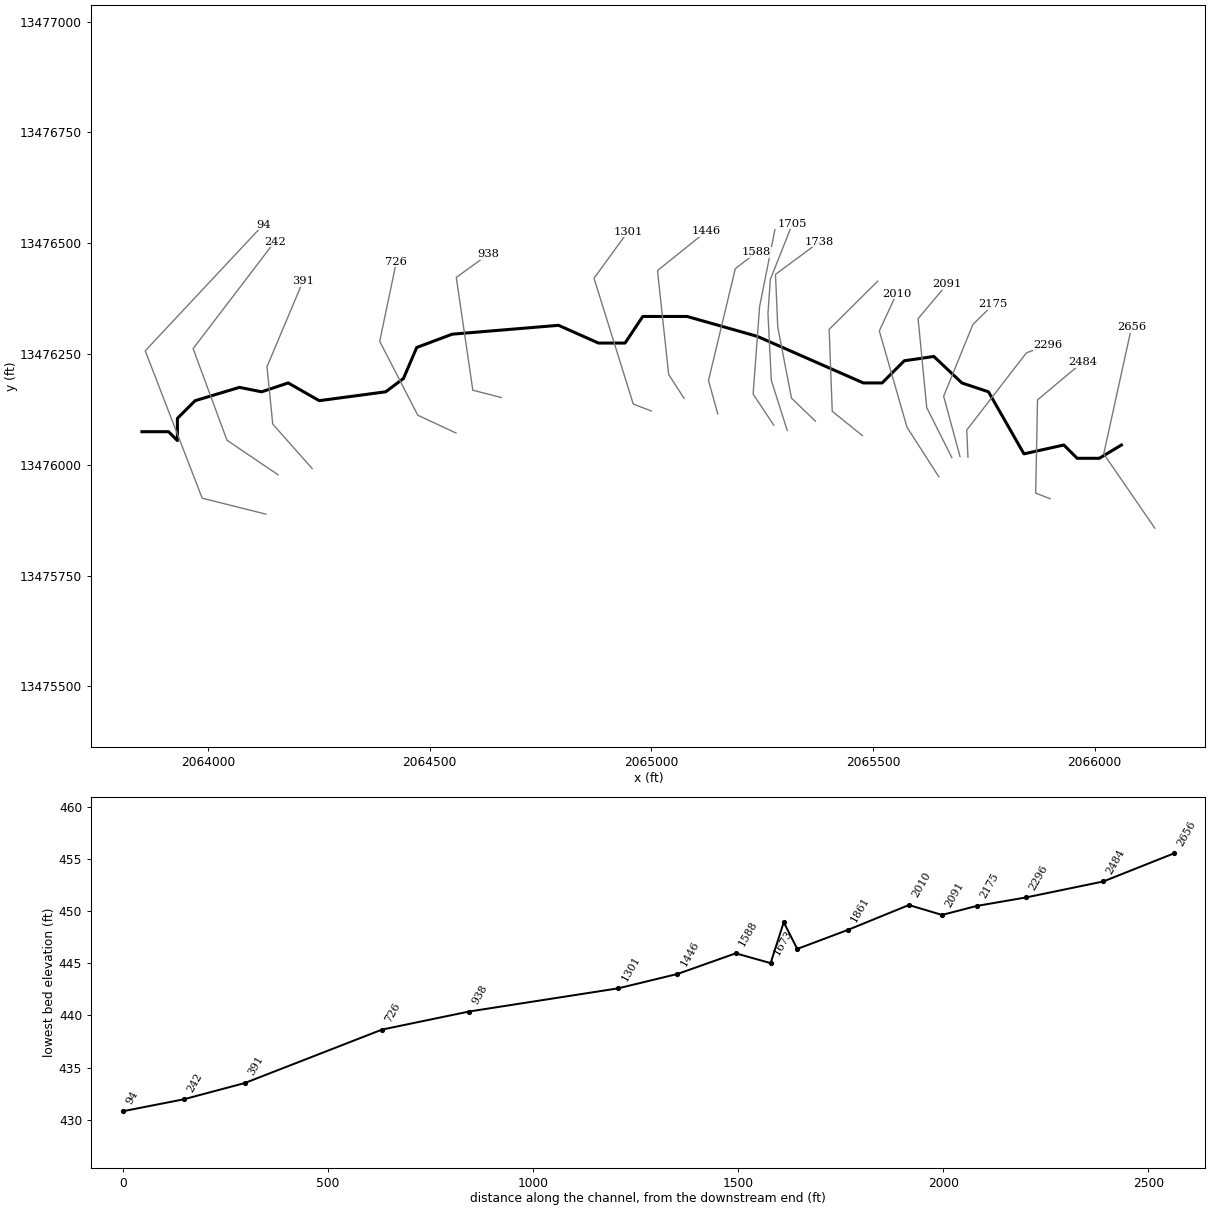
--- UNT 123 in Lagunillas Cr Wtrshd.prj (project) ---

Proj Title=UNT 123 in Lagunillas Cr Wtrshd Base Level Engineering
Current Plan=p01
Default Exp/Contr=0.3,0.1
English Units
Geom File=g01
Flow File=f01
Plan File=p01
BEGIN DESCRIPTION:
UNT 123 in Lagunillas Cr Wtrshd
END DESCRIPTION:

--- UNT 123 in Lagunillas Cr Wtrshd.p01 (plan) ---

Plan Title=Multiple Run
Short Identifier=Multiple
Geom File=g01
Flow File=f01
Subcritical Flow
K Sum by GR= 0
Std Step Tol= 0.01
Critical Tol= 0.01
Num of Std Step Trials= 20
Max Error Tol= 0.3
Flow Tol Ratio= 0.001
Split Flow NTrial= 30
Split Flow Tol= 0.02
Split Flow Ratio= 0.02
Log Output Level= 0
Friction Slope Method= 1
Unsteady Friction Slope Method= 2
Unsteady Bridges Friction Slope Method= 1
Parabolic Critical Depth
Global Vel Dist=  1 , 1 , 1
Global Log Level= 0
CheckData=True
Encroach Param= -1, 0, 0, 0
BEGIN DESCRIPTION:
Multiple Run
END DESCRIPTION:

--- UNT 123 in Lagunillas Cr Wtrshd.f01 (steady flow) ---

Flow Title=Multiple
Number of Profiles=7
Profile Names=10-year,25-year,50-year,1pct_min,100-year,1pct_plu,500-year
River Rch & RM= UNT 123 in Lagun,Reach-1,2656
      66      84      98      57     114     228     157
Boundary for River Rch & Prof#=UNT 123 in Lagun,Reach-1,1
Up Type=0
Dn Type=3
Dn Slope=0.005
Boundary for River Rch & Prof#=UNT 123 in Lagun,Reach-1,2
Up Type=0
Dn Type=3
Dn Slope=0.005
Boundary for River Rch & Prof#=UNT 123 in Lagun,Reach-1,3
Up Type=0
Dn Type=3
Dn Slope=0.005
Boundary for River Rch & Prof#=UNT 123 in Lagun,Reach-1,4
Up Type=0
Dn Type=3
Dn Slope=0.005
Boundary for River Rch & Prof#=UNT 123 in Lagun,Reach-1,5
Up Type=0
Dn Type=3
Dn Slope=0.005
Boundary for River Rch & Prof#=UNT 123 in Lagun,Reach-1,6
Up Type=0
Dn Type=3
Dn Slope=0.005
Boundary for River Rch & Prof#=UNT 123 in Lagun,Reach-1,7
Up Type=0
Dn Type=3
Dn Slope=0.005

--- UNT 123 in Lagunillas Cr Wtrshd.g01 (geometry) ---

Geom Title=Existing Conditions

River Reach=UNT 123 in Lagun,Reach-1
Reach XY= 30
      2066060.80     13476044.54      2066010.80     13476014.54
      2065960.80     13476014.54      2065930.80     13476044.54
      2065840.80     13476024.54      2065760.80     13476164.54
      2065700.80     13476184.54      2065637.55     13476244.28
      2065570.80     13476234.54      2065520.80     13476184.54
      2065478.52     13476184.54      2065239.15     13476289.64
      2065080.80     13476334.54      2064980.80     13476334.54
      2064940.80     13476274.54      2064880.80     13476274.54
      2064790.80     13476314.54      2064550.80     13476294.54
      2064470.80     13476264.54      2064440.80     13476194.54
      2064400.80     13476164.54      2064250.80     13476144.54
      2064180.80     13476184.54      2064120.80     13476164.54
      2064070.80     13476174.54      2063970.80     13476144.54
      2063930.80     13476104.54      2063930.80     13476054.54
      2063910.80     13476074.54      2063850.80     13476074.54

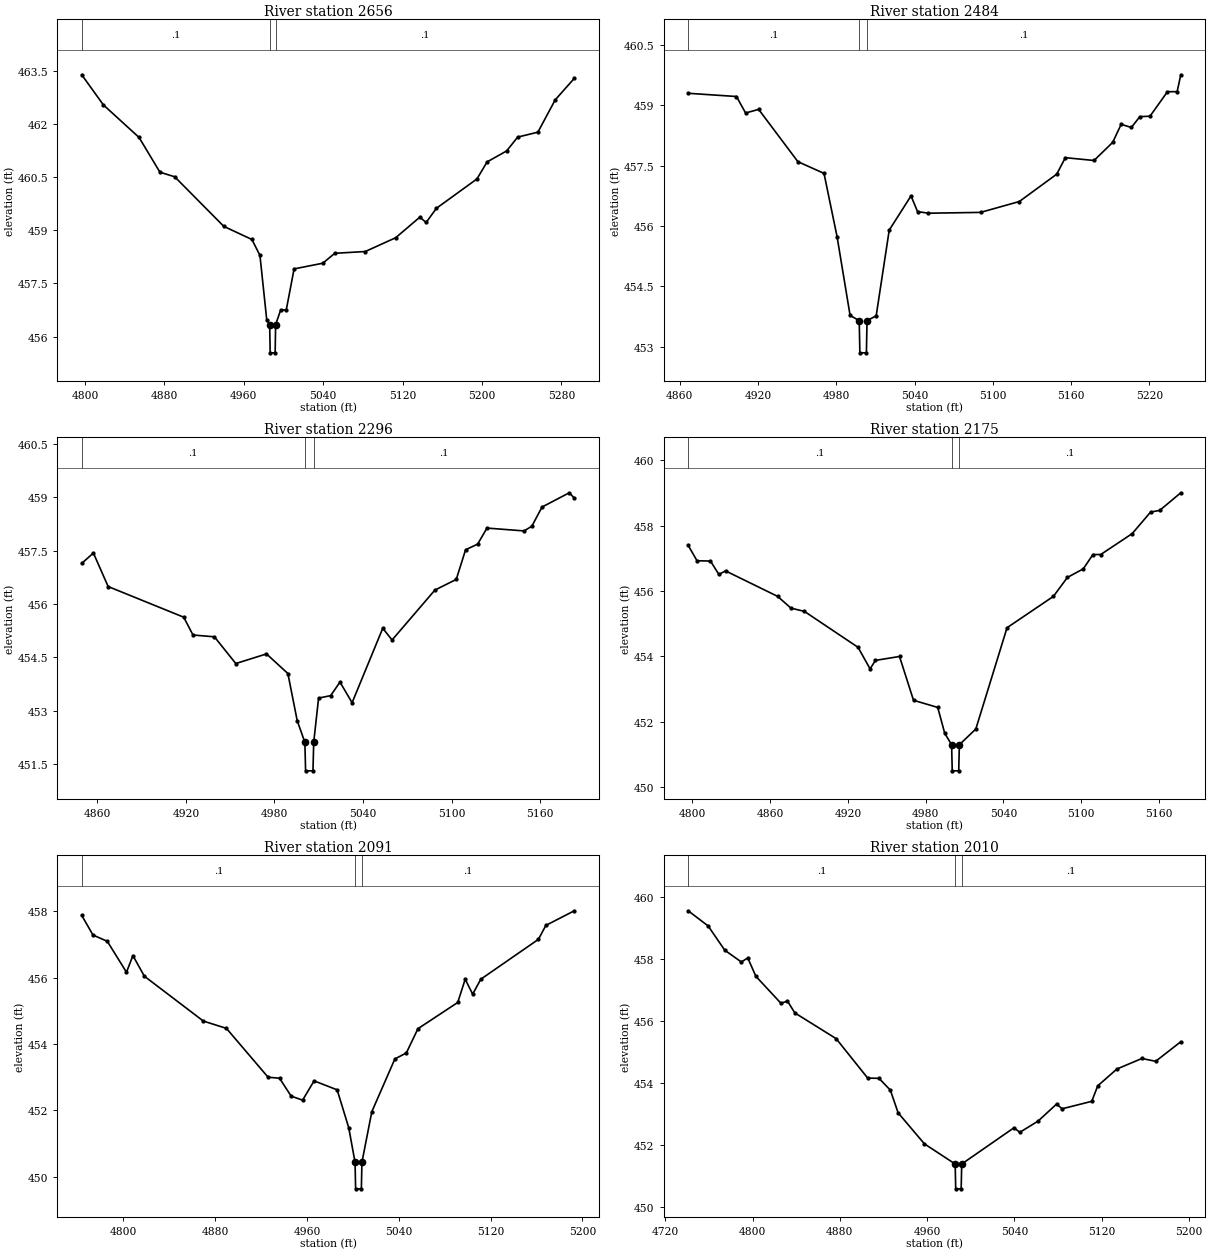
Type RM Length L Ch R = 1,2656,172,172,172
BEGIN DESCRIPTION:
UNT 123 in Lagunillas Cr Wtrshd 3.0
END DESCRIPTION:
XS GIS Cut Line= 3
      2066135.97     13475857.01      2066020.80     13476024.54
      2066083.71     13476310.81
#Sta/Elev= 30
  4796.7  463.39  4818.5  462.54  4854.5  461.62  4875.5  460.64  4890.4  460.51
  4939.9  459.11  4968.2  458.74  4976.3  458.29  4983.1  456.48  4986.1  456.34
  4986.6  455.54  4991.6  455.54  4992.1  456.34  4997.2  456.75  5002.8  456.75
  5010.7  457.91  5039.6  458.07  5051.7  458.35  5082.4  458.40  5113.1  458.79
  5137.4  459.37  5143.8  459.22  5154.1  459.62  5195.0  460.45  5205.2  460.93
  5224.9  461.24  5236.0  461.63  5256.4  461.77  5273.8  462.68  5293.1  463.29
#Mann=3,-1,0
  4796.7     0.1       0  4986.1    0.07       0  4992.1     0.1       0
Bank Sta=4986.1,4992.1
Exp/Cntr=0.3,0.1

Type RM Length L Ch R = 1,2484,188,188,188
BEGIN DESCRIPTION:
Mapping XS 090eabac
END DESCRIPTION:
XS GIS Cut Line= 4
      2065899.87     13475923.38      2065867.28     13475935.86
      2065871.44     13476146.28      2065972.81     13476231.20
#Sta/Elev= 30
  4866.4  459.30  4903.4  459.22  4910.4  458.81  4920.4  458.90  4950.5  457.60
  4970.5  457.31  4980.5  455.74  4990.5  453.78  4997.5  453.65  4998.0  452.85
  5003.0  452.85  5003.5  453.65  5010.5  453.77  5020.5  455.90  5037.2  456.75
  5042.2  456.36  5050.5  456.32  5090.5  456.34  5120.2  456.61  5148.9  457.29
  5155.5  457.70  5177.5  457.63  5191.8  458.08  5198.3  458.53  5206.1  458.45
  5212.6  458.72  5220.4  458.73  5233.8  459.34  5241.2  459.34  5244.0  459.76
#Mann=3,-1,0
  4866.4     0.1       0  4997.5    0.07       0  5003.5     0.1       0
Bank Sta=4997.5,5003.5
Exp/Cntr=0.3,0.1

Type RM Length L Ch R = 1,2296,121,121,121
BEGIN DESCRIPTION:
Mapping XS 9db143be
END DESCRIPTION:
XS GIS Cut Line= 4
      2065714.50     13476017.08      2065711.72     13476078.22
      2065846.44     13476252.53      2065895.62     13476270.29
#Sta/Elev= 30
  4849.4  457.14  4857.3  457.43  4867.3  456.49  4918.5  455.63  4924.8  455.13
  4939.3  455.08  4953.8  454.33  4974.6  454.60  4989.1  454.05  4995.4  452.73
  5000.6  452.12  5001.1  451.32  5006.1  451.32  5006.6  452.12  5009.9  453.36
  5018.1  453.43  5024.4  453.81  5032.6  453.23  5053.4  455.32  5059.7  454.99
  5088.7  456.39  5103.2  456.69  5109.5  457.52  5117.7  457.68  5124.0  458.13
  5149.1  458.05  5154.4  458.18  5161.3  458.72  5179.8  459.12  5183.2  458.97
#Mann=3,-1,0
  4849.4     0.1       0  5000.6    0.07       0  5006.6     0.1       0
Bank Sta=5000.6,5006.6
Exp/Cntr=0.3,0.1

Type RM Length L Ch R = 1,2175,84,84,84
BEGIN DESCRIPTION:
Mapping XS 575b28f0
END DESCRIPTION:
XS GIS Cut Line= 4
      2065696.52     13476018.43      2065659.64     13476154.61
      2065725.61     13476316.42      2065771.47     13476361.58
#Sta/Elev= 30
  4796.7  457.40  4803.5  456.93  4813.9  456.92  4820.4  456.51  4825.5  456.62
  4865.7  455.84  4876.0  455.48  4886.4  455.38  4927.8  454.28  4937.1  453.62
  4941.2  453.88  4959.8  454.00  4970.6  452.66  4989.3  452.44  4994.7  451.65
  5000.0  451.30  5000.5  450.50  5005.5  450.50  5006.0  451.30  5018.7  451.78
  5042.8  454.88  5078.6  455.84  5089.4  456.42  5101.6  456.68  5109.1  457.12
  5115.1  457.12  5139.4  457.76  5153.6  458.42  5160.6  458.47  5176.9  459.01
#Mann=3,-1,0
  4796.7     0.1       0  5000.0    0.07       0  5006.0     0.1       0
Bank Sta=5000,5006
Exp/Cntr=0.3,0.1

Type RM Length L Ch R = 1,2091,81,81,81
BEGIN DESCRIPTION:
Mapping XS 4ae3022c
END DESCRIPTION:
XS GIS Cut Line= 4
      2065678.08     13476016.25      2065621.44     13476128.92
      2065602.00     13476329.61      2065667.29     13476407.40
#Sta/Elev= 30
  4763.7  457.87  4773.5  457.28  4786.0  457.09  4802.7  456.16  4808.3  456.66
  4818.3  456.04  4869.7  454.69  4889.8  454.47  4926.1  453.00  4936.1  452.97
  4946.2  452.43  4956.2  452.31  4966.2  452.89  4986.3  452.62  4996.4  451.48
  5001.9  450.44  5002.4  449.64  5007.4  449.64  5007.9  450.44  5016.5  451.96
  5036.6  453.55  5046.6  453.73  5056.7  454.46  5091.4  455.25  5097.9  455.95
  5104.4  455.50  5111.5  455.95  5161.7  457.15  5168.2  457.57  5193.0  458.01
#Mann=3,-1,0
  4763.7     0.1       0  5001.9    0.07       0  5007.9     0.1       0
Bank Sta=5001.9,5007.9
Exp/Cntr=0.3,0.1

Type RM Length L Ch R = 1,2010,149,149,149
BEGIN DESCRIPTION:
Mapping XS 15f639d5
END DESCRIPTION:
XS GIS Cut Line= 4
      2065648.78     13475972.84      2065577.00     13476084.47
      2065514.50     13476301.83      2065553.40     13476385.88
#Sta/Elev= 30
  4741.0  459.55  4759.3  459.06  4774.5  458.28  4789.7  457.90  4795.6  458.03
  4803.0  457.44  4826.0  456.57  4832.0  456.64  4838.7  456.26  4876.6  455.43
  4905.5  454.16  4915.9  454.15  4926.3  453.77  4933.4  453.04  4957.5  452.04
  4985.7  451.39  4986.2  450.59  4991.2  450.59  4991.7  451.39  5039.7  452.56
  5044.9  452.41  5061.6  452.77  5078.6  453.32  5083.8  453.17  5110.9  453.41
  5116.4  453.91  5133.9  454.45  5156.8  454.79  5169.5  454.70  5192.5  455.33
#Mann=3,-1,0
  4741.0     0.1       0  4985.7    0.07       0  4991.7     0.1       0
Bank Sta=4985.7,4991.7
Exp/Cntr=0.3,0.1

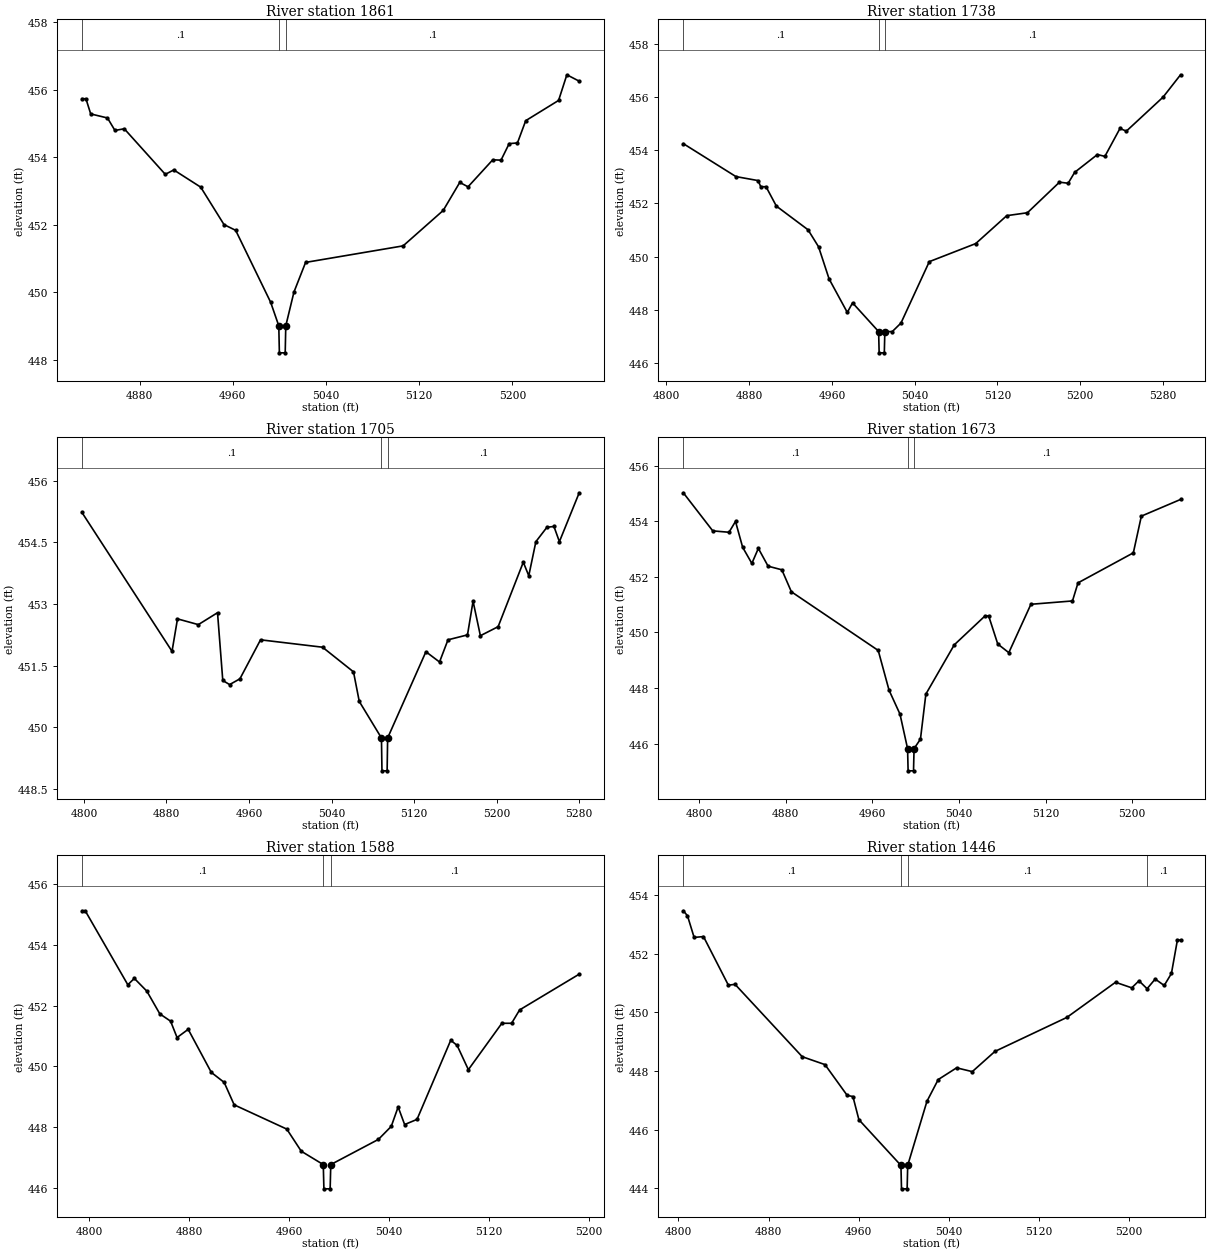
Type RM Length L Ch R = 1,1861,123,123,123
BEGIN DESCRIPTION:
Mapping XS 8438975b
END DESCRIPTION:
XS GIS Cut Line= 4
      2065476.33     13476065.70      2065408.25     13476120.58
      2065401.30     13476305.31      2065510.83     13476414.14
#Sta/Elev= 30
  4830.6  455.73  4834.0  455.73  4838.1  455.28  4852.5  455.16  4858.9  454.79
  4866.9  454.84  4902.1  453.49  4909.4  453.62  4932.5  453.11  4952.5  452.00
  4962.5  451.83  4992.5  449.70  4999.5  449.00  5000.0  448.20  5005.0  448.20
  5005.5  449.00  5012.5  450.00  5022.5  450.88  5106.2  451.37  5140.6  452.42
  5154.8  453.25  5161.9  453.12  5183.1  453.92  5190.2  453.91  5197.2  454.40
  5204.3  454.42  5211.4  455.08  5239.6  455.68  5246.7  456.44  5257.3  456.25
#Mann=3,-1,0
  4830.6     0.1       0  4999.5    0.07       0  5005.5     0.1       0
Bank Sta=4999.5,5005.5
Exp/Cntr=0.3,0.1

Type RM Length L Ch R = 1,1738,33,33,33
BEGIN DESCRIPTION:
Mapping XS cbe2462f
END DESCRIPTION:
XS GIS Cut Line= 5
      2065370.38     13476098.25      2065316.27     13476150.30
      2065285.37     13476310.45      2065280.22     13476429.41
      2065379.58     13476503.02
#Sta/Elev= 30
  4816.3  454.25  4867.2  453.01  4888.6  452.86  4891.2  452.63  4896.3  452.63
  4906.3  451.90  4936.9  451.01  4947.1  450.37  4957.3  449.16  4974.9  447.90
  4980.0  448.26  5005.2  447.18  5005.7  446.38  5010.7  446.38  5011.2  447.18
  5018.4  447.18  5026.8  447.50  5054.2  449.81  5099.1  450.49  5129.1  451.54
  5149.1  451.65  5180.1  452.80  5188.5  452.76  5194.8  453.17  5216.8  453.84
  5224.0  453.77  5238.6  454.82  5244.8  454.72  5280.3  456.00  5297.2  456.84
#Mann=3,-1,0
  4816.3     0.1       0  5005.2    0.07       0  5011.2     0.1       0
Bank Sta=5005.2,5011.2
Exp/Cntr=0.3,0.1

Type RM Length L Ch R = 1,1705,32,32,32
BEGIN DESCRIPTION:
Mapping XS 5e732477
END DESCRIPTION:
XS GIS Cut Line= 5
      2065306.64     13476077.51      2065270.83     13476190.36
      2065263.23     13476341.19      2065268.66     13476418.23
      2065318.55     13476544.05
#Sta/Elev= 30
  4798.1  455.23  4885.4  451.85  4890.7  452.64  4910.9  452.50  4929.5  452.79
  4934.6  451.14  4941.2  451.04  4951.2  451.18  4971.2  452.13  5031.3  451.95
  5061.3  451.35  5066.9  450.63  5088.4  449.74  5088.9  448.94  5093.9  448.94
  5094.4  449.74  5131.5  451.84  5144.7  451.59  5152.9  452.13  5171.8  452.25
  5177.2  453.07  5184.3  452.23  5201.5  452.45  5225.9  454.02  5231.2  453.69
  5238.1  454.52  5248.8  454.87  5255.6  454.89  5260.9  454.52  5280.1  455.71
#Mann=3,-1,0
  4798.1     0.1       0  5088.4    0.07       0  5094.4     0.1       0
Bank Sta=5088.4,5094.4
Exp/Cntr=0.3,0.1

Type RM Length L Ch R = 1,1673,85,85,85
BEGIN DESCRIPTION:
Mapping XS 09e6a126
END DESCRIPTION:
XS GIS Cut Line= 4
      2065276.33     13476089.29      2065229.78     13476159.47
      2065244.36     13476356.69      2065278.98     13476530.50
#Sta/Elev= 30
  4785.4  455.02  4812.6  453.65  4827.6  453.60  4833.6  453.99  4840.2  453.06
  4848.7  452.48  4854.7  453.02  4863.7  452.38  4876.4  452.25  4885.2  451.46
  4965.4  449.35  4975.4  447.92  4985.5  447.06  4992.5  445.82  4993.0  445.02
  4998.0  445.02  4998.5  445.82  5004.4  446.16  5009.4  447.78  5035.6  449.55
  5064.0  450.59  5067.4  450.59  5075.8  449.58  5086.0  449.27  5106.4  451.01
  5144.8  451.13  5149.9  451.78  5201.0  452.86  5208.4  454.18  5244.6  454.78
#Mann=3,-1,0
  4785.4     0.1       0  4992.5    0.07       0  4998.5     0.1       0
Bank Sta=4992.5,4998.5
Exp/Cntr=0.3,0.1

Type RM Length L Ch R = 1,1588,142,142,142
BEGIN DESCRIPTION:
Mapping XS d55bcb69
END DESCRIPTION:
XS GIS Cut Line= 4
      2065149.92     13476115.00      2065129.08     13476190.03
      2065189.50     13476442.11      2065237.39     13476479.59
#Sta/Elev= 30
  4794.1  455.13  4796.7  455.13  4830.8  452.69  4836.0  452.90  4846.0  452.48
  4856.4  451.73  4865.0  451.49  4870.2  450.95  4879.1  451.22  4897.6  449.80
  4907.9  449.47  4915.9  448.73  4958.0  447.93  4969.6  447.20  4987.2  446.76
  4987.7  445.96  4992.7  445.96  4993.2  446.76  5031.3  447.59  5041.6  448.02
  5047.1  448.66  5052.3  448.08  5062.2  448.25  5089.2  450.86  5094.3  450.69
  5103.3  449.89  5130.1  451.42  5137.9  451.42  5144.3  451.86  5192.0  453.04
#Mann=3,-1,0
  4794.1     0.1       0  4987.2    0.07       0  4993.2     0.1       0
Bank Sta=4987.2,4993.2
Exp/Cntr=0.3,0.1

Type RM Length L Ch R = 1,1446,145,145,145
BEGIN DESCRIPTION:
Mapping XS 08d81c0c
END DESCRIPTION:
XS GIS Cut Line= 4
      2065073.91     13476149.92      2065039.19     13476203.73
      2065014.02     13476438.11      2065124.29     13476526.67
#Sta/Elev= 30
  4804.4  453.47  4808.1  453.30  4814.0  452.56  4822.3  452.59  4844.4  450.93
  4850.3  450.96  4909.9  448.49  4930.1  448.22  4949.8  447.17  4954.9  447.13
  4960.2  446.34  4997.5  444.78  4998.0  443.98  5003.0  443.98  5003.5  444.78
  5020.6  446.97  5030.6  447.71  5046.9  448.11  5060.8  447.98  5080.9  448.67
  5144.7  449.83  5187.9  451.03  5202.3  450.84  5208.7  451.08  5215.9  450.81
  5223.1  451.14  5231.1  450.92  5237.5  451.33  5242.8  452.47  5245.6  452.47
#Mann=4,-1,0
  4804.4     0.1       0  4997.5    0.07       0  5003.5     0.1       0
  5215.9     0.1       0
Bank Sta=4997.5,5003.5
Exp/Cntr=0.3,0.1

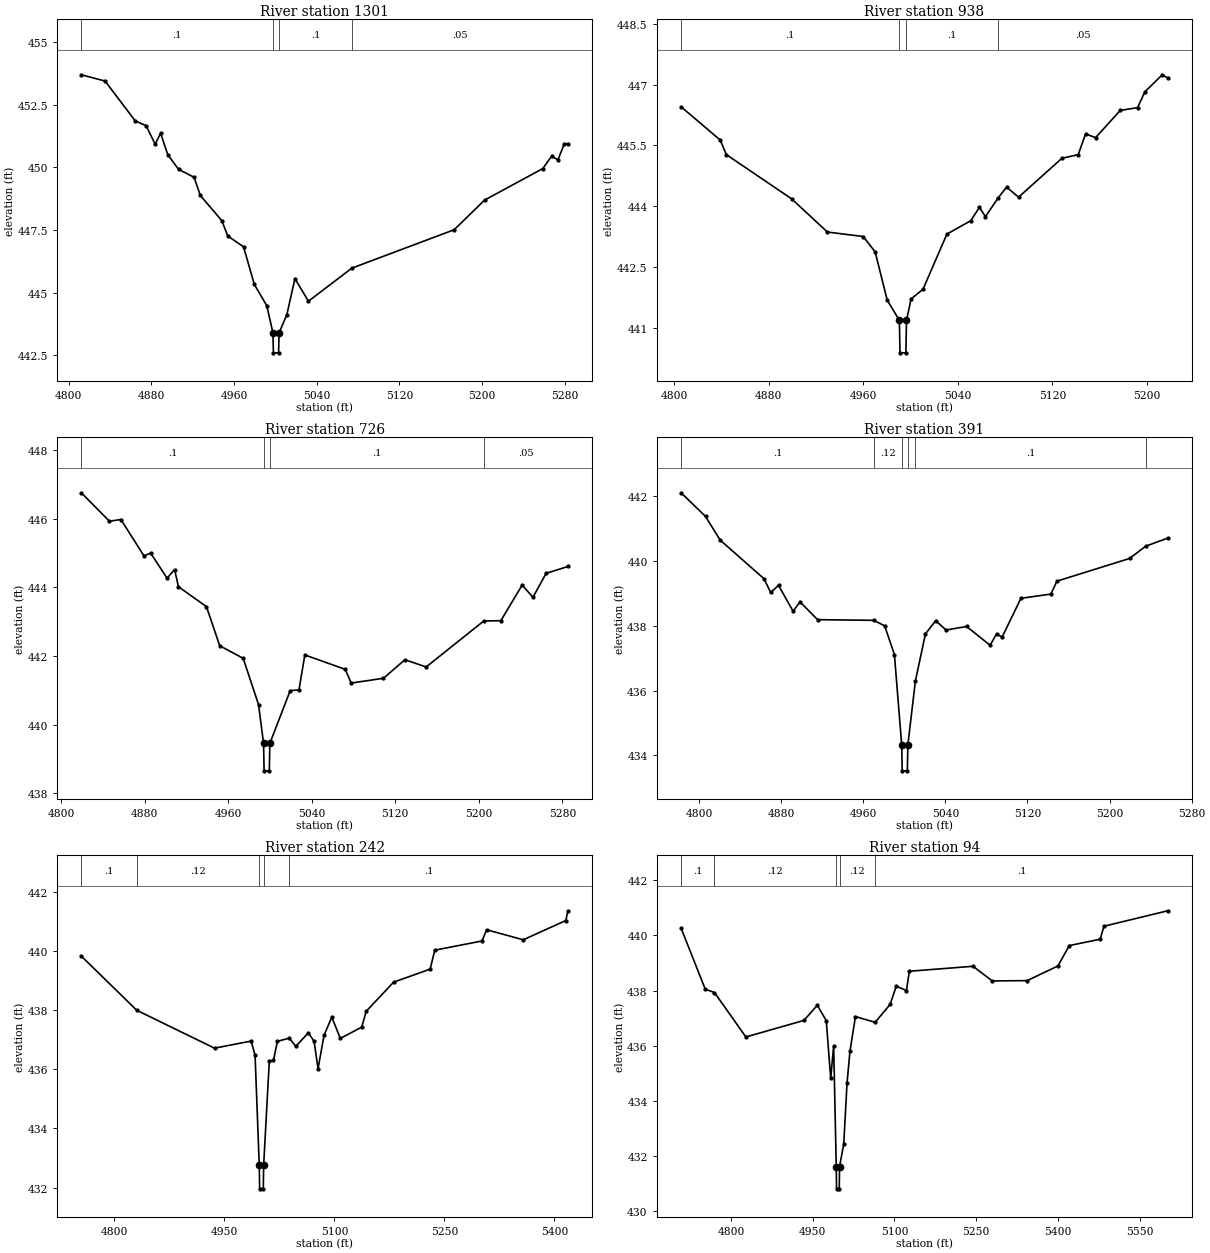
Type RM Length L Ch R = 1,1301,363,363,363
BEGIN DESCRIPTION:
Mapping XS 6df442c6
END DESCRIPTION:
XS GIS Cut Line= 4
      2065000.15     13476121.26      2064959.33     13476136.89
      2064870.79     13476420.75      2064947.16     13476525.76
#Sta/Elev= 30
  4812.1  453.69  4835.1  453.44  4864.3  451.85  4874.8  451.66  4883.6  450.92
  4888.8  451.36  4895.7  450.51  4906.2  449.92  4921.3  449.60  4927.2  448.88
  4948.1  447.87  4953.8  447.26  4969.1  446.83  4979.5  445.33  4991.6  444.48
  4997.5  443.40  4998.0  442.60  5003.0  442.60  5003.5  443.40  5011.0  444.12
  5018.8  445.56  5031.9  444.66  5074.0  445.98  5172.9  447.51  5202.3  448.69
  5258.7  449.95  5267.2  450.44  5273.4  450.30  5279.5  450.94  5283.0  450.94
#Mann=4,-1,0
  4812.1     0.1       0  4997.5    0.07       0  5003.5     0.1       0
  5074.0    0.05       0
Bank Sta=4997.5,5003.5
Exp/Cntr=0.3,0.1

Type RM Length L Ch R = 1,938,212,212,212
BEGIN DESCRIPTION:
Mapping XS 5a564b8f
END DESCRIPTION:
XS GIS Cut Line= 4
      2064661.62     13476151.64      2064597.35     13476168.14
      2064560.03     13476422.48      2064631.46     13476474.36
#Sta/Elev= 30
  4805.9  446.45  4839.0  445.63  4844.2  445.27  4899.4  444.18  4929.7  443.36
  4960.0  443.25  4970.1  442.87  4980.3  441.68  4990.6  441.18  4991.1  440.38
  4996.1  440.38  4996.6  441.18  5000.5  441.71  5010.6  441.95  5030.8  443.31
  5051.0  443.64  5058.3  443.97  5063.4  443.74  5074.1  444.20  5081.3  444.47
  5091.4  444.22  5128.1  445.18  5141.9  445.27  5148.1  445.78  5156.6  445.69
  5177.4  446.36  5192.1  446.43  5198.3  446.82  5213.0  447.24  5217.6  447.16
#Mann=4,-1,0
  4805.9     0.1       0  4990.6    0.07       0  4996.6     0.1       0
  5074.1    0.05       0
Bank Sta=4990.6,4996.6
Exp/Cntr=0.3,0.1

Type RM Length L Ch R = 1,726,335,335,335
BEGIN DESCRIPTION:
Mapping XS ea6c9c6d
END DESCRIPTION:
XS GIS Cut Line= 4
      2064559.38     13476071.57      2064473.22     13476111.72
      2064387.28     13476278.38      2064424.83     13476457.83
#Sta/Elev= 30
  4819.4  446.76  4846.3  445.93  4857.3  445.98  4879.4  444.92  4885.8  445.00
  4901.5  444.27  4908.7  444.52  4912.4  444.02  4939.2  443.44  4951.9  442.30
  4974.4  441.93  4989.1  440.58  4993.9  439.45  4994.4  438.65  4999.4  438.65
  4999.9  439.45  5019.4  440.99  5027.8  441.01  5033.4  442.03  5072.1  441.61
  5077.8  441.21  5108.7  441.35  5129.2  441.89  5149.6  441.68  5204.7  443.02
  5221.1  443.03  5241.5  444.07  5251.8  443.71  5264.4  444.41  5285.3  444.61
#Mann=4,-1,0
  4819.4     0.1       0  4993.9    0.07       0  4999.9     0.1       0
  5204.7    0.05       0
Bank Sta=4993.9,4999.9
Exp/Cntr=0.3,0.1

Type RM Length L Ch R = 1,391,149,149,149
BEGIN DESCRIPTION:
Mapping XS d8d5bdf9
END DESCRIPTION:
XS GIS Cut Line= 4
      2064234.93     13475991.28      2064145.96     13476091.75
      2064132.94     13476221.09      2064214.34     13476414.47
#Sta/Elev= 30
  4782.6  442.11  4806.4  441.38  4820.6  440.65  4863.2  439.46  4869.9  439.03
  4877.5  439.25  4891.7  438.45  4898.4  438.74  4915.6  438.19  4970.1  438.17
  4980.9  438.00  4990.4  437.11  4997.5  434.32  4998.0  433.52  5003.0  433.52
  5003.5  434.32  5010.8  436.29  5020.6  437.75  5030.6  438.16  5040.7  437.87
  5060.7  437.98  5083.6  437.40  5089.9  437.75  5095.3  437.65  5113.6  438.85
  5142.8  438.98  5148.7  439.38  5219.4  440.08  5235.2  440.46  5256.6  440.71
#Mann=6,-1,0
  4782.6     0.1       0  4970.1    0.12       0  4997.5    0.07       0
  5003.5    0.12       0  5010.8     0.1       0  5235.2    0.05       0
Bank Sta=4997.5,5003.5
Exp/Cntr=0.3,0.1

Type RM Length L Ch R = 1,242,148,148,148
BEGIN DESCRIPTION:
Mapping XS f48ea486
END DESCRIPTION:
XS GIS Cut Line= 4
      2064158.11     13475977.18      2064042.67     13476055.29
      2063966.28     13476261.89      2064150.71     13476503.61
#Sta/Elev= 30
  4754.8  439.82  4830.4  437.99  4936.5  436.71  4986.4  436.95  4991.8  436.47
  4997.5  432.76  4998.0  431.96  5003.0  431.96  5003.5  432.76  5011.2  436.27
  5016.9  436.30  5022.2  436.94  5038.5  437.05  5047.3  436.77  5064.5  437.23
  5072.3  436.94  5077.7  436.02  5085.8  437.14  5096.4  437.76  5108.1  437.04
  5137.2  437.42  5143.5  437.96  5180.8  438.94  5230.6  439.38  5236.9  440.02
  5301.3  440.33  5307.6  440.71  5357.5  440.37  5415.6  441.02  5418.5  441.35
#Mann=5,-1,0
  4754.8     0.1       0  4830.4    0.12       0  4997.5    0.07       0
  5003.5    0.12       0  5038.5     0.1       0
Bank Sta=4997.5,5003.5
Exp/Cntr=0.3,0.1

Type RM Length L Ch R = 1,94,0,0,0
BEGIN DESCRIPTION:
UNT 123 in Lagunillas Cr Wtrshd 1.0
END DESCRIPTION:
XS GIS Cut Line= 4
      2064130.43     13475888.55      2063986.72     13475924.57
      2063858.25     13476256.98      2064124.20     13476541.09
#Sta/Elev= 30
  4708.1  440.26  4752.5  438.05  4769.4  437.93  4827.1  436.32  4933.8  436.92
  4958.3  437.47  4974.7  436.91  4982.9  434.82  4988.3  436.00  4993.1  431.62
  4993.6  430.82  4998.6  430.82  4999.1  431.62  5006.8  432.44  5012.9  434.65
  5018.2  435.80  5028.3  437.06  5064.5  436.85  5092.0  437.50  5103.3  438.16
  5122.0  438.00  5127.3  438.70  5244.3  438.88  5279.5  438.35  5343.5  438.36
  5400.1  438.89  5421.1  439.63  5477.8  439.86  5484.7  440.33  5601.8  440.89
#Mann=5,-1,0
  4708.1     0.1       0  4769.4    0.12       0  4993.1    0.07       0
  4999.1    0.12       0  5064.5     0.1       0
Bank Sta=4993.1,4999.1
Exp/Cntr=0.3,0.1

Chan Stop Cuts=-1