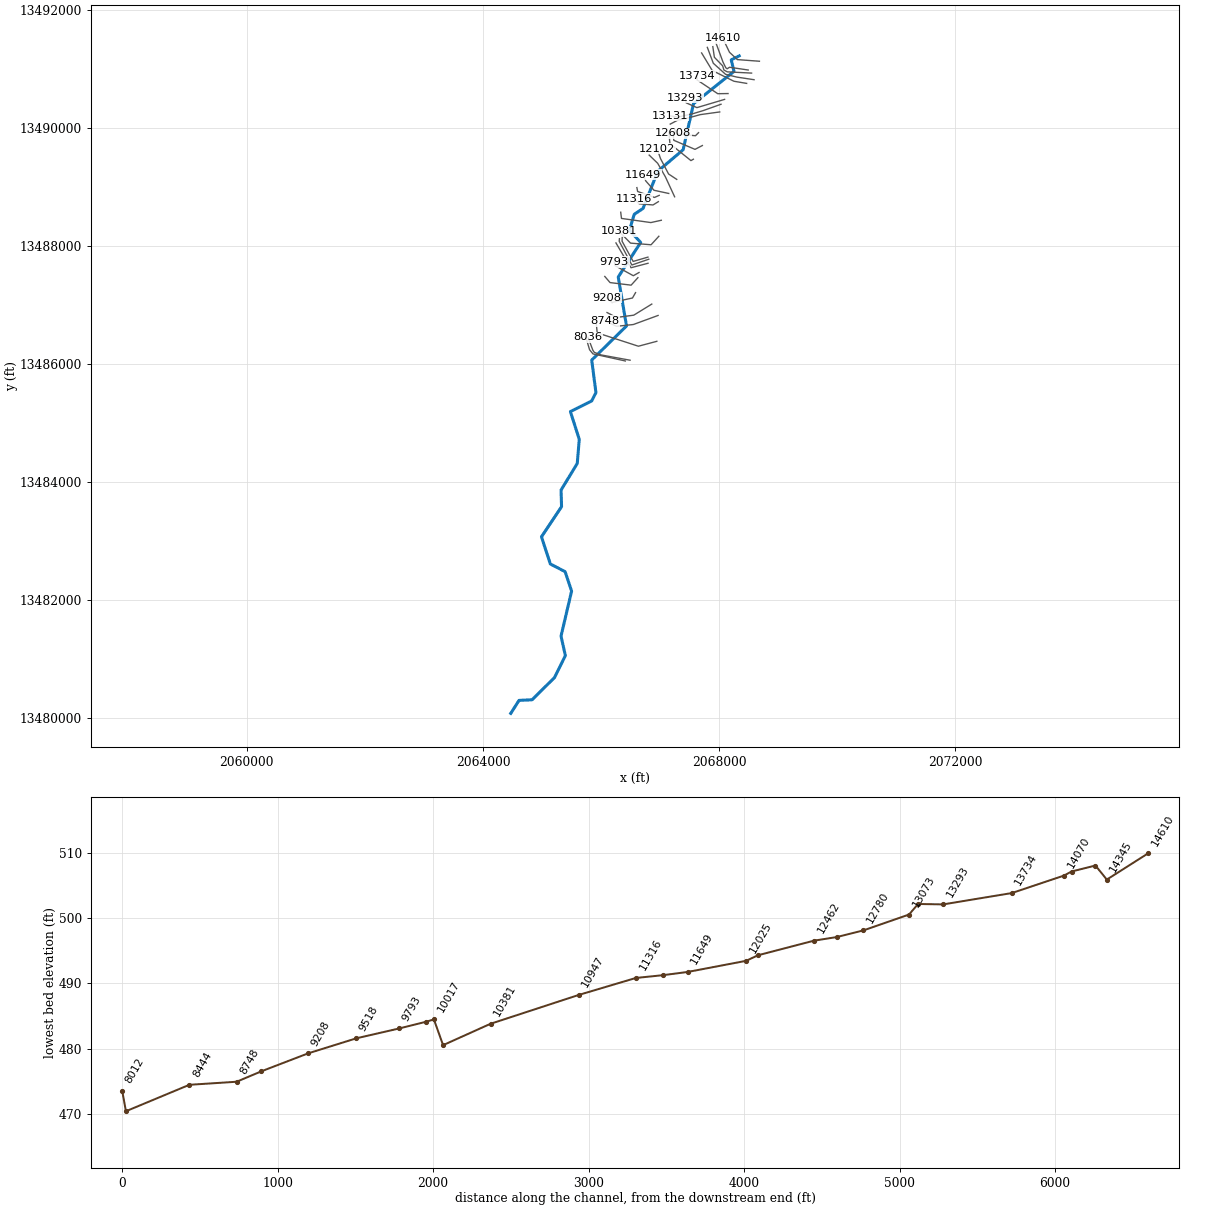
--- UNT 124 in Lagunillas Cr Wtrshd.prj (project) ---

Proj Title=UNT 124 in Lagunillas Cr Wtrshd Base Level Engineering
Current Plan=p01
Default Exp/Contr=0.3,0.1
English Units
Geom File=g01
Flow File=f01
Plan File=p01
BEGIN DESCRIPTION:
UNT 124 in Lagunillas Cr Wtrshd
END DESCRIPTION:

--- UNT 124 in Lagunillas Cr Wtrshd.p01 (plan) ---

Plan Title=Multiple Run
Short Identifier=Multiple
Geom File=g01
Flow File=f01
Subcritical Flow
K Sum by GR= 0
Std Step Tol= 0.01
Critical Tol= 0.01
Num of Std Step Trials= 20
Max Error Tol= 0.3
Flow Tol Ratio= 0.001
Split Flow NTrial= 30
Split Flow Tol= 0.02
Split Flow Ratio= 0.02
Log Output Level= 0
Friction Slope Method= 1
Unsteady Friction Slope Method= 2
Unsteady Bridges Friction Slope Method= 1
Parabolic Critical Depth
Global Vel Dist=  1 , 1 , 1
Global Log Level= 0
CheckData=True
Encroach Param= -1, 0, 0, 0
BEGIN DESCRIPTION:
Multiple Run
END DESCRIPTION:

--- UNT 124 in Lagunillas Cr Wtrshd.f01 (steady flow) ---

Flow Title=Multiple
Number of Profiles=7
Profile Names=10-year,25-year,50-year,1pct_min,100-year,1pct_plu,500-year
River Rch & RM= UNT 124 in Lagun,Reach-1,14610
     155     208     250     151     301     600     439
River Rch & RM= UNT 124 in Lagun,Reach-1,8036
     235     322     394     240     479     955     717
Boundary for River Rch & Prof#=UNT 124 in Lagun,Reach-1,1
Up Type=0
Dn Type=3
Dn Slope=0.005
Boundary for River Rch & Prof#=UNT 124 in Lagun,Reach-1,2
Up Type=0
Dn Type=3
Dn Slope=0.005
Boundary for River Rch & Prof#=UNT 124 in Lagun,Reach-1,3
Up Type=0
Dn Type=3
Dn Slope=0.005
Boundary for River Rch & Prof#=UNT 124 in Lagun,Reach-1,4
Up Type=0
Dn Type=3
Dn Slope=0.005
Boundary for River Rch & Prof#=UNT 124 in Lagun,Reach-1,5
Up Type=0
Dn Type=3
Dn Slope=0.005
Boundary for River Rch & Prof#=UNT 124 in Lagun,Reach-1,6
Up Type=0
Dn Type=3
Dn Slope=0.005
Boundary for River Rch & Prof#=UNT 124 in Lagun,Reach-1,7
Up Type=0
Dn Type=3
Dn Slope=0.005

--- UNT 124 in Lagunillas Cr Wtrshd.g01 (geometry) ---

Geom Title=Existing Conditions

River Reach=UNT 124 in Lagun,Reach-1
Reach XY= 30
      2068338.84     13491218.09      2068204.29     13491150.81
      2068250.80     13490954.54      2067565.52     13490408.70
      2067389.57     13489628.44      2066960.80     13489264.54
      2066710.85     13488634.59      2066560.80     13488534.54
      2066480.80     13488264.54      2066670.82     13488059.00
      2066290.80     13487474.54      2066430.80     13486644.54
      2065841.56     13486067.37      2065913.01     13485516.75
      2065840.80     13485374.54      2065480.80     13485194.54
      2065630.80     13484724.54      2065596.80     13484316.53
      2065322.50     13483866.01      2065330.80     13483584.54
      2064990.80     13483074.54      2065140.80     13482614.54
      2065390.80     13482484.54      2065500.80     13482154.54
      2065321.89     13481392.66      2065395.50     13481062.80
      2065211.47     13480690.57      2064830.80     13480314.54
      2064610.80     13480304.54      2064470.80     13480084.54

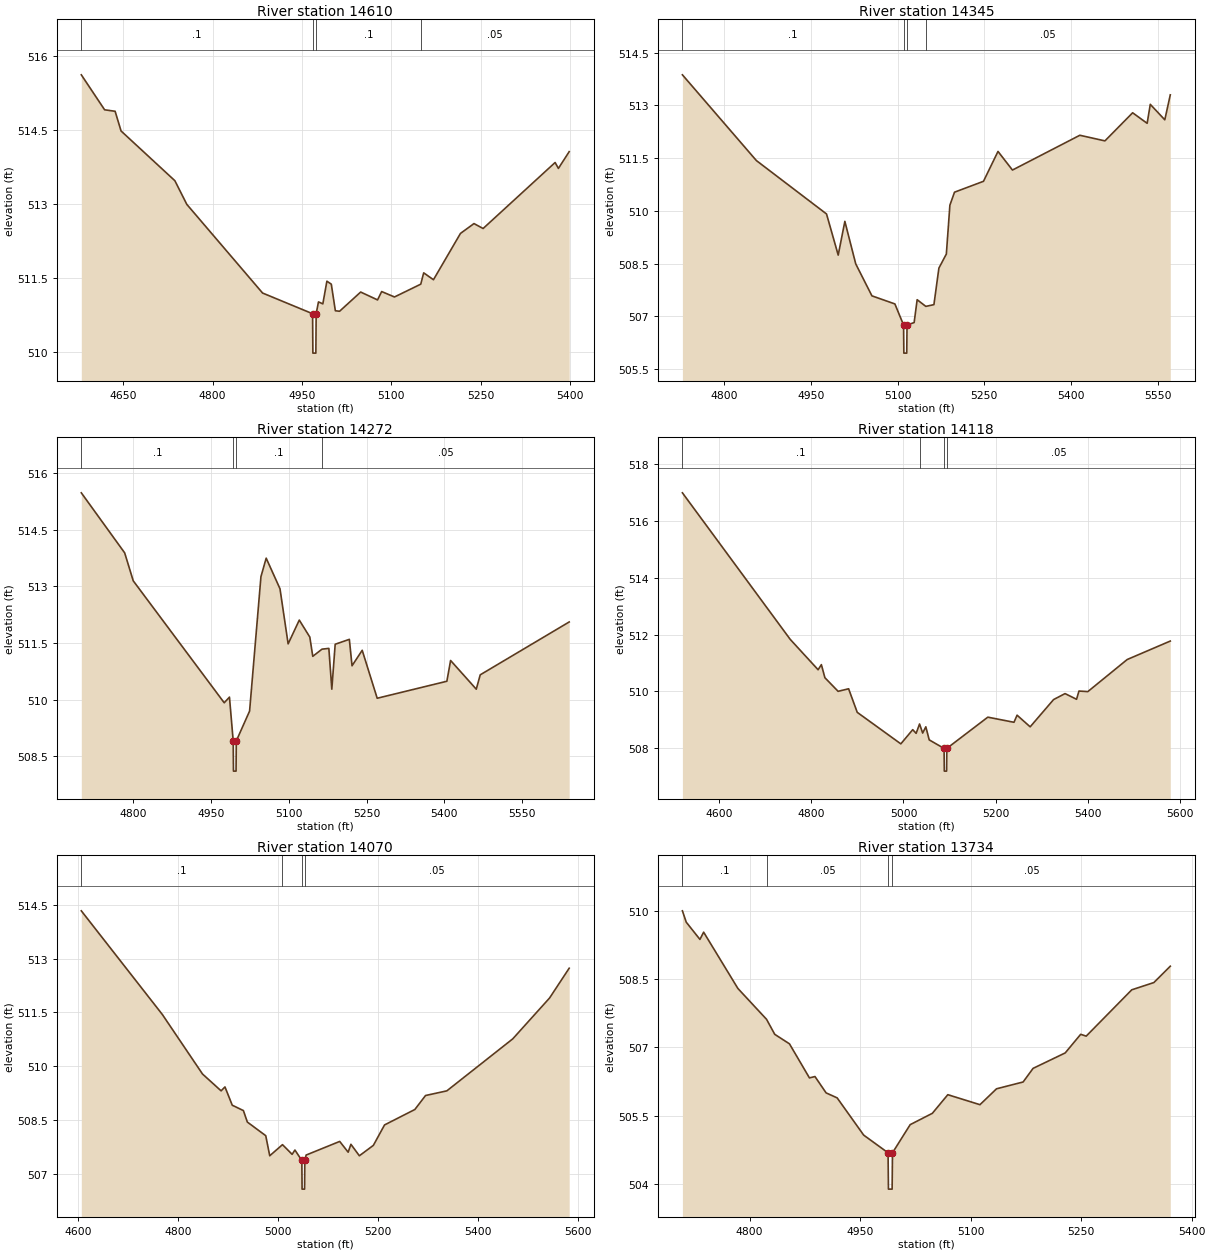
Type RM Length L Ch R = 1,14610,265,265,265
BEGIN DESCRIPTION:
Mapping XS d76d9419
END DESCRIPTION:
XS GIS Cut Line= 4
      2068681.53     13491127.28      2068307.69     13491155.12
      2068174.35     13491279.60      2068061.72     13491515.28
#Sta/Elev= 30
  4579.9  515.62  4619.0  514.91  4636.6  514.88  4646.6  514.48  4736.9  513.47
  4756.9  512.99  4884.0  511.19  4967.9  510.77  4968.4  509.97  4973.4  509.97
  4973.9  510.77  4977.8  511.01  4985.1  510.97  4991.9  511.43  4999.3  511.37
  5006.1  510.83  5013.2  510.82  5048.6  511.21  5076.9  511.05  5083.8  511.22
  5105.3  511.11  5149.4  511.37  5154.3  511.60  5170.7  511.46  5216.0  512.40
  5238.7  512.60  5254.0  512.50  5374.8  513.84  5380.3  513.72  5398.4  514.06
#Mann=4,-1,0
  4579.9     0.1       0  4967.9    0.07       0  4973.9     0.1       0
  5149.4    0.05       0
Bank Sta=4967.9,4973.9
Exp/Cntr=0.3,0.1

Type RM Length L Ch R = 1,14345,73,73,73
BEGIN DESCRIPTION:
Mapping XS ff97929e
END DESCRIPTION:
XS GIS Cut Line= 6
      2068491.37     13490978.85      2068176.29     13491025.72
      2068134.63     13490999.68      2068111.19     13491017.91
      2068064.31     13491114.26      2067947.48     13491431.02
#Sta/Elev= 30
  4728.0  513.87  4855.9  511.43  4977.2  509.91  4997.4  508.74  5008.9  509.70
  5027.7  508.49  5055.7  507.58  5095.4  507.35  5110.4  506.75  5110.9  505.95
  5115.9  505.95  5116.4  506.75  5128.7  506.82  5133.9  507.47  5148.9  507.28
  5162.9  507.33  5171.5  508.37  5184.4  508.77  5190.5  510.16  5198.5  510.53
  5248.6  510.84  5273.7  511.69  5298.7  511.16  5415.2  512.15  5458.6  511.99
  5506.5  512.79  5531.6  512.49  5537.0  513.03  5562.1  512.59  5571.6  513.30
#Mann=4,-1,0
  4728.0     0.1       0  5110.4    0.07       0  5116.4     0.1       0
  5148.9    0.05       0
Bank Sta=5110.4,5116.4
Exp/Cntr=0.3,0.1

Type RM Length L Ch R = 1,14272,154,154,154
BEGIN DESCRIPTION:
Mapping XS 4d6bc02f
END DESCRIPTION:
XS GIS Cut Line= 6
      2068548.65     13490926.76      2068137.23     13490947.60
      2068079.94     13490978.85      2068059.10     13491049.16
      2067918.48     13491194.99      2067892.43     13491374.71
#Sta/Elev= 30
  4700.0  515.48  4783.6  513.89  4800.1  513.15  4975.5  509.92  4985.6  510.07
  4992.8  508.91  4993.3  508.11  4998.3  508.11  4998.8  508.91  5024.4  509.70
  5046.3  513.26  5056.4  513.75  5083.0  512.94  5098.7  511.48  5120.2  512.11
  5140.5  511.66  5146.2  511.15  5164.0  511.34  5177.2  511.36  5182.9  510.28
  5189.4  511.47  5216.7  511.60  5221.9  510.90  5241.5  511.31  5270.4  510.04
  5404.7  510.49  5411.9  511.04  5461.4  510.28  5469.0  510.66  5640.5  512.06
#Mann=4,-1,0
  4700.0     0.1       0  4992.8    0.07       0  4998.8     0.1       0
  5164.0    0.05       0
Bank Sta=4992.8,4998.8
Exp/Cntr=0.3,0.1

Type RM Length L Ch R = 1,14118,48,48,48
BEGIN DESCRIPTION:
Mapping XS 76081fb5
END DESCRIPTION:
XS GIS Cut Line= 5
      2068590.39     13490814.78      2068298.69     13490859.06
      2068108.58     13490905.93      2067900.25     13491093.43
      2067799.35     13491362.51
#Sta/Elev= 30
  4520.4  516.99  4754.3  511.83  4814.8  510.76  4821.9  510.94  4829.5  510.48
  4858.2  510.00  4881.0  510.09  4899.7  509.26  4994.3  508.15  5020.1  508.65
  5027.5  508.52  5034.9  508.85  5041.7  508.53  5048.5  508.75  5055.9  508.29
  5088.1  507.99  5088.6  507.19  5093.6  507.19  5094.1  507.99  5183.0  509.09
  5239.8  508.91  5246.5  509.16  5274.9  508.75  5325.7  509.71  5350.6  509.92
  5375.5  509.72  5380.8  510.01  5400.0  509.99  5485.4  511.12  5578.9  511.77
#Mann=4,-1,0
  4520.4     0.1       0  5034.9    0.05       0  5088.1    0.07       0
  5094.1    0.05       0
Bank Sta=5088.1,5094.1
Exp/Cntr=0.3,0.1

Type RM Length L Ch R = 1,14070,336,336,336
BEGIN DESCRIPTION:
Mapping XS f9fa5433
END DESCRIPTION:
XS GIS Cut Line= 4
      2068465.32     13490752.29      2068249.21     13490788.74
      2067882.02     13490971.03      2067702.35     13491267.88
#Sta/Elev= 30
  4606.1  514.33  4768.2  511.44  4848.6  509.78  4885.8  509.31  4893.5  509.42
  4908.1  508.91  4930.4  508.76  4938.3  508.44  4975.1  508.06  4983.1  507.50
  5008.6  507.81  5027.9  507.54  5033.5  507.66  5047.3  507.37  5047.8  506.57
  5052.8  506.57  5053.3  507.37  5055.9  507.52  5123.1  507.90  5140.0  507.60
  5145.5  507.82  5162.4  507.50  5190.4  507.79  5212.8  508.36  5273.4  508.79
  5294.8  509.18  5337.4  509.31  5469.3  510.76  5543.0  511.90  5582.2  512.73
#Mann=4,-1,0
  4606.1     0.1       0  5008.6    0.05       0  5047.3    0.07       0
  5053.3    0.05       0
Bank Sta=5047.3,5053.3
Exp/Cntr=0.3,0.1

Type RM Length L Ch R = 1,13734,441,441,441
BEGIN DESCRIPTION:
Mapping XS cc847c23
END DESCRIPTION:
XS GIS Cut Line= 4
      2068150.24     13490580.41      2067975.77     13490577.81
      2067624.21     13490812.18      2067624.21     13490877.26
#Sta/Elev= 30
  4708.9  510.01  4714.1  509.76  4732.7  509.38  4737.7  509.54  4784.2  508.30
  4823.1  507.62  4834.2  507.29  4854.2  507.08  4881.3  506.33  4888.8  506.36
  4903.9  506.00  4918.9  505.89  4954.9  505.07  4988.0  504.68  4988.5  503.88
  4993.5  503.88  4994.0  504.68  5018.0  505.30  5048.1  505.55  5069.1  505.96
  5112.7  505.74  5135.2  506.09  5171.3  506.24  5184.8  506.54  5228.4  506.88
  5249.4  507.29  5256.9  507.25  5318.7  508.27  5348.7  508.43  5371.0  508.79
#Mann=4,-1,0
  4708.9     0.1       0  4823.1    0.05       0  4988.0    0.03       0
  4994.0    0.05       0
Bank Sta=4988,4994
Exp/Cntr=0.3,0.1

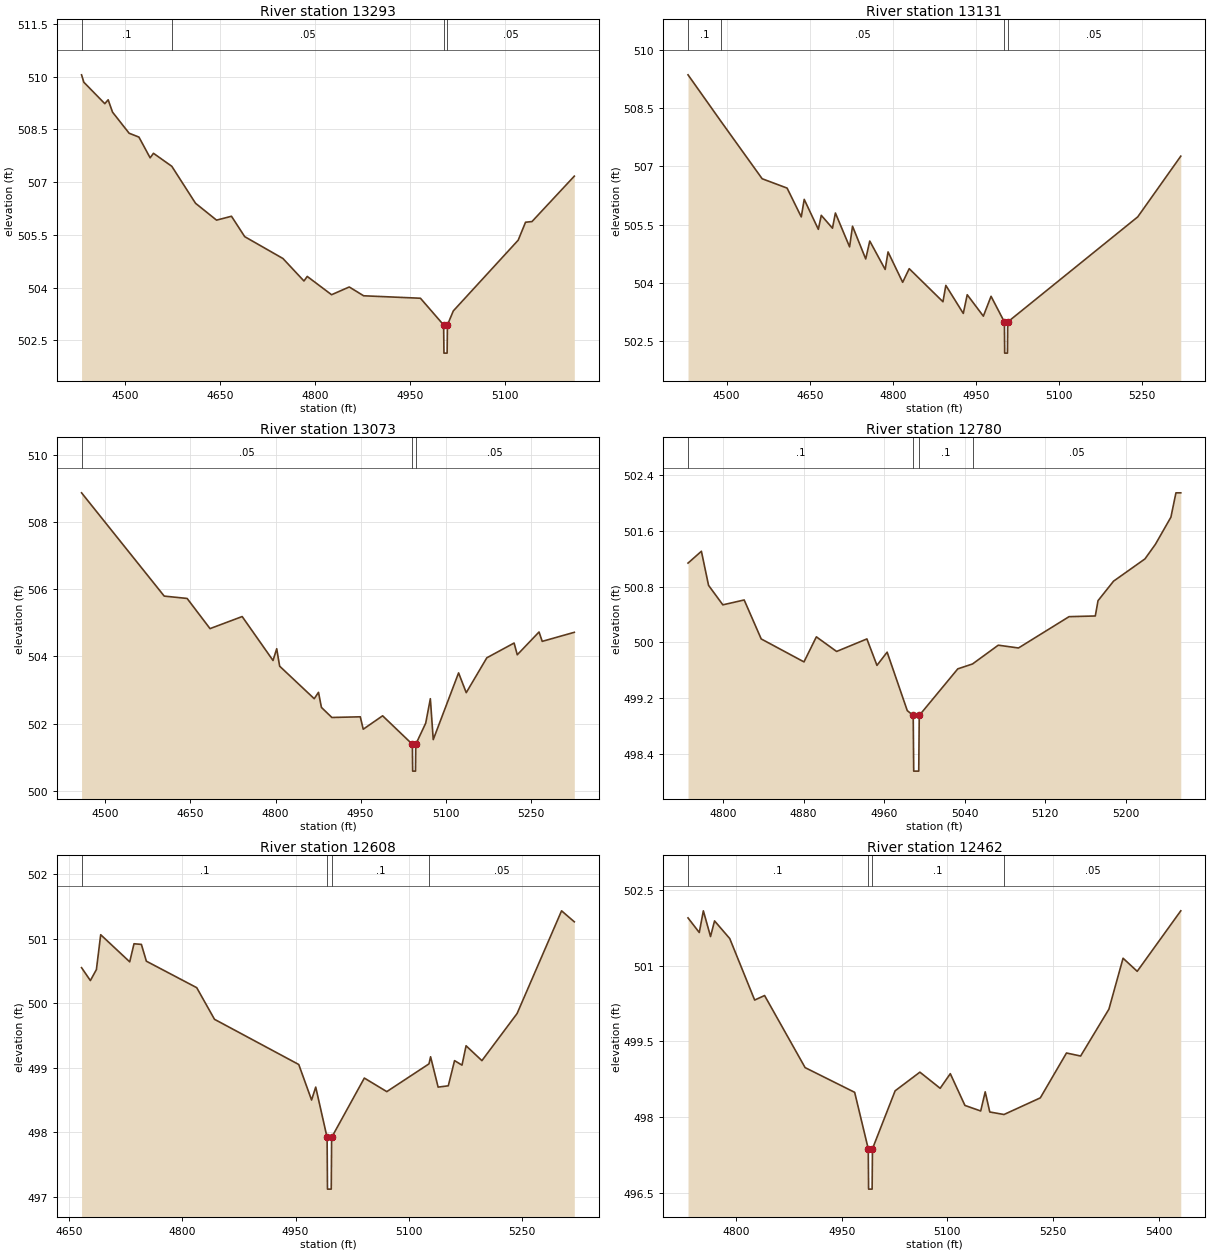
Type RM Length L Ch R = 1,13293,162,162,162
BEGIN DESCRIPTION:
Mapping XS e2c8e7fb
END DESCRIPTION:
XS GIS Cut Line= 4
      2068091.86     13490481.47      2067622.63     13490341.89
      2067440.34     13490423.66      2067423.27     13490510.55
#Sta/Elev= 30
  4431.3  510.05  4434.9  509.84  4468.0  509.23  4473.3  509.34  4480.2  508.99
  4506.4  508.39  4521.9  508.28  4539.6  507.69  4544.8  507.82  4573.8  507.45
  4611.2  506.40  4644.4  505.92  4668.0  506.03  4688.9  505.45  4749.2  504.83
  4782.4  504.19  4787.6  504.32  4826.0  503.80  4853.9  504.02  4876.6  503.77
  4966.3  503.70  5002.9  502.94  5003.4  502.14  5008.4  502.14  5008.9  502.94
  5018.2  503.34  5120.6  505.35  5132.2  505.86  5142.4  505.88  5209.2  507.17
#Mann=4,-1,0
  4431.3     0.1       0  4573.8    0.05       0  5002.9    0.03       0
  5008.9    0.05       0
Bank Sta=5002.9,5008.9
Exp/Cntr=0.3,0.1

Type RM Length L Ch R = 1,13131,58,58,58
BEGIN DESCRIPTION:
Mapping XS 48ee09ed
END DESCRIPTION:
XS GIS Cut Line= 5
      2068031.06     13490398.99      2067727.75     13490291.15
      2067560.22     13490240.80      2067305.01     13490182.64
      2067175.71     13490201.73
#Sta/Elev= 30
  4430.3  509.35  4490.0  508.15  4564.1  506.68  4609.1  506.44  4634.7  505.70
  4640.0  506.15  4665.5  505.38  4670.8  505.74  4691.0  505.41  4696.3  505.80
  4721.9  504.93  4727.2  505.46  4751.0  504.62  4758.3  505.08  4786.1  504.35
  4791.3  504.80  4817.7  504.02  4829.5  504.37  4890.4  503.52  4895.6  503.94
  4927.1  503.22  4934.2  503.70  4963.3  503.15  4977.2  503.66  5001.3  503.00
  5001.8  502.20  5006.8  502.20  5007.3  503.00  5241.9  505.70  5319.6  507.26
#Mann=4,-1,0
  4430.3     0.1       0  4490.0    0.05       0  5001.3    0.04       0
  5007.3    0.05       0
Bank Sta=5001.3,5007.3
Exp/Cntr=0.3,0.1

Type RM Length L Ch R = 1,13073,293,293,293
BEGIN DESCRIPTION:
Mapping XS a50784df
END DESCRIPTION:
XS GIS Cut Line= 5
      2068009.44     13490268.81      2067680.01     13490223.44
      2067451.71     13490160.07      2067291.12     13490126.22
      2067171.34     13490062.86
#Sta/Elev= 30
  4457.9  508.88  4603.7  505.80  4644.1  505.73  4684.5  504.83  4741.2  505.19
  4795.6  503.88  4802.1  504.23  4807.3  503.71  4868.3  502.74  4875.8  502.93
  4881.0  502.48  4899.4  502.18  4949.5  502.20  4954.7  501.83  4988.9  502.23
  5041.4  501.38  5041.9  500.58  5046.9  500.58  5047.4  501.38  5064.9  502.01
  5073.1  502.74  5078.2  501.52  5122.9  503.51  5136.4  502.92  5172.7  503.96
  5220.8  504.40  5226.4  504.05  5264.8  504.73  5270.4  504.45  5327.0  504.72
#Mann=3,-1,0
  4457.9    0.05       0  5041.4    0.04       0  5047.4    0.05       0
Bank Sta=5041.4,5047.4
Exp/Cntr=0.3,0.1

Type RM Length L Ch R = 1,12780,172,172,172
BEGIN DESCRIPTION:
Mapping XS 600100d3
END DESCRIPTION:
XS GIS Cut Line= 4
      2067650.69     13489918.17      2067598.58     13489866.06
      2067271.50     13489895.23      2067247.21     13489979.21
#Sta/Elev= 30
  4765.1  501.14  4778.4  501.31  4785.5  500.82  4799.7  500.54  4820.9  500.61
  4837.8  500.05  4880.3  499.72  4892.6  500.08  4912.7  499.87  4942.8  500.05
  4952.8  499.67  4962.9  499.86  4982.9  499.02  4988.8  498.95  4989.3  498.15
  4994.3  498.15  4994.8  498.95  5033.1  499.62  5047.7  499.69  5073.3  499.96
  5093.4  499.92  5143.6  500.37  5169.7  500.38  5172.4  500.60  5187.8  500.88
  5219.0  501.20  5229.4  501.41  5244.8  501.80  5249.8  502.15  5254.6  502.15
#Mann=4,-1,0
  4765.1     0.1       0  4988.8    0.07       0  4994.8     0.1       0
  5047.7    0.05       0
Bank Sta=4988.8,4994.8
Exp/Cntr=0.3,0.1

Type RM Length L Ch R = 1,12608,146,146,146
BEGIN DESCRIPTION:
Mapping XS 97d46aa5
END DESCRIPTION:
XS GIS Cut Line= 4
      2067715.38     13489700.22      2067590.35     13489635.10
      2067231.57     13489788.63      2067218.60     13489910.52
#Sta/Elev= 30
  4666.1  500.55  4677.8  500.35  4685.8  500.52  4691.5  501.06  4730.0  500.64
  4735.7  500.92  4745.5  500.91  4752.1  500.65  4818.9  500.24  4842.5  499.75
  4954.3  499.05  4971.3  498.50  4976.8  498.70  4991.9  497.92  4992.4  497.12
  4997.4  497.12  4997.9  497.92  5041.3  498.84  5071.1  498.63  5127.1  499.06
  5129.2  499.17  5139.2  498.70  5152.7  498.72  5161.0  499.11  5170.9  499.04
  5176.3  499.34  5197.3  499.11  5244.0  499.84  5303.0  501.43  5319.9  501.26
#Mann=4,-1,0
  4666.1     0.1       0  4991.9    0.07       0  4997.9     0.1       0
  5127.1    0.05       0
Bank Sta=4991.9,4997.9
Exp/Cntr=0.3,0.1

Type RM Length L Ch R = 1,12462,360,360,360
BEGIN DESCRIPTION:
Mapping XS cb2fe03a
END DESCRIPTION:
XS GIS Cut Line= 4
      2067563.15     13489468.31      2067521.50     13489444.88
      2067166.47     13489731.34      2067147.37     13489926.63
#Sta/Elev= 30
  4731.4  501.95  4747.4  501.66  4753.2  502.09  4763.4  501.58  4769.1  501.89
  4790.7  501.54  4826.1  500.32  4840.2  500.41  4897.8  498.98  4968.2  498.49
  4987.5  497.37  4988.0  496.57  4993.0  496.57  4993.5  497.37  5025.7  498.52
  5060.9  498.89  5089.7  498.57  5104.1  498.86  5124.9  498.23  5147.3  498.12
  5153.7  498.50  5160.2  498.10  5180.4  498.05  5232.0  498.38  5269.2  499.27
  5289.3  499.21  5329.5  500.14  5349.6  501.15  5369.7  500.89  5431.6  502.09
#Mann=4,-1,0
  4731.4     0.1       0  4987.5    0.07       0  4993.5     0.1       0
  5180.4    0.05       0
Bank Sta=4987.5,4993.5
Exp/Cntr=0.3,0.1

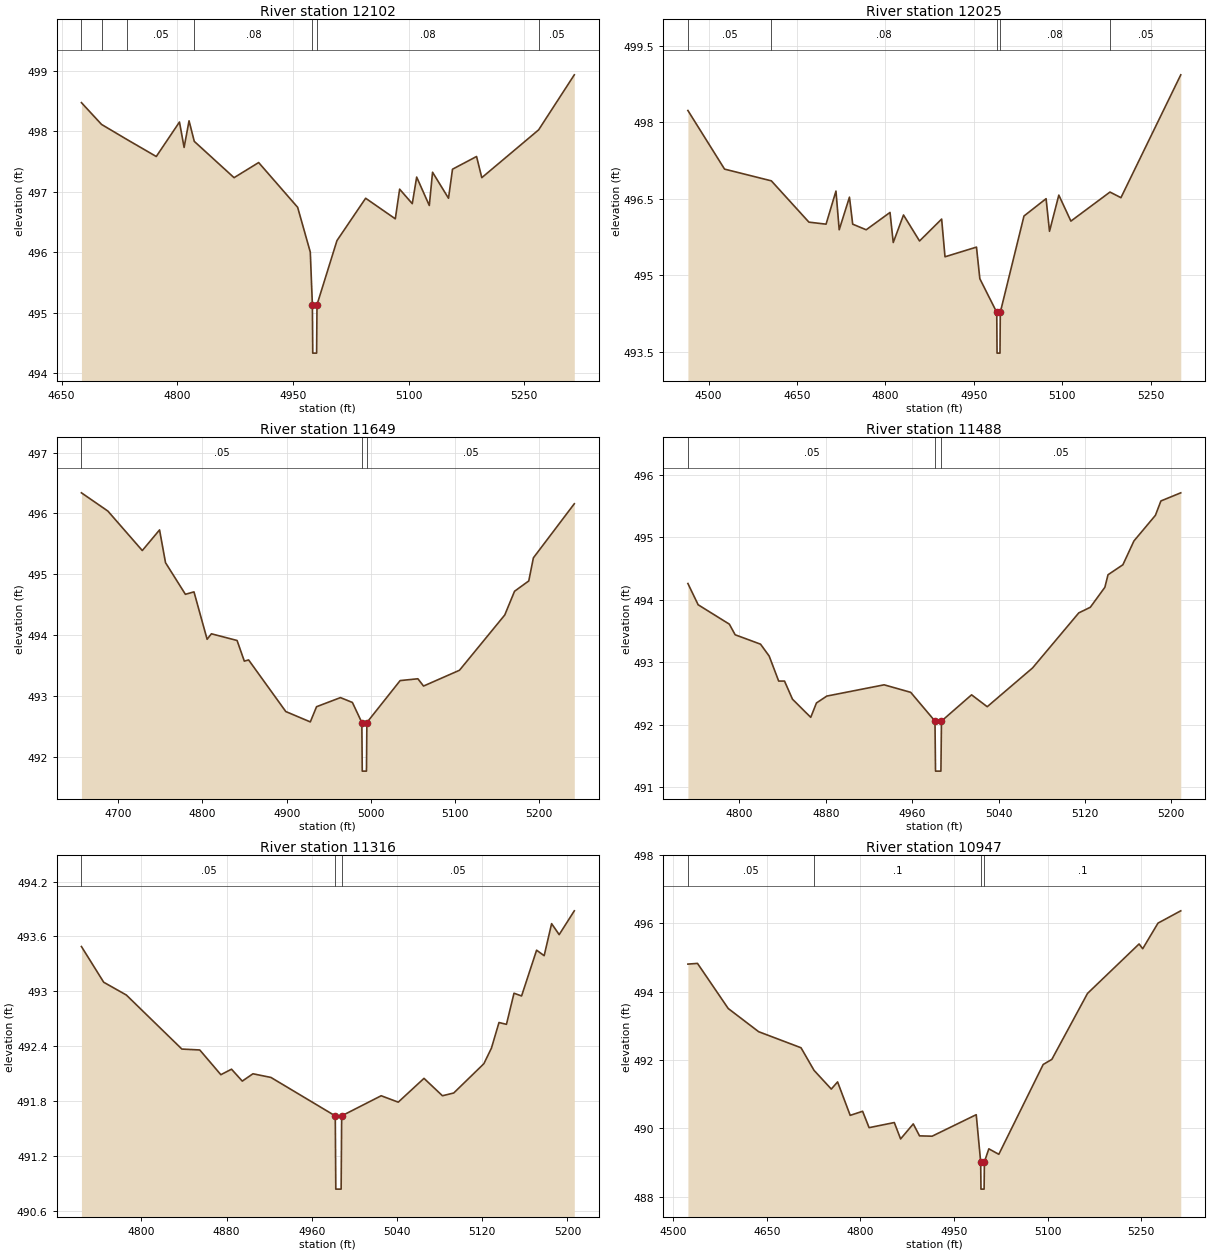
Type RM Length L Ch R = 1,12102,77,77,77
BEGIN DESCRIPTION:
Mapping XS 11cc215e
END DESCRIPTION:
XS GIS Cut Line= 4
      2067281.45     13489126.76      2067143.46     13489217.88
      2067007.18     13489477.43      2066948.16     13489648.42
#Sta/Elev= 30
  4675.7  498.47  4701.8  498.11  4734.9  497.86  4772.8  497.58  4802.9  498.15
  4808.9  497.73  4815.3  498.17  4822.1  497.83  4873.7  497.23  4905.6  497.48
  4956.2  496.74  4972.6  496.00  4975.3  495.13  4975.8  494.33  4980.8  494.33
  4981.3  495.13  5007.2  496.19  5044.4  496.89  5082.9  496.55  5088.5  497.04
  5104.9  496.80  5110.6  497.24  5127.0  496.77  5131.2  497.32  5151.9  496.89
  5157.1  497.37  5188.3  497.58  5195.1  497.23  5268.8  498.02  5315.1  498.93
#Mann=7,-1,0
  4675.7    0.05       0  4701.8    0.08       0  4734.9    0.05       0
  4822.1    0.08       0  4975.3    0.07       0  4981.3    0.08       0
  5268.8    0.05       0
Bank Sta=4975.3,4981.3
Exp/Cntr=0.3,0.1

Type RM Length L Ch R = 1,12025,376,376,376
BEGIN DESCRIPTION:
Mapping XS a98bb4b6
END DESCRIPTION:
XS GIS Cut Line= 4
      2067245.49     13488832.21      2067089.64     13489169.27
      2066958.57     13489399.31      2066814.50     13489538.17
#Sta/Elev= 30
  4464.8  498.23  4527.0  497.08  4606.4  496.85  4670.1  496.04  4699.2  496.00
  4716.0  496.65  4721.5  495.89  4738.9  496.53  4744.4  496.00  4767.3  495.89
  4807.7  496.23  4813.2  495.64  4830.6  496.18  4857.8  495.67  4895.3  496.10
  4901.0  495.36  4954.4  495.55  4960.1  494.93  4988.8  494.27  4989.3  493.47
  4994.3  493.47  4994.8  494.27  5035.0  496.16  5072.5  496.50  5078.3  495.86
  5094.1  496.57  5114.6  496.06  5180.9  496.63  5199.5  496.52  5301.0  498.93
#Mann=5,-1,0
  4464.8    0.05       0  4606.4    0.08       0  4988.8    0.07       0
  4994.8    0.08       0  5180.9    0.05       0
Bank Sta=4988.8,4994.8
Exp/Cntr=0.3,0.1

Type RM Length L Ch R = 1,11649,161,161,161
BEGIN DESCRIPTION:
Mapping XS bc12de09
END DESCRIPTION:
XS GIS Cut Line= 4
      2067145.73     13488888.58      2066896.70     13488942.13
      2066758.68     13489098.38      2066707.49     13489209.45
#Sta/Elev= 30
  4656.2  496.34  4687.6  496.04  4728.5  495.39  4749.0  495.73  4756.1  495.19
  4779.7  494.67  4789.9  494.71  4805.5  493.93  4810.6  494.02  4841.1  493.91
  4849.7  493.57  4854.8  493.59  4899.0  492.74  4928.1  492.57  4935.5  492.82
  4963.9  492.97  4978.1  492.89  4989.3  492.56  4989.8  491.76  4994.8  491.76
  4995.3  492.56  5034.8  493.25  5055.9  493.28  5062.6  493.16  5105.3  493.42
  5159.1  494.33  5170.7  494.72  5187.6  494.89  5193.1  495.27  5241.7  496.16
#Mann=3,-1,0
  4656.2    0.05       0  4989.3    0.03       0  4995.3    0.05       0
Bank Sta=4989.3,4995.3
Exp/Cntr=0.3,0.1

Type RM Length L Ch R = 1,11488,172,172,172
BEGIN DESCRIPTION:
Mapping XS 4489af7a
END DESCRIPTION:
XS GIS Cut Line= 4
      2066984.08     13488855.79      2066903.88     13488820.89
      2066618.98     13488921.94      2066606.48     13488987.61
#Sta/Elev= 30
  4752.2  494.26  4761.7  493.92  4790.6  493.61  4796.0  493.44  4819.5  493.29
  4827.5  493.10  4836.3  492.70  4841.7  492.70  4849.1  492.41  4866.0  492.12
  4871.3  492.35  4880.9  492.46  4934.0  492.64  4958.6  492.52  4981.1  492.06
  4981.6  491.26  4986.6  491.26  4987.1  492.06  5015.0  492.48  5029.5  492.29
  5071.5  492.91  5114.3  493.79  5125.0  493.88  5138.5  494.20  5141.4  494.40
  5155.2  494.56  5165.4  494.94  5185.3  495.35  5190.4  495.58  5208.8  495.71
#Mann=3,-1,0
  4752.2    0.05       0  4981.1    0.03       0  4987.1    0.05       0
Bank Sta=4981.1,4987.1
Exp/Cntr=0.3,0.1

Type RM Length L Ch R = 1,11316,369,369,369
BEGIN DESCRIPTION:
Mapping XS be382c66
END DESCRIPTION:
XS GIS Cut Line= 4
      2066970.04     13488749.55      2066879.40     13488693.81
      2066645.55     13488713.60      2066559.30     13488799.33
#Sta/Elev= 30
  4743.7  493.49  4764.6  493.10  4785.9  492.96  4838.0  492.37  4854.8  492.36
  4874.6  492.09  4884.6  492.15  4894.7  492.02  4904.7  492.10  4921.6  492.06
  4982.0  491.64  4982.5  490.84  4987.5  490.84  4988.0  491.64  5025.1  491.86
  5041.1  491.79  5065.3  492.05  5082.6  491.86  5093.2  491.89  5121.5  492.21
  5128.6  492.38  5135.7  492.66  5142.7  492.64  5149.8  492.98  5156.9  492.95
  5171.0  493.45  5178.1  493.39  5185.1  493.74  5192.2  493.62  5206.4  493.88
#Mann=3,-1,0
  4743.7    0.05       0  4982.0    0.03       0  4988.0    0.05       0
Bank Sta=4982,4988
Exp/Cntr=0.3,0.1

Type RM Length L Ch R = 1,10947,566,566,566
BEGIN DESCRIPTION:
Mapping XS ea2f61b8
END DESCRIPTION:
XS GIS Cut Line= 4
      2067020.04     13488434.57      2066842.96     13488395.51
      2066345.56     13488465.83      2066332.70     13488571.27
#Sta/Elev= 30
  4523.6  494.81  4539.0  494.83  4588.2  493.51  4637.0  492.83  4704.9  492.36
  4725.7  491.70  4753.4  491.15  4763.5  491.36  4783.7  490.38  4803.6  490.50
  4814.0  490.02  4854.4  490.17  4864.5  489.69  4884.8  490.13  4894.8  489.78
  4915.0  489.77  4985.7  490.40  4992.8  489.02  4993.3  488.22  4998.3  488.22
  4998.8  489.02  5005.9  489.40  5021.9  489.24  5093.0  491.87  5106.9  492.02
  5164.0  493.95  5246.7  495.40  5252.5  495.26  5277.0  496.01  5313.5  496.37
#Mann=4,-1,0
  4523.6    0.05       0  4725.7     0.1       0  4992.8    0.07       0
  4998.8     0.1       0
Bank Sta=4992.8,4998.8
Exp/Cntr=0.3,0.1

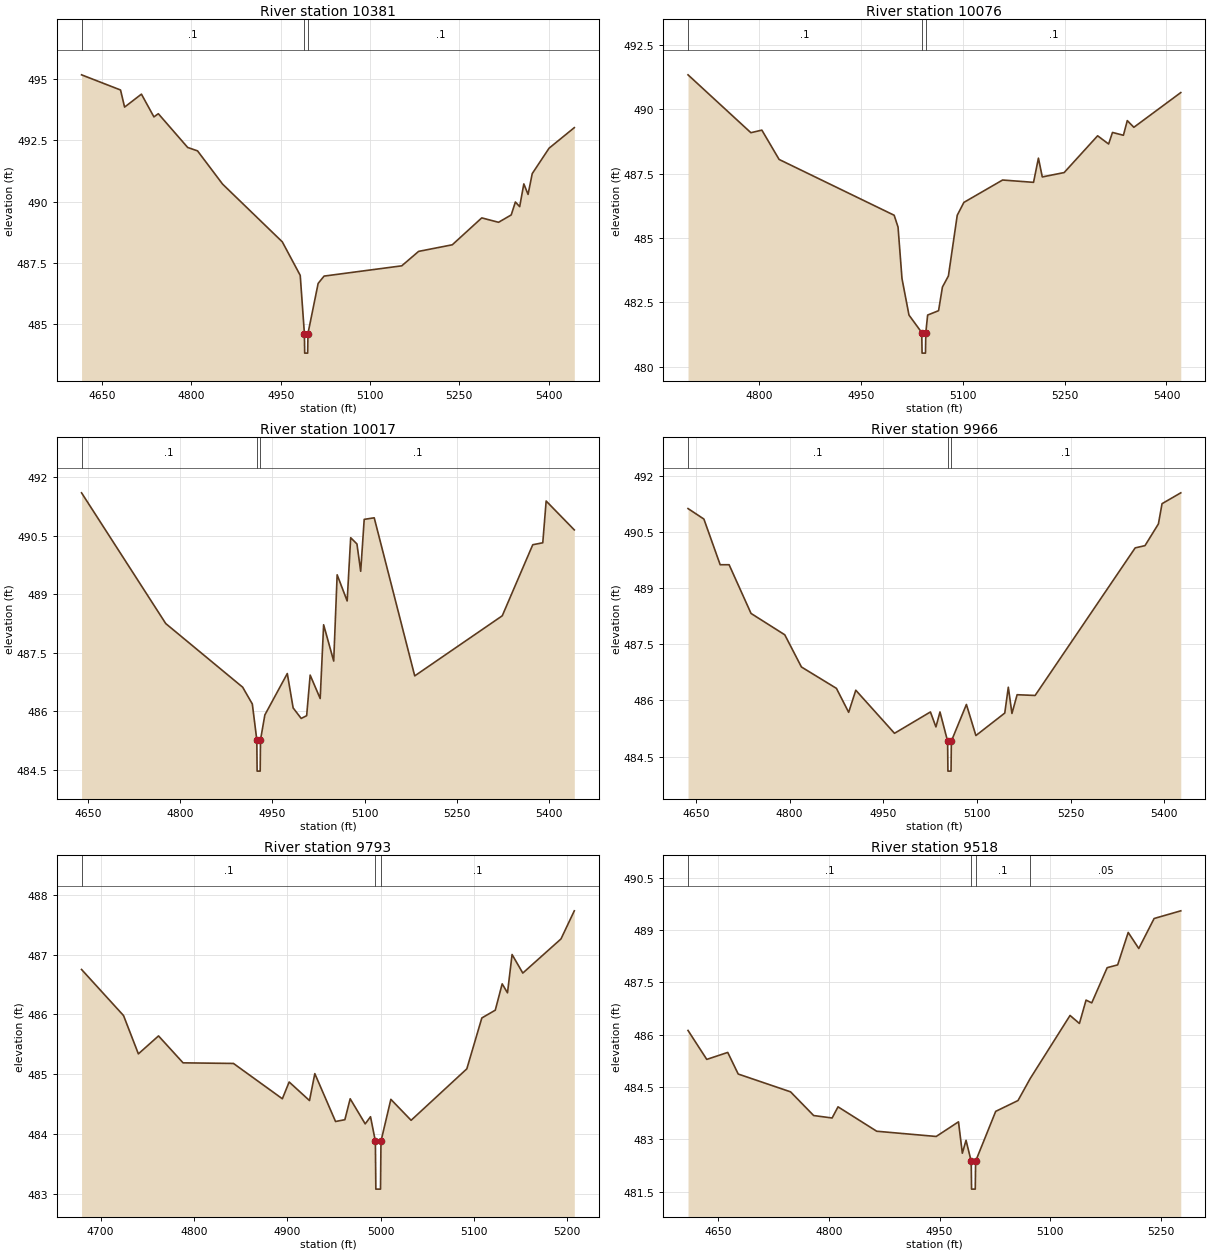
Type RM Length L Ch R = 1,10381,305,305,305
BEGIN DESCRIPTION:
Mapping XS 2edf4729
END DESCRIPTION:
XS GIS Cut Line= 4
      2066978.38     13488163.75      2066846.83     13488019.77
      2066498.74     13488047.54      2066300.49     13488250.44
#Sta/Elev= 30
  4615.3  495.18  4680.8  494.56  4687.6  493.86  4715.9  494.39  4736.9  493.46
  4744.3  493.59  4793.6  492.21  4810.2  492.07  4852.3  490.71  4952.6  488.35
  4982.7  486.98  4989.7  484.60  4990.2  483.80  4995.2  483.80  4995.7  484.60
  5012.8  486.65  5022.8  486.95  5153.3  487.37  5181.6  487.96  5238.2  488.23
  5287.7  489.33  5315.9  489.15  5337.2  489.45  5344.2  489.98  5351.4  489.79
  5358.4  490.72  5365.5  490.29  5372.5  491.14  5400.8  492.18  5443.2  493.02
#Mann=3,-1,0
  4615.3     0.1       0  4989.7    0.07       0  4995.7     0.1       0
Bank Sta=4989.7,4995.7
Exp/Cntr=0.3,0.1

Type RM Length L Ch R = 1,10076,59,59,59
BEGIN DESCRIPTION:
Mapping XS accef6fa
END DESCRIPTION:
XS GIS Cut Line= 4
      2066793.88     13487810.57      2066543.01     13487737.65
      2066355.51     13488080.53      2066358.11     13488154.33
#Sta/Elev= 30
  4695.2  491.34  4787.8  489.09  4804.0  489.19  4829.4  488.05  4998.9  485.88
  5004.6  485.42  5010.4  483.42  5020.7  482.00  5039.5  481.32  5040.0  480.52
  5045.0  480.52  5045.5  481.32  5048.2  482.00  5064.3  482.17  5070.0  483.09
  5078.8  483.52  5091.8  485.88  5101.6  486.38  5158.6  487.25  5204.2  487.16
  5211.4  488.10  5217.1  487.37  5249.3  487.54  5298.6  488.97  5314.8  488.65
  5320.5  489.10  5336.6  488.99  5342.3  489.56  5352.0  489.30  5421.1  490.65
#Mann=3,-1,0
  4695.2     0.1       0  5039.5    0.07       0  5045.5     0.1       0
Bank Sta=5039.5,5045.5
Exp/Cntr=0.3,0.1

Type RM Length L Ch R = 1,10017,51,51,51
BEGIN DESCRIPTION:
Mapping XS 85c42142
END DESCRIPTION:
XS GIS Cut Line= 4
      2066807.79     13487774.98      2066521.31     13487676.88
      2066306.90     13488079.66      2066311.04     13488121.95
#Sta/Elev= 30
  4639.4  491.60  4776.4  488.25  4901.5  486.62  4917.2  486.19  4924.5  485.27
  4925.0  484.47  4930.0  484.47  4930.5  485.27  4937.6  485.91  4974.1  486.97
  4983.6  486.09  4996.7  485.82  5005.6  485.89  5011.3  486.93  5027.6  486.33
  5033.2  488.22  5049.6  487.29  5055.2  489.50  5071.5  488.83  5077.2  490.45
  5087.4  490.29  5093.5  489.59  5099.2  490.92  5115.5  490.96  5181.4  486.91
  5323.8  488.45  5373.4  490.27  5389.7  490.32  5395.2  491.39  5441.0  490.65
#Mann=3,-1,0
  4639.4     0.1       0  4924.5    0.07       0  4930.5     0.1       0
Bank Sta=4924.5,4930.5
Exp/Cntr=0.3,0.1

Type RM Length L Ch R = 1,9966,173,173,173
BEGIN DESCRIPTION:
Mapping XS afc019aa
END DESCRIPTION:
XS GIS Cut Line= 4
      2066794.77     13487706.40      2066507.42     13487630.88
      2066394.57     13487807.96      2066251.88     13488050.97
#Sta/Elev= 30
  4637.5  491.12  4662.9  490.84  4689.0  489.62  4703.3  489.62  4738.4  488.32
  4792.4  487.75  4819.1  486.89  4875.1  486.32  4894.7  485.68  4906.1  486.27
  4968.1  485.12  5025.6  485.69  5034.4  485.29  5040.9  485.69  5053.1  484.91
  5053.6  484.11  5058.6  484.11  5059.1  484.91  5083.2  485.89  5098.4  485.06
  5144.6  485.66  5150.3  486.35  5156.1  485.65  5164.4  486.15  5193.2  486.13
  5353.4  490.07  5369.1  490.13  5390.6  490.71  5396.4  491.25  5426.4  491.54
#Mann=3,-1,0
  4637.5     0.1       0  5053.1    0.07       0  5059.1     0.1       0
Bank Sta=5053.1,5059.1
Exp/Cntr=0.3,0.1

Type RM Length L Ch R = 1,9793,275,275,275
BEGIN DESCRIPTION:
Mapping XS 6566be13
END DESCRIPTION:
XS GIS Cut Line= 4
      2066642.84     13487550.15      2066546.48     13487495.46
      2066238.32     13487664.73      2066224.43     13487728.96
#Sta/Elev= 30
  4679.5  486.75  4724.5  485.98  4740.4  485.34  4762.0  485.64  4788.3  485.19
  4842.3  485.18  4894.7  484.59  4902.0  484.87  4923.8  484.56  4929.5  485.01
  4951.7  484.21  4961.7  484.24  4967.4  484.59  4983.5  484.17  4989.2  484.29
  4994.4  483.88  4994.9  483.08  4999.9  483.08  5000.4  483.88  5011.0  484.58
  5032.7  484.23  5092.4  485.09  5108.5  485.94  5122.9  486.07  5130.3  486.51
  5136.0  486.36  5140.9  487.00  5152.4  486.69  5193.3  487.26  5207.6  487.73
#Mann=3,-1,0
  4679.5     0.1       0  4994.4    0.07       0  5000.4     0.1       0
Bank Sta=4994.4,5000.4
Exp/Cntr=0.3,0.1

Type RM Length L Ch R = 1,9518,310,310,310
BEGIN DESCRIPTION:
Mapping XS 6fcef9cc
END DESCRIPTION:
XS GIS Cut Line= 4
      2066623.72     13487462.46      2066509.15     13487335.74
      2066152.38     13487379.14      2066062.98     13487483.30
#Sta/Elev= 30
  4609.2  486.12  4634.6  485.29  4663.0  485.49  4677.2  484.87  4748.1  484.36
  4779.4  483.68  4804.4  483.61  4812.4  483.93  4864.8  483.23  4945.4  483.08
  4975.6  483.50  4980.8  482.60  4985.8  482.97  4992.8  482.37  4993.3  481.57
  4998.3  481.57  4998.8  482.37  5026.0  483.80  5056.2  484.11  5072.7  484.74
  5126.7  486.55  5139.4  486.32  5148.4  486.99  5156.1  486.91  5177.0  487.92
  5191.2  488.00  5205.5  488.93  5219.8  488.47  5240.6  489.33  5276.7  489.55
#Mann=4,-1,0
  4609.2     0.1       0  4992.8    0.07       0  4998.8     0.1       0
  5072.7    0.05       0
Bank Sta=4992.8,4998.8
Exp/Cntr=0.3,0.1

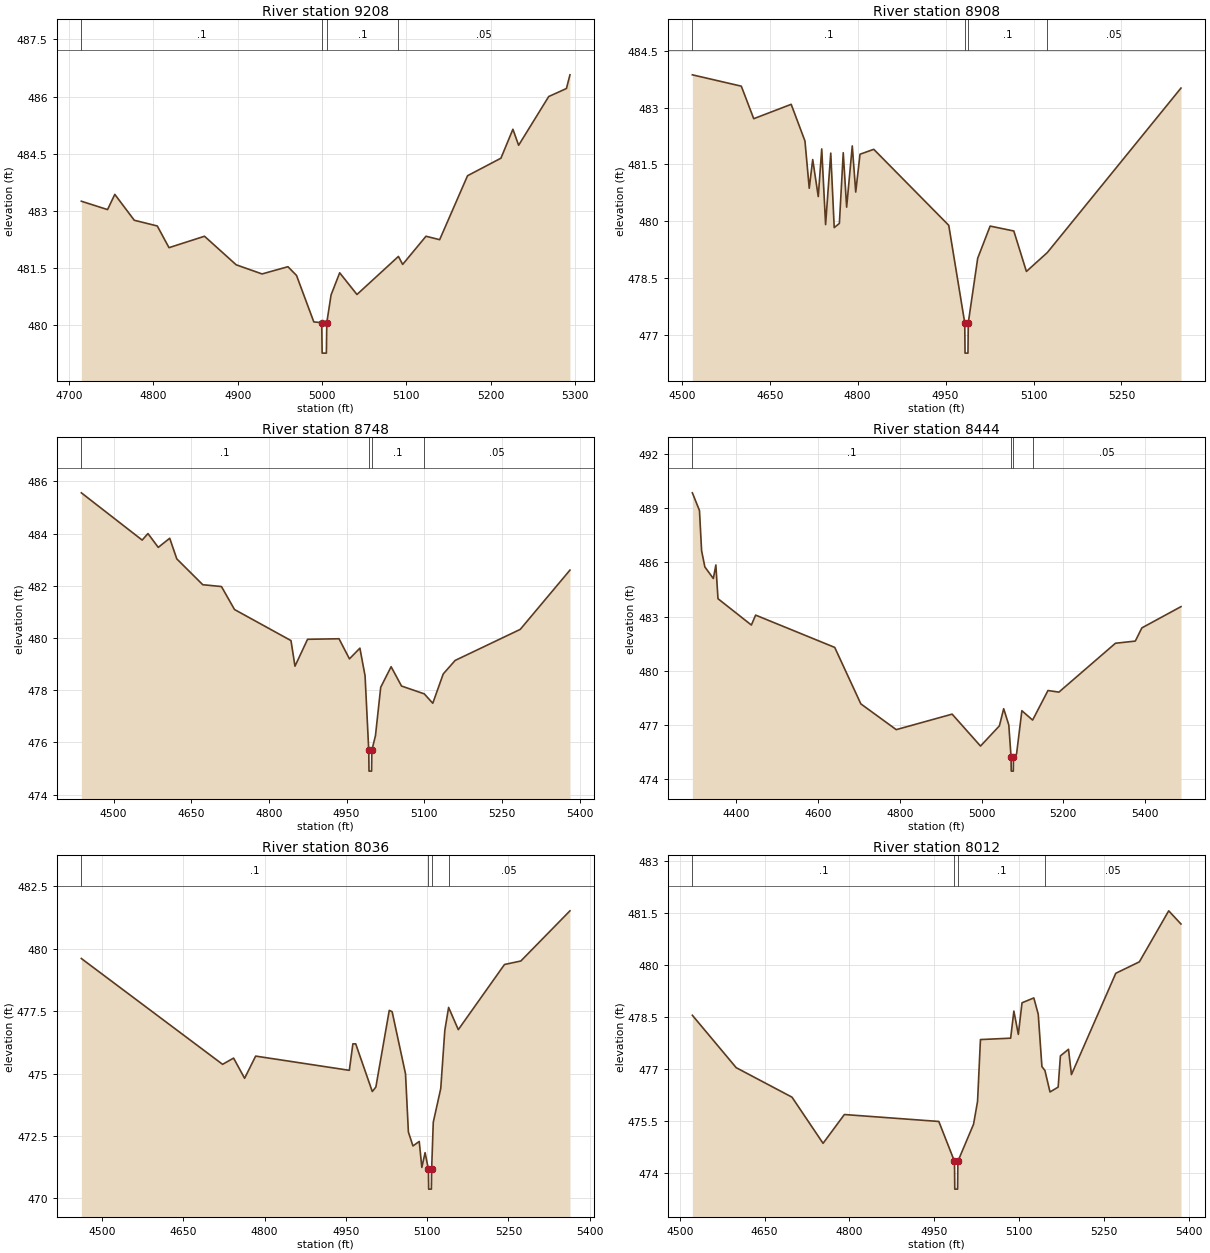
Type RM Length L Ch R = 1,9208,300,300,300
BEGIN DESCRIPTION:
Mapping XS d073fa37
END DESCRIPTION:
XS GIS Cut Line= 4
      2066584.01     13487209.51      2066531.94     13487118.40
      2066183.63     13487042.44      2066096.81     13487122.75
#Sta/Elev= 30
  4714.4  483.25  4745.5  483.03  4754.1  483.43  4777.2  482.75  4804.5  482.60
  4818.4  482.03  4860.5  482.33  4898.1  481.58  4928.8  481.34  4959.5  481.53
  4969.7  481.30  4990.2  480.08  4999.6  480.06  5000.1  479.26  5005.1  479.26
  5005.6  480.06  5010.7  480.79  5020.9  481.37  5041.4  480.80  5090.6  481.80
  5095.6  481.59  5123.3  482.33  5139.5  482.24  5172.6  483.92  5212.2  484.38
  5226.4  485.14  5233.2  484.72  5268.9  486.00  5289.9  486.21  5294.1  486.57
#Mann=4,-1,0
  4714.4     0.1       0  4999.6    0.07       0  5005.6     0.1       0
  5090.6    0.05       0
Bank Sta=4999.6,5005.6
Exp/Cntr=0.3,0.1

Type RM Length L Ch R = 1,8908,160,160,160
BEGIN DESCRIPTION:
Mapping XS c908b8ea
END DESCRIPTION:
XS GIS Cut Line= 4
      2066858.57     13487015.29      2066553.64     13486827.60
      2066261.76     13486788.54      2066101.14     13486872.10
#Sta/Elev= 30
  4518.0  483.87  4601.5  483.57  4622.7  482.71  4686.6  483.09  4710.1  482.12
  4717.4  480.87  4723.3  481.63  4732.8  480.65  4738.7  481.91  4745.3  479.91
  4754.1  481.80  4760.0  479.83  4768.8  479.94  4775.4  481.81  4781.2  480.37
  4790.8  481.99  4796.7  480.77  4804.0  481.77  4827.5  481.90  4955.4  479.89
  4982.7  477.31  4983.2  476.51  4988.2  476.51  4988.7  477.31  5004.8  479.02
  5026.0  479.87  5066.4  479.74  5087.9  478.67  5123.6  479.17  5351.6  483.52
#Mann=4,-1,0
  4518.0     0.1       0  4982.7    0.07       0  4988.7     0.1       0
  5123.6    0.05       0
Bank Sta=4982.7,4988.7
Exp/Cntr=0.3,0.1

Type RM Length L Ch R = 1,8748,304,304,304
BEGIN DESCRIPTION:
Mapping XS c4d91528
END DESCRIPTION:
XS GIS Cut Line= 4
      2066965.35     13486822.60      2066546.05     13486669.18
      2066262.84     13486638.80      2066070.79     13486729.94
#Sta/Elev= 30
  4437.6  485.56  4555.1  483.75  4566.3  484.00  4586.2  483.47  4608.3  483.82
  4622.0  483.03  4672.2  482.04  4708.3  481.97  4733.5  481.09  4842.6  479.90
  4850.3  478.92  4874.6  479.95  4935.4  479.97  4955.5  479.20  4975.7  479.61
  4985.7  478.55  4992.8  475.70  4993.3  474.90  4998.3  474.90  4998.8  475.70
  5005.8  476.26  5015.9  478.11  5036.0  478.90  5056.1  478.16  5100.0  477.86
  5116.5  477.50  5136.6  478.62  5159.7  479.14  5285.5  480.33  5381.5  482.60
#Mann=4,-1,0
  4437.6     0.1       0  4992.8    0.07       0  4998.8     0.1       0
  5100.0    0.05       0
Bank Sta=4992.8,4998.8
Exp/Cntr=0.3,0.1

Type RM Length L Ch R = 1,8444,408,408,408
BEGIN DESCRIPTION:
Mapping XS 47045240
END DESCRIPTION:
XS GIS Cut Line= 4
      2066944.55     13486385.10      2066632.02     13486301.76
      2065934.10     13486528.33      2065921.09     13486666.30
#Sta/Elev= 30
  4292.4  489.86  4309.8  488.88  4315.0  486.65  4323.0  485.75  4343.7  485.11
  4349.9  485.86  4355.1  483.99  4436.8  482.53  4447.2  483.08  4640.8  481.29
  4704.7  478.16  4791.4  476.73  4928.1  477.59  4997.6  475.82  5043.8  476.94
  5054.3  477.89  5066.8  476.99  5072.3  475.23  5072.8  474.43  5077.8  474.43
  5078.3  475.23  5085.8  475.38  5098.8  477.78  5125.1  477.26  5162.7  478.90
  5189.4  478.81  5327.8  481.52  5376.4  481.64  5392.4  482.37  5488.2  483.55
#Mann=4,-1,0
  4292.4     0.1       0  5072.3    0.07       0  5078.3     0.1       0
  5125.1    0.05       0
Bank Sta=5072.3,5078.3
Exp/Cntr=0.3,0.1

Type RM Length L Ch R = 1,8036,24,24,24
BEGIN DESCRIPTION:
Mapping XS eaff8d9d
END DESCRIPTION:
XS GIS Cut Line= 5
      2066491.36     13486064.79      2065997.00     13486154.86
      2065884.15     13486198.26      2065861.37     13486232.98
      2065777.83     13486454.31
#Sta/Elev= 30
  4462.0  479.61  4722.6  475.37  4742.9  475.62  4763.2  474.81  4783.6  475.70
  4956.4  475.13  4963.0  476.19  4968.2  476.19  4998.8  474.28  5005.4  474.46
  5030.1  477.53  5035.4  477.48  5060.1  474.99  5065.4  472.66  5073.8  472.10
  5085.4  472.28  5090.2  471.24  5096.2  471.83  5102.3  471.17  5102.8  470.37
  5107.8  470.37  5108.3  471.17  5111.3  473.05  5125.1  474.40  5132.6  476.73
  5139.6  477.65  5157.5  476.76  5242.7  479.37  5272.9  479.51  5363.5  481.52
#Mann=4,-1,0
  4462.0     0.1       0  5102.3    0.07       0  5108.3     0.1       0
  5139.6    0.05       0
Bank Sta=5102.3,5108.3
Exp/Cntr=0.3,0.1

Type RM Length L Ch R = 1,8012,38,38,38
BEGIN DESCRIPTION:
Mapping XS 220e50b3
END DESCRIPTION:
XS GIS Cut Line= 5
      2066410.67     13486051.76      2066006.77     13486140.75
      2065863.54     13486171.13      2065804.94     13486242.75
      2065745.28     13486445.62
#Sta/Elev= 30
  4522.3  478.54  4599.8  477.03  4698.5  476.18  4753.4  474.85  4791.1  475.68
  4958.1  475.48  4985.8  474.33  4986.3  473.53  4991.3  473.53  4991.8  474.33
  5019.5  475.40  5026.6  476.06  5031.7  477.84  5085.1  477.88  5090.8  478.66
  5098.7  477.99  5105.2  478.90  5126.1  479.04  5133.9  478.57  5140.4  477.06
  5145.7  476.95  5154.7  476.33  5169.1  476.47  5173.1  477.37  5187.4  477.56
  5192.6  476.83  5271.0  479.75  5312.7  480.08  5364.6  481.55  5386.3  481.17
#Mann=4,-1,0
  4522.3     0.1       0  4985.8    0.07       0  4991.8     0.1       0
  5145.7    0.05       0
Bank Sta=4985.8,4991.8
Exp/Cntr=0.3,0.1