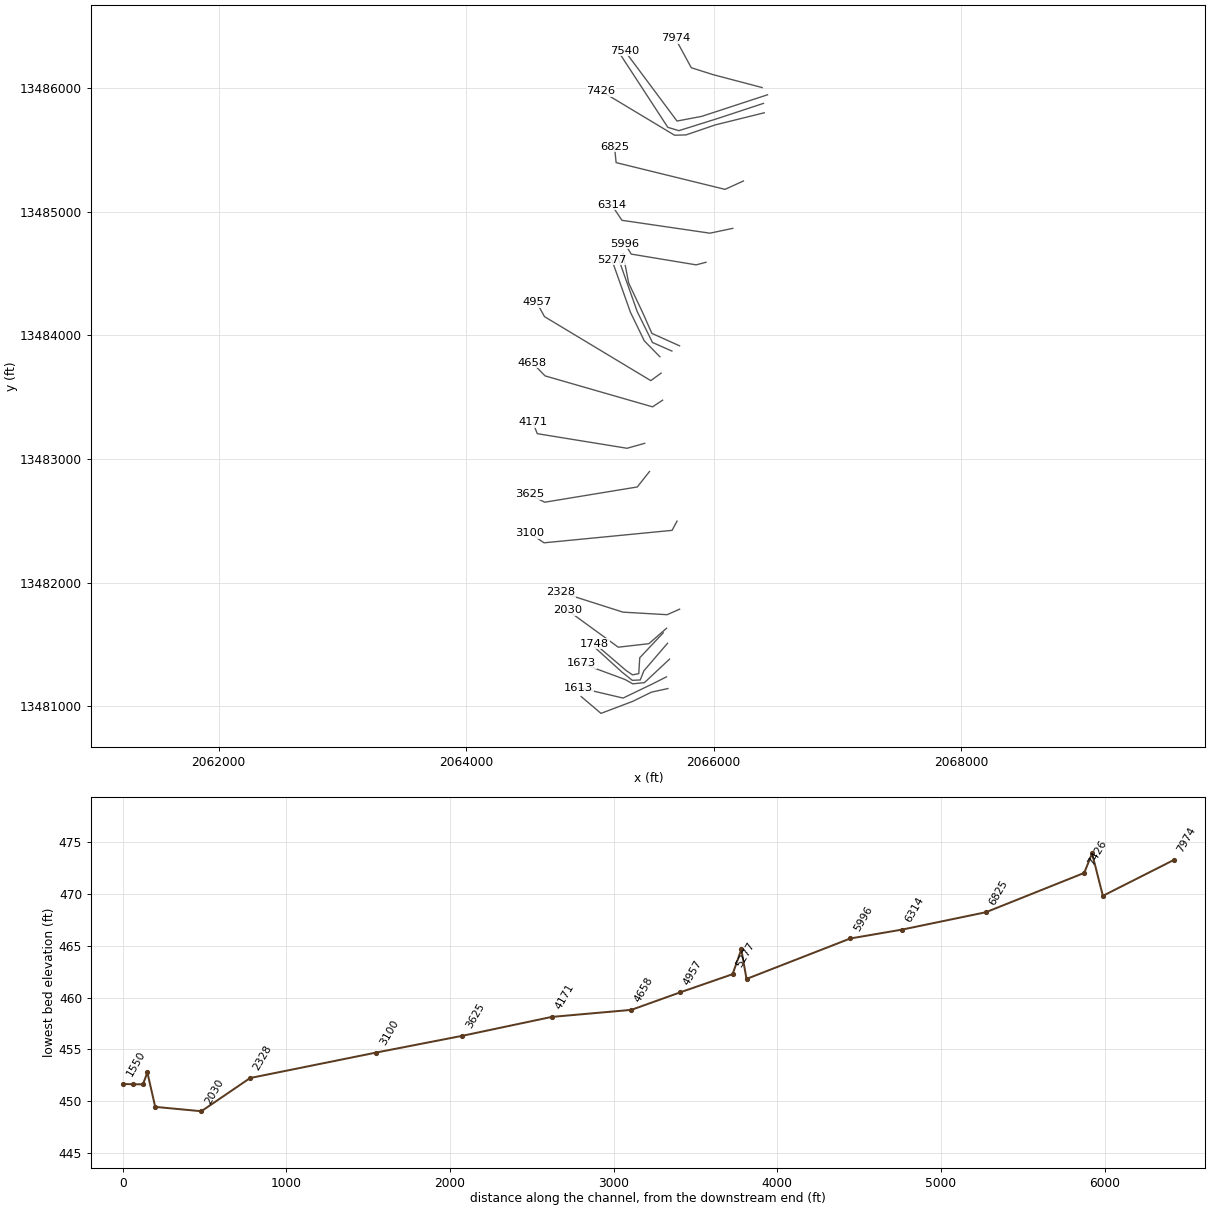
HEC-RAS study UNT 124 in Lagunillas Cr Wtrshd.prj: UNT 124 in Lagunillas Cr Wtrshd Base Level Engineering

--- UNT 124 in Lagunillas Cr Wtrshd.g01 (geometry) --- (continued)

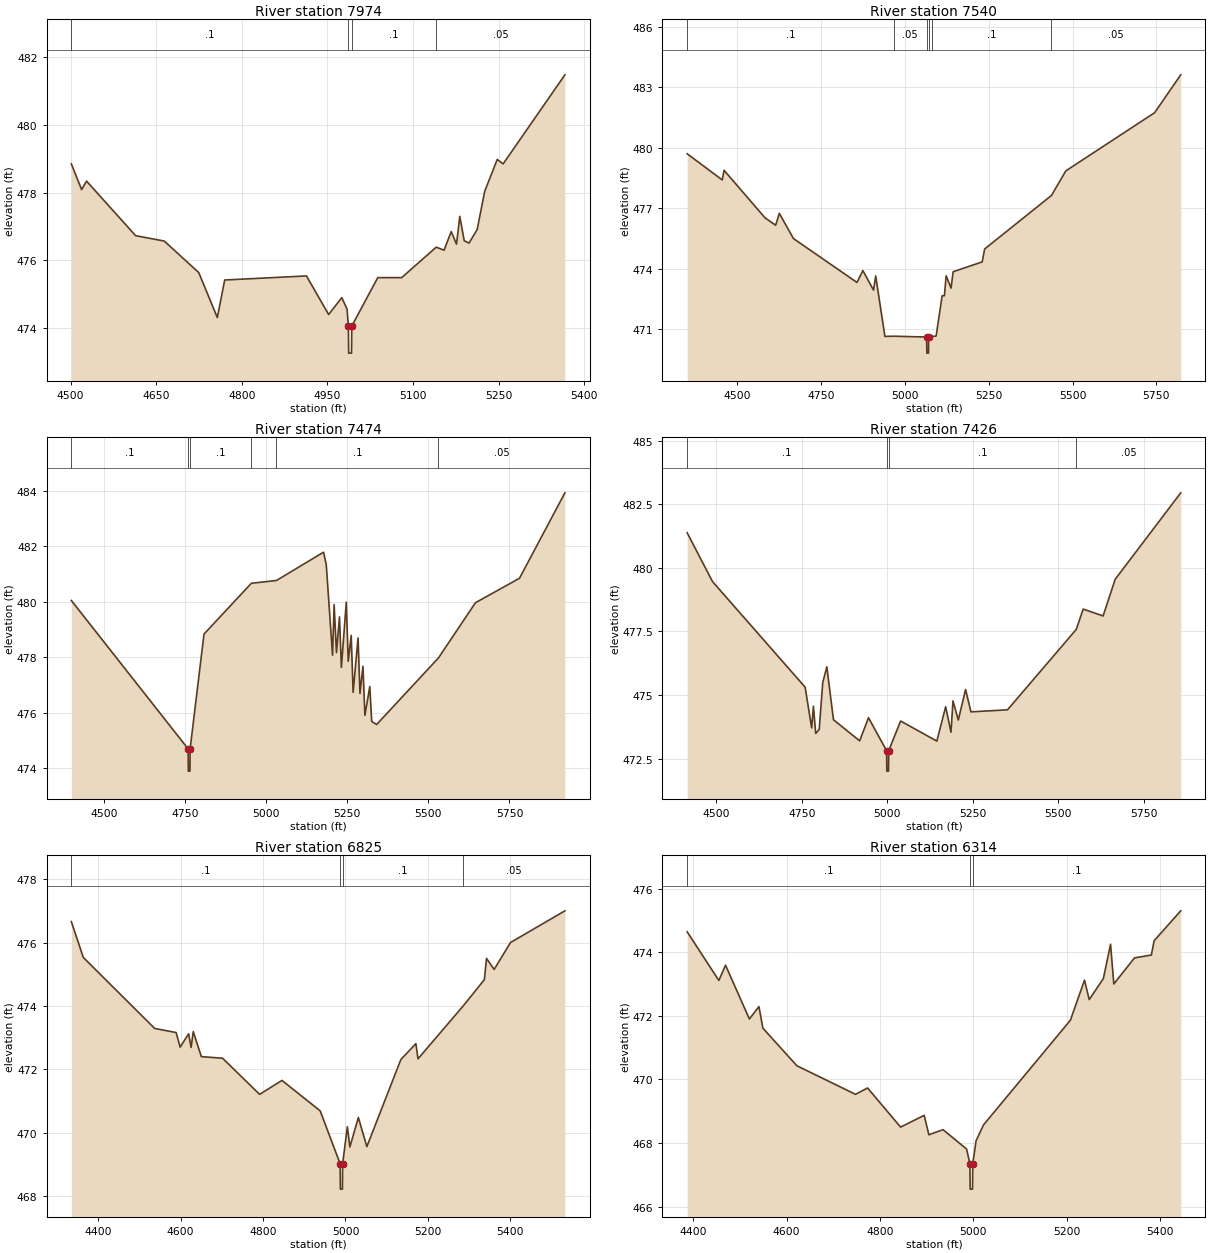
Type RM Length L Ch R = 1,7974,434,434,434
BEGIN DESCRIPTION:
Mapping XS 920f074c
END DESCRIPTION:
XS GIS Cut Line= 4
      2066392.42     13486002.29      2065998.09     13486106.03
      2065820.13     13486162.45      2065691.05     13486400.01
#Sta/Elev= 30
  4501.2  478.85  4519.2  478.09  4527.9  478.34  4613.8  476.73  4664.0  476.57
  4724.4  475.64  4757.0  474.31  4769.9  475.42  4913.2  475.54  4952.0  474.40
  4975.1  474.90  4984.3  474.56  4986.6  474.06  4987.1  473.26  4992.1  473.26
  4992.6  474.06  5038.1  475.49  5080.0  475.49  5140.6  476.39  5154.3  476.30
  5166.8  476.85  5176.1  476.48  5181.8  477.30  5189.6  476.58  5198.0  476.51
  5212.3  476.91  5225.5  478.04  5247.4  478.98  5257.8  478.85  5366.0  481.48
#Mann=4,-1,0
  4501.2     0.1       0  4986.6    0.07       0  4992.6     0.1       0
  5140.6    0.05       0
Bank Sta=4986.6,4992.6
Exp/Cntr=0.3,0.1

Type RM Length L Ch R = 1,7540,66,66,66
BEGIN DESCRIPTION:
Mapping XS 3ba2f5cb
END DESCRIPTION:
XS GIS Cut Line= 4
      2066436.04     13485943.71      2065903.99     13485769.24
      2065704.77     13485731.48      2065281.50     13486299.65
#Sta/Elev= 30
  4351.4  479.70  4456.0  478.40  4461.3  478.88  4583.4  476.52  4615.2  476.15
  4626.1  476.74  4668.2  475.49  4857.6  473.31  4875.1  473.90  4906.9  472.93
  4913.4  473.63  4940.8  470.63  4966.9  470.64  5065.2  470.60  5065.7  469.80
  5070.7  469.80  5071.2  470.60  5081.2  470.62  5093.5  470.65  5111.4  472.65
  5118.1  472.65  5123.4  473.64  5138.0  473.03  5144.2  473.84  5230.7  474.33
  5238.1  474.97  5437.3  477.63  5480.1  478.85  5744.8  481.74  5822.6  483.62
#Mann=6,-1,0
  4351.4     0.1       0  4966.9    0.05       0  5065.2   0.033       0
  5071.2    0.05       0  5081.2     0.1       0  5437.3    0.05       0
Bank Sta=5065.2,5071.2
Exp/Cntr=0.3,0.1

Type RM Length L Ch R = 1,7474,48,48,48
BEGIN DESCRIPTION:
Mapping XS 282a9410
END DESCRIPTION:
XS GIS Cut Line= 5
      2066403.53     13485874.28      2066029.86     13485751.01
      2065719.96     13485653.79      2065630.55     13485680.70
      2065242.45     13486275.78
#Sta/Elev= 30
  4398.9  480.04  4759.2  474.69  4759.7  473.89  4764.7  473.89  4765.2  474.69
  4808.0  478.83  4954.1  480.66  5031.3  480.76  5176.6  481.78  5185.0  481.34
  5204.4  478.07  5209.3  479.89  5216.6  478.16  5225.8  479.45  5231.7  477.63
  5246.8  479.98  5252.8  477.85  5262.0  478.78  5267.9  476.73  5283.1  478.69
  5289.0  476.69  5298.2  477.67  5304.2  475.90  5319.3  476.94  5325.2  475.68
  5340.4  475.57  5531.1  477.97  5645.2  479.96  5780.9  480.84  5921.0  483.92
#Mann=6,-1,0
  4398.9     0.1       0  4759.2   0.033       0  4765.2     0.1       0
  4954.1    0.05       0  5031.3     0.1       0  5531.1    0.05       0
Bank Sta=4759.2,4765.2
Exp/Cntr=0.3,0.1

Type RM Length L Ch R = 1,7426,601,601,601
BEGIN DESCRIPTION:
Mapping XS 48e15010
END DESCRIPTION:
XS GIS Cut Line= 5
      2066409.98     13485798.31      2066013.36     13485700.23
      2065777.69     13485619.50      2065685.24     13485616.89
      2065090.54     13485974.10
#Sta/Elev= 30
  4414.6  481.38  4488.8  479.46  4759.7  475.31  4778.8  473.71  4783.9  474.56
  4790.6  473.49  4800.9  473.65  4811.2  475.49  4823.2  476.11  4842.6  474.03
  4919.2  473.20  4945.1  474.11  4998.1  472.81  4998.6  472.01  5003.6  472.01
  5004.1  472.81  5039.0  473.98  5145.0  473.19  5170.8  474.54  5186.4  473.54
  5192.2  474.77  5207.8  474.02  5229.1  475.22  5244.7  474.34  5351.7  474.42
  5552.9  477.58  5573.1  478.38  5631.4  478.11  5666.7  479.55  5858.5  482.95
#Mann=4,-1,0
  4414.6     0.1       0  4998.1    0.07       0  5004.1     0.1       0
  5552.9    0.05       0
Bank Sta=4998.1,5004.1
Exp/Cntr=0.3,0.1

Type RM Length L Ch R = 1,6825,511,511,511
BEGIN DESCRIPTION:
Mapping XS 5b6d5717
END DESCRIPTION:
XS GIS Cut Line= 4
      2066241.37     13485247.06      2066092.96     13485179.37
      2065212.75     13485395.51      2065199.73     13485523.07
#Sta/Elev= 30
  4334.8  476.66  4363.8  475.53  4537.0  473.29  4589.0  473.16  4598.8  472.70
  4619.4  473.12  4625.4  472.69  4630.6  473.19  4650.3  472.40  4701.8  472.35
  4791.7  471.21  4845.9  471.65  4938.6  470.69  4987.1  469.02  4987.6  468.22
  4992.6  468.22  4993.1  469.02  5004.6  470.19  5010.7  469.55  5031.3  470.48
  5051.9  469.56  5134.5  472.31  5170.9  472.81  5176.0  472.33  5286.4  474.01
  5337.1  474.83  5342.3  475.50  5360.8  475.15  5400.5  476.00  5532.5  477.00
#Mann=4,-1,0
  4334.8     0.1       0  4987.1    0.07       0  4993.1     0.1       0
  5286.4    0.05       0
Bank Sta=4987.1,4993.1
Exp/Cntr=0.3,0.1

Type RM Length L Ch R = 1,6314,318,318,318
BEGIN DESCRIPTION:
Mapping XS 70e8ff5a
END DESCRIPTION:
XS GIS Cut Line= 4
      2066155.44     13484864.26      2065970.56     13484825.20
      2065259.63     13484929.37      2065176.30     13485054.36
#Sta/Elev= 30
  4386.8  474.64  4454.7  473.11  4469.0  473.59  4520.1  471.90  4540.6  472.29
  4549.1  471.61  4621.8  470.43  4747.5  469.53  4773.4  469.73  4844.2  468.50
  4894.7  468.87  4904.8  468.26  4935.1  468.42  4985.6  467.81  4992.7  467.35
  4993.2  466.55  4998.3  466.55  4998.8  467.35  5005.9  468.07  5021.9  468.57
  5208.0  471.86  5238.3  473.12  5248.4  472.51  5278.7  473.17  5294.1  474.25
  5301.1  473.00  5345.4  473.82  5381.5  473.91  5387.5  474.36  5444.5  475.30
#Mann=3,-1,0
  4386.8     0.1       0  4992.7    0.07       0  4998.8     0.1       0
Bank Sta=4992.7,4998.8
Exp/Cntr=0.3,0.1

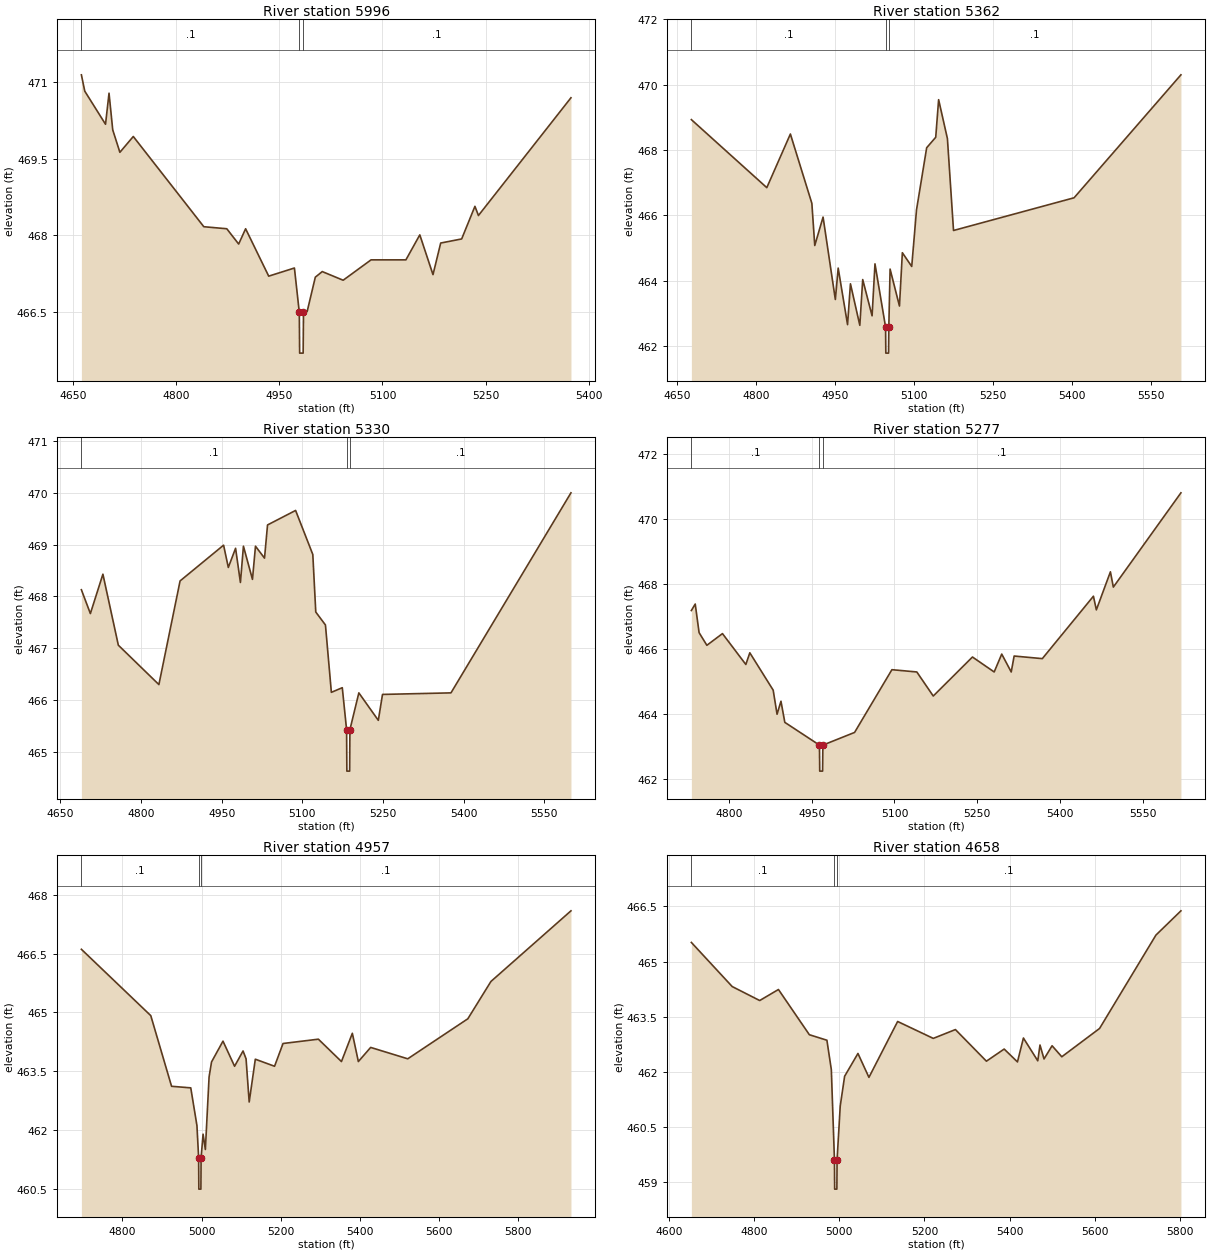
Type RM Length L Ch R = 1,5996,634,634,634
BEGIN DESCRIPTION:
Mapping XS a0f885ce
END DESCRIPTION:
XS GIS Cut Line= 4
      2065939.17     13484590.09      2065859.35     13484569.27
      2065335.04     13484656.08      2065282.96     13484739.41
#Sta/Elev= 30
  4662.0  471.15  4666.9  470.83  4697.1  470.18  4702.2  470.79  4707.6  470.07
  4718.0  469.63  4737.5  469.94  4840.1  468.17  4873.5  468.13  4890.8  467.83
  4900.9  468.13  4934.5  467.20  4971.9  467.36  4979.0  466.49  4979.5  465.69
  4984.6  465.69  4985.1  466.49  4990.5  466.51  5002.3  467.18  5012.4  467.29
  5042.8  467.12  5083.4  467.52  5134.1  467.52  5154.3  468.01  5173.5  467.23
  5184.7  467.85  5215.2  467.93  5234.5  468.57  5239.6  468.39  5374.2  470.70
#Mann=3,-1,0
  4662.0     0.1       0  4979.0    0.07       0  4985.1     0.1       0
Bank Sta=4979,4985.1
Exp/Cntr=0.3,0.1

Type RM Length L Ch R = 1,5362,32,32,32
BEGIN DESCRIPTION:
Mapping XS b9b56799
END DESCRIPTION:
XS GIS Cut Line= 5
      2065725.70     13483914.74      2065501.71     13484015.45
      2065427.06     13484183.86      2065314.21     13484421.70
      2065269.08     13484654.31
#Sta/Elev= 30
  4677.5  468.93  4820.8  466.85  4865.6  468.49  4906.4  466.37  4911.9  465.08
  4927.7  465.95  4951.0  463.43  4956.4  464.39  4974.2  462.66  4979.7  463.91
  4997.5  462.64  5003.0  464.04  5020.8  462.93  5026.3  464.52  5046.4  462.59
  5046.9  461.79  5052.1  461.79  5052.6  462.59  5055.0  464.36  5072.8  463.23
  5078.3  464.86  5096.1  464.44  5105.2  466.17  5124.5  468.07  5141.7  468.39
  5147.2  469.54  5163.9  468.35  5175.5  465.54  5404.5  466.54  5607.5  470.30
#Mann=3,-1,0
  4677.5     0.1       0  5046.4    0.07       0  5052.6     0.1       0
Bank Sta=5046.4,5052.6
Exp/Cntr=0.3,0.1

Type RM Length L Ch R = 1,5330,53,53,53
BEGIN DESCRIPTION:
Mapping XS 191375fb
END DESCRIPTION:
XS GIS Cut Line= 4
      2065663.56     13483872.53      2065506.42     13483941.98
      2065384.02     13484189.38      2065229.58     13484625.31
#Sta/Elev= 30
  4689.2  468.13  4705.9  467.67  4729.2  468.43  4757.9  467.06  4833.3  466.30
  4872.7  468.30  4953.6  468.99  4962.4  468.56  4975.9  468.93  4984.9  468.27
  4990.5  468.97  5007.3  468.33  5012.9  468.97  5029.7  468.74  5035.3  469.38
  5087.5  469.66  5119.5  468.81  5125.0  467.70  5143.0  467.45  5154.0  466.15
  5174.3  466.24  5182.3  465.43  5182.8  464.63  5188.0  464.63  5188.5  465.43
  5205.1  466.14  5241.3  465.61  5249.1  466.11  5376.4  466.14  5599.5  470.00
#Mann=3,-1,0
  4689.2     0.1       0  5182.3    0.07       0  5188.5     0.1       0
Bank Sta=5182.3,5188.5
Exp/Cntr=0.3,0.1

Type RM Length L Ch R = 1,5277,320,320,320
BEGIN DESCRIPTION:
Mapping XS c890e47f
END DESCRIPTION:
XS GIS Cut Line= 4
      2065566.32     13483826.52      2065440.45     13483955.00
      2065328.47     13484185.90      2065177.53     13484611.33
#Sta/Elev= 30
  4731.7  467.19  4738.7  467.39  4745.7  466.51  4759.8  466.12  4788.1  466.48
  4830.5  465.53  4837.7  465.89  4880.1  464.74  4887.1  464.00  4894.2  464.40
  4901.2  463.75  4964.0  463.05  4964.5  462.25  4969.7  462.25  4970.2  463.05
  5027.7  463.44  5095.4  465.37  5140.6  465.30  5170.4  464.56  5241.5  465.76
  5280.9  465.30  5294.6  465.85  5311.8  465.30  5317.1  465.79  5368.2  465.71
  5460.9  467.63  5466.2  467.21  5491.7  468.38  5497.0  467.91  5619.6  470.81
#Mann=3,-1,0
  4731.7     0.1       0  4964.0    0.07       0  4970.2     0.1       0
Bank Sta=4964,4970.2
Exp/Cntr=0.3,0.1

Type RM Length L Ch R = 1,4957,299,299,299
BEGIN DESCRIPTION:
Mapping XS 2beb65d9
END DESCRIPTION:
XS GIS Cut Line= 4
      2065576.39     13483694.29      2065493.03     13483633.51
      2064633.65     13484150.87      2064571.14     13484265.47
#Sta/Elev= 30
  4696.2  466.61  4871.5  464.92  4924.0  463.12  4972.5  463.08  4988.1  462.12
  4992.4  461.30  4992.9  460.50  4998.1  460.50  4998.6  461.30  5003.6  461.90
  5009.4  461.51  5018.8  463.36  5025.0  463.74  5053.9  464.27  5083.2  463.63
  5104.6  464.02  5112.2  463.82  5120.1  462.72  5135.6  463.81  5184.2  463.63
  5205.6  464.21  5294.9  464.32  5353.2  463.75  5380.7  464.47  5395.9  463.75
  5427.0  464.11  5520.7  463.82  5672.5  464.84  5730.8  465.79  5933.0  467.59
#Mann=3,-1,0
  4696.2     0.1       0  4992.4    0.07       0  4998.6     0.1       0
Bank Sta=4992.4,4998.6
Exp/Cntr=0.3,0.1

Type RM Length L Ch R = 1,4658,487,487,487
BEGIN DESCRIPTION:
Mapping XS e27317f2
END DESCRIPTION:
XS GIS Cut Line= 4
      2065588.54     13483475.54      2065506.92     13483421.70
      2064638.86     13483671.70      2064534.67     13483777.63
#Sta/Elev= 30
  4652.6  465.52  4748.5  464.32  4813.1  463.94  4857.1  464.24  4929.7  463.01
  4970.9  462.86  4981.3  462.06  4988.6  459.61  4989.1  458.81  4994.3  458.81
  4994.8  459.61  5002.2  461.07  5012.5  461.88  5043.8  462.50  5069.6  461.85
  5137.0  463.37  5220.7  462.91  5272.7  463.15  5345.5  462.29  5387.2  462.62
  5418.4  462.27  5432.4  462.92  5466.1  462.30  5471.3  462.73  5480.8  462.35
  5499.7  462.71  5522.5  462.41  5611.2  463.18  5743.6  465.72  5802.3  466.38
#Mann=3,-1,0
  4652.6     0.1       0  4988.6    0.07       0  4994.8     0.1       0
Bank Sta=4988.6,4994.8
Exp/Cntr=0.3,0.1

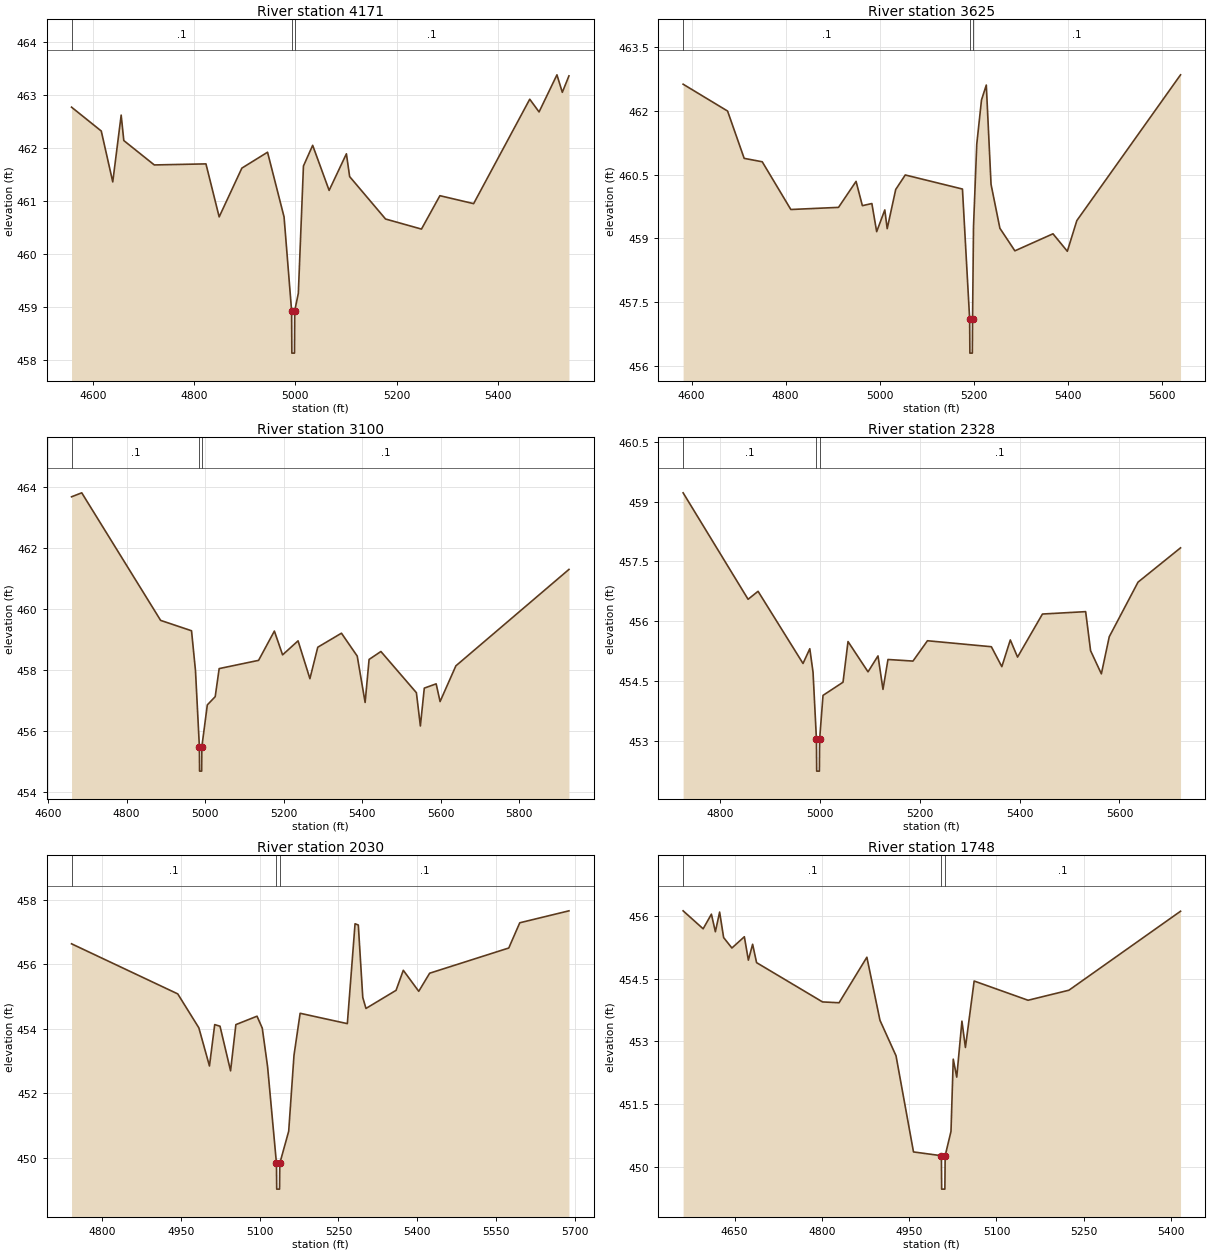
Type RM Length L Ch R = 1,4171,546,546,546
BEGIN DESCRIPTION:
Mapping XS 5be3f4f4
END DESCRIPTION:
XS GIS Cut Line= 4
      2065443.39     13483126.73      2065301.05     13483086.81
      2064575.36     13483204.87      2064539.46     13483297.17
#Sta/Elev= 30
  4558.1  462.77  4616.8  462.32  4639.5  461.36  4656.1  462.62  4661.3  462.14
  4721.5  461.68  4823.5  461.70  4849.6  460.70  4894.4  461.62  4945.1  461.92
  4977.7  460.70  4992.6  458.93  4993.1  458.13  4998.3  458.13  4998.8  458.93
  5005.9  459.26  5016.0  461.66  5034.2  462.05  5066.7  461.20  5100.8  461.89
  5107.2  461.46  5178.1  460.66  5249.0  460.47  5285.4  461.10  5352.0  460.95
  5462.8  462.92  5481.2  462.68  5516.5  463.38  5527.1  463.05  5540.2  463.36
#Mann=3,-1,0
  4558.1     0.1       0  4992.6    0.07       0  4998.8     0.1       0
Bank Sta=4992.6,4998.8
Exp/Cntr=0.3,0.1

Type RM Length L Ch R = 1,3625,525,525,525
BEGIN DESCRIPTION:
Mapping XS 00b90a66
END DESCRIPTION:
XS GIS Cut Line= 4
      2065482.63     13482899.15      2065383.65     13482774.13
      2064635.39     13482650.87      2064510.35     13482713.39
#Sta/Elev= 30
  4582.0  462.62  4676.5  461.99  4711.8  460.88  4750.2  460.80  4811.0  459.68
  4912.4  459.73  4949.7  460.34  4963.1  459.77  4983.3  459.82  4993.5  459.16
  5010.8  459.67  5015.9  459.23  5034.0  460.15  5054.3  460.49  5175.9  460.16
  5191.2  457.11  5191.7  456.31  5196.9  456.31  5197.4  457.11  5199.4  459.28
  5206.3  461.21  5216.4  462.25  5226.6  462.60  5236.7  460.27  5255.5  459.24
  5287.4  458.71  5368.4  459.11  5398.9  458.70  5419.1  459.42  5639.6  462.84
#Mann=3,-1,0
  4582.0     0.1       0  5191.2    0.07       0  5197.4     0.1       0
Bank Sta=5191.2,5197.4
Exp/Cntr=0.3,0.1

Type RM Length L Ch R = 1,3100,772,772,772
BEGIN DESCRIPTION:
Mapping XS 3200b3d1
END DESCRIPTION:
XS GIS Cut Line= 4
      2065704.85     13482498.12      2065664.90     13482423.44
      2064630.18     13482322.74      2064512.15     13482402.59
#Sta/Elev= 30
  4660.0  463.69  4686.0  463.82  4886.9  459.64  4965.6  459.30  4975.7  457.99
  4985.6  455.50  4986.1  454.70  4991.4  454.70  4991.9  455.50  5005.8  456.87
  5025.9  457.14  5036.0  458.06  5136.4  458.33  5176.6  459.29  5197.5  458.51
  5236.9  458.97  5267.1  457.73  5287.1  458.76  5347.4  459.22  5387.6  458.47
  5407.7  456.95  5417.8  458.36  5447.9  458.62  5538.3  457.27  5548.4  456.18
  5558.4  457.42  5588.6  457.56  5598.6  456.98  5638.8  458.15  5926.8  461.31
#Mann=3,-1,0
  4660.0     0.1       0  4985.6    0.07       0  4991.9     0.1       0
Bank Sta=4985.6,4991.9
Exp/Cntr=0.3,0.1

Type RM Length L Ch R = 1,2328,298,298,298
BEGIN DESCRIPTION:
Mapping XS 91d1cd14
END DESCRIPTION:
XS GIS Cut Line= 4
      2065725.75     13481786.30      2065624.82     13481741.81
      2065267.83     13481762.42      2064763.82     13481923.45
#Sta/Elev= 30
  4725.4  459.22  4855.6  456.55  4875.6  456.75  4965.7  454.94  4979.3  455.31
  4985.8  454.72  4992.6  453.04  4993.1  452.24  4998.5  452.24  4999.0  453.04
  5005.8  454.14  5045.9  454.47  5055.9  455.49  5096.0  454.73  5116.0  455.13
  5126.0  454.29  5136.0  455.04  5186.1  455.00  5215.1  455.51  5343.2  455.36
  5364.2  454.86  5381.2  455.53  5395.7  455.10  5445.6  456.18  5532.2  456.24
  5542.1  455.26  5563.7  454.68  5579.5  455.61  5637.2  456.98  5722.4  457.84
#Mann=3,-1,0
  4725.4     0.1       0  4992.6    0.07       0  4999.0     0.1       0
Bank Sta=4992.6,4999
Exp/Cntr=0.3,0.1

Type RM Length L Ch R = 1,2030,282,282,282
BEGIN DESCRIPTION:
Mapping XS 82823d69
END DESCRIPTION:
XS GIS Cut Line= 4
      2065620.47     13481632.21      2065477.25     13481507.43
      2065229.86     13481479.22      2064818.83     13481778.51
#Sta/Elev= 30
  4741.6  456.63  4943.9  455.08  4984.1  454.03  5004.3  452.85  5014.3  454.13
  5024.4  454.08  5044.5  452.70  5054.6  454.13  5094.9  454.39  5104.9  454.02
  5115.0  452.83  5131.9  449.84  5132.4  449.04  5137.8  449.04  5138.3  449.84
  5155.2  450.83  5165.3  453.18  5177.0  454.48  5266.9  454.16  5281.6  457.25
  5287.8  457.21  5296.3  454.97  5302.4  454.63  5359.7  455.19  5373.5  455.81
  5402.9  455.16  5423.7  455.72  5574.4  456.50  5595.3  457.28  5689.0  457.65
#Mann=3,-1,0
  4741.6     0.1       0  5131.9    0.07       0  5138.3     0.1       0
Bank Sta=5131.9,5138.3
Exp/Cntr=0.3,0.1

Type RM Length L Ch R = 1,1748,48,48,48
BEGIN DESCRIPTION:
Mapping XS 639e4706
END DESCRIPTION:
XS GIS Cut Line= 6
      2065593.35     13481595.31      2065403.47     13481393.50
      2065395.87     13481265.46      2065344.87     13481255.70
      2065293.88     13481290.42      2065038.90     13481508.66
#Sta/Elev= 30
  4561.7  456.12  4596.1  455.69  4610.3  456.04  4617.1  455.62  4624.4  456.09
  4631.3  455.48  4645.5  455.23  4666.9  455.50  4673.8  454.94  4681.1  455.32
  4687.9  454.88  4801.2  453.94  4829.6  453.92  4877.4  455.01  4899.9  453.50
  4927.5  452.65  4957.5  450.35  5005.4  450.26  5005.9  449.46  5011.4  449.46
  5011.9  450.26  5021.9  450.84  5025.8  452.57  5031.8  452.14  5040.7  453.48
  5046.7  452.85  5061.7  454.44  5154.3  453.98  5224.5  454.22  5416.3  456.11
#Mann=3,-1,0
  4561.7     0.1       0  5005.4    0.07       0  5011.9     0.1       0
Bank Sta=5005.4,5011.9
Exp/Cntr=0.3,0.1

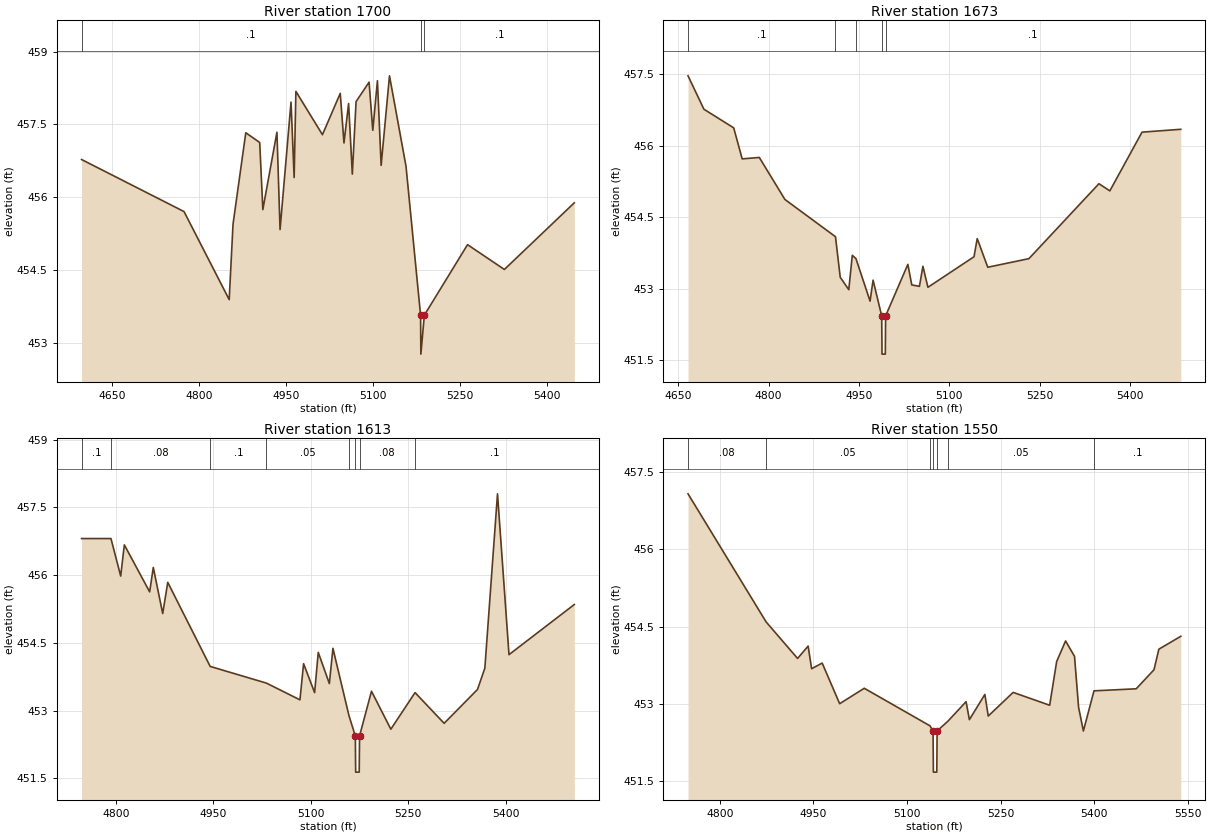
Type RM Length L Ch R = 1,1700,27,27,27
BEGIN DESCRIPTION:
Mapping XS 246d9621
END DESCRIPTION:
XS GIS Cut Line= 6
      2065628.06     13481510.66      2065437.10     13481288.25
      2065407.81     13481214.46      2065343.79     13481211.21
      2065259.15     13481278.48      2065033.46     13481483.56
#Sta/Elev= 30
  4597.6  456.78  4774.3  455.71  4852.2  453.90  4858.8  455.45  4880.8  457.33
  4904.8  457.13  4910.2  455.75  4934.5  457.34  4939.9  455.34  4958.8  457.96
  4964.2  456.41  4967.2  458.18  5013.0  457.29  5043.7  458.14  5050.1  457.12
  5058.1  457.93  5064.5  456.48  5071.0  457.97  5093.4  458.37  5099.8  457.38
  5107.8  458.40  5114.2  456.66  5128.6  458.50  5157.1  456.64  5182.2  453.58
  5182.7  452.78  5188.7  453.58  5263.2  455.03  5326.7  454.52  5447.3  455.89
#Mann=3,-1,0
  4597.6     0.1       0  5182.2    0.07       0  5188.7     0.1       0
Bank Sta=5182.2,5188.7
Exp/Cntr=0.3,0.1

Type RM Length L Ch R = 1,1673,60,60,60
BEGIN DESCRIPTION:
Mapping XS 52654dfc
END DESCRIPTION:
XS GIS Cut Line= 5
      2065644.37     13481382.66      2065441.45     13481192.76
      2065347.04     13481183.00      2065283.03     13481218.80
      2064934.67     13481347.94
#Sta/Elev= 30
  4666.4  457.46  4692.8  456.76  4742.2  456.37  4756.3  455.72  4784.7  455.75
  4827.2  454.87  4911.1  454.09  4919.0  453.24  4933.2  452.98  4939.0  453.70
  4945.1  453.63  4968.5  452.74  4973.5  453.18  4987.8  452.43  4988.3  451.63
  4993.8  451.63  4994.3  452.43  5031.2  453.51  5037.7  453.08  5050.4  453.05
  5056.2  453.47  5064.5  453.03  5141.0  453.67  5146.3  454.05  5163.8  453.45
  5232.1  453.63  5348.3  455.20  5366.4  455.05  5419.8  456.28  5484.1  456.34
#Mann=5,-1,0
  4666.4     0.1       0  4911.1    0.08       0  4945.1     0.1       0
  4987.8    0.07       0  4994.3     0.1       0
Bank Sta=4987.8,4994.3
Exp/Cntr=0.3,0.1

Type RM Length L Ch R = 1,1613,63,63,63
BEGIN DESCRIPTION:
Mapping XS 7b6cfa9a
END DESCRIPTION:
XS GIS Cut Line= 4
      2065619.36     13481239.40      2065505.46     13481181.91
      2065268.92     13481067.98      2064909.88     13481152.56
#Sta/Elev= 30
  4746.8  456.81  4792.1  456.81  4807.1  455.98  4812.7  456.67  4851.7  455.63
  4857.3  456.17  4871.8  455.15  4879.6  455.84  4944.9  453.98  5031.6  453.61
  5083.2  453.24  5088.8  454.04  5105.8  453.40  5111.4  454.29  5128.5  453.60
  5134.0  454.38  5158.7  452.89  5168.5  452.44  5169.0  451.64  5174.5  451.64
  5175.0  452.44  5193.4  453.43  5223.2  452.59  5260.5  453.40  5305.3  452.72
  5356.7  453.47  5368.0  453.94  5387.5  457.80  5405.2  454.24  5505.8  455.35
#Mann=8,-1,0
  4746.8     0.1       0  4792.1    0.08       0  4944.9     0.1       0
  5031.6    0.05       0  5158.7    0.08       0  5168.5    0.07       0
  5175.0    0.08       0  5260.5     0.1       0
Bank Sta=5168.5,5175
Exp/Cntr=0.3,0.1

Type RM Length L Ch R = 1,1550,484,484,484
BEGIN DESCRIPTION:
Mapping XS dc22997b
END DESCRIPTION:
XS GIS Cut Line= 5
      2065631.34     13481145.02      2065497.87     13481115.72
      2065347.19     13481041.49      2065090.25     13480944.27
      2064930.23     13481080.21
#Sta/Elev= 30
  4749.1  457.08  4874.2  454.59  4924.6  453.88  4941.5  454.12  4947.1  453.68
  4964.0  453.79  4992.0  453.00  5031.4  453.30  5136.7  452.57  5141.6  452.47
  5142.1  451.67  5147.6  451.67  5148.1  452.47  5165.4  452.66  5194.5  453.04
  5199.8  452.69  5224.6  453.18  5230.0  452.76  5269.9  453.22  5328.4  452.97
  5339.6  453.82  5353.9  454.22  5368.2  453.92  5374.7  452.93  5382.4  452.47
  5399.4  453.25  5467.0  453.29  5495.5  453.66  5503.3  454.06  5538.4  454.31
#Mann=7,-1,0
  4749.1    0.08       0  4874.2    0.05       0  5136.7     0.1       0
  5141.6    0.04       0  5148.1     0.1       0  5165.4    0.05       0
  5399.4     0.1       0
Bank Sta=5141.6,5148.1
Exp/Cntr=0.3,0.1