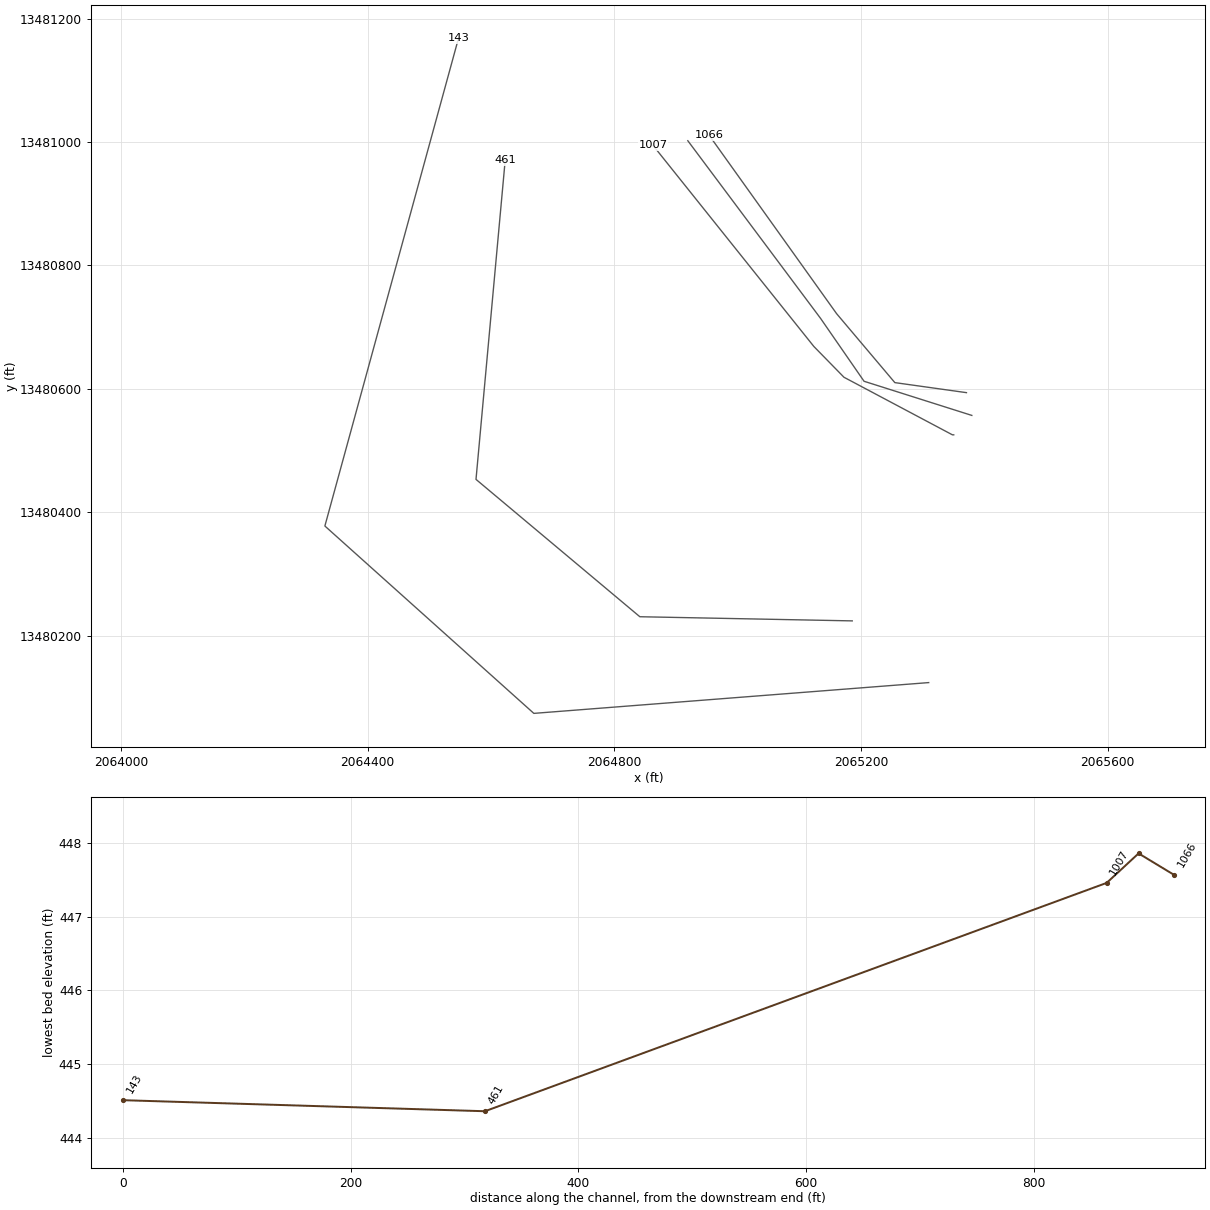
HEC-RAS study UNT 124 in Lagunillas Cr Wtrshd.prj: UNT 124 in Lagunillas Cr Wtrshd Base Level Engineering

--- UNT 124 in Lagunillas Cr Wtrshd.g01 (geometry) --- (continued)

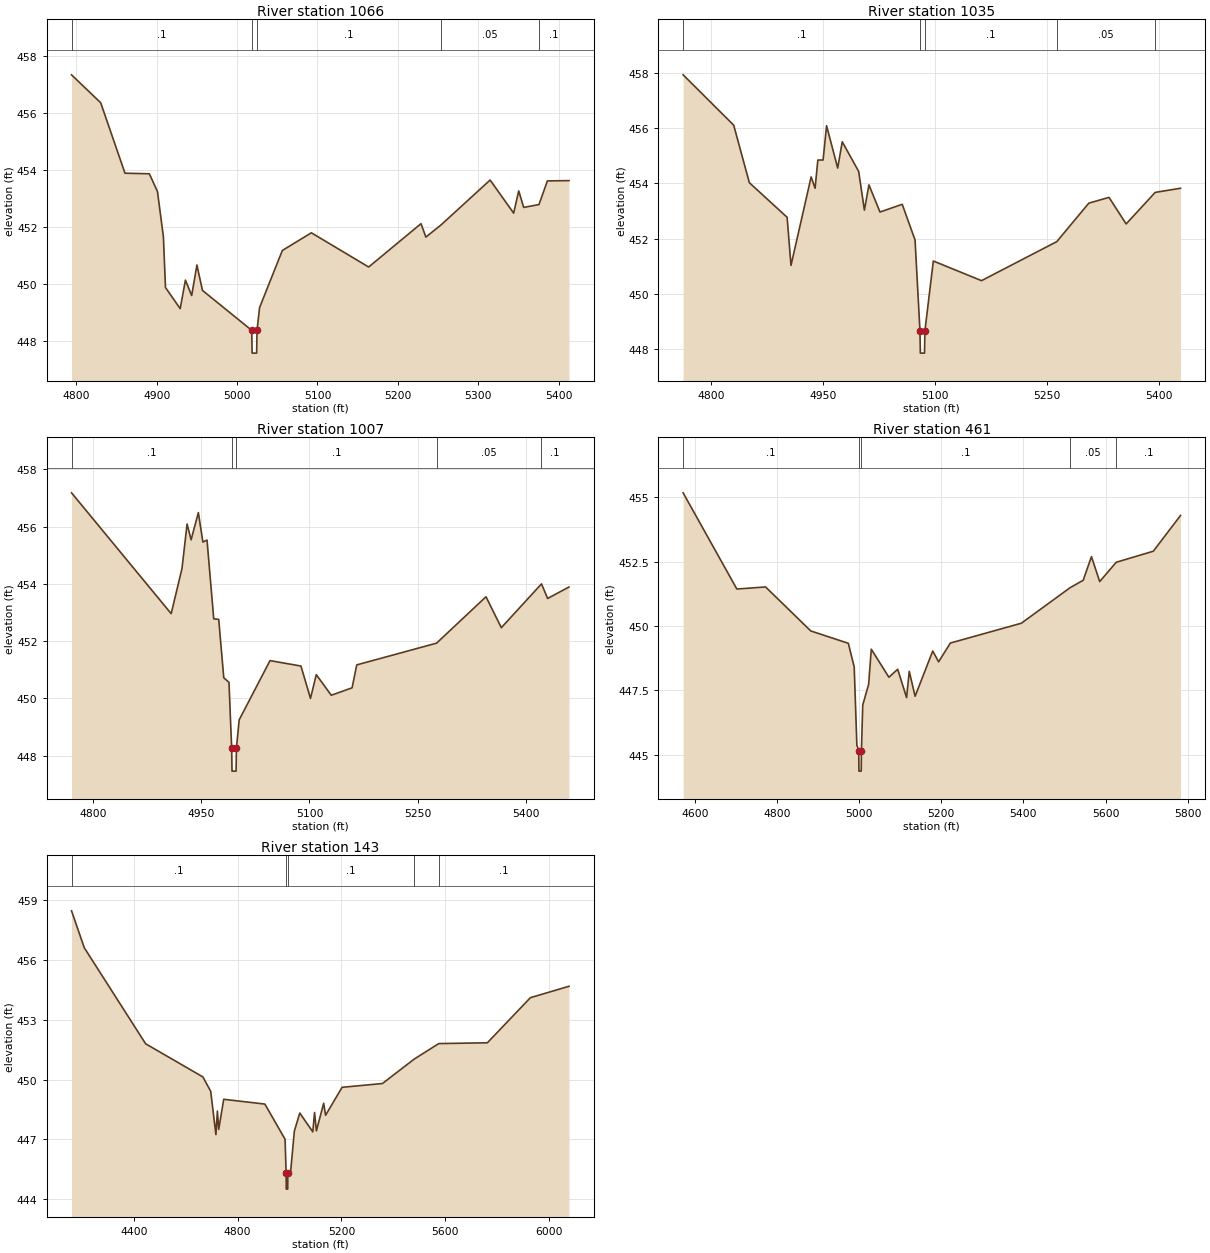
Type RM Length L Ch R = 1,1066,31,31,31
BEGIN DESCRIPTION:
Mapping XS 4bd88cf0
END DESCRIPTION:
XS GIS Cut Line= 4
      2065370.90     13480593.81      2065254.81     13480610.08
      2065160.41     13480721.84      2064953.80     13481010.99
#Sta/Elev= 30
  4794.0  457.33  4830.3  456.35  4860.5  453.88  4890.8  453.86  4900.9  453.24
  4908.3  451.65  4910.9  449.87  4929.2  449.13  4935.7  450.13  4943.5  449.59
  4950.0  450.66  4956.9  449.77  5018.2  448.37  5018.7  447.57  5024.3  447.57
  5024.8  448.37  5028.0  449.17  5056.3  451.17  5092.4  451.79  5163.7  450.59
  5228.8  452.11  5234.9  451.64  5253.5  452.06  5314.8  453.64  5344.1  452.48
  5350.4  453.26  5356.6  452.68  5375.6  452.78  5386.1  453.61  5412.9  453.62
#Mann=5,-1,0
  4794.0     0.1       0  5018.2    0.07       0  5024.8     0.1       0
  5253.5    0.05       0  5375.6     0.1       0
Bank Sta=5018.2,5024.8
Exp/Cntr=0.3,0.1

Type RM Length L Ch R = 1,1035,28,28,28
BEGIN DESCRIPTION:
Mapping XS 6b48a2d1
END DESCRIPTION:
XS GIS Cut Line= 4
      2065379.63     13480556.90      2065204.90     13480612.25
      2065134.37     13480714.25      2064919.18     13481002.23
#Sta/Elev= 30
  4762.7  457.92  4830.5  456.10  4851.5  454.02  4902.1  452.77  4907.3  451.03
  4934.3  454.23  4939.6  453.82  4943.3  454.84  4950.3  454.84  4955.0  456.08
  4969.9  454.55  4976.0  455.50  4998.0  454.43  5005.7  453.03  5011.8  453.94
  5026.6  452.96  5056.4  453.24  5073.6  451.95  5080.2  448.66  5080.7  447.86
  5086.3  447.86  5086.8  448.66  5098.1  451.19  5162.7  450.48  5263.6  451.89
  5306.5  453.28  5333.6  453.49  5356.6  452.53  5395.5  453.67  5429.5  453.82
#Mann=5,-1,0
  4762.7     0.1       0  5080.2    0.07       0  5086.8     0.1       0
  5263.6    0.05       0  5395.5     0.1       0
Bank Sta=5080.2,5086.8
Exp/Cntr=0.3,0.1

Type RM Length L Ch R = 1,1007,546,546,546
BEGIN DESCRIPTION:
Mapping XS 3867a39f
END DESCRIPTION:
XS GIS Cut Line= 5
      2065350.29     13480525.44      2065348.13     13480525.44
      2065172.35     13480618.76      2065123.52     13480668.67
      2064862.80     13480994.64
#Sta/Elev= 30
  4770.7  457.18  4908.6  452.96  4923.6  454.54  4930.6  456.09  4936.2  455.54
  4946.2  456.49  4952.5  455.46  4958.2  455.53  4967.5  452.78  4974.4  452.76
  4981.4  450.72  4988.6  450.56  4992.3  448.26  4992.8  447.46  4998.4  447.46
  4998.9  448.26  5002.7  449.25  5045.4  451.32  5088.2  451.13  5101.4  450.00
  5109.4  450.83  5130.2  450.11  5159.0  450.37  5165.4  451.17  5275.9  451.93
  5344.3  453.55  5365.5  452.47  5421.1  454.00  5429.6  453.49  5459.1  453.89
#Mann=5,-1,0
  4770.7     0.1       0  4992.3    0.07       0  4998.9     0.1       0
  5275.9    0.05       0  5421.1     0.1       0
Bank Sta=4992.3,4998.9
Exp/Cntr=0.3,0.1

Type RM Length L Ch R = 1,461,318,318,318
BEGIN DESCRIPTION:
Mapping XS 5b7f1cd4
END DESCRIPTION:
XS GIS Cut Line= 4
      2065185.75     13480223.79      2064841.40     13480230.52
      2064575.78     13480453.18      2064623.14     13480971.00
#Sta/Elev= 30
  4571.5  455.18  4702.3  451.44  4772.3  451.52  4882.3  449.81  4973.7  449.33
  4988.0  448.41  4994.5  445.37  4999.0  445.16  4999.5  444.36  5005.1  444.36
  5005.6  445.16  5008.8  446.93  5023.1  447.73  5029.6  449.10  5072.5  448.01
  5093.9  448.32  5115.5  447.22  5122.0  448.24  5136.3  447.27  5179.2  449.03
  5193.5  448.61  5222.1  449.34  5394.9  450.11  5513.5  451.49  5545.5  451.78
  5565.6  452.70  5585.7  451.73  5625.9  452.48  5716.2  452.91  5782.5  454.30
#Mann=5,-1,0
  4571.5     0.1       0  4999.0    0.07       0  5005.6     0.1       0
  5513.5    0.05       0  5625.9     0.1       0
Bank Sta=4999,5005.6
Exp/Cntr=0.3,0.1

Type RM Length L Ch R = 1,143,0,0,0
BEGIN DESCRIPTION:
UNT 124 in Lagunillas Cr Wtrshd 1.0
END DESCRIPTION:
XS GIS Cut Line= 4
      2065309.71     13480123.75      2064669.53     13480073.84
      2064330.77     13480377.59      2064547.38     13481168.23
#Sta/Elev= 30
  4160.0  458.45  4209.1  456.60  4445.6  451.79  4666.2  450.13  4696.3  449.41
  4716.4  447.24  4722.1  448.42  4727.1  447.50  4746.5  449.01  4905.1  448.77
  4982.8  447.01  4987.0  445.31  4987.5  444.51  4993.1  444.51  4993.6  445.31
  5004.5  445.41  5018.7  447.42  5039.6  448.32  5089.8  447.38  5096.5  448.35
  5103.7  447.43  5131.6  448.81  5139.1  448.21  5202.6  449.61  5358.1  449.80
  5480.2  451.02  5575.2  451.80  5762.5  451.84  5928.4  454.10  6076.9  454.67
#Mann=5,-1,0
  4160.0     0.1       0  4987.0    0.07       0  4993.6     0.1       0
  5480.2    0.05       0  5575.2     0.1       0
Bank Sta=4987,4993.6
Exp/Cntr=0.3,0.1

Chan Stop Cuts=-1