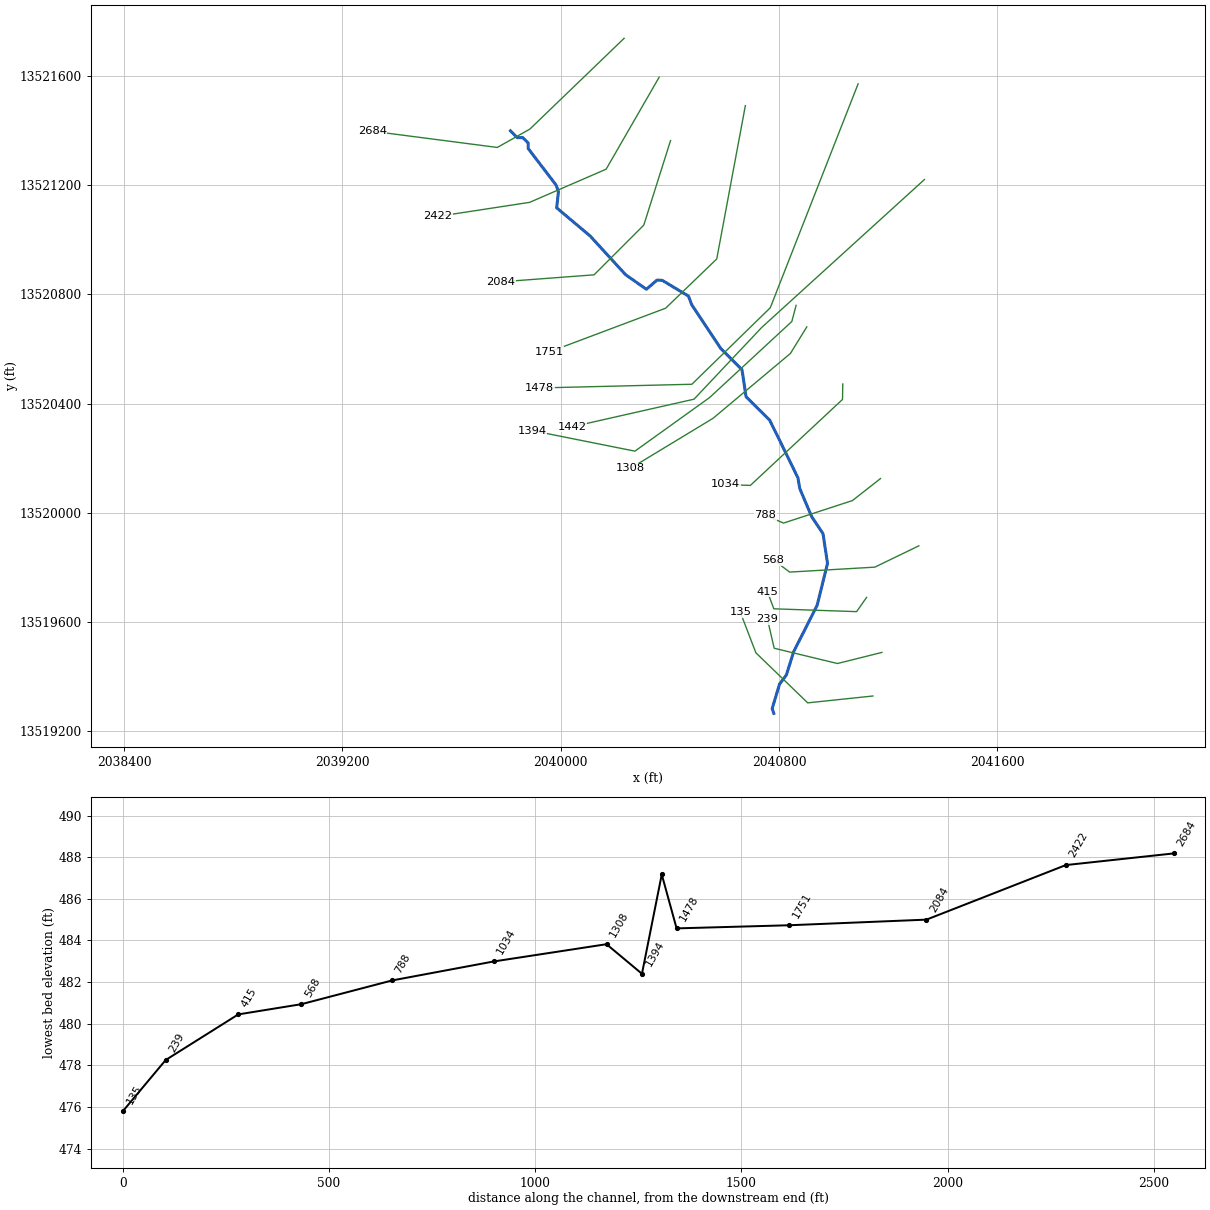
--- UNT 126 in Lagunillas Cr Wtrshd.prj (project) ---

Proj Title=UNT 126 in Lagunillas Cr Wtrshd Base Level Engineering
Current Plan=p01
Default Exp/Contr=0.3,0.1
English Units
Geom File=g01
Flow File=f01
Plan File=p01
BEGIN DESCRIPTION:
UNT 126 in Lagunillas Cr Wtrshd
END DESCRIPTION:

--- UNT 126 in Lagunillas Cr Wtrshd.p01 (plan) ---

Plan Title=Multiple Run
Short Identifier=Multiple
Geom File=g01
Flow File=f01
Subcritical Flow
K Sum by GR= 0
Std Step Tol= 0.01
Critical Tol= 0.01
Num of Std Step Trials= 20
Max Error Tol= 0.3
Flow Tol Ratio= 0.001
Split Flow NTrial= 30
Split Flow Tol= 0.02
Split Flow Ratio= 0.02
Log Output Level= 0
Friction Slope Method= 1
Unsteady Friction Slope Method= 2
Unsteady Bridges Friction Slope Method= 1
Parabolic Critical Depth
Global Vel Dist=  1 , 1 , 1
Global Log Level= 0
CheckData=True
Encroach Param= -1, 0, 0, 0
BEGIN DESCRIPTION:
Multiple Run
END DESCRIPTION:

--- UNT 126 in Lagunillas Cr Wtrshd.f01 (steady flow) ---

Flow Title=Multiple
Number of Profiles=7
Profile Names=10-year,25-year,50-year,1pct_min,100-year,1pct_plu,500-year
River Rch & RM= UNT 126 in Lagun,Reach-1,2684
     104     135     159      94     187     373     262
River Rch & RM= UNT 126 in Lagun,Reach-1,1478
     113     148     175     103     206     411     291
Boundary for River Rch & Prof#=UNT 126 in Lagun,Reach-1,1
Up Type=0
Dn Type=3
Dn Slope=0.005
Boundary for River Rch & Prof#=UNT 126 in Lagun,Reach-1,2
Up Type=0
Dn Type=3
Dn Slope=0.005
Boundary for River Rch & Prof#=UNT 126 in Lagun,Reach-1,3
Up Type=0
Dn Type=3
Dn Slope=0.005
Boundary for River Rch & Prof#=UNT 126 in Lagun,Reach-1,4
Up Type=0
Dn Type=3
Dn Slope=0.005
Boundary for River Rch & Prof#=UNT 126 in Lagun,Reach-1,5
Up Type=0
Dn Type=3
Dn Slope=0.005
Boundary for River Rch & Prof#=UNT 126 in Lagun,Reach-1,6
Up Type=0
Dn Type=3
Dn Slope=0.005
Boundary for River Rch & Prof#=UNT 126 in Lagun,Reach-1,7
Up Type=0
Dn Type=3
Dn Slope=0.005

--- UNT 126 in Lagunillas Cr Wtrshd.g01 (geometry) ---

Geom Title=Existing Conditions

River Reach=UNT 126 in Lagun,Reach-1
Reach XY= 30
      2039815.80     13521399.54      2039840.80     13521374.54
      2039860.80     13521374.54      2039880.80     13521354.54
      2039880.80     13521334.54      2039982.94     13521200.79
      2039991.62     13521176.92      2039985.11     13521117.24
      2040107.72     13521014.16      2040237.93     13520872.01
      2040313.88     13520818.84      2040352.95     13520852.48
      2040372.48     13520851.40      2040467.96     13520793.89
      2040479.90     13520762.42      2040586.19     13520602.13
      2040664.32     13520524.01      2040679.08     13520425.05
      2040765.88     13520339.11      2040869.18     13520128.18
      2040876.12     13520088.24      2040919.53     13519985.81
      2040961.19     13519923.31      2040977.69     13519813.94
      2040939.49     13519660.29      2040853.55     13519490.15
      2040826.84     13519405.09      2040801.84     13519371.73
      2040774.94     13519282.25      2040780.80     13519264.54

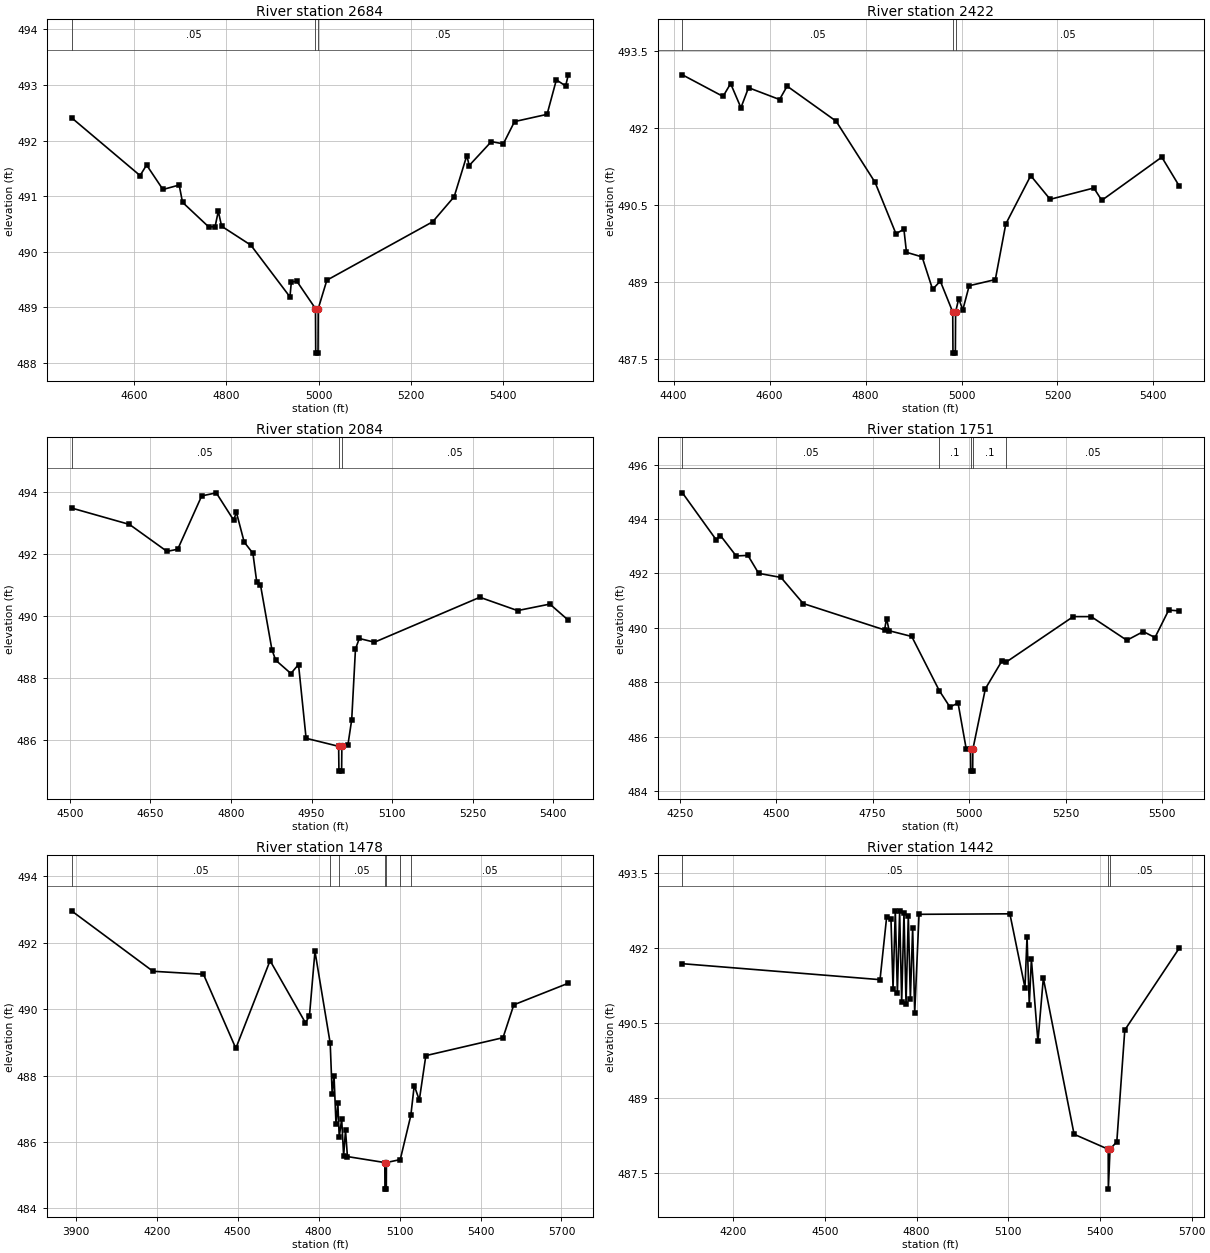
Type RM Length L Ch R = 1,2684,262,262,262
BEGIN DESCRIPTION:
UNT 126 in Lagunillas Cr Wtrshd 2.0
END DESCRIPTION:
XS GIS Cut Line= 4
      2040232.25     13521738.45      2039886.84     13521405.83
      2039767.48     13521338.55      2039309.27     13521398.08
#Sta/Elev= 30
  4463.7  492.41  4612.6  491.37  4626.7  491.56  4662.2  491.12  4697.5  491.20
  4704.7  490.89  4761.3  490.45  4775.4  490.45  4782.4  490.73  4789.6  490.46
  4853.1  490.12  4938.0  489.19  4941.0  489.46  4953.1  489.47  4993.4  488.98
  4993.9  488.18  4998.9  488.18  4999.4  488.98  5018.1  489.49  5247.9  490.54
  5294.5  490.99  5322.0  491.73  5327.1  491.55  5375.2  491.98  5401.2  491.94
  5425.6  492.34  5496.2  492.47  5516.4  493.09  5536.5  492.98  5542.3  493.18
#Mann=3,-1,0
  4463.7    0.05       0  4993.4    0.03       0  4999.4    0.05       0
Bank Sta=4993.4,4999.4
Exp/Cntr=0.3,0.1

Type RM Length L Ch R = 1,2422,338,338,338
BEGIN DESCRIPTION:
Mapping XS 3460cc9d
END DESCRIPTION:
XS GIS Cut Line= 4
      2040360.72     13521596.09      2040166.40     13521258.90
      2039886.02     13521137.37      2039549.10     13521085.80
#Sta/Elev= 30
  4418.2  493.03  4502.9  492.61  4518.7  492.86  4540.2  492.39  4556.0  492.78
  4620.7  492.55  4636.5  492.81  4738.5  492.13  4819.8  490.94  4863.4  489.94
  4879.9  490.03  4885.3  489.58  4917.9  489.49  4939.7  488.86  4955.8  489.02
  4981.7  488.42  4982.2  487.62  4987.2  487.62  4987.7  488.42  4994.2  488.68
  5002.7  488.46  5016.0  488.93  5070.5  489.05  5092.3  490.13  5144.3  491.07
  5184.8  490.61  5275.9  490.83  5292.4  490.59  5417.5  491.43  5453.8  490.87
#Mann=3,-1,0
  4418.2    0.05       0  4981.7    0.03       0  4987.7    0.05       0
Bank Sta=4981.7,4987.7
Exp/Cntr=0.3,0.1

Type RM Length L Ch R = 1,2084,333,333,333
BEGIN DESCRIPTION:
Mapping XS 11e41bb3
END DESCRIPTION:
XS GIS Cut Line= 4
      2040402.38     13521363.45      2040304.42     13521054.03
      2040122.13     13520871.74      2039780.85     13520846.08
#Sta/Elev= 30
  4503.3  493.49  4611.2  492.96  4681.0  492.09  4701.0  492.16  4745.6  493.88
  4772.7  493.98  4805.0  493.10  4810.2  493.35  4824.7  492.39  4840.9  492.03
  4848.0  491.11  4855.0  491.01  4876.3  488.92  4883.3  488.58  4911.6  488.15
  4925.8  488.44  4939.9  486.06  5000.5  485.80  5001.0  485.00  5006.0  485.00
  5006.5  485.80  5017.7  485.84  5024.8  486.66  5031.8  488.94  5038.9  489.28
  5067.2  489.16  5263.3  490.61  5333.5  490.18  5393.6  490.39  5427.9  489.87
#Mann=3,-1,0
  4503.3    0.05       0  5000.5    0.03       0  5006.5    0.05       0
Bank Sta=5000.5,5006.5
Exp/Cntr=0.3,0.1

Type RM Length L Ch R = 1,1751,273,273,273
BEGIN DESCRIPTION:
Mapping XS e7f830a5
END DESCRIPTION:
XS GIS Cut Line= 4
      2040676.69     13521491.95      2040571.78     13520929.90
      2040384.28     13520749.35      2039957.94     13520589.14
#Sta/Elev= 30
  4256.9  494.96  4344.1  493.24  4355.5  493.39  4396.2  492.64  4426.7  492.66
  4454.5  492.00  4512.3  491.85  4570.0  490.89  4780.8  489.92  4785.9  490.34
  4792.9  489.89  4851.2  489.68  4922.6  487.69  4950.0  487.09  4971.3  487.23
  4992.4  485.55  5003.6  485.53  5004.1  484.73  5009.1  484.73  5009.6  485.53
  5042.1  487.76  5084.5  488.77  5096.2  488.74  5269.8  490.41  5316.2  490.41
  5408.7  489.54  5451.4  489.86  5481.6  489.64  5517.2  490.65  5544.4  490.62
#Mann=5,-1,0
  4256.9    0.05       0  4922.6     0.1       0  5003.6    0.07       0
  5009.6     0.1       0  5096.2    0.05       0
Bank Sta=5003.6,5009.6
Exp/Cntr=0.3,0.1

Type RM Length L Ch R = 1,1478,36,36,36
BEGIN DESCRIPTION:
Mapping XS 4120c52b
END DESCRIPTION:
XS GIS Cut Line= 4
      2041089.86     13521571.74      2040767.96     13520751.08
      2040480.63     13520470.70      2039923.19     13520457.19
#Sta/Elev= 30
  3884.6  492.96  4186.4  491.14  4373.5  491.05  4493.4  488.82  4620.3  491.46
  4751.2  489.59  4766.1  489.79  4786.6  491.74  4843.1  488.97  4850.4  487.44
  4857.3  487.99  4864.5  486.54  4871.5  487.16  4876.5  486.15  4885.6  486.69
  4892.8  485.58  4899.8  486.35  4906.9  485.56  5045.4  485.38  5045.9  484.58
  5050.9  484.58  5051.4  485.38  5102.6  485.47  5141.8  486.80  5154.4  487.70
  5173.2  487.26  5197.4  488.60  5483.3  489.14  5523.3  490.13  5725.2  490.78
#Mann=7,-1,0
  3884.6    0.05       0  4843.1     0.1       0  4876.5    0.05       0
  5045.4   0.033       0  5051.4    0.05       0  5102.6     0.1       0
  5141.8    0.05       0
Bank Sta=5045.4,5051.4
Exp/Cntr=0.3,0.1

Type RM Length L Ch R = 1,1442,48,48,48
BEGIN DESCRIPTION:
Mapping XS b01c4aff
END DESCRIPTION:
XS GIS Cut Line= 4
      2041332.96     13521221.10      2040736.71     13520679.03
      2040488.45     13520416.01      2040041.26     13520314.83
#Sta/Elev= 30
  4033.3  491.69  4680.1  491.37  4701.7  492.62  4715.9  492.59  4722.7  491.19
  4730.1  492.75  4736.9  491.10  4744.3  492.74  4751.0  490.92  4758.5  492.71
  4765.2  490.89  4772.7  492.65  4779.4  490.98  4786.9  492.41  4793.6  490.70
  4807.8  492.68  5105.1  492.69  5154.5  491.21  5161.3  492.23  5168.6  490.86
  5175.5  491.78  5196.9  490.13  5214.6  491.40  5315.3  488.27  5426.9  487.97
  5427.4  487.17  5432.9  487.97  5455.1  488.12  5481.2  490.36  5659.3  492.00
#Mann=3,-1,0
  4033.3    0.05       0  5426.9   0.033       0  5432.9    0.05       0
Bank Sta=5426.9,5432.9
Exp/Cntr=0.3,0.1

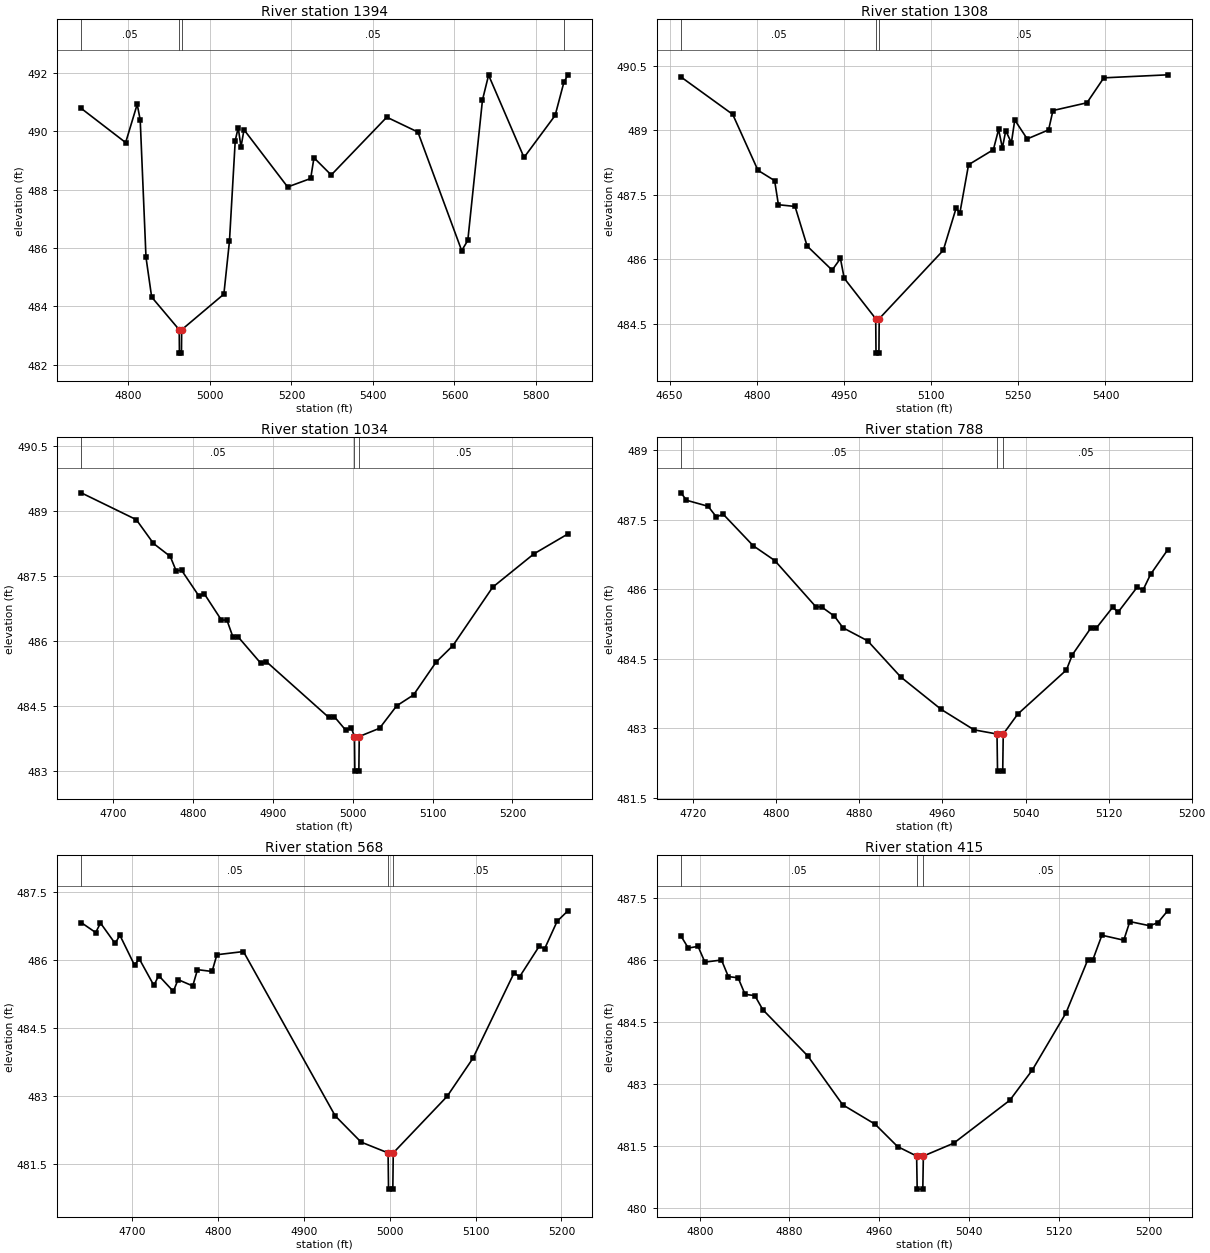
Type RM Length L Ch R = 1,1394,86,86,86
BEGIN DESCRIPTION:
Mapping XS b4dfd598
END DESCRIPTION:
XS GIS Cut Line= 5
      2040862.59     13520759.80      2040846.95     13520700.74
      2040545.74     13520422.09      2040271.84     13520225.53
      2039894.28     13520301.04
#Sta/Elev= 30
  4684.6  490.78  4793.5  489.61  4821.8  490.92  4829.2  490.39  4843.4  485.68
  4857.3  484.32  4924.9  483.20  4925.4  482.40  4930.4  482.40  4930.9  483.20
  5034.4  484.42  5048.1  486.23  5062.3  489.68  5069.6  490.12  5076.4  489.46
  5083.8  490.05  5190.8  488.09  5247.3  488.38  5255.4  489.09  5297.7  488.50
  5434.0  490.48  5510.3  489.97  5617.7  485.91  5632.7  486.26  5668.7  491.07
  5683.7  491.92  5770.6  489.10  5846.9  490.54  5868.3  491.67  5878.2  491.93
#Mann=4,-1,0
  4684.6    0.05       0  4924.9    0.03       0  4930.9    0.05       0
  5868.3     0.1       0
Bank Sta=4924.9,4930.9
Exp/Cntr=0.3,0.1

Type RM Length L Ch R = 1,1308,274,274,274
BEGIN DESCRIPTION:
Mapping XS 8defe749
END DESCRIPTION:
XS GIS Cut Line= 4
      2040901.66     13520680.81      2040841.74     13520583.55
      2040557.89     13520345.70      2040256.24     13520163.05
#Sta/Elev= 30
  4669.7  490.24  4758.7  489.37  4802.1  488.07  4830.8  487.83  4837.3  487.27
  4865.9  487.23  4886.7  486.31  4929.7  485.75  4944.0  486.02  4950.5  485.56
  5004.7  484.62  5005.2  483.82  5010.2  483.82  5010.7  484.62  5120.9  486.21
  5143.0  487.19  5149.5  487.08  5164.4  488.20  5207.1  488.55  5216.1  489.02
  5222.6  488.59  5228.4  488.99  5238.1  488.71  5243.9  489.24  5265.3  488.80
  5302.1  489.01  5309.6  489.46  5368.1  489.64  5397.1  490.22  5506.9  490.29
#Mann=3,-1,0
  4669.7    0.05       0  5004.7    0.03       0  5010.7    0.05       0
Bank Sta=5004.7,5010.7
Exp/Cntr=0.3,0.1

Type RM Length L Ch R = 1,1034,246,246,246
BEGIN DESCRIPTION:
Mapping XS e211e51d
END DESCRIPTION:
XS GIS Cut Line= 5
      2041033.59     13520471.58      2041032.72     13520415.15
      2040695.04     13520100.04      2040643.83     13520101.78
      2040604.72     13520106.99
#Sta/Elev= 30
  4660.4  489.42  4729.3  488.80  4750.8  488.25  4771.8  487.95  4779.1  487.62
  4786.0  487.63  4807.5  487.04  4814.3  487.09  4835.8  486.48  4842.7  486.48
  4850.0  486.10  4856.8  486.09  4885.2  485.48  4892.0  485.52  4970.2  484.23
  4977.0  484.25  4991.2  483.94  4998.5  483.98  5002.3  483.79  5002.8  482.99
  5007.8  482.99  5008.3  483.79  5033.7  483.98  5055.2  484.50  5076.2  484.75
  5104.5  485.51  5125.5  485.89  5175.3  487.24  5226.9  488.01  5269.4  488.47
#Mann=3,-1,0
  4660.4    0.05       0  5002.3    0.03       0  5008.3    0.05       0
Bank Sta=5002.3,5008.3
Exp/Cntr=0.3,0.1

Type RM Length L Ch R = 1,788,220,220,220
BEGIN DESCRIPTION:
Mapping XS a7bae877
END DESCRIPTION:
XS GIS Cut Line= 4
      2041171.85     13520125.09      2041069.18     13520044.49
      2040816.57     13519962.02      2040749.82     13519989.90
#Sta/Elev= 30
  4708.2  488.08  4713.5  487.92  4734.3  487.79  4742.3  487.56  4748.8  487.62
  4777.7  486.94  4798.5  486.62  4838.2  485.62  4843.6  485.62  4856.0  485.42
  4864.2  485.17  4887.9  484.89  4919.8  484.11  4958.8  483.41  4990.4  482.97
  5012.5  482.88  5013.0  482.08  5018.0  482.08  5018.5  482.88  5032.5  483.31
  5079.3  484.26  5085.1  484.59  5102.7  485.16  5108.0  485.16  5123.8  485.61
  5129.2  485.51  5147.6  486.05  5153.0  485.98  5160.3  486.32  5176.8  486.85
#Mann=3,-1,0
  4708.2    0.05       0  5012.5    0.03       0  5018.5    0.05       0
Bank Sta=5012.5,5018.5
Exp/Cntr=0.3,0.1

Type RM Length L Ch R = 1,568,153,153,153
BEGIN DESCRIPTION:
Mapping XS 77b4def7
END DESCRIPTION:
XS GIS Cut Line= 4
      2041312.53     13519878.59      2041151.04     13519800.45
      2040839.14     13519782.33      2040779.20     13519826.86
#Sta/Elev= 30
  4641.0  486.83  4657.8  486.61  4663.4  486.82  4680.4  486.37  4686.0  486.55
  4703.0  485.89  4708.5  486.03  4725.6  485.44  4731.1  485.66  4748.2  485.31
  4753.7  485.57  4770.8  485.43  4776.3  485.79  4793.3  485.75  4798.9  486.12
  4829.8  486.19  4936.6  482.56  4966.7  481.98  4998.2  481.74  4998.7  480.94
  5003.7  480.94  5004.2  481.74  5066.9  482.99  5096.9  483.83  5144.9  485.72
  5151.2  485.63  5174.2  486.31  5180.4  486.25  5195.0  486.86  5207.5  487.09
#Mann=3,-1,0
  4641.0    0.05       0  4998.2    0.03       0  5004.2    0.05       0
Bank Sta=4998.2,5004.2
Exp/Cntr=0.3,0.1

Type RM Length L Ch R = 1,415,176,176,176
BEGIN DESCRIPTION:
Mapping XS 01c59122
END DESCRIPTION:
XS GIS Cut Line= 4
      2041120.82     13519689.45      2041084.37     13519637.37
      2040780.98     13519647.78      2040757.61     13519710.11
#Sta/Elev= 30
  4783.3  486.57  4789.8  486.28  4798.5  486.32  4804.6  485.94  4819.4  485.99
  4825.5  485.59  4834.2  485.56  4840.4  485.16  4849.1  485.13  4856.2  484.79
  4896.3  483.67  4927.4  482.49  4956.3  482.02  4976.3  481.48  4993.3  481.25
  4993.8  480.45  4998.8  480.45  4999.3  481.25  5026.3  481.56  5076.4  482.60
  5096.4  483.33  5126.4  484.71  5145.9  486.00  5150.4  486.00  5158.4  486.59
  5177.9  486.47  5183.3  486.92  5200.9  486.82  5208.2  486.89  5217.0  487.18
#Mann=3,-1,0
  4783.3    0.05       0  4993.3    0.03       0  4999.3    0.05       0
Bank Sta=4993.3,4999.3
Exp/Cntr=0.3,0.1

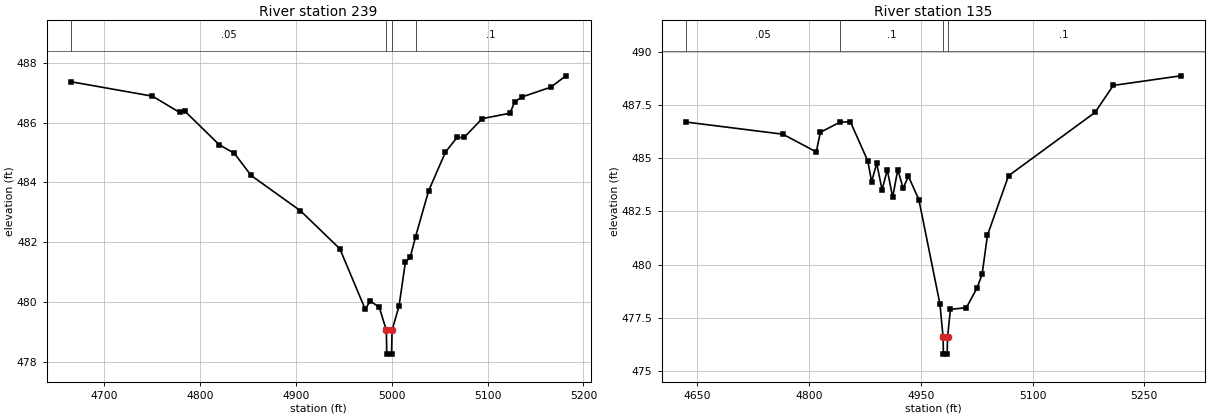
Type RM Length L Ch R = 1,239,104,104,104
BEGIN DESCRIPTION:
Mapping XS 2bf365b3
END DESCRIPTION:
XS GIS Cut Line= 4
      2041177.10     13519487.95      2041014.05     13519447.26
      2040782.28     13519503.25      2040757.54     13519610.04
#Sta/Elev= 30
  4665.6  487.36  4750.2  486.88  4778.5  486.34  4783.7  486.39  4819.8  485.26
  4835.7  484.97  4853.2  484.23  4904.7  483.05  4945.8  481.78  4972.3  479.76
  4977.5  480.04  4987.0  479.82  4994.3  479.06  4994.8  478.26  4999.8  478.26
  5000.3  479.06  5007.6  479.87  5014.2  481.33  5019.3  481.50  5024.8  482.18
  5038.4  483.71  5056.0  485.01  5068.1  485.50  5075.5  485.50  5094.4  486.13
  5123.3  486.31  5128.4  486.69  5135.5  486.85  5166.0  487.18  5181.7  487.56
#Mann=4,-1,0
  4665.6    0.05       0  4994.3    0.03       0  5000.3    0.05       0
  5024.8     0.1       0
Bank Sta=4994.3,5000.3
Exp/Cntr=0.3,0.1

Type RM Length L Ch R = 1,135,0,0,0
BEGIN DESCRIPTION:
UNT 126 in Lagunillas Cr Wtrshd 1.0
END DESCRIPTION:
XS GIS Cut Line= 4
      2041144.12     13519328.23      2040905.14     13519303.07
      2040715.25     13519486.45      2040657.97     13519635.55
#Sta/Elev= 30
  4634.9  486.69  4764.7  486.12  4809.5  485.29  4815.0  486.21  4841.0  486.68
  4855.2  486.71  4878.8  484.86  4883.8  483.89  4890.7  484.75  4897.9  483.51
  4904.9  484.45  4912.1  483.16  4919.0  484.46  4926.2  483.58  4933.2  484.15
  4947.3  483.05  4975.6  478.15  4979.8  476.60  4980.3  475.80  4985.3  475.80
  4985.8  476.60  4989.7  477.90  5011.1  477.98  5025.2  478.89  5032.2  479.54
  5039.4  481.38  5067.7  484.17  5183.8  487.14  5208.4  488.41  5298.9  488.86
#Mann=4,-1,0
  4634.9    0.05       0  4841.0     0.1       0  4979.8    0.07       0
  4985.8     0.1       0
Bank Sta=4979.8,4985.8
Exp/Cntr=0.3,0.1

Chan Stop Cuts=-1