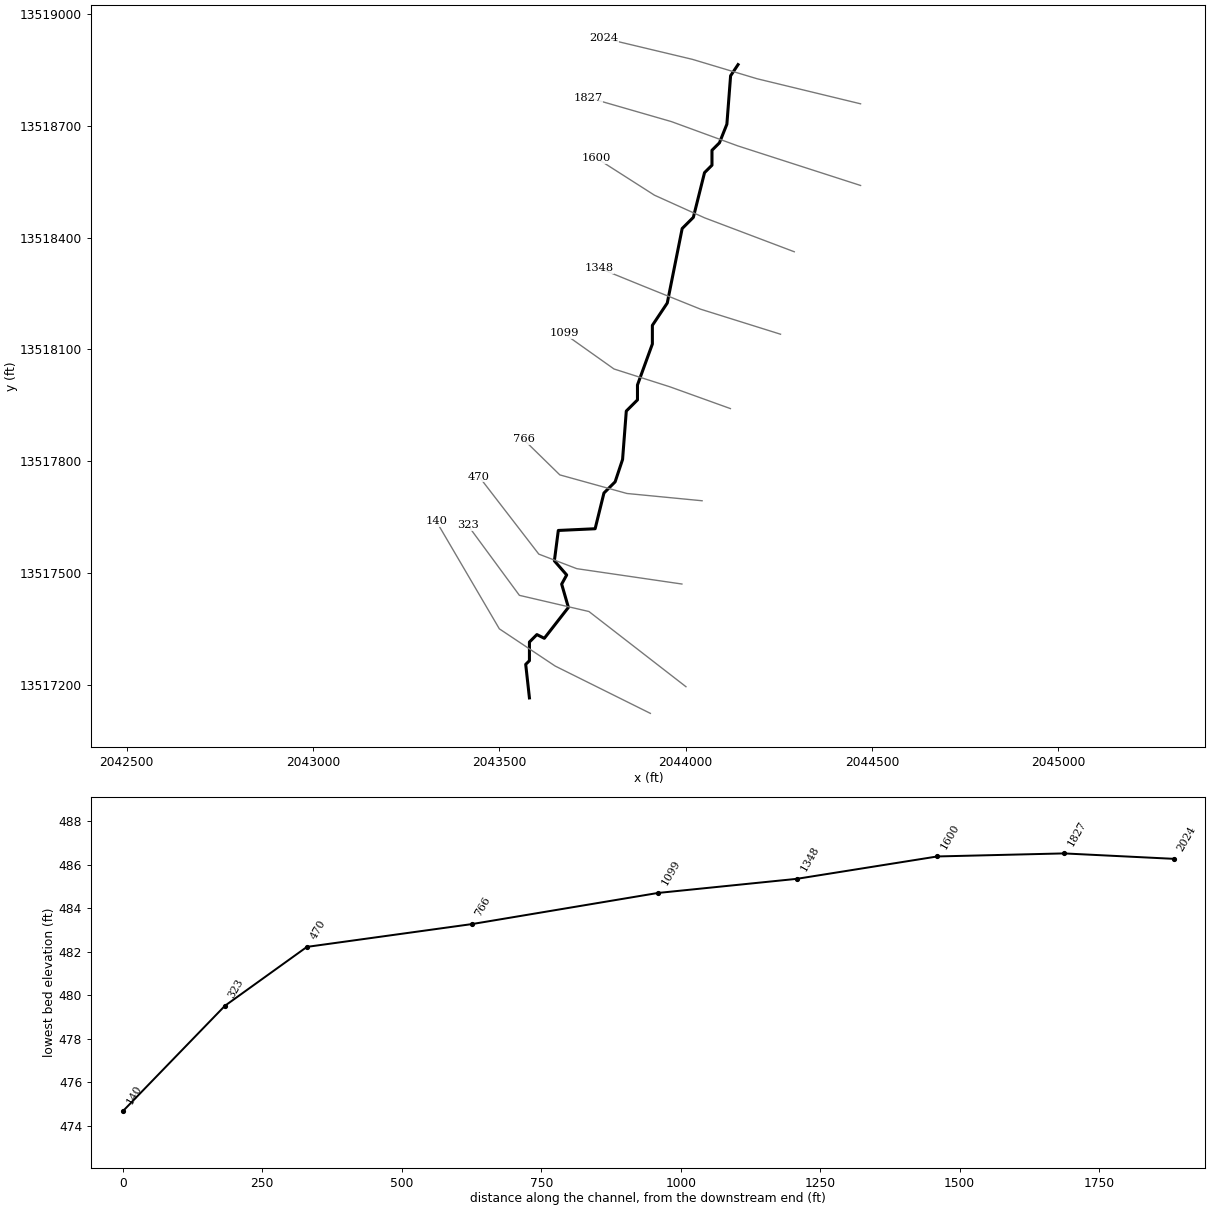
--- UNT 128 in Lagunillas Cr Wtrshd.prj (project) ---

Proj Title=UNT 128 in Lagunillas Cr Wtrshd Base Level Engineering
Current Plan=p01
Default Exp/Contr=0.3,0.1
English Units
Geom File=g01
Flow File=f01
Plan File=p01
BEGIN DESCRIPTION:
UNT 128 in Lagunillas Cr Wtrshd
END DESCRIPTION:

--- UNT 128 in Lagunillas Cr Wtrshd.p01 (plan) ---

Plan Title=Multiple Run
Short Identifier=Multiple
Geom File=g01
Flow File=f01
Subcritical Flow
K Sum by GR= 0
Std Step Tol= 0.01
Critical Tol= 0.01
Num of Std Step Trials= 20
Max Error Tol= 0.3
Flow Tol Ratio= 0.001
Split Flow NTrial= 30
Split Flow Tol= 0.02
Split Flow Ratio= 0.02
Log Output Level= 0
Friction Slope Method= 1
Unsteady Friction Slope Method= 2
Unsteady Bridges Friction Slope Method= 1
Parabolic Critical Depth
Global Vel Dist=  1 , 1 , 1
Global Log Level= 0
CheckData=True
Encroach Param= -1, 0, 0, 0
BEGIN DESCRIPTION:
Multiple Run
END DESCRIPTION:

--- UNT 128 in Lagunillas Cr Wtrshd.f01 (steady flow) ---

Flow Title=Multiple
Number of Profiles=7
Profile Names=10-year,25-year,50-year,1pct_min,100-year,1pct_plu,500-year
River Rch & RM= UNT 128 in Lagun,Reach-1,2024
      79     101     118      69     138     275     190
Boundary for River Rch & Prof#=UNT 128 in Lagun,Reach-1,1
Up Type=0
Dn Type=3
Dn Slope=0.005
Boundary for River Rch & Prof#=UNT 128 in Lagun,Reach-1,2
Up Type=0
Dn Type=3
Dn Slope=0.005
Boundary for River Rch & Prof#=UNT 128 in Lagun,Reach-1,3
Up Type=0
Dn Type=3
Dn Slope=0.005
Boundary for River Rch & Prof#=UNT 128 in Lagun,Reach-1,4
Up Type=0
Dn Type=3
Dn Slope=0.005
Boundary for River Rch & Prof#=UNT 128 in Lagun,Reach-1,5
Up Type=0
Dn Type=3
Dn Slope=0.005
Boundary for River Rch & Prof#=UNT 128 in Lagun,Reach-1,6
Up Type=0
Dn Type=3
Dn Slope=0.005
Boundary for River Rch & Prof#=UNT 128 in Lagun,Reach-1,7
Up Type=0
Dn Type=3
Dn Slope=0.005

--- UNT 128 in Lagunillas Cr Wtrshd.g01 (geometry) ---

Geom Title=Existing Conditions

River Reach=UNT 128 in Lagun,Reach-1
Reach XY= 30
      2044140.80     13518864.54      2044120.80     13518834.54
      2044110.80     13518704.54      2044090.80     13518654.54
      2044070.80     13518634.54      2044070.80     13518594.54
      2044050.80     13518574.54      2044020.80     13518454.54
      2043990.80     13518424.54      2043950.80     13518224.54
      2043910.80     13518164.54      2043910.80     13518114.54
      2043870.80     13518004.54      2043870.80     13517964.54
      2043840.80     13517934.54      2043830.80     13517804.54
      2043810.80     13517744.54      2043780.80     13517714.54
      2043757.14     13517618.65      2043658.31     13517614.05
      2043647.76     13517532.48      2043680.80     13517494.54
      2043667.32     13517469.98      2043685.38     13517407.48
      2043620.80     13517324.54      2043600.80     13517334.54
      2043580.80     13517314.54      2043580.80     13517264.54
      2043570.80     13517254.54      2043580.80     13517164.54

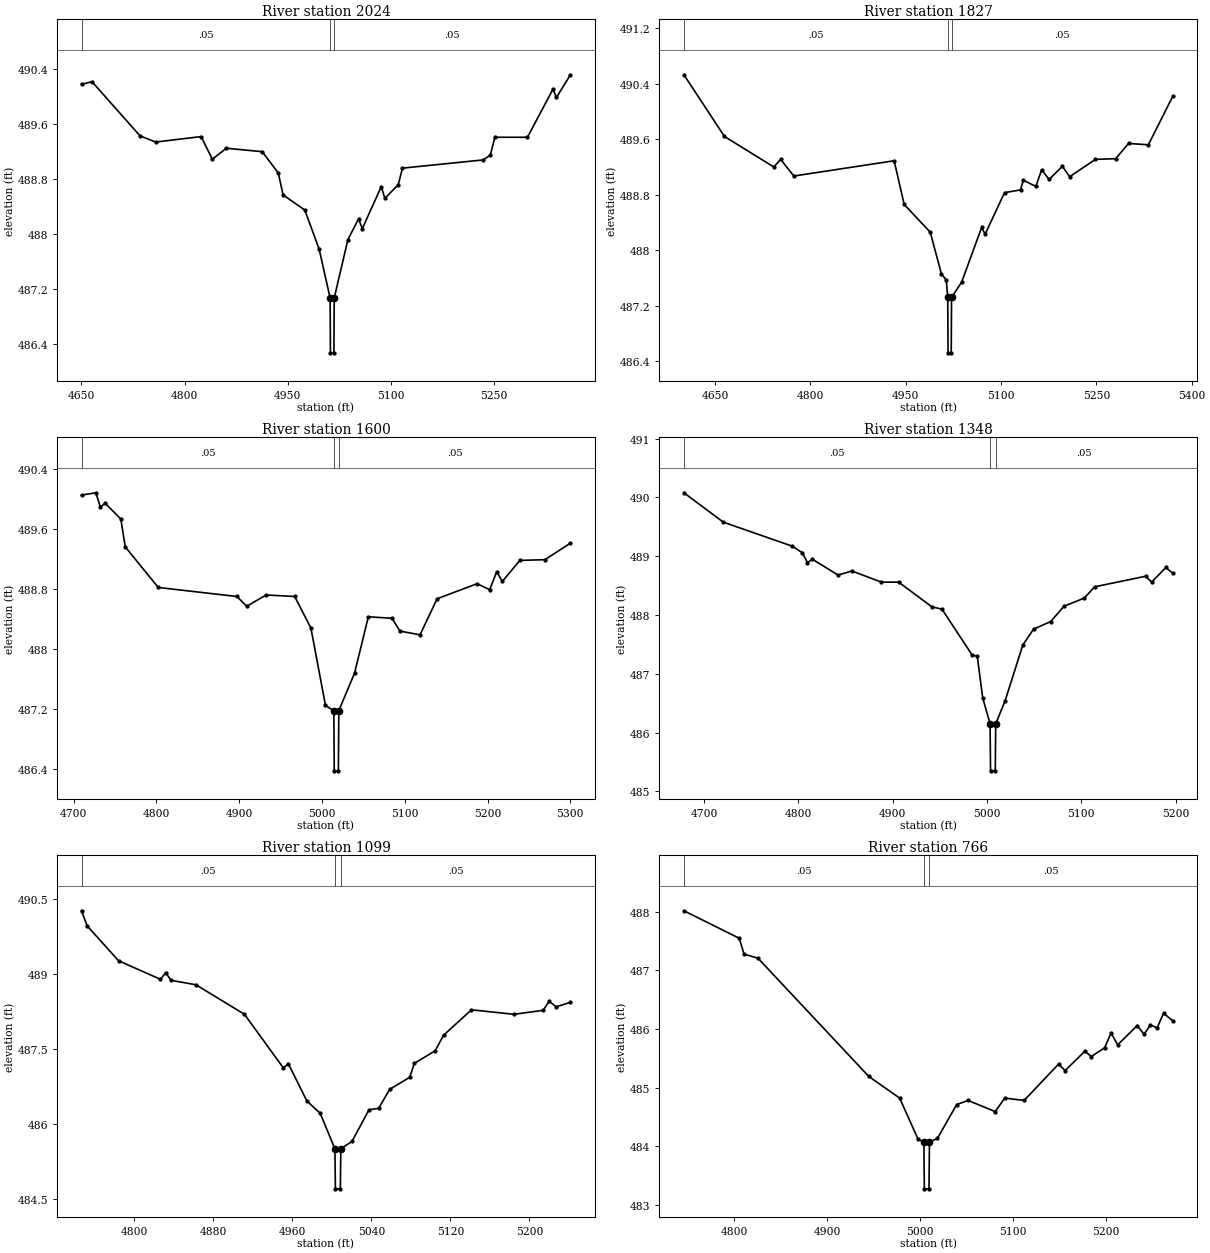
Type RM Length L Ch R = 1,2024,197,197,197
BEGIN DESCRIPTION:
UNT 128 in Lagunillas Cr Wtrshd 4.0
END DESCRIPTION:
XS GIS Cut Line= 4
      2044469.68     13518759.30      2044191.90     13518826.58
      2044018.29     13518878.66      2043781.79     13518935.07
#Sta/Elev= 30
  4650.4  490.18  4665.5  490.22  4735.4  489.43  4758.1  489.34  4824.1  489.42
  4840.4  489.09  4860.8  489.25  4912.9  489.20  4936.2  488.89  4943.2  488.57
  4974.7  488.35  4995.6  487.78  5011.5  487.07  5012.0  486.27  5017.0  486.27
  5017.5  487.07  5037.4  487.92  5052.8  488.22  5058.3  488.08  5085.8  488.69
  5091.1  488.52  5110.5  488.72  5116.6  488.96  5233.9  489.08  5244.2  489.15
  5250.9  489.41  5298.2  489.41  5335.2  490.11  5340.3  489.99  5360.6  490.32
#Mann=3,-1,0
  4650.4    0.05       0  5011.5   0.035       0  5017.5    0.05       0
Bank Sta=5011.5,5017.5
Exp/Cntr=0.3,0.1

Type RM Length L Ch R = 1,1827,227,227,227
BEGIN DESCRIPTION:
Mapping XS a45f219c
END DESCRIPTION:
XS GIS Cut Line= 4
      2044469.70     13518540.11      2044139.82     13518646.46
      2043961.87     13518711.56      2043738.08     13518776.11
#Sta/Elev= 30
  4601.2  490.53  4665.0  489.64  4742.7  489.20  4753.2  489.31  4774.2  489.07
  4931.9  489.29  4947.7  488.66  4988.7  488.26  5006.2  487.66  5013.9  487.57
  5016.2  487.32  5016.7  486.52  5021.7  486.52  5022.2  487.32  5038.1  487.54
  5069.6  488.33  5075.0  488.23  5105.5  488.83  5130.7  488.87  5135.0  489.01
  5154.8  488.92  5163.9  489.16  5175.7  489.02  5196.5  489.21  5208.0  489.06
  5248.5  489.31  5280.5  489.32  5300.6  489.54  5331.8  489.52  5370.2  490.22
#Mann=3,-1,0
  4601.2    0.05       0  5016.2   0.035       0  5022.2    0.05       0
Bank Sta=5016.2,5022.2
Exp/Cntr=0.3,0.1

Type RM Length L Ch R = 1,1600,252,252,252
BEGIN DESCRIPTION:
Mapping XS 0372b5df
END DESCRIPTION:
XS GIS Cut Line= 4
      2044291.71     13518362.17      2044050.84     13518453.31
      2043916.30     13518514.08      2043760.03     13518613.91
#Sta/Elev= 30
  4709.5  490.05  4726.8  490.08  4732.2  489.89  4738.1  489.94  4757.0  489.73
  4762.3  489.36  4802.2  488.82  4897.1  488.70  4909.1  488.57  4932.6  488.72
  4967.0  488.70  4986.6  488.28  5004.2  487.25  5014.3  487.18  5014.8  486.38
  5019.8  486.38  5020.3  487.18  5039.3  487.68  5056.0  488.43  5084.6  488.41
  5094.1  488.24  5118.4  488.19  5139.1  488.67  5187.4  488.87  5202.6  488.79
  5211.1  489.03  5217.8  488.90  5239.0  489.18  5269.4  489.19  5300.1  489.41
#Mann=3,-1,0
  4709.5    0.05       0  5014.3   0.035       0  5020.3    0.05       0
Bank Sta=5014.3,5020.3
Exp/Cntr=0.3,0.1

Type RM Length L Ch R = 1,1348,249,249,249
BEGIN DESCRIPTION:
Mapping XS 852e30dc
END DESCRIPTION:
XS GIS Cut Line= 4
      2044254.85     13518140.81      2044039.99     13518208.09
      2043883.74     13518271.02      2043768.25     13518318.07
#Sta/Elev= 30
  4678.7  490.08  4720.5  489.58  4793.8  489.17  4804.3  489.06  4809.7  488.89
  4814.9  488.95  4842.1  488.68  4856.7  488.75  4888.1  488.56  4906.4  488.56
  4941.6  488.14  4952.3  488.10  4984.3  487.32  4989.7  487.30  4995.5  486.59
  5003.3  486.15  5003.8  485.35  5008.8  485.35  5009.3  486.15  5019.2  486.54
  5038.0  487.49  5049.4  487.76  5067.6  487.89  5081.7  488.15  5103.3  488.29
  5114.1  488.48  5168.1  488.66  5174.6  488.56  5189.7  488.81  5197.0  488.71
#Mann=3,-1,0
  4678.7    0.05       0  5003.3   0.035       0  5009.3    0.05       0
Bank Sta=5003.3,5009.3
Exp/Cntr=0.3,0.1

Type RM Length L Ch R = 1,1099,333,333,333
BEGIN DESCRIPTION:
Mapping XS afd31e0f
END DESCRIPTION:
XS GIS Cut Line= 4
      2044120.27     13517941.17      2043957.53     13517999.75
      2043807.79     13518047.50      2043673.26     13518142.97
#Sta/Elev= 30
  4746.5  490.26  4752.1  489.96  4784.0  489.26  4826.4  488.89  4831.7  489.02
  4837.1  488.87  4862.4  488.78  4911.5  488.19  4950.8  487.12  4956.0  487.20
  4974.6  486.46  4988.2  486.21  5003.1  485.50  5003.6  484.70  5008.6  484.70
  5009.1  485.50  5020.4  485.65  5037.6  486.28  5047.4  486.31  5058.6  486.69
  5078.8  486.93  5083.6  487.21  5104.6  487.46  5113.1  487.77  5141.4  488.28
  5184.5  488.19  5214.0  488.27  5220.1  488.45  5227.2  488.34  5241.6  488.43
#Mann=3,-1,0
  4746.5    0.05       0  5003.1   0.035       0  5009.1    0.05       0
Bank Sta=5003.1,5009.1
Exp/Cntr=0.3,0.1

Type RM Length L Ch R = 1,766,296,296,296
BEGIN DESCRIPTION:
Mapping XS 7f1132ea
END DESCRIPTION:
XS GIS Cut Line= 4
      2044044.32     13517693.77      2043842.51     13517713.30
      2043662.39     13517763.21      2043564.76     13517858.67
#Sta/Elev= 30
  4746.1  488.02  4805.7  487.55  4810.8  487.28  4825.8  487.21  4945.1  485.19
  4978.3  484.82  4998.1  484.12  5004.4  484.07  5004.9  483.27  5009.9  483.27
  5010.4  484.07  5018.9  484.13  5039.7  484.71  5052.0  484.78  5081.1  484.59
  5091.5  484.82  5112.3  484.78  5149.3  485.40  5156.4  485.29  5177.6  485.62
  5184.7  485.53  5198.9  485.68  5205.9  485.93  5213.0  485.73  5234.1  486.06
  5241.3  485.91  5248.3  486.07  5255.4  486.02  5262.4  486.27  5272.3  486.14
#Mann=3,-1,0
  4746.1    0.05       0  5004.4   0.035       0  5010.4    0.05       0
Bank Sta=5004.4,5010.4
Exp/Cntr=0.3,0.1

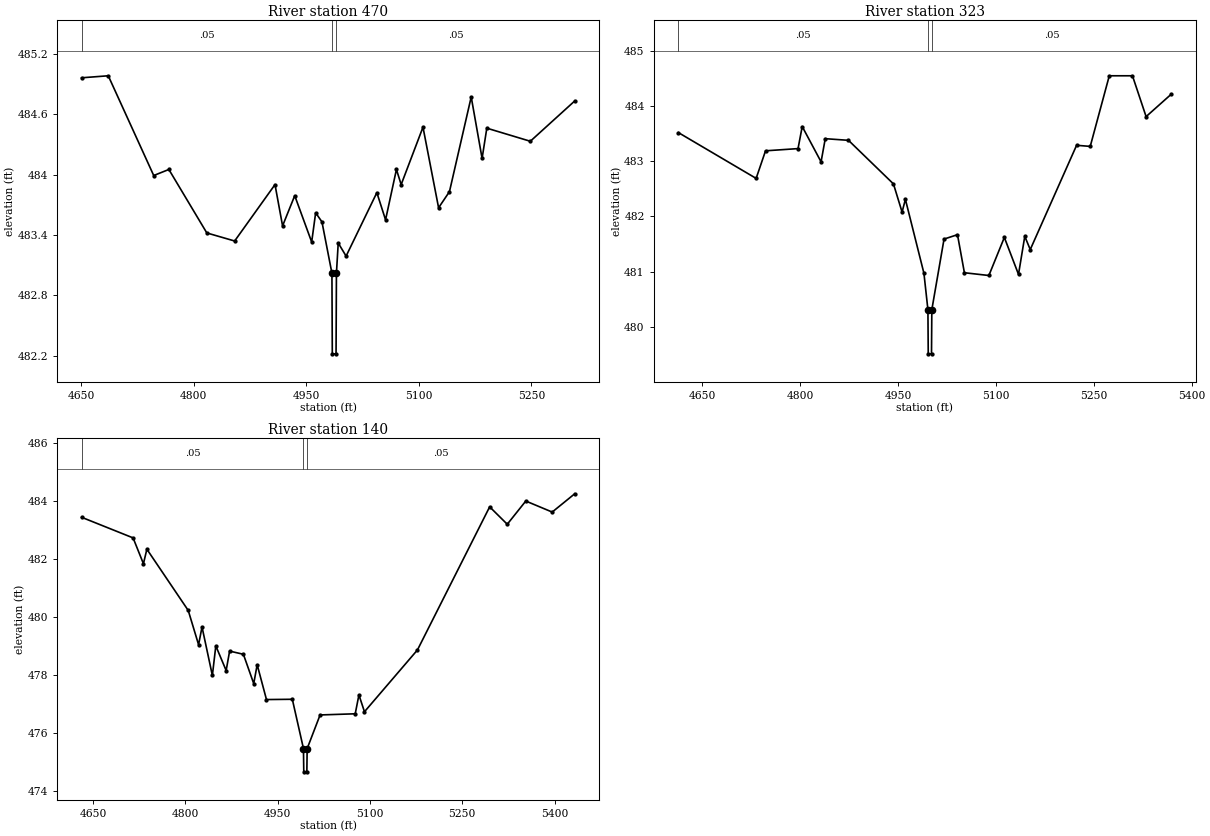
Type RM Length L Ch R = 1,470,147,147,147
BEGIN DESCRIPTION:
Mapping XS f1fd5af7
END DESCRIPTION:
XS GIS Cut Line= 4
      2043990.11     13517470.24      2043707.96     13517511.47
      2043605.97     13517550.53      2043445.38     13517758.86
#Sta/Elev= 30
  4650.4  484.96  4685.9  484.98  4746.5  483.99  4766.7  484.05  4817.3  483.42
  4854.4  483.34  4908.2  483.90  4918.3  483.49  4934.5  483.79  4957.1  483.33
  4962.4  483.62  4970.8  483.53  4984.1  483.02  4984.6  482.22  4989.6  482.22
  4990.1  483.02  4992.5  483.32  5003.0  483.19  5044.0  483.82  5055.6  483.55
  5070.1  484.05  5076.4  483.90  5105.5  484.47  5126.3  483.67  5140.8  483.83
  5169.8  484.77  5184.3  484.16  5190.6  484.46  5248.6  484.33  5307.8  484.73
#Mann=3,-1,0
  4650.4    0.05       0  4984.1    0.03       0  4990.1    0.05       0
Bank Sta=4984.1,4990.1
Exp/Cntr=0.3,0.1

Type RM Length L Ch R = 1,323,183,183,183
BEGIN DESCRIPTION:
Mapping XS a315e21c
END DESCRIPTION:
XS GIS Cut Line= 4
      2044000.95     13517194.62      2043740.51     13517396.46
      2043553.88     13517439.86      2043414.99     13517628.67
#Sta/Elev= 30
  4613.5  483.52  4732.6  482.69  4747.0  483.19  4796.8  483.23  4803.2  483.63
  4832.1  482.99  4838.5  483.41  4874.1  483.38  4943.0  482.59  4956.2  482.08
  4961.3  482.31  4989.7  480.97  4995.8  480.31  4996.3  479.51  5001.3  479.51
  5001.8  480.31  5020.5  481.59  5041.1  481.67  5051.7  480.98  5089.2  480.93
  5112.9  481.62  5134.6  480.95  5144.2  481.64  5152.6  481.40  5223.6  483.29
  5244.5  483.27  5273.7  484.55  5309.2  484.55  5330.1  483.81  5369.0  484.22
#Mann=3,-1,0
  4613.5    0.05       0  4995.8    0.03       0  5001.8    0.05       0
Bank Sta=4995.8,5001.8
Exp/Cntr=0.3,0.1

Type RM Length L Ch R = 1,140,0,0,0
BEGIN DESCRIPTION:
UNT 128 in Lagunillas Cr Wtrshd 1.0
END DESCRIPTION:
XS GIS Cut Line= 4
      2043905.41     13517123.03      2043650.00     13517250.00
      2043500.00     13517350.00      2043330.34     13517639.55
#Sta/Elev= 30
  4631.6  483.43  4715.2  482.72  4732.0  481.83  4737.6  482.33  4804.8  480.22
  4821.6  479.04  4827.2  479.65  4844.0  477.98  4849.6  479.00  4866.4  478.15
  4872.0  478.82  4894.4  478.71  4911.2  477.70  4916.8  478.35  4931.9  477.15
  4973.9  477.16  4992.0  475.46  4992.5  474.66  4997.5  474.66  4998.0  475.46
  5019.0  476.62  5076.1  476.66  5082.1  477.31  5091.1  476.73  5177.2  478.86
  5294.5  483.79  5323.1  483.19  5353.2  483.99  5396.1  483.61  5432.7  484.24
#Mann=3,-1,0
  4631.6    0.05       0  4992.0    0.03       0  4998.0    0.05       0
Bank Sta=4992,4998
Exp/Cntr=0.3,0.1

Chan Stop Cuts=-1