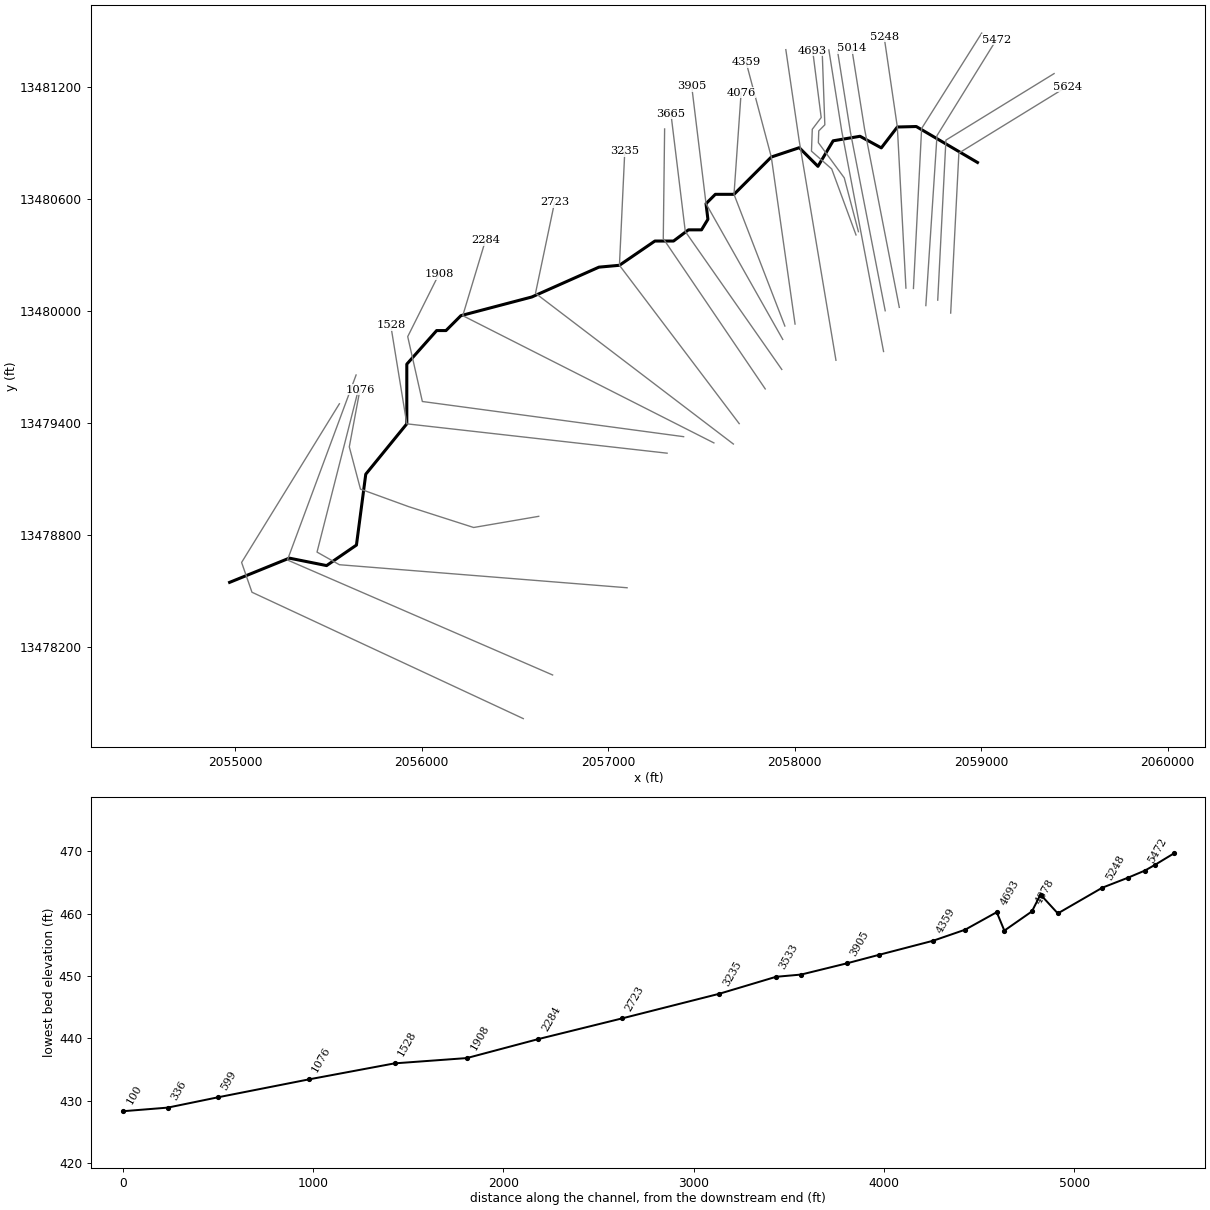
--- UNT 129 in Lagunillas Cr Wtrshd.prj (project) ---

Proj Title=UNT 129 in Lagunillas Cr Wtrshd Base Level Engineering
Current Plan=p01
Default Exp/Contr=0.3,0.1
English Units
Geom File=g01
Flow File=f01
Plan File=p01
BEGIN DESCRIPTION:
UNT 129 in Lagunillas Cr Wtrshd
END DESCRIPTION:

--- UNT 129 in Lagunillas Cr Wtrshd.p01 (plan) ---

Plan Title=Multiple Run
Short Identifier=Multiple
Geom File=g01
Flow File=f01
Subcritical Flow
K Sum by GR= 0
Std Step Tol= 0.01
Critical Tol= 0.01
Num of Std Step Trials= 20
Max Error Tol= 0.3
Flow Tol Ratio= 0.001
Split Flow NTrial= 30
Split Flow Tol= 0.02
Split Flow Ratio= 0.02
Log Output Level= 0
Friction Slope Method= 1
Unsteady Friction Slope Method= 2
Unsteady Bridges Friction Slope Method= 1
Parabolic Critical Depth
Global Vel Dist=  1 , 1 , 1
Global Log Level= 0
CheckData=True
Encroach Param= -1, 0, 0, 0
BEGIN DESCRIPTION:
Multiple Run
END DESCRIPTION:

--- UNT 129 in Lagunillas Cr Wtrshd.f01 (steady flow) ---

Flow Title=Multiple
Number of Profiles=7
Profile Names=10-year,25-year,50-year,1pct_min,100-year,1pct_plu,500-year
River Rch & RM= UNT 129 in Lagun,Reach-1,5624
     110     145     174     104     207     414     299
Boundary for River Rch & Prof#=UNT 129 in Lagun,Reach-1,1
Up Type=0
Dn Type=3
Dn Slope=0.005
Boundary for River Rch & Prof#=UNT 129 in Lagun,Reach-1,2
Up Type=0
Dn Type=3
Dn Slope=0.005
Boundary for River Rch & Prof#=UNT 129 in Lagun,Reach-1,3
Up Type=0
Dn Type=3
Dn Slope=0.005
Boundary for River Rch & Prof#=UNT 129 in Lagun,Reach-1,4
Up Type=0
Dn Type=3
Dn Slope=0.005
Boundary for River Rch & Prof#=UNT 129 in Lagun,Reach-1,5
Up Type=0
Dn Type=3
Dn Slope=0.005
Boundary for River Rch & Prof#=UNT 129 in Lagun,Reach-1,6
Up Type=0
Dn Type=3
Dn Slope=0.005
Boundary for River Rch & Prof#=UNT 129 in Lagun,Reach-1,7
Up Type=0
Dn Type=3
Dn Slope=0.005

--- UNT 129 in Lagunillas Cr Wtrshd.g01 (geometry) ---

Geom Title=Existing Conditions

River Reach=UNT 129 in Lagun,Reach-1
Reach XY= 30
      2058980.43     13480795.79      2058652.30     13480988.50
      2058550.74     13480985.90      2058464.80     13480873.92
      2058350.72     13480936.23      2058206.62     13480911.92
      2058125.00     13480775.00      2058025.00     13480875.00
      2057875.00     13480825.00      2057675.00     13480625.00
      2057575.00     13480625.00      2057525.00     13480575.00
      2057535.12     13480491.11      2057500.80     13480434.54
      2057430.80     13480434.54      2057350.80     13480374.54
      2057250.80     13480374.54      2057060.80     13480244.54
      2056950.80     13480234.54      2056590.80     13480074.54
      2056210.80     13479974.54      2056130.80     13479894.54
      2056080.80     13479894.54      2055920.80     13479714.54
      2055920.80     13479394.54      2055700.80     13479124.54
      2055650.80     13478744.54      2055490.80     13478634.54
      2055290.80     13478674.54      2054970.80     13478544.54

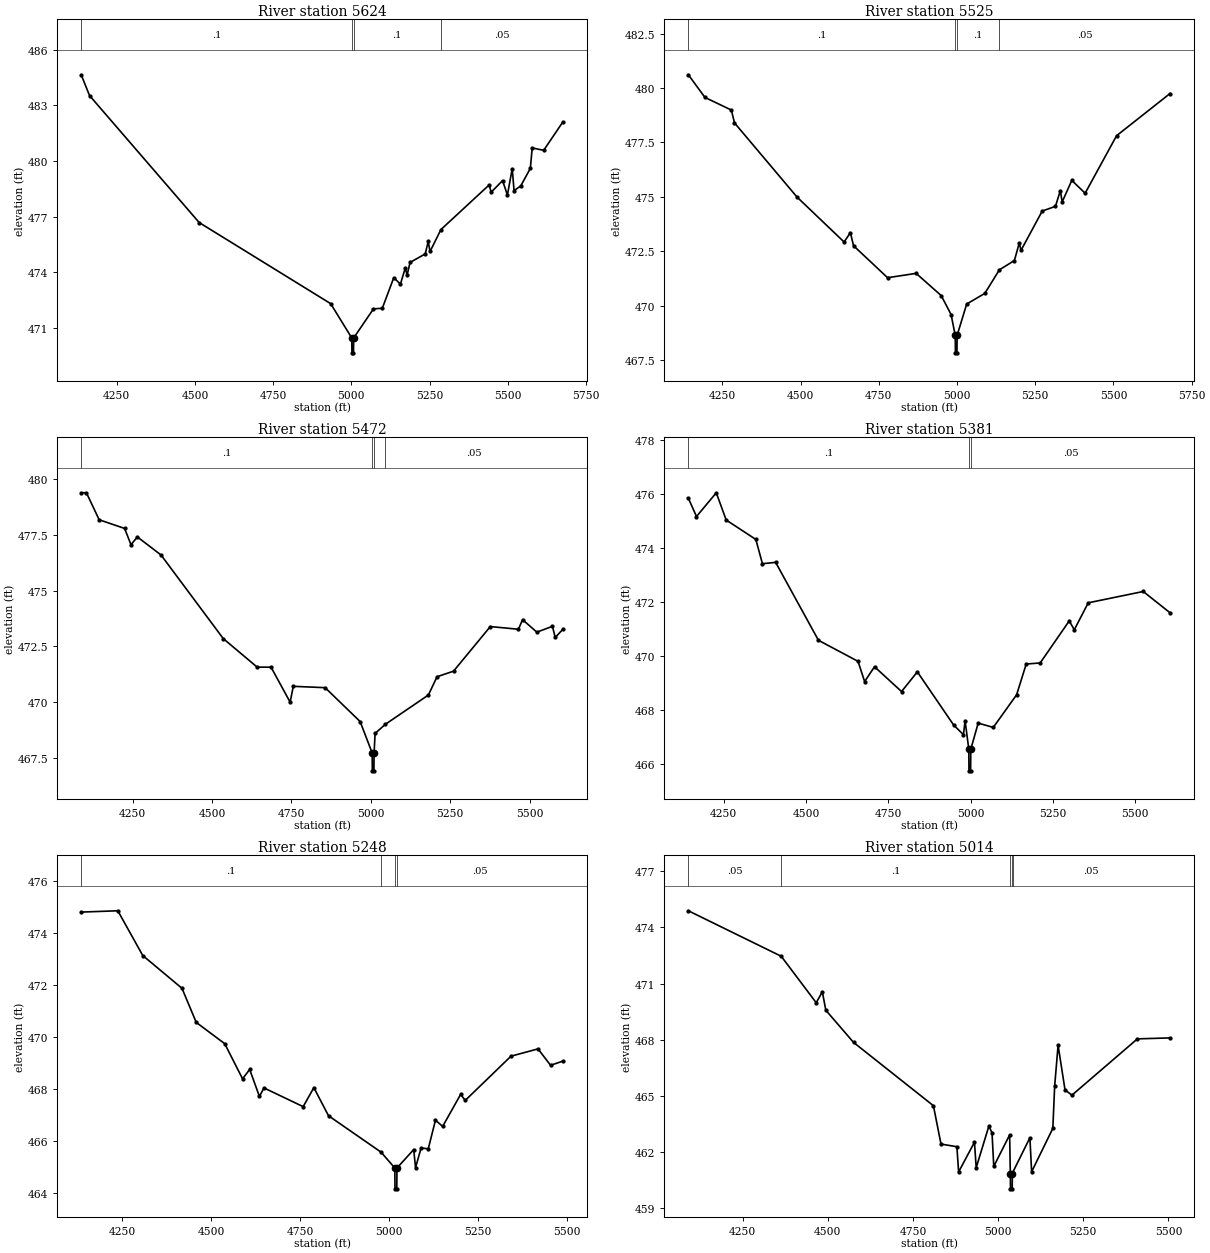
Type RM Length L Ch R = 1,5624,99,99,99
BEGIN DESCRIPTION:
UNT 129 in Lagunillas Cr Wtrshd 2.0
END DESCRIPTION:
XS GIS Cut Line= 3
      2058836.71     13479988.31      2058880.60     13480846.14
      2059460.86     13481203.06
#Sta/Elev= 30
  4136.2  484.65  4162.9  483.53  4513.4  476.69  4933.9  472.32  5001.4  470.47
  5001.9  469.67  5006.9  469.67  5007.4  470.47  5070.8  472.04  5099.0  472.07
  5135.7  473.72  5157.0  473.37  5172.4  474.24  5178.3  473.86  5187.8  474.54
  5236.3  475.00  5245.8  475.67  5251.7  475.13  5286.4  476.31  5441.0  478.72
  5446.9  478.32  5483.6  478.95  5499.0  478.17  5514.4  479.59  5520.3  478.41
  5541.6  478.66  5572.4  479.61  5578.3  480.71  5615.0  480.58  5676.4  482.11
#Mann=4,-1,0
  4136.2     0.1       0  5001.4    0.07       0  5007.4     0.1       0
  5286.4    0.05       0
Bank Sta=5001.4,5007.4
Exp/Cntr=0.3,0.1

Type RM Length L Ch R = 1,5525,53,53,53
BEGIN DESCRIPTION:
UNT 129 in Lagunillas Cr Wtrshd 1.0
END DESCRIPTION:
XS GIS Cut Line= 3
      2058767.26     13480057.71      2058811.16     13480915.59
      2059391.13     13481272.32
#Sta/Elev= 30
  4141.0  480.61  4194.0  479.57  4278.5  478.99  4288.5  478.40  4488.7  474.99
  4638.9  472.93  4659.0  473.36  4669.0  472.76  4777.9  471.29  4869.2  471.49
  4949.3  470.47  4980.9  469.60  4994.2  468.64  4994.7  467.84  4999.7  467.84
  5000.2  468.64  5030.7  470.08  5088.7  470.57  5135.2  471.65  5183.3  472.08
  5198.8  472.88  5204.6  472.55  5272.2  474.35  5314.7  474.57  5330.1  475.29
  5336.0  474.77  5366.8  475.76  5409.4  475.17  5509.9  477.81  5680.9  479.75
#Mann=4,-1,0
  4141.0     0.1       0  4994.2    0.07       0  5000.2     0.1       0
  5135.2    0.05       0
Bank Sta=4994.2,5000.2
Exp/Cntr=0.3,0.1

Type RM Length L Ch R = 1,5472,91,91,91
BEGIN DESCRIPTION:
UNT 129 in Lagunillas Cr Wtrshd 3.0
END DESCRIPTION:
XS GIS Cut Line= 3
      2058703.56     13480028.52      2058763.45     13480939.94
      2059081.15     13481452.94
#Sta/Elev= 30
  4087.8  479.39  4104.3  479.39  4144.4  478.18  4224.6  477.79  4244.6  477.06
  4264.7  477.41  4339.2  476.60  4535.2  472.85  4642.0  471.57  4685.6  471.57
  4745.7  470.00  4755.7  470.71  4855.9  470.65  4966.2  469.13  5004.1  467.72
  5004.6  466.92  5009.6  466.92  5010.1  467.72  5013.3  468.60  5045.9  469.01
  5181.1  470.32  5208.3  471.14  5260.3  471.39  5376.1  473.39  5464.7  473.27
  5477.6  473.70  5522.6  473.14  5571.7  473.40  5580.5  472.90  5604.6  473.27
#Mann=4,-1,0
  4087.8     0.1       0  5004.1    0.07       0  5010.1     0.1       0
  5045.9    0.05       0
Bank Sta=5004.1,5010.1
Exp/Cntr=0.3,0.1

Type RM Length L Ch R = 1,5381,133,133,133
BEGIN DESCRIPTION:
UNT 129 in Lagunillas Cr Wtrshd 5.0
END DESCRIPTION:
XS GIS Cut Line= 3
      2058637.06     13480120.29      2058680.95     13480978.09
      2059003.01     13481489.38
#Sta/Elev= 30
  4142.9  475.86  4167.6  475.18  4227.7  476.06  4257.8  475.05  4347.9  474.33
  4367.9  473.43  4408.0  473.48  4538.1  470.59  4658.3  469.81  4678.3  469.06
  4708.4  469.61  4790.5  468.69  4838.5  469.42  4948.7  467.45  4978.5  467.09
  4983.5  467.61  4994.8  466.55  4995.3  465.75  5000.3  465.75  5000.8  466.55
  5023.3  467.52  5069.1  467.36  5140.0  468.57  5169.2  469.71  5211.6  469.75
  5299.9  471.31  5315.2  470.98  5357.6  471.98  5524.7  472.40  5606.1  471.61
#Mann=3,-1,0
  4142.9     0.1       0  4994.8    0.03       0  5000.8    0.05       0
Bank Sta=4994.8,5000.8
Exp/Cntr=0.3,0.1

Type RM Length L Ch R = 1,5248,234,234,234
BEGIN DESCRIPTION:
UNT 129 in Lagunillas Cr Wtrshd 6.0
END DESCRIPTION:
XS GIS Cut Line= 3
      2058596.78     13480122.22      2058550.74     13480985.90
      2058479.88     13481469.23
#Sta/Elev= 30
  4135.1  474.81  4238.0  474.86  4308.1  473.14  4418.3  471.88  4458.3  470.57
  4538.4  469.75  4588.5  468.40  4608.5  468.76  4635.9  467.72  4648.6  468.05
  4758.8  467.33  4788.8  468.06  4830.0  466.98  4977.7  465.58  5016.3  464.97
  5016.8  464.17  5021.8  464.17  5022.3  464.97  5069.4  465.68  5074.5  464.98
  5090.1  465.74  5110.3  465.71  5130.5  466.81  5150.7  466.57  5201.2  467.80
  5214.2  467.57  5342.7  469.27  5418.6  469.55  5453.9  468.92  5488.5  469.08
#Mann=4,-1,0
  4135.1     0.1       0  4977.7    0.05       0  5016.3    0.03       0
  5022.3    0.05       0
Bank Sta=5016.3,5022.3
Exp/Cntr=0.3,0.1

Type RM Length L Ch R = 1,5014,91,91,91
BEGIN DESCRIPTION:
UNT 129 in Lagunillas Cr Wtrshd 7.0
END DESCRIPTION:
XS GIS Cut Line= 3
      2058561.20     13480018.90      2058375.00     13480975.00
      2058305.98     13481409.59
#Sta/Elev= 30
  4090.8  474.89  4363.5  472.46  4466.1  469.98  4484.2  470.56  4494.3  469.58
  4575.8  467.86  4810.2  464.48  4832.5  462.43  4879.1  462.29  4884.2  460.94
  4930.7  462.53  4935.8  461.17  4973.2  463.40  4982.3  463.02  4987.4  461.24
  5034.0  462.92  5036.0  460.84  5036.5  460.04  5041.5  460.04  5042.0  460.84
  5042.6  460.90  5093.5  462.77  5098.5  460.95  5160.8  463.27  5166.1  465.51
  5176.2  467.71  5196.5  465.33  5216.7  465.04  5409.1  468.05  5504.9  468.10
#Mann=5,-1,0
  4090.8    0.05       0  4363.5     0.1       0  5036.0    0.07       0
  5042.0     0.1       0  5042.6    0.05       0
Bank Sta=5036,5042
Exp/Cntr=0.3,0.1

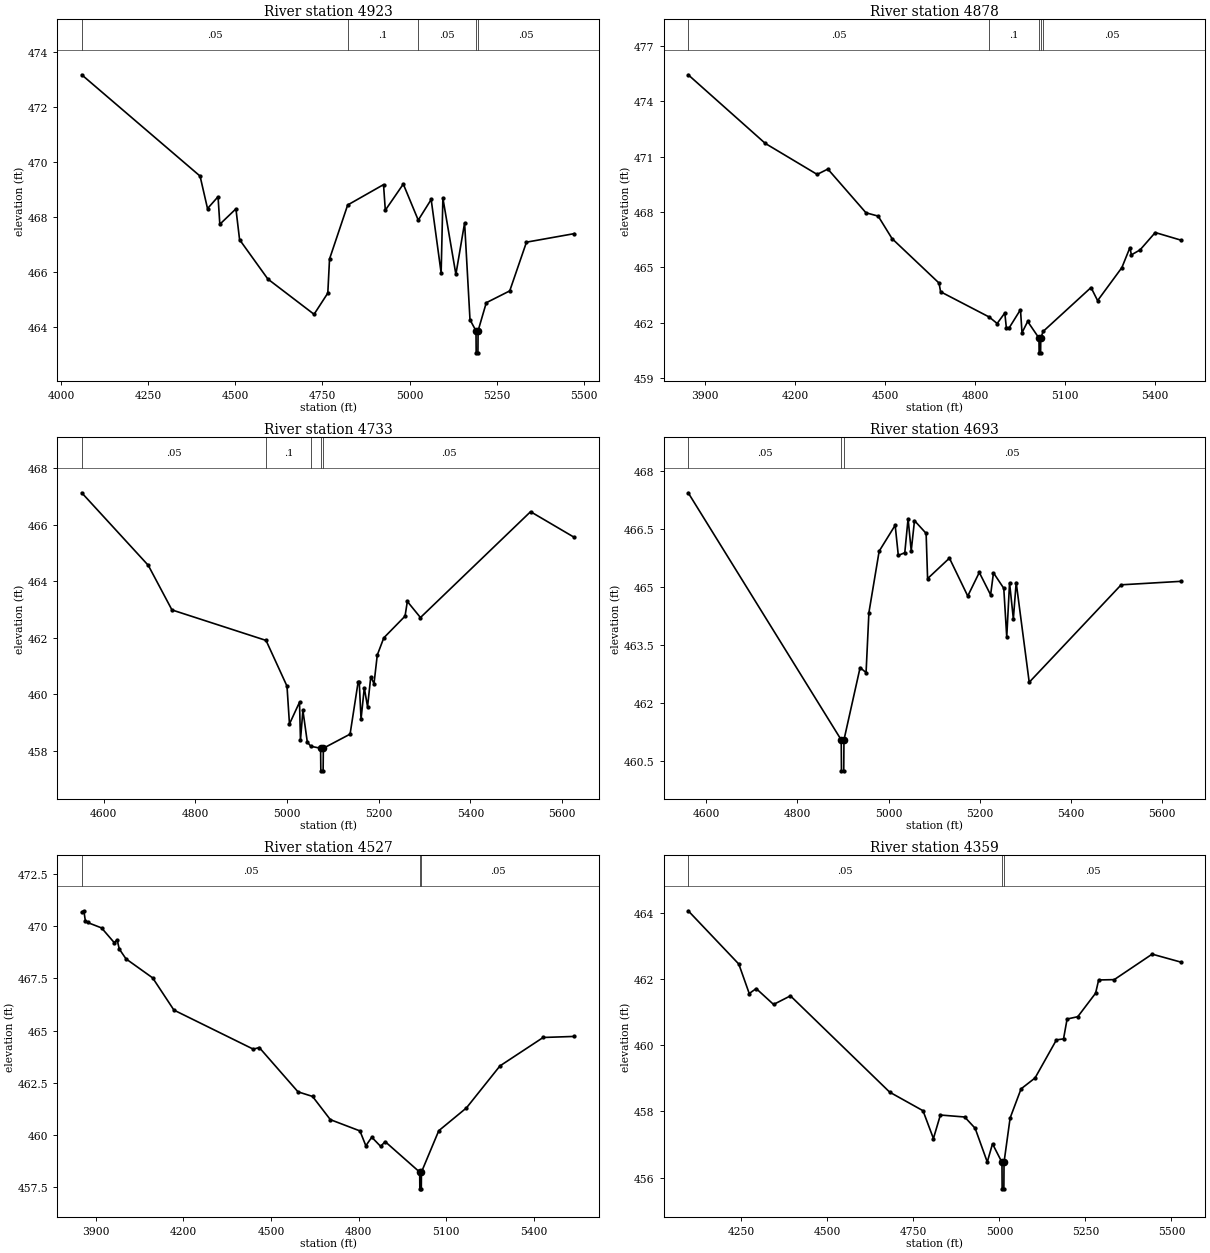
Type RM Length L Ch R = 1,4923,45,45,45
BEGIN DESCRIPTION:
UNT 129 in Lagunillas Cr Wtrshd 8.0
END DESCRIPTION:
XS GIS Cut Line= 3
      2058485.66     13480000.74      2058299.48     13480956.77
      2058230.57     13481390.64
#Sta/Elev= 30
  4059.5  473.17  4399.0  469.49  4420.4  468.31  4450.6  468.74  4455.7  467.74
  4501.9  468.30  4512.4  467.18  4593.6  465.75  4726.1  464.47  4765.5  465.24
  4770.5  466.48  4822.5  468.44  4925.4  469.18  4930.5  468.25  4982.1  469.20
  5025.0  467.89  5062.1  468.64  5090.7  465.97  5095.7  468.69  5133.0  465.92
  5158.0  467.79  5173.5  464.27  5190.7  463.87  5191.2  463.07  5196.2  463.07
  5196.7  463.87  5220.2  464.89  5287.5  465.32  5335.5  467.09  5472.8  467.40
#Mann=5,-1,0
  4059.5    0.05       0  4822.5     0.1       0  5025.0    0.05       0
  5190.7    0.07       0  5196.7    0.05       0
Bank Sta=5190.7,5196.7
Exp/Cntr=0.3,0.1

Type RM Length L Ch R = 1,4878,145,145,145
BEGIN DESCRIPTION:
UNT 129 in Lagunillas Cr Wtrshd 9.0
END DESCRIPTION:
XS GIS Cut Line= 3
      2058476.82     13479782.32      2058252.60     13480964.58
      2058183.59     13481399.10
#Sta/Elev= 30
  3843.4  475.44  4100.6  471.72  4273.6  470.04  4309.3  470.33  4436.5  467.96
  4477.2  467.78  4523.5  466.56  4680.3  464.15  4685.4  463.68  4847.7  462.31
  4874.1  461.96  4899.6  462.53  4904.7  461.74  4914.8  461.74  4951.9  462.71
  4957.0  461.46  4975.9  462.07  5013.6  461.17  5014.1  460.37  5019.1  460.37
  5019.6  461.17  5027.5  461.53  5187.3  463.91  5209.2  463.20  5290.2  464.99
  5316.9  466.07  5322.0  465.68  5350.9  465.95  5401.5  466.89  5486.7  466.48
#Mann=5,-1,0
  3843.4    0.05       0  4847.7     0.1       0  5013.6    0.07       0
  5019.6     0.1       0  5027.5    0.05       0
Bank Sta=5013.6,5019.6
Exp/Cntr=0.3,0.1

Type RM Length L Ch R = 1,4733,40,40,40
BEGIN DESCRIPTION:
Mapping XS 74bd748d
END DESCRIPTION:
XS GIS Cut Line= 6
      2058342.10     13480424.69      2058266.15     13480713.30
      2058127.26     13480902.10      2058129.43     13480965.03
      2058161.98     13480997.58      2058146.80     13481420.38
#Sta/Elev= 30
  4552.3  467.13  4697.4  464.56  4749.1  462.98  4954.3  461.90  5000.0  460.28
  5005.4  458.94  5027.3  459.71  5029.4  458.37  5034.7  459.42  5044.3  458.30
  5051.9  458.15  5073.3  458.08  5073.8  457.28  5078.8  457.28  5079.3  458.08
  5137.6  458.58  5155.1  460.42  5157.6  460.42  5161.5  459.11  5168.6  460.22
  5175.7  459.55  5182.7  460.61  5189.8  460.37  5196.9  461.38  5211.1  461.99
  5257.5  462.76  5262.5  463.28  5291.1  462.71  5531.3  466.46  5626.7  465.55
#Mann=5,-1,0
  4552.3    0.05       0  4954.3     0.1       0  5051.9    0.05       0
  5073.3    0.07       0  5079.3    0.05       0
Bank Sta=5073.3,5079.3
Exp/Cntr=0.3,0.1

Type RM Length L Ch R = 1,4693,166,166,166
BEGIN DESCRIPTION:
Mapping XS 3acf9c83
END DESCRIPTION:
XS GIS Cut Line= 6
      2058329.10     13480407.27      2058198.87     13480761.04
      2058090.37     13480856.53      2058094.71     13480973.71
      2058142.45     13481036.65      2058096.87     13481394.75
#Sta/Elev= 30
  4560.3  467.43  4895.9  461.04  4896.4  460.24  4901.4  460.24  4901.9  461.04
  4937.3  462.91  4950.4  462.78  4956.6  464.33  4979.1  465.92  5014.2  466.59
  5021.1  465.81  5035.3  465.88  5042.5  466.76  5049.4  465.93  5056.6  466.71
  5082.1  466.38  5085.3  465.21  5133.2  465.74  5173.4  464.76  5198.7  465.37
  5223.5  464.79  5229.8  465.36  5252.4  464.96  5258.9  463.70  5265.1  465.10
  5273.4  464.17  5279.6  465.11  5308.2  462.53  5509.8  465.05  5640.6  465.14
#Mann=3,-1,0
  4560.3    0.05       0  4895.9    0.03       0  4901.9    0.05       0
Bank Sta=4895.9,4901.9
Exp/Cntr=0.3,0.1

Type RM Length L Ch R = 1,4527,168,168,168
BEGIN DESCRIPTION:
UNT 129 in Lagunillas Cr Wtrshd 12.0
END DESCRIPTION:
XS GIS Cut Line= 3
      2058221.62     13479735.43      2058023.92     13480915.93
      2057952.87     13481400.61
#Sta/Elev= 30
  3851.6  470.66  3858.8  470.73  3863.9  470.26  3871.4  470.17  3919.5  469.91
  3962.7  469.21  3972.8  469.34  3980.2  468.90  4003.2  468.43  4094.5  467.52
  4167.3  465.98  4439.2  464.11  4459.5  464.19  4592.2  462.07  4642.0  461.85
  4702.9  460.74  4804.3  460.20  4824.5  459.49  4844.8  459.90  4875.2  459.46
  4890.5  459.69  5008.9  458.23  5009.4  457.43  5014.4  457.43  5014.9  458.23
  5074.2  460.21  5168.9  461.30  5283.8  463.31  5431.7  464.67  5538.4  464.72
#Mann=3,-1,0
  3851.6    0.05       0  5008.9    0.03       0  5014.9    0.05       0
Bank Sta=5008.9,5014.9
Exp/Cntr=0.3,0.1

Type RM Length L Ch R = 1,4359,283,283,283
BEGIN DESCRIPTION:
UNT 129 in Lagunillas Cr Wtrshd 13.0
END DESCRIPTION:
XS GIS Cut Line= 3
      2058002.34     13479929.41      2057875.00     13480825.00
      2057739.67     13481334.33
#Sta/Elev= 30
  4095.4  464.06  4242.5  462.45  4272.8  461.56  4293.0  461.71  4343.5  461.23
  4392.5  461.49  4681.1  458.58  4777.8  458.02  4808.1  457.18  4828.3  457.89
  4899.0  457.83  4929.3  457.49  4964.6  456.47  4979.8  457.02  5007.3  456.46
  5007.8  455.66  5012.8  455.66  5013.3  456.46  5031.0  457.80  5062.8  458.68
  5103.5  459.01  5165.6  460.16  5186.2  460.19  5196.6  460.79  5227.6  460.86
  5279.4  461.57  5288.3  461.97  5333.6  461.98  5443.8  462.75  5527.0  462.51
#Mann=3,-1,0
  4095.4    0.05       0  5007.3    0.03       0  5013.3    0.05       0
Bank Sta=5007.3,5013.3
Exp/Cntr=0.3,0.1

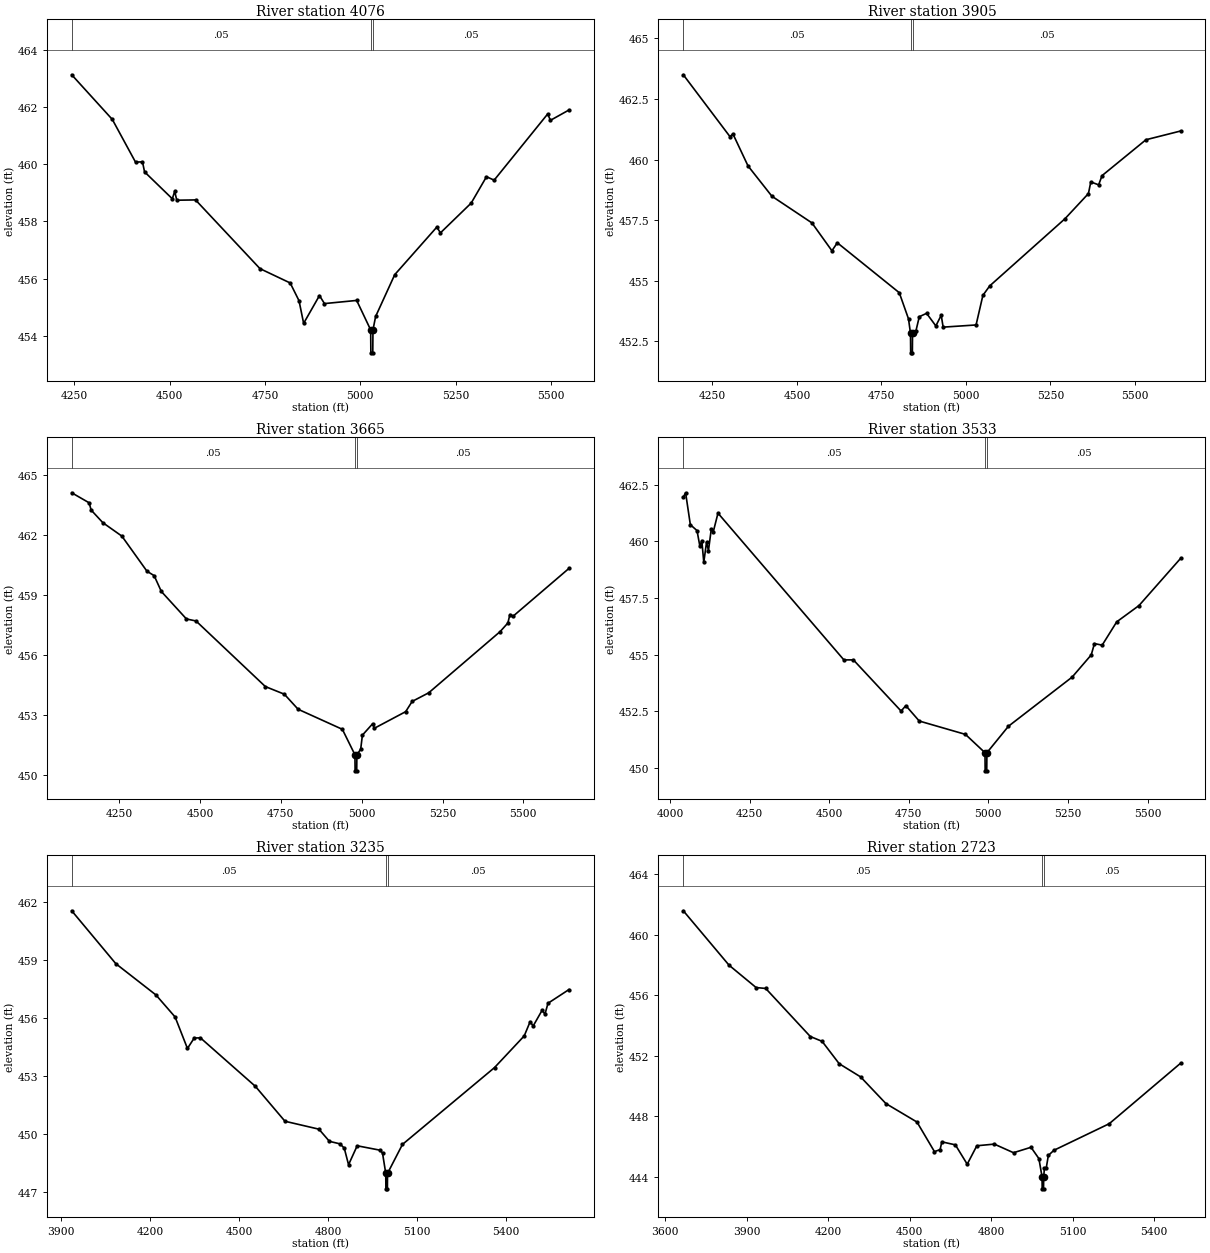
Type RM Length L Ch R = 1,4076,171,171,171
BEGIN DESCRIPTION:
UNT 129 in Lagunillas Cr Wtrshd 14.0
END DESCRIPTION:
XS GIS Cut Line= 3
      2057947.67     13479918.92      2057675.00     13480625.00
      2057713.23     13481170.76
#Sta/Elev= 30
  4243.1  463.12  4349.6  461.56  4410.4  460.07  4428.7  460.08  4434.1  459.73
  4506.9  458.79  4513.2  459.05  4518.6  458.74  4567.8  458.75  4736.8  456.35
  4816.0  455.85  4839.2  455.23  4851.3  454.44  4892.8  455.41  4905.9  455.13
  4990.4  455.24  5027.1  454.21  5027.6  453.41  5032.6  453.41  5033.1  454.21
  5040.1  454.68  5090.2  456.14  5200.5  457.80  5210.1  457.60  5290.7  458.64
  5330.8  459.56  5350.9  459.44  5491.2  461.75  5498.6  461.53  5547.1  461.89
#Mann=3,-1,0
  4243.1    0.05       0  5027.1    0.03       0  5033.1    0.05       0
Bank Sta=5027.1,5033.1
Exp/Cntr=0.3,0.1

Type RM Length L Ch R = 1,3905,240,240,240
BEGIN DESCRIPTION:
UNT 129 in Lagunillas Cr Wtrshd 15.0
END DESCRIPTION:
XS GIS Cut Line= 3
      2057936.38     13479847.11      2057525.00     13480575.00
      2057448.09     13481205.63
#Sta/Elev= 30
  4163.9  463.50  4301.9  460.95  4310.8  461.06  4355.4  459.74  4426.1  458.49
  4544.5  457.39  4603.7  456.24  4619.6  456.57  4803.0  454.51  4830.3  453.43
  4836.2  452.83  4836.7  452.03  4841.7  452.03  4842.2  452.83  4852.0  452.92
  4862.2  453.52  4883.8  453.66  4911.2  453.14  4927.1  453.58  4932.8  453.09
  5030.2  453.18  5050.4  454.40  5070.5  454.79  5293.2  457.56  5362.7  458.60
  5369.7  459.08  5392.9  458.96  5403.0  459.34  5532.9  460.82  5635.3  461.18
#Mann=3,-1,0
  4163.9    0.05       0  4836.2    0.03       0  4842.2    0.05       0
Bank Sta=4836.2,4842.2
Exp/Cntr=0.3,0.1

Type RM Length L Ch R = 1,3665,132,132,132
BEGIN DESCRIPTION:
UNT 129 in Lagunillas Cr Wtrshd 16.0
END DESCRIPTION:
XS GIS Cut Line= 3
      2057931.14     13479686.14      2057413.89     13480425.69
      2057336.98     13481056.33
#Sta/Elev= 30
  4103.3  464.09  4157.2  463.59  4163.3  463.23  4199.5  462.60  4258.4  461.93
  4336.0  460.18  4358.2  459.96  4380.5  459.17  4458.1  457.80  4487.7  457.70
  4702.2  454.43  4760.9  454.05  4803.4  453.30  4940.3  452.30  4979.2  451.03
  4979.7  450.23  4984.7  450.23  4985.2  451.03  4997.0  451.31  5002.3  452.01
  5034.1  452.58  5039.1  452.35  5136.1  453.18  5156.2  453.69  5207.4  454.12
  5428.2  457.17  5452.2  457.60  5458.4  458.02  5468.5  457.94  5641.1  460.32
#Mann=3,-1,0
  4103.3    0.05       0  4979.2    0.03       0  4985.2    0.05       0
Bank Sta=4979.2,4985.2
Exp/Cntr=0.3,0.1

Type RM Length L Ch R = 1,3533,298,298,298
BEGIN DESCRIPTION:
UNT 129 in Lagunillas Cr Wtrshd 17.0
END DESCRIPTION:
XS GIS Cut Line= 3
      2057842.45     13479581.75      2057295.83     13480387.50
      2057303.02     13480975.49
#Sta/Elev= 30
  4042.0  461.96  4049.2  462.15  4064.1  460.74  4085.1  460.48  4094.0  459.79
  4100.1  460.04  4106.3  459.08  4115.0  459.97  4121.0  459.60  4130.0  460.56
  4136.0  460.42  4150.9  461.25  4546.3  454.77  4576.2  454.77  4726.0  452.51
  4740.9  452.75  4783.0  452.07  4928.1  451.48  4989.5  450.67  4990.0  449.87
  4995.0  449.87  4995.5  450.67  5063.2  451.84  5263.2  454.01  5323.2  454.99
  5333.2  455.49  5357.5  455.42  5403.2  456.45  5473.2  457.17  5603.7  459.25
#Mann=3,-1,0
  4042.0    0.05       0  4989.5    0.03       0  4995.5    0.05       0
Bank Sta=4989.5,4995.5
Exp/Cntr=0.3,0.1

Type RM Length L Ch R = 1,3235,512,512,512
BEGIN DESCRIPTION:
UNT 129 in Lagunillas Cr Wtrshd 18.0
END DESCRIPTION:
XS GIS Cut Line= 3
      2057702.90     13479395.63      2057060.80     13480244.54
      2057089.47     13480855.67
#Sta/Elev= 30
  3935.6  461.55  4084.3  458.81  4219.6  457.19  4284.1  456.05  4325.7  454.42
  4348.6  454.96  4369.4  454.97  4554.6  452.46  4654.5  450.65  4768.9  450.24
  4804.3  449.61  4839.7  449.48  4854.3  449.26  4868.8  448.40  4897.9  449.38
  4975.5  449.15  4983.3  449.00  4994.2  447.95  4994.7  447.15  4999.7  447.15
  5000.2  447.95  5050.5  449.45  5360.9  453.43  5461.0  455.07  5481.0  455.81
  5491.0  455.58  5521.0  456.39  5531.0  456.20  5541.1  456.76  5611.8  457.47
#Mann=3,-1,0
  3935.6    0.05       0  4994.2    0.03       0  5000.2    0.05       0
Bank Sta=4994.2,5000.2
Exp/Cntr=0.3,0.1

Type RM Length L Ch R = 1,2723,439,439,439
BEGIN DESCRIPTION:
UNT 129 in Lagunillas Cr Wtrshd 27.0
END DESCRIPTION:
XS GIS Cut Line= 3
      2057671.66     13479286.25      2056610.80     13480094.54
      2056712.98     13480581.53
#Sta/Elev= 30
  3666.3  461.59  3834.7  457.99  3934.4  456.51  3969.8  456.45  4134.0  453.27
  4177.5  452.95  4240.4  451.47  4319.1  450.60  4412.6  448.83  4526.9  447.61
  4591.3  445.65  4612.1  445.79  4618.4  446.30  4668.3  446.10  4711.9  444.82
  4747.3  446.04  4811.7  446.15  4882.4  445.58  4946.9  445.94  4975.9  445.19
  4987.5  443.99  4988.0  443.19  4993.0  443.19  4993.5  443.99  4996.3  444.55
  5002.8  444.55  5010.7  445.40  5031.1  445.74  5235.0  447.50  5497.6  451.50
#Mann=3,-1,0
  3666.3    0.05       0  4987.5    0.03       0  4993.5    0.05       0
Bank Sta=4987.5,4993.5
Exp/Cntr=0.3,0.1

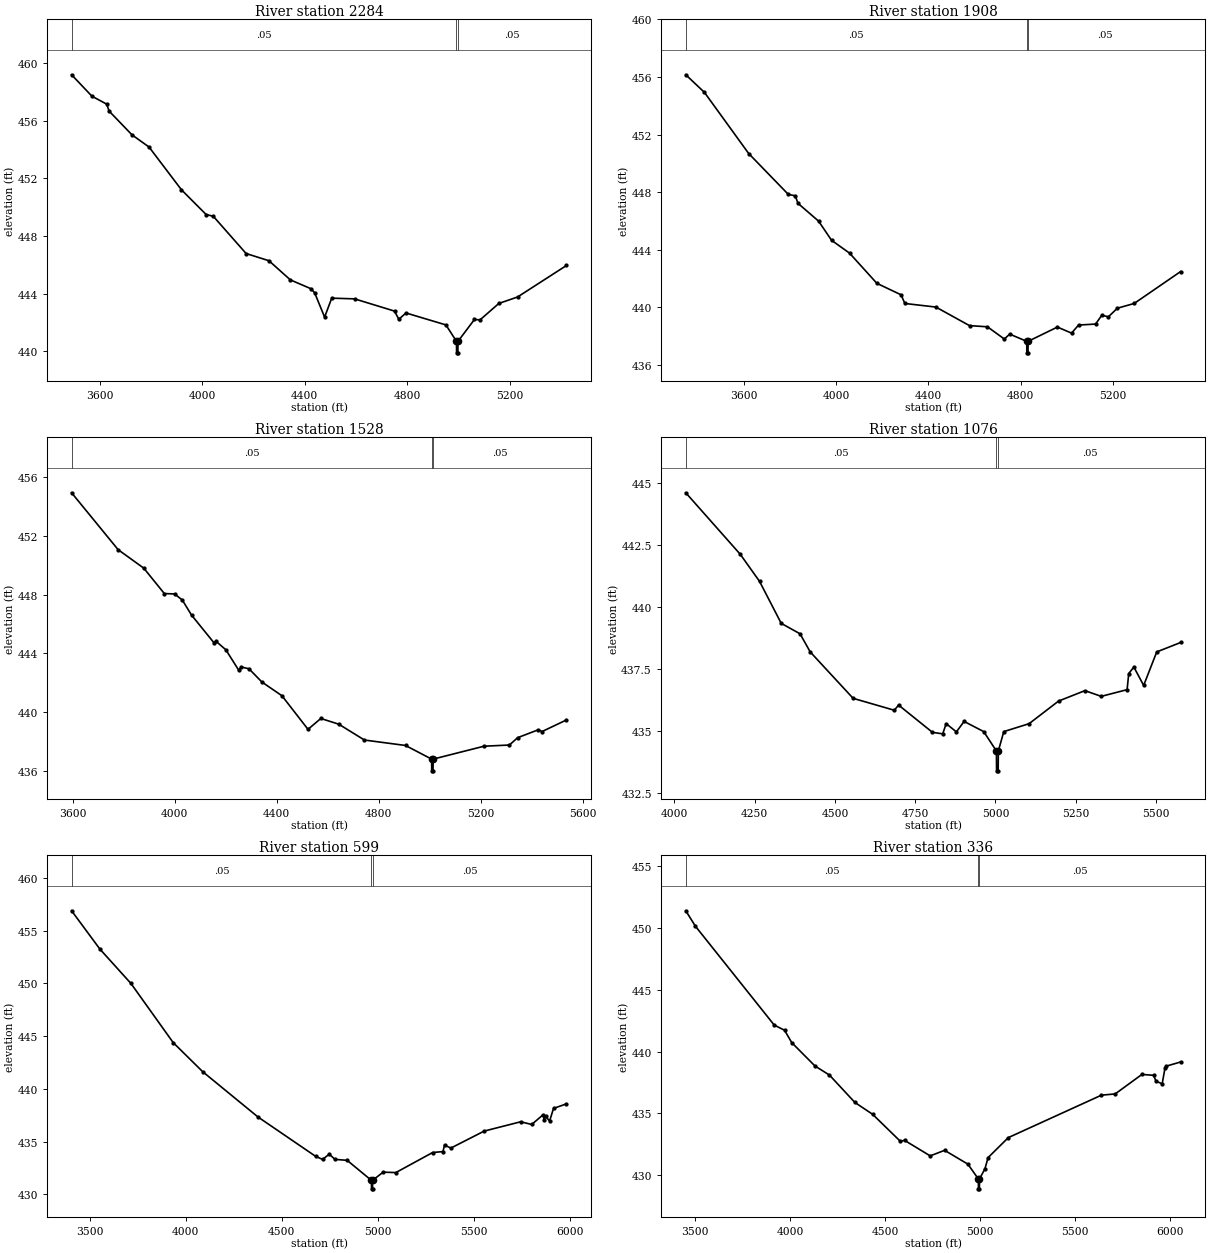
Type RM Length L Ch R = 1,2284,376,376,376
BEGIN DESCRIPTION:
UNT 129 in Lagunillas Cr Wtrshd 26.0
END DESCRIPTION:
XS GIS Cut Line= 3
      2057567.20     13479292.28      2056220.80     13479974.54
      2056342.38     13480377.81
#Sta/Elev= 30
  3490.6  459.20  3570.0  457.71  3627.6  457.16  3636.8  456.68  3725.9  455.03
  3792.7  454.18  3919.1  451.21  4015.4  449.49  4043.3  449.37  4171.4  446.78
  4260.4  446.28  4343.9  444.95  4423.6  444.34  4438.6  444.06  4477.6  442.36
  4505.4  443.68  4594.5  443.63  4750.4  442.78  4767.1  442.21  4795.0  442.65
  4950.9  441.82  4992.0  440.68  4992.5  439.88  4997.5  439.88  4998.0  440.68
  5062.2  442.20  5084.0  442.17  5157.2  443.31  5230.3  443.76  5421.2  445.95
#Mann=3,-1,0
  3490.6    0.05       0  4992.0    0.03       0  4998.0    0.05       0
Bank Sta=4992,4998
Exp/Cntr=0.3,0.1

Type RM Length L Ch R = 1,1908,380,380,380
BEGIN DESCRIPTION:
UNT 129 in Lagunillas Cr Wtrshd 24.0
END DESCRIPTION:
XS GIS Cut Line= 4
      2057404.91     13479325.70      2056004.13     13479514.33
      2055925.70     13479862.16      2056092.39     13480195.53
#Sta/Elev= 30
  3349.4  456.15  3430.0  454.93  3621.7  450.68  3793.3  447.84  3823.5  447.74
  3835.0  447.22  3924.5  445.98  3980.5  444.65  4058.3  443.76  4176.7  441.66
  4281.7  440.86  4297.8  440.26  4432.3  440.01  4577.9  438.72  4655.5  438.64
  4728.5  437.79  4751.9  438.13  4825.6  437.63  4826.1  436.83  4831.1  436.83
  4831.6  437.63  4958.3  438.62  5019.8  438.20  5049.9  438.76  5123.8  438.83
  5150.9  439.45  5178.9  439.33  5218.0  439.93  5290.7  440.26  5492.1  442.48
#Mann=3,-1,0
  3349.4    0.05       0  4825.6    0.03       0  4831.6    0.05       0
Bank Sta=4825.6,4831.6
Exp/Cntr=0.3,0.1

Type RM Length L Ch R = 1,1528,452,452,452
BEGIN DESCRIPTION:
UNT 129 in Lagunillas Cr Wtrshd 25.0
END DESCRIPTION:
XS GIS Cut Line= 3
      2057316.35     13479237.16      2055920.80     13479394.54
      2055834.55     13479924.16
#Sta/Elev= 30
  3595.6  454.94  3778.1  451.06  3878.7  449.80  3959.2  448.07  3999.5  448.04
  4029.7  447.63  4066.0  446.60  4155.9  444.67  4161.0  444.83  4200.8  444.23
  4251.1  442.84  4261.1  443.06  4291.3  442.94  4341.7  442.04  4420.6  441.10
  4522.8  438.81  4573.1  439.55  4643.6  439.16  4744.2  438.08  4905.2  437.71
  5007.6  436.78  5008.1  435.98  5013.1  435.98  5013.6  436.78  5213.2  437.66
  5312.8  437.74  5344.9  438.24  5426.0  438.78  5440.8  438.66  5536.6  439.45
#Mann=3,-1,0
  3595.6    0.05       0  5007.6    0.03       0  5013.6    0.05       0
Bank Sta=5007.6,5013.6
Exp/Cntr=0.3,0.1

Type RM Length L Ch R = 1,1076,477,477,477
BEGIN DESCRIPTION:
Mapping XS a2e50291
END DESCRIPTION:
XS GIS Cut Line= 6
      2056628.07     13478898.65      2056279.16     13478838.76
      2055930.20     13478950.74      2055672.39     13479044.49
      2055612.49     13479271.05      2055669.78     13479578.33
#Sta/Elev= 30
  4035.4  444.60  4205.3  442.12  4265.3  441.03  4332.8  439.34  4391.4  438.92
  4423.1  438.19  4556.8  436.32  4685.3  435.84  4698.3  436.05  4804.0  434.95
  4835.9  434.89  4846.7  435.30  4878.5  434.97  4902.6  435.39  4963.7  434.98
  5003.2  434.20  5003.7  433.40  5008.7  433.40  5009.2  434.20  5026.2  434.98
  5105.1  435.30  5196.8  436.21  5278.9  436.63  5329.8  436.40  5410.4  436.67
  5415.5  437.32  5431.5  437.58  5462.0  436.84  5502.7  438.19  5577.3  438.57
#Mann=3,-1,0
  4035.4    0.05       0  5003.2    0.03       0  5009.2    0.05       0
Bank Sta=5003.2,5009.2
Exp/Cntr=0.3,0.1

Type RM Length L Ch R = 1,599,263,263,263
BEGIN DESCRIPTION:
UNT 129 in Lagunillas Cr Wtrshd 22.0
END DESCRIPTION:
XS GIS Cut Line= 4
      2057101.81     13478515.68      2055559.28     13478639.21
      2055439.49     13478706.91      2055659.31     13479570.30
#Sta/Elev= 30
  3405.7  456.87  3553.0  453.24  3714.4  449.99  3934.2  444.39  4087.9  441.63
  4375.6  437.34  4676.6  433.60  4712.1  433.32  4746.8  433.81  4776.9  433.32
  4840.0  433.23  4966.5  431.33  4967.0  430.53  4972.0  430.53  4972.5  431.33
  5027.0  432.11  5093.4  432.07  5284.9  433.97  5338.8  434.06  5346.8  434.68
  5379.7  434.39  5553.2  436.00  5742.7  436.88  5800.8  436.63  5860.2  437.55
  5865.4  437.06  5873.0  437.40  5893.7  436.95  5914.3  438.15  5981.7  438.58
#Mann=3,-1,0
  3405.7    0.05       0  4966.5    0.03       0  4972.5    0.05       0
Bank Sta=4966.5,4972.5
Exp/Cntr=0.3,0.1

Type RM Length L Ch R = 1,336,236,236,236
BEGIN DESCRIPTION:
UNT 129 in Lagunillas Cr Wtrshd 21.0
END DESCRIPTION:
XS GIS Cut Line= 3
      2056702.50     13478048.07      2055280.80     13478664.54
      2055648.93     13479656.42
#Sta/Elev= 30
  3450.4  451.41  3501.1  450.16  3916.4  442.15  3970.9  441.73  4008.6  440.73
  4131.4  438.83  4207.3  438.10  4341.4  435.88  4434.8  434.92  4581.1  432.73
  4603.0  432.81  4738.3  431.55  4814.1  432.00  4936.9  430.88  4992.0  429.68
  4992.5  428.88  4997.5  428.88  4998.0  429.68  5026.8  430.51  5043.2  431.41
  5149.8  433.03  5640.5  436.47  5713.0  436.57  5853.8  438.15  5914.9  438.08
  5928.5  437.60  5960.5  437.39  5975.7  438.69  5981.8  438.82  6058.0  439.16
#Mann=3,-1,0
  3450.4    0.05       0  4992.0    0.03       0  4998.0    0.05       0
Bank Sta=4992,4998
Exp/Cntr=0.3,0.1

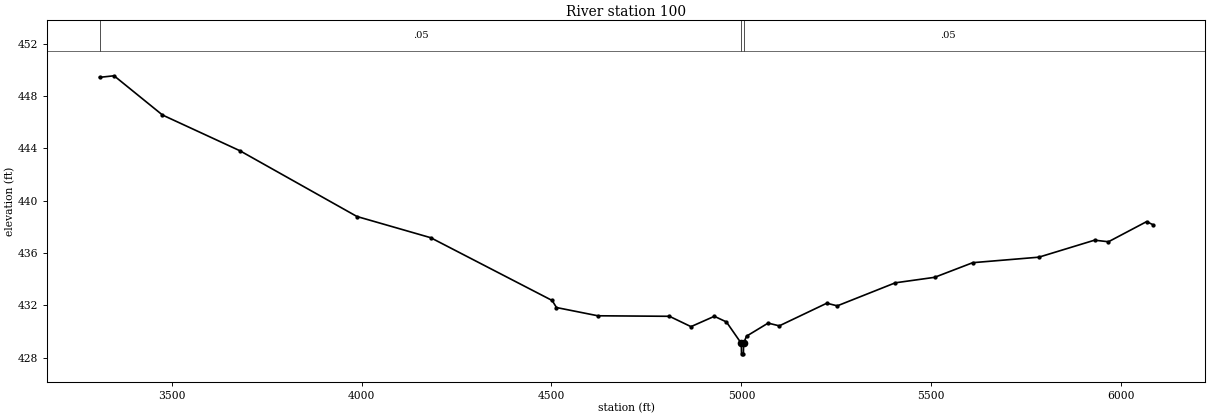
Type RM Length L Ch R = 1,100,0,0,0
BEGIN DESCRIPTION:
UNT 129 in Lagunillas Cr Wtrshd 20.0
END DESCRIPTION:
XS GIS Cut Line= 4
      2056545.30     13477814.12      2055090.67     13478491.67
      2055035.12     13478651.39      2055559.43     13479502.09
#Sta/Elev= 30
  3310.0  449.44  3348.3  449.56  3475.8  446.56  3679.5  443.83  3987.9  438.80
  4181.9  437.18  4501.7  432.38  4513.2  431.84  4622.1  431.21  4810.6  431.17
  4867.3  430.38  4928.8  431.17  4960.6  430.74  4999.8  429.10  5000.3  428.30
  5005.3  428.30  5005.8  429.10  5013.5  429.65  5070.3  430.65  5099.8  430.44
  5224.8  432.17  5252.5  431.97  5405.2  433.73  5508.7  434.15  5609.2  435.27
  5783.1  435.69  5929.8  436.99  5966.5  436.87  6067.0  438.41  6083.1  438.18
#Mann=3,-1,0
  3310.0    0.05       0  4999.8    0.03       0  5005.8    0.05       0
Bank Sta=4999.8,5005.8
Exp/Cntr=0.3,0.1

Chan Stop Cuts=-1