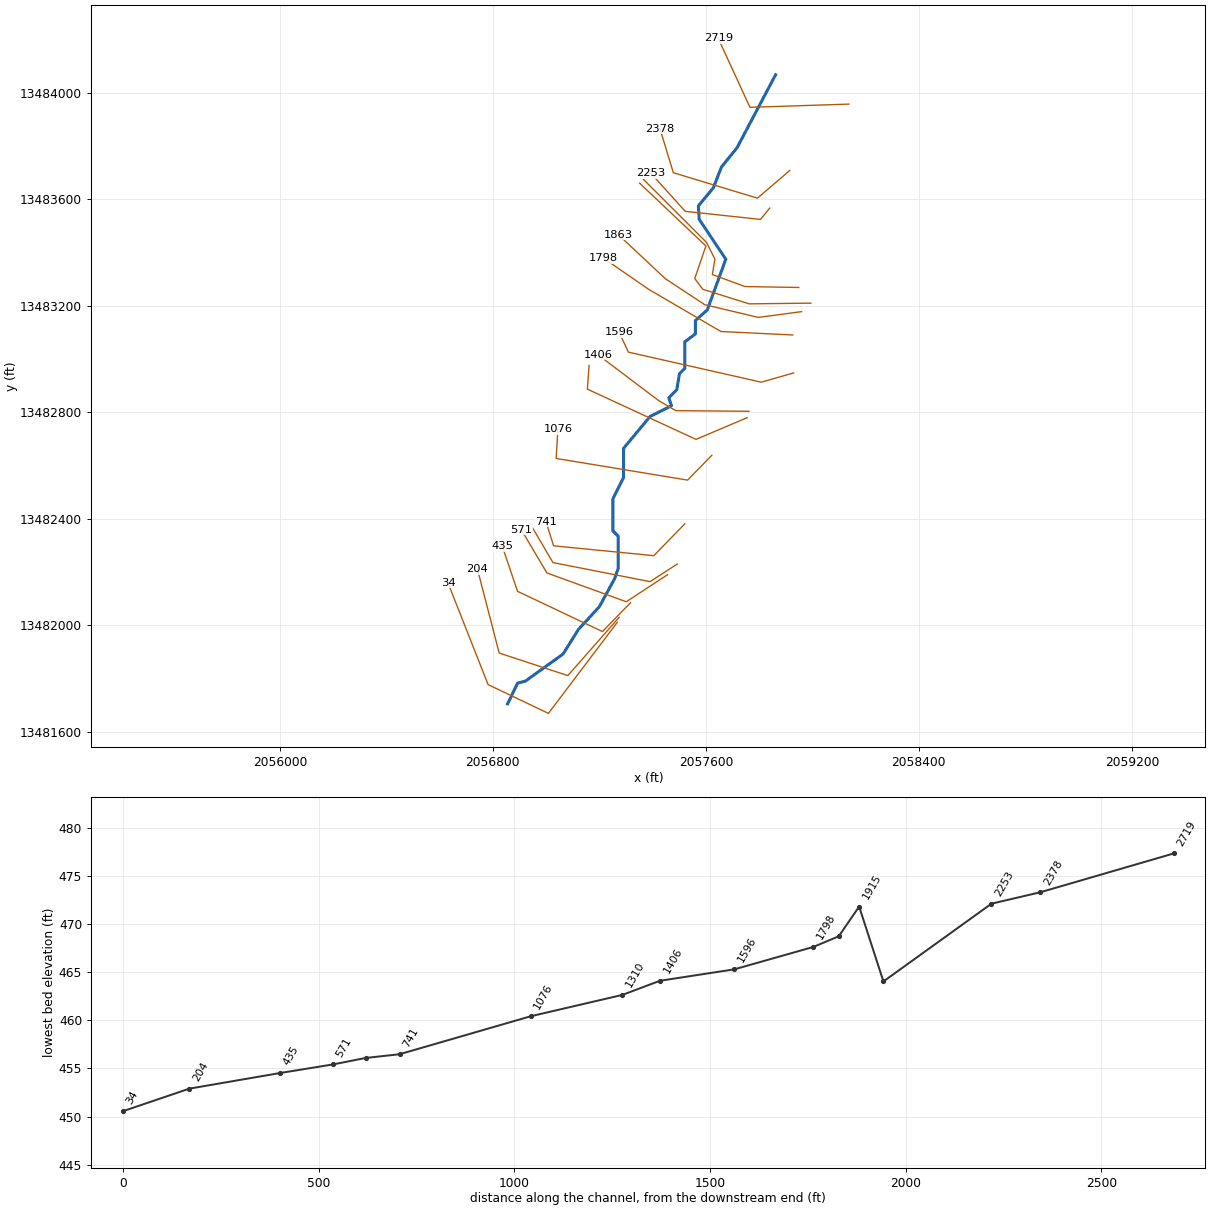
--- UNT 132 in Lagunillas Cr Wtrshd.prj (project) ---

Proj Title=UNT 132 in Lagunillas Cr Wtrshd Base Level Engineering
Current Plan=p01
Default Exp/Contr=0.3,0.1
English Units
Geom File=g01
Flow File=f01
Plan File=p01
BEGIN DESCRIPTION:
UNT 132 in Lagunillas Cr Wtrshd
END DESCRIPTION:

--- UNT 132 in Lagunillas Cr Wtrshd.p01 (plan) ---

Plan Title=Multiple Run
Short Identifier=Multiple
Geom File=g01
Flow File=f01
Subcritical Flow
K Sum by GR= 0
Std Step Tol= 0.01
Critical Tol= 0.01
Num of Std Step Trials= 20
Max Error Tol= 0.3
Flow Tol Ratio= 0.001
Split Flow NTrial= 30
Split Flow Tol= 0.02
Split Flow Ratio= 0.02
Log Output Level= 0
Friction Slope Method= 1
Unsteady Friction Slope Method= 2
Unsteady Bridges Friction Slope Method= 1
Parabolic Critical Depth
Global Vel Dist=  1 , 1 , 1
Global Log Level= 0
CheckData=True
Encroach Param= -1, 0, 0, 0
BEGIN DESCRIPTION:
Multiple Run
END DESCRIPTION:

--- UNT 132 in Lagunillas Cr Wtrshd.f01 (steady flow) ---

Flow Title=Multiple
Number of Profiles=7
Profile Names=10-year,25-year,50-year,1pct_min,100-year,1pct_plu,500-year
River Rch & RM= UNT 132 in Lagun,Reach-1,2719
      47      59      68      39      78     155     104
River Rch & RM= UNT 132 in Lagun,Reach-1,34
     134     179     215     129     256     512     371
Boundary for River Rch & Prof#=UNT 132 in Lagun,Reach-1,1
Up Type=0
Dn Type=3
Dn Slope=0.005
Boundary for River Rch & Prof#=UNT 132 in Lagun,Reach-1,2
Up Type=0
Dn Type=3
Dn Slope=0.005
Boundary for River Rch & Prof#=UNT 132 in Lagun,Reach-1,3
Up Type=0
Dn Type=3
Dn Slope=0.005
Boundary for River Rch & Prof#=UNT 132 in Lagun,Reach-1,4
Up Type=0
Dn Type=3
Dn Slope=0.005
Boundary for River Rch & Prof#=UNT 132 in Lagun,Reach-1,5
Up Type=0
Dn Type=3
Dn Slope=0.005
Boundary for River Rch & Prof#=UNT 132 in Lagun,Reach-1,6
Up Type=0
Dn Type=3
Dn Slope=0.005
Boundary for River Rch & Prof#=UNT 132 in Lagun,Reach-1,7
Up Type=0
Dn Type=3
Dn Slope=0.005

--- UNT 132 in Lagunillas Cr Wtrshd.g01 (geometry) ---

Geom Title=Existing Conditions

River Reach=UNT 132 in Lagun,Reach-1
Reach XY= 30
      2057862.05     13484067.93      2057717.21     13483793.64
      2057658.92     13483721.58      2057628.06     13483642.98
      2057571.90     13483575.23      2057575.00     13483525.00
      2057675.00     13483375.00      2057605.40     13483184.54
      2057560.80     13483144.54      2057560.80     13483094.54
      2057520.80     13483064.54      2057520.80     13482964.54
      2057500.80     13482944.54      2057490.80     13482884.54
      2057460.80     13482854.54      2057470.80     13482824.54
      2057390.80     13482784.54      2057290.80     13482664.54
      2057290.80     13482554.54      2057250.80     13482474.54
      2057250.80     13482354.54      2057270.80     13482334.54
      2057270.80     13482213.88      2057257.31     13482174.99
      2057200.02     13482069.96      2057121.89     13481984.89
      2057063.73     13481892.00      2056922.24     13481790.44
      2056892.72     13481782.63      2056855.40     13481704.54

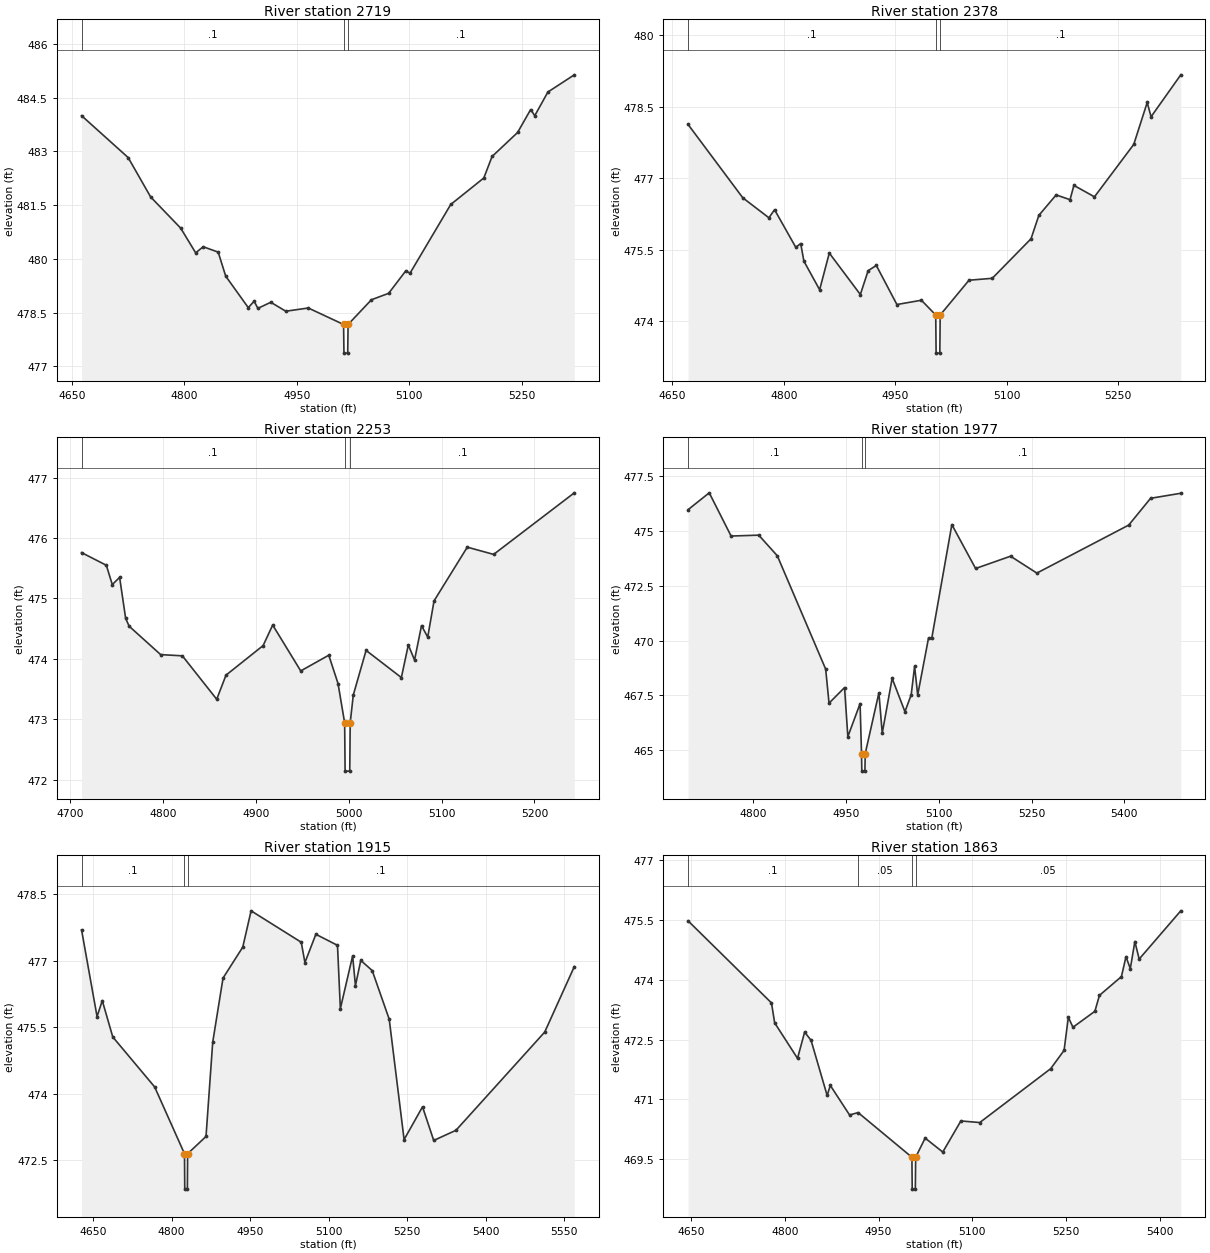
Type RM Length L Ch R = 1,2719,341,341,341
BEGIN DESCRIPTION:
UNT 132 in Lagunillas Cr Wtrshd 4.0
END DESCRIPTION:
XS GIS Cut Line= 3
      2058137.04     13483957.49      2057765.69     13483945.53
      2057646.47     13484204.58
#Sta/Elev= 30
  4663.1  484.00  4725.2  482.83  4755.2  481.73  4795.2  480.86  4815.2  480.17
  4825.2  480.34  4845.2  480.19  4855.2  479.52  4885.3  478.64  4893.1  478.82
  4898.1  478.62  4915.3  478.79  4935.3  478.54  4965.3  478.63  5012.3  478.17
  5012.8  477.37  5017.8  477.37  5018.3  478.17  5049.4  478.86  5072.4  479.04
  5095.3  479.67  5100.8  479.60  5155.1  481.52  5199.2  482.26  5210.2  482.86
  5244.2  483.53  5261.6  484.17  5267.1  484.00  5284.6  484.66  5319.8  485.14
#Mann=3,-1,0
  4663.1     0.1       0  5012.3    0.07       0  5018.3     0.1       0
Bank Sta=5012.3,5018.3
Exp/Cntr=0.3,0.1

Type RM Length L Ch R = 1,2378,125,125,125
BEGIN DESCRIPTION:
Mapping XS dcf6b8f6
END DESCRIPTION:
XS GIS Cut Line= 4
      2057915.41     13483708.48      2057793.87     13483604.30
      2057477.90     13483699.79      2057427.56     13483865.56
#Sta/Elev= 30
  4670.9  478.13  4744.6  476.59  4779.8  476.17  4787.4  476.34  4816.0  475.55
  4822.6  475.63  4826.9  475.26  4848.1  474.66  4861.1  475.43  4902.9  474.56
  4913.4  475.06  4924.4  475.17  4952.1  474.35  4985.1  474.44  5004.4  474.13
  5004.9  473.33  5009.9  473.33  5010.4  474.13  5049.2  474.86  5080.5  474.90
  5132.7  475.73  5143.2  476.22  5166.5  476.65  5185.2  476.55  5190.4  476.85
  5218.1  476.61  5271.0  477.71  5289.1  478.59  5294.3  478.29  5334.3  479.17
#Mann=3,-1,0
  4670.9     0.1       0  5004.4    0.07       0  5010.4     0.1       0
Bank Sta=5004.4,5010.4
Exp/Cntr=0.3,0.1

Type RM Length L Ch R = 1,2253,276,276,276
BEGIN DESCRIPTION:
Mapping XS 74f2fb13
END DESCRIPTION:
XS GIS Cut Line= 4
      2057839.88     13483566.97      2057805.16     13483524.44
      2057522.61     13483554.83      2057394.16     13483697.16
#Sta/Elev= 30
  4712.1  475.76  4738.8  475.55  4745.2  475.23  4753.1  475.35  4759.6  474.67
  4763.4  474.54  4797.3  474.07  4820.7  474.05  4857.7  473.33  4867.7  473.73
  4907.7  474.22  4918.0  474.56  4948.2  473.80  4978.4  474.06  4988.4  473.59
  4995.5  472.94  4996.0  472.14  5001.0  472.14  5001.5  472.94  5004.8  473.40
  5018.6  474.14  5056.6  473.69  5064.1  474.23  5070.8  473.98  5078.3  474.55
  5085.0  474.36  5091.8  474.96  5127.6  475.85  5156.0  475.73  5242.9  476.75
#Mann=3,-1,0
  4712.1     0.1       0  4995.5    0.07       0  5001.5     0.1       0
Bank Sta=4995.5,5001.5
Exp/Cntr=0.3,0.1

Type RM Length L Ch R = 1,1977,62,62,62
BEGIN DESCRIPTION:
Mapping XS 60a8ce3b
END DESCRIPTION:
XS GIS Cut Line= 6
      2057949.28     13483268.80      2057747.00     13483272.27
      2057624.60     13483317.41      2057633.98     13483375.28
      2057602.73     13483437.78      2057365.75     13483674.76
#Sta/Elev= 30
  4694.8  475.97  4729.1  476.74  4764.4  474.77  4809.1  474.81  4839.1  473.87
  4917.3  468.70  4922.7  467.15  4947.8  467.86  4953.1  465.62  4972.9  467.13
  4975.2  464.85  4975.7  464.05  4980.7  464.05  4981.2  464.85  5003.3  467.62
  5008.7  465.78  5024.7  468.28  5045.4  466.76  5055.5  467.53  5061.0  468.83
  5066.0  467.52  5083.5  470.12  5088.8  470.12  5121.2  475.29  5159.6  473.29
  5216.1  473.85  5258.6  473.08  5407.1  475.27  5442.4  476.49  5491.2  476.72
#Mann=3,-1,0
  4694.8     0.1       0  4975.2    0.07       0  4981.2     0.1       0
Bank Sta=4975.2,4981.2
Exp/Cntr=0.3,0.1

Type RM Length L Ch R = 1,1915,52,52,52
BEGIN DESCRIPTION:
Mapping XS 63a68910
END DESCRIPTION:
XS GIS Cut Line= 6
      2057994.62     13483209.92      2057762.88     13483207.32
      2057588.40     13483262.00      2057558.45     13483302.37
      2057600.12     13483424.76      2057351.07     13483660.84
#Sta/Elev= 30
  4628.0  477.70  4657.6  475.74  4667.6  476.10  4687.6  475.28  4767.6  474.15
  4824.6  472.64  4825.1  471.84  4830.1  471.84  4830.6  472.64  4865.7  473.03
  4878.5  475.16  4898.2  476.61  4935.9  477.31  4951.8  478.13  5047.6  477.42
  5054.6  476.96  5075.5  477.60  5116.8  477.35  5122.3  475.92  5145.7  477.11
  5151.1  476.44  5161.3  477.01  5183.1  476.78  5215.6  475.68  5244.0  472.96
  5279.2  473.70  5300.6  472.94  5343.1  473.17  5512.6  475.39  5569.1  476.87
#Mann=3,-1,0
  4628.0     0.1       0  4824.6    0.07       0  4830.6     0.1       0
Bank Sta=4824.6,4830.6
Exp/Cntr=0.3,0.1

Type RM Length L Ch R = 1,1863,65,65,65
BEGIN DESCRIPTION:
Mapping XS 30df4aa3
END DESCRIPTION:
XS GIS Cut Line= 5
      2057959.63     13483178.08      2057797.35     13483156.39
      2057595.96     13483204.13      2057448.39     13483301.35
      2057272.16     13483466.30
#Sta/Elev= 30
  4645.0  475.48  4778.6  473.42  4783.7  472.92  4820.3  472.03  4831.7  472.69
  4842.0  472.48  4867.7  471.10  4872.8  471.35  4903.6  470.61  4917.3  470.67
  5003.4  469.55  5003.9  468.75  5008.9  468.75  5009.4  469.55  5024.6  470.03
  5052.8  469.68  5081.8  470.46  5112.0  470.42  5225.5  471.77  5247.0  472.23
  5253.8  473.06  5261.2  472.81  5296.3  473.21  5303.6  473.61  5338.8  474.08
  5346.1  474.58  5353.0  474.28  5360.3  474.96  5367.2  474.52  5433.8  475.73
#Mann=4,-1,0
  4645.0     0.1       0  4917.3    0.05       0  5003.4    0.04       0
  5009.4    0.05       0
Bank Sta=5003.4,5009.4
Exp/Cntr=0.3,0.1

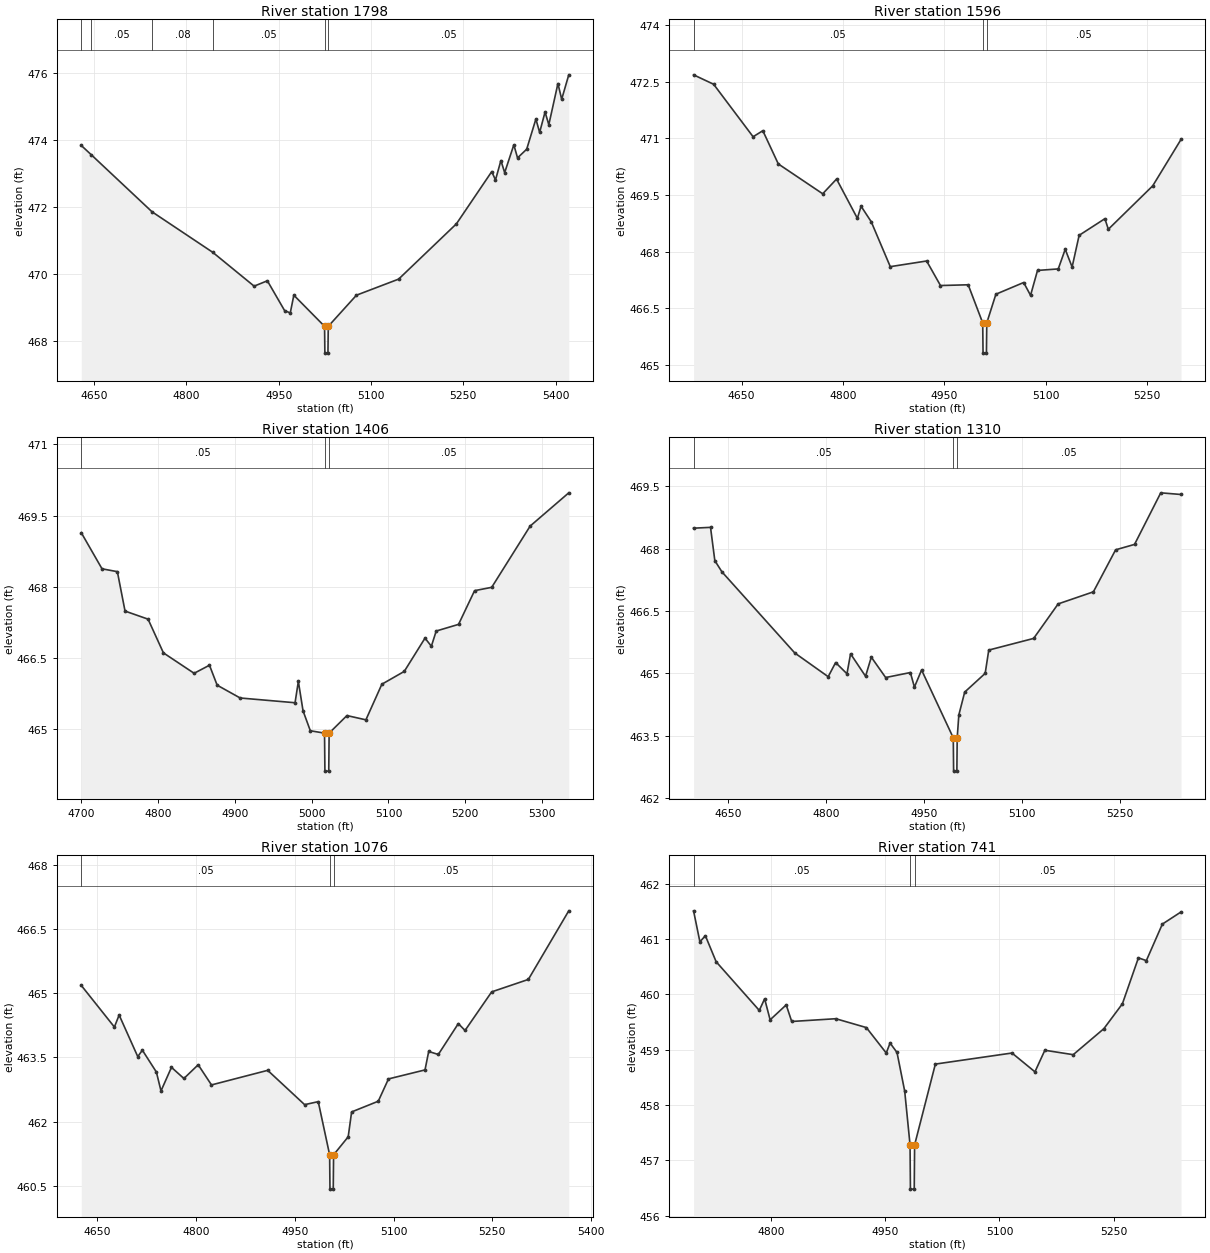
Type RM Length L Ch R = 1,1798,202,202,202
BEGIN DESCRIPTION:
Mapping XS 71c8e36a
END DESCRIPTION:
XS GIS Cut Line= 4
      2057926.72     13483090.41      2057656.72     13483103.44
      2057385.89     13483261.42      2057214.84     13483379.50
#Sta/Elev= 30
  4629.5  473.84  4645.9  473.56  4744.4  471.86  4843.0  470.65  4910.2  469.64
  4931.7  469.80  4959.7  468.91  4968.9  468.84  4974.7  469.37  5024.6  468.44
  5025.1  467.64  5030.1  467.64  5030.6  468.44  5076.4  469.37  5144.9  469.85
  5238.7  471.50  5296.1  473.06  5302.2  472.81  5311.0  473.39  5317.1  473.03
  5332.0  473.86  5338.0  473.47  5352.9  473.73  5367.8  474.63  5373.9  474.23
  5382.7  474.84  5388.8  474.46  5403.6  475.69  5409.7  475.22  5421.2  475.95
#Mann=6,-1,0
  4629.5    0.08       0  4645.9    0.05       0  4744.4    0.08       0
  4843.0    0.05       0  5024.6    0.04       0  5030.6    0.05       0
Bank Sta=5024.6,5030.6
Exp/Cntr=0.3,0.1

Type RM Length L Ch R = 1,1596,190,190,190
BEGIN DESCRIPTION:
Mapping XS 8b83f1ae
END DESCRIPTION:
XS GIS Cut Line= 4
      2057929.68     13482947.83      2057808.20     13482913.12
      2057309.06     13483025.96      2057273.95     13483101.52
#Sta/Elev= 30
  4579.0  472.68  4608.7  472.43  4667.1  471.04  4681.5  471.20  4704.4  470.32
  4770.1  469.53  4790.6  469.92  4821.4  468.88  4826.9  469.20  4841.9  468.79
  4870.1  467.60  4923.9  467.75  4944.4  467.10  4985.4  467.12  5006.9  466.11
  5007.4  465.31  5012.4  465.31  5012.9  466.11  5026.4  466.87  5067.5  467.18
  5077.7  466.84  5088.0  467.50  5118.7  467.54  5129.0  468.06  5139.2  467.59
  5149.6  468.43  5187.7  468.87  5192.8  468.59  5258.5  469.74  5300.4  470.97
#Mann=3,-1,0
  4579.0    0.05       0  5006.9    0.03       0  5012.9    0.05       0
Bank Sta=5006.9,5012.9
Exp/Cntr=0.3,0.1

Type RM Length L Ch R = 1,1406,96,96,96
BEGIN DESCRIPTION:
Mapping XS ecd302c2
END DESCRIPTION:
XS GIS Cut Line= 4
      2057761.96     13482803.79      2057487.29     13482806.10
      2057421.88     13482844.57      2057194.90     13483016.15
#Sta/Elev= 30
  4699.8  469.14  4726.8  468.38  4746.8  468.32  4756.8  467.49  4786.8  467.32
  4806.8  466.61  4846.8  466.18  4866.8  466.35  4876.8  465.93  4906.8  465.66
  4978.3  465.56  4982.6  466.01  4988.7  465.39  4998.2  464.97  5016.7  464.92
  5017.2  464.12  5022.2  464.12  5022.7  464.92  5045.9  465.29  5070.6  465.20
  5091.4  465.95  5120.6  466.22  5147.6  466.92  5155.9  466.75  5162.2  467.07
  5191.3  467.21  5212.2  467.92  5234.5  467.99  5284.6  469.28  5334.9  469.98
#Mann=3,-1,0
  4699.8    0.05       0  5016.7    0.03       0  5022.7    0.05       0
Bank Sta=5016.7,5022.7
Exp/Cntr=0.3,0.1

Type RM Length L Ch R = 1,1310,234,234,234
BEGIN DESCRIPTION:
Mapping XS 3d961eaa
END DESCRIPTION:
XS GIS Cut Line= 4
      2057755.06     13482779.67      2057562.97     13482698.27
      2057154.99     13482887.07      2057161.50     13482976.06
#Sta/Elev= 30
  4596.7  468.49  4622.7  468.51  4629.3  467.71  4640.2  467.44  4751.9  465.49
  4803.1  464.92  4814.5  465.26  4831.9  464.99  4837.4  465.47  4860.4  464.93
  4869.2  465.39  4891.2  464.90  4929.1  465.02  4935.3  464.67  4946.3  465.08
  4994.9  463.45  4995.4  462.65  5000.4  462.65  5000.9  463.45  5003.4  464.00
  5012.4  464.55  5043.8  465.00  5049.3  465.56  5118.1  465.84  5155.7  466.67
  5209.7  466.96  5243.8  467.97  5272.8  468.10  5313.0  469.34  5344.1  469.30
#Mann=3,-1,0
  4596.7    0.05       0  4994.9    0.03       0  5000.9    0.05       0
Bank Sta=4994.9,5000.9
Exp/Cntr=0.3,0.1

Type RM Length L Ch R = 1,1076,335,335,335
BEGIN DESCRIPTION:
Mapping XS 585676af
END DESCRIPTION:
XS GIS Cut Line= 4
      2057622.65     13482638.60      2057531.50     13482545.28
      2057037.80     13482626.66      2057044.31     13482736.25
#Sta/Elev= 30
  4625.6  465.18  4675.9  464.21  4683.1  464.49  4711.4  463.52  4718.4  463.67
  4739.7  463.16  4746.7  462.72  4762.6  463.27  4781.5  463.01  4803.2  463.33
  4823.4  462.86  4908.8  463.20  4964.9  462.40  4985.6  462.47  5002.9  461.23
  5003.4  460.43  5008.4  460.43  5008.9  461.23  5031.1  461.65  5036.3  462.23
  5076.8  462.48  5092.3  463.00  5147.8  463.21  5153.4  463.64  5168.0  463.57
  5198.4  464.29  5208.6  464.13  5249.1  465.03  5304.8  465.32  5366.2  466.92
#Mann=3,-1,0
  4625.6    0.05       0  5002.9    0.03       0  5008.9    0.05       0
Bank Sta=5002.9,5008.9
Exp/Cntr=0.3,0.1

Type RM Length L Ch R = 1,741,87,87,87
BEGIN DESCRIPTION:
Mapping XS 3db27091
END DESCRIPTION:
XS GIS Cut Line= 4
      2057520.92     13482380.98      2057404.67     13482261.52
      2057028.15     13482298.42      2056999.96     13482388.39
#Sta/Elev= 30
  4698.8  461.51  4707.1  460.95  4714.3  461.06  4728.4  460.59  4785.0  459.71
  4792.0  459.92  4799.2  459.54  4820.3  459.81  4827.5  459.51  4885.3  459.56
  4925.4  459.40  4951.5  458.94  4956.5  459.12  4965.6  458.95  4975.7  458.25
  4982.7  457.28  4983.2  456.48  4988.2  456.48  4988.7  457.28  5015.9  458.74
  5116.4  458.94  5146.5  458.60  5159.5  458.99  5196.7  458.91  5236.9  459.38
  5261.2  459.83  5282.2  460.66  5292.6  460.61  5313.6  461.27  5338.1  461.49
#Mann=3,-1,0
  4698.8    0.05       0  4982.7    0.03       0  4988.7    0.05       0
Bank Sta=4982.7,4988.7
Exp/Cntr=0.3,0.1

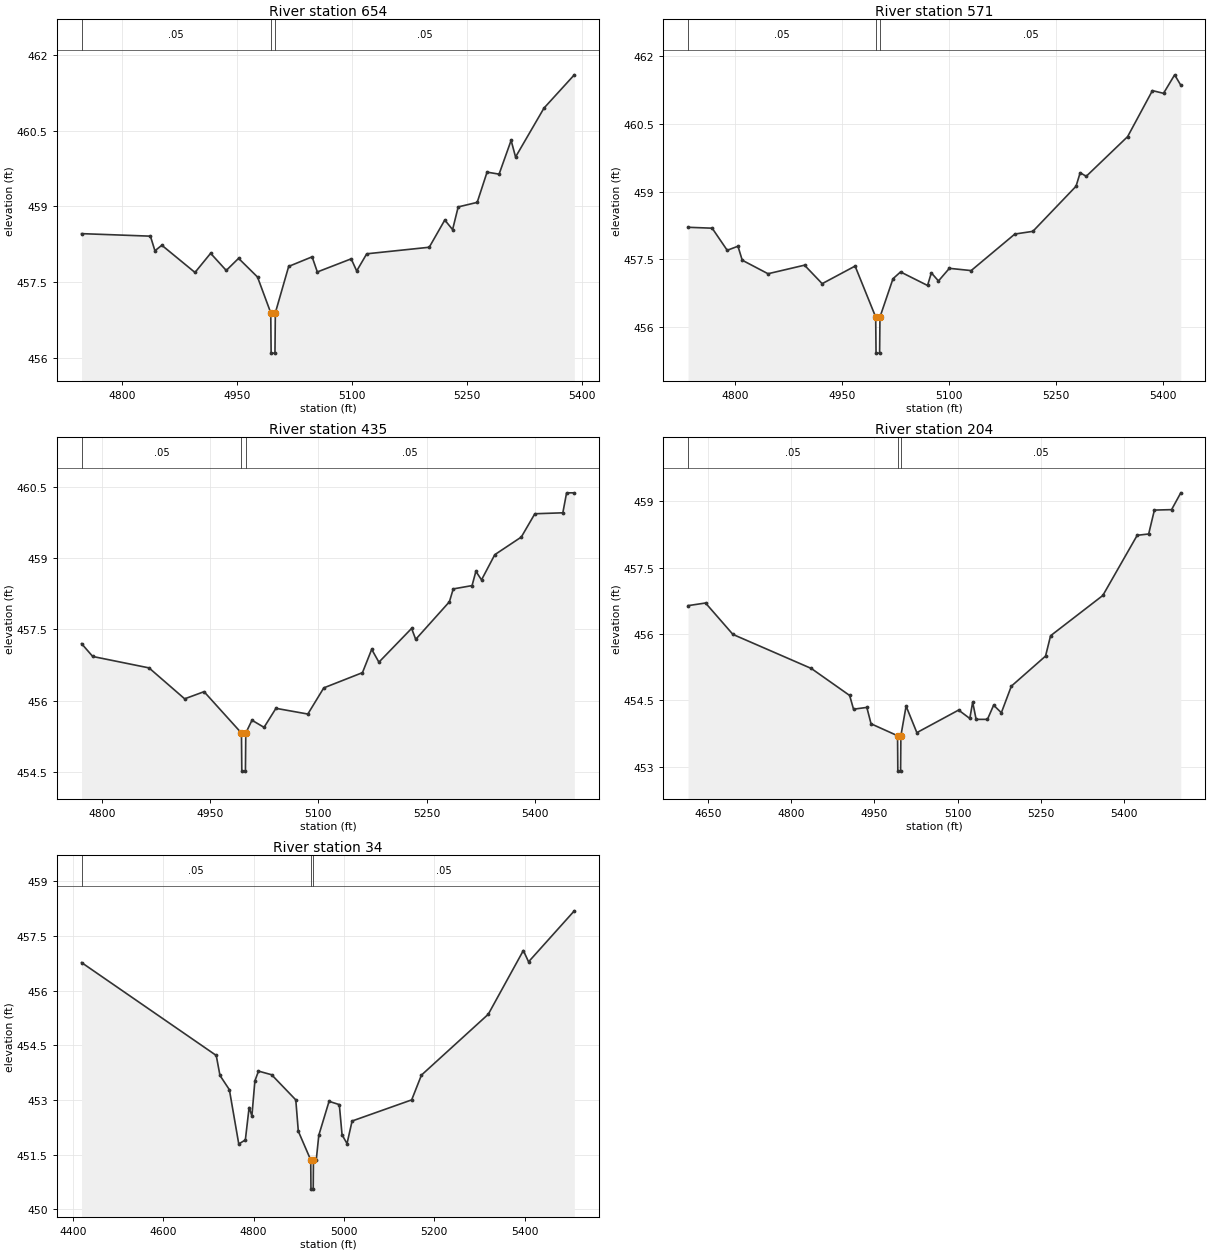
Type RM Length L Ch R = 1,654,83,83,83
BEGIN DESCRIPTION:
Mapping XS 60b43c26
END DESCRIPTION:
XS GIS Cut Line= 4
      2057493.08     13482230.31      2057390.25     13482163.93
      2057025.67     13482235.54      2056950.17     13482364.40
#Sta/Elev= 30
  4747.1  458.46  4837.0  458.41  4842.9  458.12  4851.9  458.23  4895.2  457.69
  4915.6  458.07  4936.0  457.73  4952.1  457.97  4976.8  457.60  4994.1  456.89
  4994.6  456.09  4999.6  456.09  5000.1  456.89  5017.5  457.81  5048.1  458.00
  5054.9  457.70  5099.1  457.96  5106.3  457.72  5119.4  458.06  5201.0  458.19
  5221.3  458.73  5231.5  458.54  5238.8  458.99  5263.6  459.08  5276.5  459.68
  5292.2  459.64  5307.9  460.31  5313.7  459.98  5350.8  460.95  5390.4  461.61
#Mann=3,-1,0
  4747.1    0.05       0  4994.1    0.03       0  5000.1    0.05       0
Bank Sta=4994.1,5000.1
Exp/Cntr=0.3,0.1

Type RM Length L Ch R = 1,571,136,136,136
BEGIN DESCRIPTION:
Mapping XS f661f531
END DESCRIPTION:
XS GIS Cut Line= 4
      2057456.26     13482189.99      2057301.27     13482088.40
      2057003.10     13482196.48      2056906.75     13482359.23
#Sta/Elev= 30
  4733.7  458.21  4767.6  458.19  4788.7  457.70  4803.8  457.79  4809.8  457.48
  4846.0  457.18  4897.2  457.37  4922.0  456.96  4968.2  457.35  4997.1  456.22
  4997.6  455.42  5002.6  455.42  5003.1  456.22  5021.4  457.07  5032.0  457.22
  5069.9  456.92  5075.2  457.20  5085.2  457.02  5100.5  457.30  5131.1  457.25
  5192.4  458.06  5217.7  458.12  5278.3  459.12  5284.1  459.42  5292.6  459.34
  5350.7  460.22  5385.5  461.24  5401.1  461.18  5416.7  461.59  5425.3  461.36
#Mann=3,-1,0
  4733.7    0.05       0  4997.1    0.03       0  5003.1    0.05       0
Bank Sta=4997.1,5003.1
Exp/Cntr=0.3,0.1

Type RM Length L Ch R = 1,435,231,231,231
BEGIN DESCRIPTION:
Mapping XS 2b348de3
END DESCRIPTION:
XS GIS Cut Line= 4
      2057317.18     13482084.91      2057211.76     13481976.47
      2056892.75     13482127.51      2056835.46     13482296.78
#Sta/Elev= 30
  4771.9  457.20  4787.4  456.93  4865.4  456.69  4914.8  456.04  4941.7  456.19
  4993.5  455.32  4994.0  454.52  4999.0  454.52  4999.5  455.32  5008.1  455.59
  5024.8  455.44  5041.3  455.84  5085.5  455.72  5107.6  456.27  5161.2  456.59
  5174.0  457.08  5184.0  456.81  5229.3  457.52  5235.0  457.29  5281.7  458.08
  5287.0  458.35  5313.1  458.42  5318.4  458.72  5326.2  458.54  5344.6  459.07
  5381.3  459.44  5400.1  459.93  5438.9  459.95  5444.1  460.37  5454.8  460.37
#Mann=3,-1,0
  4771.9    0.05       0  4993.5    0.03       0  4999.5    0.05       0
Bank Sta=4993.5,4999.5
Exp/Cntr=0.3,0.1

Type RM Length L Ch R = 1,204,170,170,170
BEGIN DESCRIPTION:
Mapping XS 6cbe0a95
END DESCRIPTION:
XS GIS Cut Line= 4
      2057274.37     13482029.82      2057081.66     13481811.06
      2056823.84     13481895.70      2056742.08     13482211.08
#Sta/Elev= 30
  4613.8  456.64  4645.4  456.70  4694.8  455.99  4836.2  455.22  4905.3  454.61
  4912.3  454.30  4936.3  454.34  4943.9  453.97  4991.7  453.70  4992.2  452.90
  4997.2  452.90  4997.7  453.70  5007.1  454.37  5026.5  453.77  5101.8  454.28
  5122.0  454.09  5127.2  454.46  5133.4  454.07  5153.8  454.07  5165.0  454.39
  5178.9  454.22  5196.9  454.82  5258.6  455.50  5267.7  455.96  5361.9  456.87
  5423.9  458.23  5444.6  458.26  5454.9  458.80  5485.9  458.81  5502.5  459.19
#Mann=3,-1,0
  4613.8    0.05       0  4991.7    0.03       0  4997.7    0.05       0
Bank Sta=4991.7,4997.7
Exp/Cntr=0.3,0.1

Type RM Length L Ch R = 1,34,0,0,0
BEGIN DESCRIPTION:
UNT 132 in Lagunillas Cr Wtrshd 11.0
END DESCRIPTION:
XS GIS Cut Line= 4
      2057267.43     13482011.17      2057008.74     13481669.13
      2056782.18     13481777.21      2056631.14     13482160.02
#Sta/Elev= 30
  4418.9  456.77  4717.2  454.22  4725.5  453.67  4746.3  453.28  4767.1  451.79
  4781.7  451.90  4790.0  452.79  4796.2  452.56  4802.8  453.52  4810.8  453.79
  4839.9  453.69  4893.4  453.00  4899.0  452.14  4926.5  451.35  4927.0  450.55
  4932.0  450.55  4932.5  451.35  4938.8  451.36  4944.4  452.03  4967.1  452.96
  4989.8  452.87  4995.9  452.04  5006.9  451.80  5018.1  452.42  5150.1  453.00
  5171.7  453.68  5319.7  455.35  5397.4  457.10  5409.0  456.79  5510.3  458.19
#Mann=3,-1,0
  4418.9    0.05       0  4926.5    0.03       0  4932.5    0.05       0
Bank Sta=4926.5,4932.5
Exp/Cntr=0.3,0.1

Chan Stop Cuts=-1