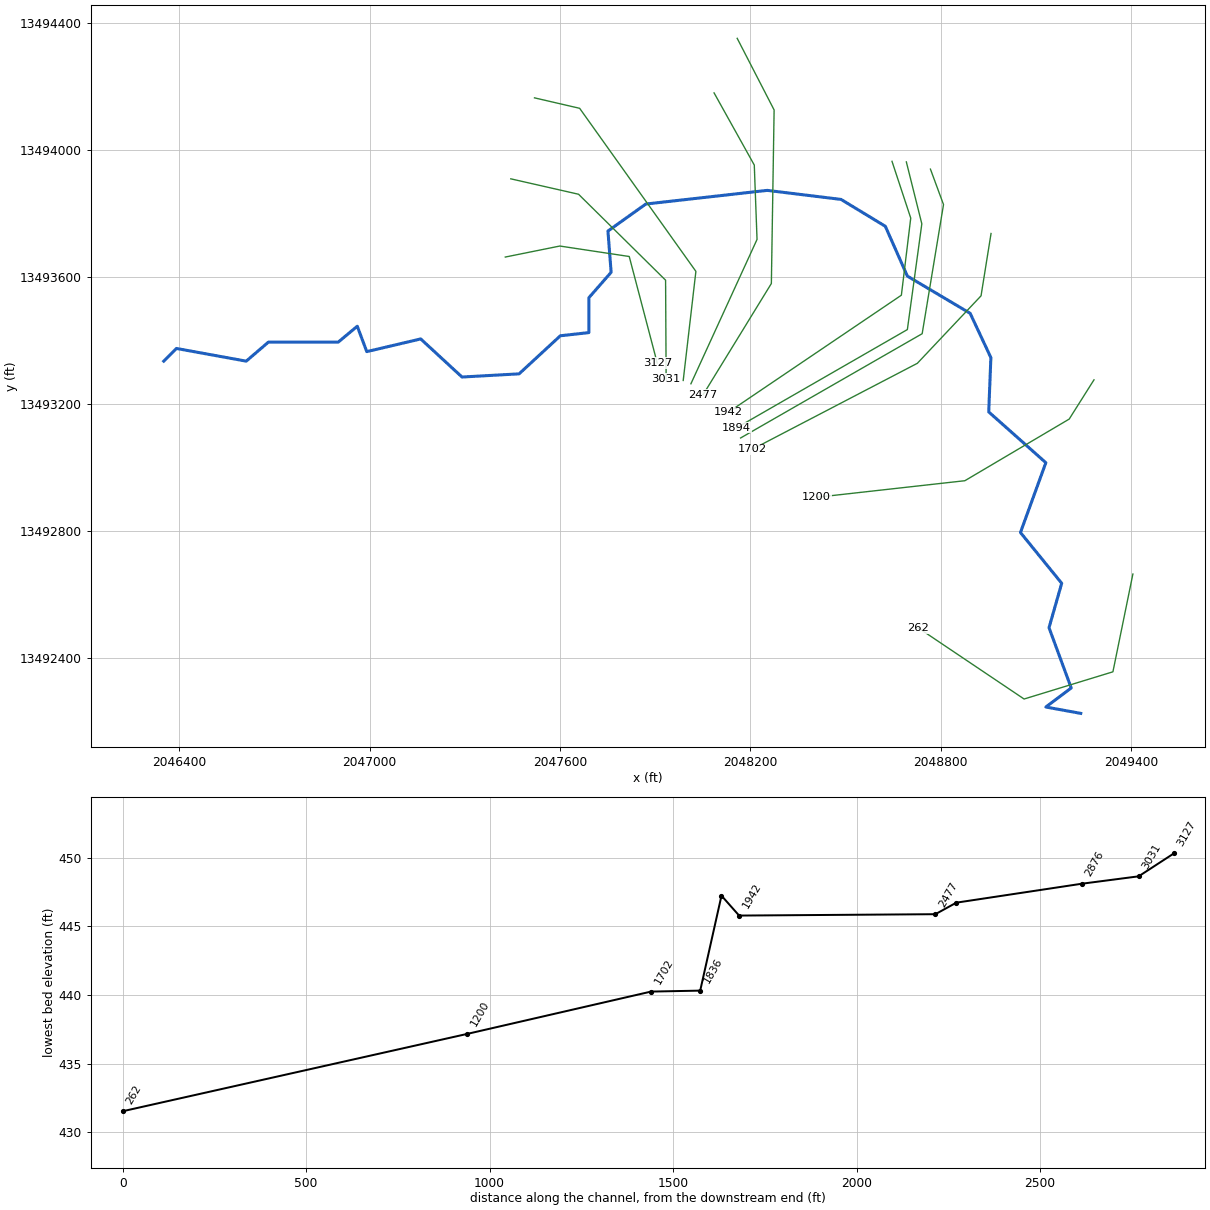
--- UNT 134 in Lagunillas Cr Wtrshd.prj (project) ---

Proj Title=UNT 134 in Lagunillas Cr Wtrshd Base Level Engineering
Current Plan=p01
Default Exp/Contr=0.3,0.1
English Units
Geom File=g01
Flow File=f01
Plan File=p01
BEGIN DESCRIPTION:
UNT 134 in Lagunillas Cr Wtrshd
END DESCRIPTION:

--- UNT 134 in Lagunillas Cr Wtrshd.p01 (plan) ---

Plan Title=Multiple Run
Short Identifier=Multiple
Geom File=g01
Flow File=f01
Subcritical Flow
K Sum by GR= 0
Std Step Tol= 0.01
Critical Tol= 0.01
Num of Std Step Trials= 20
Max Error Tol= 0.3
Flow Tol Ratio= 0.001
Split Flow NTrial= 30
Split Flow Tol= 0.02
Split Flow Ratio= 0.02
Log Output Level= 0
Friction Slope Method= 1
Unsteady Friction Slope Method= 2
Unsteady Bridges Friction Slope Method= 1
Parabolic Critical Depth
Global Vel Dist=  1 , 1 , 1
Global Log Level= 0
CheckData=True
Encroach Param= -1, 0, 0, 0
BEGIN DESCRIPTION:
Multiple Run
END DESCRIPTION:

--- UNT 134 in Lagunillas Cr Wtrshd.f01 (steady flow) ---

Flow Title=Multiple
Number of Profiles=7
Profile Names=10-year,25-year,50-year,1pct_min,100-year,1pct_plu,500-year
River Rch & RM= UNT 134 in Lagun,Reach-1,3127
     139     187     225     136     270     540     396
River Rch & RM= UNT 134 in Lagun,Reach-1,2876
     155     209     253     153     304     607     448
Boundary for River Rch & Prof#=UNT 134 in Lagun,Reach-1,1
Up Type=0
Dn Type=3
Dn Slope=0.005
Boundary for River Rch & Prof#=UNT 134 in Lagun,Reach-1,2
Up Type=0
Dn Type=3
Dn Slope=0.005
Boundary for River Rch & Prof#=UNT 134 in Lagun,Reach-1,3
Up Type=0
Dn Type=3
Dn Slope=0.005
Boundary for River Rch & Prof#=UNT 134 in Lagun,Reach-1,4
Up Type=0
Dn Type=3
Dn Slope=0.005
Boundary for River Rch & Prof#=UNT 134 in Lagun,Reach-1,5
Up Type=0
Dn Type=3
Dn Slope=0.005
Boundary for River Rch & Prof#=UNT 134 in Lagun,Reach-1,6
Up Type=0
Dn Type=3
Dn Slope=0.005
Boundary for River Rch & Prof#=UNT 134 in Lagun,Reach-1,7
Up Type=0
Dn Type=3
Dn Slope=0.005

--- UNT 134 in Lagunillas Cr Wtrshd.g01 (geometry) ---

Geom Title=Existing Conditions

River Reach=UNT 134 in Lagun,Reach-1
Reach XY= 30
      2046350.80     13493334.54      2046390.80     13493374.54
      2046610.80     13493334.54      2046680.80     13493394.54
      2046900.80     13493394.54      2046960.80     13493444.54
      2046990.80     13493364.54      2047160.80     13493404.54
      2047290.80     13493284.54      2047470.80     13493294.54
      2047600.80     13493414.54      2047690.80     13493424.54
      2047690.80     13493534.54      2047760.80     13493614.54
      2047750.80     13493744.54      2047870.10     13493829.66
      2048252.74     13493872.72      2048485.38     13493844.25
      2048624.96     13493759.53      2048694.40     13493602.58
      2048892.32     13493485.22      2048957.60     13493345.64
      2048950.80     13493174.54      2049130.80     13493014.54
      2049050.80     13492794.54      2049180.80     13492634.54
      2049140.80     13492494.54      2049210.80     13492304.54
      2049130.80     13492244.54      2049240.80     13492224.54

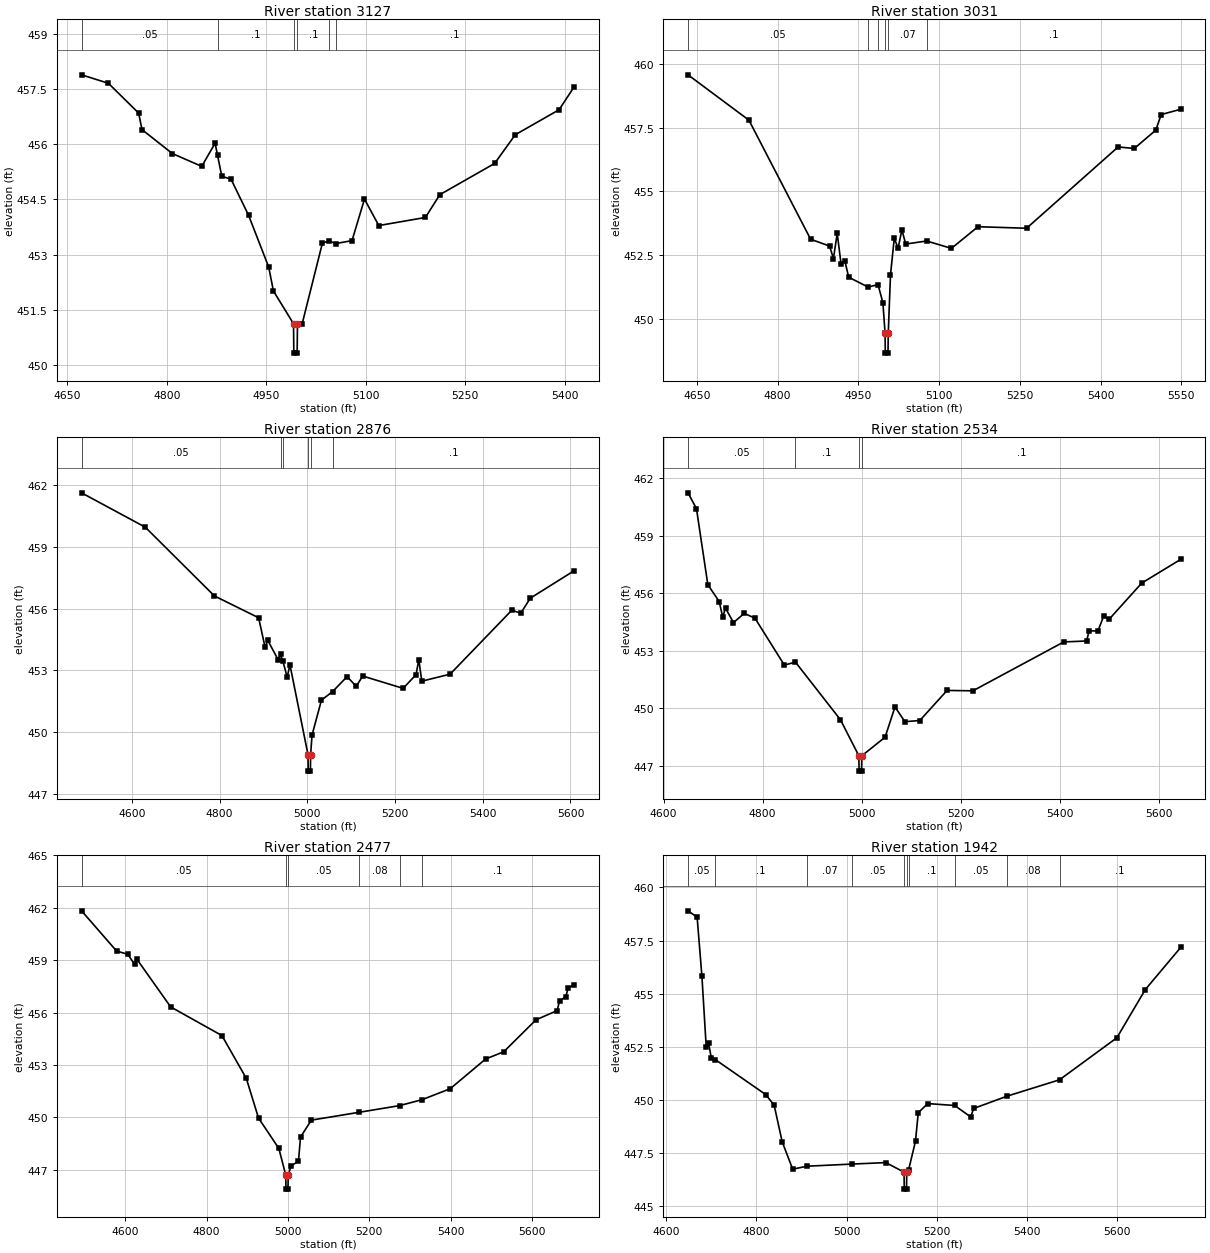
Type RM Length L Ch R = 1,3127,96,96,96
BEGIN DESCRIPTION:
Mapping XS 78a22319
END DESCRIPTION:
XS GIS Cut Line= 4
      2047427.28     13493662.60      2047599.14     13493697.32
      2047817.89     13493664.34      2047906.10     13493328.79
#Sta/Elev= 30
  4671.3  457.89  4711.8  457.66  4757.4  456.85  4762.5  456.40  4808.2  455.75
  4852.6  455.40  4872.8  456.03  4876.5  455.70  4882.9  455.13  4896.9  455.05
  4923.3  454.07  4953.7  452.66  4960.8  452.01  4991.1  451.12  4991.6  450.32
  4996.6  450.32  4997.1  451.12  5004.2  451.12  5034.8  453.32  5045.2  453.37
  5054.8  453.30  5079.4  453.38  5098.2  454.51  5119.8  453.79  5190.1  454.01
  5211.9  454.63  5294.6  455.48  5325.7  456.26  5391.8  456.94  5414.8  457.57
#Mann=6,-1,0
  4671.3    0.05       0  4876.5     0.1       0  4991.1    0.07       0
  4997.1     0.1       0  5045.2    0.07       0  5054.8     0.1       0
Bank Sta=4991.1,4997.1
Exp/Cntr=0.3,0.1

Type RM Length L Ch R = 1,3031,155,155,155
BEGIN DESCRIPTION:
Mapping XS 6078f5a1
END DESCRIPTION:
XS GIS Cut Line= 4
      2047444.64     13493909.12      2047658.17     13493860.52
      2047932.47     13493589.68      2047934.20     13493278.55
#Sta/Elev= 30
  4633.5  459.57  4746.7  457.79  4861.3  453.12  4896.6  452.85  4903.7  452.36
  4910.7  453.35  4917.8  452.16  4924.9  452.27  4932.0  451.63  4968.2  451.24
  4986.5  451.34  4995.6  450.63  4999.6  449.45  5000.1  448.65  5005.1  448.65
  5005.6  449.45  5009.7  451.72  5016.7  453.15  5023.9  452.77  5030.9  453.49
  5038.0  452.93  5077.0  453.05  5122.9  452.76  5172.3  453.61  5262.6  453.55
  5432.7  456.74  5462.7  456.68  5502.7  457.40  5512.7  458.01  5549.1  458.22
#Mann=6,-1,0
  4633.5    0.05       0  4968.2     0.1       0  4986.5    0.07       0
  4999.6    0.07       0  5005.6    0.07       0  5077.0     0.1       0
Bank Sta=4999.6,5005.6
Exp/Cntr=0.3,0.1

Type RM Length L Ch R = 1,2876,342,342,342
BEGIN DESCRIPTION:
Mapping XS a7a0241c
END DESCRIPTION:
XS GIS Cut Line= 4
      2047519.30     13494164.33      2047661.64     13494131.35
      2048027.96     13493617.46      2047988.02     13493273.67
#Sta/Elev= 30
  4485.5  461.63  4630.8  459.96  4788.4  456.62  4889.2  455.56  4903.9  454.12
  4910.1  454.46  4933.4  453.53  4939.1  453.78  4944.5  453.45  4954.3  452.67
  4960.5  453.28  5001.7  448.91  5002.2  448.11  5007.2  448.11  5007.7  448.91
  5010.9  449.86  5032.4  451.56  5057.6  451.97  5090.8  452.70  5111.7  452.23
  5126.4  452.73  5218.6  452.13  5248.1  452.80  5254.3  453.53  5261.1  452.48
  5325.6  452.82  5466.5  455.93  5486.7  455.78  5508.4  456.51  5608.8  457.85
#Mann=6,-1,0
  4485.5    0.05       0  4939.1     0.1       0  4944.5    0.12       0
  5001.7    0.07       0  5007.7    0.12       0  5057.6     0.1       0
Bank Sta=5001.7,5007.7
Exp/Cntr=0.3,0.1

Type RM Length L Ch R = 1,2534,57,57,57
BEGIN DESCRIPTION:
Mapping XS 9f6a3ee8
END DESCRIPTION:
XS GIS Cut Line= 4
      2048085.24     13494179.98      2048211.99     13493952.53
      2048220.67     13493718.16      2048012.34     13493263.31
#Sta/Elev= 30
  4649.5  461.25  4666.6  460.42  4689.5  456.46  4712.4  455.58  4719.5  454.78
  4725.3  455.23  4741.3  454.48  4763.0  454.96  4784.7  454.71  4844.1  452.26
  4866.4  452.42  4957.4  449.41  4994.5  447.53  4995.0  446.73  5000.0  446.73
  5000.5  447.53  5047.5  448.50  5067.5  450.08  5087.5  449.31  5117.6  449.37
  5172.7  450.94  5224.9  450.92  5408.3  453.47  5454.3  453.52  5459.8  454.05
  5477.3  454.04  5488.9  454.81  5499.9  454.65  5565.8  456.54  5644.7  457.78
#Mann=4,-1,0
  4649.5    0.05       0  4866.4     0.1       0  4994.5    0.07       0
  5000.5     0.1       0
Bank Sta=4994.5,5000.5
Exp/Cntr=0.3,0.1

Type RM Length L Ch R = 1,2477,535,535,535
BEGIN DESCRIPTION:
Mapping XS a1d3d990
END DESCRIPTION:
XS GIS Cut Line= 4
      2048158.15     13494351.87      2048274.49     13494126.14
      2048265.81     13493579.27      2048050.94     13493229.24
#Sta/Elev= 30
  4492.6  461.82  4578.7  459.52  4606.5  459.33  4623.0  458.75  4628.7  459.05
  4711.7  456.32  4837.7  454.68  4897.7  452.23  4927.7  449.96  4977.7  448.22
  4994.7  446.69  4995.2  445.89  5000.2  445.89  5000.7  446.69  5007.7  447.22
  5026.0  447.49  5031.0  448.87  5057.7  449.84  5175.7  450.29  5274.4  450.67
  5330.0  451.01  5399.2  451.64  5486.2  453.34  5530.6  453.75  5609.9  455.58
  5662.1  456.11  5667.9  456.67  5683.4  456.90  5689.2  457.43  5704.2  457.57
#Mann=6,-1,0
  4492.6    0.05       0  4994.7    0.04       0  5000.7    0.05       0
  5175.7    0.08       0  5274.4    0.05       0  5330.0     0.1       0
Bank Sta=4994.7,5000.7
Exp/Cntr=0.3,0.1

Type RM Length L Ch R = 1,1942,48,48,48
BEGIN DESCRIPTION:
Mapping XS 08dd6612
END DESCRIPTION:
XS GIS Cut Line= 4
      2048646.03     13493964.21      2048705.04     13493785.43
      2048675.53     13493542.37      2048129.25     13493172.90
#Sta/Elev= 30
  4648.2  458.90  4668.4  458.60  4679.0  455.82  4688.5  452.50  4693.8  452.67
  4700.0  451.95  4708.8  451.89  4820.8  450.24  4839.2  449.74  4857.0  448.02
  4880.3  446.73  4912.0  446.87  5011.8  446.97  5086.8  447.04  5127.2  446.59
  5127.7  445.79  5132.7  445.79  5133.2  446.59  5137.1  446.68  5152.6  448.05
  5158.7  449.39  5179.7  449.82  5239.4  449.73  5275.1  449.19  5281.5  449.59
  5355.7  450.17  5471.9  450.94  5599.1  452.92  5662.1  455.19  5740.8  457.18
#Mann=10,-1,0
  4648.2    0.05       0  4708.8     0.1       0  4912.0    0.07       0
  5011.8    0.05       0  5127.2    0.07       0  5133.2    0.05       0
  5137.1     0.1       0  5239.4    0.05       0  5355.7    0.08       0
  5471.9     0.1       0
Bank Sta=5127.2,5133.2
Exp/Cntr=0.3,0.1

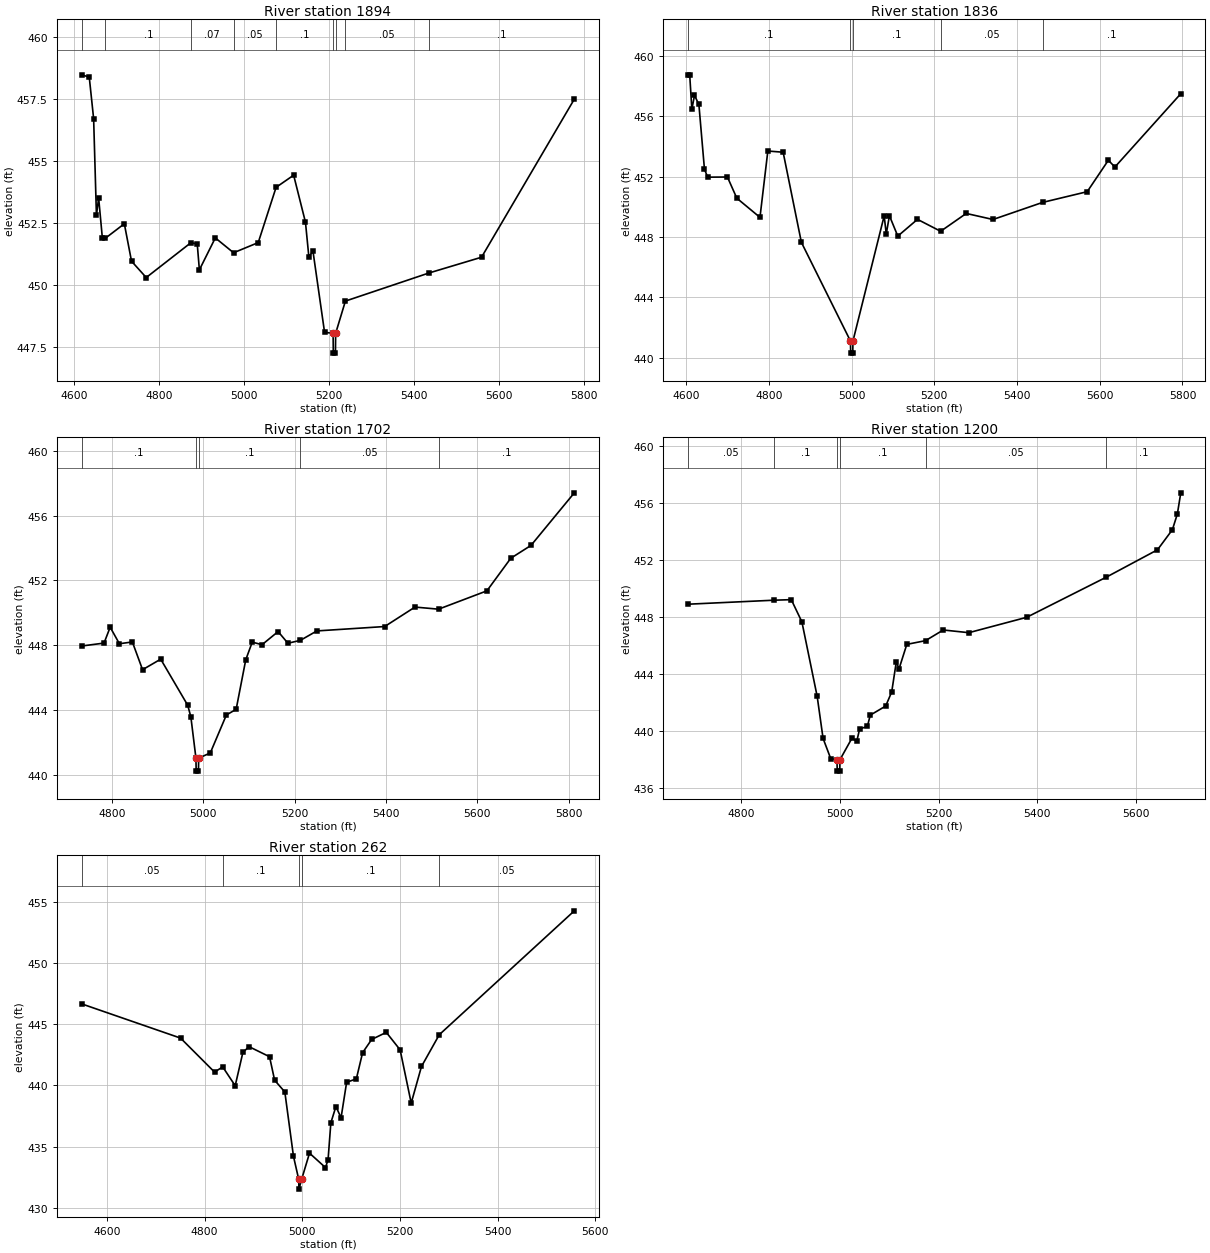
Type RM Length L Ch R = 1,1894,58,58,58
BEGIN DESCRIPTION:
Mapping XS 9914aad6
END DESCRIPTION:
XS GIS Cut Line= 4
      2048691.14     13493962.55      2048739.98     13493767.20
      2048694.41     13493434.08      2048155.86     13493124.24
#Sta/Elev= 30
  4617.8  458.47  4635.9  458.38  4646.2  456.70  4652.8  452.80  4658.0  453.50
  4666.8  451.87  4674.1  451.88  4718.4  452.46  4735.3  450.95  4769.9  450.29
  4875.3  451.70  4889.9  451.64  4894.9  450.60  4932.4  451.89  4975.3  451.29
  5033.3  451.70  5075.3  453.93  5116.6  454.42  5144.4  452.52  5152.4  451.12
  5162.0  451.36  5189.3  448.08  5209.4  448.04  5209.9  447.24  5214.9  447.24
  5215.4  448.04  5238.3  449.34  5434.1  450.47  5558.5  451.11  5776.7  457.49
#Mann=9,-1,0
  4617.8    0.05       0  4674.1     0.1       0  4875.3    0.07       0
  4975.3    0.05       0  5075.3     0.1       0  5209.4   0.033       0
  5215.4     0.1       0  5238.3    0.05       0  5434.1     0.1       0
Bank Sta=5209.4,5215.4
Exp/Cntr=0.3,0.1

Type RM Length L Ch R = 1,1836,134,134,134
BEGIN DESCRIPTION:
Mapping XS fcad292f
END DESCRIPTION:
XS GIS Cut Line= 4
      2048767.12     13493939.68      2048808.34     13493827.96
      2048741.07     13493421.06      2048168.84     13493092.41
#Sta/Elev= 30
  4604.5  458.73  4608.6  458.73  4613.8  456.45  4620.2  457.37  4630.8  456.77
  4644.3  452.48  4652.1  451.96  4699.8  451.97  4722.5  450.57  4778.5  449.30
  4797.5  453.69  4834.5  453.61  4878.6  447.65  4997.3  441.12  4997.8  440.32
  5002.8  440.32  5003.3  441.12  5078.8  449.40  5083.8  448.20  5091.5  449.41
  5111.7  448.06  5159.3  449.17  5215.3  448.38  5277.2  449.56  5341.9  449.16
  5461.8  450.29  5569.7  451.00  5620.8  453.08  5636.6  452.63  5795.9  457.48
#Mann=5,-1,0
  4604.5     0.1       0  4997.3    0.07       0  5003.3     0.1       0
  5215.3    0.05       0  5461.8     0.1       0
Bank Sta=4997.3,5003.3
Exp/Cntr=0.3,0.1

Type RM Length L Ch R = 1,1702,502,502,502
BEGIN DESCRIPTION:
Mapping XS a9bbae3a
END DESCRIPTION:
XS GIS Cut Line= 4
      2048958.08     13493736.80      2048926.61     13493540.42
      2048725.87     13493327.75      2048205.33     13493056.52
#Sta/Elev= 30
  4734.0  447.96  4783.2  448.14  4796.6  449.12  4816.8  448.10  4845.2  448.21
  4867.5  446.50  4907.2  447.15  4966.3  444.31  4973.2  443.59  4984.3  441.05
  4984.8  440.25  4989.8  440.25  4990.3  441.05  5015.7  441.37  5050.9  443.71
  5072.3  444.06  5093.3  447.11  5107.5  448.20  5128.9  448.04  5164.1  448.85
  5185.6  448.13  5212.9  448.31  5248.9  448.89  5397.3  449.16  5463.6  450.36
  5515.2  450.23  5621.0  451.36  5673.3  453.37  5717.5  454.16  5812.3  457.40
#Mann=5,-1,0
  4734.0     0.1       0  4984.3    0.07       0  4990.3     0.1       0
  5212.9    0.05       0  5515.2     0.1       0
Bank Sta=4984.3,4990.3
Exp/Cntr=0.3,0.1

Type RM Length L Ch R = 1,1200,938,938,938
BEGIN DESCRIPTION:
Mapping XS 70f9ab47
END DESCRIPTION:
XS GIS Cut Line= 4
      2049282.53     13493275.68      2049204.39     13493151.97
      2048875.61     13492957.74      2048408.12     13492905.46
#Sta/Elev= 30
  4692.3  448.88  4866.2  449.16  4901.6  449.20  4923.1  447.64  4954.1  442.40
  4966.0  439.46  4981.6  438.03  4994.2  437.96  4994.7  437.16  4999.7  437.16
  5000.2  437.96  5024.5  439.47  5034.3  439.26  5040.1  440.12  5055.8  440.30
  5061.6  441.09  5092.9  441.73  5105.1  442.72  5114.3  444.81  5120.1  444.36
  5135.7  446.06  5173.6  446.32  5209.6  447.07  5261.4  446.88  5378.6  447.96
  5539.5  450.77  5643.7  452.70  5673.9  454.11  5684.0  455.22  5690.9  456.70
#Mann=6,-1,0
  4692.3    0.05       0  4866.2     0.1       0  4994.2    0.07       0
  5000.2     0.1       0  5173.6    0.05       0  5539.5     0.1       0
Bank Sta=4994.2,5000.2
Exp/Cntr=0.3,0.1

Type RM Length L Ch R = 1,262,0,0,0
BEGIN DESCRIPTION:
UNT 134 in Lagunillas Cr Wtrshd 1.0
END DESCRIPTION:
XS GIS Cut Line= 4
      2049405.12     13492663.65      2049342.19     13492355.53
      2049062.25     13492269.80      2048729.06     13492493.73
#Sta/Elev= 30
  4548.1  446.67  4750.8  443.87  4820.4  441.09  4837.0  441.52  4862.6  439.98
  4878.4  442.71  4891.0  443.17  4932.9  442.35  4943.3  440.43  4964.2  439.47
  4981.9  434.21  4992.6  432.33  4993.1  431.53  4998.6  432.33  5014.7  434.47
  5047.4  433.29  5052.7  433.93  5058.4  436.95  5068.8  438.28  5079.3  437.36
  5090.7  440.26  5110.6  440.54  5123.4  442.68  5142.0  443.76  5171.9  444.34
  5200.2  442.91  5222.9  438.56  5243.9  441.55  5280.4  444.15  5556.8  454.27
#Mann=5,-1,0
  4548.1    0.05       0  4837.0     0.1       0  4992.6    0.07       0
  4998.6     0.1       0  5280.4    0.05       0
Bank Sta=4992.6,4998.6
Exp/Cntr=0.3,0.1

Chan Stop Cuts=-1