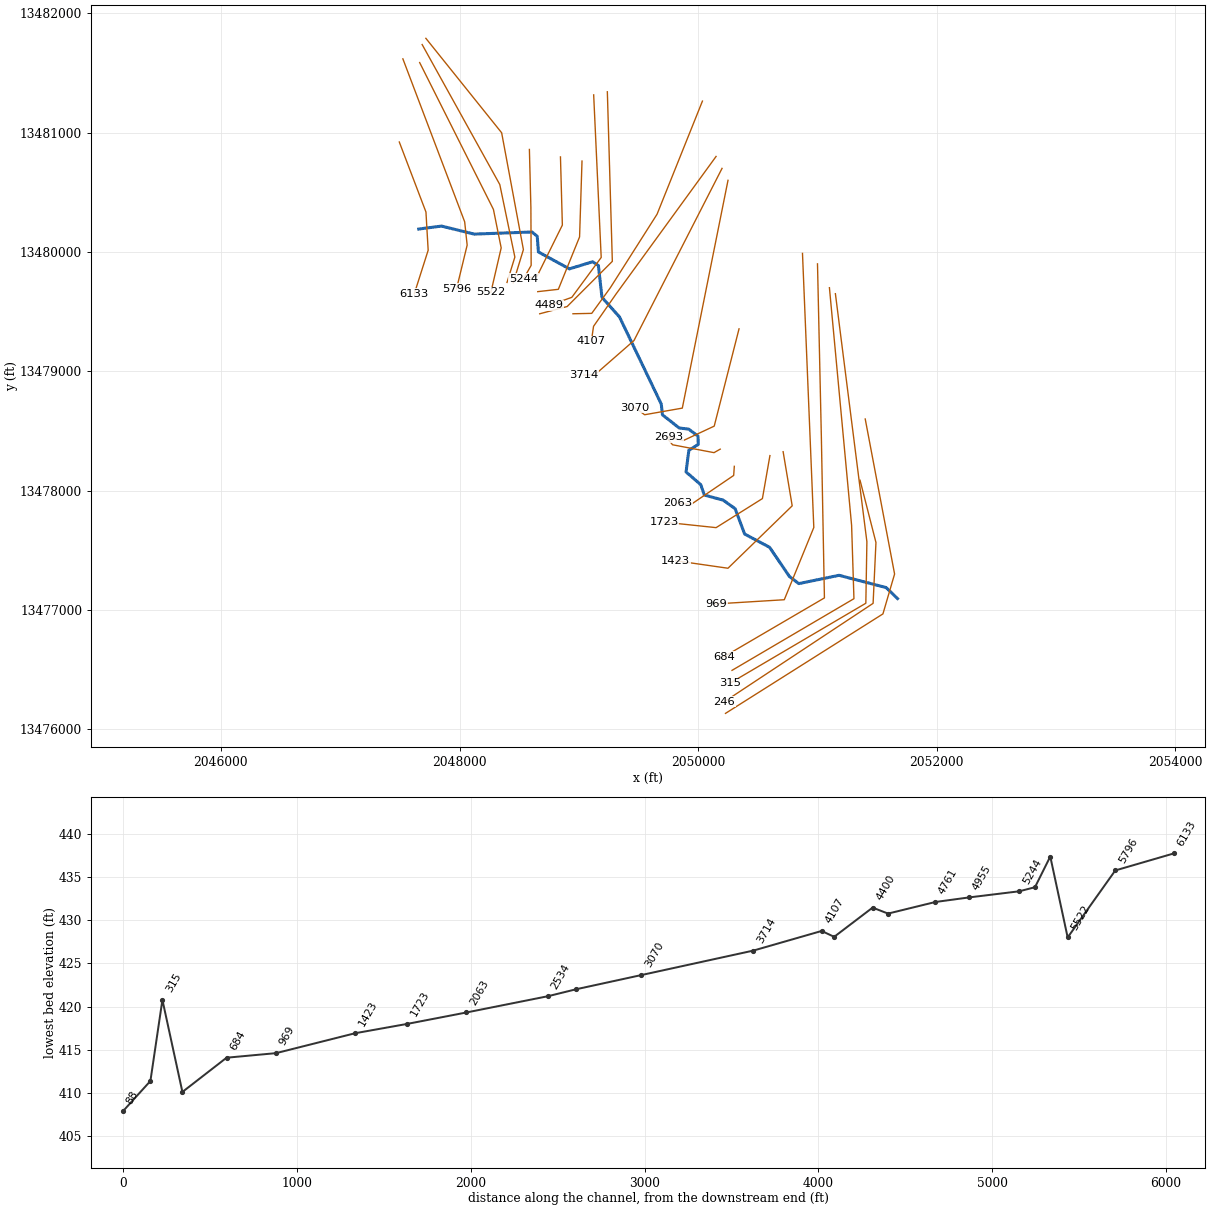
--- UNT 135 in Lagunillas Cr Wtrshd.prj (project) ---

Proj Title=UNT 135 in Lagunillas Cr Wtrshd Base Level Engineering
Current Plan=p01
Default Exp/Contr=0.3,0.1
English Units
Geom File=g01
Flow File=f01
Plan File=p01
BEGIN DESCRIPTION:
UNT 135 in Lagunillas Cr Wtrshd
END DESCRIPTION:

--- UNT 135 in Lagunillas Cr Wtrshd.p01 (plan) ---

Plan Title=Multiple Run
Short Identifier=Multiple
Geom File=g01
Flow File=f01
Subcritical Flow
K Sum by GR= 0
Std Step Tol= 0.01
Critical Tol= 0.01
Num of Std Step Trials= 20
Max Error Tol= 0.3
Flow Tol Ratio= 0.001
Split Flow NTrial= 30
Split Flow Tol= 0.02
Split Flow Ratio= 0.02
Log Output Level= 0
Friction Slope Method= 1
Unsteady Friction Slope Method= 2
Unsteady Bridges Friction Slope Method= 1
Parabolic Critical Depth
Global Vel Dist=  1 , 1 , 1
Global Log Level= 0
CheckData=True
Encroach Param= -1, 0, 0, 0
BEGIN DESCRIPTION:
Multiple Run
END DESCRIPTION:

--- UNT 135 in Lagunillas Cr Wtrshd.f01 (steady flow) ---

Flow Title=Multiple
Number of Profiles=7
Profile Names=10-year,25-year,50-year,1pct_min,100-year,1pct_plu,500-year
River Rch & RM= UNT 135 in Lagun,Reach-1,6133
     176     238     289     175     349     696     516
River Rch & RM= UNT 135 in Lagun,Reach-1,1423
     221     303     371     226     452     902     680
Boundary for River Rch & Prof#=UNT 135 in Lagun,Reach-1,1
Up Type=0
Dn Type=3
Dn Slope=0.005
Boundary for River Rch & Prof#=UNT 135 in Lagun,Reach-1,2
Up Type=0
Dn Type=3
Dn Slope=0.005
Boundary for River Rch & Prof#=UNT 135 in Lagun,Reach-1,3
Up Type=0
Dn Type=3
Dn Slope=0.005
Boundary for River Rch & Prof#=UNT 135 in Lagun,Reach-1,4
Up Type=0
Dn Type=3
Dn Slope=0.005
Boundary for River Rch & Prof#=UNT 135 in Lagun,Reach-1,5
Up Type=0
Dn Type=3
Dn Slope=0.005
Boundary for River Rch & Prof#=UNT 135 in Lagun,Reach-1,6
Up Type=0
Dn Type=3
Dn Slope=0.005
Boundary for River Rch & Prof#=UNT 135 in Lagun,Reach-1,7
Up Type=0
Dn Type=3
Dn Slope=0.005

--- UNT 135 in Lagunillas Cr Wtrshd.g01 (geometry) ---

Geom Title=Existing Conditions

River Reach=UNT 135 in Lagun,Reach-1
Reach XY= 30
      2047657.94     13480191.61      2047848.91     13480216.57
      2048122.35     13480149.29      2048607.59     13480166.96
      2048651.34     13480130.85      2048661.06     13479999.60
      2048920.78     13479857.93      2049115.92     13479917.65
      2049163.84     13479885.71      2049193.76     13479619.56
      2049340.80     13479454.54      2049690.80     13478724.54
      2049700.80     13478634.54      2049840.80     13478524.54
      2049920.80     13478514.54      2049998.33     13478456.27
      2050000.93     13478386.82      2049921.94     13478337.34
      2049898.50     13478155.92      2050021.77     13478049.15
      2050051.28     13477962.34      2050209.27     13477919.81
      2050309.96     13477847.76      2050389.39     13477635.61
      2050598.16     13477524.84      2050764.82     13477280.05
      2050842.95     13477220.15      2051180.62     13477289.60
      2051574.72     13477187.17      2051670.80     13477094.54

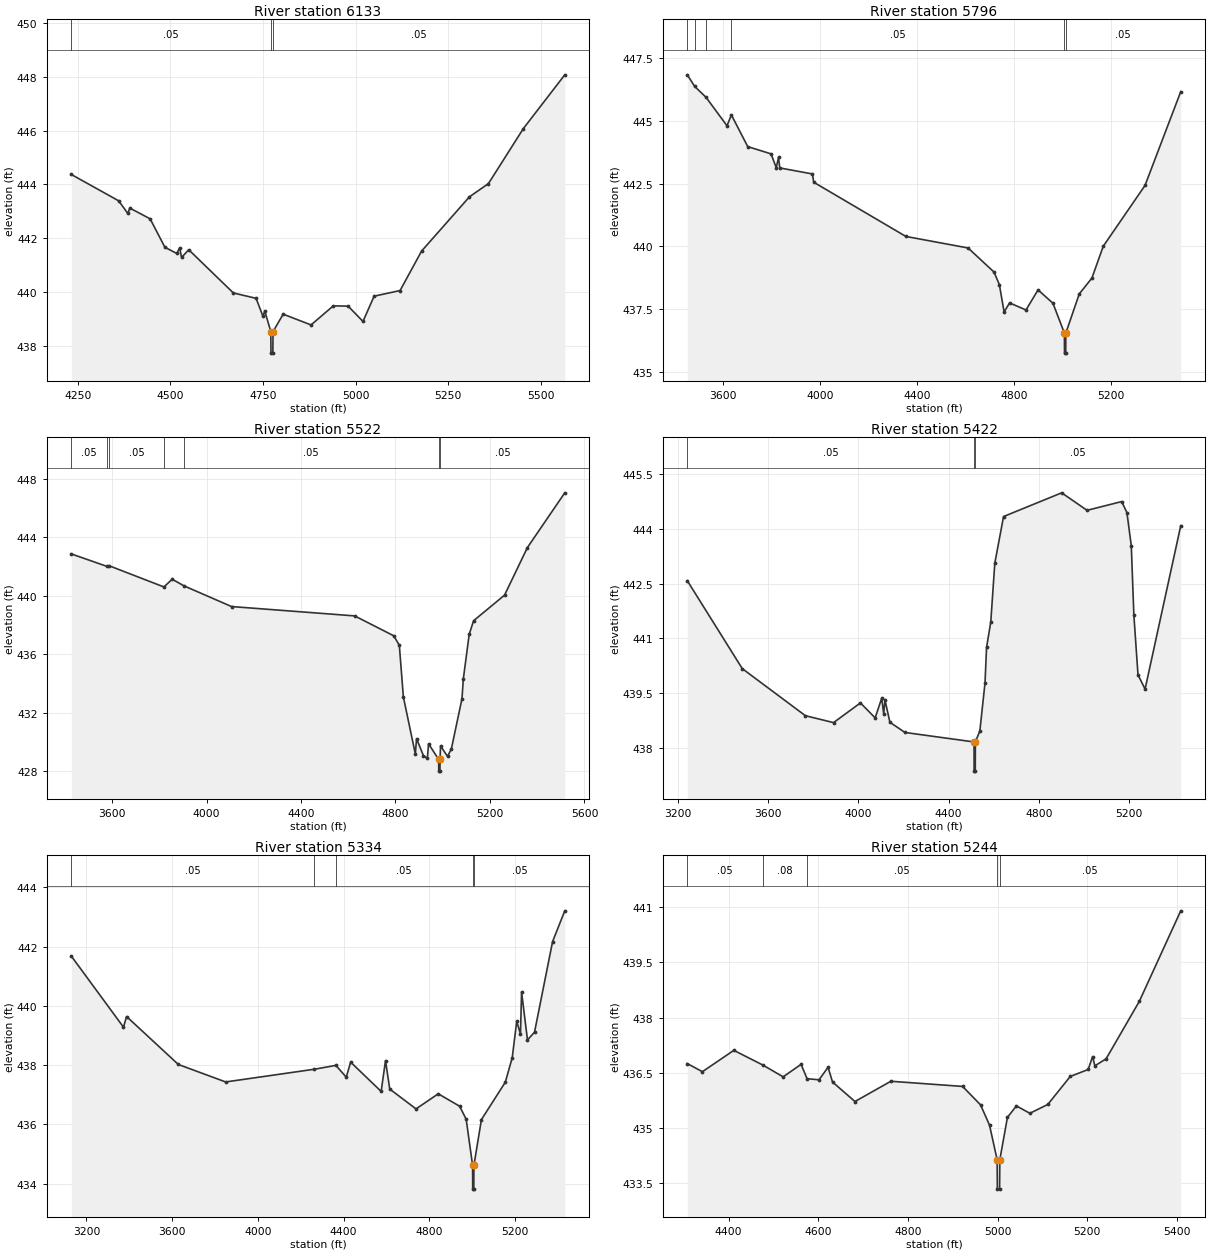
Type RM Length L Ch R = 1,6133,337,337,337
BEGIN DESCRIPTION:
UNT 135 in Lagunillas Cr Wtrshd 2.0
END DESCRIPTION:
XS GIS Cut Line= 4
      2047495.21     13480921.18      2047718.59     13480334.30
      2047737.15     13480013.96      2047620.72     13479648.48
#Sta/Elev= 30
  4232.6  444.37  4360.4  443.39  4385.1  442.92  4390.5  443.12  4445.3  442.72
  4485.3  441.66  4517.4  441.43  4525.0  441.64  4530.3  441.28  4549.5  441.57
  4670.1  439.96  4731.4  439.76  4749.8  439.10  4755.1  439.28  4771.2  438.52
  4771.7  437.72  4776.7  437.72  4777.2  438.52  4804.6  439.17  4879.9  438.77
  4940.0  439.48  4980.0  439.47  5020.1  438.90  5050.2  439.84  5120.3  440.05
  5178.4  441.52  5307.7  443.54  5358.8  444.03  5453.2  446.08  5565.0  448.08
#Mann=3,-1,0
  4232.6    0.05       0  4771.2    0.03       0  4777.2    0.05       0
Bank Sta=4771.2,4777.2
Exp/Cntr=0.3,0.1

Type RM Length L Ch R = 1,5796,274,274,274
BEGIN DESCRIPTION:
Mapping XS aef2a808
END DESCRIPTION:
XS GIS Cut Line= 4
      2047525.24     13481618.06      2048043.10     13480252.34
      2048063.94     13480057.02      2047974.55     13479689.26
#Sta/Elev= 30
  3451.5  446.84  3481.8  446.38  3529.1  445.94  3615.2  444.81  3633.4  445.24
  3700.8  443.98  3797.0  443.69  3818.4  443.14  3827.7  443.55  3833.0  443.13
  3967.7  442.89  3973.0  442.56  4353.1  440.40  4609.8  439.94  4716.8  438.98
  4738.8  438.48  4758.3  437.39  4780.9  437.75  4848.7  437.47  4898.3  438.27
  4959.7  437.74  5007.0  436.55  5007.5  435.75  5012.5  435.75  5013.0  436.55
  5068.4  438.11  5120.5  438.74  5167.4  440.01  5339.5  442.43  5487.0  446.17
#Mann=6,-1,0
  3451.5    0.08       0  3481.8    0.05       0  3529.1    0.08       0
  3633.4    0.05       0  5007.0    0.03       0  5013.0    0.05       0
Bank Sta=5007,5013
Exp/Cntr=0.3,0.1

Type RM Length L Ch R = 1,5522,100,100,100
BEGIN DESCRIPTION:
Mapping XS 5f7cee64
END DESCRIPTION:
XS GIS Cut Line= 4
      2047665.88     13481586.79      2048283.99     13480356.50
      2048349.09     13480033.59      2048262.56     13479660.74
#Sta/Elev= 30
  3427.7  442.86  3578.0  442.01  3586.3  442.06  3819.7  440.60  3854.7  441.13
  3904.0  440.68  4105.9  439.26  4627.2  438.62  4792.5  437.26  4816.3  436.61
  4833.3  433.08  4884.1  429.17  4889.2  430.22  4918.3  429.06  4934.9  428.87
  4940.0  429.87  4982.7  428.80  4983.2  428.00  4988.2  428.00  4988.7  428.80
  4990.8  429.72  5020.3  429.01  5036.5  429.51  5081.5  432.95  5087.3  434.32
  5112.1  437.36  5130.7  438.29  5261.7  440.04  5358.3  443.29  5516.7  447.04
#Mann=7,-1,0
  3427.7    0.05       0  3578.0    0.08       0  3586.3    0.05       0
  3819.7    0.08       0  3904.0    0.05       0  4982.7   0.033       0
  4988.7    0.05       0
Bank Sta=4982.7,4988.7
Exp/Cntr=0.3,0.1

Type RM Length L Ch R = 1,5422,88,88,88
BEGIN DESCRIPTION:
Mapping XS 75c13d45
END DESCRIPTION:
XS GIS Cut Line= 4
      2047686.72     13481737.82      2048337.37     13480564.84
      2048463.68     13479956.76      2048397.98     13479744.09
#Sta/Elev= 30
  3243.4  442.58  3486.8  440.17  3766.2  438.88  3891.0  438.69  4010.0  439.23
  4075.2  438.82  4104.3  439.36  4113.0  438.93  4118.7  439.31  4140.5  438.70
  4207.2  438.42  4513.0  438.16  4513.5  437.36  4518.5  437.36  4519.0  438.16
  4538.8  438.46  4561.7  439.78  4568.5  440.75  4587.2  441.45  4605.0  443.06
  4643.8  444.34  4901.2  444.99  5013.6  444.51  5166.8  444.75  5190.0  444.45
  5209.4  443.54  5220.8  441.64  5239.1  440.00  5270.5  439.61  5428.4  444.09
#Mann=3,-1,0
  3243.4    0.05       0  4513.0    0.03       0  4519.0    0.05       0
Bank Sta=4513,4519
Exp/Cntr=0.3,0.1

Type RM Length L Ch R = 1,5334,90,90,90
BEGIN DESCRIPTION:
Mapping XS a48ae78c
END DESCRIPTION:
XS GIS Cut Line= 4
      2047717.93     13481789.95      2048353.00     13480998.43
      2048535.29     13480019.26      2048450.06     13479740.59
#Sta/Elev= 30
  3129.4  441.68  3372.7  439.28  3387.1  439.64  3628.7  438.02  3849.5  437.43
  4263.9  437.86  4363.6  437.99  4412.2  437.59  4432.5  438.10  4574.9  437.11
  4595.2  438.15  4615.0  437.19  4737.6  436.52  4841.3  437.03  4941.1  436.61
  4971.6  436.17  5001.6  434.61  5002.1  433.81  5007.1  433.81  5007.6  434.61
  5042.8  436.16  5154.1  437.42  5186.5  438.25  5207.4  439.48  5224.9  439.05
  5230.1  440.47  5257.6  438.85  5290.4  439.11  5374.7  442.17  5431.6  443.21
#Mann=5,-1,0
  3129.4    0.05       0  4263.9    0.08       0  4363.6    0.05       0
  5001.6    0.03       0  5007.6    0.05       0
Bank Sta=5001.6,5007.6
Exp/Cntr=0.3,0.1

Type RM Length L Ch R = 1,5244,289,289,289
BEGIN DESCRIPTION:
Mapping XS 9fe39020
END DESCRIPTION:
XS GIS Cut Line= 4
      2048585.49     13480858.65      2048598.11     13480370.15
      2048600.28     13479887.30      2048536.86     13479775.33
#Sta/Elev= 30
  4308.0  436.75  4341.7  436.53  4411.7  437.11  4476.5  436.71  4521.7  436.39
  4561.7  436.73  4575.0  436.34  4601.7  436.31  4621.8  436.65  4631.8  436.25
  4681.8  435.72  4761.8  436.27  4921.8  436.13  4961.8  435.63  4981.8  435.08
  4998.8  434.14  4999.3  433.34  5004.3  433.34  5004.8  434.14  5021.8  435.29
  5041.8  435.60  5071.8  435.40  5111.8  435.64  5161.8  436.40  5201.8  436.59
  5211.7  436.94  5216.7  436.69  5241.8  436.88  5315.8  438.44  5408.2  440.90
#Mann=5,-1,0
  4308.0    0.05       0  4476.5    0.08       0  4575.0    0.05       0
  4998.8    0.03       0  5004.8    0.05       0
Bank Sta=4998.8,5004.8
Exp/Cntr=0.3,0.1

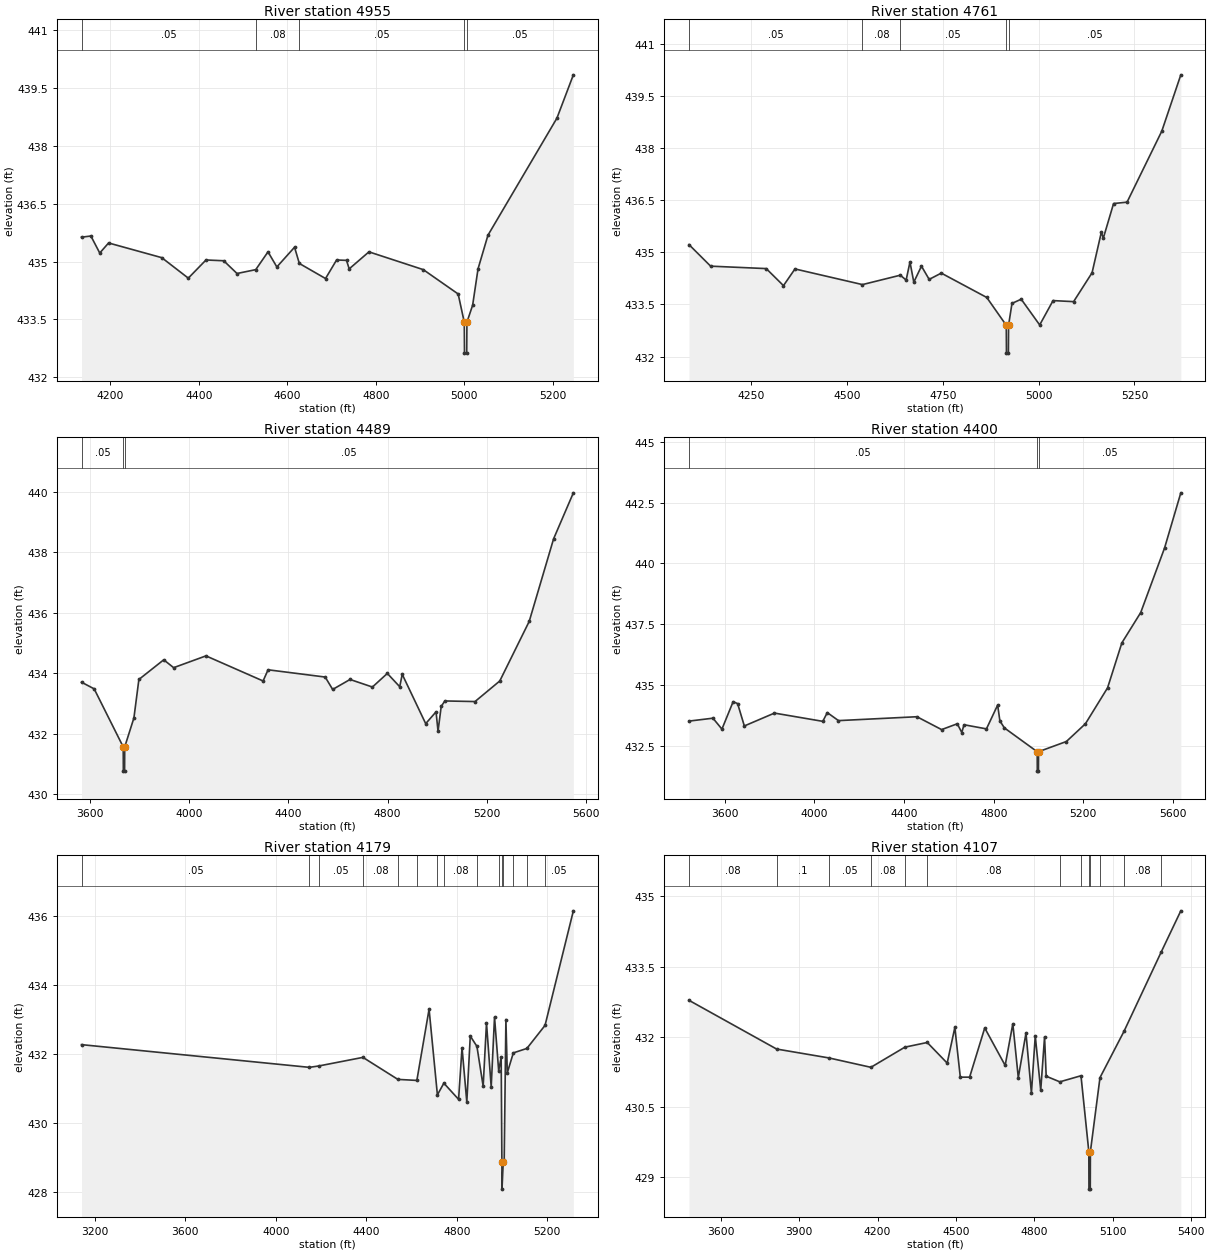
Type RM Length L Ch R = 1,4955,194,194,194
BEGIN DESCRIPTION:
Mapping XS 85ccd6a3
END DESCRIPTION:
XS GIS Cut Line= 4
      2048845.90     13480796.23      2048861.78     13480224.76
      2048650.20     13479797.24      2048588.60     13479785.56
#Sta/Elev= 30
  4135.1  435.63  4156.3  435.66  4176.3  435.22  4196.3  435.48  4316.4  435.10
  4376.4  434.57  4416.4  435.04  4456.4  435.02  4486.5  434.69  4528.8  434.79
  4556.5  435.25  4576.5  434.86  4616.5  435.37  4627.3  434.95  4686.5  434.56
  4711.5  435.04  4733.9  435.03  4740.0  434.81  4784.6  435.25  4907.4  434.79
  4986.2  434.16  5000.0  433.43  5000.5  432.63  5005.5  432.63  5006.0  433.43
  5018.9  433.87  5031.1  434.81  5053.5  435.68  5209.4  438.71  5246.5  439.83
#Mann=5,-1,0
  4135.1    0.05       0  4528.8    0.08       0  4627.3    0.05       0
  5000.0    0.03       0  5006.0    0.05       0
Bank Sta=5000,5006
Exp/Cntr=0.3,0.1

Type RM Length L Ch R = 1,4761,272,272,272
BEGIN DESCRIPTION:
Mapping XS 9801b089
END DESCRIPTION:
XS GIS Cut Line= 4
      2049026.46     13480761.43      2049006.10     13480126.01
      2048828.15     13479686.56      2048655.61     13479667.03
#Sta/Elev= 30
  4087.6  435.22  4144.1  434.60  4289.2  434.53  4334.2  434.04  4364.2  434.52
  4540.3  434.07  4639.1  434.34  4654.3  434.20  4664.3  434.72  4674.3  434.14
  4694.3  434.60  4714.4  434.22  4746.0  434.40  4864.7  433.70  4915.6  432.90
  4916.1  432.10  4921.1  432.10  4921.6  432.90  4930.5  433.53  4954.6  433.65
  5002.8  432.91  5037.7  433.61  5091.3  433.58  5139.5  434.41  5163.6  435.57
  5169.0  435.41  5195.6  436.40  5230.8  436.44  5321.4  438.48  5371.1  440.10
#Mann=5,-1,0
  4087.6    0.05       0  4540.3    0.08       0  4639.1    0.05       0
  4915.6    0.03       0  4921.6    0.05       0
Bank Sta=4915.6,4921.6
Exp/Cntr=0.3,0.1

Type RM Length L Ch R = 1,4489,89,89,89
BEGIN DESCRIPTION:
Mapping XS ffe98640
END DESCRIPTION:
XS GIS Cut Line= 4
      2049124.21     13481315.94      2049187.31     13479953.49
      2048940.99     13479619.29      2048750.03     13479550.93
#Sta/Elev= 30
  3566.6  433.70  3617.6  433.48  3734.7  431.56  3735.2  430.76  3740.2  430.76
  3740.7  431.56  3777.8  432.52  3797.8  433.79  3897.9  434.44  3937.9  434.18
  4068.1  434.57  4298.3  433.74  4318.3  434.11  4548.6  433.87  4578.6  433.46
  4648.7  433.79  4738.8  433.54  4798.9  433.99  4848.9  433.55  4858.9  433.96
  4953.5  432.33  4995.2  432.72  5003.2  432.08  5016.0  432.90  5030.7  433.08
  5152.2  433.06  5252.0  433.74  5370.6  435.71  5468.9  438.44  5548.5  439.96
#Mann=3,-1,0
  3566.6    0.05       0  3734.7    0.03       0  3740.7    0.05       0
Bank Sta=3734.7,3740.7
Exp/Cntr=0.3,0.1

Type RM Length L Ch R = 1,4400,221,221,221
BEGIN DESCRIPTION:
Mapping XS 6b39b30e
END DESCRIPTION:
XS GIS Cut Line= 4
      2049238.79     13481341.99      2049280.62     13479920.94
      2048901.93     13479542.25      2048671.94     13479481.49
#Sta/Elev= 30
  3440.0  433.51  3547.0  433.63  3587.1  433.18  3637.1  434.31  3657.1  434.23
  3687.1  433.31  3821.5  433.84  4037.2  433.50  4057.3  433.86  4107.3  433.53
  4457.4  433.69  4567.5  433.16  4637.5  433.40  4657.5  433.04  4667.5  433.36
  4767.6  433.19  4817.6  434.17  4827.6  433.52  4847.6  433.23  4994.1  432.25
  4994.6  431.45  4999.6  431.45  5000.1  432.25  5124.4  432.67  5209.3  433.40
  5308.2  434.88  5371.9  436.73  5456.1  437.98  5562.6  440.64  5635.1  442.91
#Mann=3,-1,0
  3440.0    0.05       0  4994.1    0.03       0  5000.1    0.05       0
Bank Sta=4994.1,5000.1
Exp/Cntr=0.3,0.1

Type RM Length L Ch R = 1,4179,72,72,72
BEGIN DESCRIPTION:
Mapping XS eb7a57e0
END DESCRIPTION:
XS GIS Cut Line= 5
      2050035.68     13481263.90      2049655.46     13480315.96
      2049263.15     13479698.73      2049107.99     13479484.98
      2048950.66     13479481.72
#Sta/Elev= 30
  3141.4  432.27  4148.5  431.61  4190.3  431.65  4385.4  431.90  4539.8  431.26
  4623.8  431.23  4677.8  433.30  4714.6  430.81  4743.1  431.15  4808.2  430.68
  4823.5  432.18  4844.6  430.60  4859.9  432.52  4889.3  432.22  4916.9  431.06
  4931.6  432.90  4952.4  431.04  4967.1  433.07  4985.5  431.51  4996.5  431.91
  4999.7  428.87  5000.2  428.07  5005.7  428.87  5009.9  428.92  5017.4  433.00
  5023.5  431.45  5050.2  432.03  5110.2  432.16  5190.4  432.83  5315.6  436.16
#Mann=15,-1,0
  3141.4    0.05       0  4148.5    0.08       0  4190.3    0.05       0
  4385.4    0.08       0  4539.8    0.05       0  4623.8    0.08       0
  4714.6    0.05       0  4743.1    0.08       0  4889.3    0.05       0
  4985.5    0.08       0  4999.7    0.07       0  5005.7    0.08       0
  5050.2    0.05       0  5110.2    0.08       0  5190.4    0.05       0
Bank Sta=4999.7,5005.7
Exp/Cntr=0.3,0.1

Type RM Length L Ch R = 1,4107,393,393,393
BEGIN DESCRIPTION:
Mapping XS 991f39ec
END DESCRIPTION:
XS GIS Cut Line= 4
      2050149.99     13480799.98      2049309.81     13479644.48
      2049123.18     13479376.47      2049104.73     13479251.68
#Sta/Elev= 30
  3478.7  432.78  3813.9  431.74  4014.3  431.55  4174.6  431.35  4304.5  431.78
  4390.1  431.88  4466.4  431.44  4495.7  432.20  4516.6  431.14  4552.2  431.14
  4610.0  432.19  4688.2  431.39  4717.5  432.28  4738.4  431.13  4767.8  432.08
  4788.6  430.80  4803.3  432.02  4824.2  430.86  4838.9  432.00  4845.1  431.16
  4897.2  431.04  4978.2  431.17  5008.2  429.55  5008.7  428.75  5013.7  428.75
  5014.2  429.55  5050.9  431.13  5142.9  432.12  5285.0  433.81  5360.1  434.69
#Mann=13,-1,0
  3478.7    0.08       0  3813.9     0.1       0  4014.3    0.05       0
  4174.6    0.08       0  4304.5     0.1       0  4390.1    0.08       0
  4897.2     0.1       0  4978.2    0.08       0  5008.2    0.07       0
  5014.2    0.08       0  5050.9    0.05       0  5142.9    0.08       0
  5285.0     0.1       0
Bank Sta=5008.2,5014.2
Exp/Cntr=0.3,0.1

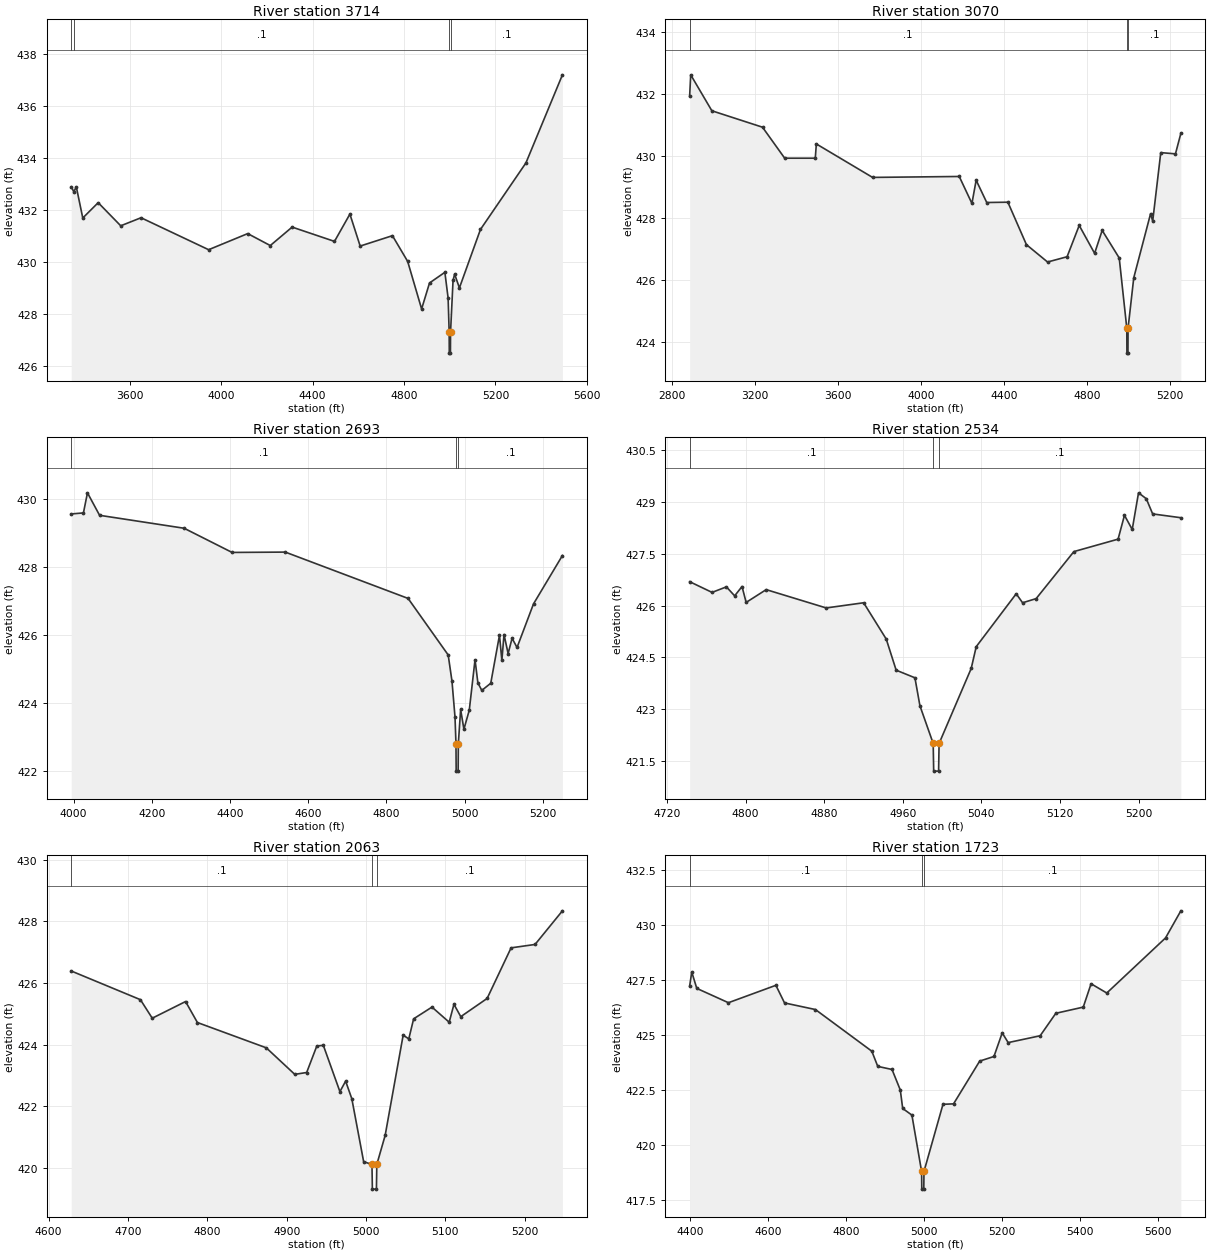
Type RM Length L Ch R = 1,3714,644,644,644
BEGIN DESCRIPTION:
Mapping XS 4efbb74d
END DESCRIPTION:
XS GIS Cut Line= 4
      2050199.99     13480699.98      2049461.83     13479256.87
      2049135.22     13478971.50      2049041.87     13478967.16
#Sta/Elev= 30
  3344.8  432.88  3356.3  432.69  3367.0  432.88  3395.3  431.68  3462.7  432.27
  3561.3  431.38  3650.1  431.69  3945.7  430.46  4116.6  431.08  4215.3  430.62
  4310.9  431.33  4496.1  430.78  4563.5  431.83  4608.4  430.60  4749.5  431.00
  4816.1  430.01  4877.1  428.18  4911.7  429.18  4978.8  429.59  4993.0  428.60
  4997.6  427.28  4998.1  426.48  5003.1  426.48  5003.6  427.28  5014.6  429.28
  5021.5  429.52  5042.4  428.99  5134.5  431.24  5333.3  433.80  5492.9  437.19
#Mann=4,-1,0
  3344.8    0.08       0  3356.3     0.1       0  4997.6    0.07       0
  5003.6     0.1       0
Bank Sta=4997.6,5003.6
Exp/Cntr=0.3,0.1

Type RM Length L Ch R = 1,3070,377,377,377
BEGIN DESCRIPTION:
Mapping XS 928ab6f6
END DESCRIPTION:
XS GIS Cut Line= 4
      2050250.01     13480600.05      2049867.10     13478690.92
      2049551.13     13478635.37      2049469.77     13478695.95
#Sta/Elev= 30
  2884.0  431.95  2889.1  432.63  2991.1  431.47  3235.4  430.94  3342.4  429.94
  3490.0  429.94  3495.1  430.40  3766.3  429.32  4184.4  429.35  4245.6  428.48
  4266.0  429.23  4317.0  428.51  4419.0  428.52  4508.5  427.15  4610.4  426.59
  4704.6  426.76  4763.1  427.77  4837.4  426.87  4873.9  427.61  4956.1  426.72
  4992.7  424.45  4993.2  423.65  4998.2  423.65  4998.7  424.45  5026.2  426.08
  5107.4  428.15  5117.6  427.91  5156.5  430.12  5227.4  430.08  5253.4  430.74
#Mann=3,-1,0
  2884.0     0.1       0  4992.7    0.07       0  4998.7     0.1       0
Bank Sta=4992.7,4998.7
Exp/Cntr=0.3,0.1

Type RM Length L Ch R = 1,2693,159,159,159
BEGIN DESCRIPTION:
Mapping XS c2cafef5
END DESCRIPTION:
XS GIS Cut Line= 4
      2050342.44     13479355.25      2050134.47     13478539.88
      2049874.05     13478418.35      2049750.79     13478447.87
#Sta/Elev= 30
  3994.1  429.55  4025.3  429.58  4035.6  430.17  4066.6  429.51  4282.7  429.13
  4405.3  428.42  4541.3  428.43  4855.2  427.07  4957.7  425.41  4967.4  424.64
  4975.1  423.59  4977.6  422.80  4978.1  422.00  4983.1  422.00  4983.6  422.80
  4989.5  423.81  4997.9  423.23  5011.6  423.79  5026.3  425.27  5033.6  424.59
  5043.6  424.37  5066.5  424.58  5088.8  425.99  5094.9  425.25  5100.4  426.01
  5110.9  425.45  5121.0  425.90  5133.7  425.63  5175.8  426.91  5249.7  428.33
#Mann=3,-1,0
  3994.1     0.1       0  4977.6    0.07       0  4983.6     0.1       0
Bank Sta=4977.6,4983.6
Exp/Cntr=0.3,0.1

Type RM Length L Ch R = 1,2534,471,471,471
BEGIN DESCRIPTION:
Mapping XS 94024781
END DESCRIPTION:
XS GIS Cut Line= 4
      2050184.81     13478347.17      2050132.73     13478317.66
      2049785.51     13478383.63      2049730.51     13478450.66
#Sta/Elev= 30
  4743.0  426.69  4765.8  426.38  4780.4  426.54  4788.8  426.28  4796.3  426.55
  4800.5  426.09  4820.9  426.46  4882.0  425.93  4920.1  426.08  4943.1  425.03
  4953.2  424.13  4972.3  423.91  4977.4  423.10  4990.9  422.01  4991.4  421.21
  4996.4  421.21  4996.9  422.01  5029.6  424.18  5034.7  424.81  5075.4  426.34
  5081.9  426.08  5095.7  426.20  5134.1  427.56  5179.1  427.92  5185.6  428.61
  5193.5  428.20  5199.9  429.26  5207.8  429.09  5214.3  428.65  5243.0  428.54
#Mann=3,-1,0
  4743.0     0.1       0  4990.9    0.07       0  4996.9     0.1       0
Bank Sta=4990.9,4996.9
Exp/Cntr=0.3,0.1

Type RM Length L Ch R = 1,2063,340,340,340
BEGIN DESCRIPTION:
Mapping XS 2c0eac91
END DESCRIPTION:
XS GIS Cut Line= 4
      2050302.87     13478203.08      2050297.66     13478126.69
      2049940.02     13477883.63      2049830.68     13477895.78
#Sta/Elev= 30
  4628.5  426.39  4715.7  425.46  4730.6  424.86  4772.6  425.40  4787.5  424.72
  4874.3  423.90  4910.2  423.04  4925.2  423.10  4938.0  423.96  4946.2  423.98
  4967.1  422.48  4974.3  422.82  4982.1  422.25  4997.0  420.21  5007.5  420.12
  5008.0  419.32  5013.1  419.32  5013.6  420.12  5024.1  421.06  5046.8  424.31
  5053.9  424.19  5060.0  424.84  5083.1  425.22  5104.8  424.73  5110.8  425.31
  5119.4  424.91  5152.6  425.50  5182.8  427.14  5213.0  427.25  5247.5  428.34
#Mann=3,-1,0
  4628.5     0.1       0  5007.5    0.07       0  5013.6     0.1       0
Bank Sta=5007.5,5013.6
Exp/Cntr=0.3,0.1

Type RM Length L Ch R = 1,1723,300,300,300
BEGIN DESCRIPTION:
Mapping XS b3245c01
END DESCRIPTION:
XS GIS Cut Line= 4
      2050601.35     13478293.00      2050538.41     13477932.73
      2050150.09     13477689.19      2049715.93     13477735.25
#Sta/Elev= 30
  4398.8  427.22  4404.2  427.85  4417.1  427.11  4498.3  426.46  4620.1  427.25
  4642.3  426.45  4721.6  426.15  4866.3  424.26  4881.6  423.57  4918.2  423.43
  4939.4  422.50  4945.6  421.66  4969.2  421.36  4994.1  418.80  4994.6  418.00
  4999.7  418.00  5000.2  418.80  5049.0  421.85  5076.1  421.87  5143.2  423.81
  5179.8  424.02  5201.0  425.09  5216.3  424.65  5298.4  424.96  5338.6  425.98
  5409.0  426.26  5429.1  427.32  5469.4  426.90  5620.2  429.40  5659.5  430.63
#Mann=3,-1,0
  4398.8     0.1       0  4994.1    0.07       0  5000.2     0.1       0
Bank Sta=4994.1,5000.2
Exp/Cntr=0.3,0.1

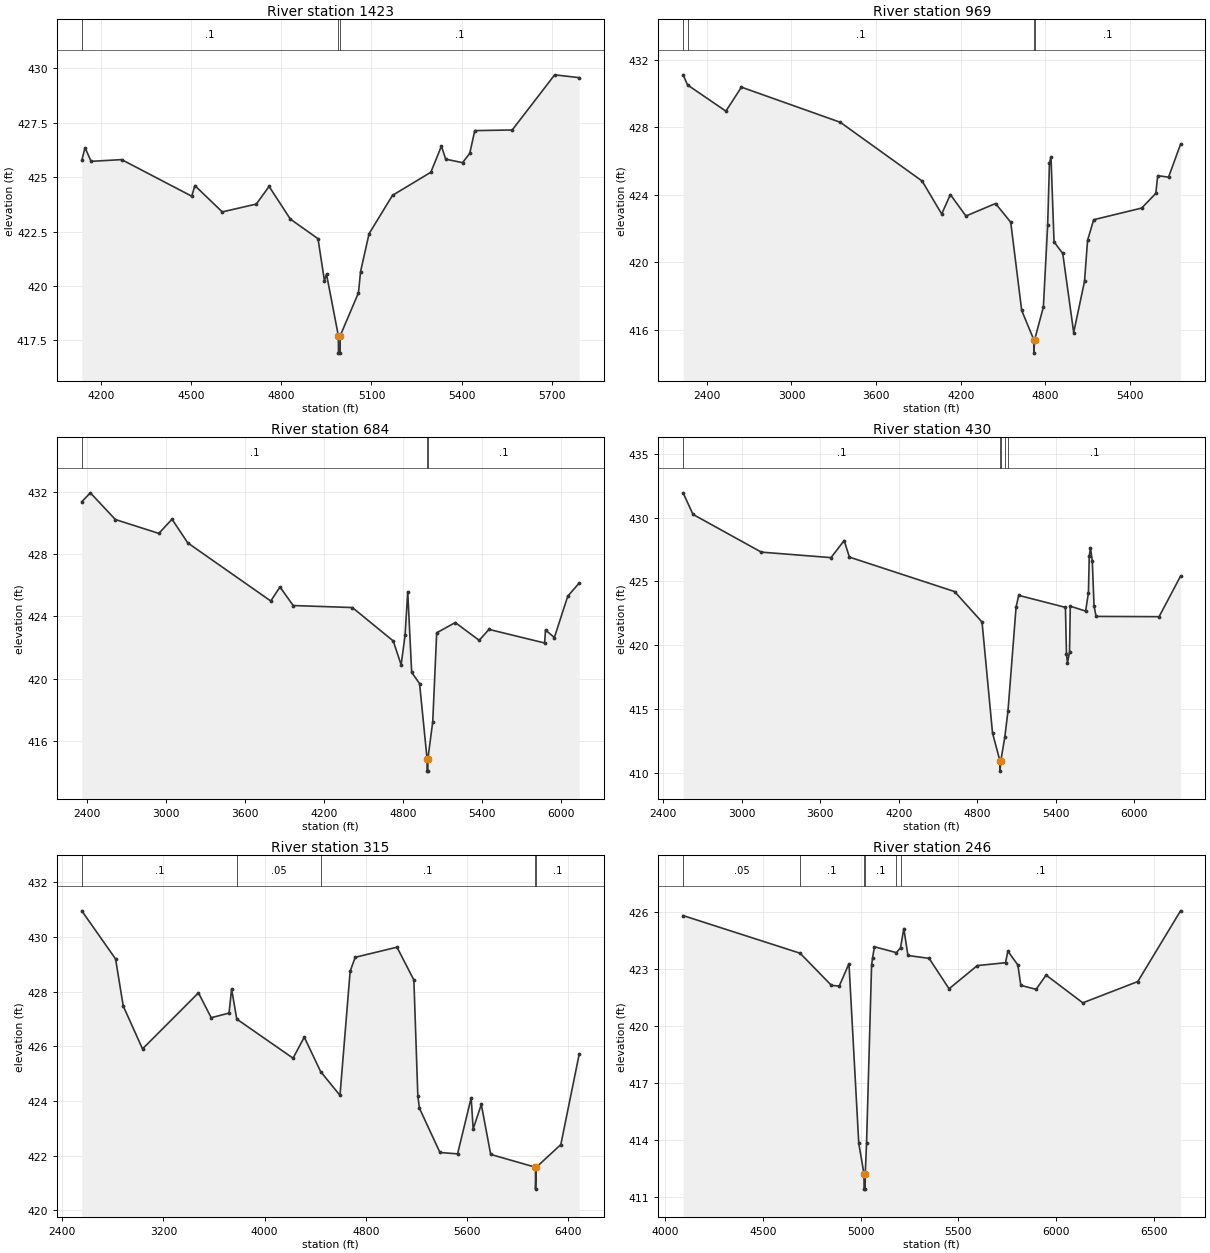
Type RM Length L Ch R = 1,1423,454,454,454
BEGIN DESCRIPTION:
Mapping XS d77de5dd
END DESCRIPTION:
XS GIS Cut Line= 4
      2050712.02     13478325.57      2050787.98     13477871.97
      2050249.78     13477348.96      2049811.45     13477411.89
#Sta/Elev= 30
  4137.2  425.76  4147.9  426.35  4168.2  425.72  4269.6  425.80  4502.8  424.12
  4512.9  424.61  4604.1  423.40  4717.3  423.76  4759.7  424.57  4830.4  423.07
  4922.3  422.17  4943.6  420.25  4950.6  420.54  4989.9  417.72  4990.4  416.92
  4995.7  416.92  4996.2  417.72  5056.8  419.69  5063.7  420.66  5092.0  422.40
  5169.9  424.16  5297.3  425.22  5332.5  426.42  5346.7  425.82  5402.9  425.66
  5426.7  426.09  5443.3  427.13  5567.8  427.16  5708.9  429.69  5790.4  429.56
#Mann=3,-1,0
  4137.2     0.1       0  4989.9    0.07       0  4996.2     0.1       0
Bank Sta=4989.9,4996.2
Exp/Cntr=0.3,0.1

Type RM Length L Ch R = 1,969,285,285,285
BEGIN DESCRIPTION:
Mapping XS c924bcc4
END DESCRIPTION:
XS GIS Cut Line= 4
      2050874.21     13479987.82      2050969.10     13477690.49
      2050721.71     13477085.02      2050150.03     13477050.00
#Sta/Elev= 30
  2232.3  431.10  2263.8  430.50  2535.4  428.95  2645.5  430.37  3346.5  428.29
  3926.6  424.81  4065.2  422.86  4126.7  424.01  4236.8  422.74  4447.0  423.48
  4554.7  422.37  4632.2  417.15  4718.0  415.42  4718.5  414.62  4724.3  415.42
  4786.0  417.35  4816.5  422.22  4829.2  425.88  4840.0  426.25  4861.6  421.21
  4923.4  420.52  5000.9  415.84  5077.6  418.87  5099.3  421.30  5142.6  422.52
  5482.9  423.21  5583.1  424.08  5596.5  425.13  5673.3  425.04  5758.4  426.99
#Mann=4,-1,0
  2232.3    0.05       0  2263.8     0.1       0  4718.0    0.07       0
  4724.3     0.1       0
Bank Sta=4718,4724.3
Exp/Cntr=0.3,0.1

Type RM Length L Ch R = 1,684,254,254,254
BEGIN DESCRIPTION:
Mapping XS 2d108de9
END DESCRIPTION:
XS GIS Cut Line= 4
      2051000.00     13479900.04      2051032.47     13478446.13
      2051058.08     13477100.21      2050214.20     13476606.54
#Sta/Elev= 30
  2362.6  431.35  2427.7  431.92  2617.7  430.21  2947.8  429.32  3047.8  430.23
  3167.8  428.71  3798.0  424.99  3868.0  425.89  3968.0  424.70  4418.1  424.57
  4728.2  422.43  4788.2  420.90  4818.2  422.80  4838.2  425.59  4868.2  420.42
  4928.2  419.70  4985.0  414.89  4985.5  414.09  4990.9  414.09  4991.4  414.89
  5028.2  417.25  5058.2  422.95  5199.3  423.61  5381.1  422.47  5455.5  423.17
  5877.7  422.30  5884.9  423.13  5952.1  422.65  6053.8  425.30  6140.7  426.14
#Mann=3,-1,0
  2362.6     0.1       0  4985.0    0.07       0  4991.4     0.1       0
Bank Sta=4985,4991.4
Exp/Cntr=0.3,0.1

Type RM Length L Ch R = 1,430,115,115,115
BEGIN DESCRIPTION:
Mapping XS a9b1d617
END DESCRIPTION:
XS GIS Cut Line= 4
      2051100.00     13479700.00      2051285.94     13477707.85
      2051305.47     13477093.70      2050283.67     13476493.13
#Sta/Elev= 30
  2552.2  431.95  2627.5  430.26  3149.8  427.30  3682.1  426.87  3782.5  428.21
  3822.7  426.91  4625.9  424.21  4836.0  421.82  4916.0  413.13  4972.9  410.93
  4973.4  410.13  4979.3  410.93  5010.2  412.81  5034.5  414.87  5096.1  422.99
  5116.1  423.91  5473.1  422.97  5481.2  419.28  5488.8  418.62  5504.4  419.45
  5510.2  423.06  5627.4  422.68  5648.9  424.11  5655.2  427.00  5664.6  427.65
  5678.4  426.62  5691.8  423.08  5707.5  422.26  6188.8  422.24  6352.7  425.42
#Mann=5,-1,0
  2552.2     0.1       0  4972.9    0.07       0  4979.3     0.1       0
  5010.2    0.05       0  5034.5     0.1       0
Bank Sta=4972.9,4979.3
Exp/Cntr=0.3,0.1

Type RM Length L Ch R = 1,315,69,69,69
BEGIN DESCRIPTION:
Mapping XS fb36614a
END DESCRIPTION:
XS GIS Cut Line= 4
      2051150.00     13479650.01      2051413.98     13477571.13
      2051405.17     13477055.61      2050266.27     13476385.47
#Sta/Elev= 30
  2554.4  430.96  2821.5  429.20  2882.0  427.48  3034.5  425.91  3476.8  427.96
  3577.6  427.05  3718.7  427.22  3738.8  428.10  3779.8  427.00  4224.6  425.57
  4313.4  426.34  4442.6  425.08  4595.7  424.21  4676.1  428.75  4716.1  429.26
  5046.2  429.63  5179.9  428.43  5211.2  424.19  5223.8  423.74  5386.2  422.12
  5525.4  422.07  5632.9  424.12  5648.6  422.98  5713.0  423.88  5787.2  422.05
  6141.3  421.58  6141.8  420.78  6147.7  421.58  6341.7  422.41  6487.0  425.72
#Mann=5,-1,0
  2554.4     0.1       0  3779.8    0.05       0  4442.6     0.1       0
  6141.3    0.07       0  6147.7     0.1       0
Bank Sta=6141.3,6147.7
Exp/Cntr=0.3,0.1

Type RM Length L Ch R = 1,246,158,158,158
BEGIN DESCRIPTION:
Mapping XS 66695d02
END DESCRIPTION:
XS GIS Cut Line= 4
      2051356.57     13478086.85      2051489.93     13477564.62
      2051466.06     13477054.64      2050217.69     13476229.24
#Sta/Elev= 30
  4091.8  425.79  4690.5  423.81  4850.7  422.12  4890.7  422.08  4940.7  423.26
  4990.8  413.81  5017.6  412.20  5018.1  411.40  5023.5  411.40  5024.0  412.20
  5030.8  413.85  5056.5  423.19  5061.5  423.56  5070.9  424.15  5183.6  423.84
  5204.6  424.10  5221.4  425.11  5242.5  423.69  5350.8  423.54  5453.1  421.94
  5597.6  423.16  5742.0  423.31  5754.0  423.92  5805.2  423.19  5820.3  422.12
  5898.5  421.91  5949.7  422.66  6137.6  421.20  6419.1  422.32  6637.9  426.04
#Mann=6,-1,0
  4091.8    0.05       0  4690.5     0.1       0  5017.6    0.07       0
  5024.0     0.1       0  5183.6    0.16       0  5204.6     0.1       0
Bank Sta=5017.6,5024
Exp/Cntr=0.3,0.1

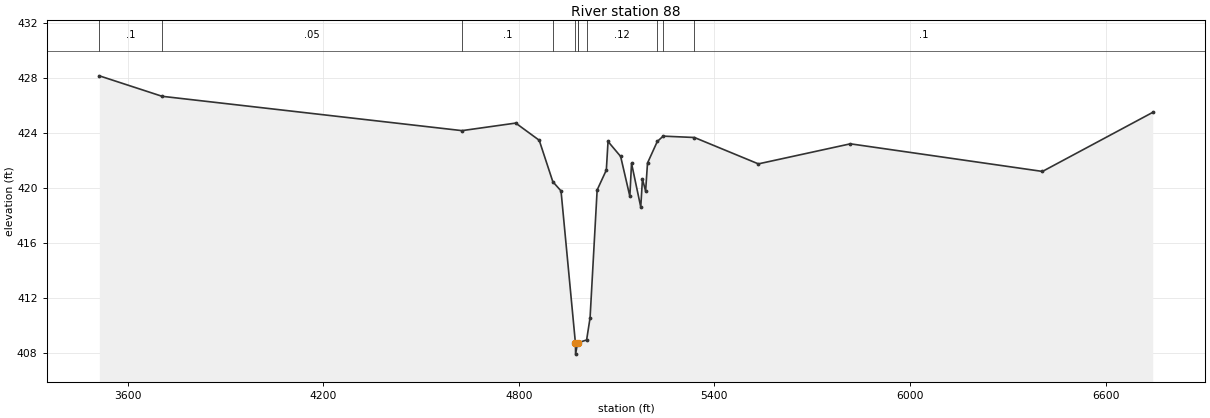
Type RM Length L Ch R = 1,88,0,0,0
BEGIN DESCRIPTION:
UNT 135 in Lagunillas Cr Wtrshd 1.0
END DESCRIPTION:
XS GIS Cut Line= 4
      2051400.01     13478599.96      2051646.13     13477300.49
      2051548.48     13476966.28      2050229.04     13476132.60
#Sta/Elev= 30
  3513.4  428.16  3705.9  426.67  4625.9  424.17  4790.7  424.72  4862.8  423.47
  4904.6  420.45  4929.7  419.78  4973.9  408.70  4974.4  407.90  4980.3  408.70
  4980.7  408.72  5008.2  408.93  5018.8  410.54  5040.5  419.85  5068.7  421.30
  5073.9  423.38  5112.6  422.29  5140.8  419.39  5146.0  421.79  5174.3  418.61
  5179.5  420.64  5189.2  419.77  5195.0  421.81  5225.0  423.38  5243.1  423.77
  5339.0  423.67  5535.1  421.75  5817.4  423.21  6406.6  421.20  6744.9  425.50
#Mann=11,-1,0
  3513.4     0.1       0  3705.9    0.05       0  4625.9     0.1       0
  4904.6    0.12       0  4973.9    0.07       0  4980.3    0.12       0
  4980.7    0.16       0  5008.2    0.12       0  5225.0    0.16       0
  5243.1    0.12       0  5339.0     0.1       0
Bank Sta=4973.9,4980.3
Exp/Cntr=0.3,0.1

Chan Stop Cuts=-1