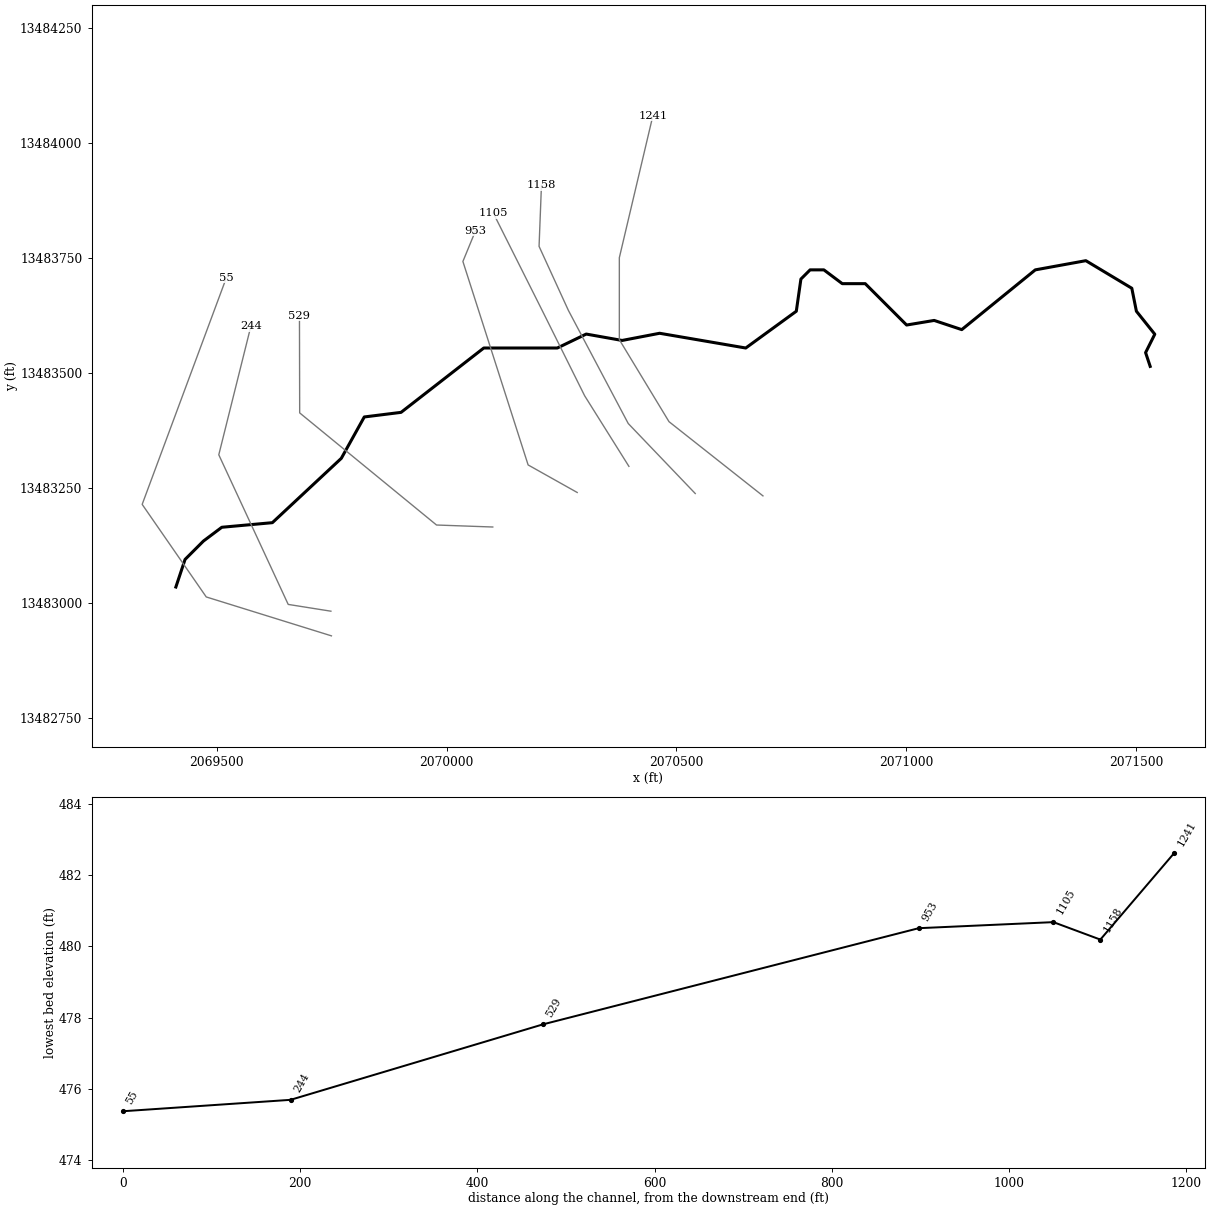
--- UNT 141 in Lagunillas Cr Wtrshd.prj (project) ---

Proj Title=UNT 141 in Lagunillas Cr Wtrshd Base Level Engineering
Current Plan=p01
Default Exp/Contr=0.3,0.1
English Units
Geom File=g01
Flow File=f01
Plan File=p01
BEGIN DESCRIPTION:
UNT 141 in Lagunillas Cr Wtrshd
END DESCRIPTION:

--- UNT 141 in Lagunillas Cr Wtrshd.p01 (plan) ---

Plan Title=Multiple Run
Short Identifier=Multiple
Geom File=g01
Flow File=f01
Subcritical Flow
K Sum by GR= 0
Std Step Tol= 0.01
Critical Tol= 0.01
Num of Std Step Trials= 20
Max Error Tol= 0.3
Flow Tol Ratio= 0.001
Split Flow NTrial= 30
Split Flow Tol= 0.02
Split Flow Ratio= 0.02
Log Output Level= 0
Friction Slope Method= 1
Unsteady Friction Slope Method= 2
Unsteady Bridges Friction Slope Method= 1
Parabolic Critical Depth
Global Vel Dist=  1 , 1 , 1
Global Log Level= 0
CheckData=True
Encroach Param= -1, 0, 0, 0
BEGIN DESCRIPTION:
Multiple Run
END DESCRIPTION:

--- UNT 141 in Lagunillas Cr Wtrshd.f01 (steady flow) ---

Flow Title=Multiple
Number of Profiles=7
Profile Names=10-year,25-year,50-year,1pct_min,100-year,1pct_plu,500-year
River Rch & RM= UNT 141 in Lagun,Reach-1,1241
     108     142     169     100     200     398     284
Boundary for River Rch & Prof#=UNT 141 in Lagun,Reach-1,1
Up Type=0
Dn Type=3
Dn Slope=0.005
Boundary for River Rch & Prof#=UNT 141 in Lagun,Reach-1,2
Up Type=0
Dn Type=3
Dn Slope=0.005
Boundary for River Rch & Prof#=UNT 141 in Lagun,Reach-1,3
Up Type=0
Dn Type=3
Dn Slope=0.005
Boundary for River Rch & Prof#=UNT 141 in Lagun,Reach-1,4
Up Type=0
Dn Type=3
Dn Slope=0.005
Boundary for River Rch & Prof#=UNT 141 in Lagun,Reach-1,5
Up Type=0
Dn Type=3
Dn Slope=0.005
Boundary for River Rch & Prof#=UNT 141 in Lagun,Reach-1,6
Up Type=0
Dn Type=3
Dn Slope=0.005
Boundary for River Rch & Prof#=UNT 141 in Lagun,Reach-1,7
Up Type=0
Dn Type=3
Dn Slope=0.005

--- UNT 141 in Lagunillas Cr Wtrshd.g01 (geometry) ---

Geom Title=Existing Conditions

River Reach=UNT 141 in Lagun,Reach-1
Reach XY= 30
      2071530.80     13483514.54      2071520.80     13483544.54
      2071540.80     13483584.54      2071500.80     13483634.54
      2071490.80     13483684.54      2071390.80     13483744.54
      2071280.80     13483724.54      2071120.80     13483594.54
      2071060.80     13483614.54      2071000.80     13483604.54
      2070910.80     13483694.54      2070860.80     13483694.54
      2070820.80     13483724.54      2070790.80     13483724.54
      2070770.80     13483704.54      2070760.80     13483634.54
      2070650.80     13483554.54      2070463.40     13483586.60
      2070381.80     13483570.98      2070303.67     13483584.87
      2070240.80     13483554.54      2070080.80     13483554.54
      2069900.80     13483414.54      2069820.80     13483404.54
      2069770.80     13483314.54      2069620.80     13483174.54
      2069510.80     13483164.54      2069470.80     13483134.54
      2069430.80     13483094.54      2069410.80     13483034.54

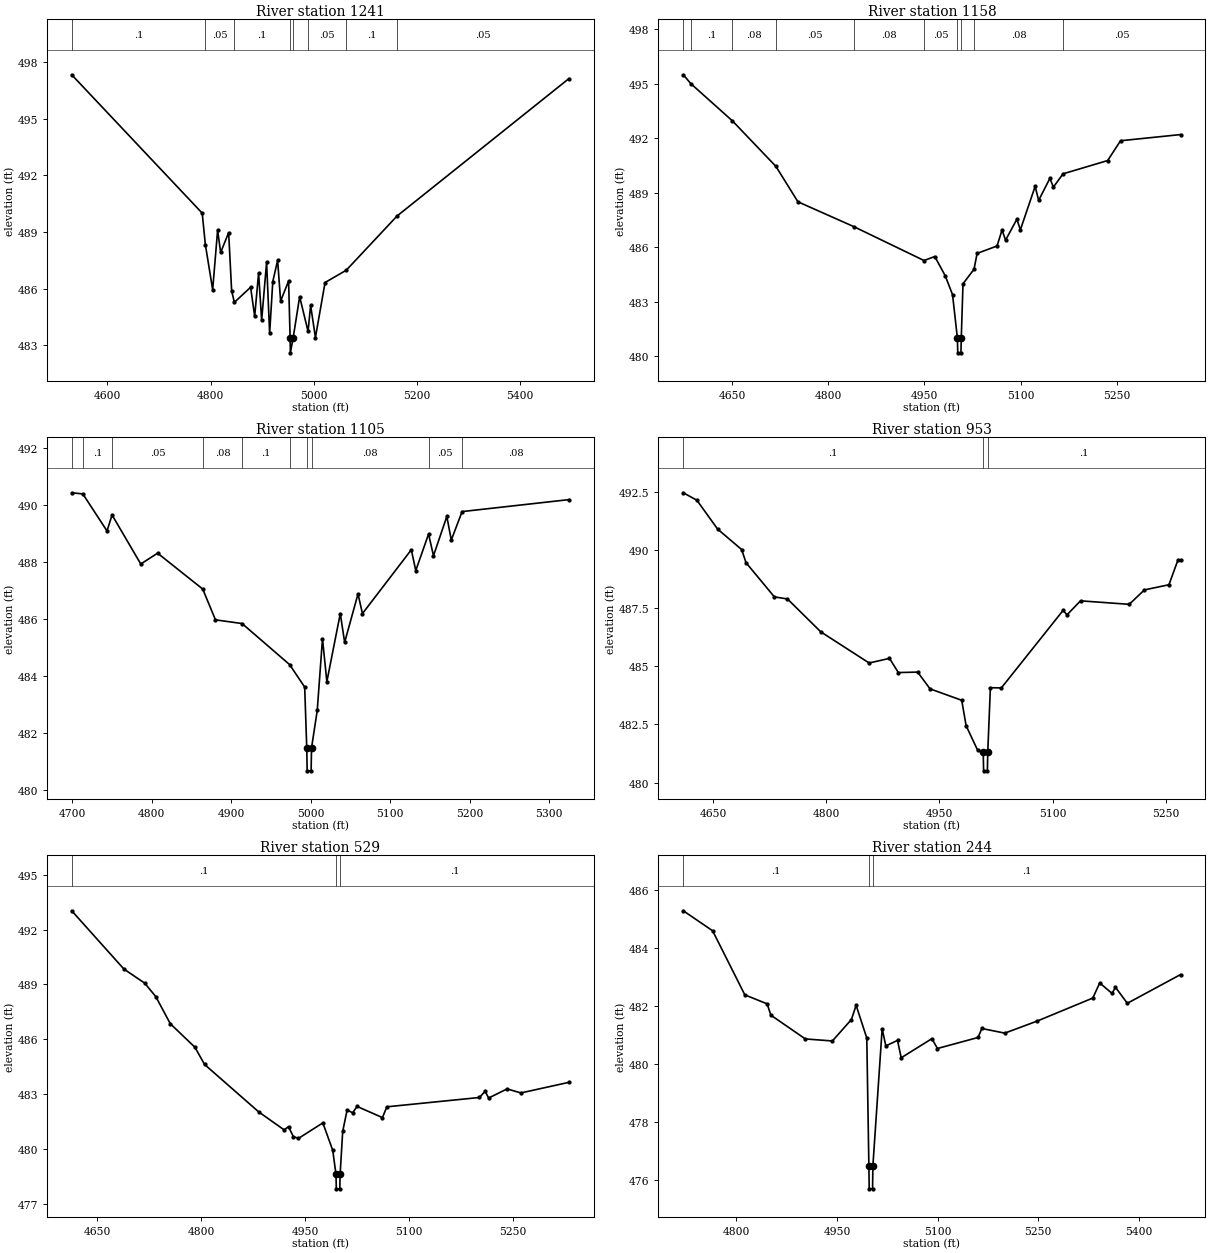
Type RM Length L Ch R = 1,1241,83,83,83
BEGIN DESCRIPTION:
Mapping XS d73be2ce
END DESCRIPTION:
XS GIS Cut Line= 5
      2070688.23     13483232.82      2070483.81     13483394.27
      2070375.74     13483572.65      2070375.74     13483751.04
      2070448.65     13484059.60
#Sta/Elev= 30
  4530.8  497.32  4783.9  490.00  4790.0  488.34  4804.2  485.95  4813.8  489.10
  4819.7  487.92  4835.2  488.97  4841.0  485.89  4846.3  485.28  4877.8  486.08
  4885.7  484.54  4893.3  486.83  4899.2  484.33  4908.8  487.40  4914.7  483.64
  4920.8  486.38  4930.2  487.50  4936.0  485.35  4951.5  486.41  4954.4  483.41
  4954.9  482.61  4960.4  483.41  4972.9  485.58  4989.2  483.75  4994.2  485.12
  5003.5  483.42  5022.2  486.33  5063.3  486.98  5161.9  489.85  5495.3  497.12
#Mann=8,-1,0
  4530.8     0.1       0  4790.0    0.05       0  4846.3     0.1       0
  4954.4    0.04       0  4960.4     0.1       0  4989.2    0.05       0
  5063.3     0.1       0  5161.9    0.05       0
Bank Sta=4954.4,4960.4
Exp/Cntr=0.3,0.1

Type RM Length L Ch R = 1,1158,53,53,53
BEGIN DESCRIPTION:
Mapping XS 1e09d5e5
END DESCRIPTION:
XS GIS Cut Line= 5
      2070540.91     13483237.96      2070395.08     13483390.30
      2070264.87     13483636.40      2070201.07     13483775.72
      2070206.28     13483908.57
#Sta/Elev= 30
  4574.0  495.49  4585.8  495.00  4650.7  492.95  4718.4  490.45  4752.8  488.50
  4839.6  487.14  4949.4  485.27  4966.2  485.49  4982.5  484.43  4993.9  483.39
  5001.5  480.99  5002.0  480.19  5007.0  480.19  5007.5  480.99  5010.2  483.99
  5027.4  484.79  5032.2  485.66  5063.3  486.07  5071.1  486.95  5076.6  486.39
  5094.2  487.54  5099.7  486.96  5122.7  489.35  5128.2  488.58  5145.7  489.79
  5151.2  489.31  5166.2  490.04  5235.8  490.77  5255.9  491.86  5349.5  492.20
#Mann=10,-1,0
  4574.0    0.05       0  4585.8     0.1       0  4650.7    0.08       0
  4718.4    0.05       0  4839.6    0.08       0  4949.4    0.05       0
  5001.5    0.04       0  5007.5    0.05       0  5027.4    0.08       0
  5166.2    0.05       0
Bank Sta=5001.5,5007.5
Exp/Cntr=0.3,0.1

Type RM Length L Ch R = 1,1105,152,152,152
BEGIN DESCRIPTION:
Mapping XS 86984139
END DESCRIPTION:
XS GIS Cut Line= 4
      2070396.56     13483297.06      2070300.22     13483450.69
      2070209.94     13483632.12      2070101.45     13483848.23
#Sta/Elev= 30
  4699.3  490.44  4713.3  490.40  4743.7  489.10  4750.1  489.66  4786.2  487.94
  4807.4  488.32  4864.2  487.06  4880.2  485.98  4913.7  485.85  4973.5  484.41
  4992.5  483.62  4995.1  481.48  4995.6  480.68  5000.6  480.68  5001.1  481.48
  5008.3  482.80  5014.9  485.32  5020.4  483.81  5037.3  486.20  5042.8  485.19
  5059.6  486.89  5065.2  486.20  5126.7  488.44  5132.3  487.71  5148.4  488.99
  5154.6  488.23  5171.4  489.61  5177.0  488.78  5190.6  489.78  5325.1  490.20
#Mann=10,-1,0
  4699.3    0.08       0  4713.3     0.1       0  4750.1    0.05       0
  4864.2    0.08       0  4913.7     0.1       0  4973.5    0.08       0
  4995.1    0.07       0  5001.1    0.08       0  5148.4    0.05       0
  5190.6    0.08       0
Bank Sta=4995.1,5001.1
Exp/Cntr=0.3,0.1

Type RM Length L Ch R = 1,953,424,424,424
BEGIN DESCRIPTION:
Mapping XS f6ab51ac
END DESCRIPTION:
XS GIS Cut Line= 4
      2070284.06     13483240.23      2070177.27     13483300.14
      2070035.34     13483742.85      2070062.70     13483809.29
#Sta/Elev= 30
  4610.4  492.45  4628.4  492.13  4655.9  490.89  4687.8  490.01  4693.5  489.45
  4731.1  487.98  4748.5  487.89  4792.6  486.48  4856.8  485.14  4883.7  485.34
  4895.5  484.73  4921.1  484.75  4937.5  484.03  4979.5  483.54  4985.3  482.45
  5000.5  481.40  5008.0  481.31  5008.5  480.51  5013.5  480.51  5014.0  481.31
  5017.5  484.08  5032.0  484.07  5113.9  487.40  5119.1  487.21  5137.0  487.81
  5201.6  487.66  5221.7  488.28  5254.2  488.50  5266.0  489.55  5269.6  489.55
#Mann=3,-1,0
  4610.4     0.1       0  5008.0    0.07       0  5014.0     0.1       0
Bank Sta=5008,5014
Exp/Cntr=0.3,0.1

Type RM Length L Ch R = 1,529,285,285,285
BEGIN DESCRIPTION:
Mapping XS fde2d40d
END DESCRIPTION:
XS GIS Cut Line= 4
      2070100.36     13483165.10      2069977.95     13483169.44
      2069680.21     13483413.37      2069679.73     13483624.38
#Sta/Elev= 30
  4613.0  493.03  4688.4  489.84  4718.4  489.07  4734.5  488.33  4755.4  486.85
  4791.0  485.56  4804.9  484.62  4883.2  482.02  4919.8  481.04  4926.2  481.21
  4933.2  480.67  4940.6  480.57  4975.8  481.42  4990.1  479.92  4994.8  478.61
  4995.3  477.81  5000.3  477.81  5000.8  478.61  5004.5  480.95  5010.9  482.13
  5018.8  481.97  5025.3  482.32  5061.9  481.71  5068.3  482.30  5202.0  482.81
  5210.3  483.15  5215.3  482.78  5242.0  483.28  5262.0  483.06  5331.4  483.64
#Mann=3,-1,0
  4613.0     0.1       0  4994.8    0.07       0  5000.8     0.1       0
Bank Sta=4994.8,5000.8
Exp/Cntr=0.3,0.1

Type RM Length L Ch R = 1,244,189,189,189
BEGIN DESCRIPTION:
Mapping XS 55ab179b
END DESCRIPTION:
XS GIS Cut Line= 4
      2069748.16     13482981.94      2069655.25     13482996.70
      2069504.21     13483322.22      2069574.02     13483601.91
#Sta/Elev= 30
  4720.9  485.28  4764.6  484.59  4812.6  482.38  4845.9  482.07  4851.4  481.68
  4902.8  480.86  4943.1  480.79  4971.5  481.53  4978.5  482.02  4994.4  480.89
  4997.5  476.49  4998.0  475.69  5003.0  475.69  5003.5  476.49  5017.3  481.21
  5022.8  480.62  5040.2  480.81  5045.7  480.21  5091.5  480.87  5099.7  480.53
  5160.2  480.91  5165.9  481.22  5200.1  481.06  5248.8  481.48  5331.3  482.27
  5341.6  482.79  5360.0  482.43  5365.1  482.64  5382.8  482.09  5462.1  483.08
#Mann=3,-1,0
  4720.9     0.1       0  4997.5    0.07       0  5003.5     0.1       0
Bank Sta=4997.5,5003.5
Exp/Cntr=0.3,0.1

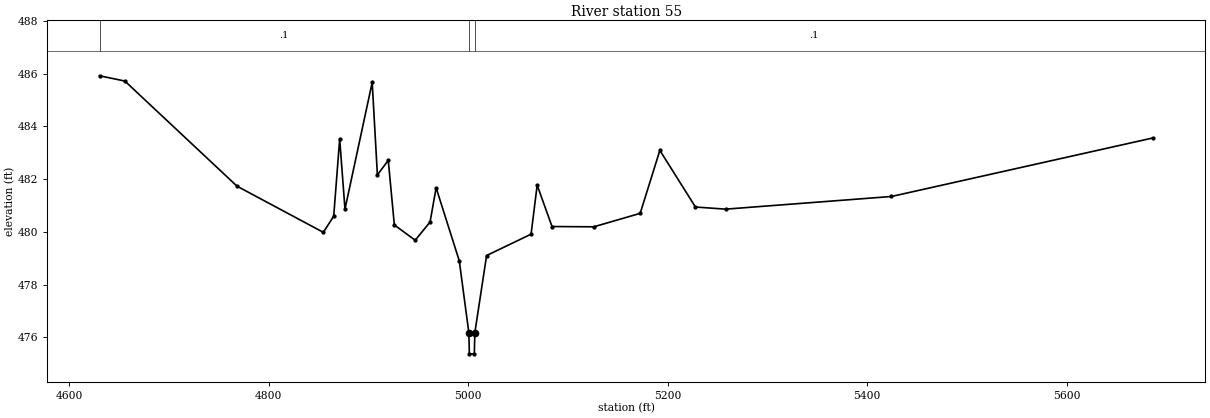
Type RM Length L Ch R = 1,55,0,0,0
BEGIN DESCRIPTION:
UNT 141 in Lagunillas Cr Wtrshd 1.0
END DESCRIPTION:
XS GIS Cut Line= 4
      2069749.27     13482928.31      2069476.93     13483012.94
      2069337.50     13483214.32      2069520.66     13483707.26
#Sta/Elev= 30
  4630.2  485.92  4655.6  485.72  4768.1  481.73  4854.6  479.98  4865.0  480.59
  4871.0  483.52  4876.3  480.86  4903.6  485.67  4908.8  482.16  4919.7  482.71
  4925.8  480.26  4946.7  479.68  4961.6  480.37  4967.7  481.67  4990.9  478.90
  5000.5  476.17  5001.0  475.37  5006.0  475.37  5006.5  476.17  5018.3  479.10
  5062.9  479.91  5069.0  481.77  5083.9  480.20  5125.8  480.19  5172.3  480.70
  5192.0  483.09  5227.7  480.94  5258.0  480.86  5424.2  481.34  5686.2  483.56
#Mann=3,-1,0
  4630.2     0.1       0  5000.5    0.07       0  5006.5     0.1       0
Bank Sta=5000.5,5006.5
Exp/Cntr=0.3,0.1

Chan Stop Cuts=-1