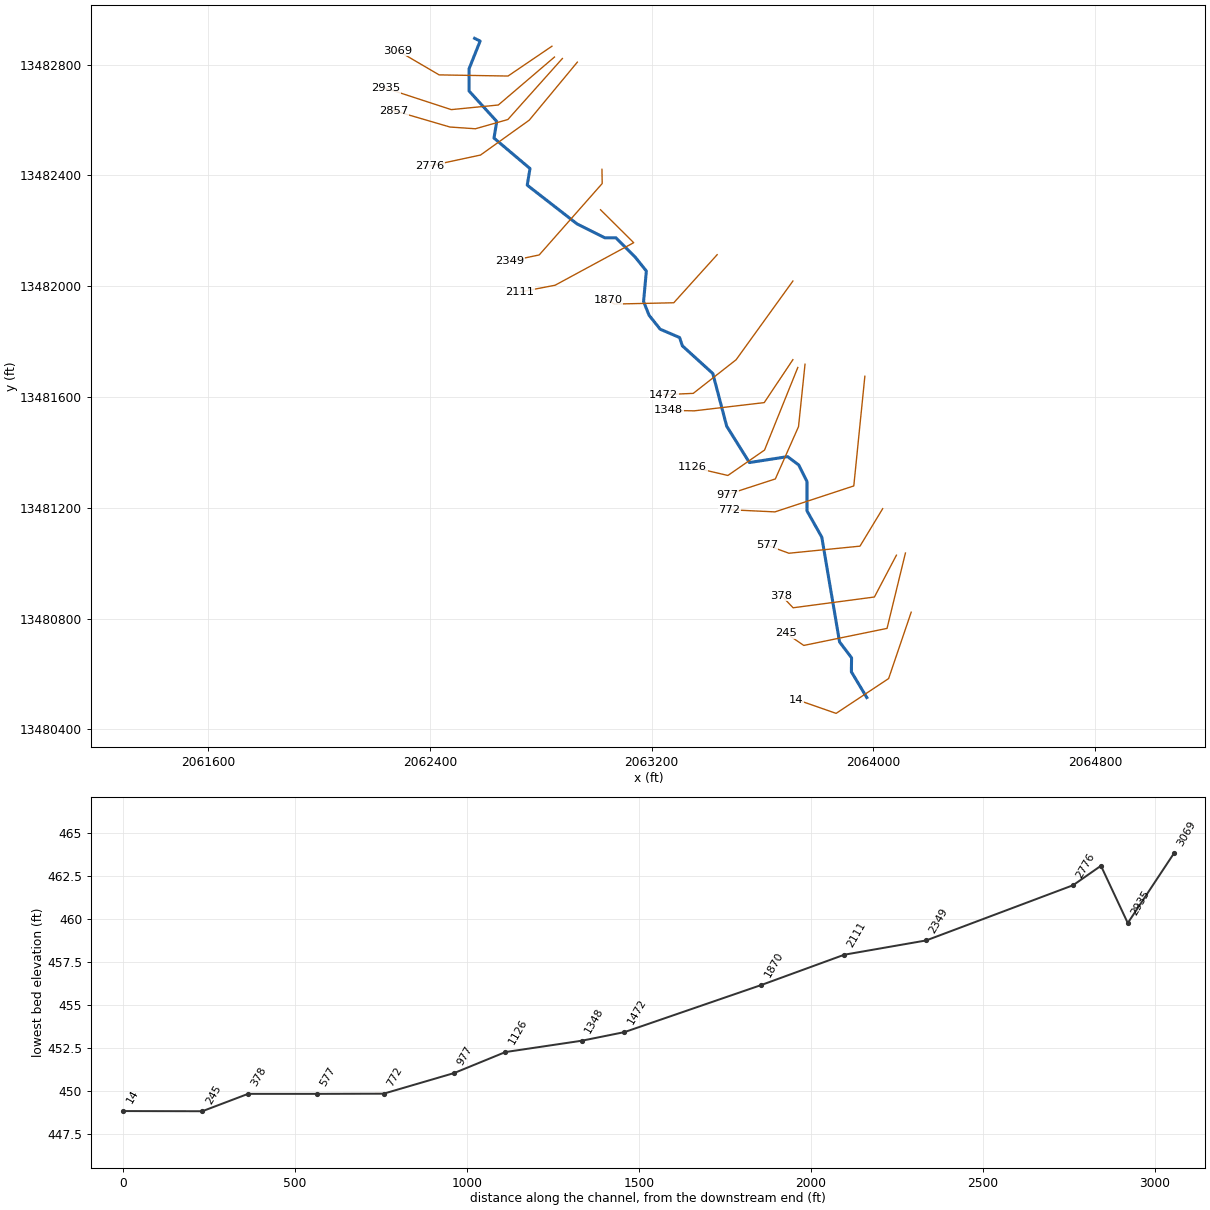
--- UNT 143 in Lagunillas Cr Wtrshd.prj (project) ---

Proj Title=UNT 143 in Lagunillas Cr Wtrshd Base Level Engineering
Current Plan=p01
Default Exp/Contr=0.3,0.1
English Units
Geom File=g01
Flow File=f01
Plan File=p01
BEGIN DESCRIPTION:
UNT 143 in Lagunillas Cr Wtrshd
END DESCRIPTION:

--- UNT 143 in Lagunillas Cr Wtrshd.p01 (plan) ---

Plan Title=Multiple Run
Short Identifier=Multiple
Geom File=g01
Flow File=f01
Subcritical Flow
K Sum by GR= 0
Std Step Tol= 0.01
Critical Tol= 0.01
Num of Std Step Trials= 20
Max Error Tol= 0.3
Flow Tol Ratio= 0.001
Split Flow NTrial= 30
Split Flow Tol= 0.02
Split Flow Ratio= 0.02
Log Output Level= 0
Friction Slope Method= 1
Unsteady Friction Slope Method= 2
Unsteady Bridges Friction Slope Method= 1
Parabolic Critical Depth
Global Vel Dist=  1 , 1 , 1
Global Log Level= 0
CheckData=True
Encroach Param= -1, 0, 0, 0
BEGIN DESCRIPTION:
Multiple Run
END DESCRIPTION:

--- UNT 143 in Lagunillas Cr Wtrshd.f01 (steady flow) ---

Flow Title=Multiple
Number of Profiles=7
Profile Names=10-year,25-year,50-year,1pct_min,100-year,1pct_plu,500-year
River Rch & RM= UNT 143 in Lagun,Reach-1,3069
      92     120     141      83     166     332     233
Boundary for River Rch & Prof#=UNT 143 in Lagun,Reach-1,1
Up Type=0
Dn Type=3
Dn Slope=0.005
Boundary for River Rch & Prof#=UNT 143 in Lagun,Reach-1,2
Up Type=0
Dn Type=3
Dn Slope=0.005
Boundary for River Rch & Prof#=UNT 143 in Lagun,Reach-1,3
Up Type=0
Dn Type=3
Dn Slope=0.005
Boundary for River Rch & Prof#=UNT 143 in Lagun,Reach-1,4
Up Type=0
Dn Type=3
Dn Slope=0.005
Boundary for River Rch & Prof#=UNT 143 in Lagun,Reach-1,5
Up Type=0
Dn Type=3
Dn Slope=0.005
Boundary for River Rch & Prof#=UNT 143 in Lagun,Reach-1,6
Up Type=0
Dn Type=3
Dn Slope=0.005
Boundary for River Rch & Prof#=UNT 143 in Lagun,Reach-1,7
Up Type=0
Dn Type=3
Dn Slope=0.005

--- UNT 143 in Lagunillas Cr Wtrshd.g01 (geometry) ---

Geom Title=Existing Conditions

River Reach=UNT 143 in Lagun,Reach-1
Reach XY= 30
      2062560.80     13482894.54      2062580.80     13482884.54
      2062540.80     13482784.54      2062540.80     13482704.54
      2062640.80     13482594.54      2062630.80     13482534.54
      2062760.80     13482424.54      2062750.80     13482364.54
      2062930.80     13482224.54      2063030.80     13482174.54
      2063070.80     13482174.54      2063140.80     13482104.54
      2063180.80     13482054.54      2063170.80     13481944.54
      2063190.80     13481894.54      2063230.80     13481844.54
      2063300.80     13481814.54      2063310.80     13481784.54
      2063420.80     13481684.54      2063470.80     13481494.54
      2063552.78     13481363.17      2063690.80     13481384.54
      2063730.80     13481354.54      2063760.80     13481294.54
      2063760.80     13481188.69      2063814.06     13481094.07
      2063878.30     13480715.60      2063921.70     13480658.31
      2063920.83     13480607.96      2063976.55     13480514.99

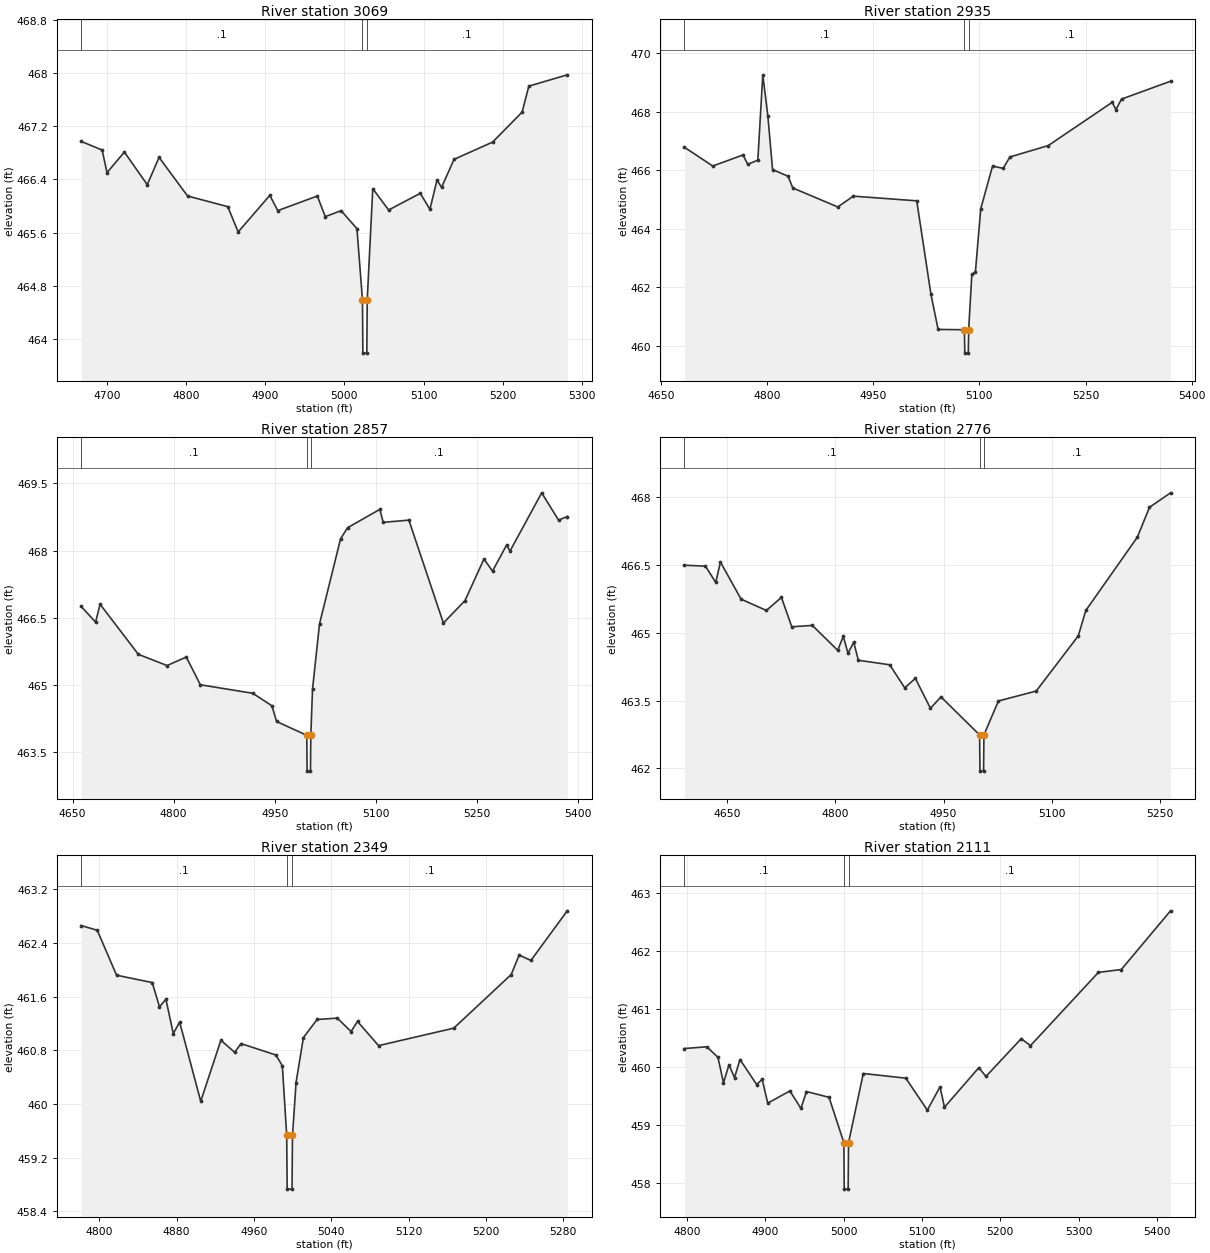
Type RM Length L Ch R = 1,3069,134,134,134
BEGIN DESCRIPTION:
Mapping XS f82e1102
END DESCRIPTION:
XS GIS Cut Line= 4
      2062840.08     13482866.11      2062681.47     13482758.42
      2062432.86     13482762.59      2062283.18     13482850.21
#Sta/Elev= 30
  4667.6  466.97  4694.1  466.84  4700.1  466.50  4722.1  466.81  4751.0  466.32
  4765.9  466.73  4801.9  466.15  4852.7  465.99  4865.8  465.61  4905.8  466.16
  4915.8  465.93  4965.8  466.15  4975.8  465.84  4995.8  465.93  5015.8  465.66
  5022.8  464.59  5023.3  463.79  5028.3  463.79  5028.8  464.59  5035.8  466.26
  5055.8  465.94  5095.8  466.19  5108.0  465.95  5116.9  466.39  5122.7  466.28
  5138.4  466.70  5187.2  466.96  5224.4  467.41  5232.9  467.80  5281.4  467.97
#Mann=3,-1,0
  4667.6     0.1       0  5022.8    0.07       0  5028.8     0.1       0
Bank Sta=5022.8,5028.8
Exp/Cntr=0.3,0.1

Type RM Length L Ch R = 1,2935,78,78,78
BEGIN DESCRIPTION:
Mapping XS 9fb5e40b
END DESCRIPTION:
XS GIS Cut Line= 4
      2062849.16     13482827.02      2062646.40     13482653.87
      2062476.61     13482637.21      2062239.21     13482714.81
#Sta/Elev= 30
  4683.1  466.78  4723.1  466.14  4765.9  466.52  4772.5  466.20  4786.8  466.34
  4793.8  469.26  4801.0  467.84  4807.6  466.02  4829.6  465.79  4836.2  465.39
  4899.8  464.74  4921.8  465.11  5011.4  464.95  5031.5  461.75  5041.6  460.55
  5078.8  460.54  5079.3  459.74  5084.3  459.74  5084.8  460.54  5089.3  462.44
  5094.3  462.51  5101.9  464.68  5118.6  466.14  5133.6  466.06  5143.1  466.45
  5197.3  466.84  5287.7  468.32  5292.9  468.07  5300.9  468.43  5370.1  469.04
#Mann=3,-1,0
  4683.1     0.1       0  5078.8    0.07       0  5084.8     0.1       0
Bank Sta=5078.8,5084.8
Exp/Cntr=0.3,0.1

Type RM Length L Ch R = 1,2857,81,81,81
BEGIN DESCRIPTION:
Mapping XS 548a2f11
END DESCRIPTION:
XS GIS Cut Line= 5
      2062877.80     13482821.81      2062680.87     13482601.44
      2062563.68     13482568.11      2062472.01     13482574.36
      2062268.60     13482633.88
#Sta/Elev= 30
  4662.8  466.75  4684.1  466.40  4690.8  466.80  4747.6  465.68  4790.2  465.43
  4818.7  465.62  4839.6  465.00  4917.3  464.81  4945.8  464.53  4952.6  464.18
  4997.5  463.87  4998.0  463.07  5003.0  463.07  5003.5  463.87  5006.0  464.90
  5016.4  466.36  5047.6  468.26  5058.0  468.51  5105.9  468.92  5110.9  468.63
  5149.0  468.68  5200.2  466.38  5232.2  466.88  5260.4  467.81  5273.1  467.54
  5293.9  468.12  5299.1  467.99  5346.1  469.29  5371.1  468.68  5384.0  468.76
#Mann=3,-1,0
  4662.8     0.1       0  4997.5    0.07       0  5003.5     0.1       0
Bank Sta=4997.5,5003.5
Exp/Cntr=0.3,0.1

Type RM Length L Ch R = 1,2776,427,427,427
BEGIN DESCRIPTION:
Mapping XS ccb78a14
END DESCRIPTION:
XS GIS Cut Line= 4
      2062931.73     13482808.59      2062758.10     13482599.14
      2062582.31     13482473.27      2062400.01     13482434.21
#Sta/Elev= 30
  4590.4  466.49  4619.5  466.47  4633.8  466.11  4640.3  466.56  4669.0  465.74
  4704.1  465.49  4725.0  465.78  4739.3  465.13  4767.9  465.16  4803.1  464.61
  4810.9  464.92  4817.4  464.54  4825.3  464.79  4831.8  464.39  4875.3  464.29
  4896.2  463.78  4910.9  463.99  4931.8  463.33  4946.5  463.58  5000.1  462.74
  5000.6  461.94  5005.6  461.94  5006.1  462.74  5026.2  463.49  5078.7  463.71
  5137.1  464.93  5147.5  465.49  5219.1  467.11  5235.9  467.77  5265.1  468.09
#Mann=3,-1,0
  4590.4     0.1       0  5000.1    0.07       0  5006.1     0.1       0
Bank Sta=5000.1,5006.1
Exp/Cntr=0.3,0.1

Type RM Length L Ch R = 1,2349,238,238,238
BEGIN DESCRIPTION:
Mapping XS e7a975d5
END DESCRIPTION:
XS GIS Cut Line= 4
      2063020.58     13482421.63      2063021.45     13482370.41
      2062794.02     13482112.60      2062688.23     13482090.42
#Sta/Elev= 30
  4781.2  462.66  4797.8  462.59  4817.8  461.92  4854.7  461.81  4862.2  461.45
  4868.9  461.56  4876.5  461.05  4883.1  461.22  4904.9  460.04  4925.8  460.95
  4940.0  460.77  4946.7  460.90  4982.7  460.73  4989.4  460.57  4993.9  459.53
  4994.4  458.73  4999.4  458.73  4999.9  459.53  5003.6  460.32  5011.2  460.99
  5025.4  461.26  5046.3  461.28  5060.5  461.08  5067.2  461.23  5089.0  460.87
  5166.8  461.13  5226.3  461.93  5234.5  462.22  5246.7  462.14  5284.3  462.88
#Mann=3,-1,0
  4781.2     0.1       0  4993.9    0.07       0  4999.9     0.1       0
Bank Sta=4993.9,4999.9
Exp/Cntr=0.3,0.1

Type RM Length L Ch R = 1,2111,241,241,241
BEGIN DESCRIPTION:
Mapping XS 5d2aada3
END DESCRIPTION:
XS GIS Cut Line= 4
      2063015.40     13482275.76      2063135.16     13482156.87
      2062851.31     13482003.22      2062724.54     13481978.91
#Sta/Elev= 30
  4796.8  460.32  4825.3  460.35  4839.5  460.17  4846.6  459.73  4853.6  460.04
  4860.7  459.82  4867.7  460.13  4889.0  459.70  4896.0  459.79  4903.1  459.38
  4931.4  459.59  4945.5  459.29  4952.6  459.58  4981.4  459.48  5000.3  458.70
  5000.8  457.90  5005.8  457.90  5006.3  458.70  5025.1  459.89  5079.4  459.81
  5106.9  459.26  5123.1  459.66  5128.8  459.31  5172.6  459.99  5181.8  459.84
  5226.8  460.49  5238.6  460.37  5325.3  461.63  5354.6  461.68  5417.4  462.69
#Mann=3,-1,0
  4796.8     0.1       0  5000.3    0.07       0  5006.3     0.1       0
Bank Sta=5000.3,5006.3
Exp/Cntr=0.3,0.1

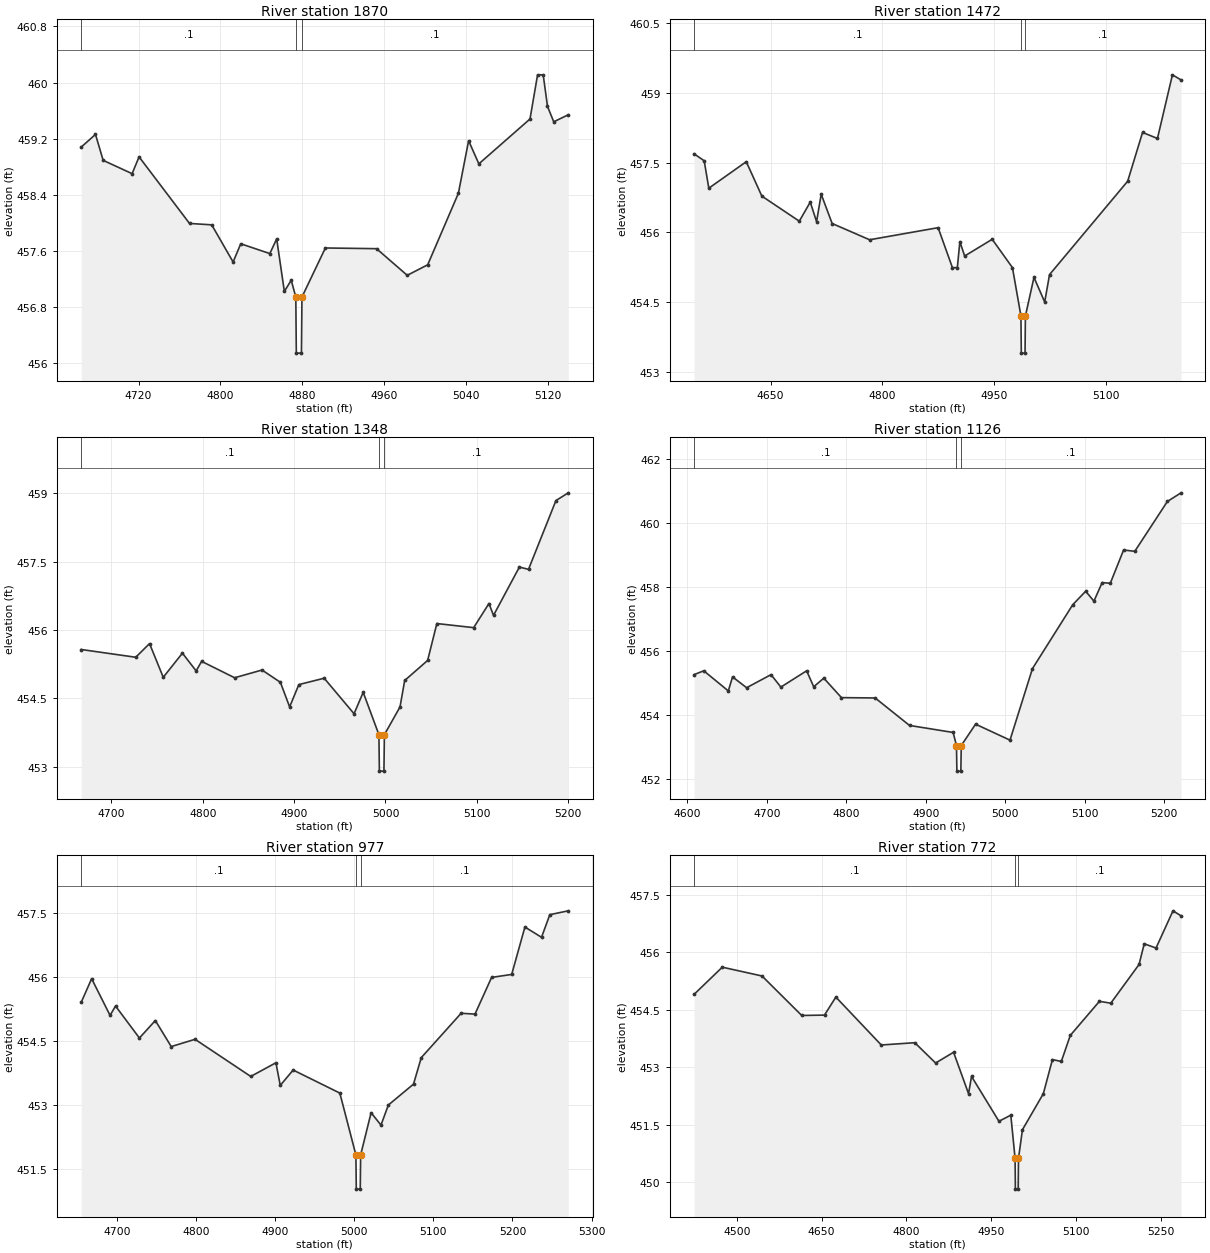
Type RM Length L Ch R = 1,1870,398,398,398
BEGIN DESCRIPTION:
Mapping XS 088b24ad
END DESCRIPTION:
XS GIS Cut Line= 4
      2063436.42     13482113.51      2063279.82     13481939.98
      2063065.24     13481935.30      2063042.33     13481950.74
#Sta/Elev= 30
  4664.0  459.08  4677.9  459.26  4685.4  458.89  4713.7  458.70  4720.5  458.94
  4769.8  457.99  4791.5  457.97  4812.4  457.44  4819.9  457.70  4848.3  457.56
  4855.0  457.77  4862.5  457.02  4869.2  457.18  4873.7  456.94  4874.2  456.14
  4879.2  456.14  4879.7  456.94  4902.6  457.64  4952.6  457.63  4982.6  457.25
  5002.6  457.40  5032.6  458.42  5042.6  459.17  5052.6  458.84  5102.6  459.48
  5110.0  460.11  5115.5  460.11  5119.7  459.66  5125.8  459.44  5140.0  459.54
#Mann=3,-1,0
  4664.0     0.1       0  4873.7    0.07       0  4879.7     0.1       0
Bank Sta=4873.7,4879.7
Exp/Cntr=0.3,0.1

Type RM Length L Ch R = 1,1472,124,124,124
BEGIN DESCRIPTION:
Mapping XS 1864c894
END DESCRIPTION:
XS GIS Cut Line= 4
      2063709.85     13482018.44      2063504.82     13481734.26
      2063350.14     13481612.90      2063243.37     13481608.21
#Sta/Elev= 30
  4547.2  457.69  4560.8  457.54  4567.0  456.95  4617.3  457.52  4638.2  456.78
  4688.5  456.24  4703.2  456.65  4711.7  456.23  4717.9  456.82  4732.6  456.19
  4782.9  455.84  4874.9  456.10  4894.1  455.24  4900.7  455.24  4904.1  455.80
  4910.5  455.49  4947.5  455.85  4974.7  455.24  4986.1  454.20  4986.6  453.40
  4991.6  453.40  4992.1  454.20  5003.6  455.03  5018.0  454.50  5024.5  455.09
  5129.4  457.10  5149.4  458.15  5169.4  458.02  5189.5  459.39  5201.1  459.28
#Mann=3,-1,0
  4547.2     0.1       0  4986.1    0.07       0  4992.1     0.1       0
Bank Sta=4986.1,4992.1
Exp/Cntr=0.3,0.1

Type RM Length L Ch R = 1,1348,222,222,222
BEGIN DESCRIPTION:
Mapping XS 2dcd0e39
END DESCRIPTION:
XS GIS Cut Line= 4
      2063709.81     13481734.53      2063606.39     13481579.57
      2063353.78     13481549.88      2063261.55     13481551.44
#Sta/Elev= 30
  4667.1  455.57  4726.7  455.40  4741.8  455.70  4756.8  454.96  4777.8  455.49
  4792.8  455.10  4798.8  455.31  4834.9  454.95  4864.9  455.12  4885.0  454.85
  4895.1  454.31  4905.2  454.80  4932.9  454.94  4965.6  454.16  4975.6  454.63
  4992.8  453.70  4993.3  452.90  4998.3  452.90  4998.8  453.70  5015.9  454.31
  5021.0  454.89  5046.1  455.33  5056.2  456.14  5096.5  456.05  5113.2  456.58
  5118.2  456.32  5146.5  457.38  5156.5  457.33  5186.5  458.84  5200.0  459.01
#Mann=3,-1,0
  4667.1     0.1       0  4992.8    0.07       0  4998.8     0.1       0
Bank Sta=4992.8,4998.8
Exp/Cntr=0.3,0.1

Type RM Length L Ch R = 1,1126,149,149,149
BEGIN DESCRIPTION:
Mapping XS 9fc1a366
END DESCRIPTION:
XS GIS Cut Line= 4
      2063727.54     13481706.33      2063607.43     13481408.21
      2063475.14     13481316.55      2063348.30     13481346.15
#Sta/Elev= 30
  4608.6  455.26  4620.8  455.38  4651.7  454.75  4657.0  455.19  4674.7  454.85
  4705.4  455.26  4717.8  454.87  4750.2  455.38  4759.1  454.88  4771.8  455.15
  4794.0  454.54  4836.4  454.53  4879.6  453.67  4934.5  453.45  4938.7  453.04
  4939.2  452.24  4944.2  452.24  4944.7  453.04  4962.7  453.71  5006.0  453.21
  5034.3  455.45  5085.0  457.45  5101.2  457.87  5111.6  457.56  5121.9  458.14
  5132.2  458.12  5148.9  459.16  5163.0  459.12  5204.0  460.68  5221.2  460.95
#Mann=3,-1,0
  4608.6     0.1       0  4938.7    0.07       0  4944.7     0.1       0
Bank Sta=4938.7,4944.7
Exp/Cntr=0.3,0.1

Type RM Length L Ch R = 1,977,205,205,205
BEGIN DESCRIPTION:
Mapping XS 66929e22
END DESCRIPTION:
XS GIS Cut Line= 4
      2063753.58     13481718.07      2063730.14     13481492.78
      2063646.49     13481304.05      2063472.88     13481247.60
#Sta/Elev= 30
  4655.1  455.40  4668.2  455.95  4691.5  455.09  4698.4  455.31  4728.6  454.56
  4748.7  454.97  4768.8  454.36  4798.9  454.53  4869.3  453.66  4901.1  453.98
  4906.6  453.45  4922.9  453.81  4981.9  453.27  5002.2  451.82  5002.7  451.02
  5007.7  451.02  5008.2  451.82  5021.4  452.81  5033.9  452.52  5043.2  452.99
  5075.0  453.48  5084.8  454.10  5135.2  455.14  5152.7  455.12  5173.7  455.98
  5199.1  456.05  5215.8  457.16  5236.8  456.92  5247.3  457.45  5270.6  457.54
#Mann=3,-1,0
  4655.1     0.1       0  5002.2    0.07       0  5008.2     0.1       0
Bank Sta=5002.2,5008.2
Exp/Cntr=0.3,0.1

Type RM Length L Ch R = 1,772,195,195,195
BEGIN DESCRIPTION:
Mapping XS e4a3feb1
END DESCRIPTION:
XS GIS Cut Line= 4
      2063969.62     13481674.70      2063929.69     13481278.82
      2063644.97     13481185.07      2063480.70     13481192.91
#Sta/Elev= 30
  4424.3  454.90  4474.3  455.61  4544.6  455.38  4614.9  454.35  4655.2  454.36
  4675.3  454.83  4755.7  453.58  4815.0  453.64  4851.9  453.11  4883.7  453.39
  4910.2  452.31  4915.5  452.76  4964.0  451.59  4985.0  451.75  4992.6  450.62
  4993.1  449.82  4998.1  449.82  4998.6  450.62  5005.6  451.37  5042.6  452.31
  5058.7  453.20  5074.4  453.15  5090.3  453.83  5141.9  454.72  5162.0  454.67
  5212.0  455.68  5221.2  456.22  5242.1  456.11  5272.1  457.08  5286.4  456.95
#Mann=3,-1,0
  4424.3     0.1       0  4992.6    0.07       0  4998.6     0.1       0
Bank Sta=4992.6,4998.6
Exp/Cntr=0.3,0.1

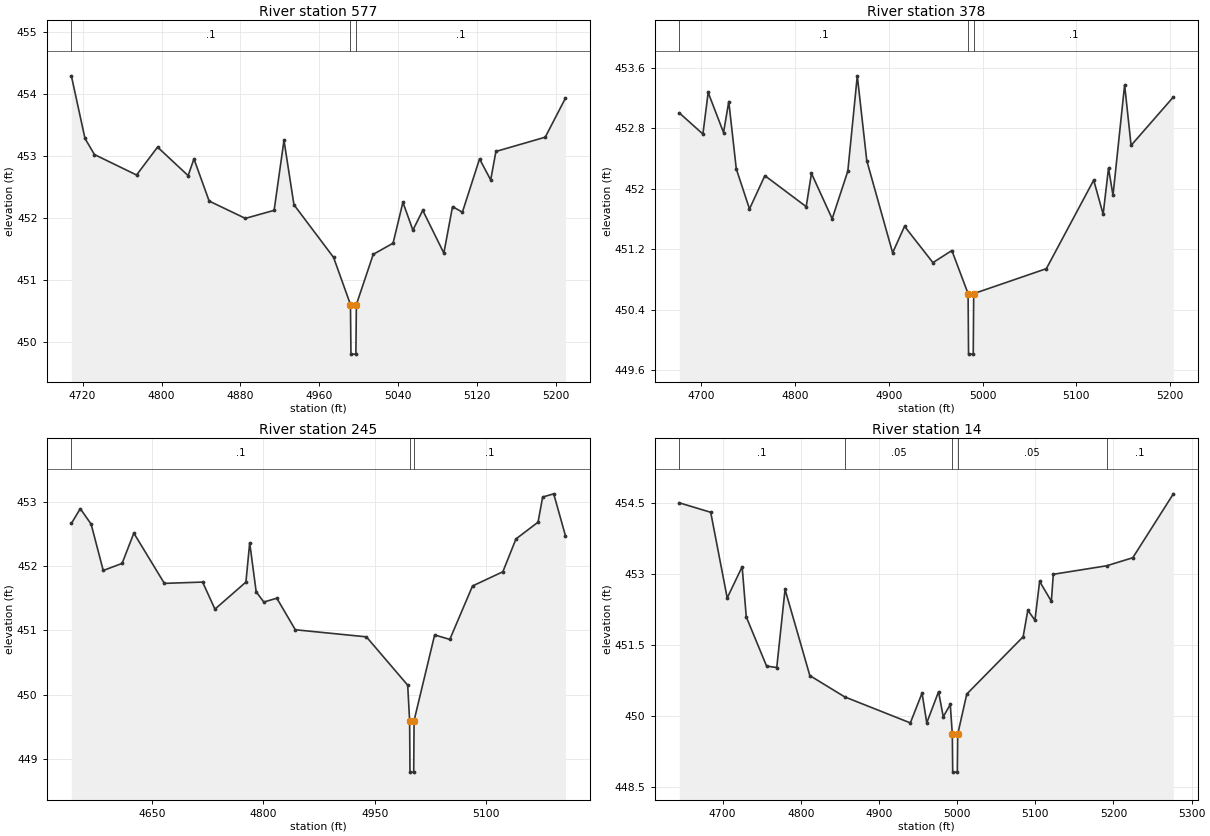
Type RM Length L Ch R = 1,577,199,199,199
BEGIN DESCRIPTION:
Mapping XS 55121cc5
END DESCRIPTION:
XS GIS Cut Line= 4
      2064034.05     13481196.81      2063952.03     13481061.40
      2063695.45     13481035.82      2063615.78     13481064.98
#Sta/Elev= 30
  4708.6  454.30  4722.4  453.29  4732.0  453.03  4774.7  452.70  4796.0  453.15
  4827.0  452.69  4832.9  452.96  4848.3  452.28  4885.0  452.00  4914.2  452.13
  4924.2  453.26  4934.3  452.22  4974.5  451.37  4991.6  450.61  4992.1  449.81
  4997.1  449.81  4997.6  450.61  5014.7  451.42  5034.8  451.60  5044.8  452.26
  5054.9  451.81  5064.9  452.13  5086.3  451.44  5095.1  452.19  5105.1  452.10
  5122.5  452.96  5133.8  452.62  5139.1  453.08  5189.1  453.31  5209.6  453.94
#Mann=3,-1,0
  4708.6     0.1       0  4991.6    0.07       0  4997.6     0.1       0
Bank Sta=4991.6,4997.6
Exp/Cntr=0.3,0.1

Type RM Length L Ch R = 1,378,133,133,133
BEGIN DESCRIPTION:
Mapping XS 6f6347a8
END DESCRIPTION:
XS GIS Cut Line= 4
      2064083.52     13481028.82      2064004.11     13480877.80
      2063710.55     13480838.94      2063668.90     13480882.63
#Sta/Elev= 30
  4676.4  453.00  4701.6  452.72  4707.2  453.27  4723.6  452.74  4729.2  453.15
  4737.2  452.26  4751.3  451.73  4767.7  452.17  4811.8  451.76  4817.4  452.20
  4839.5  451.60  4856.2  452.23  4866.3  453.49  4876.4  452.37  4904.0  451.15
  4916.7  451.50  4947.0  451.02  4967.2  451.18  4984.5  450.61  4985.0  449.81
  4990.0  449.81  4990.5  450.61  5068.0  450.94  5118.5  452.11  5128.6  451.66
  5134.3  452.27  5139.1  451.91  5151.5  453.37  5158.4  452.57  5203.5  453.21
#Mann=3,-1,0
  4676.4     0.1       0  4984.5    0.07       0  4990.5     0.1       0
Bank Sta=4984.5,4990.5
Exp/Cntr=0.3,0.1

Type RM Length L Ch R = 1,245,231,231,231
BEGIN DESCRIPTION:
Mapping XS 256ca613
END DESCRIPTION:
XS GIS Cut Line= 4
      2064116.09     13481036.67      2064049.68     13480764.52
      2063749.09     13480703.01      2063684.55     13480747.25
#Sta/Elev= 30
  4541.7  452.66  4553.7  452.89  4568.3  452.65  4584.6  451.93  4610.0  452.04
  4625.8  452.51  4666.9  451.73  4718.4  451.75  4735.0  451.33  4776.7  451.75
  4781.8  452.36  4790.5  451.60  4800.8  451.44  4818.3  451.50  4843.2  451.01
  4938.9  450.90  4994.5  450.15  4997.1  449.60  4997.6  448.80  5002.6  448.80
  5003.1  449.60  5030.8  450.93  5051.2  450.86  5081.8  451.69  5122.6  451.91
  5140.3  452.42  5170.0  452.68  5176.2  453.07  5191.1  453.12  5206.9  452.47
#Mann=3,-1,0
  4541.7     0.1       0  4997.1    0.07       0  5003.1     0.1       0
Bank Sta=4997.1,5003.1
Exp/Cntr=0.3,0.1

Type RM Length L Ch R = 1,14,0,0,0
BEGIN DESCRIPTION:
UNT 143 in Lagunillas Cr Wtrshd 20.0
END DESCRIPTION:
XS GIS Cut Line= 4
      2064136.91     13480823.08      2064055.39     13480583.43
      2063865.80     13480457.74      2063722.79     13480507.72
#Sta/Elev= 30
  4644.5  454.50  4684.7  454.30  4705.8  452.49  4724.9  453.15  4730.2  452.09
  4756.2  451.05  4769.2  451.02  4779.8  452.67  4811.5  450.85  4856.1  450.40
  4940.1  449.85  4955.1  450.48  4961.1  449.85  4976.2  450.51  4982.2  449.98
  4991.2  450.24  4993.8  449.61  4994.3  448.81  5000.2  448.81  5000.7  449.61
  5012.3  450.46  5084.4  451.67  5090.4  452.23  5099.5  452.02  5105.5  452.84
  5120.5  452.42  5123.0  452.99  5191.3  453.17  5224.7  453.34  5276.6  454.69
#Mann=5,-1,0
  4644.5     0.1       0  4856.1    0.05       0  4993.8    0.04       0
  5000.7    0.05       0  5191.3     0.1       0
Bank Sta=4993.8,5000.7
Exp/Cntr=0.3,0.1

Chan Stop Cuts=-1