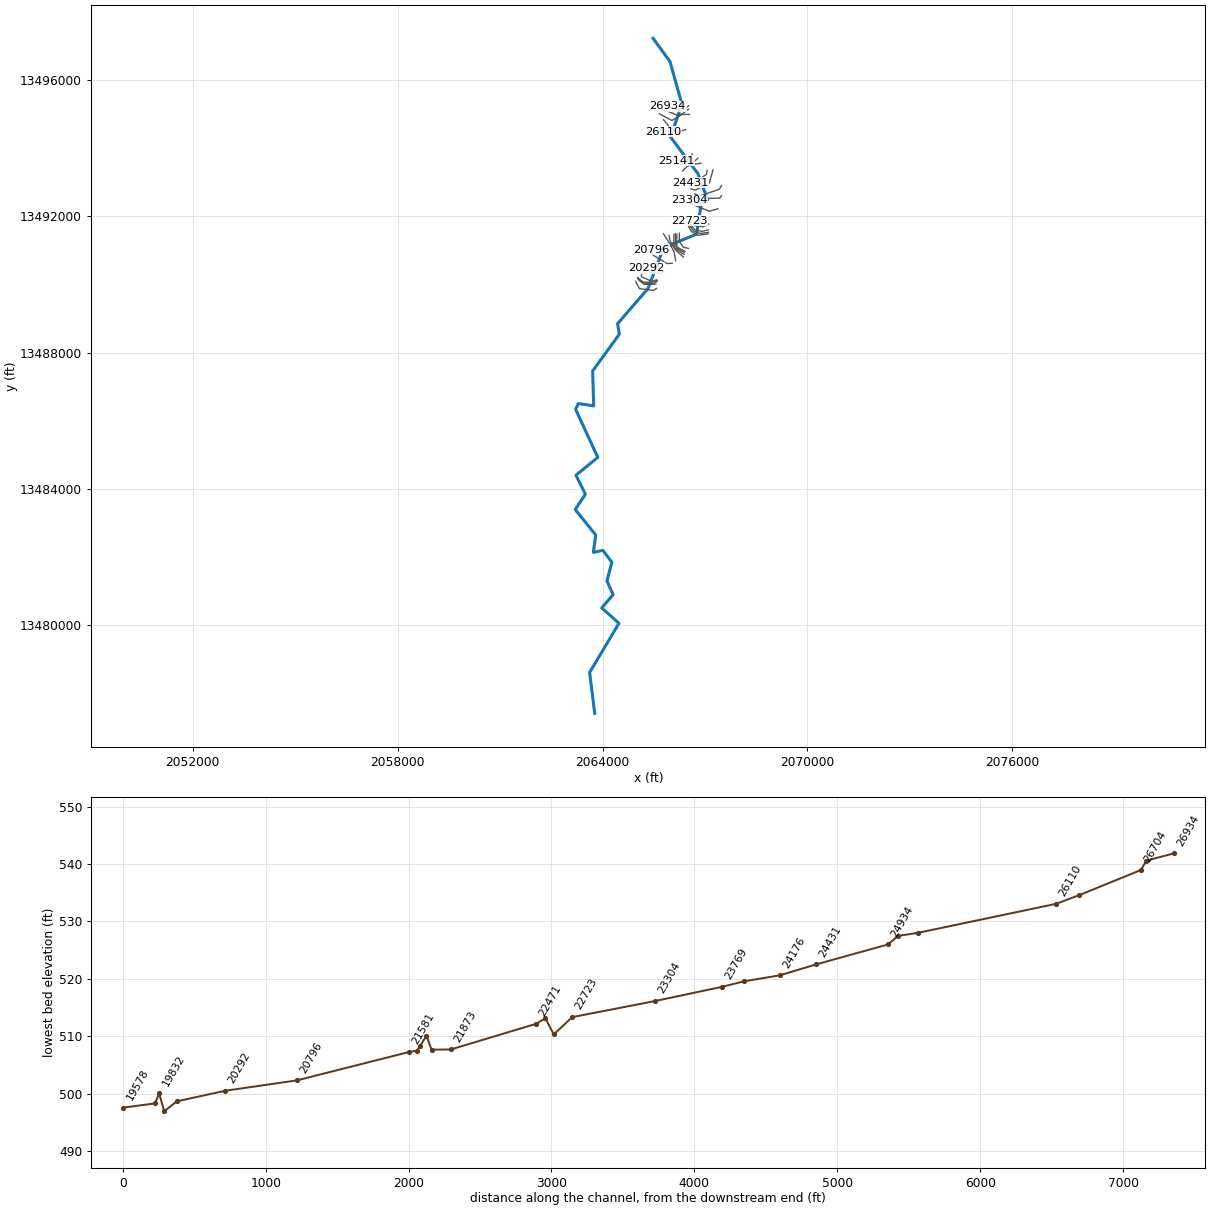
--- UNT 144 in Lagunillas Cr Wtrshd.prj (project) ---

Proj Title=UNT 144 in Lagunillas Cr Wtrshd Base Level Engineering
Current Plan=p01
Default Exp/Contr=0.3,0.1
English Units
Geom File=g01
Flow File=f01
Plan File=p01
BEGIN DESCRIPTION:
UNT 144 in Lagunillas Cr Wtrshd
END DESCRIPTION:

--- UNT 144 in Lagunillas Cr Wtrshd.p01 (plan) ---

Plan Title=Multiple Run
Short Identifier=Multiple
Geom File=g01
Flow File=f01
Subcritical Flow
K Sum by GR= 0
Std Step Tol= 0.01
Critical Tol= 0.01
Num of Std Step Trials= 20
Max Error Tol= 0.3
Flow Tol Ratio= 0.001
Split Flow NTrial= 30
Split Flow Tol= 0.02
Split Flow Ratio= 0.02
Log Output Level= 0
Friction Slope Method= 1
Unsteady Friction Slope Method= 2
Unsteady Bridges Friction Slope Method= 1
Parabolic Critical Depth
Global Vel Dist=  1 , 1 , 1
Global Log Level= 0
CheckData=True
Encroach Param= -1, 0, 0, 0
BEGIN DESCRIPTION:
Multiple Run
END DESCRIPTION:

--- UNT 144 in Lagunillas Cr Wtrshd.f01 (steady flow) ---

Flow Title=Multiple
Number of Profiles=7
Profile Names=10-year,25-year,50-year,1pct_min,100-year,1pct_plu,500-year
River Rch & RM= UNT 144 in Lagun,Reach-1,26934
     128     169     201     120     239     477     342
River Rch & RM= UNT 144 in Lagun,Reach-1,19244
     177     239     288     174     347     692     510
River Rch & RM= UNT 144 in Lagun,Reach-1,17186
     254     348     425     259     516    1030     773
River Rch & RM= UNT 144 in Lagun,Reach-1,4647
     299     414     509     311     621    1240     941
River Rch & RM= UNT 144 in Lagun,Reach-1,3801
     445     628     782     485     967    1930    1502
River Rch & RM= UNT 144 in Lagun,Reach-1,2688
     484     686     857     532    1062    2119    1656
Boundary for River Rch & Prof#=UNT 144 in Lagun,Reach-1,1
Up Type=0
Dn Type=3
Dn Slope=0.005
Boundary for River Rch & Prof#=UNT 144 in Lagun,Reach-1,2
Up Type=0
Dn Type=3
Dn Slope=0.005
Boundary for River Rch & Prof#=UNT 144 in Lagun,Reach-1,3
Up Type=0
Dn Type=3
Dn Slope=0.005
Boundary for River Rch & Prof#=UNT 144 in Lagun,Reach-1,4
Up Type=0
Dn Type=3
Dn Slope=0.005
Boundary for River Rch & Prof#=UNT 144 in Lagun,Reach-1,5
Up Type=0
Dn Type=3
Dn Slope=0.005
Boundary for River Rch & Prof#=UNT 144 in Lagun,Reach-1,6
Up Type=0
Dn Type=3
Dn Slope=0.005
Boundary for River Rch & Prof#=UNT 144 in Lagun,Reach-1,7
Up Type=0
Dn Type=3
Dn Slope=0.005

--- UNT 144 in Lagunillas Cr Wtrshd.g01 (geometry) ---

Geom Title=Existing Conditions

River Reach=UNT 144 in Lagun,Reach-1
Reach XY= 30
      2065479.68     13497206.59      2065975.00     13496525.00
      2066325.00     13495275.00      2065990.80     13494314.54
      2066790.80     13493244.54      2067080.80     13492474.54
      2066891.29     13492366.09      2066755.87     13491469.56
      2065790.80     13491074.54      2065330.80     13489874.54
      2064440.80     13488844.54      2064490.80     13488534.54
      2063709.26     13487457.93      2063740.80     13486434.54
      2063290.80     13486504.54      2063210.80     13486334.54
      2063860.80     13484924.54      2063220.80     13484404.54
      2063496.89     13483845.52      2063199.67     13483398.30
      2063800.37     13482650.38      2063729.53     13482144.82
      2064010.09     13482201.77      2064272.66     13481851.41
      2064128.20     13481309.02      2064308.25     13480903.54
      2063976.55     13480514.99      2064480.80     13480064.54
      2063620.80     13478624.54      2063770.80     13477424.54

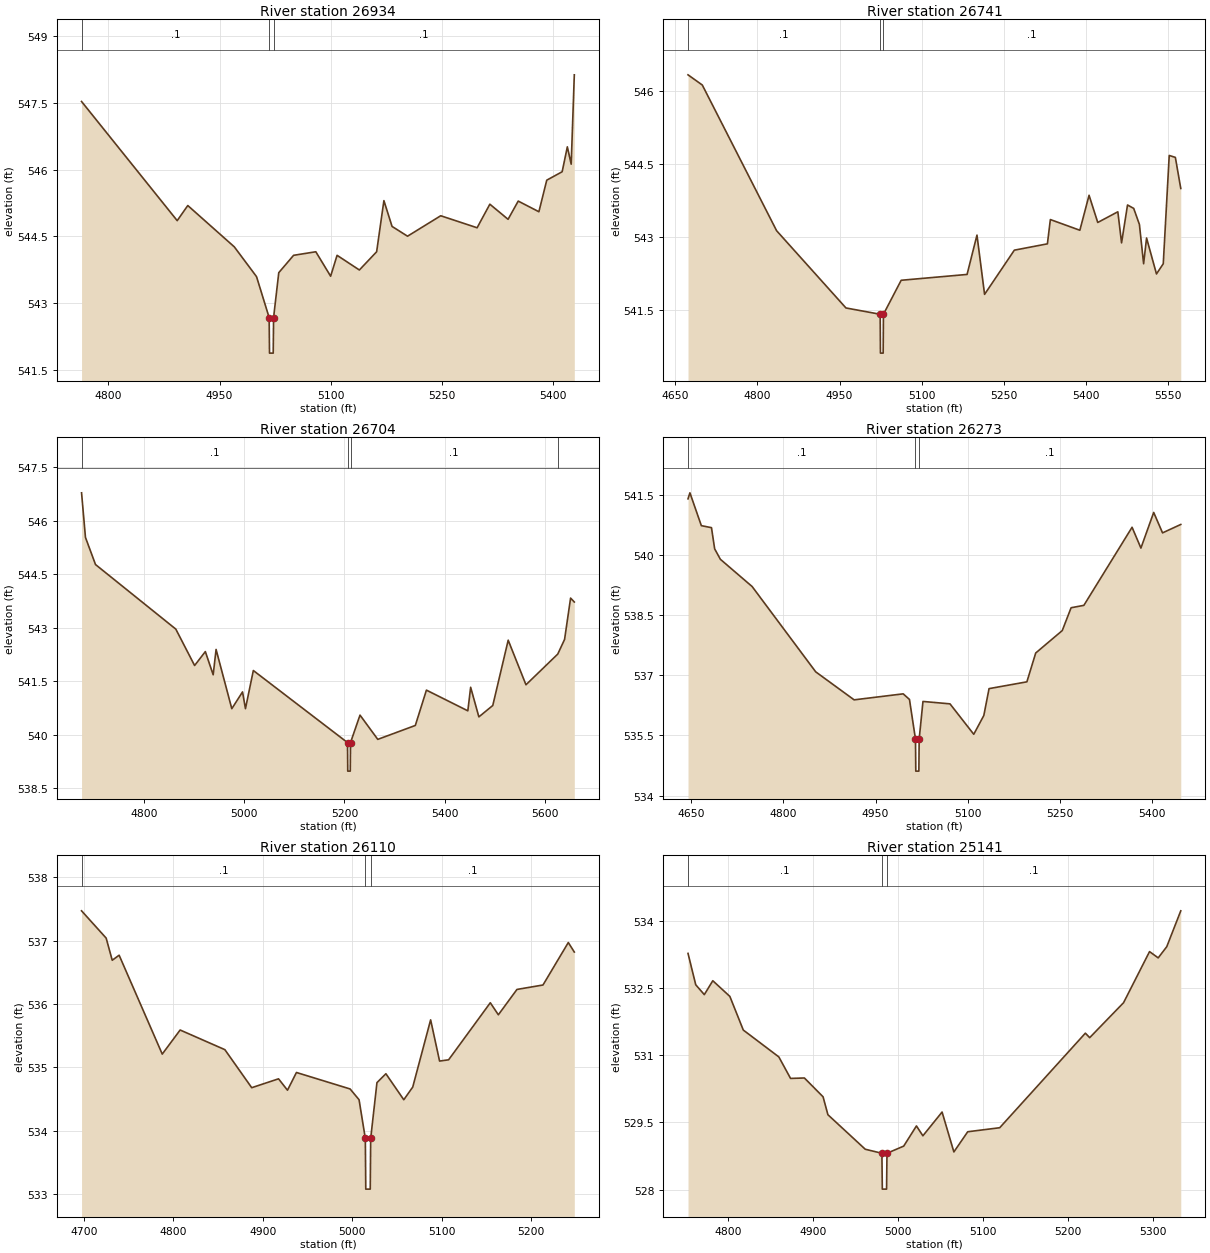
Type RM Length L Ch R = 1,26934,193,193,193
BEGIN DESCRIPTION:
Mapping XS b830b0d2
END DESCRIPTION:
XS GIS Cut Line= 4
      2066521.89     13495230.52      2066393.77     13495122.74
      2066212.52     13495121.69      2065909.32     13495212.19
#Sta/Elev= 30
  4763.8  547.53  4892.9  544.85  4907.2  545.19  4970.0  544.26  5000.0  543.59
  5017.0  542.67  5017.5  541.87  5022.5  541.87  5023.0  542.67  5030.0  543.68
  5050.0  544.07  5080.0  544.15  5100.0  543.60  5108.7  544.07  5138.8  543.74
  5162.1  544.15  5171.9  545.30  5182.9  544.72  5203.8  544.50  5248.6  544.96
  5297.7  544.69  5314.9  545.22  5339.5  544.88  5353.2  545.29  5381.1  545.05
  5391.7  545.76  5412.5  545.95  5419.5  546.51  5424.7  546.12  5428.9  548.13
#Mann=3,-1,0
  4763.8     0.1       0  5017.0    0.07       0  5023.0     0.1       0
Bank Sta=5017,5023
Exp/Cntr=0.3,0.1

Type RM Length L Ch R = 1,26741,37,37,37
BEGIN DESCRIPTION:
Mapping XS 2d965300
END DESCRIPTION:
XS GIS Cut Line= 4
      2066517.96     13495127.64      2066367.72     13495017.53
      2066214.95     13494941.49      2065715.57     13495155.95
#Sta/Elev= 30
  4673.1  546.34  4699.2  546.13  4835.0  543.13  4961.7  541.54  5024.2  541.41
  5024.7  540.61  5029.7  540.61  5030.2  541.41  5062.6  542.11  5183.0  542.23
  5201.1  543.04  5215.0  541.82  5269.4  542.73  5329.8  542.86  5335.2  543.36
  5389.1  543.14  5405.9  543.86  5421.8  543.30  5458.5  543.52  5465.3  542.88
  5476.2  543.66  5487.5  543.59  5497.9  543.26  5505.6  542.45  5511.0  542.98
  5529.1  542.24  5541.5  542.45  5552.4  544.68  5563.6  544.64  5573.5  544.00
#Mann=3,-1,0
  4673.1     0.1       0  5024.2    0.07       0  5030.2     0.1       0
Bank Sta=5024.2,5030.2
Exp/Cntr=0.3,0.1

Type RM Length L Ch R = 1,26704,431,431,431
BEGIN DESCRIPTION:
Mapping XS 6af5e629
END DESCRIPTION:
XS GIS Cut Line= 4
      2066542.79     13494975.32      2066333.00     13494977.94
      2066032.40     13494800.05      2065658.47     13494996.74
#Sta/Elev= 30
  4676.2  546.78  4684.0  545.53  4704.0  544.77  4864.0  542.96  4901.4  541.94
  4922.8  542.33  4938.4  541.68  4944.2  542.39  4975.5  540.73  4996.9  541.20
  5002.7  540.73  5018.4  541.80  5206.0  539.78  5206.5  538.98  5211.5  538.98
  5212.0  539.78  5230.9  540.55  5266.3  539.87  5341.1  540.26  5363.2  541.25
  5445.7  540.67  5451.3  541.33  5467.7  540.50  5495.4  540.82  5526.1  542.65
  5561.5  541.40  5624.8  542.26  5638.4  542.67  5650.4  543.83  5657.8  543.72
#Mann=4,-1,0
  4676.2     0.1       0  5206.0    0.07       0  5212.0     0.1       0
  5624.8    0.05       0
Bank Sta=5206,5212
Exp/Cntr=0.3,0.1

Type RM Length L Ch R = 1,26273,163,163,163
BEGIN DESCRIPTION:
Mapping XS 43313a56
END DESCRIPTION:
XS GIS Cut Line= 4
      2066435.97     13494530.01      2066214.03     13494471.39
      2065977.23     13494580.42      2065782.34     13494824.26
#Sta/Elev= 30
  4644.6  541.41  4647.7  541.56  4666.3  540.74  4682.8  540.69  4688.0  540.16
  4697.3  539.90  4749.0  539.22  4852.5  537.09  4915.1  536.39  4995.0  536.54
  5005.2  536.40  5015.0  535.41  5015.5  534.61  5020.5  534.61  5021.0  535.41
  5027.2  536.35  5071.2  536.29  5109.9  535.53  5126.3  536.00  5134.8  536.67
  5196.4  536.84  5210.8  537.56  5254.0  538.12  5268.4  538.69  5289.2  538.75
  5367.7  540.70  5382.1  540.18  5402.9  541.07  5417.3  540.56  5447.0  540.77
#Mann=3,-1,0
  4644.6     0.1       0  5015.0    0.07       0  5021.0     0.1       0
Bank Sta=5015,5021
Exp/Cntr=0.3,0.1

Type RM Length L Ch R = 1,26110,969,969,969
BEGIN DESCRIPTION:
Mapping XS e8c62657
END DESCRIPTION:
XS GIS Cut Line= 4
      2066291.81     13494426.95      2066243.89     13494388.76
      2065846.67     13494397.09      2065790.68     13494470.35
#Sta/Elev= 30
  4697.4  537.47  4724.9  537.04  4731.7  536.69  4739.4  536.77  4787.6  535.21
  4807.6  535.59  4857.6  535.28  4887.6  534.68  4917.6  534.82  4927.6  534.64
  4937.6  534.92  4997.6  534.66  5007.6  534.49  5014.6  533.88  5015.1  533.08
  5020.1  533.08  5020.6  533.88  5027.6  534.76  5037.6  534.90  5057.6  534.49
  5067.6  534.69  5087.6  535.75  5097.6  535.10  5107.7  535.12  5154.3  536.02
  5163.3  535.83  5184.1  536.23  5213.2  536.30  5241.5  536.97  5248.2  536.82
#Mann=3,-1,0
  4697.4     0.1       0  5014.6    0.07       0  5020.6     0.1       0
Bank Sta=5014.6,5020.6
Exp/Cntr=0.3,0.1

Type RM Length L Ch R = 1,25141,138,138,138
BEGIN DESCRIPTION:
Mapping XS 6d806556
END DESCRIPTION:
XS GIS Cut Line= 4
      2066626.61     13493824.09      2066617.24     13493731.42
      2066344.82     13493587.30      2066168.84     13493620.95
#Sta/Elev= 30
  4752.5  533.27  4761.6  532.57  4771.7  532.35  4781.7  532.66  4801.8  532.31
  4817.6  531.56  4859.5  530.96  4873.3  530.48  4889.6  530.49  4911.6  530.07
  4917.3  529.67  4961.3  528.90  4980.9  528.81  4981.4  528.01  4986.4  528.01
  4986.9  528.81  5006.6  528.97  5021.6  529.42  5029.2  529.20  5051.8  529.73
  5065.7  528.84  5082.0  529.29  5119.7  529.38  5220.6  531.49  5225.7  531.39
  5265.6  532.17  5296.2  533.31  5306.4  533.17  5316.5  533.42  5333.0  534.22
#Mann=3,-1,0
  4752.5     0.1       0  4980.9    0.07       0  4986.9     0.1       0
Bank Sta=4980.9,4986.9
Exp/Cntr=0.3,0.1

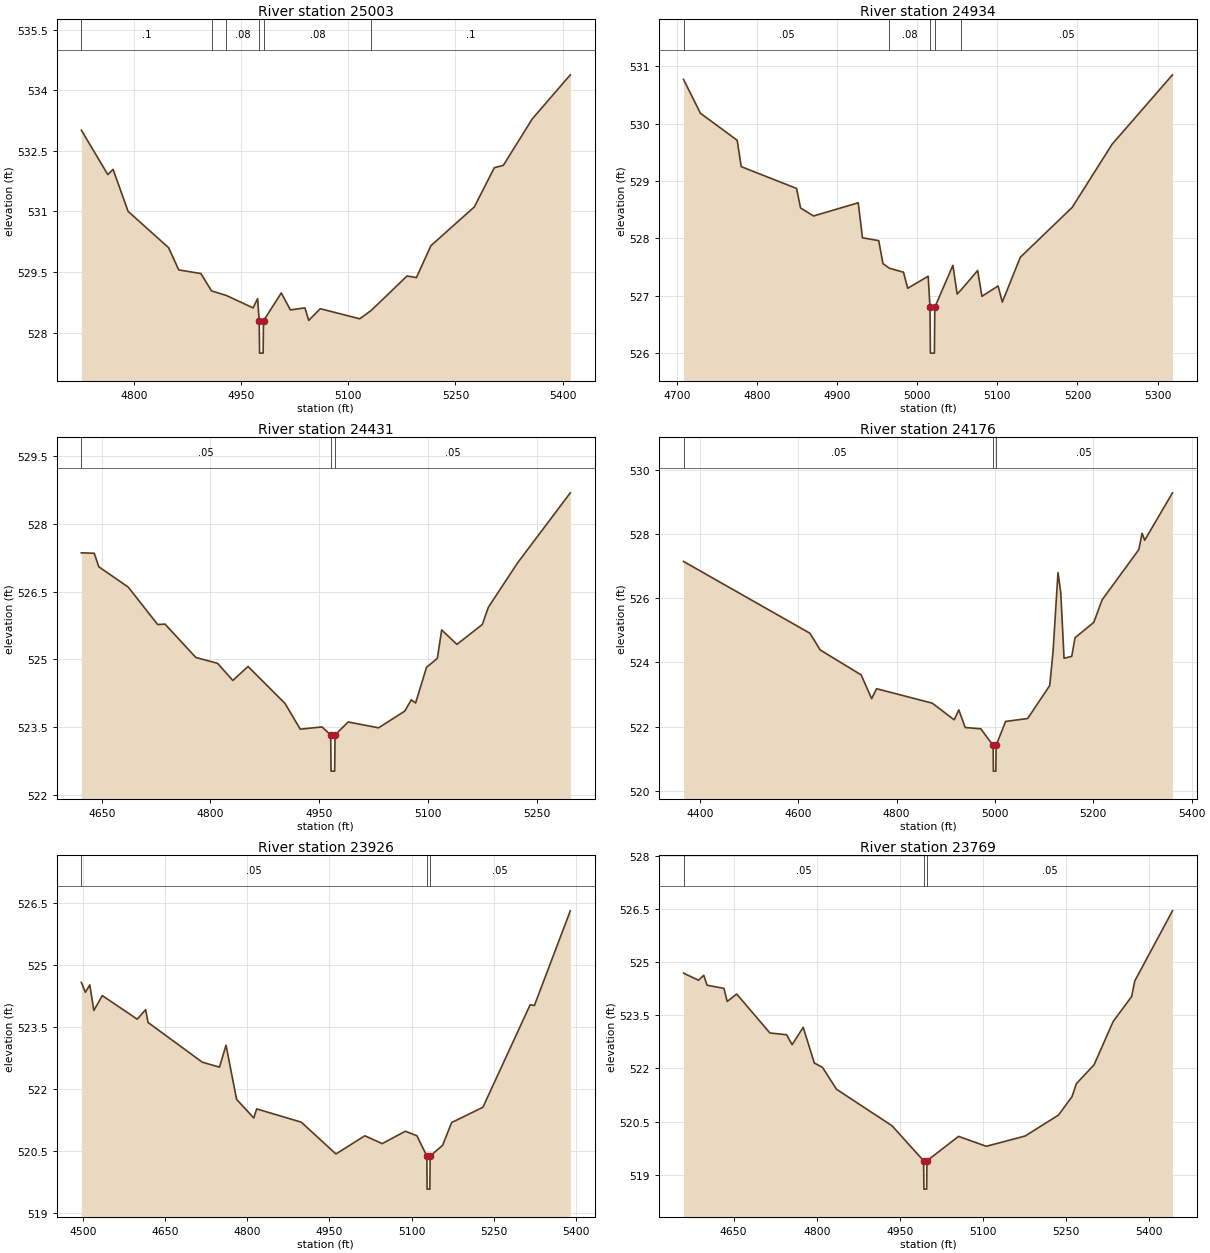
Type RM Length L Ch R = 1,25003,69,69,69
BEGIN DESCRIPTION:
Mapping XS 21fd5430
END DESCRIPTION:
XS GIS Cut Line= 4
      2066790.79     13493691.76      2066675.49     13493586.18
      2066408.13     13493506.32      2066162.54     13493546.94
#Sta/Elev= 30
  4726.4  533.01  4763.4  531.91  4770.8  532.04  4791.8  531.00  4848.5  530.10
  4862.7  529.55  4893.7  529.46  4908.6  529.03  4929.0  528.92  4966.7  528.61
  4973.1  528.84  4975.3  528.29  4975.8  527.49  4980.8  527.49  4981.3  528.29
  5006.2  528.98  5018.9  528.56  5039.3  528.61  5044.6  528.30  5060.7  528.59
  5116.0  528.34  5132.3  528.55  5182.2  529.40  5195.3  529.36  5215.6  530.15
  5276.4  531.11  5304.3  532.08  5317.0  532.14  5357.5  533.29  5410.7  534.38
#Mann=6,-1,0
  4726.4     0.1       0  4908.6    0.05       0  4929.0    0.08       0
  4975.3    0.07       0  4981.3    0.08       0  5132.3     0.1       0
Bank Sta=4975.3,4981.3
Exp/Cntr=0.3,0.1

Type RM Length L Ch R = 1,24934,503,503,503
BEGIN DESCRIPTION:
Mapping XS befbf093
END DESCRIPTION:
XS GIS Cut Line= 4
      2066885.94     13493548.68      2066672.02     13493520.90
      2066478.27     13493452.15      2066340.79     13493322.32
#Sta/Elev= 30
  4708.3  530.77  4729.4  530.18  4775.3  529.71  4780.3  529.25  4849.4  528.87
  4854.4  528.53  4870.6  528.39  4926.4  528.62  4931.7  528.01  4952.0  527.96
  4957.3  527.56  4965.2  527.48  4982.9  527.41  4988.2  527.13  5013.7  527.34
  5016.0  526.80  5016.5  526.00  5021.5  526.00  5022.0  526.80  5044.6  527.53
  5049.9  527.03  5055.3  527.11  5075.5  527.44  5080.8  526.99  5101.0  527.17
  5106.3  526.89  5128.7  527.67  5193.5  528.54  5243.3  529.64  5318.7  530.85
#Mann=5,-1,0
  4708.3    0.05       0  4965.2    0.08       0  5016.0    0.07       0
  5022.0    0.08       0  5055.3    0.05       0
Bank Sta=5016,5022
Exp/Cntr=0.3,0.1

Type RM Length L Ch R = 1,24431,255,255,255
BEGIN DESCRIPTION:
Mapping XS 55eb76ca
END DESCRIPTION:
XS GIS Cut Line= 4
      2067062.82     13493338.74      2067041.98     13493218.04
      2066686.08     13492980.19      2066561.91     13492975.85
#Sta/Elev= 30
  4621.8  527.36  4639.6  527.35  4645.9  527.05  4686.5  526.60  4727.1  525.77
  4737.2  525.78  4779.8  525.04  4809.8  524.91  4830.8  524.53  4851.8  524.84
  4902.9  524.02  4923.9  523.45  4953.9  523.50  4965.9  523.32  4966.4  522.52
  4971.4  522.52  4971.9  523.32  4990.0  523.61  5032.0  523.48  5068.1  523.85
  5077.1  524.10  5083.1  524.03  5098.1  524.82  5113.1  525.02  5119.1  525.65
  5140.1  525.33  5175.1  525.77  5183.4  526.15  5223.5  527.13  5296.6  528.69
#Mann=3,-1,0
  4621.8    0.05       0  4965.9    0.03       0  4971.9    0.05       0
Bank Sta=4965.9,4971.9
Exp/Cntr=0.3,0.1

Type RM Length L Ch R = 1,24176,250,250,250
BEGIN DESCRIPTION:
Mapping XS 12183e06
END DESCRIPTION:
XS GIS Cut Line= 4
      2067236.74     13493351.59      2067120.86     13492958.40
      2066717.22     13492757.88      2066589.76     13492798.19
#Sta/Elev= 30
  4366.7  527.15  4623.8  524.91  4644.6  524.39  4728.0  523.61  4749.2  522.87
  4759.3  523.18  4872.5  522.73  4917.1  522.21  4926.5  522.52  4939.5  521.97
  4971.3  521.93  4996.3  521.41  4996.8  520.61  5001.8  520.61  5002.3  521.41
  5021.7  522.16  5066.5  522.25  5111.4  523.28  5118.1  524.33  5128.2  526.80
  5133.8  526.18  5140.5  524.13  5156.2  524.19  5162.8  524.77  5201.0  525.25
  5217.8  525.95  5292.6  527.52  5299.2  528.03  5304.5  527.81  5361.0  529.29
#Mann=3,-1,0
  4366.7    0.05       0  4996.3    0.03       0  5002.3    0.05       0
Bank Sta=4996.3,5002.3
Exp/Cntr=0.3,0.1

Type RM Length L Ch R = 1,23926,157,157,157
BEGIN DESCRIPTION:
Mapping XS 18ad14c5
END DESCRIPTION:
XS GIS Cut Line= 4
      2067482.83     13492888.07      2067417.74     13492782.62
      2066840.91     13492586.00      2066695.00     13492650.56
#Sta/Elev= 30
  4497.1  524.57  4504.5  524.33  4512.5  524.51  4519.9  523.89  4535.3  524.25
  4599.1  523.68  4614.5  523.91  4618.9  523.60  4717.9  522.64  4749.3  522.52
  4761.3  523.05  4780.6  521.74  4812.0  521.29  4817.2  521.51  4898.6  521.19
  4962.0  520.42  5014.8  520.86  5046.5  520.67  5088.8  520.97  5109.9  520.86
  5128.0  520.37  5128.5  519.57  5133.5  519.57  5134.0  520.37  5156.8  520.63
  5173.3  521.18  5230.4  521.55  5316.7  524.03  5324.4  524.01  5390.0  526.30
#Mann=3,-1,0
  4497.1    0.05       0  5128.0    0.03       0  5134.0    0.05       0
Bank Sta=5128,5134
Exp/Cntr=0.3,0.1

Type RM Length L Ch R = 1,23769,465,465,465
BEGIN DESCRIPTION:
Mapping XS c10ae099
END DESCRIPTION:
XS GIS Cut Line= 4
      2067481.54     13492597.72      2067435.97     13492526.11
      2066837.01     13492503.97      2066658.62     13492589.29
#Sta/Elev= 30
  4559.7  524.69  4586.9  524.49  4596.2  524.63  4602.1  524.35  4632.6  524.26
  4638.5  523.89  4655.6  524.10  4715.6  523.00  4745.6  522.95  4755.6  522.67
  4775.6  523.16  4795.7  522.15  4810.3  522.03  4835.7  521.41  4935.8  520.38
  4992.8  519.39  4993.3  518.59  4998.3  518.59  4998.8  519.39  5055.8  520.08
  5105.9  519.80  5175.9  520.09  5236.0  520.68  5260.4  521.20  5268.4  521.57
  5300.2  522.10  5334.9  523.33  5368.1  524.03  5373.7  524.47  5441.7  526.45
#Mann=3,-1,0
  4559.7    0.05       0  4992.8    0.03       0  4998.8    0.05       0
Bank Sta=4992.8,4998.8
Exp/Cntr=0.3,0.1

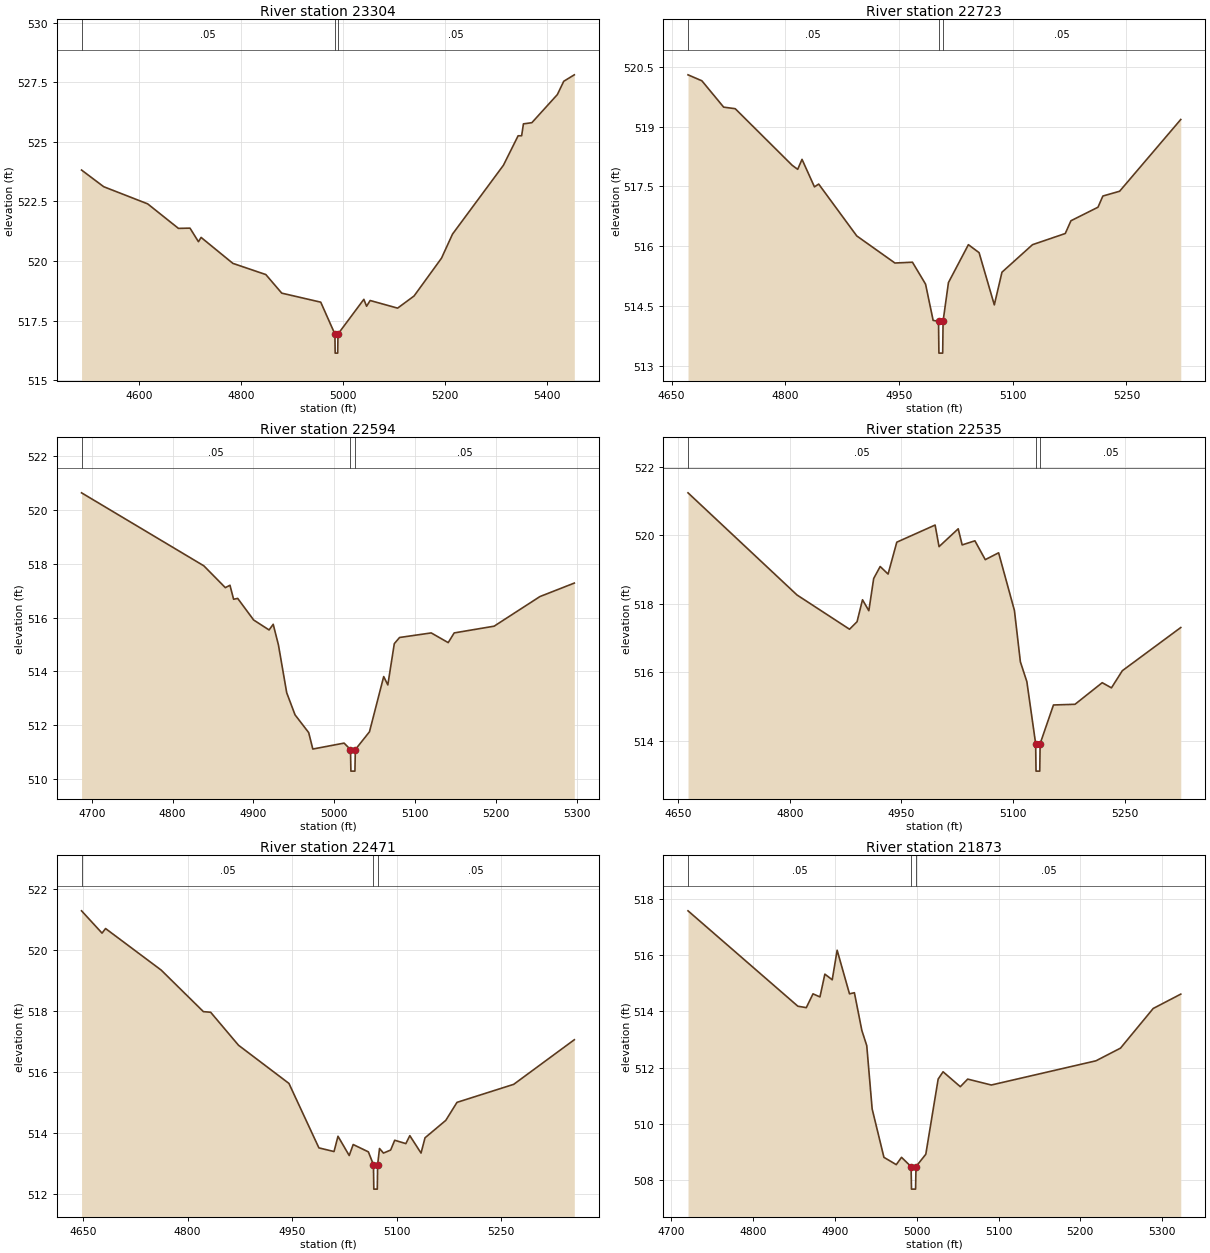
Type RM Length L Ch R = 1,23304,581,581,581
BEGIN DESCRIPTION:
Mapping XS 4e7f748d
END DESCRIPTION:
XS GIS Cut Line= 4
      2067379.96     13492212.30      2067124.77     13492140.69
      2066571.38     13492363.34      2066541.44     13492464.88
#Sta/Elev= 30
  4486.5  523.82  4530.0  523.12  4616.3  522.40  4676.7  521.37  4699.4  521.38
  4716.0  520.81  4721.2  520.99  4783.6  519.90  4848.3  519.43  4879.5  518.65
  4956.1  518.27  4983.9  516.93  4984.4  516.13  4989.4  516.13  4989.9  516.93
  5040.7  518.39  5046.1  518.10  5053.1  518.34  5107.0  518.02  5139.3  518.53
  5193.2  520.12  5214.8  521.13  5314.7  524.02  5343.6  525.26  5350.5  525.26
  5354.0  525.76  5370.6  525.81  5420.6  526.99  5433.2  527.55  5453.9  527.82
#Mann=3,-1,0
  4486.5    0.05       0  4983.9    0.03       0  4989.9    0.05       0
Bank Sta=4983.9,4989.9
Exp/Cntr=0.3,0.1

Type RM Length L Ch R = 1,22723,129,129,129
BEGIN DESCRIPTION:
Mapping XS b22d21ce
END DESCRIPTION:
XS GIS Cut Line= 4
      2067106.58     13491768.32      2066948.78     13491685.02
      2066651.56     13491723.91      2066543.91     13491857.94
#Sta/Elev= 30
  4671.6  520.30  4689.9  520.15  4718.6  519.49  4733.9  519.45  4809.1  518.03
  4816.3  517.93  4822.0  518.18  4838.4  517.49  4844.0  517.56  4894.2  516.26
  4944.6  515.58  4967.7  515.60  4985.0  515.05  4995.0  514.14  5002.1  514.12
  5002.6  513.32  5007.6  513.32  5008.1  514.12  5015.2  515.09  5041.5  516.04
  5055.6  515.84  5075.7  514.53  5085.8  515.35  5126.1  516.04  5169.3  516.32
  5176.8  516.64  5212.5  516.98  5218.9  517.26  5241.0  517.38  5321.7  519.18
#Mann=3,-1,0
  4671.6    0.05       0  5002.1    0.03       0  5008.1    0.05       0
Bank Sta=5002.1,5008.1
Exp/Cntr=0.3,0.1

Type RM Length L Ch R = 1,22594,59,59,59
BEGIN DESCRIPTION:
Mapping XS cf4c81ac
END DESCRIPTION:
XS GIS Cut Line= 4
      2067092.26     13491591.22      2066913.58     13491548.87
      2066707.33     13491594.01      2066562.89     13491753.03
#Sta/Elev= 30
  4687.3  520.63  4838.6  517.92  4865.2  517.11  4870.9  517.20  4875.4  516.68
  4880.5  516.71  4900.2  515.91  4919.3  515.54  4924.4  515.75  4930.9  514.98
  4941.1  513.21  4951.4  512.39  4968.3  511.73  4973.4  511.12  5012.1  511.34
  5020.0  511.10  5020.5  510.30  5025.5  510.30  5026.0  511.10  5043.5  511.76
  5061.1  513.81  5066.2  513.50  5074.2  515.03  5080.7  515.26  5119.9  515.43
  5140.9  515.07  5148.3  515.43  5197.7  515.68  5254.4  516.78  5296.9  517.28
#Mann=3,-1,0
  4687.3    0.05       0  5020.0    0.03       0  5026.0    0.05       0
Bank Sta=5020,5026
Exp/Cntr=0.3,0.1

Type RM Length L Ch R = 1,22535,64,64,64
BEGIN DESCRIPTION:
Mapping XS a4c1d5b3
END DESCRIPTION:
XS GIS Cut Line= 4
      2067100.02     13491519.59      2066858.72     13491489.14
      2066664.97     13491557.20      2066542.81     13491731.11
#Sta/Elev= 30
  4663.6  521.24  4809.8  518.26  4880.3  517.26  4890.4  517.48  4897.7  518.12
  4906.2  517.80  4912.7  518.74  4921.4  519.09  4932.0  518.87  4943.7  519.80
  4995.1  520.30  5000.4  519.67  5026.1  520.19  5031.4  519.72  5048.5  519.84
  5062.4  519.29  5080.3  519.49  5101.5  517.81  5109.5  516.31  5118.2  515.73
  5130.0  513.92  5130.5  513.12  5135.5  513.12  5136.0  513.92  5153.9  515.05
  5182.8  515.07  5219.3  515.70  5231.7  515.55  5246.3  516.05  5324.7  517.31
#Mann=3,-1,0
  4663.6    0.05       0  5130.0    0.03       0  5136.0    0.05       0
Bank Sta=5130,5136
Exp/Cntr=0.3,0.1

Type RM Length L Ch R = 1,22471,598,598,598
BEGIN DESCRIPTION:
Mapping XS a82a338c
END DESCRIPTION:
XS GIS Cut Line= 4
      2067088.33     13491474.02      2066797.61     13491434.98
      2066601.77     13491543.31      2066510.13     13491709.94
#Sta/Elev= 30
  4647.9  521.27  4677.3  520.54  4682.4  520.69  4762.2  519.33  4822.8  517.97
  4833.2  517.95  4873.2  516.87  4945.6  515.62  4988.6  513.51  5010.3  513.39
  5016.0  513.89  5032.1  513.26  5037.8  513.62  5059.6  513.38  5066.9  512.96
  5067.4  512.16  5072.4  512.16  5072.9  512.96  5075.6  513.49  5081.3  513.34
  5091.6  513.44  5097.4  513.76  5113.4  513.65  5119.1  513.91  5135.2  513.34
  5140.9  513.84  5170.7  514.41  5186.8  515.00  5268.2  515.59  5355.2  517.05
#Mann=3,-1,0
  4647.9    0.05       0  5066.9    0.03       0  5072.9    0.05       0
Bank Sta=5066.9,5072.9
Exp/Cntr=0.3,0.1

Type RM Length L Ch R = 1,21873,134,134,134
BEGIN DESCRIPTION:
Mapping XS 1b64c850
END DESCRIPTION:
XS GIS Cut Line= 4
      2066515.36     13491049.55      2066364.14     13491087.19
      2066247.39     13491264.27      2066249.77     13491498.73
#Sta/Elev= 30
  4720.4  517.57  4854.7  514.18  4865.0  514.13  4873.2  514.62  4881.7  514.51
  4887.7  515.32  4896.7  515.12  4902.7  516.17  4917.8  514.62  4923.8  514.66
  4932.9  513.32  4938.9  512.78  4945.5  510.53  4959.9  508.81  4975.0  508.55
  4981.4  508.81  4993.1  508.48  4993.6  507.68  4998.6  507.68  4999.1  508.48
  5011.1  508.92  5026.2  511.59  5032.2  511.85  5053.3  511.32  5062.3  511.59
  5091.2  511.38  5219.1  512.24  5249.1  512.69  5289.1  514.10  5322.8  514.61
#Mann=3,-1,0
  4720.4    0.05       0  4993.1    0.03       0  4999.1    0.05       0
Bank Sta=4993.1,4999.1
Exp/Cntr=0.3,0.1

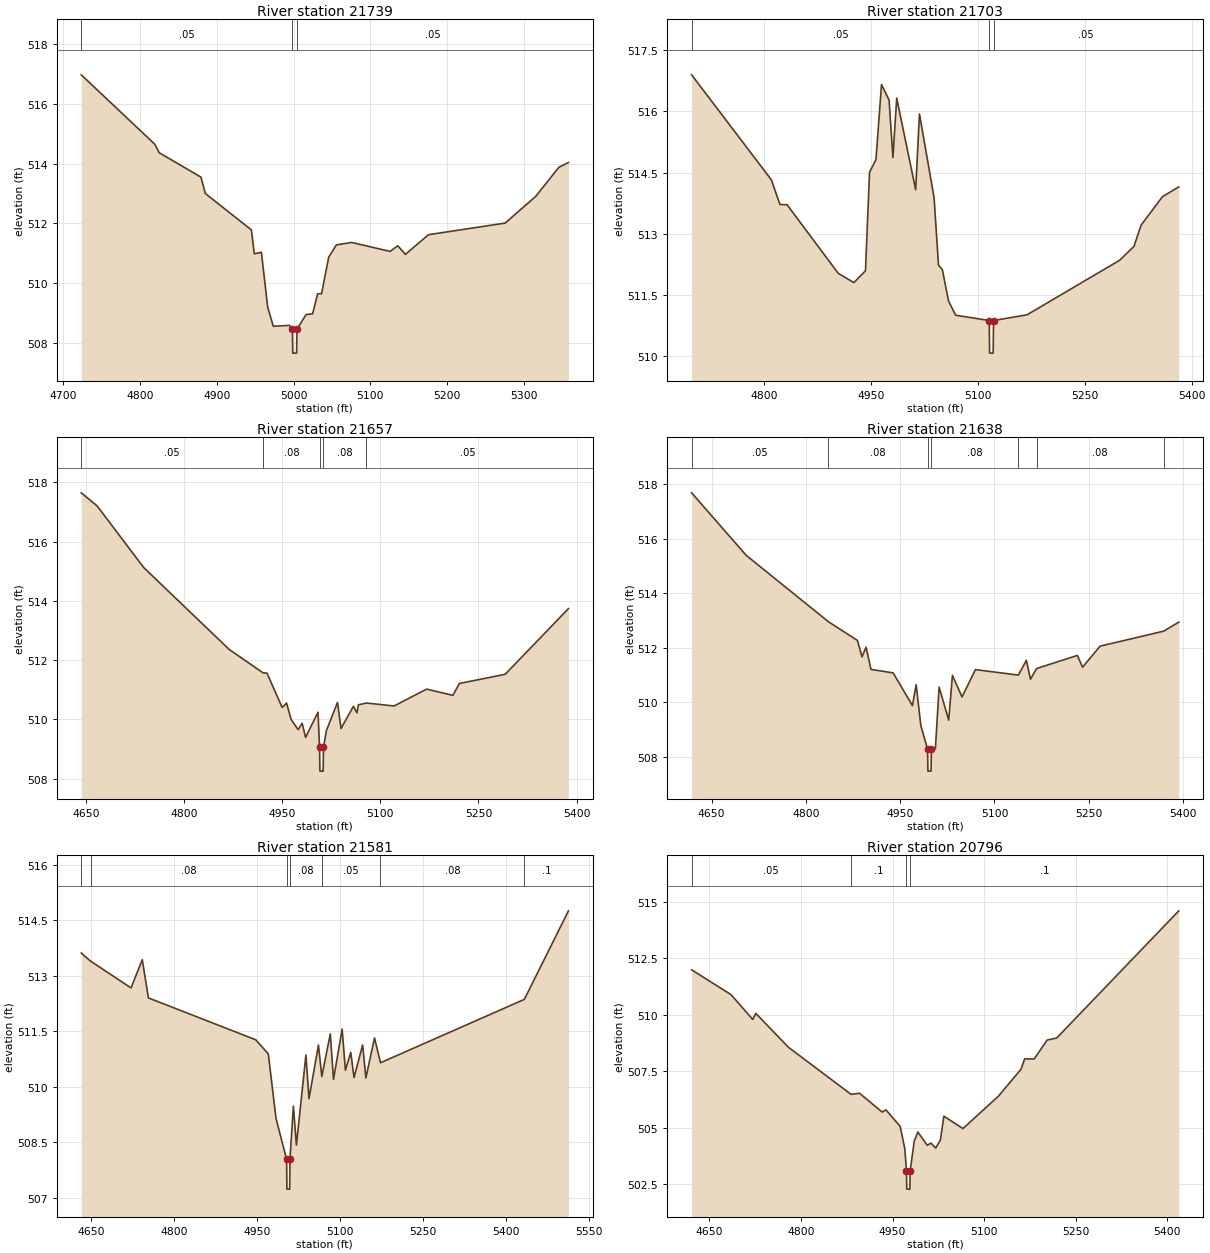
Type RM Length L Ch R = 1,21739,36,36,36
BEGIN DESCRIPTION:
Mapping XS 2eacb075
END DESCRIPTION:
XS GIS Cut Line= 4
      2066412.56     13490963.59      2066213.36     13491070.35
      2066170.31     13491141.18      2066176.85     13491467.52
#Sta/Elev= 30
  4723.2  516.98  4819.2  514.65  4824.8  514.37  4879.3  513.55  4885.0  513.00
  4945.1  511.78  4948.8  510.98  4958.1  511.03  4966.3  509.19  4973.6  508.55
  4994.9  508.58  4998.5  508.45  4999.0  507.65  5004.0  507.65  5004.5  508.45
  5016.2  508.94  5024.9  508.97  5031.4  509.64  5036.5  509.64  5045.9  510.87
  5055.9  511.28  5075.9  511.36  5125.9  511.06  5135.9  511.25  5145.9  510.96
  5175.9  511.62  5276.0  512.01  5316.0  512.91  5346.0  513.88  5358.5  514.04
#Mann=3,-1,0
  4723.2    0.05       0  4998.5    0.03       0  5004.5    0.05       0
Bank Sta=4998.5,5004.5
Exp/Cntr=0.3,0.1

Type RM Length L Ch R = 1,21703,46,46,46
BEGIN DESCRIPTION:
Mapping XS 07e1aac4
END DESCRIPTION:
XS GIS Cut Line= 4
      2066394.30     13490934.96      2066168.22     13491055.07
      2066139.75     13491142.57      2066133.88     13491477.91
#Sta/Elev= 30
  4698.6  516.90  4810.6  514.32  4822.4  513.72  4832.6  513.71  4904.2  512.03
  4926.2  511.80  4942.5  512.09  4948.2  514.51  4957.2  514.82  4965.0  516.66
  4975.6  516.28  4981.0  514.87  4986.3  516.33  5012.9  514.08  5018.2  515.94
  5038.7  513.89  5044.9  512.23  5050.3  512.12  5059.0  511.35  5069.0  511.00
  5116.1  510.87  5116.6  510.07  5121.6  510.07  5122.1  510.87  5169.1  511.01
  5299.1  512.35  5319.1  512.69  5329.1  513.21  5359.1  513.91  5382.0  514.15
#Mann=3,-1,0
  4698.6    0.05       0  5116.1    0.03       0  5122.1    0.05       0
Bank Sta=5116.1,5122.1
Exp/Cntr=0.3,0.1

Type RM Length L Ch R = 1,21657,19,19,19
BEGIN DESCRIPTION:
Mapping XS 53be3a0b
END DESCRIPTION:
XS GIS Cut Line= 4
      2066395.56     13490872.49      2066128.64     13491039.10
      2066088.36     13491141.18      2066088.31     13491461.79
#Sta/Elev= 30
  4642.7  517.65  4666.9  517.21  4738.0  515.13  4868.9  512.36  4920.7  511.57
  4926.7  511.56  4949.9  510.40  4956.6  510.55  4963.7  509.99  4974.4  509.65
  4980.4  509.87  4985.7  509.39  5004.7  510.24  5007.1  509.05  5007.6  508.25
  5012.6  508.25  5013.1  509.05  5017.4  509.61  5034.5  510.57  5039.9  509.69
  5058.9  510.44  5064.2  510.22  5066.5  510.49  5078.8  510.55  5120.9  510.45
  5170.9  511.02  5210.9  510.81  5220.9  511.21  5290.9  511.52  5387.7  513.74
#Mann=5,-1,0
  4642.7    0.05       0  4920.7    0.08       0  5007.1    0.07       0
  5013.1    0.08       0  5078.8    0.05       0
Bank Sta=5007.1,5013.1
Exp/Cntr=0.3,0.1

Type RM Length L Ch R = 1,21638,57,57,57
BEGIN DESCRIPTION:
Mapping XS 614ff8d0
END DESCRIPTION:
XS GIS Cut Line= 5
      2066364.36     13490802.14      2066143.92     13490993.09
      2066057.98     13491130.25      2065977.25     13491275.21
      2065947.74     13491427.95
#Sta/Elev= 30
  4618.2  517.68  4705.0  515.39  4835.6  512.96  4882.0  512.27  4889.2  511.67
  4895.8  512.02  4903.5  511.21  4938.8  511.08  4969.5  509.88  4975.4  510.65
  4982.9  509.14  4993.6  508.28  4994.1  507.48  4999.1  507.48  4999.6  508.28
  5006.0  508.30  5011.9  510.56  5027.2  509.35  5033.1  510.99  5048.4  510.20
  5069.7  511.20  5138.0  511.00  5150.7  511.54  5157.3  510.85  5167.0  511.24
  5231.8  511.72  5240.1  511.29  5268.0  512.06  5369.1  512.61  5393.2  512.94
#Mann=7,-1,0
  4618.2    0.05       0  4835.6    0.08       0  4993.6    0.07       0
  4999.6    0.08       0  5138.0    0.05       0  5167.0    0.08       0
  5369.1    0.05       0
Bank Sta=4993.6,4999.6
Exp/Cntr=0.3,0.1

Type RM Length L Ch R = 1,21581,785,785,785
BEGIN DESCRIPTION:
Mapping XS 4eaf886c
END DESCRIPTION:
XS GIS Cut Line= 5
      2066139.08     13490686.31      2066097.91     13490935.80
      2066018.05     13491102.47      2065926.04     13491256.98
      2065784.56     13491478.31
#Sta/Elev= 30
  4632.6  513.61  4649.7  513.39  4722.5  512.67  4742.8  513.43  4753.9  512.40
  4947.8  511.27  4970.5  510.89  4984.4  509.15  5003.6  508.04  5004.1  507.24
  5009.1  507.24  5009.6  508.04  5015.8  509.48  5021.3  508.43  5038.5  510.86
  5044.0  509.68  5061.1  511.13  5067.2  510.28  5082.5  511.43  5088.3  510.20
  5103.9  511.56  5109.8  510.45  5119.5  510.93  5125.4  510.25  5140.9  511.13
  5146.8  510.24  5162.4  511.32  5173.2  510.65  5433.1  512.36  5512.8  514.75
#Mann=7,-1,0
  4632.6     0.1       0  4649.7    0.08       0  5003.6    0.07       0
  5009.6    0.08       0  5067.2    0.05       0  5173.2    0.08       0
  5433.1     0.1       0
Bank Sta=5003.6,5009.6
Exp/Cntr=0.3,0.1

Type RM Length L Ch R = 1,20796,504,504,504
BEGIN DESCRIPTION:
Mapping XS 479d894e
END DESCRIPTION:
XS GIS Cut Line= 4
      2066039.54     13490614.32      2065887.65     13490607.81
      2065470.99     13490857.37      2065425.79     13491011.26
#Sta/Elev= 30
  4620.8  512.00  4685.4  510.90  4721.0  509.80  4726.0  510.07  4779.4  508.57
  4881.8  506.49  4896.1  506.53  4933.0  505.70  4939.1  505.80  4962.4  505.07
  4970.0  504.09  4972.8  503.09  4973.3  502.29  4978.3  502.29  4978.8  503.09
  4985.5  504.41  4991.4  504.82  5006.9  504.23  5012.8  504.33  5020.7  504.11
  5028.3  504.46  5034.1  505.52  5065.3  504.97  5123.6  506.41  5160.5  507.60
  5166.4  508.06  5181.9  508.05  5203.3  508.89  5218.9  508.98  5418.9  514.61
#Mann=4,-1,0
  4620.8    0.05       0  4881.8     0.1       0  4972.8    0.07       0
  4978.8     0.1       0
Bank Sta=4972.8,4978.8
Exp/Cntr=0.3,0.1

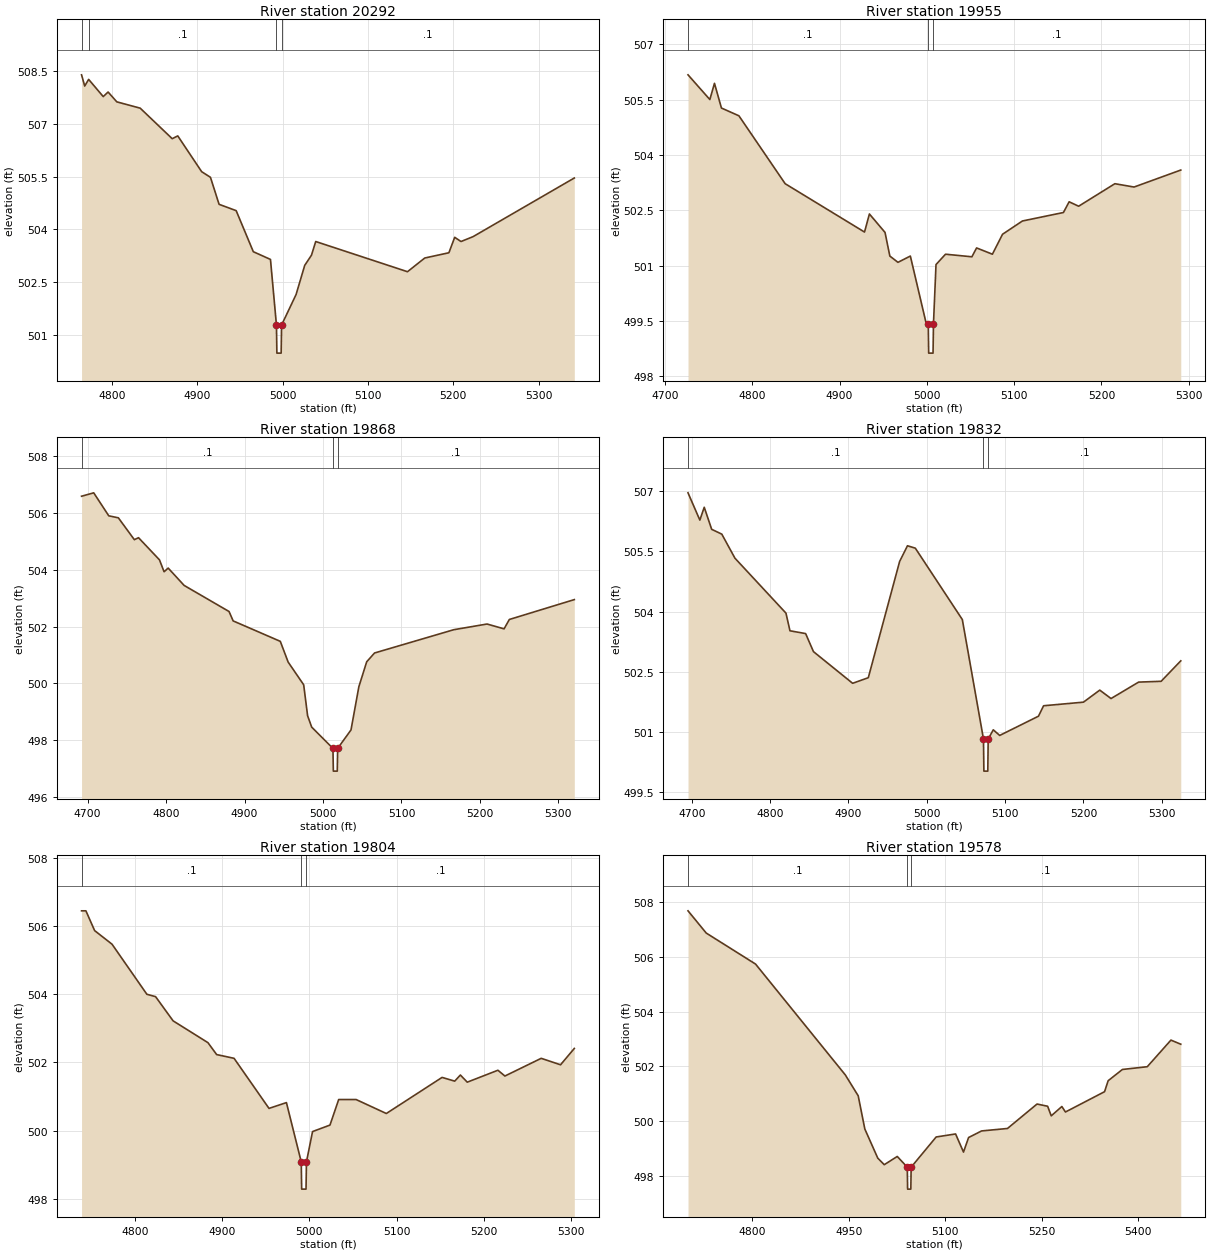
Type RM Length L Ch R = 1,20292,337,337,337
BEGIN DESCRIPTION:
Mapping XS 98027ea3
END DESCRIPTION:
XS GIS Cut Line= 4
      2065781.28     13490382.96      2065683.23     13490327.43
      2065408.92     13490349.13      2065269.13     13490476.84
#Sta/Elev= 30
  4764.5  508.40  4768.2  508.08  4772.8  508.27  4789.9  507.78  4795.6  507.91
  4805.8  507.63  4833.2  507.45  4870.7  506.58  4877.2  506.66  4905.2  505.64
  4915.5  505.48  4925.6  504.71  4945.6  504.53  4965.7  503.36  4985.8  503.14
  4992.8  501.27  4993.3  500.47  4998.3  500.47  4998.8  501.27  5015.8  502.14
  5025.9  502.97  5033.8  503.26  5038.8  503.65  5146.3  502.79  5166.5  503.18
  5194.8  503.33  5201.6  503.77  5209.0  503.65  5223.2  503.79  5341.7  505.46
#Mann=4,-1,0
  4764.5    0.05       0  4772.8     0.1       0  4992.8    0.07       0
  4998.8     0.1       0
Bank Sta=4992.8,4998.8
Exp/Cntr=0.3,0.1

Type RM Length L Ch R = 1,19955,87,87,87
BEGIN DESCRIPTION:
Mapping XS 46de80e7
END DESCRIPTION:
XS GIS Cut Line= 4
      2065581.70     13490127.78      2065443.64     13490086.97
      2065144.16     13490216.31      2065133.75     13490310.06
#Sta/Elev= 30
  4726.4  506.17  4751.4  505.50  4756.7  505.94  4764.7  505.27  4784.7  505.06
  4837.7  503.22  4928.6  501.91  4934.2  502.40  4952.1  501.90  4957.6  501.26
  4966.9  501.09  4981.1  501.26  4999.1  499.45  5001.6  499.43  5002.1  498.63
  5007.1  498.63  5007.6  499.43  5010.5  501.03  5021.4  501.31  5051.6  501.24
  5057.0  501.48  5075.1  501.31  5086.7  501.85  5109.5  502.21  5156.5  502.44
  5163.0  502.73  5173.9  502.61  5215.4  503.22  5237.4  503.13  5290.9  503.59
#Mann=3,-1,0
  4726.4     0.1       0  5001.6    0.07       0  5007.6     0.1       0
Bank Sta=5001.6,5007.6
Exp/Cntr=0.3,0.1

Type RM Length L Ch R = 1,19868,36,36,36
BEGIN DESCRIPTION:
Mapping XS ed7184e8
END DESCRIPTION:
XS GIS Cut Line= 4
      2065599.85     13490111.27      2065420.21     13490055.72
      2065177.15     13490066.14      2065030.48     13490197.19
#Sta/Elev= 30
  4692.3  506.59  4707.8  506.71  4727.0  505.90  4739.2  505.83  4759.6  505.06
  4764.9  505.13  4791.6  504.35  4797.5  503.93  4802.7  504.06  4823.0  503.45
  4880.3  502.53  4885.5  502.20  4945.6  501.48  4955.6  500.75  4975.4  499.95
  4980.4  498.86  4985.6  498.46  5012.7  497.71  5013.2  496.91  5018.2  496.91
  5018.7  497.71  5035.7  498.36  5045.7  499.88  5055.7  500.76  5065.7  501.07
  5166.7  501.89  5209.1  502.09  5230.8  501.92  5237.5  502.25  5320.3  502.95
#Mann=3,-1,0
  4692.3     0.1       0  5012.7    0.07       0  5018.7     0.1       0
Bank Sta=5012.7,5018.7
Exp/Cntr=0.3,0.1

Type RM Length L Ch R = 1,19832,28,28,28
BEGIN DESCRIPTION:
Mapping XS 6499cd34
END DESCRIPTION:
XS GIS Cut Line= 4
      2065592.08     13490077.43      2065480.10     13490021.87
      2065211.00     13490026.21      2065029.39     13490174.97
#Sta/Elev= 30
  4695.3  506.96  4710.4  506.28  4716.0  506.60  4725.5  506.05  4738.4  505.93
  4755.2  505.33  4820.3  503.96  4825.4  503.52  4845.4  503.45  4855.4  503.00
  4905.4  502.21  4925.4  502.35  4965.4  505.25  4975.4  505.64  4985.4  505.58
  5045.4  503.80  5072.4  500.82  5072.9  500.02  5077.9  500.02  5078.4  500.82
  5084.9  501.05  5093.1  500.91  5142.6  501.39  5149.1  501.65  5200.0  501.74
  5220.8  502.04  5235.2  501.83  5270.4  502.24  5299.1  502.26  5324.2  502.77
#Mann=3,-1,0
  4695.3     0.1       0  5072.4    0.07       0  5078.4     0.1       0
Bank Sta=5072.4,5078.4
Exp/Cntr=0.3,0.1

Type RM Length L Ch R = 1,19804,226,226,226
BEGIN DESCRIPTION:
Mapping XS eeca07e4
END DESCRIPTION:
XS GIS Cut Line= 4
      2065559.95     13490006.24      2065373.33     13489997.56
      2065216.21     13489997.56      2065042.63     13490135.57
#Sta/Elev= 30
  4738.4  506.45  4743.4  506.45  4753.4  505.87  4773.4  505.47  4813.4  504.00
  4823.4  503.93  4843.5  503.22  4883.5  502.58  4893.5  502.23  4913.5  502.12
  4953.6  500.65  4973.6  500.82  4990.6  499.08  4991.1  498.28  4996.1  498.28
  4996.6  499.08  5003.6  499.97  5023.6  500.16  5033.6  500.91  5053.6  500.91
  5088.3  500.50  5152.3  501.56  5166.8  501.45  5173.3  501.63  5181.2  501.42
  5216.4  501.77  5224.4  501.60  5266.1  502.12  5288.3  501.93  5304.1  502.41
#Mann=3,-1,0
  4738.4     0.1       0  4990.6    0.07       0  4996.6     0.1       0
Bank Sta=4990.6,4996.6
Exp/Cntr=0.3,0.1

Type RM Length L Ch R = 1,19578,334,334,334
BEGIN DESCRIPTION:
Mapping XS 89dbd737
END DESCRIPTION:
XS GIS Cut Line= 4
      2065581.07     13489877.18      2065492.54     13489819.03
      2065079.20     13489872.46      2064967.23     13490088.58
#Sta/Elev= 30
  4700.1  507.67  4728.4  506.86  4805.1  505.73  4944.7  501.69  4964.7  500.93
  4975.0  499.72  4995.1  498.66  5005.2  498.42  5025.4  498.72  5041.0  498.33
  5041.5  497.53  5046.5  497.53  5047.0  498.33  5085.9  499.43  5116.1  499.54
  5128.4  498.88  5136.3  499.41  5156.5  499.65  5196.8  499.74  5242.7  500.63
  5259.2  500.55  5264.8  500.20  5281.3  500.54  5286.9  500.34  5347.7  501.08
  5353.3  501.48  5375.5  501.89  5414.1  501.99  5450.9  502.96  5466.2  502.81
#Mann=3,-1,0
  4700.1     0.1       0  5041.0    0.07       0  5047.0     0.1       0
Bank Sta=5041,5047
Exp/Cntr=0.3,0.1