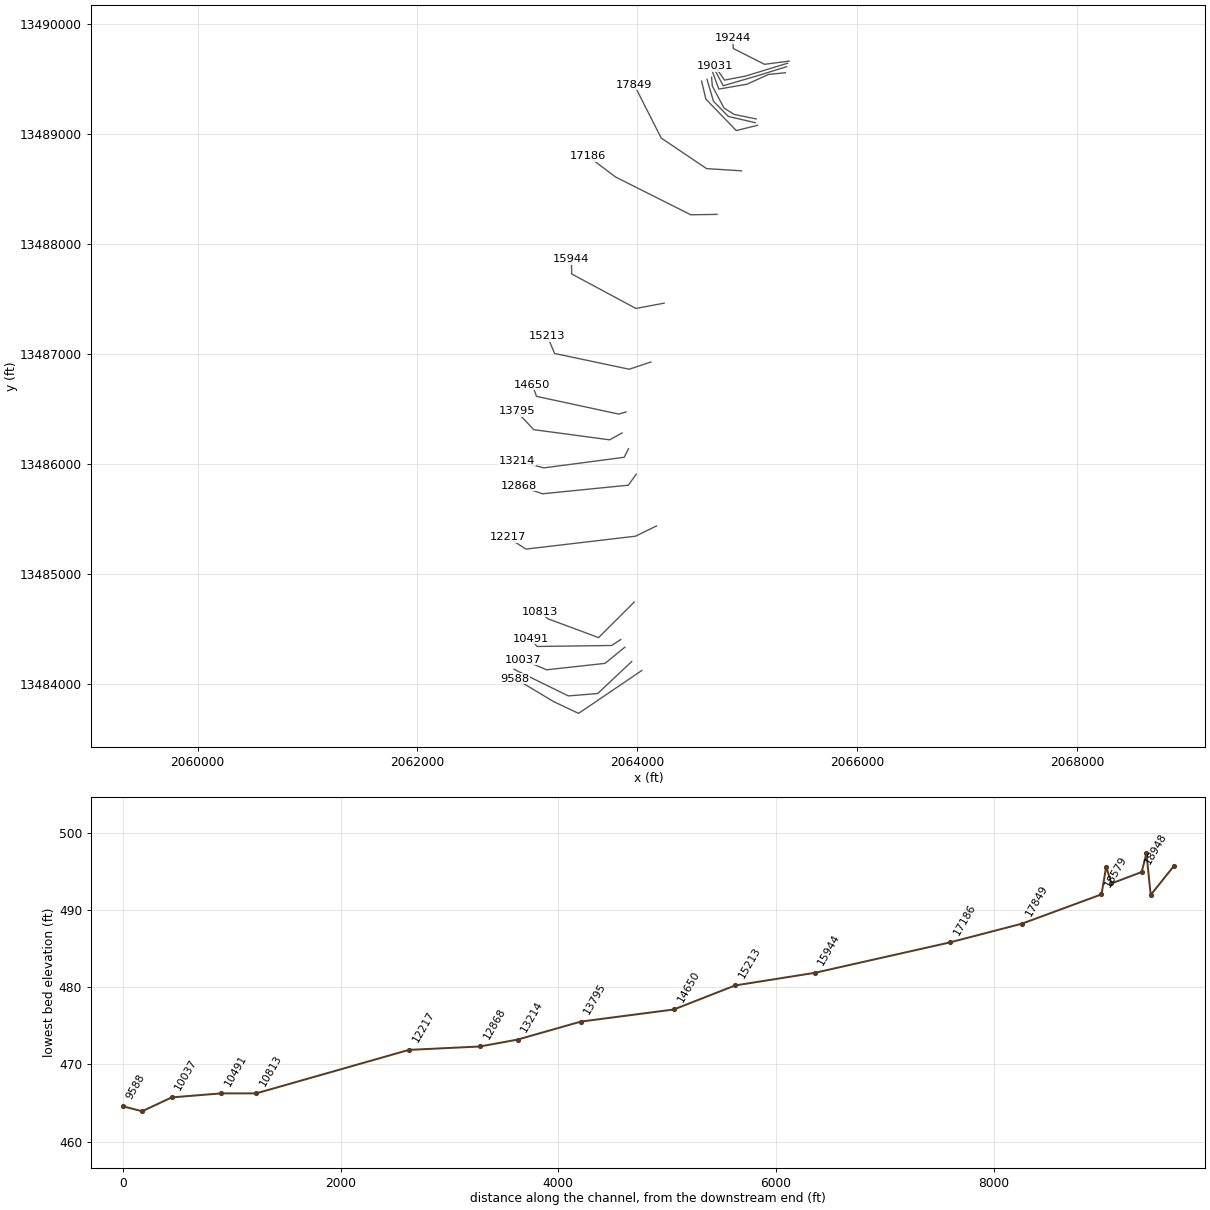
HEC-RAS study UNT 144 in Lagunillas Cr Wtrshd.prj: UNT 144 in Lagunillas Cr Wtrshd Base Level Engineering

--- UNT 144 in Lagunillas Cr Wtrshd.g01 (geometry) --- (continued)

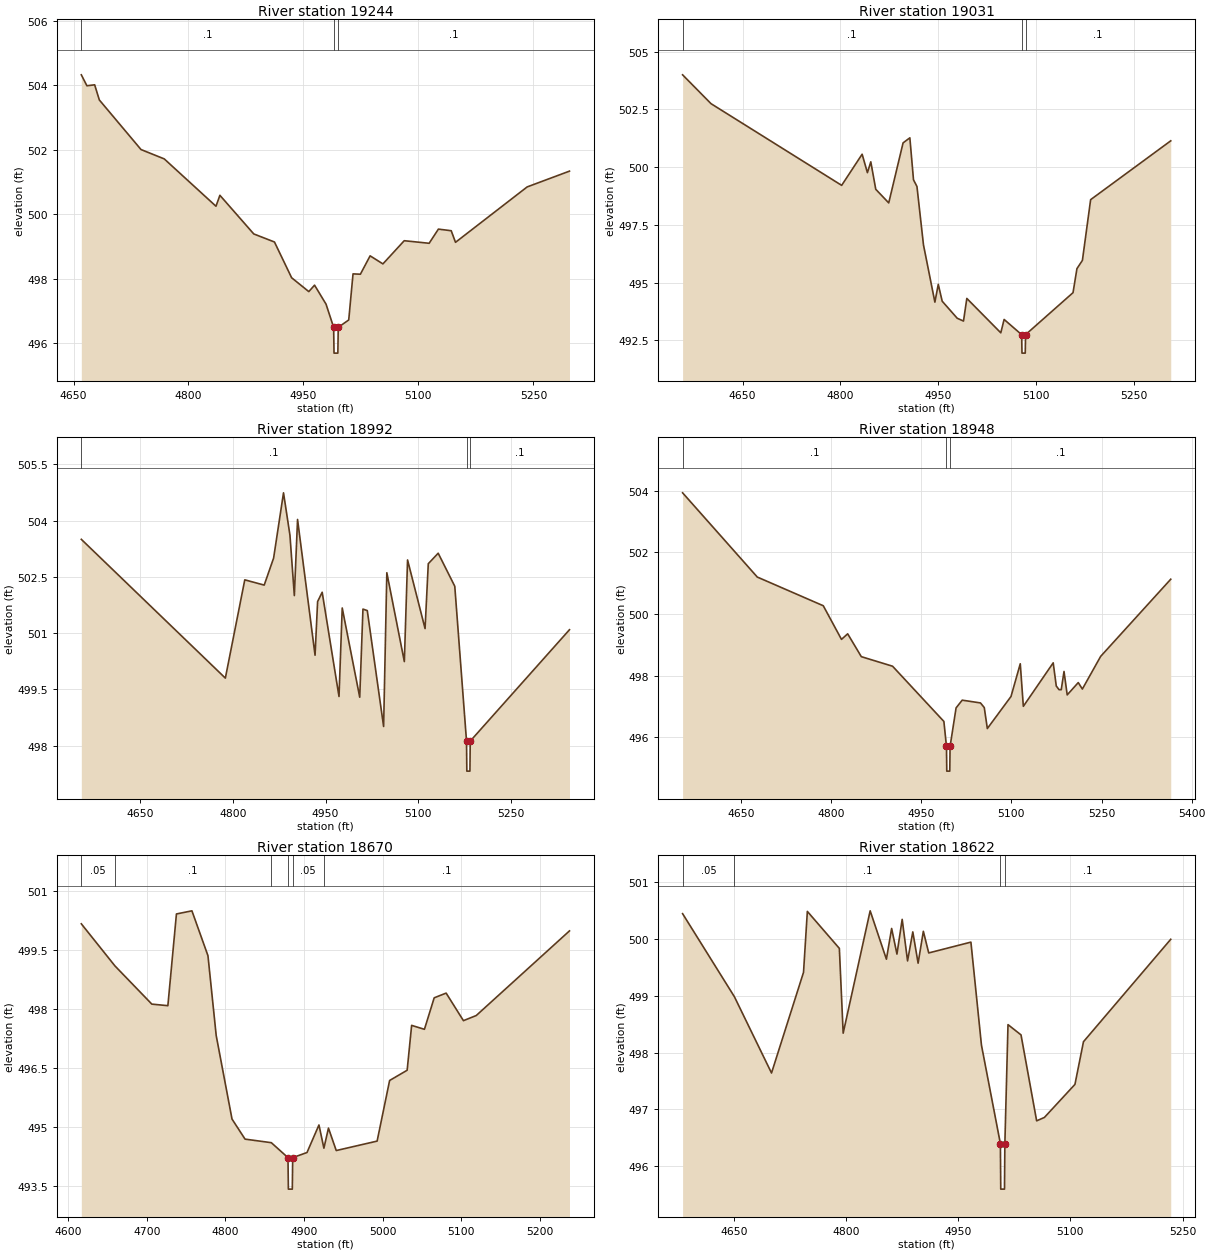
Type RM Length L Ch R = 1,19244,213,213,213
BEGIN DESCRIPTION:
Mapping XS 9a02f886
END DESCRIPTION:
XS GIS Cut Line= 4
      2065382.26     13489663.21      2065158.34     13489633.70
      2064874.49     13489777.37      2064868.42     13489870.08
#Sta/Elev= 30
  4660.2  504.33  4667.5  503.99  4677.6  504.02  4683.7  503.55  4738.1  502.01
  4768.4  501.72  4835.9  500.25  4841.0  500.59  4885.2  499.39  4912.2  499.14
  4934.6  498.03  4957.0  497.60  4964.5  497.80  4979.5  497.21  4989.4  496.49
  4989.9  495.69  4994.9  495.69  4995.4  496.49  5009.1  496.72  5014.7  498.15
  5024.3  498.14  5037.0  498.71  5053.7  498.46  5081.5  499.18  5114.0  499.10
  5126.1  499.54  5142.8  499.49  5148.4  499.13  5241.9  500.85  5297.1  501.34
#Mann=3,-1,0
  4660.2     0.1       0  4989.4    0.07       0  4995.4     0.1       0
Bank Sta=4989.4,4995.4
Exp/Cntr=0.3,0.1

Type RM Length L Ch R = 1,19031,39,39,39
BEGIN DESCRIPTION:
Mapping XS 7770b288
END DESCRIPTION:
XS GIS Cut Line= 4
      2065368.35     13489643.80      2064985.17     13489526.50
      2064794.19     13489490.04      2064707.37     13489616.80
#Sta/Elev= 30
  4557.9  504.00  4601.5  502.75  4801.9  499.21  4833.3  500.56  4841.4  499.76
  4846.6  500.23  4854.2  499.04  4874.1  498.45  4896.1  501.05  4906.5  501.27
  4912.1  499.45  4917.4  499.16  4927.4  496.63  4944.9  494.15  4950.1  494.92
  4956.1  494.19  4979.2  493.45  4988.8  493.33  4993.9  494.31  5046.0  492.82
  5051.1  493.40  5078.0  492.74  5078.5  491.94  5083.5  491.94  5084.0  492.74
  5156.8  494.56  5162.8  495.60  5171.2  495.96  5183.8  498.59  5306.7  501.14
#Mann=3,-1,0
  4557.9     0.1       0  5078.0    0.07       0  5084.0     0.1       0
Bank Sta=5078,5084
Exp/Cntr=0.3,0.1

Type RM Length L Ch R = 1,18992,44,44,44
BEGIN DESCRIPTION:
Mapping XS 7f47cc8a
END DESCRIPTION:
XS GIS Cut Line= 4
      2065357.45     13489611.24      2065088.90     13489528.24
      2064782.47     13489438.83      2064693.94     13489605.48
#Sta/Elev= 30
  4555.3  503.50  4788.1  499.80  4819.5  502.42  4850.9  502.28  4866.1  503.00
  4882.1  504.74  4892.5  503.61  4899.6  502.00  4904.8  504.03  4933.1  500.41
  4937.2  501.84  4944.6  502.09  4971.8  499.31  4977.0  501.67  5005.3  499.29
  5010.5  501.64  5017.5  501.60  5043.9  498.51  5049.1  502.61  5077.4  500.24
  5082.6  502.95  5110.9  501.12  5116.1  502.85  5132.1  503.13  5158.9  502.25
  5177.9  498.12  5178.4  497.32  5183.4  497.32  5183.9  498.12  5344.3  501.09
#Mann=3,-1,0
  4555.3     0.1       0  5177.9    0.07       0  5183.9     0.1       0
Bank Sta=5177.9,5183.9
Exp/Cntr=0.3,0.1

Type RM Length L Ch R = 1,18948,278,278,278
BEGIN DESCRIPTION:
Mapping XS 252d2686
END DESCRIPTION:
XS GIS Cut Line= 5
      2065348.76     13489556.99      2065195.67     13489542.12
      2064999.49     13489452.71      2064742.54     13489408.44
      2064679.81     13489579.46
#Sta/Elev= 30
  4552.9  503.93  4677.2  501.20  4787.0  500.27  4817.3  499.18  4827.6  499.36
  4850.3  498.62  4902.3  498.31  4987.7  496.52  4992.0  495.71  4992.5  494.91
  4997.5  494.91  4998.0  495.71  5008.0  496.96  5018.2  497.21  5048.6  497.12
  5054.9  496.97  5060.0  496.29  5099.4  497.33  5114.8  498.39  5119.9  497.01
  5169.6  498.42  5174.7  497.67  5179.3  497.55  5183.0  497.55  5187.6  498.14
  5192.9  497.38  5211.3  497.78  5218.1  497.57  5248.6  498.63  5365.2  501.13
#Mann=3,-1,0
  4552.9     0.1       0  4992.0    0.07       0  4998.0     0.1       0
Bank Sta=4992,4998
Exp/Cntr=0.3,0.1

Type RM Length L Ch R = 1,18670,48,48,48
BEGIN DESCRIPTION:
Mapping XS cd269f41
END DESCRIPTION:
XS GIS Cut Line= 5
      2065082.85     13489136.74      2064882.30     13489177.54
      2064789.42     13489236.57      2064683.52     13489435.35
      2064676.57     13489516.11
#Sta/Elev= 30
  4616.6  500.17  4659.4  499.10  4706.3  498.13  4726.7  498.09  4737.6  500.42
  4757.3  500.50  4777.7  499.36  4788.2  497.33  4808.3  495.21  4824.9  494.70
  4858.3  494.61  4879.5  494.23  4880.0  493.43  4885.0  493.43  4885.5  494.23
  4903.7  494.36  4918.9  495.06  4925.2  494.47  4931.0  494.98  4940.9  494.41
  4992.9  494.65  5008.8  496.19  5031.1  496.45  5036.8  497.59  5053.1  497.49
  5065.5  498.29  5080.7  498.41  5102.7  497.71  5119.0  497.84  5237.6  499.99
#Mann=6,-1,0
  4616.6    0.05       0  4659.4     0.1       0  4858.3    0.05       0
  4879.5    0.07       0  4885.5    0.05       0  4925.2     0.1       0
Bank Sta=4879.5,4885.5
Exp/Cntr=0.3,0.1

Type RM Length L Ch R = 1,18622,43,43,43
BEGIN DESCRIPTION:
Mapping XS 2c4deb16
END DESCRIPTION:
XS GIS Cut Line= 4
      2065074.11     13489102.90      2064829.35     13489159.31
      2064693.93     13489297.33      2064634.91     13489496.96
#Sta/Elev= 30
  4581.5  500.44  4650.8  498.98  4700.4  497.64  4743.2  499.41  4748.3  500.48
  4791.1  499.83  4796.2  498.34  4832.3  500.49  4854.0  499.64  4861.0  500.18
  4868.1  499.73  4875.1  500.34  4882.3  499.61  4889.3  500.12  4896.4  499.57
  4903.4  500.13  4910.6  499.75  4967.0  499.94  4981.1  498.13  5006.4  496.40
  5006.9  495.60  5011.9  495.60  5012.4  496.40  5016.6  498.49  5034.0  498.31
  5054.9  496.80  5065.3  496.86  5106.1  497.44  5117.5  498.19  5234.2  499.99
#Mann=4,-1,0
  4581.5    0.05       0  4650.8     0.1       0  5006.4    0.07       0
  5012.4     0.1       0
Bank Sta=5006.4,5012.4
Exp/Cntr=0.3,0.1

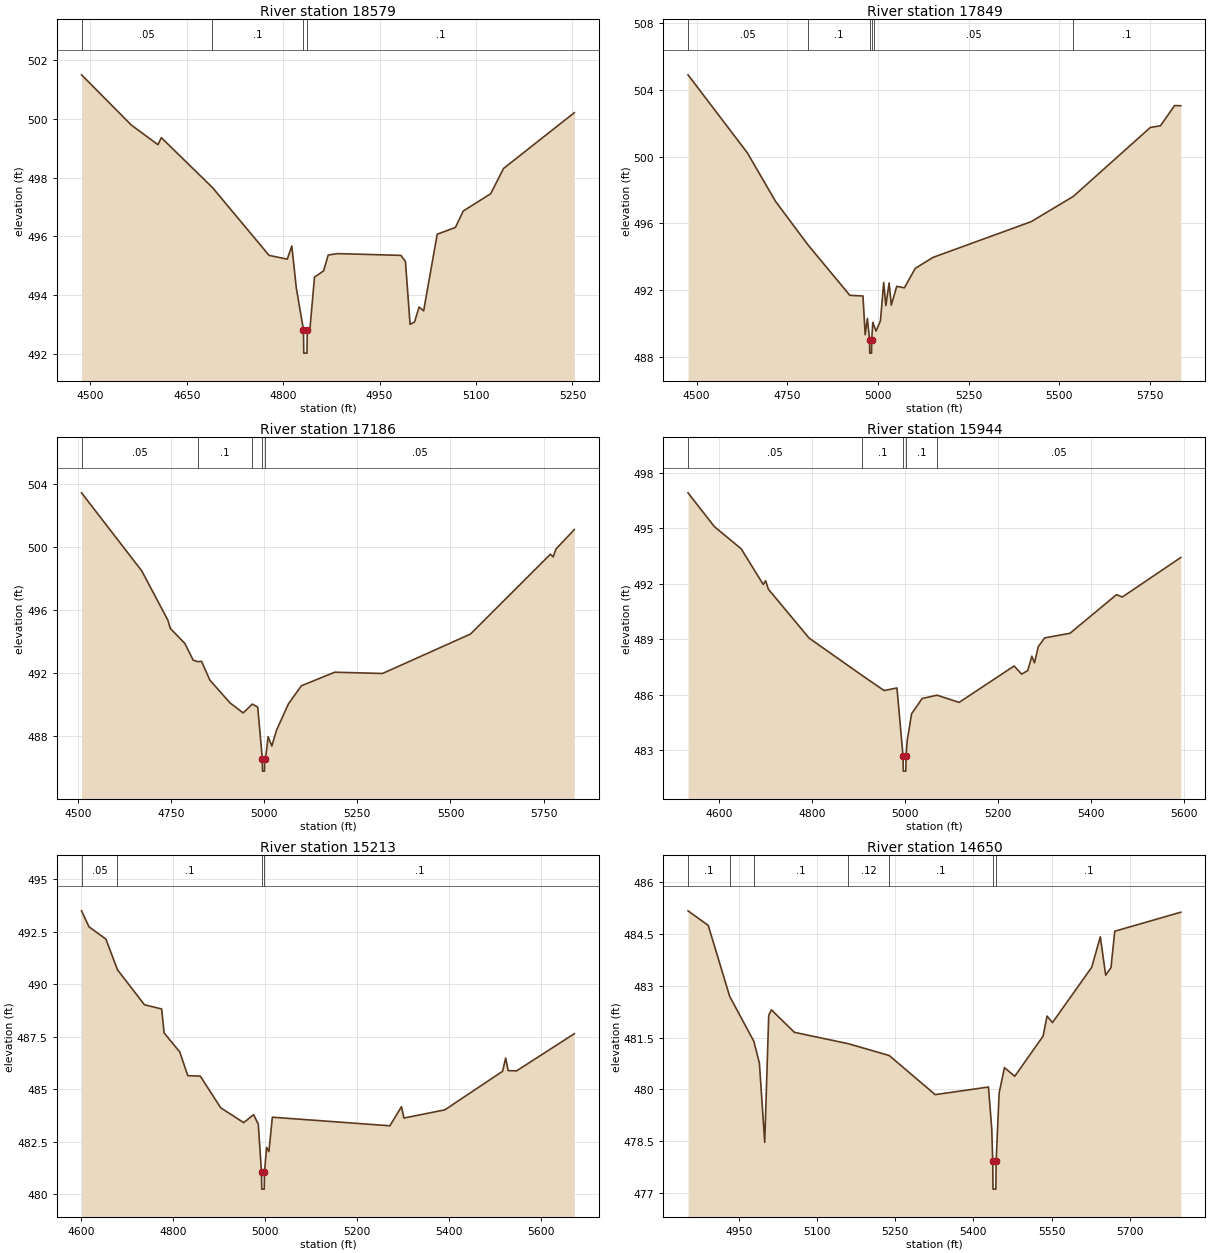
Type RM Length L Ch R = 1,18579,730,730,730
BEGIN DESCRIPTION:
Mapping XS bb048124
END DESCRIPTION:
XS GIS Cut Line= 4
      2065094.99     13489078.59      2064901.40     13489030.84
      2064624.49     13489317.30      2064585.78     13489481.59
#Sta/Elev= 30
  4486.4  501.50  4563.8  499.79  4605.3  499.12  4610.5  499.36  4690.1  497.66
  4778.1  495.35  4806.4  495.22  4813.5  495.67  4820.5  494.24  4831.6  492.82
  4832.1  492.02  4837.1  492.02  4837.6  492.82  4841.8  492.87  4848.8  494.61
  4862.9  494.82  4870.1  495.36  4884.3  495.41  4983.3  495.35  4990.3  495.14
  4997.5  493.00  5004.4  493.08  5011.5  493.59  5018.6  493.46  5039.7  496.07
  5068.0  496.30  5080.2  496.86  5122.9  497.45  5142.9  498.31  5253.0  500.21
#Mann=4,-1,0
  4486.4    0.05       0  4690.1     0.1       0  4831.6    0.07       0
  4837.6     0.1       0
Bank Sta=4831.6,4837.6
Exp/Cntr=0.3,0.1

Type RM Length L Ch R = 1,17849,663,663,663
BEGIN DESCRIPTION:
Mapping XS 6fc7fae8
END DESCRIPTION:
XS GIS Cut Line= 4
      2064948.60     13488664.64      2064631.17     13488684.74
      2064218.31     13488962.89      2063973.09     13489446.82
#Sta/Elev= 30
  4476.5  504.89  4640.4  500.21  4717.6  497.32  4806.5  494.73  4922.6  491.69
  4958.8  491.65  4964.9  489.33  4971.0  490.31  4976.9  489.03  4977.4  488.23
  4982.4  488.23  4982.9  489.03  4985.9  490.07  4987.9  489.95  4994.9  489.55
  5007.0  490.17  5015.9  492.46  5021.9  491.08  5030.9  492.43  5036.9  491.10
  5051.9  492.23  5072.9  492.14  5102.8  493.30  5151.7  493.96  5422.5  496.10
  5538.6  497.61  5751.0  501.74  5778.9  501.84  5817.8  503.05  5834.9  503.04
#Mann=6,-1,0
  4476.5    0.05       0  4806.5     0.1       0  4976.9    0.03       0
  4982.9     0.1       0  4987.9    0.05       0  5538.6     0.1       0
Bank Sta=4976.9,4982.9
Exp/Cntr=0.3,0.1

Type RM Length L Ch R = 1,17186,1242,1242,1242
BEGIN DESCRIPTION:
Mapping XS 38235453
END DESCRIPTION:
XS GIS Cut Line= 4
      2064726.62     13488268.22      2064487.06     13488264.74
      2063803.03     13488608.49      2063549.79     13488799.29
#Sta/Elev= 30
  4510.1  503.44  4671.7  498.49  4741.7  495.37  4748.2  494.85  4787.4  493.89
  4809.7  492.83  4822.2  492.74  4832.1  492.76  4854.4  491.57  4908.7  490.12
  4943.7  489.49  4968.5  490.05  4982.8  489.86  4995.1  486.60  4995.6  485.80
  5000.9  485.80  5001.4  486.60  5005.1  486.85  5010.7  487.98  5020.6  487.39
  5033.0  488.38  5065.4  490.07  5100.0  491.21  5189.3  492.07  5317.7  491.99
  5553.8  494.49  5768.2  499.55  5775.7  499.38  5782.8  499.87  5832.3  501.11
#Mann=5,-1,0
  4510.1    0.05       0  4822.2     0.1       0  4968.5    0.05       0
  4995.1    0.03       0  5001.4    0.05       0
Bank Sta=4995.1,5001.4
Exp/Cntr=0.3,0.1

Type RM Length L Ch R = 1,15944,731,731,731
BEGIN DESCRIPTION:
Mapping XS ad023449
END DESCRIPTION:
XS GIS Cut Line= 4
      2064244.93     13487460.61      2063988.42     13487412.43
      2063403.78     13487726.24      2063401.20     13487860.79
#Sta/Elev= 30
  4533.9  496.92  4590.6  495.09  4648.2  493.89  4695.6  491.96  4700.7  492.16
  4706.8  491.70  4794.1  489.06  4908.0  487.04  4955.4  486.22  4983.0  486.36
  4996.1  482.66  4996.6  481.86  5002.0  481.86  5002.5  482.66  5005.0  483.51
  5014.4  484.96  5037.1  485.79  5069.1  485.97  5116.6  485.58  5234.8  487.55
  5251.0  487.11  5264.1  487.30  5272.9  488.08  5278.6  487.72  5286.8  488.60
  5300.5  489.07  5354.9  489.32  5454.9  491.41  5467.2  491.28  5593.0  493.42
#Mann=5,-1,0
  4533.9    0.05       0  4908.0     0.1       0  4996.1    0.07       0
  5002.5     0.1       0  5069.1    0.05       0
Bank Sta=4996.1,5002.5
Exp/Cntr=0.3,0.1

Type RM Length L Ch R = 1,15213,563,563,563
BEGIN DESCRIPTION:
Mapping XS 926abfc8
END DESCRIPTION:
XS GIS Cut Line= 4
      2064124.79     13486925.26      2063927.11     13486859.36
      2063248.10     13487002.82      2063183.27     13487159.02
#Sta/Elev= 30
  4601.2  493.50  4617.3  492.74  4654.2  492.15  4679.3  490.69  4738.0  489.02
  4775.4  488.82  4780.7  487.68  4814.8  486.77  4832.2  485.64  4859.4  485.62
  4903.7  484.11  4953.8  483.40  4975.3  483.78  4985.5  483.33  4992.5  481.03
  4993.0  480.23  4998.5  480.23  4999.0  481.03  5003.5  482.22  5008.6  482.02
  5016.1  483.66  5271.7  483.25  5296.8  484.16  5302.3  483.62  5391.2  484.01
  5516.8  485.85  5523.4  486.48  5528.9  485.88  5547.3  485.87  5672.7  487.64
#Mann=4,-1,0
  4601.2    0.05       0  4679.3     0.1       0  4992.5    0.07       0
  4999.0     0.1       0
Bank Sta=4992.5,4999
Exp/Cntr=0.3,0.1

Type RM Length L Ch R = 1,14650,855,855,855
BEGIN DESCRIPTION:
Mapping XS ab40755e
END DESCRIPTION:
XS GIS Cut Line= 4
      2063897.51     13486471.32      2063832.39     13486451.14
      2063083.75     13486612.61      2063045.24     13486718.08
#Sta/Elev= 30
  4851.9  485.16  4890.7  484.74  4931.9  482.69  4978.3  481.39  4989.0  480.76
  4999.2  478.47  5006.9  482.14  5012.0  482.30  5056.2  481.65  5160.0  481.32
  5238.3  480.98  5326.6  479.85  5428.9  480.07  5435.2  478.86  5437.1  477.92
  5437.6  477.12  5443.1  477.12  5443.6  477.92  5449.4  479.90  5459.6  480.63
  5479.4  480.38  5533.8  481.54  5541.4  482.12  5551.7  481.93  5627.2  483.53
  5643.7  484.41  5654.0  483.30  5664.2  483.52  5671.4  484.57  5798.2  485.12
#Mann=7,-1,0
  4851.9     0.1       0  4931.9    0.12       0  4978.3     0.1       0
  5160.0    0.12       0  5238.3     0.1       0  5437.1    0.07       0
  5443.6     0.1       0
Bank Sta=5437.1,5443.6
Exp/Cntr=0.3,0.1

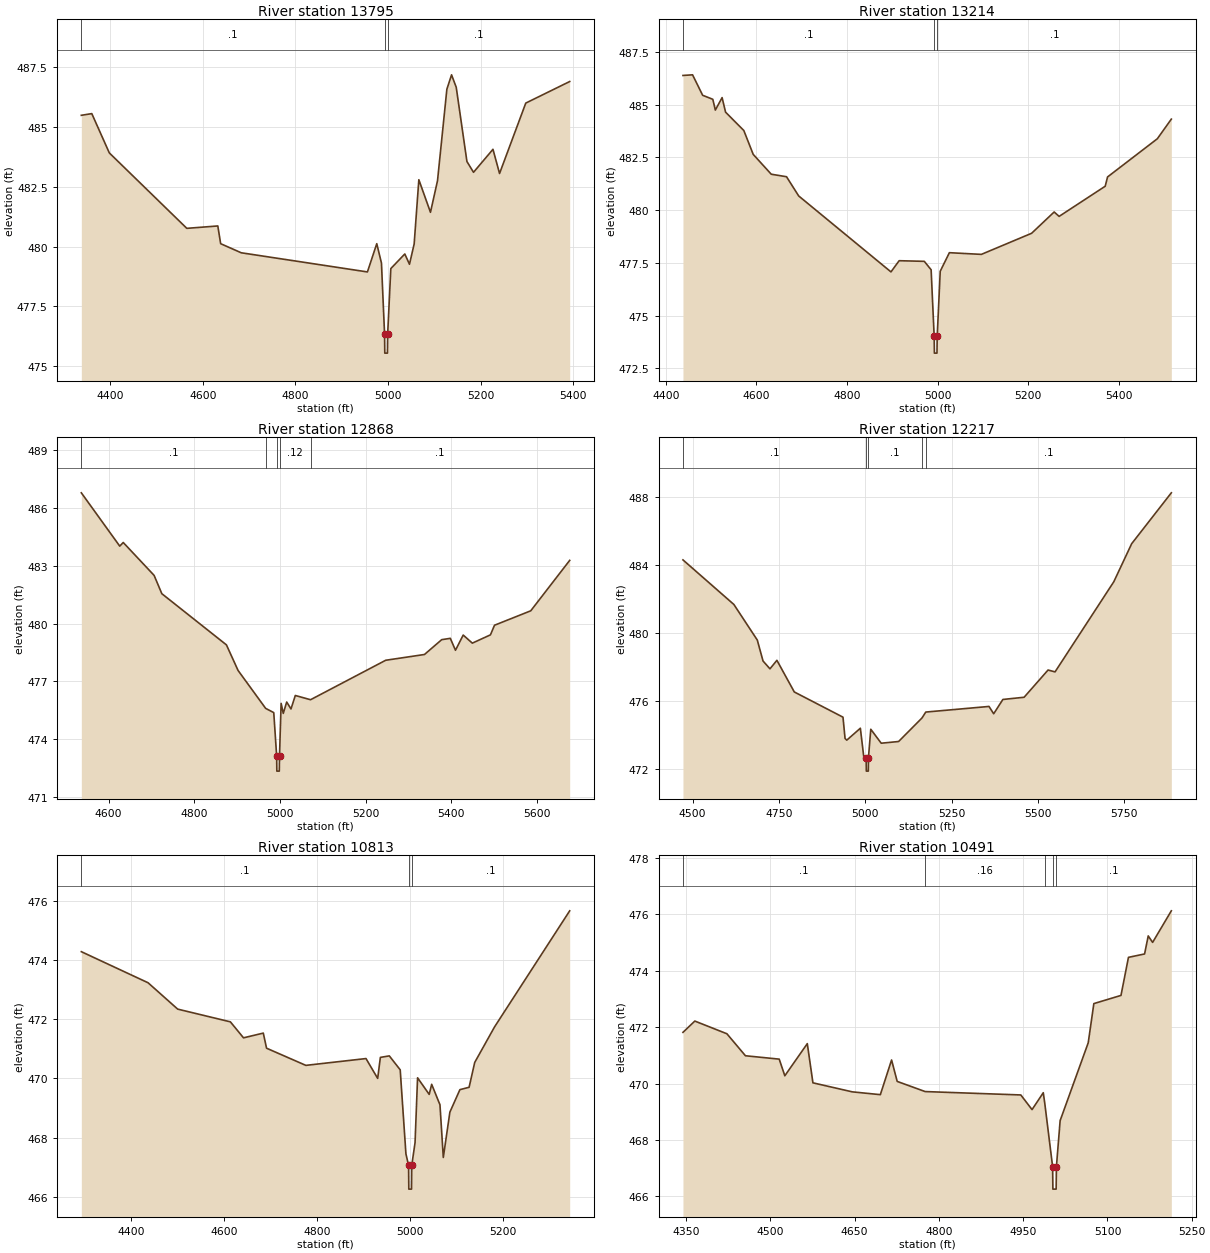
Type RM Length L Ch R = 1,13795,581,581,581
BEGIN DESCRIPTION:
Mapping XS 30796ec7
END DESCRIPTION:
XS GIS Cut Line= 4
      2063862.09     13486279.60      2063748.84     13486217.12
      2063058.73     13486309.57      2062902.46     13486476.26
#Sta/Elev= 30
  4337.9  485.48  4360.5  485.55  4398.3  483.91  4565.6  480.76  4632.5  480.86
  4638.6  480.12  4683.0  479.74  4955.4  478.94  4975.6  480.12  4985.7  479.31
  4992.4  476.35  4992.9  475.55  4998.6  475.55  4999.1  476.35  5005.9  479.08
  5036.1  479.69  5046.2  479.26  5056.3  480.11  5066.4  482.79  5091.5  481.43
  5106.7  482.75  5126.9  486.57  5137.0  487.17  5147.1  486.65  5170.2  483.55
  5184.4  483.10  5226.4  484.06  5240.6  483.05  5297.2  485.99  5392.0  486.89
#Mann=3,-1,0
  4337.9     0.1       0  4992.4    0.07       0  4999.1     0.1       0
Bank Sta=4992.4,4999.1
Exp/Cntr=0.3,0.1

Type RM Length L Ch R = 1,13214,346,346,346
BEGIN DESCRIPTION:
Mapping XS 61b003d7
END DESCRIPTION:
XS GIS Cut Line= 4
      2063920.72     13486136.41      2063881.65     13486058.27
      2063151.18     13485961.91      2062905.08     13486025.72
#Sta/Elev= 30
  4437.7  486.38  4458.9  486.41  4481.2  485.44  4503.6  485.25  4509.2  484.74
  4524.1  485.33  4531.8  484.64  4572.1  483.77  4592.8  482.64  4632.6  481.70
  4666.4  481.58  4693.2  480.67  4897.0  477.07  4915.1  477.60  4970.6  477.57
  4985.7  477.17  4992.4  474.02  4992.9  473.22  4998.6  473.22  4999.1  474.02
  5005.8  477.10  5026.0  477.98  5096.6  477.90  5207.6  478.90  5257.4  479.91
  5268.3  479.70  5370.1  481.13  5375.3  481.57  5485.2  483.38  5516.1  484.31
#Mann=3,-1,0
  4437.7     0.1       0  4992.4    0.07       0  4999.1     0.1       0
Bank Sta=4992.4,4999.1
Exp/Cntr=0.3,0.1

Type RM Length L Ch R = 1,12868,651,651,651
BEGIN DESCRIPTION:
Mapping XS 9c761f25
END DESCRIPTION:
XS GIS Cut Line= 4
      2063991.02     13485904.61      2063919.41     13485804.36
      2063138.16     13485726.24      2062919.05     13485801.43
#Sta/Elev= 30
  4536.5  486.79  4626.2  484.02  4634.3  484.21  4706.4  482.50  4724.4  481.55
  4875.2  478.89  4902.4  477.56  4966.8  475.59  4985.7  475.37  4992.4  473.13
  4992.9  472.33  4998.6  472.33  4999.1  473.13  5002.9  475.85  5007.9  475.33
  5015.9  475.92  5025.9  475.56  5036.0  476.26  5071.6  476.04  5247.0  478.09
  5337.5  478.39  5377.7  479.16  5397.8  479.23  5409.9  478.61  5427.9  479.40
  5449.2  478.98  5491.5  479.41  5501.0  479.91  5585.6  480.66  5676.5  483.28
#Mann=5,-1,0
  4536.5     0.1       0  4966.8    0.12       0  4992.4    0.07       0
  4999.1    0.12       0  5071.6     0.1       0
Bank Sta=4992.4,4999.1
Exp/Cntr=0.3,0.1

Type RM Length L Ch R = 1,12217,1404,1404,1404
BEGIN DESCRIPTION:
Mapping XS c953b861
END DESCRIPTION:
XS GIS Cut Line= 4
      2064175.15     13485433.47      2063984.16     13485340.14
      2062988.06     13485222.95      2062820.57     13485330.32
#Sta/Elev= 30
  4471.9  484.30  4619.4  481.68  4687.2  479.59  4703.8  478.36  4723.9  477.90
  4744.0  478.40  4794.4  476.54  4935.4  475.06  4941.4  473.81  4946.4  473.71
  4985.7  474.41  4995.8  472.69  5002.5  472.69  5003.0  471.89  5008.7  471.89
  5009.2  472.69  5015.9  474.35  5046.1  473.53  5096.5  473.63  5164.1  475.01
  5175.2  475.36  5358.3  475.69  5371.9  475.26  5398.5  476.10  5460.0  476.23
  5529.4  477.83  5549.6  477.72  5719.9  483.02  5771.5  485.25  5886.4  488.24
#Mann=5,-1,0
  4471.9     0.1       0  5002.5    0.07       0  5009.2     0.1       0
  5164.1    0.12       0  5175.2     0.1       0
Bank Sta=5002.5,5009.2
Exp/Cntr=0.3,0.1

Type RM Length L Ch R = 1,10813,322,322,322
BEGIN DESCRIPTION:
Mapping XS 240a2693
END DESCRIPTION:
XS GIS Cut Line= 4
      2063972.28     13484740.47      2063648.58     13484417.64
      2063186.34     13484589.52      2063112.08     13484654.65
#Sta/Elev= 30
  4293.5  474.28  4436.9  473.23  4500.5  472.34  4613.7  471.91  4641.9  471.37
  4684.4  471.53  4691.4  471.02  4775.8  470.44  4905.0  470.67  4930.1  470.00
  4935.9  470.71  4955.1  470.76  4978.5  470.29  4990.8  467.45  4996.5  467.06
  4997.0  466.26  5002.8  466.26  5003.3  467.06  5010.4  467.83  5015.8  470.02
  5040.8  469.46  5046.1  469.80  5063.9  469.11  5071.1  467.33  5085.2  468.86
  5106.8  469.62  5126.5  469.70  5138.6  470.54  5181.2  471.74  5342.6  475.66
#Mann=3,-1,0
  4293.5     0.1       0  4996.5    0.07       0  5003.3     0.1       0
Bank Sta=4996.5,5003.3
Exp/Cntr=0.3,0.1

Type RM Length L Ch R = 1,10491,454,454,454
BEGIN DESCRIPTION:
Mapping XS 12e6ce87
END DESCRIPTION:
XS GIS Cut Line= 4
      2063850.02     13484400.01      2063768.37     13484346.03
      2063088.68     13484336.91      2063030.06     13484407.26
#Sta/Elev= 30
  4344.5  471.82  4365.6  472.22  4422.7  471.77  4455.7  470.99  4515.8  470.87
  4525.8  470.28  4565.8  471.42  4575.8  470.03  4645.8  469.71  4695.8  469.61
  4715.8  470.84  4725.8  470.08  4775.5  469.72  4945.8  469.60  4965.8  469.08
  4985.8  469.68  4988.6  469.28  5002.4  467.06  5002.9  466.26  5008.7  466.26
  5009.2  467.06  5015.8  468.69  5065.8  471.45  5075.8  472.84  5124.1  473.13
  5137.4  474.48  5166.1  474.60  5172.6  475.24  5180.4  475.01  5213.7  476.13
#Mann=5,-1,0
  4344.5     0.1       0  4775.5    0.16       0  4988.6     0.1       0
  5002.4    0.07       0  5009.2     0.1       0
Bank Sta=5002.4,5009.2
Exp/Cntr=0.3,0.1

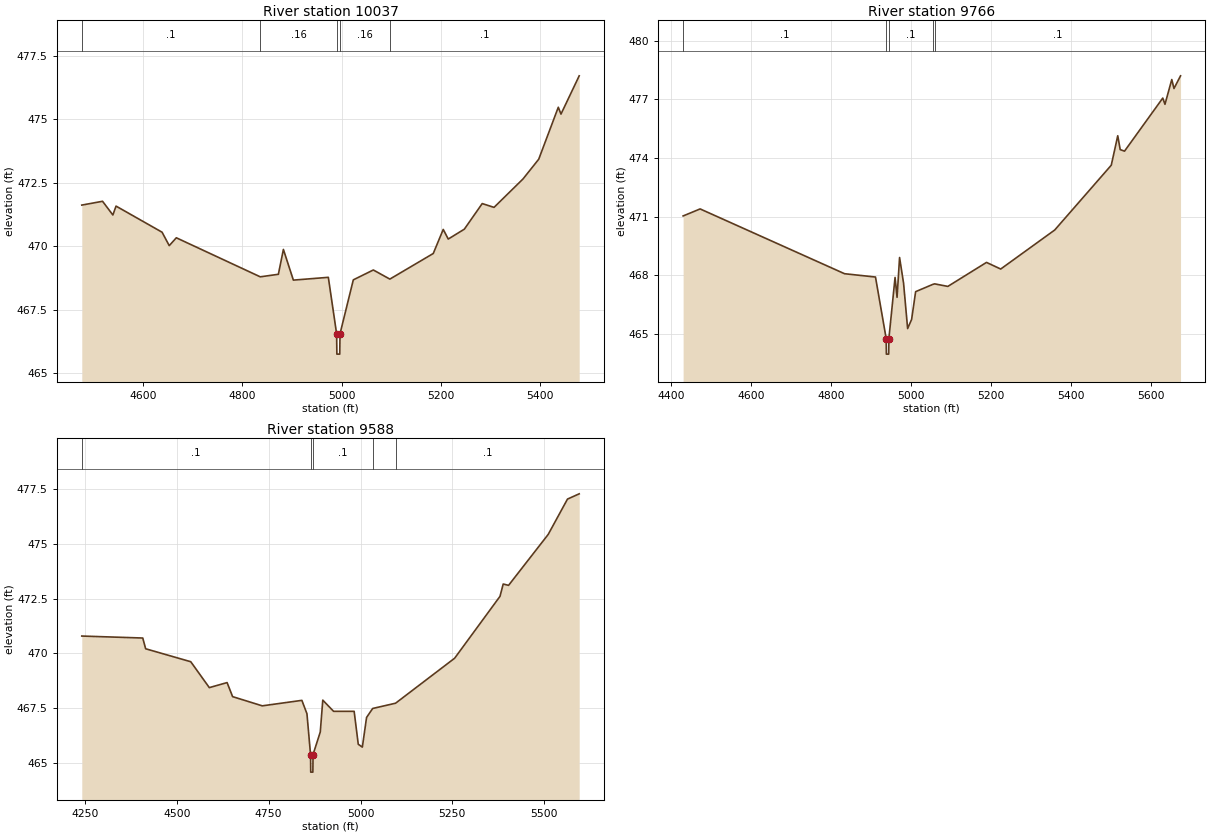
Type RM Length L Ch R = 1,10037,271,271,271
BEGIN DESCRIPTION:
Mapping XS 1d23683e
END DESCRIPTION:
XS GIS Cut Line= 4
      2063887.62     13484330.29      2063707.17     13484183.27
      2063175.92     13484124.67      2062959.87     13484215.78
#Sta/Elev= 30
  4476.7  471.62  4518.5  471.77  4539.3  471.23  4545.7  471.58  4638.4  470.55
  4652.8  470.02  4667.1  470.33  4836.1  468.79  4872.6  468.89  4882.7  469.87
  4902.8  468.66  4973.2  468.77  4989.9  466.54  4990.4  465.74  4996.2  465.74
  4996.7  466.54  5023.5  468.67  5063.8  469.06  5097.1  468.70  5184.5  469.71
  5204.6  470.66  5214.7  470.28  5247.1  470.67  5283.1  471.68  5306.9  471.53
  5365.2  472.65  5396.9  473.43  5436.3  475.48  5441.7  475.21  5478.4  476.72
#Mann=5,-1,0
  4476.7     0.1       0  4836.1    0.16       0  4989.9    0.07       0
  4996.7    0.16       0  5097.1     0.1       0
Bank Sta=4989.9,4996.7
Exp/Cntr=0.3,0.1

Type RM Length L Ch R = 1,9766,178,178,178
BEGIN DESCRIPTION:
Mapping XS 81e5d04d
END DESCRIPTION:
XS GIS Cut Line= 4
      2063950.02     13484200.02      2063640.59     13483908.78
      2063373.67     13483887.08      2062879.57     13484129.29
#Sta/Elev= 30
  4430.9  471.03  4473.4  471.39  4834.3  468.07  4911.6  467.90  4938.3  464.75
  4938.8  463.95  4944.6  463.95  4945.1  464.75  4960.5  467.88  4965.5  466.86
  4971.8  468.90  4981.8  467.58  4991.9  465.26  5001.9  465.73  5011.9  467.15
  5054.4  467.52  5059.4  467.55  5092.4  467.42  5189.0  468.65  5224.5  468.31
  5359.5  470.31  5500.8  473.63  5517.0  475.14  5523.1  474.43  5533.9  474.35
  5629.5  477.07  5635.0  476.75  5652.0  478.02  5657.5  477.56  5673.9  478.21
#Mann=5,-1,0
  4430.9     0.1       0  4938.3    0.07       0  4945.1     0.1       0
  5054.4    0.12       0  5059.4     0.1       0
Bank Sta=4938.3,4945.1
Exp/Cntr=0.3,0.1

Type RM Length L Ch R = 1,9588,214,214,214
BEGIN DESCRIPTION:
Mapping XS 390d24c4
END DESCRIPTION:
XS GIS Cut Line= 4
      2064042.40     13484118.64      2063466.55     13483728.22
      2063241.72     13483834.13      2062890.05     13484044.83
#Sta/Elev= 30
  4241.2  470.79  4407.2  470.70  4415.1  470.21  4537.9  469.62  4588.4  468.44
  4636.8  468.67  4651.8  468.03  4732.5  467.61  4840.4  467.86  4854.2  467.25
  4864.0  465.39  4864.5  464.59  4870.3  464.59  4870.8  465.39  4890.5  466.42
  4897.3  467.87  4926.7  467.36  4982.7  467.36  4993.9  465.86  5005.0  465.73
  5016.5  467.08  5033.1  467.49  5095.5  467.73  5256.3  469.78  5379.8  472.60
  5388.5  473.16  5403.1  473.10  5511.0  475.42  5563.5  477.03  5595.4  477.27
#Mann=5,-1,0
  4241.2     0.1       0  4864.0    0.07       0  4870.8     0.1       0
  5033.1    0.05       0  5095.5     0.1       0
Bank Sta=4864,4870.8
Exp/Cntr=0.3,0.1