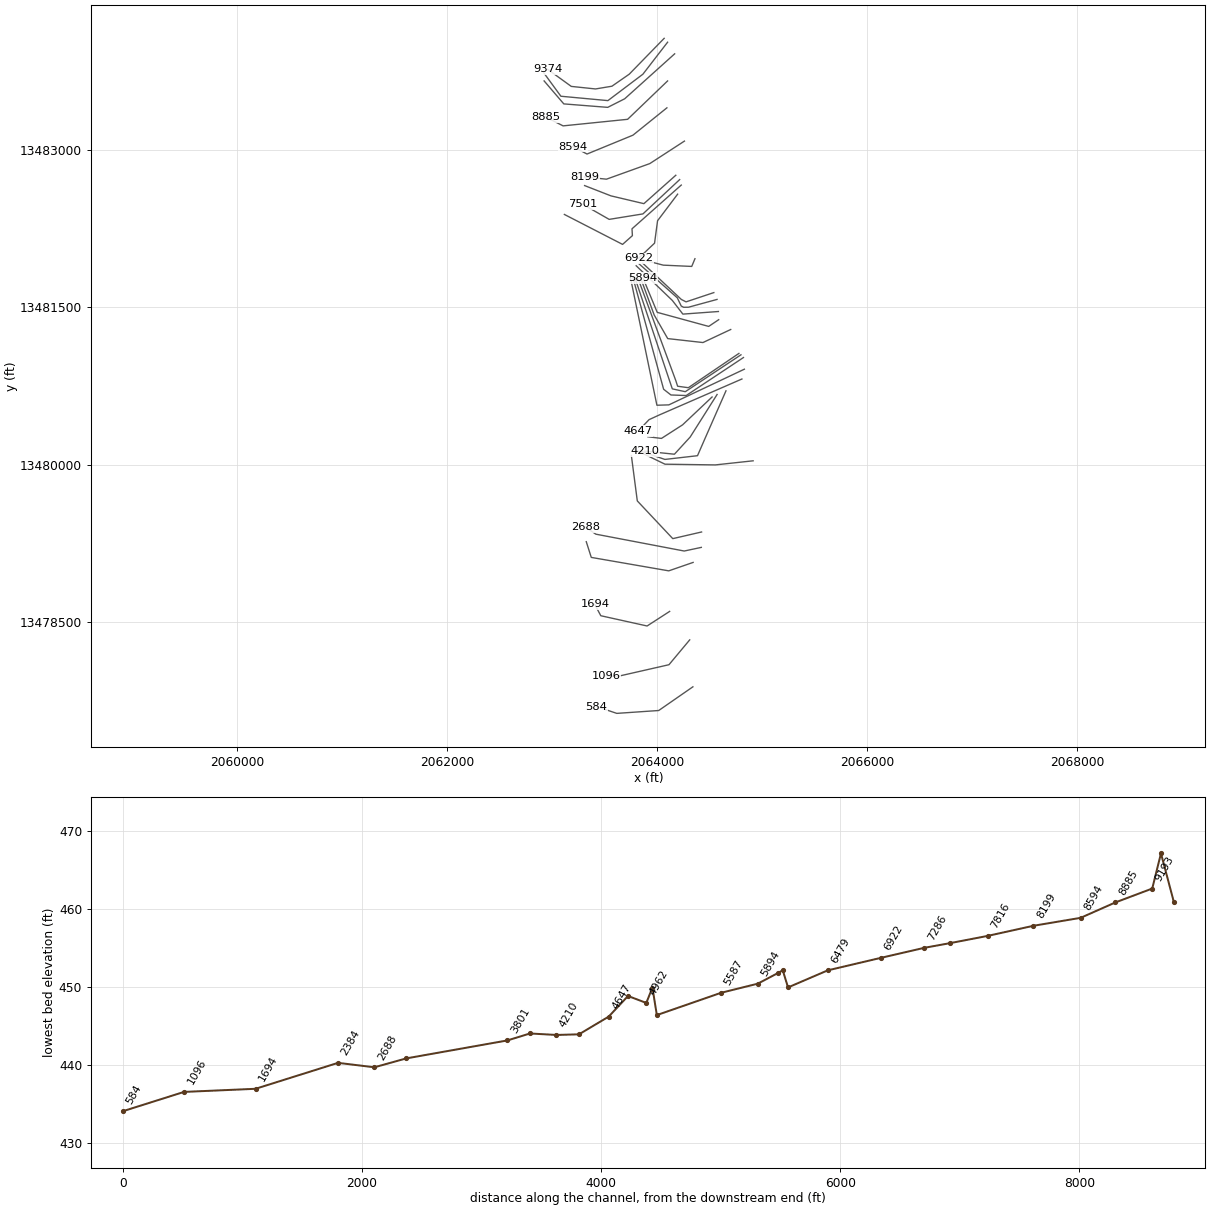
HEC-RAS study UNT 144 in Lagunillas Cr Wtrshd.prj: UNT 144 in Lagunillas Cr Wtrshd Base Level Engineering

--- UNT 144 in Lagunillas Cr Wtrshd.g01 (geometry) --- (continued)

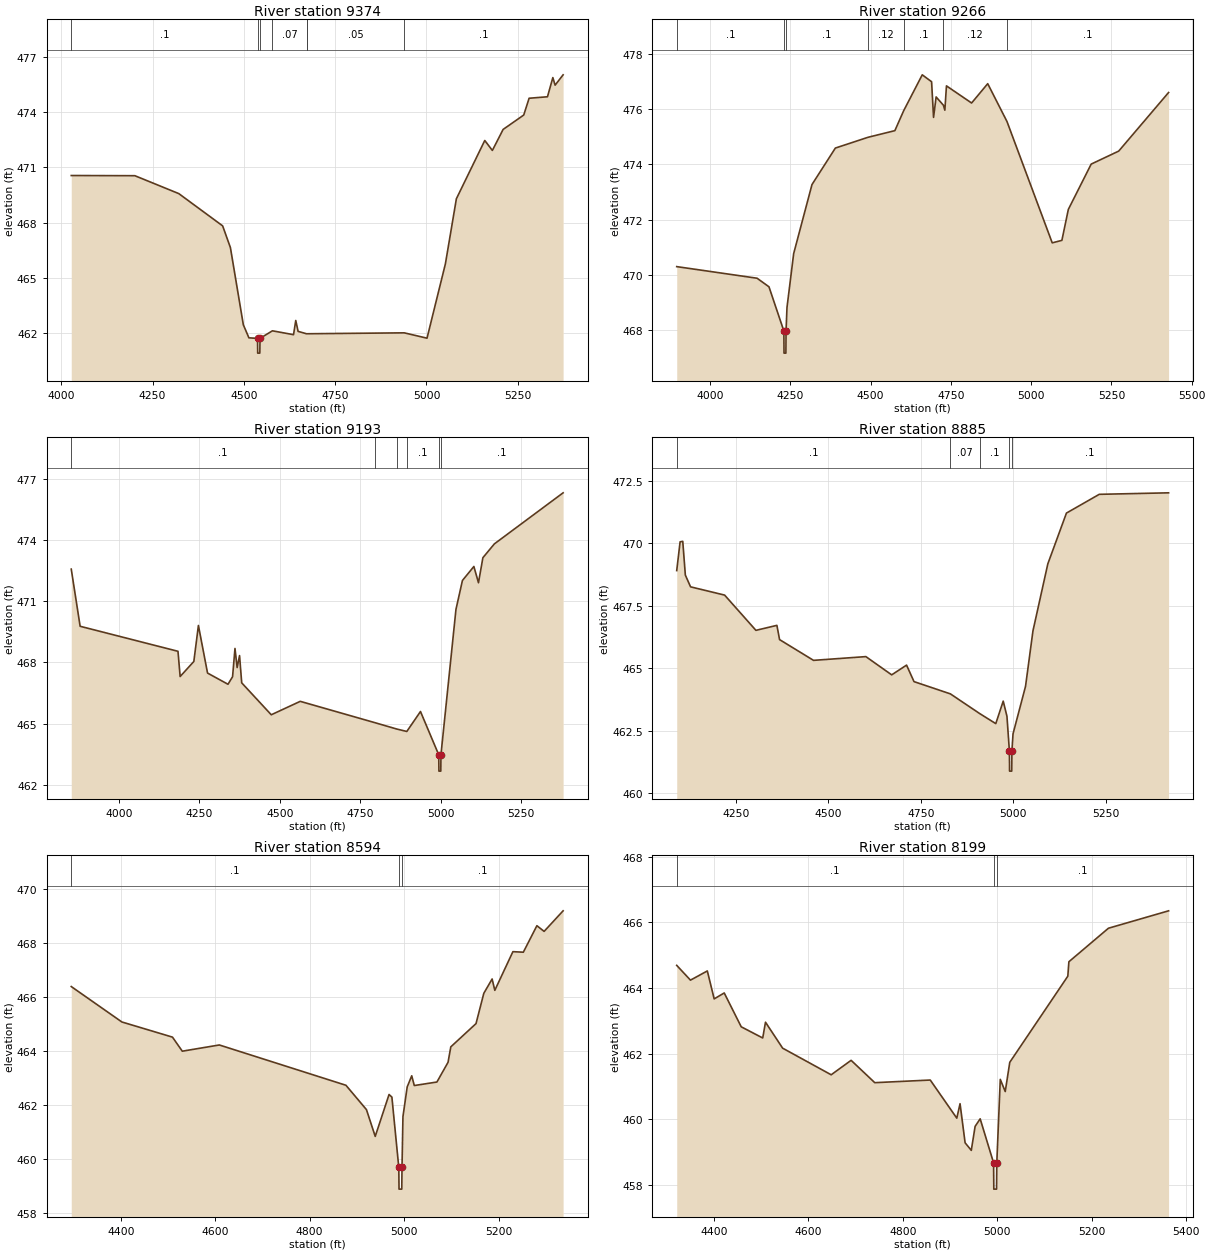
Type RM Length L Ch R = 1,9374,108,108,108
BEGIN DESCRIPTION:
Mapping XS f4b74864
END DESCRIPTION:
XS GIS Cut Line= 6
      2064066.24     13484060.02      2063733.48     13483718.53
      2063568.55     13483603.95      2063412.30     13483577.91
      2063181.39     13483602.21      2062955.73     13483765.39
#Sta/Elev= 30
  4027.4  470.55  4201.6  470.54  4321.8  469.57  4441.9  467.82  4463.2  466.64
  4498.5  462.46  4513.8  461.75  4537.4  461.72  4537.9  460.92  4543.7  460.92
  4544.2  461.72  4578.2  462.13  4636.0  461.92  4642.1  462.69  4648.5  462.10
  4671.5  461.97  4671.9  461.97  4939.2  462.02  5001.5  461.73  5051.8  465.76
  5081.9  469.29  5159.6  472.45  5180.4  471.91  5209.9  473.05  5266.3  473.83
  5281.0  474.74  5331.3  474.82  5346.0  475.86  5352.2  475.45  5374.1  476.01
#Mann=7,-1,0
  4027.4     0.1       0  4537.4    0.07       0  4544.2     0.1       0
  4578.2    0.07       0  4671.5     0.1       0  4671.9    0.05       0
  4939.2     0.1       0
Bank Sta=4537.4,4544.2
Exp/Cntr=0.3,0.1

Type RM Length L Ch R = 1,9266,73,73,73
BEGIN DESCRIPTION:
Mapping XS 34488d30
END DESCRIPTION:
XS GIS Cut Line= 5
      2064098.82     13484023.16      2063863.69     13483718.53
      2063530.35     13483466.80      2063082.44     13483508.46
      2062917.52     13483734.14
#Sta/Elev= 30
  3896.2  470.30  4146.5  469.88  4183.5  469.57  4229.9  467.97  4230.4  467.17
  4236.2  467.17  4236.7  467.97  4239.6  468.82  4260.4  470.77  4317.5  473.27
  4390.3  474.59  4492.1  474.98  4575.6  475.22  4603.0  475.94  4660.9  477.24
  4690.0  476.99  4696.1  475.70  4704.1  476.44  4726.8  476.14  4731.3  475.96
  4736.3  476.84  4814.6  476.22  4864.8  476.92  4924.8  475.55  5065.7  471.16
  5095.8  471.25  5115.9  472.37  5187.1  474.01  5272.8  474.48  5428.1  476.60
#Mann=7,-1,0
  3896.2     0.1       0  4229.9    0.07       0  4236.7     0.1       0
  4492.1    0.12       0  4603.0     0.1       0  4726.8    0.12       0
  4924.8     0.1       0
Bank Sta=4229.9,4236.7
Exp/Cntr=0.3,0.1

Type RM Length L Ch R = 1,9193,308,308,308
BEGIN DESCRIPTION:
Mapping XS 503f07be
END DESCRIPTION:
XS GIS Cut Line= 5
      2064166.08     13483912.47      2063690.07     13483484.16
      2063528.62     13483402.56      2063110.21     13483435.55
      2062922.68     13483654.33
#Sta/Elev= 30
  3851.9  472.59  3879.5  469.78  4183.7  468.55  4190.4  467.31  4233.0  468.05
  4247.2  469.82  4275.6  467.48  4339.2  466.93  4353.4  467.30  4360.9  468.69
  4367.6  467.75  4375.1  468.34  4381.8  467.00  4473.7  465.43  4563.8  466.09
  4796.3  465.04  4863.6  464.73  4895.1  464.61  4937.6  465.59  4994.4  463.46
  4994.9  462.66  5000.7  462.66  5001.2  463.46  5047.9  470.61  5068.0  472.03
  5103.6  472.72  5117.9  471.92  5131.6  473.15  5167.3  473.83  5381.0  476.34
#Mann=6,-1,0
  3851.9     0.1       0  4796.3    0.07       0  4863.6    0.12       0
  4895.1     0.1       0  4994.4    0.07       0  5001.2     0.1       0
Bank Sta=4994.4,5001.2
Exp/Cntr=0.3,0.1

Type RM Length L Ch R = 1,8885,291,291,291
BEGIN DESCRIPTION:
Mapping XS c5e22c9d
END DESCRIPTION:
XS GIS Cut Line= 4
      2064098.77     13483654.19      2063718.13     13483288.74
      2063103.55     13483226.24      2062939.34     13483309.62
#Sta/Elev= 30
  4089.8  468.90  4098.9  470.05  4106.1  470.07  4113.1  468.72  4127.2  468.25
  4219.3  467.92  4303.9  466.51  4360.6  466.71  4367.8  466.14  4459.6  465.31
  4601.1  465.46  4670.9  464.73  4711.1  465.12  4731.2  464.46  4829.5  463.97
  4909.0  463.18  4952.3  462.78  4972.4  463.68  4982.5  463.07  4989.1  461.68
  4989.6  460.88  4995.4  460.88  4995.9  461.68  4998.9  462.37  5032.7  464.27
  5052.8  466.49  5093.0  469.17  5143.3  471.20  5232.0  471.95  5419.4  472.01
#Mann=5,-1,0
  4089.8     0.1       0  4829.5    0.07       0  4909.0     0.1       0
  4989.1    0.07       0  4995.9     0.1       0
Bank Sta=4989.1,4995.9
Exp/Cntr=0.3,0.1

Type RM Length L Ch R = 1,8594,395,395,395
BEGIN DESCRIPTION:
Mapping XS 69f79a8c
END DESCRIPTION:
XS GIS Cut Line= 4
      2064092.30     13483398.15      2063768.91     13483137.69
      2063331.41     13482958.01      2063195.98     13483029.63
#Sta/Elev= 30
  4295.2  466.39  4402.4  465.08  4509.5  464.52  4530.3  464.00  4608.7  464.23
  4876.8  462.74  4920.2  461.84  4938.8  460.85  4968.1  462.40  4974.1  462.30
  4988.7  459.70  4989.2  458.90  4995.0  458.90  4995.5  459.70  4997.5  461.58
  5006.5  462.68  5016.1  463.09  5021.5  462.73  5069.4  462.86  5093.0  463.59
  5098.8  464.16  5152.2  465.02  5168.7  466.14  5186.3  466.67  5192.0  466.25
  5230.3  467.68  5252.4  467.66  5281.1  468.64  5296.4  468.43  5336.6  469.19
#Mann=3,-1,0
  4295.2     0.1       0  4988.7    0.07       0  4995.5     0.1       0
Bank Sta=4988.7,4995.5
Exp/Cntr=0.3,0.1

Type RM Length L Ch R = 1,8199,383,383,383
BEGIN DESCRIPTION:
Mapping XS b7d39a17
END DESCRIPTION:
XS GIS Cut Line= 4
      2064259.38     13483081.29      2063929.07     13482866.86
      2063516.31     13482718.42      2063308.32     13482740.42
#Sta/Elev= 30
  4321.0  464.69  4350.1  464.24  4385.8  464.52  4400.3  463.67  4421.6  463.85
  4457.6  462.82  4503.1  462.48  4509.0  462.96  4545.3  462.17  4648.1  461.36
  4690.3  461.80  4740.4  461.12  4857.9  461.20  4914.1  460.04  4921.0  460.48
  4931.7  459.29  4944.8  459.06  4952.9  459.79  4963.6  460.02  4992.0  458.68
  4992.5  457.88  4998.3  457.88  4998.8  458.68  5006.2  461.22  5016.7  460.85
  5026.3  461.74  5149.2  464.36  5151.5  464.80  5235.2  465.82  5362.6  466.35
#Mann=3,-1,0
  4321.0     0.1       0  4992.0    0.07       0  4998.8     0.1       0
Bank Sta=4992,4998.8
Exp/Cntr=0.3,0.1

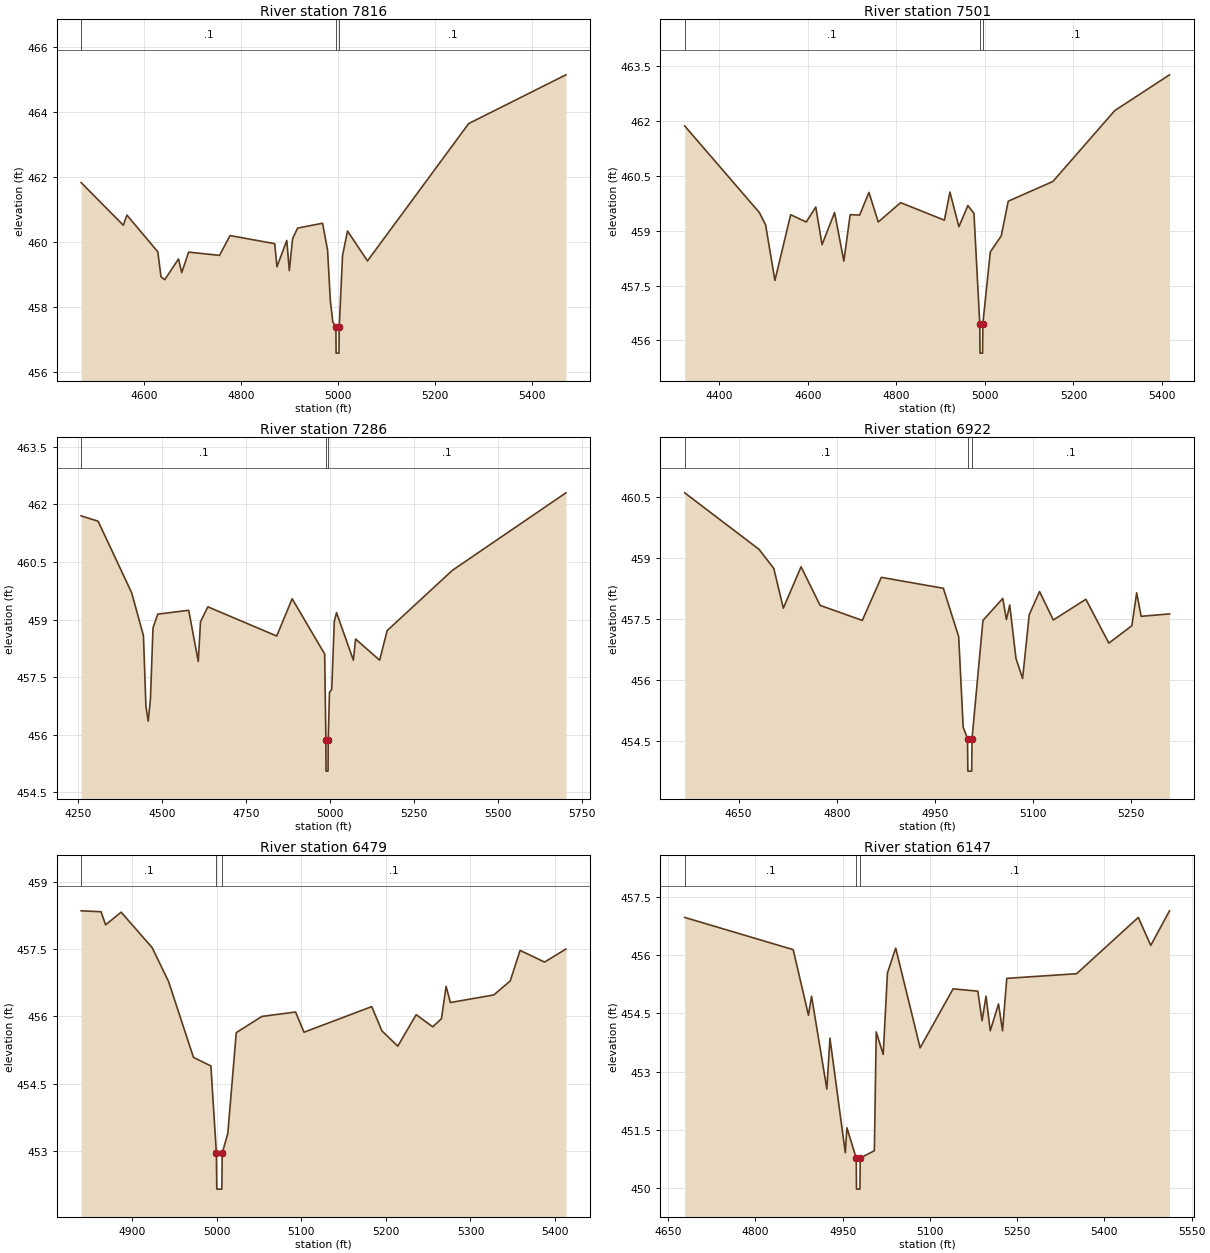
Type RM Length L Ch R = 1,7816,315,315,315
BEGIN DESCRIPTION:
Mapping XS e5be6ae0
END DESCRIPTION:
XS GIS Cut Line= 4
      2064176.95     13482755.80      2063873.08     13482485.35
      2063559.27     13482559.57      2063308.36     13482657.48
#Sta/Elev= 30
  4470.5  461.83  4557.3  460.52  4564.8  460.83  4628.4  459.70  4635.0  458.93
  4642.6  458.84  4671.0  459.48  4677.7  459.06  4691.9  459.69  4755.5  459.59
  4777.2  460.20  4869.2  459.95  4873.8  459.24  4894.1  460.05  4899.3  459.12
  4906.1  460.11  4916.4  460.43  4967.8  460.58  4978.1  459.75  4983.8  458.20
  4988.9  457.54  4995.2  457.38  4995.7  456.58  5001.6  456.58  5002.1  457.38
  5008.9  459.58  5019.2  460.34  5060.3  459.42  5268.8  463.65  5469.1  465.15
#Mann=3,-1,0
  4470.5     0.1       0  4995.2    0.07       0  5002.1     0.1       0
Bank Sta=4995.2,5002.1
Exp/Cntr=0.3,0.1

Type RM Length L Ch R = 1,7501,215,215,215
BEGIN DESCRIPTION:
Mapping XS 8834fde9
END DESCRIPTION:
XS GIS Cut Line= 4
      2064213.81     13482714.53      2063863.96     13482387.69
      2063542.35     13482335.61      2063289.83     13482479.89
#Sta/Elev= 30
  4321.8  461.87  4490.4  459.50  4504.6  459.16  4525.6  457.64  4561.2  459.44
  4596.4  459.24  4617.9  459.65  4632.1  458.62  4660.4  459.50  4681.4  458.17
  4695.6  459.44  4717.0  459.43  4738.1  460.05  4759.1  459.24  4809.6  459.77
  4908.6  459.29  4921.1  460.06  4941.3  459.11  4961.6  459.69  4975.3  459.48
  4988.5  456.45  4989.0  455.65  4994.9  455.65  4995.4  456.45  5012.3  458.42
  5037.0  458.86  5052.8  459.81  5153.7  460.35  5293.4  462.29  5417.2  463.27
#Mann=3,-1,0
  4321.8     0.1       0  4988.5    0.07       0  4995.4     0.1       0
Bank Sta=4988.5,4995.4
Exp/Cntr=0.3,0.1

Type RM Length L Ch R = 1,7286,364,364,364
BEGIN DESCRIPTION:
Mapping XS 905f036f
END DESCRIPTION:
XS GIS Cut Line= 5
      2064229.00     13482662.45      2063759.80     13482245.77
      2063763.70     13482180.66      2063669.95     13482097.33
      2063115.70     13482382.53
#Sta/Elev= 30
  4259.9  461.70  4310.4  461.56  4409.9  459.70  4445.1  458.58  4452.5  456.74
  4459.3  456.35  4466.0  456.94  4473.5  458.78  4487.7  459.14  4579.7  459.24
  4608.1  457.91  4614.8  458.94  4636.6  459.33  4841.4  458.57  4887.3  459.54
  4984.0  458.10  4987.6  455.85  4988.1  455.05  4994.0  455.05  4994.5  455.85
  4998.3  457.10  5005.0  457.18  5012.5  458.94  5019.2  459.18  5069.3  457.94
  5076.0  458.49  5147.5  457.94  5169.7  458.71  5363.6  460.28  5701.4  462.30
#Mann=3,-1,0
  4259.9     0.1       0  4987.6    0.07       0  4994.5     0.1       0
Bank Sta=4987.6,4994.5
Exp/Cntr=0.3,0.1

Type RM Length L Ch R = 1,6922,443,443,443
BEGIN DESCRIPTION:
Mapping XS 2f532d16
END DESCRIPTION:
XS GIS Cut Line= 4
      2064194.27     13482575.63      2064003.28     13482322.59
      2063974.64     13482109.05      2063823.20     13481965.85
#Sta/Elev= 30
  4567.6  460.61  4681.1  459.22  4703.7  458.75  4718.3  457.77  4745.4  458.79
  4774.5  457.84  4839.0  457.47  4868.1  458.53  4962.9  458.26  4986.3  457.07
  4993.2  454.84  4999.8  454.56  5000.3  453.76  5006.2  453.76  5006.7  454.56
  5023.4  457.47  5053.7  458.01  5059.3  457.49  5064.3  457.85  5073.9  456.53
  5084.0  456.04  5094.1  457.61  5109.9  458.18  5130.9  457.48  5180.7  457.99
  5215.8  456.91  5251.0  457.34  5258.3  458.15  5265.2  457.57  5308.5  457.63
#Mann=3,-1,0
  4567.6     0.1       0  4999.8    0.07       0  5006.7     0.1       0
Bank Sta=4999.8,5006.7
Exp/Cntr=0.3,0.1

Type RM Length L Ch R = 1,6479,332,332,332
BEGIN DESCRIPTION:
Mapping XS 26c0cc7c
END DESCRIPTION:
XS GIS Cut Line= 4
      2064359.43     13481960.85      2064328.70     13481887.41
      2064057.85     13481899.60      2063842.56     13481955.62
#Sta/Elev= 30
  4839.7  458.35  4863.2  458.33  4868.6  458.04  4887.0  458.32  4923.7  457.53
  4943.0  456.78  4972.5  455.09  4993.1  454.90  4999.6  452.96  5000.1  452.16
  5006.0  452.16  5006.5  452.96  5013.1  453.40  5023.1  455.64  5053.2  456.00
  5093.2  456.10  5103.2  455.65  5183.3  456.22  5195.3  455.68  5214.1  455.34
  5235.8  456.04  5255.4  455.77  5265.7  455.95  5271.2  456.67  5276.3  456.31
  5327.7  456.48  5347.0  456.79  5358.7  457.47  5387.6  457.21  5412.9  457.50
#Mann=3,-1,0
  4839.7     0.1       0  4999.6    0.07       0  5006.5     0.1       0
Bank Sta=4999.6,5006.5
Exp/Cntr=0.3,0.1

Type RM Length L Ch R = 1,6147,44,44,44
BEGIN DESCRIPTION:
Mapping XS bd74c9a3
END DESCRIPTION:
XS GIS Cut Line= 4
      2064539.30     13481638.14      2064274.54     13481549.91
      2064229.74     13481572.83      2063862.29     13481918.08
#Sta/Elev= 30
  4678.3  456.97  4864.8  456.14  4891.1  454.45  4896.4  454.94  4922.7  452.55
  4928.0  453.86  4954.4  450.91  4957.2  451.55  4973.2  450.77  4973.7  449.97
  4979.6  449.97  4980.1  450.77  5004.4  450.96  5007.6  454.02  5019.6  453.44
  5026.9  455.54  5041.1  456.18  5083.1  453.61  5139.8  455.13  5182.3  455.07
  5189.6  454.31  5196.4  454.94  5203.7  454.05  5217.9  454.74  5224.8  454.05
  5232.1  455.40  5352.2  455.52  5458.2  456.97  5479.7  456.25  5511.9  457.14
#Mann=3,-1,0
  4678.3     0.1       0  4973.2    0.07       0  4980.1     0.1       0
Bank Sta=4973.2,4980.1
Exp/Cntr=0.3,0.1

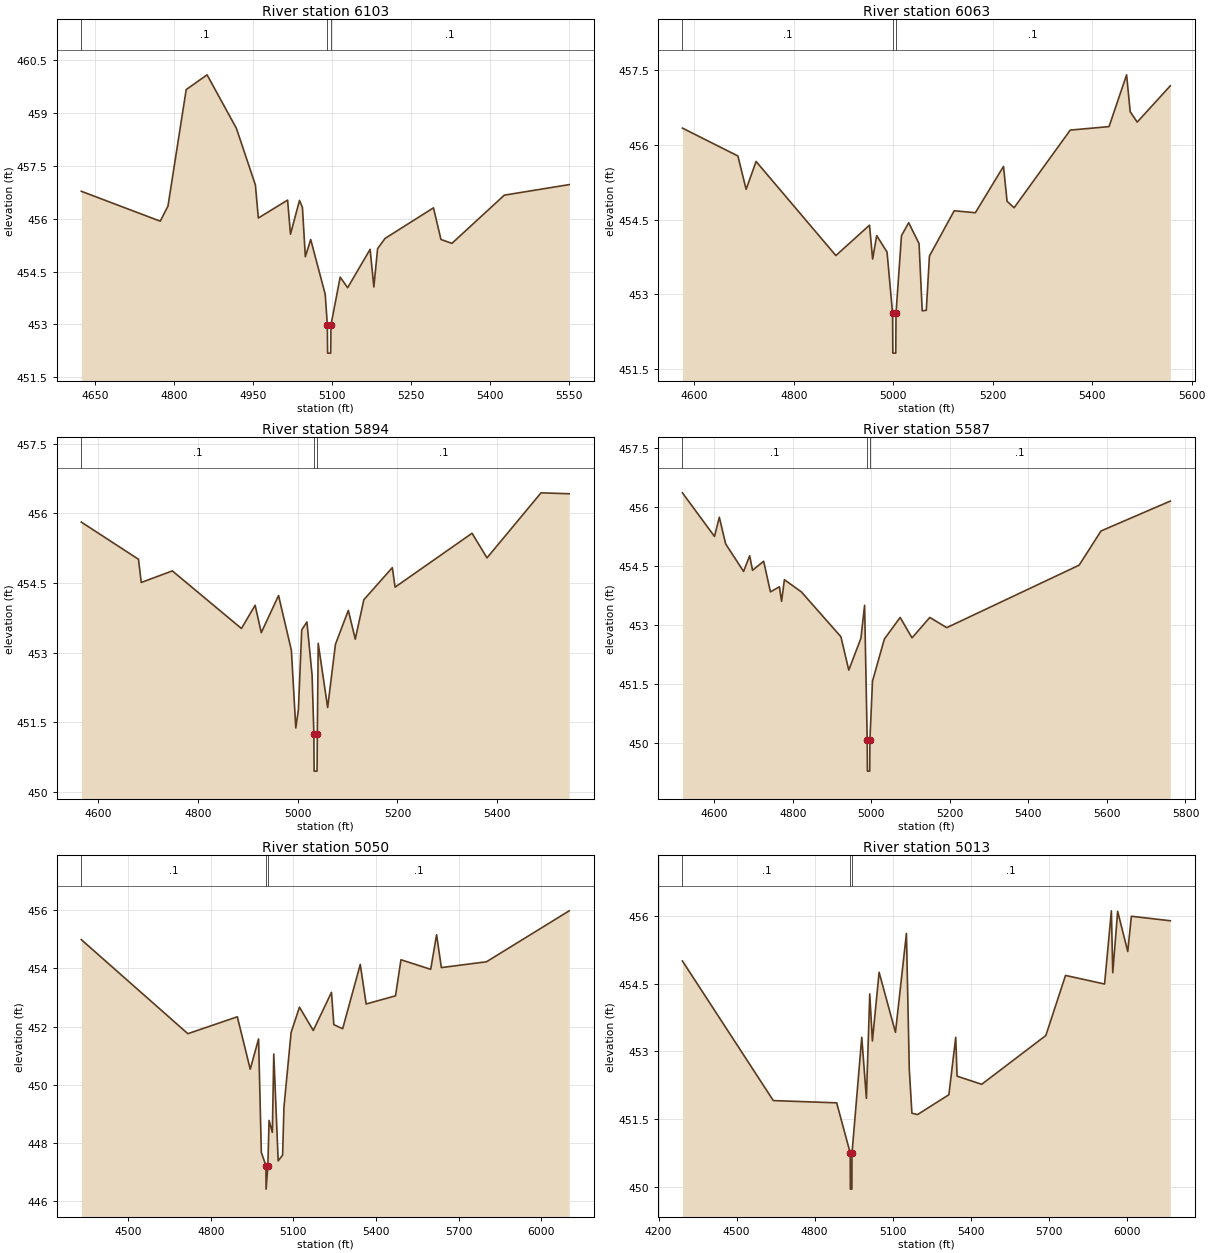
Type RM Length L Ch R = 1,6103,40,40,40
BEGIN DESCRIPTION:
Mapping XS 30912147
END DESCRIPTION:
XS GIS Cut Line= 6
      2064569.76     13481573.06      2064297.45     13481498.87
      2064251.62     13481498.35      2064228.70     13481510.33
      2064191.20     13481588.45      2063827.52     13481911.61
#Sta/Elev= 30
  4623.4  456.78  4773.4  455.93  4788.1  456.36  4822.7  459.67  4862.4  460.09
  4918.1  458.57  4954.2  456.96  4959.8  456.02  5015.4  456.53  5020.9  455.56
  5038.0  456.52  5043.6  456.32  5049.1  454.92  5059.3  455.41  5086.9  453.85
  5090.9  452.98  5091.4  452.18  5097.3  452.18  5097.8  452.98  5115.3  454.34
  5129.5  454.04  5172.2  455.13  5179.3  454.06  5186.4  455.15  5200.6  455.44
  5292.6  456.31  5306.8  455.41  5327.7  455.30  5427.2  456.67  5550.5  456.97
#Mann=3,-1,0
  4623.4     0.1       0  5090.9    0.07       0  5097.8     0.1       0
Bank Sta=5090.9,5097.8
Exp/Cntr=0.3,0.1

Type RM Length L Ch R = 1,6063,169,169,169
BEGIN DESCRIPTION:
Mapping XS 1d22b071
END DESCRIPTION:
XS GIS Cut Line= 4
      2064582.72     13481458.03      2064244.33     13481433.25
      2064143.91     13481563.48      2063799.68     13481893.90
#Sta/Elev= 30
  4576.2  456.34  4687.7  455.78  4704.3  455.11  4724.3  455.67  4884.7  453.78
  4952.3  454.39  4958.6  453.71  4966.8  454.18  4987.6  453.85  4998.7  452.62
  4999.2  451.82  5005.1  451.82  5005.6  452.62  5016.6  454.18  5031.1  454.44
  5051.9  454.02  5058.3  452.67  5066.5  452.68  5072.8  453.77  5122.6  454.68
  5165.1  454.64  5221.7  455.57  5228.9  454.87  5243.0  454.74  5355.9  456.30
  5433.9  456.37  5469.2  457.41  5476.4  456.67  5490.5  456.46  5557.1  457.19
#Mann=3,-1,0
  4576.2     0.1       0  4998.7    0.07       0  5005.6     0.1       0
Bank Sta=4998.7,5005.6
Exp/Cntr=0.3,0.1

Type RM Length L Ch R = 1,5894,307,307,307
BEGIN DESCRIPTION:
Mapping XS 09ac1926
END DESCRIPTION:
XS GIS Cut Line= 4
      2064585.35     13481379.90      2064490.26     13481316.08
      2064000.00     13481450.00      2063864.42     13481777.07
#Sta/Elev= 30
  4567.0  455.81  4681.5  455.01  4687.0  454.51  4749.2  454.76  4887.6  453.52
  4915.0  454.02  4927.3  453.43  4961.9  454.23  4987.6  453.05  4996.4  451.38
  5001.6  451.77  5008.3  453.49  5018.7  453.66  5029.1  452.51  5032.6  451.25
  5033.1  450.45  5039.0  450.45  5039.5  451.25  5041.3  453.20  5060.2  451.82
  5075.8  453.18  5101.6  453.91  5115.5  453.29  5132.7  454.14  5189.7  454.83
  5195.2  454.41  5349.3  455.57  5379.2  455.04  5487.4  456.44  5543.8  456.42
#Mann=3,-1,0
  4567.0     0.1       0  5032.6    0.07       0  5039.5     0.1       0
Bank Sta=5032.6,5039.5
Exp/Cntr=0.3,0.1

Type RM Length L Ch R = 1,5587,537,537,537
BEGIN DESCRIPTION:
Mapping XS 3ae58db2
END DESCRIPTION:
XS GIS Cut Line= 5
      2064699.98     13481286.62      2064435.58     13481162.43
      2064100.00     13481200.00      2063970.77     13481425.48
      2063849.63     13481756.44
#Sta/Elev= 30
  4519.3  456.36  4601.0  455.25  4613.2  455.74  4629.4  455.06  4675.0  454.36
  4690.5  454.76  4697.8  454.39  4726.1  454.62  4743.4  453.84  4766.2  453.97
  4771.7  453.60  4778.9  454.15  4822.1  453.84  4922.7  452.70  4942.8  451.85
  4973.7  452.66  4983.1  453.50  4989.7  450.08  4990.2  449.28  4996.1  449.28
  4996.6  450.08  5003.2  451.57  5033.4  452.64  5073.6  453.19  5103.8  452.67
  5149.1  453.19  5192.2  452.93  5529.3  454.52  5585.0  455.39  5761.4  456.15
#Mann=3,-1,0
  4519.3     0.1       0  4989.7    0.07       0  4996.6     0.1       0
Bank Sta=4989.7,4996.6
Exp/Cntr=0.3,0.1

Type RM Length L Ch R = 1,5050,37,37,37
BEGIN DESCRIPTION:
Mapping XS a4e09e3f
END DESCRIPTION:
XS GIS Cut Line= 5
      2064778.02     13481058.70      2064296.41     13480732.20
      2064194.33     13480746.27      2064177.14     13480799.39
      2063819.42     13481766.84
#Sta/Elev= 30
  4329.9  454.99  4716.9  451.76  4896.6  452.34  4943.5  450.54  4973.8  451.58
  4983.8  447.68  5000.6  447.22  5001.1  446.42  5007.5  447.22  5011.9  448.78
  5023.8  448.37  5029.0  451.06  5045.0  447.39  5061.1  447.59  5066.0  449.24
  5091.9  451.80  5122.3  452.67  5172.5  451.87  5238.6  453.18  5247.2  452.07
  5279.2  451.93  5343.2  454.14  5364.5  452.78  5471.2  453.06  5491.0  454.30
  5599.0  453.97  5620.4  455.16  5637.7  454.03  5801.6  454.23  6102.1  455.98
#Mann=3,-1,0
  4329.9     0.1       0  5000.6    0.07       0  5007.5     0.1       0
Bank Sta=5000.6,5007.5
Exp/Cntr=0.3,0.1

Type RM Length L Ch R = 1,5013,51,51,51
BEGIN DESCRIPTION:
Mapping XS a2b5815d
END DESCRIPTION:
XS GIS Cut Line= 5
      2064797.59     13481045.71      2064267.24     13480694.18
      2064143.81     13480721.27      2064120.37     13480790.02
      2063788.48     13481777.03
#Sta/Elev= 30
  4291.9  455.00  4641.5  451.91  4885.2  451.86  4937.3  450.75  4937.8  449.95
  4943.7  449.95  4944.2  450.75  4981.7  453.31  4999.5  451.96  5012.4  454.27
  5022.6  453.23  5048.4  454.75  5111.3  453.42  5153.5  455.61  5164.5  452.60
  5174.6  451.63  5196.1  451.60  5316.8  452.04  5343.1  453.31  5348.3  452.45
  5442.9  452.27  5689.7  453.35  5765.4  454.68  5915.6  454.49  5941.8  456.11
  5947.1  454.74  5965.9  456.10  6004.8  455.21  6018.7  455.99  6168.5  455.89
#Mann=3,-1,0
  4291.9     0.1       0  4937.3    0.07       0  4944.2     0.1       0
Bank Sta=4937.3,4944.2
Exp/Cntr=0.3,0.1

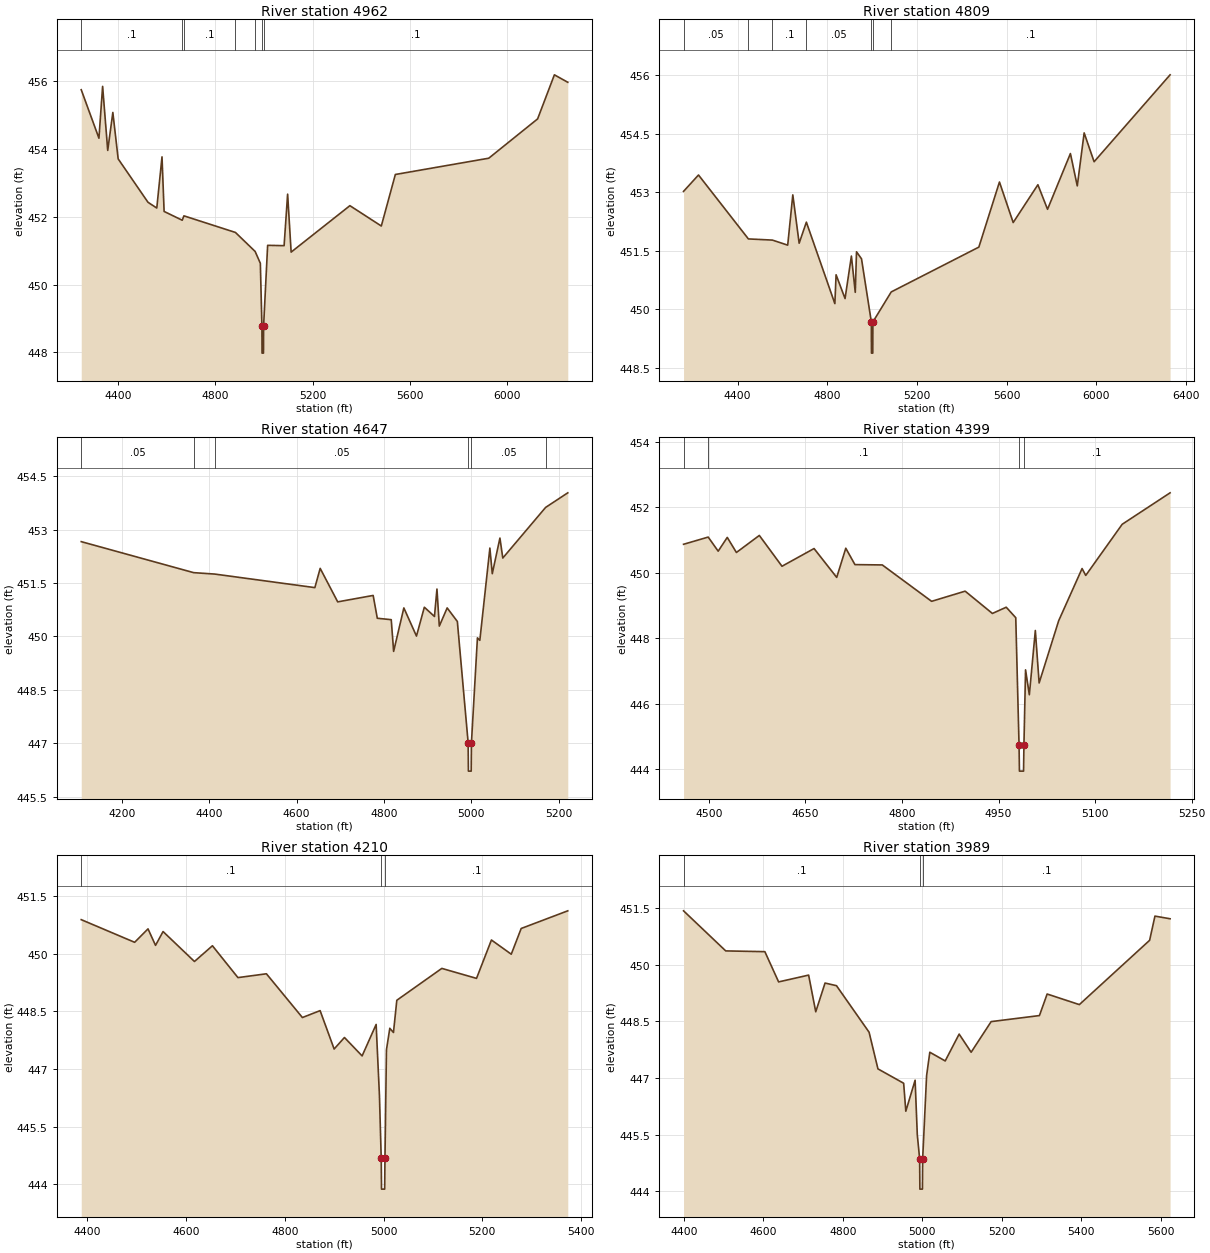
Type RM Length L Ch R = 1,4962,153,153,153
BEGIN DESCRIPTION:
Mapping XS 887c20ff
END DESCRIPTION:
XS GIS Cut Line= 5
      2064821.43     13481019.65      2064276.10     13480657.72
      2064130.79     13480662.93      2064060.99     13480717.62
      2063766.76     13481787.94
#Sta/Elev= 30
  4249.8  455.75  4322.5  454.32  4337.6  455.85  4358.6  453.96  4379.6  455.08
  4401.5  453.71  4524.0  452.43  4560.1  452.26  4581.6  453.77  4590.2  452.16
  4664.7  451.90  4671.5  452.03  4883.2  451.54  4964.1  450.98  4985.5  450.63
  4992.0  448.78  4992.5  447.98  4998.4  447.98  4998.9  448.78  5015.5  451.16
  5083.1  451.15  5097.6  452.67  5112.0  450.96  5353.4  452.33  5482.4  451.73
  5540.1  453.25  5923.8  453.73  6124.5  454.89  6193.4  456.19  6248.4  455.97
#Mann=7,-1,0
  4249.8     0.1       0  4664.7    0.08       0  4671.5     0.1       0
  4883.2    0.05       0  4964.1     0.1       0  4992.0    0.07       0
  4998.9     0.1       0
Bank Sta=4992,4998.9
Exp/Cntr=0.3,0.1

Type RM Length L Ch R = 1,4809,162,162,162
BEGIN DESCRIPTION:
Mapping XS 3b593731
END DESCRIPTION:
XS GIS Cut Line= 4
      2064830.05     13480908.59      2064110.82     13480568.73
      2063997.02     13480565.28      2063740.83     13481800.45
#Sta/Elev= 30
  4159.0  453.02  4225.7  453.44  4448.3  451.80  4555.5  451.77  4623.7  451.64
  4646.5  452.93  4674.8  451.69  4707.0  452.23  4834.1  450.14  4839.6  450.88
  4879.6  450.27  4907.9  451.36  4925.2  450.43  4930.7  451.47  4953.0  451.29
  4996.9  449.67  4997.4  448.87  5003.3  448.87  5003.8  449.67  5085.6  450.44
  5476.6  451.59  5568.5  453.26  5629.8  452.22  5740.0  453.19  5783.0  452.56
  5885.1  453.99  5915.7  453.16  5946.4  454.52  5990.8  453.78  6329.8  456.01
#Mann=7,-1,0
  4159.0    0.05       0  4448.3    0.08       0  4555.5     0.1       0
  4707.0    0.05       0  4996.9    0.04       0  5003.8    0.05       0
  5085.6     0.1       0
Bank Sta=4996.9,5003.8
Exp/Cntr=0.3,0.1

Type RM Length L Ch R = 1,4647,248,248,248
BEGIN DESCRIPTION:
Mapping XS bc068d99
END DESCRIPTION:
XS GIS Cut Line= 4
      2064806.72     13480815.13      2064020.98     13480473.18
      2063922.37     13480428.04      2063819.52     13480320.46
#Sta/Elev= 30
  4106.9  452.66  4364.3  451.79  4412.5  451.75  4641.9  451.37  4654.1  451.91
  4694.2  450.97  4775.4  451.15  4784.9  450.51  4816.8  450.47  4822.3  449.58
  4845.7  450.80  4874.6  450.01  4892.6  450.82  4915.8  450.56  4921.5  451.33
  4926.9  450.29  4944.9  450.80  4968.2  450.42  4992.9  447.02  4993.5  446.22
  4999.9  446.22  5000.5  447.02  5014.2  449.96  5019.7  449.89  5042.7  452.48
  5048.2  451.76  5065.7  452.76  5072.3  452.20  5170.3  453.62  5221.1  454.03
#Mann=6,-1,0
  4106.9    0.05       0  4364.3    0.08       0  4412.5    0.05       0
  4992.9    0.04       0  5000.5    0.05       0  5170.3     0.1       0
Bank Sta=4992.9,5000.5
Exp/Cntr=0.3,0.1

Type RM Length L Ch R = 1,4399,189,189,189
BEGIN DESCRIPTION:
Mapping XS 0b71480f
END DESCRIPTION:
XS GIS Cut Line= 4
      2064522.49     13480643.73      2064241.46     13480378.38
      2064040.42     13480249.22      2063911.12     13480264.86
#Sta/Elev= 30
  4460.7  450.87  4499.0  451.09  4514.5  450.66  4528.6  451.08  4542.8  450.62
  4578.4  451.14  4613.6  450.20  4663.4  450.74  4698.6  449.86  4712.7  450.75
  4726.9  450.25  4769.4  450.24  4846.0  449.13  4898.1  449.44  4940.4  448.76
  4961.9  448.95  4976.7  448.63  4981.8  444.75  4982.4  443.95  4988.8  443.95
  4989.4  444.75  4991.9  447.04  4997.8  446.28  5007.1  448.24  5013.0  446.64
  5043.4  448.54  5079.7  450.13  5085.4  449.92  5142.0  451.48  5216.4  452.44
#Mann=4,-1,0
  4460.7    0.05       0  4499.0     0.1       0  4981.8    0.07       0
  4989.4     0.1       0
Bank Sta=4981.8,4989.4
Exp/Cntr=0.3,0.1

Type RM Length L Ch R = 1,4210,221,221,221
BEGIN DESCRIPTION:
Mapping XS c63748da
END DESCRIPTION:
XS GIS Cut Line= 4
      2064570.22     13480667.60      2064313.86     13480262.24
      2064163.86     13480098.70      2063881.13     13480128.15
#Sta/Elev= 30
  4387.4  450.89  4495.6  450.30  4522.7  450.65  4537.9  450.22  4553.2  450.58
  4616.8  449.80  4653.2  450.21  4704.9  449.38  4762.6  449.48  4835.5  448.34
  4871.4  448.52  4899.8  447.52  4920.7  447.82  4956.5  447.34  4984.9  448.16
  4991.6  446.31  4995.2  444.67  4995.8  443.87  5002.2  443.87  5002.8  444.67
  5005.8  447.50  5012.6  448.06  5020.0  447.95  5026.8  448.79  5118.0  449.62
  5188.3  449.36  5218.5  450.36  5258.7  449.99  5278.8  450.66  5373.2  451.12
#Mann=3,-1,0
  4387.4     0.1       0  4995.2    0.07       0  5002.8     0.1       0
Bank Sta=4995.2,5002.8
Exp/Cntr=0.3,0.1

Type RM Length L Ch R = 1,3989,188,188,188
BEGIN DESCRIPTION:
Mapping XS 8d2f3b37
END DESCRIPTION:
XS GIS Cut Line= 5
      2064654.85     13480702.33      2064453.96     13480245.57
      2064383.65     13480084.63      2064073.24     13480049.09
      2063848.99     13480125.94
#Sta/Elev= 30
  4399.1  451.42  4505.2  450.36  4603.7  450.34  4638.3  449.54  4713.8  449.72
  4731.7  448.75  4755.1  449.51  4783.9  449.44  4865.9  448.21  4888.2  447.24
  4952.9  446.86  4958.3  446.12  4981.7  446.94  4987.2  445.50  4993.1  444.86
  4993.7  444.06  5000.1  444.06  5000.7  444.86  5010.6  447.06  5018.7  447.68
  5057.4  447.45  5092.5  448.16  5122.7  447.68  5173.0  448.49  5294.5  448.65
  5313.9  449.22  5394.9  448.94  5571.7  450.64  5585.1  451.28  5623.2  451.21
#Mann=3,-1,0
  4399.1     0.1       0  4993.1    0.07       0  5000.7     0.1       0
Bank Sta=4993.1,5000.7
Exp/Cntr=0.3,0.1

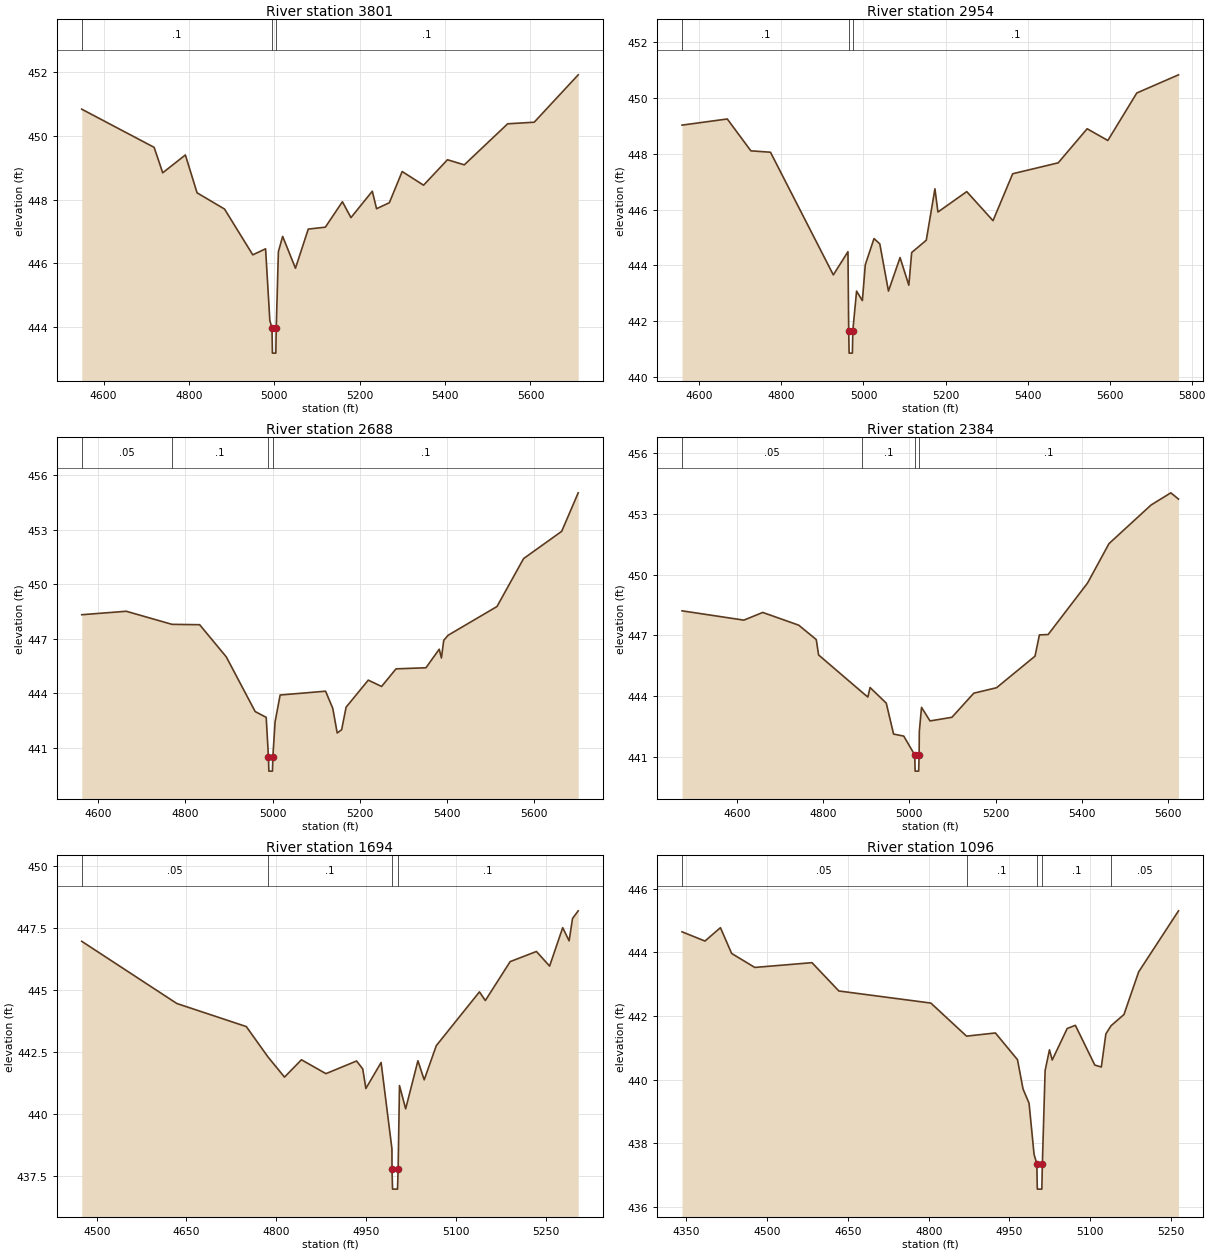
Type RM Length L Ch R = 1,3801,847,847,847
BEGIN DESCRIPTION:
Mapping XS 88091e34
END DESCRIPTION:
XS GIS Cut Line= 4
      2064913.59     13480035.95      2064553.37     13479996.88
      2064073.93     13480003.73      2063784.78     13480143.78
#Sta/Elev= 30
  4548.7  450.84  4718.3  449.64  4738.4  448.84  4791.5  449.40  4818.9  448.21
  4883.2  447.70  4949.4  446.26  4979.4  446.45  4989.4  444.19  4994.4  443.97
  4995.4  443.17  5003.4  443.17  5004.4  443.97  5009.4  446.36  5019.4  446.84
  5049.4  445.84  5079.4  447.07  5119.4  447.13  5159.4  447.93  5179.4  447.43
  5229.4  448.26  5239.4  447.71  5269.4  447.90  5299.4  448.88  5349.5  448.45
  5405.5  449.25  5444.9  449.09  5546.5  450.38  5608.7  450.43  5711.8  451.92
#Mann=3,-1,0
  4548.7     0.1       0  4994.4    0.07       0  5004.4     0.1       0
Bank Sta=4994.4,5004.4
Exp/Cntr=0.3,0.1

Type RM Length L Ch R = 1,2954,266,266,266
BEGIN DESCRIPTION:
Mapping XS 50397934
END DESCRIPTION:
XS GIS Cut Line= 4
      2064422.46     13479357.99      2064148.19     13479294.63
      2063810.25     13479654.02      2063753.84     13480085.83
#Sta/Elev= 30
  4557.7  449.02  4668.0  449.24  4725.5  448.10  4773.3  448.05  4926.5  443.66
  4962.2  444.49  4964.0  441.66  4965.0  440.86  4973.0  440.86  4974.0  441.66
  4983.2  443.08  4997.3  442.74  5004.4  444.02  5025.7  444.96  5039.8  444.77
  5060.9  443.08  5089.2  444.28  5110.6  443.29  5117.5  444.46  5153.1  444.90
  5174.2  446.74  5181.5  445.91  5251.8  446.64  5315.8  445.60  5363.8  447.28
  5474.7  447.67  5545.3  448.89  5595.7  448.47  5666.3  450.17  5768.0  450.82
#Mann=3,-1,0
  4557.7     0.1       0  4964.0    0.07       0  4974.0     0.1       0
Bank Sta=4964,4974
Exp/Cntr=0.3,0.1

Type RM Length L Ch R = 1,2688,304,304,304
BEGIN DESCRIPTION:
Mapping XS 55eceae6
END DESCRIPTION:
XS GIS Cut Line= 4
      2064420.03     13479211.31      2064257.30     13479176.59
      2063415.29     13479337.18      2063319.93     13479402.20
#Sta/Elev= 30
  4562.3  448.33  4664.5  448.52  4769.3  447.80  4832.8  447.78  4893.9  446.01
  4960.2  443.00  4985.5  442.68  4990.6  440.52  4991.6  439.72  4999.8  439.72
  5000.8  440.52  5005.9  442.44  5017.5  443.91  5121.7  444.12  5138.2  443.18
  5148.4  441.82  5158.6  442.00  5168.8  443.24  5219.7  444.73  5250.2  444.38
  5283.3  445.35  5352.0  445.41  5382.4  446.43  5387.5  445.95  5392.8  446.92
  5402.9  447.20  5514.9  448.78  5576.0  451.42  5663.4  452.92  5701.3  455.04
#Mann=4,-1,0
  4562.3    0.05       0  4769.3     0.1       0  4990.6    0.07       0
  5000.8     0.1       0
Bank Sta=4990.6,5000.8
Exp/Cntr=0.3,0.1

Type RM Length L Ch R = 1,2384,690,690,690
BEGIN DESCRIPTION:
Mapping XS e36e52cb
END DESCRIPTION:
XS GIS Cut Line= 4
      2064341.97     13479068.10      2064109.73     13478987.79
      2063371.89     13479115.83      2063324.13     13479265.60
#Sta/Elev= 30
  4472.6  448.21  4616.0  447.75  4659.9  448.13  4743.4  447.50  4784.0  446.79
  4789.4  446.03  4890.8  444.18  4903.7  443.95  4908.8  444.42  4946.4  443.65
  4963.4  442.12  4987.0  442.02  5012.4  441.09  5013.4  440.29  5021.6  440.29
  5022.6  441.09  5023.1  442.25  5028.2  443.44  5047.9  442.77  5098.7  442.95
  5149.4  444.14  5202.2  444.41  5291.5  445.97  5301.7  447.02  5322.0  447.04
  5413.3  449.58  5463.1  451.53  5560.8  453.44  5606.6  454.04  5624.4  453.73
#Mann=4,-1,0
  4472.6    0.05       0  4890.8     0.1       0  5012.4    0.07       0
  5022.6     0.1       0
Bank Sta=5012.4,5022.6
Exp/Cntr=0.3,0.1

Type RM Length L Ch R = 1,1694,598,598,598
BEGIN DESCRIPTION:
Mapping XS 4a58f112
END DESCRIPTION:
XS GIS Cut Line= 4
      2064118.44     13478601.52      2063903.57     13478462.62
      2063462.60     13478560.33      2063405.29     13478668.01
#Sta/Elev= 30
  4475.0  446.96  4633.9  444.45  4749.9  443.52  4786.3  442.29  4813.8  441.48
  4842.1  442.18  4883.0  441.62  4934.2  442.13  4944.5  441.81  4949.7  441.02
  4975.2  442.07  4993.3  438.58  4993.4  437.76  4994.3  436.96  5002.6  436.96
  5003.6  437.76  5005.9  441.14  5016.2  440.20  5036.7  442.14  5047.2  441.37
  5067.4  442.75  5139.5  444.92  5149.3  444.57  5190.8  446.14  5234.7  446.55
  5256.7  445.96  5278.6  447.51  5289.3  446.98  5295.0  447.88  5304.5  448.19
#Mann=4,-1,0
  4475.0    0.05       0  4786.3     0.1       0  4993.4    0.07       0
  5003.6     0.1       0
Bank Sta=4993.4,5003.6
Exp/Cntr=0.3,0.1

Type RM Length L Ch R = 1,1096,512,512,512
BEGIN DESCRIPTION:
Mapping XS 073b2a43
END DESCRIPTION:
XS GIS Cut Line= 4
      2064309.40     13478330.26      2064111.90     13478093.69
      2063614.51     13477980.47      2063511.34     13477990.00
#Sta/Elev= 30
  4342.0  444.65  4384.6  444.36  4413.3  444.78  4434.1  443.97  4477.1  443.53
  4583.3  443.68  4633.2  442.79  4804.0  442.41  4870.3  441.37  4923.9  441.47
  4964.9  440.63  4975.2  439.71  4986.4  439.26  4995.7  437.65  5000.8  437.36
  5001.7  436.56  5010.1  436.56  5011.1  437.36  5016.2  440.29  5024.3  440.94
  5029.4  440.62  5057.2  441.61  5072.4  441.71  5108.5  440.46  5120.6  440.40
  5129.0  441.44  5138.8  441.70  5162.6  442.05  5189.9  443.39  5263.9  445.31
#Mann=5,-1,0
  4342.0    0.05       0  4870.3     0.1       0  5000.8    0.07       0
  5011.1     0.1       0  5138.8    0.05       0
Bank Sta=5000.8,5011.1
Exp/Cntr=0.3,0.1

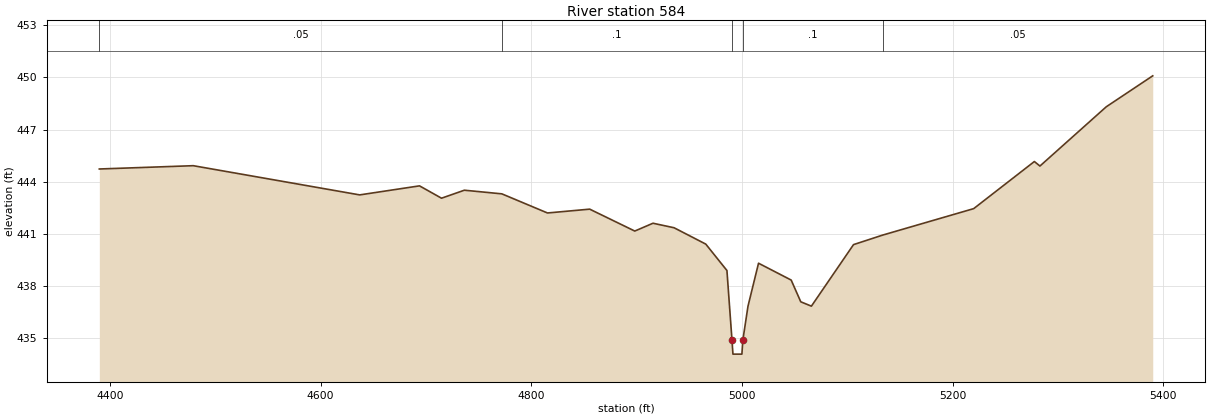
Type RM Length L Ch R = 1,584,0,0,0
BEGIN DESCRIPTION:
UNT 144 in Lagunillas Cr Wtrshd 100.0
END DESCRIPTION:
XS GIS Cut Line= 4
      2064339.81     13477883.22      2064014.25     13477657.50
      2063614.94     13477630.21      2063421.81     13477695.31
#Sta/Elev= 30
  4389.9  444.73  4479.1  444.92  4637.1  443.24  4693.9  443.76  4714.8  443.05
  4736.5  443.51  4772.1  443.30  4815.4  442.20  4855.5  442.42  4898.3  441.16
  4915.6  441.61  4935.6  441.35  4965.7  440.41  4985.8  438.89  4990.6  434.88
  4991.5  434.08  5000.0  434.08  5000.9  434.88  5005.8  436.84  5015.8  439.31
  5046.8  438.34  5055.9  437.09  5066.0  436.84  5106.0  440.38  5133.8  440.93
  5220.1  442.45  5277.7  445.16  5283.0  444.90  5346.0  448.31  5390.1  450.09
#Mann=5,-1,0
  4389.9    0.05       0  4772.1     0.1       0  4990.6    0.07       0
  5000.9     0.1       0  5133.8    0.05       0
Bank Sta=4990.6,5000.9
Exp/Cntr=0.3,0.1

Chan Stop Cuts=-1