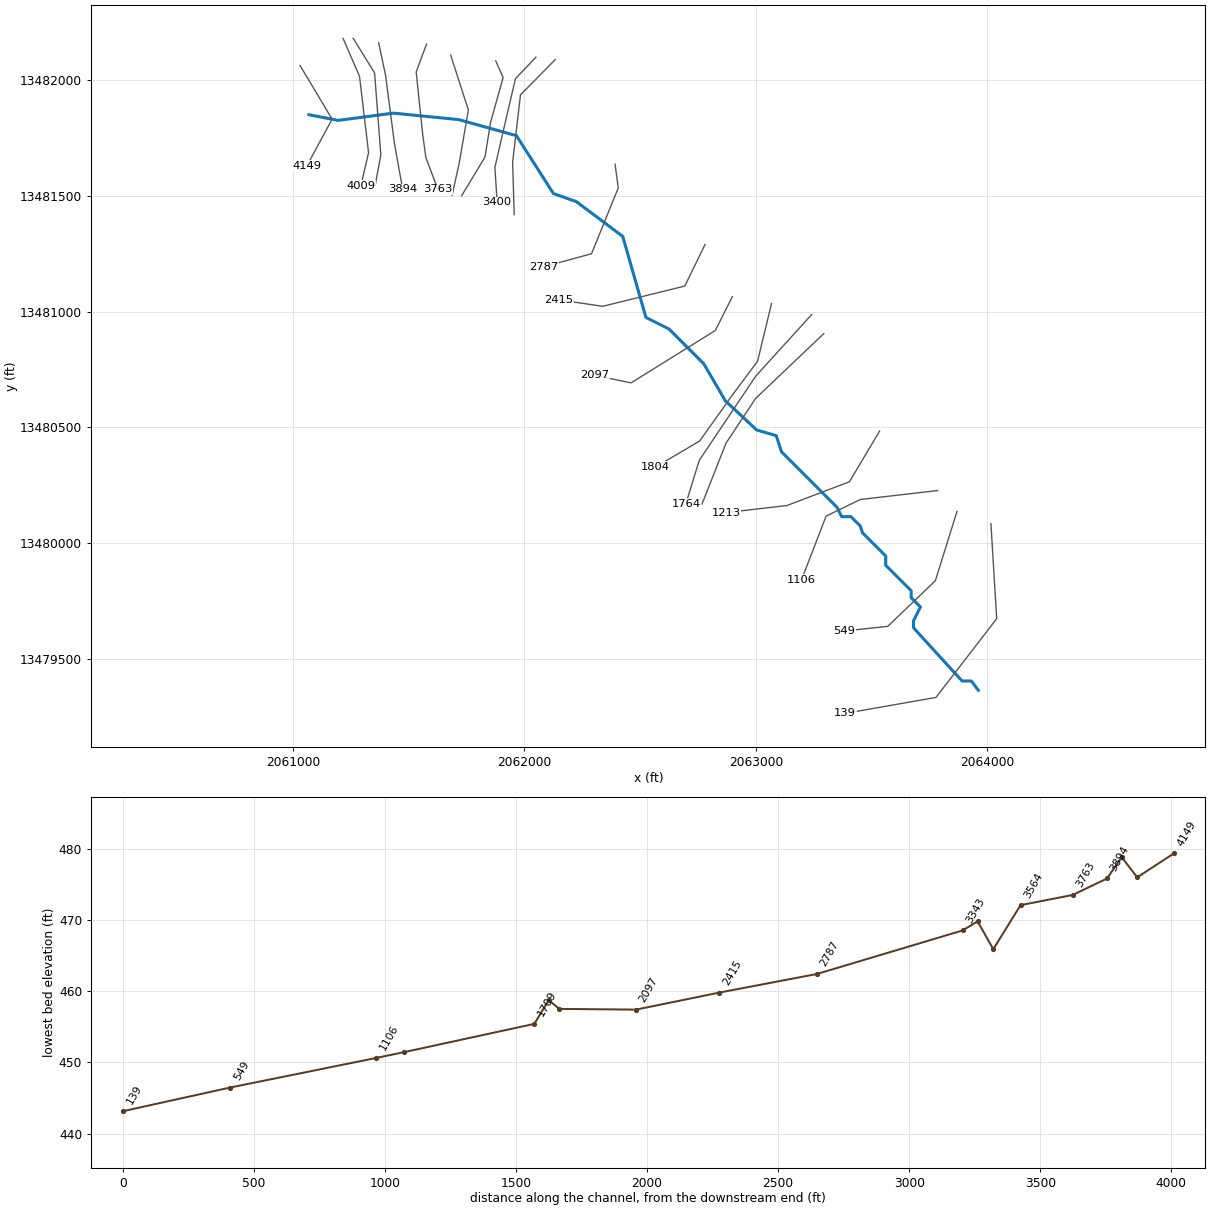
--- UNT 145 in Lagunillas Cr Wtrshd.prj (project) ---

Proj Title=UNT 145 in Lagunillas Cr Wtrshd Base Level Engineering
Current Plan=p01
Default Exp/Contr=0.3,0.1
English Units
Geom File=g01
Flow File=f01
Plan File=p01
BEGIN DESCRIPTION:
UNT 145 in Lagunillas Cr Wtrshd
END DESCRIPTION:

--- UNT 145 in Lagunillas Cr Wtrshd.p01 (plan) ---

Plan Title=Multiple Run
Short Identifier=Multiple
Geom File=g01
Flow File=f01
Subcritical Flow
K Sum by GR= 0
Std Step Tol= 0.01
Critical Tol= 0.01
Num of Std Step Trials= 20
Max Error Tol= 0.3
Flow Tol Ratio= 0.001
Split Flow NTrial= 30
Split Flow Tol= 0.02
Split Flow Ratio= 0.02
Log Output Level= 0
Friction Slope Method= 1
Unsteady Friction Slope Method= 2
Unsteady Bridges Friction Slope Method= 1
Parabolic Critical Depth
Global Vel Dist=  1 , 1 , 1
Global Log Level= 0
CheckData=True
Encroach Param= -1, 0, 0, 0
BEGIN DESCRIPTION:
Multiple Run
END DESCRIPTION:

--- UNT 145 in Lagunillas Cr Wtrshd.f01 (steady flow) ---

Flow Title=Multiple
Number of Profiles=7
Profile Names=10-year,25-year,50-year,1pct_min,100-year,1pct_plu,500-year
River Rch & RM= UNT 145 in Lagun,Reach-1,4149
      71      91     107      63     125     250     174
Boundary for River Rch & Prof#=UNT 145 in Lagun,Reach-1,1
Up Type=0
Dn Type=3
Dn Slope=0.005
Boundary for River Rch & Prof#=UNT 145 in Lagun,Reach-1,2
Up Type=0
Dn Type=3
Dn Slope=0.005
Boundary for River Rch & Prof#=UNT 145 in Lagun,Reach-1,3
Up Type=0
Dn Type=3
Dn Slope=0.005
Boundary for River Rch & Prof#=UNT 145 in Lagun,Reach-1,4
Up Type=0
Dn Type=3
Dn Slope=0.005
Boundary for River Rch & Prof#=UNT 145 in Lagun,Reach-1,5
Up Type=0
Dn Type=3
Dn Slope=0.005
Boundary for River Rch & Prof#=UNT 145 in Lagun,Reach-1,6
Up Type=0
Dn Type=3
Dn Slope=0.005
Boundary for River Rch & Prof#=UNT 145 in Lagun,Reach-1,7
Up Type=0
Dn Type=3
Dn Slope=0.005

--- UNT 145 in Lagunillas Cr Wtrshd.g01 (geometry) ---

Geom Title=Existing Conditions

River Reach=UNT 145 in Lagun,Reach-1
Reach XY= 30
      2061070.03     13481850.40      2061195.03     13481826.09
      2061434.62     13481857.34      2061715.87     13481829.56
      2061965.87     13481760.12      2062125.59     13481510.12
      2062225.00     13481475.00      2062425.00     13481325.00
      2062525.00     13480975.00      2062625.00     13480925.00
      2062775.00     13480775.00      2062868.37     13480614.55
      2063003.79     13480488.69      2063087.99     13480464.38
      2063110.80     13480394.54      2063350.80     13480154.54
      2063370.80     13480114.54      2063410.80     13480114.54
      2063450.80     13480074.54      2063460.80     13480044.54
      2063560.80     13479944.54      2063560.80     13479904.54
      2063670.80     13479794.54      2063670.80     13479764.54
      2063710.80     13479724.54      2063680.80     13479664.54
      2063680.80     13479634.54      2063890.80     13479404.54
      2063930.80     13479404.54      2063960.80     13479364.54

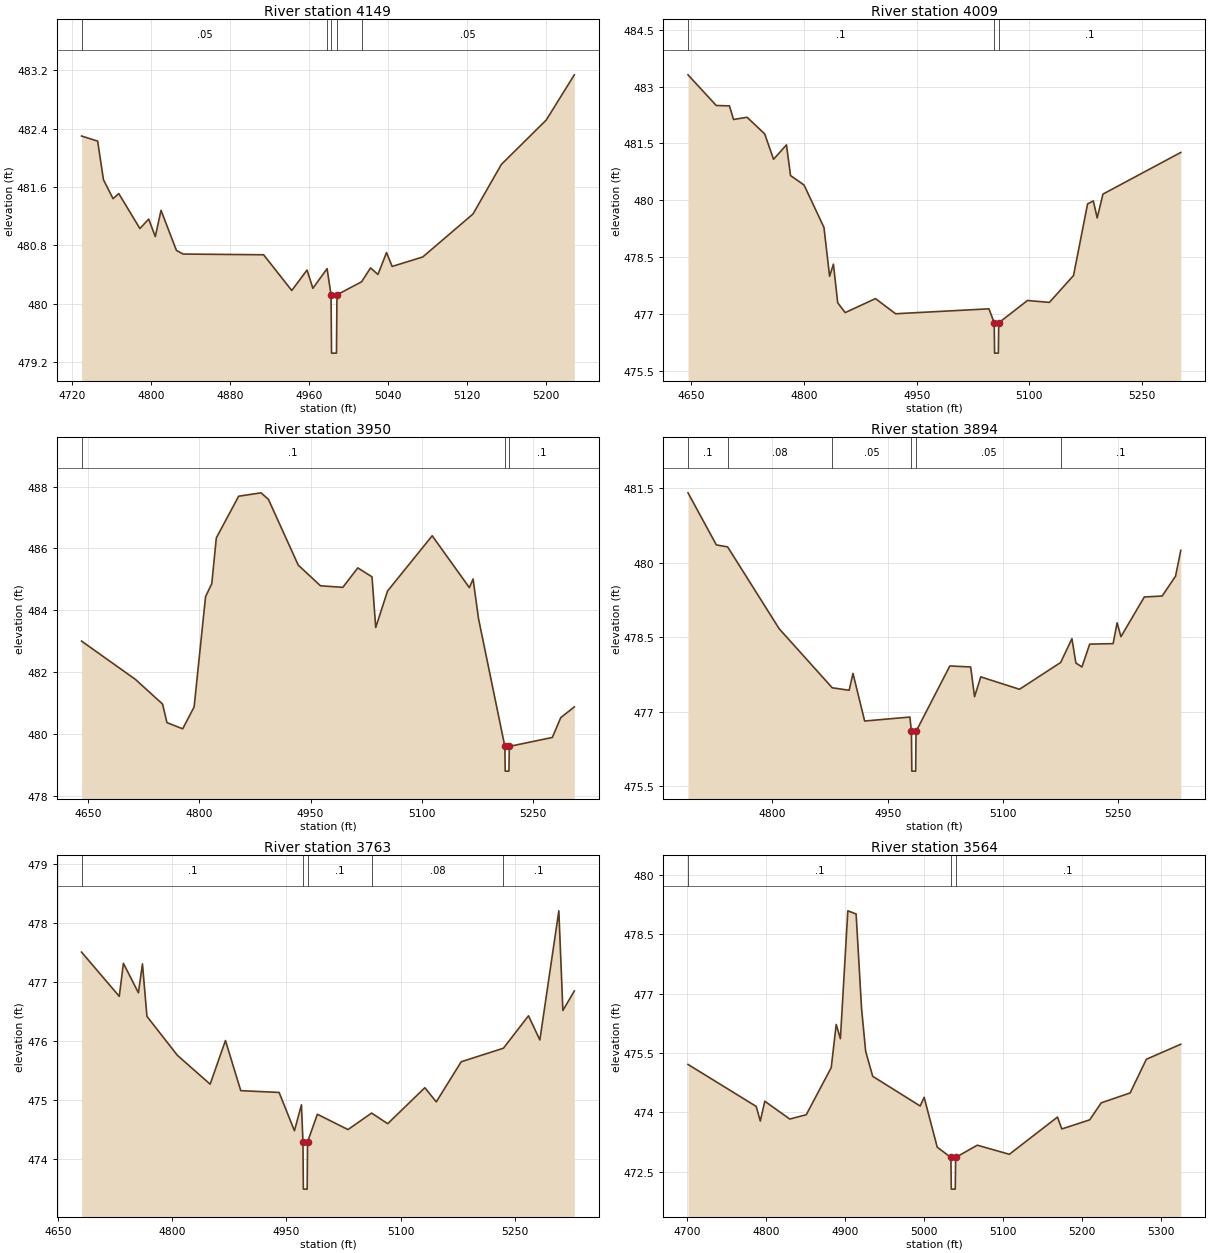
Type RM Length L Ch R = 1,4149,140,140,140
BEGIN DESCRIPTION:
UNT 145 in Lagunillas Cr Wtrshd 9.0
END DESCRIPTION:
XS GIS Cut Line= 3
      2061031.21     13482063.34      2061169.82     13481831.25
      2061061.03     13481630.01
#Sta/Elev= 30
  4729.4  482.30  4745.7  482.23  4751.6  481.70  4761.3  481.44  4767.1  481.51
  4788.5  481.03  4797.4  481.16  4804.1  480.92  4809.9  481.28  4825.5  480.73
  4832.3  480.68  4913.8  480.67  4942.3  480.18  4957.8  480.46  4963.7  480.21
  4978.1  480.48  4982.1  480.12  4982.6  479.32  4987.6  479.32  4988.1  480.12
  5013.1  480.30  5022.1  480.49  5029.6  480.40  5038.3  480.70  5044.0  480.51
  5075.0  480.64  5125.9  481.23  5154.6  481.91  5200.1  482.52  5228.5  483.14
#Mann=5,-1,0
  4729.4    0.05       0  4978.1     0.1       0  4982.1    0.07       0
  4988.1     0.1       0  5013.1    0.05       0
Bank Sta=4982.1,4988.1
Exp/Cntr=0.3,0.1

Type RM Length L Ch R = 1,4009,59,59,59
BEGIN DESCRIPTION:
Mapping XS ea9bfb28
END DESCRIPTION:
XS GIS Cut Line= 4
      2061217.62     13482179.51      2061288.22     13482016.35
      2061327.29     13481686.49      2061294.29     13481544.11
#Sta/Elev= 30
  4645.6  483.31  4683.2  482.50  4700.8  482.49  4706.2  482.13  4724.2  482.19
  4747.7  481.75  4759.5  481.08  4776.7  481.46  4782.1  480.65  4800.1  480.40
  4826.6  479.28  4834.1  477.99  4839.2  478.31  4844.9  477.29  4854.9  477.03
  4895.2  477.40  4922.0  477.00  5046.3  477.13  5053.3  476.76  5053.8  475.96
  5058.8  475.96  5059.3  476.76  5097.6  477.35  5126.8  477.30  5158.9  478.01
  5177.6  479.90  5185.3  479.98  5190.4  479.53  5198.1  480.16  5301.7  481.26
#Mann=3,-1,0
  4645.6     0.1       0  5053.3    0.07       0  5059.3     0.1       0
Bank Sta=5053.3,5059.3
Exp/Cntr=0.3,0.1

Type RM Length L Ch R = 1,3950,56,56,56
BEGIN DESCRIPTION:
Mapping XS 6813aedf
END DESCRIPTION:
XS GIS Cut Line= 4
      2061261.02     13482180.39      2061353.33     13482031.11
      2061380.24     13481676.94      2061355.93     13481545.87
#Sta/Elev= 30
  4641.4  483.00  4714.0  481.76  4750.6  480.96  4756.5  480.36  4777.7  480.16
  4793.1  480.87  4808.5  484.44  4816.9  484.86  4823.0  486.34  4853.1  487.69
  4883.2  487.80  4893.2  487.59  4933.4  485.46  4963.4  484.79  4993.5  484.74
  5013.6  485.37  5032.8  485.08  5037.8  483.44  5053.7  484.62  5113.9  486.41
  5164.0  484.73  5169.0  485.01  5176.3  483.73  5211.8  479.59  5212.3  478.79
  5217.3  478.79  5217.8  479.59  5275.8  479.88  5287.1  480.52  5305.4  480.87
#Mann=3,-1,0
  4641.4     0.1       0  5211.8    0.07       0  5217.8     0.1       0
Bank Sta=5211.8,5217.8
Exp/Cntr=0.3,0.1

Type RM Length L Ch R = 1,3894,131,131,131
BEGIN DESCRIPTION:
Mapping XS 1b6ceb85
END DESCRIPTION:
XS GIS Cut Line= 4
      2061370.80     13482161.07      2061400.91     13482019.95
      2061439.10     13481726.20      2061474.65     13481528.29
#Sta/Elev= 30
  4690.1  481.41  4727.0  480.36  4741.7  480.32  4808.8  478.67  4877.9  477.48
  4899.9  477.43  4904.9  477.77  4920.1  476.81  4979.0  476.89  4981.0  476.60
  4981.5  475.80  4986.5  475.80  4987.0  476.60  5031.0  477.92  5058.1  477.90
  5063.2  477.30  5071.3  477.70  5121.7  477.45  5175.3  477.99  5190.0  478.47
  5195.1  477.98  5203.0  477.90  5213.1  478.36  5243.6  478.37  5248.8  478.79
  5253.8  478.51  5284.2  479.31  5307.5  479.33  5324.9  479.73  5331.7  480.25
#Mann=6,-1,0
  4690.1     0.1       0  4741.7    0.08       0  4877.9    0.05       0
  4981.0    0.04       0  4987.0    0.05       0  5175.3     0.1       0
Bank Sta=4981,4987
Exp/Cntr=0.3,0.1

Type RM Length L Ch R = 1,3763,199,199,199
BEGIN DESCRIPTION:
Mapping XS 9a499916
END DESCRIPTION:
XS GIS Cut Line= 5
      2061577.62     13482155.42      2061532.96     13482035.20
      2061560.95     13481766.51      2061574.73     13481665.52
      2061626.32     13481528.75
#Sta/Elev= 30
  4681.2  477.51  4730.7  476.76  4736.1  477.32  4755.8  476.82  4761.1  477.31
  4767.0  476.42  4806.9  475.76  4849.9  475.27  4870.0  476.01  4890.1  475.16
  4940.4  475.13  4960.5  474.48  4969.7  474.92  4971.7  474.29  4972.2  473.49
  4977.2  473.49  4977.7  474.29  4990.6  474.76  5030.8  474.50  5061.7  474.78
  5082.9  474.60  5131.6  475.21  5146.6  474.97  5179.3  475.65  5234.7  475.88
  5267.6  476.43  5282.5  476.02  5307.4  478.21  5312.7  476.52  5327.7  476.85
#Mann=5,-1,0
  4681.2     0.1       0  4971.7    0.07       0  4977.7     0.1       0
  5061.7    0.08       0  5234.7     0.1       0
Bank Sta=4971.7,4977.7
Exp/Cntr=0.3,0.1

Type RM Length L Ch R = 1,3564,104,104,104
BEGIN DESCRIPTION:
Mapping XS dd448455
END DESCRIPTION:
XS GIS Cut Line= 4
      2061682.01     13482107.49      2061758.36     13481871.00
      2061718.21     13481638.79      2061688.08     13481502.44
#Sta/Elev= 30
  4701.4  475.21  4787.7  474.15  4792.9  473.78  4798.6  474.28  4830.2  473.83
  4851.1  473.94  4882.7  475.13  4889.0  476.22  4894.3  475.86  4903.7  479.09
  4914.2  479.01  4921.1  476.62  4926.3  475.54  4935.2  474.91  4995.3  474.16
  5000.3  474.38  5016.9  473.12  5034.2  472.86  5034.7  472.06  5039.7  472.06
  5040.2  472.86  5067.6  473.17  5108.2  472.94  5169.1  473.88  5174.6  473.58
  5209.9  473.81  5224.5  474.24  5261.1  474.49  5281.6  475.34  5325.2  475.72
#Mann=3,-1,0
  4701.4     0.1       0  5034.2    0.07       0  5040.2     0.1       0
Bank Sta=5034.2,5040.2
Exp/Cntr=0.3,0.1

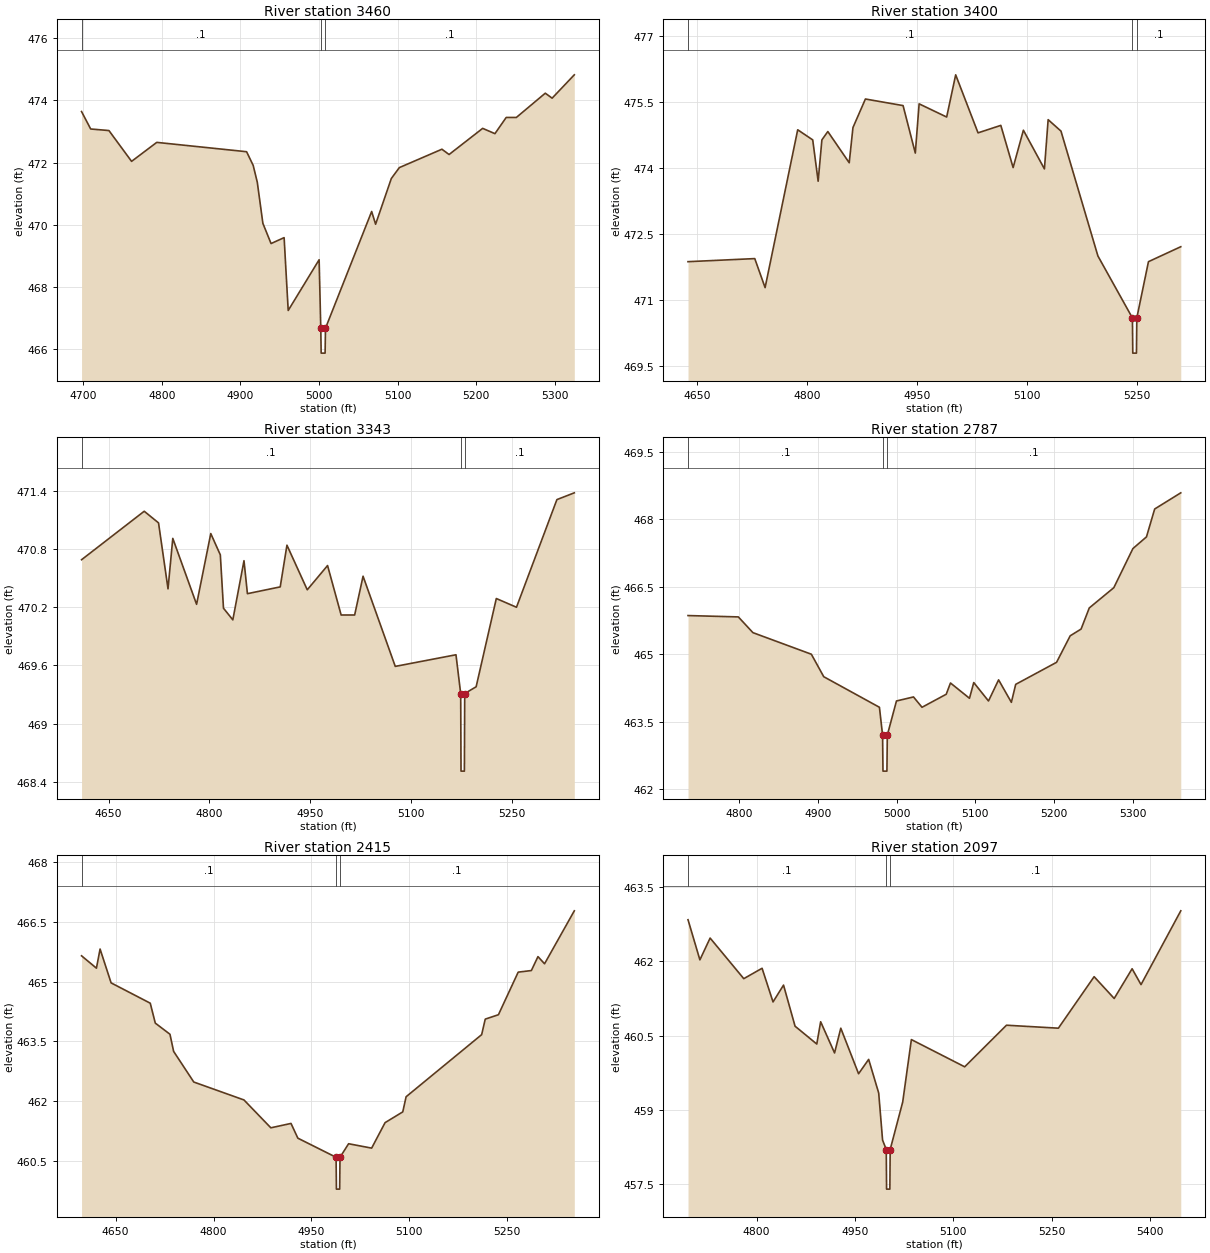
Type RM Length L Ch R = 1,3460,60,60,60
BEGIN DESCRIPTION:
Mapping XS a02afd0b
END DESCRIPTION:
XS GIS Cut Line= 5
      2061876.46     13482083.18      2061908.41     13482011.14
      2061854.24     13481817.39      2061829.93     13481667.39
      2061729.49     13481500.88
#Sta/Elev= 30
  4698.1  473.64  4709.7  473.08  4732.9  473.03  4761.7  472.04  4793.7  472.65
  4907.9  472.35  4916.3  471.91  4921.5  471.37  4928.6  470.05  4939.0  469.40
  4955.6  469.59  4960.8  467.25  5000.1  468.88  5002.2  466.68  5002.7  465.88
  5007.7  465.88  5008.2  466.68  5066.9  470.43  5071.9  470.02  5091.9  471.49
  5102.1  471.84  5156.2  472.43  5165.3  472.26  5208.0  473.10  5223.6  472.93
  5237.9  473.45  5250.8  473.45  5287.6  474.23  5296.3  474.07  5324.5  474.82
#Mann=3,-1,0
  4698.1     0.1       0  5002.2    0.07       0  5008.2     0.1       0
Bank Sta=5002.2,5008.2
Exp/Cntr=0.3,0.1

Type RM Length L Ch R = 1,3400,57,57,57
BEGIN DESCRIPTION:
Mapping XS b24b8e1e
END DESCRIPTION:
XS GIS Cut Line= 5
      2062050.06     13482098.82      2061961.88     13482006.28
      2061927.16     13481858.37      2061872.99     13481623.64
      2061882.53     13481472.10
#Sta/Elev= 30
  4637.6  471.87  4728.7  471.94  4742.8  471.28  4787.3  474.87  4807.8  474.64
  4815.2  473.70  4820.3  474.64  4828.4  474.83  4857.6  474.12  4862.7  474.92
  4879.7  475.57  4931.1  475.42  4947.8  474.34  4953.0  475.46  4990.6  475.16
  5002.9  476.12  5033.4  474.80  5064.5  474.97  5081.3  474.01  5095.3  474.86
  5124.0  473.98  5129.1  475.10  5146.6  474.84  5197.0  472.00  5244.1  470.59
  5244.6  469.79  5249.6  469.79  5250.1  470.59  5266.0  471.87  5310.1  472.21
#Mann=3,-1,0
  4637.6     0.1       0  5244.1    0.07       0  5250.1     0.1       0
Bank Sta=5244.1,5250.1
Exp/Cntr=0.3,0.1

Type RM Length L Ch R = 1,3343,556,556,556
BEGIN DESCRIPTION:
Mapping XS 5a1d8c66
END DESCRIPTION:
XS GIS Cut Line= 4
      2062133.43     13482088.44      2061983.41     13481936.14
      2061949.56     13481645.69      2061956.29     13481419.09
#Sta/Elev= 30
  4609.9  470.69  4703.1  471.19  4724.4  471.07  4738.5  470.39  4745.6  470.91
  4781.0  470.23  4802.1  470.96  4816.3  470.74  4821.0  470.19  4834.9  470.07
  4851.5  470.68  4856.6  470.34  4905.4  470.41  4915.4  470.84  4945.6  470.38
  4975.8  470.63  4996.0  470.12  5016.1  470.12  5028.6  470.52  5076.5  469.59
  5166.8  469.71  5173.8  469.31  5174.3  468.51  5179.3  468.51  5179.8  469.31
  5196.8  469.38  5226.8  470.29  5256.8  470.20  5316.9  471.31  5342.8  471.38
#Mann=3,-1,0
  4609.9     0.1       0  5173.8    0.07       0  5179.8     0.1       0
Bank Sta=5173.8,5179.8
Exp/Cntr=0.3,0.1

Type RM Length L Ch R = 1,2787,372,372,372
BEGIN DESCRIPTION:
Mapping XS 26b81a86
END DESCRIPTION:
XS GIS Cut Line= 4
      2062392.08     13481636.62      2062405.63     13481534.06
      2062290.35     13481250.03      2062083.07     13481193.62
#Sta/Elev= 30
  4735.6  465.86  4799.4  465.83  4817.9  465.48  4892.0  465.00  4907.7  464.50
  4978.3  463.82  4982.3  463.20  4982.8  462.40  4987.8  462.40  4988.3  463.20
  4999.9  463.96  5021.5  464.05  5032.3  463.82  5063.0  464.11  5068.4  464.36
  5092.5  464.02  5097.9  464.37  5116.6  463.96  5129.4  464.43  5145.6  463.93
  5151.1  464.33  5202.9  464.82  5220.2  465.41  5234.0  465.56  5244.4  466.03
  5275.5  466.48  5299.7  467.35  5316.9  467.61  5327.3  468.23  5360.4  468.59
#Mann=3,-1,0
  4735.6     0.1       0  4982.3    0.07       0  4988.3     0.1       0
Bank Sta=4982.3,4988.3
Exp/Cntr=0.3,0.1

Type RM Length L Ch R = 1,2415,318,318,318
BEGIN DESCRIPTION:
Mapping XS d5a2b59a
END DESCRIPTION:
XS GIS Cut Line= 4
      2062780.39     13481289.65      2062693.13     13481110.45
      2062338.27     13481022.95      2062149.94     13481050.95
#Sta/Elev= 30
  4597.7  465.65  4620.5  465.34  4626.1  465.82  4643.0  464.97  4703.0  464.46
  4710.7  463.96  4733.2  463.68  4738.8  463.25  4769.7  462.48  4846.6  462.03
  4887.8  461.33  4918.7  461.44  4929.2  461.07  4987.8  460.59  4988.3  459.79
  4993.3  459.79  4993.8  460.59  5007.0  460.93  5042.3  460.82  5062.9  461.46
  5090.0  461.73  5095.1  462.11  5210.9  463.67  5216.4  464.06  5236.6  464.17
  5266.9  465.24  5287.1  465.28  5297.2  465.63  5307.3  465.45  5352.9  466.78
#Mann=3,-1,0
  4597.7     0.1       0  4987.8    0.07       0  4993.8     0.1       0
Bank Sta=4987.8,4993.8
Exp/Cntr=0.3,0.1

Type RM Length L Ch R = 1,2097,293,293,293
BEGIN DESCRIPTION:
Mapping XS 076c08fe
END DESCRIPTION:
XS GIS Cut Line= 4
      2062898.68     13481065.06      2062824.89     13480918.57
      2062460.88     13480692.31      2062305.69     13480724.87
#Sta/Elev= 30
  4695.5  462.84  4713.6  462.03  4729.2  462.47  4780.5  461.65  4808.4  461.86
  4825.1  461.18  4841.1  461.52  4858.7  460.69  4891.8  460.33  4897.7  460.78
  4918.9  460.15  4928.4  460.65  4955.5  459.73  4970.9  460.02  4986.2  459.34
  4992.1  458.39  4997.7  458.20  4998.2  457.40  5003.2  457.40  5003.7  458.20
  5022.8  459.16  5036.0  460.42  5117.3  459.87  5181.0  460.71  5260.1  460.65
  5314.6  461.69  5345.2  461.25  5372.5  461.85  5386.1  461.53  5446.7  463.02
#Mann=3,-1,0
  4695.5     0.1       0  4997.7    0.07       0  5003.7     0.1       0
Bank Sta=4997.7,5003.7
Exp/Cntr=0.3,0.1

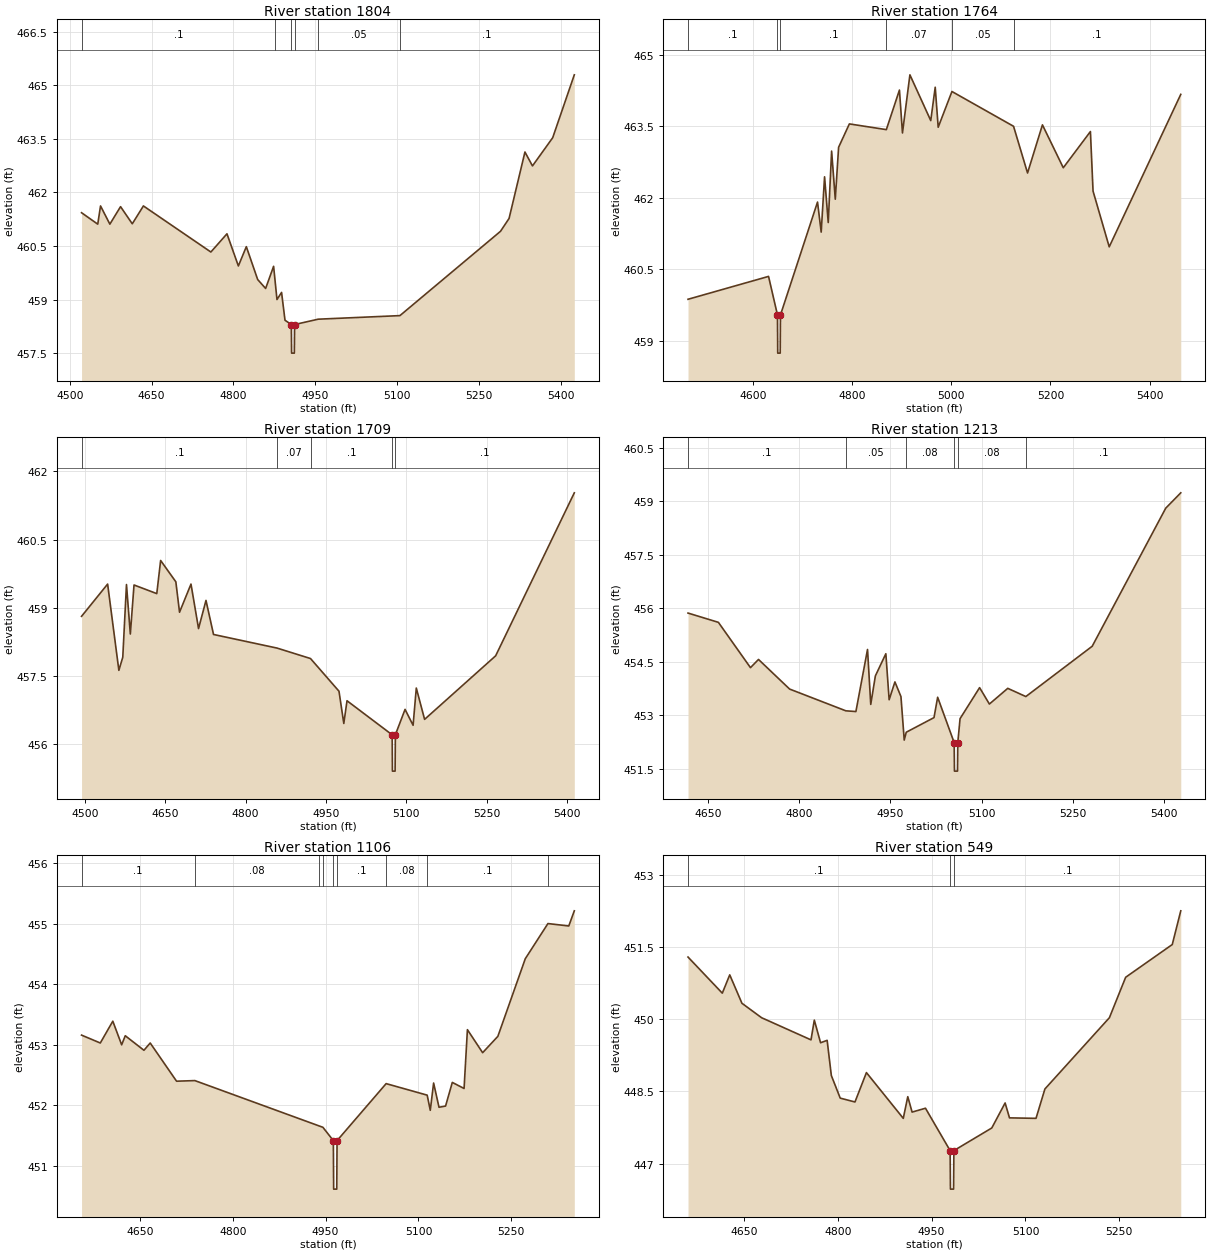
Type RM Length L Ch R = 1,1804,40,40,40
BEGIN DESCRIPTION:
Mapping XS 78ce6797
END DESCRIPTION:
XS GIS Cut Line= 5
      2063067.80     13481035.41      2063007.45     13480785.88
      2062897.73     13480638.66      2062757.45     13480441.44
      2062567.04     13480329.17
#Sta/Elev= 30
  4521.5  461.43  4551.2  461.11  4556.3  461.62  4573.4  461.11  4593.0  461.60
  4614.5  461.12  4634.9  461.62  4758.6  460.33  4788.1  460.84  4809.0  459.94
  4823.6  460.48  4844.4  459.56  4859.0  459.31  4873.6  459.93  4876.2  459.54
  4879.8  459.00  4888.2  459.20  4894.5  458.42  4906.1  458.30  4906.6  457.50
  4911.6  457.50  4912.1  458.30  4955.4  458.45  5105.2  458.55  5289.6  460.91
  5305.3  461.27  5334.4  463.13  5348.2  462.74  5385.3  463.53  5424.9  465.29
#Mann=6,-1,0
  4521.5     0.1       0  4876.2    0.07       0  4906.1   0.033       0
  4912.1    0.07       0  4955.4    0.05       0  5105.2     0.1       0
Bank Sta=4906.1,4912.1
Exp/Cntr=0.3,0.1

Type RM Length L Ch R = 1,1764,55,55,55
BEGIN DESCRIPTION:
Mapping XS a5574111
END DESCRIPTION:
XS GIS Cut Line= 4
      2063241.41     13480987.67      2062999.81     13480721.99
      2062755.37     13480357.41      2062697.95     13480171.00
#Sta/Elev= 30
  4469.6  459.87  4631.9  460.35  4649.9  459.54  4650.4  458.74  4655.4  458.74
  4655.9  459.54  4730.6  461.91  4738.0  461.28  4744.8  462.44  4752.2  461.48
  4759.0  462.98  4766.4  461.97  4773.1  463.06  4794.8  463.55  4869.3  463.43
  4895.7  464.26  4901.8  463.36  4916.8  464.58  4958.8  463.62  4967.8  464.32
  4973.8  463.48  5001.5  464.23  5125.7  463.50  5153.9  462.52  5183.9  463.53
  5225.9  462.63  5280.6  463.39  5285.9  462.14  5318.5  460.97  5462.7  464.17
#Mann=6,-1,0
  4469.6     0.1       0  4649.9    0.07       0  4655.9     0.1       0
  4869.3    0.07       0  5001.5    0.05       0  5125.7     0.1       0
Bank Sta=4649.9,4655.9
Exp/Cntr=0.3,0.1

Type RM Length L Ch R = 1,1709,496,496,496
BEGIN DESCRIPTION:
Mapping XS 6a078809
END DESCRIPTION:
XS GIS Cut Line= 4
      2063293.49     13480905.20      2062999.12     13480625.47
      2062871.34     13480432.41      2062767.63     13480169.42
#Sta/Elev= 30
  4493.5  458.81  4542.2  459.52  4563.2  457.62  4570.5  457.91  4577.4  459.51
  4584.6  458.42  4591.5  459.50  4634.0  459.31  4641.2  460.04  4669.6  459.57
  4676.5  458.90  4697.9  459.52  4712.0  458.54  4725.9  459.16  4740.0  458.41
  4858.7  458.11  4921.1  457.88  4974.3  457.16  4983.3  456.45  4989.3  456.95
  5073.6  456.20  5074.1  455.40  5079.1  455.40  5079.6  456.20  5097.7  456.76
  5112.7  456.41  5118.7  457.23  5134.2  456.54  5266.9  457.94  5413.8  461.53
#Mann=5,-1,0
  4493.5     0.1       0  4858.7    0.07       0  4921.1     0.1       0
  5073.6    0.07       0  5079.6     0.1       0
Bank Sta=5073.6,5079.6
Exp/Cntr=0.3,0.1

Type RM Length L Ch R = 1,1213,107,107,107
BEGIN DESCRIPTION:
Mapping XS 3d4a8330
END DESCRIPTION:
XS GIS Cut Line= 4
      2063534.54     13480484.57      2063404.33     13480265.22
      2063134.01     13480162.62      2062870.51     13480131.90
#Sta/Elev= 30
  4617.6  455.87  4667.5  455.61  4720.2  454.34  4733.4  454.57  4784.5  453.74
  4876.9  453.13  4893.4  453.11  4912.5  454.85  4917.8  453.31  4925.4  454.11
  4942.6  454.73  4948.0  453.44  4957.5  453.94  4967.4  453.53  4972.8  452.31
  4976.1  452.53  5021.7  452.94  5027.7  453.51  5054.8  452.24  5055.3  451.44
  5060.3  451.44  5060.8  452.24  5064.5  452.91  5096.6  453.78  5112.7  453.32
  5142.9  453.76  5172.6  453.53  5281.6  454.94  5402.4  458.81  5427.1  459.24
#Mann=6,-1,0
  4617.6     0.1       0  4876.9    0.05       0  4976.1    0.08       0
  5054.8    0.07       0  5060.8    0.08       0  5172.6     0.1       0
Bank Sta=5054.8,5060.8
Exp/Cntr=0.3,0.1

Type RM Length L Ch R = 1,1106,557,557,557
BEGIN DESCRIPTION:
Mapping XS 0c813766
END DESCRIPTION:
XS GIS Cut Line= 4
      2063785.13     13480227.37      2063451.20     13480188.66
      2063303.28     13480116.79      2063197.05     13479841.06
#Sta/Elev= 30
  4555.7  453.16  4586.0  453.03  4606.2  453.39  4620.5  453.00  4626.3  453.15
  4656.5  452.91  4666.6  453.03  4709.2  452.40  4738.8  452.41  4940.1  451.66
  4945.6  451.64  4962.5  451.42  4963.0  450.62  4968.0  450.62  4968.5  451.42
  5047.8  452.36  5114.1  452.17  5119.1  451.92  5124.5  452.37  5133.2  451.97
  5143.8  451.99  5154.7  452.38  5173.7  452.28  5179.1  453.25  5203.7  452.87
  5228.3  453.14  5272.6  454.42  5309.2  455.00  5342.9  454.96  5351.8  455.21
#Mann=9,-1,0
  4555.7     0.1       0  4738.8    0.08       0  4940.1    0.05       0
  4945.6     0.1       0  4962.5    0.07       0  4968.5     0.1       0
  5047.8    0.08       0  5114.1     0.1       0  5309.2    0.05       0
Bank Sta=4962.5,4968.5
Exp/Cntr=0.3,0.1

Type RM Length L Ch R = 1,549,410,410,410
BEGIN DESCRIPTION:
Mapping XS 486ba872
END DESCRIPTION:
XS GIS Cut Line= 4
      2063868.72     13480137.29      2063775.29     13479837.97
      2063569.73     13479640.74      2063381.52     13479620.83
#Sta/Elev= 30
  4560.6  451.29  4615.4  450.54  4627.3  450.92  4646.8  450.33  4678.2  450.03
  4757.2  449.57  4762.5  449.98  4772.5  449.51  4783.0  449.56  4789.7  448.83
  4803.9  448.36  4827.5  448.28  4845.8  448.89  4904.7  447.94  4911.9  448.39
  4918.8  448.07  4940.2  448.15  4979.6  447.27  4980.1  446.47  4985.1  446.47
  4985.6  447.27  5046.2  447.74  5067.5  448.26  5074.5  447.95  5116.9  447.94
  5131.1  448.55  5234.2  450.03  5260.2  450.87  5334.7  451.55  5348.3  452.25
#Mann=3,-1,0
  4560.6     0.1       0  4979.6    0.07       0  4985.6     0.1       0
Bank Sta=4979.6,4985.6
Exp/Cntr=0.3,0.1

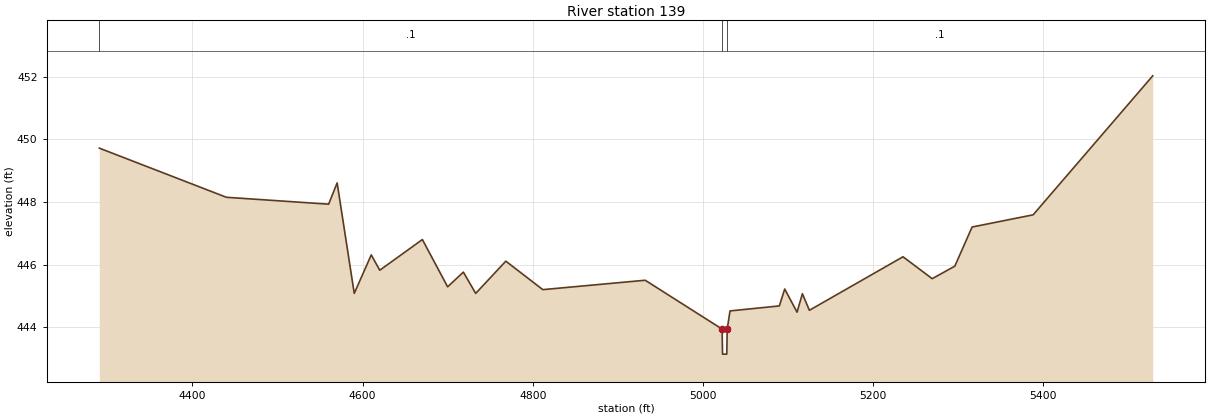
Type RM Length L Ch R = 1,139,0,0,0
BEGIN DESCRIPTION:
UNT 145 in Lagunillas Cr Wtrshd 18.0
END DESCRIPTION:
XS GIS Cut Line= 4
      2064015.21     13480084.12      2064040.17     13479673.99
      2063777.89     13479333.80      2063385.83     13479264.92
#Sta/Elev= 30
  4290.5  449.72  4439.9  448.15  4560.1  447.93  4570.1  448.61  4590.2  445.08
  4610.2  446.31  4620.2  445.82  4670.3  446.80  4700.0  445.29  4718.5  445.76
  4733.0  445.08  4768.4  446.11  4811.9  445.20  4932.3  445.50  5022.7  443.94
  5023.2  443.14  5028.2  443.14  5028.7  443.94  5032.0  444.52  5090.0  444.68
  5096.3  445.22  5110.8  444.48  5117.1  445.07  5125.3  444.54  5235.4  446.25
  5269.7  445.55  5296.3  445.95  5316.6  447.20  5388.4  447.59  5529.0  452.03
#Mann=3,-1,0
  4290.5     0.1       0  5022.7    0.07       0  5028.7     0.1       0
Bank Sta=5022.7,5028.7
Exp/Cntr=0.3,0.1

Chan Stop Cuts=-1