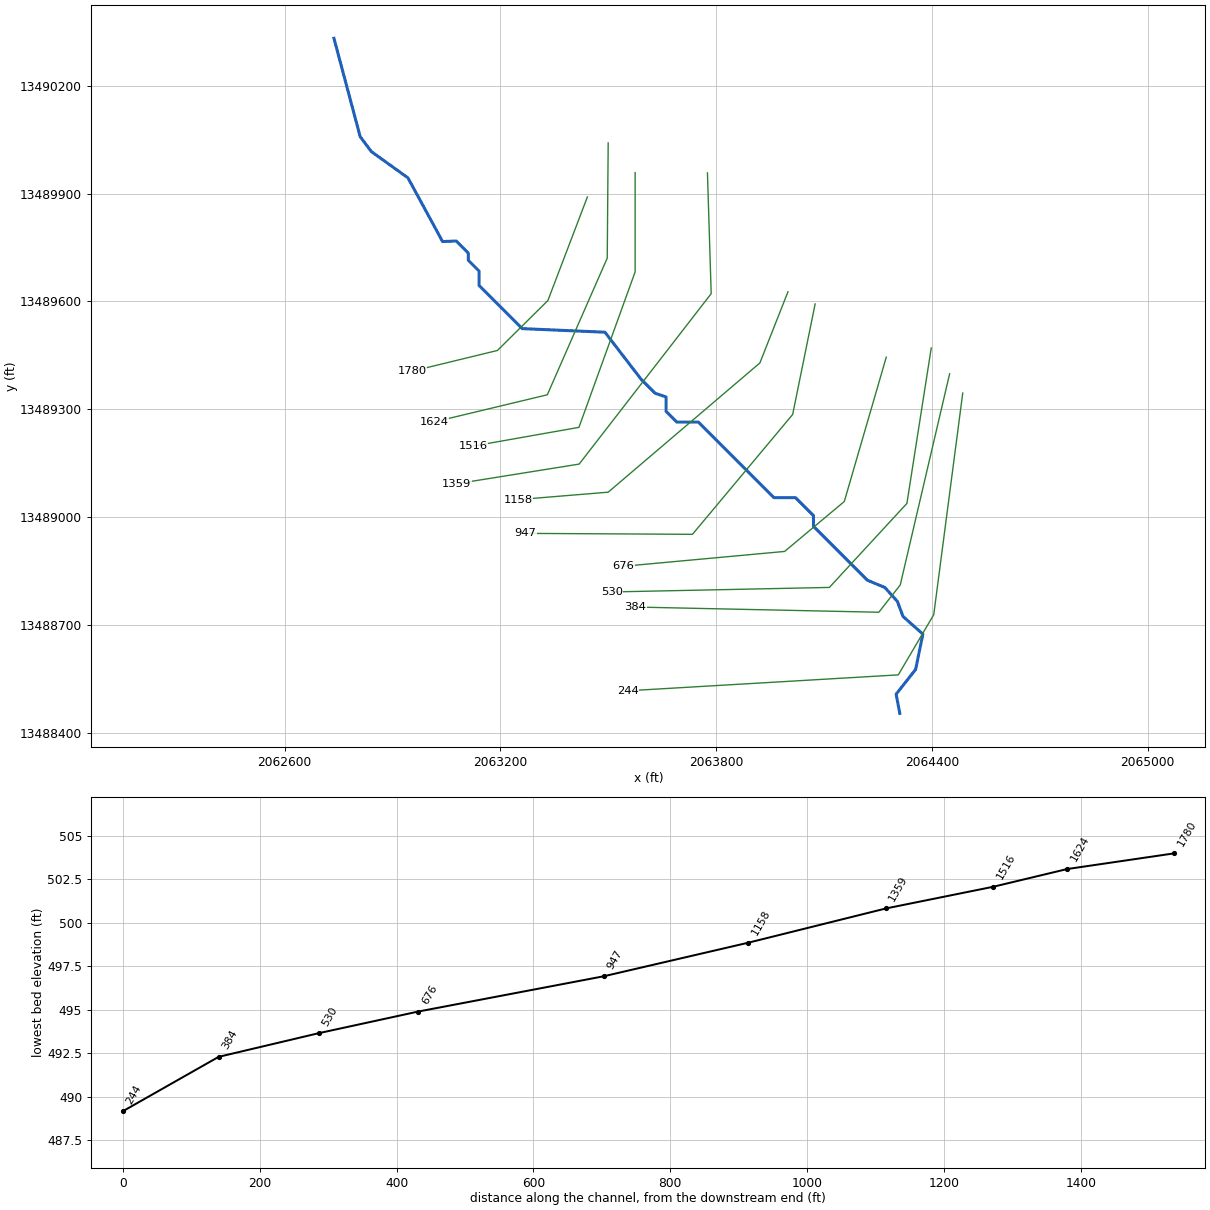
--- UNT 147 in Lagunillas Cr Wtrshd.prj (project) ---

Proj Title=UNT 147 in Lagunillas Cr Wtrshd Base Level Engineering
Current Plan=p01
Default Exp/Contr=0.3,0.1
English Units
Geom File=g01
Flow File=f01
Plan File=p01
BEGIN DESCRIPTION:
UNT 147 in Lagunillas Cr Wtrshd
END DESCRIPTION:

--- UNT 147 in Lagunillas Cr Wtrshd.p01 (plan) ---

Plan Title=Multiple Run
Short Identifier=Multiple
Geom File=g01
Flow File=f01
Subcritical Flow
K Sum by GR= 0
Std Step Tol= 0.01
Critical Tol= 0.01
Num of Std Step Trials= 20
Max Error Tol= 0.3
Flow Tol Ratio= 0.001
Split Flow NTrial= 30
Split Flow Tol= 0.02
Split Flow Ratio= 0.02
Log Output Level= 0
Friction Slope Method= 1
Unsteady Friction Slope Method= 2
Unsteady Bridges Friction Slope Method= 1
Parabolic Critical Depth
Global Vel Dist=  1 , 1 , 1
Global Log Level= 0
CheckData=True
Encroach Param= -1, 0, 0, 0
BEGIN DESCRIPTION:
Multiple Run
END DESCRIPTION:

--- UNT 147 in Lagunillas Cr Wtrshd.f01 (steady flow) ---

Flow Title=Multiple
Number of Profiles=7
Profile Names=10-year,25-year,50-year,1pct_min,100-year,1pct_plu,500-year
River Rch & RM= UNT 147 in Lagun,Reach-1,1780
      54      68      78      45      89     178     119
Boundary for River Rch & Prof#=UNT 147 in Lagun,Reach-1,1
Up Type=0
Dn Type=3
Dn Slope=0.005
Boundary for River Rch & Prof#=UNT 147 in Lagun,Reach-1,2
Up Type=0
Dn Type=3
Dn Slope=0.005
Boundary for River Rch & Prof#=UNT 147 in Lagun,Reach-1,3
Up Type=0
Dn Type=3
Dn Slope=0.005
Boundary for River Rch & Prof#=UNT 147 in Lagun,Reach-1,4
Up Type=0
Dn Type=3
Dn Slope=0.005
Boundary for River Rch & Prof#=UNT 147 in Lagun,Reach-1,5
Up Type=0
Dn Type=3
Dn Slope=0.005
Boundary for River Rch & Prof#=UNT 147 in Lagun,Reach-1,6
Up Type=0
Dn Type=3
Dn Slope=0.005
Boundary for River Rch & Prof#=UNT 147 in Lagun,Reach-1,7
Up Type=0
Dn Type=3
Dn Slope=0.005

--- UNT 147 in Lagunillas Cr Wtrshd.g01 (geometry) ---

Geom Title=Existing Conditions

River Reach=UNT 147 in Lagun,Reach-1
Reach XY= 30
      2062737.28     13490331.80      2062810.19     13490058.37
      2062841.45     13490016.70      2062943.01     13489943.78
      2063039.36     13489766.70      2063077.23     13489768.11
      2063110.80     13489734.54      2063110.80     13489714.54
      2063140.80     13489684.54      2063140.80     13489644.54
      2063260.80     13489524.54      2063490.80     13489514.54
      2063590.80     13489384.54      2063630.80     13489344.54
      2063660.80     13489334.54      2063660.80     13489294.54
      2063690.80     13489264.54      2063750.80     13489264.54
      2063960.80     13489054.54      2064020.80     13489054.54
      2064070.80     13489004.54      2064070.80     13488974.54
      2064220.23     13488825.11      2064269.41     13488804.54
      2064304.14     13488765.78      2064319.76     13488724.12
      2064375.00     13488675.00      2064354.91     13488576.78
      2064300.66     13488507.97      2064310.80     13488454.54

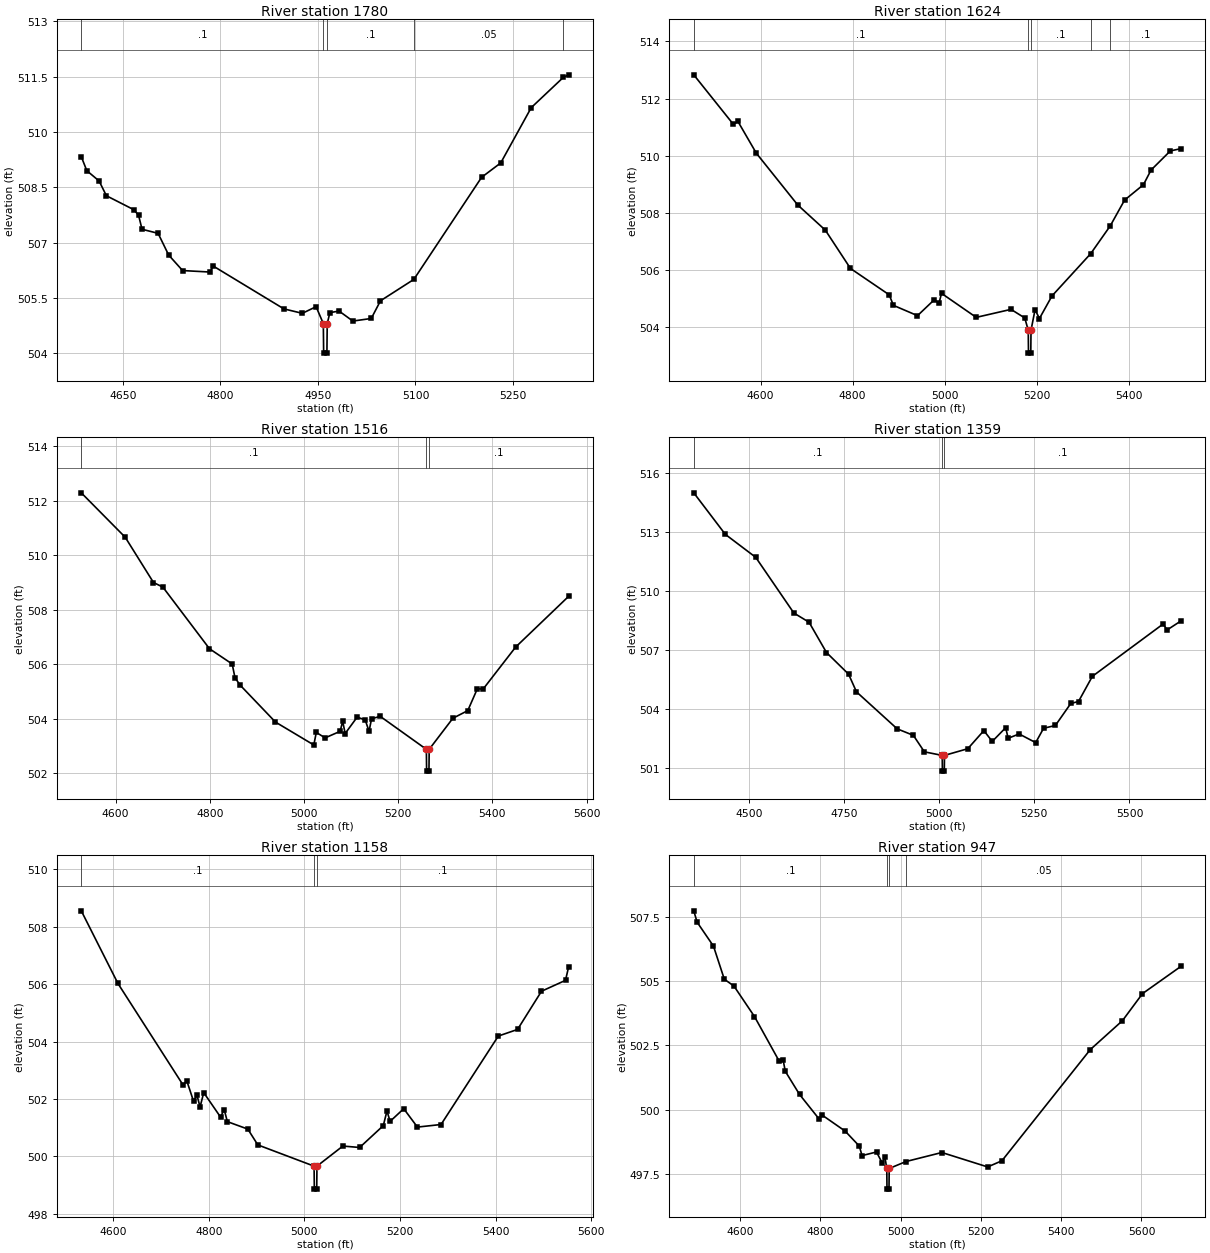
Type RM Length L Ch R = 1,1780,156,156,156
BEGIN DESCRIPTION:
Mapping XS bf3bd67a
END DESCRIPTION:
XS GIS Cut Line= 4
      2063442.02     13489890.59      2063332.22     13489602.67
      2063191.95     13489463.78      2062955.08     13489406.23
#Sta/Elev= 30
  4586.1  509.33  4594.6  508.95  4613.5  508.67  4624.7  508.27  4667.0  507.89
  4674.2  507.74  4679.5  507.36  4704.2  507.25  4720.5  506.66  4741.9  506.24
  4783.8  506.20  4789.2  506.36  4897.7  505.20  4926.0  505.08  4947.2  505.26
  4958.3  504.80  4958.8  504.00  4963.8  504.00  4964.3  504.80  4968.4  505.10
  4982.6  505.14  5003.7  504.87  5032.0  504.94  5046.2  505.42  5097.5  506.00
  5201.7  508.77  5231.1  509.16  5278.0  510.66  5327.3  511.48  5335.4  511.55
#Mann=5,-1,0
  4586.1     0.1       0  4958.3    0.07       0  4964.3     0.1       0
  5097.5    0.05       0  5327.3     0.1       0
Bank Sta=4958.3,4964.3
Exp/Cntr=0.3,0.1

Type RM Length L Ch R = 1,1624,108,108,108
BEGIN DESCRIPTION:
Mapping XS 7aac8bbd
END DESCRIPTION:
XS GIS Cut Line= 4
      2063499.89     13490040.99      2063497.28     13489720.72
      2063330.61     13489340.51      2063015.55     13489265.00
#Sta/Elev= 30
  4454.6  512.83  4540.6  511.10  4550.6  511.20  4590.6  510.09  4680.6  508.28
  4740.6  507.40  4795.3  506.06  4879.4  505.14  4888.7  504.77  4941.0  504.41
  4977.7  504.97  4987.7  504.84  4993.2  505.19  5068.7  504.35  5144.3  504.63
  5174.2  504.33  5181.8  503.90  5182.3  503.10  5187.3  503.10  5187.8  503.90
  5196.6  504.62  5206.1  504.31  5233.4  505.10  5317.7  506.58  5360.1  507.55
  5391.2  508.45  5432.3  508.99  5448.7  509.50  5490.7  510.17  5514.0  510.25
#Mann=5,-1,0
  4454.6     0.1       0  5181.8    0.07       0  5187.8     0.1       0
  5317.7    0.05       0  5360.1     0.1       0
Bank Sta=5181.8,5187.8
Exp/Cntr=0.3,0.1

Type RM Length L Ch R = 1,1516,157,157,157
BEGIN DESCRIPTION:
Mapping XS 384175b6
END DESCRIPTION:
XS GIS Cut Line= 4
      2063574.83     13489958.34      2063574.83     13489682.26
      2063418.58     13489249.97      2063124.29     13489197.88
#Sta/Elev= 30
  4527.3  512.29  4620.6  510.66  4680.6  509.00  4700.6  508.83  4799.5  506.57
  4847.7  506.01  4853.6  505.51  4864.3  505.24  4939.6  503.88  5021.0  503.04
  5026.3  503.50  5045.0  503.30  5076.9  503.54  5082.3  503.91  5087.6  503.46
  5113.0  504.06  5130.1  503.96  5138.3  503.54  5143.6  504.00  5162.0  504.09
  5260.0  502.88  5260.5  502.08  5265.5  502.08  5266.0  502.88  5316.3  504.02
  5347.9  504.30  5368.2  505.10  5380.5  505.09  5449.5  506.63  5561.9  508.49
#Mann=3,-1,0
  4527.3     0.1       0  5260.0    0.07       0  5266.0     0.1       0
Bank Sta=5260,5266
Exp/Cntr=0.3,0.1

Type RM Length L Ch R = 1,1359,201,201,201
BEGIN DESCRIPTION:
Mapping XS 636b513f
END DESCRIPTION:
XS GIS Cut Line= 4
      2063775.93     13489957.73      2063786.34     13489621.76
      2063419.16     13489147.80      2063078.98     13489093.27
#Sta/Elev= 30
  4355.4  514.98  4438.2  512.87  4518.2  511.70  4618.3  508.87  4658.3  508.40
  4704.1  506.86  4762.1  505.76  4782.9  504.86  4889.8  502.98  4932.3  502.65
  4961.3  501.81  5008.1  501.63  5008.6  500.83  5013.6  500.83  5014.1  501.63
  5075.3  501.97  5117.5  502.89  5139.6  502.34  5174.9  503.04  5181.3  502.50
  5210.2  502.72  5253.7  502.28  5274.5  503.01  5305.4  503.15  5345.9  504.27
  5366.2  504.37  5402.6  505.65  5588.5  508.31  5599.1  508.01  5635.6  508.47
#Mann=3,-1,0
  4355.4     0.1       0  5008.1    0.07       0  5014.1     0.1       0
Bank Sta=5008.1,5014.1
Exp/Cntr=0.3,0.1

Type RM Length L Ch R = 1,1158,211,211,211
BEGIN DESCRIPTION:
Mapping XS 7a49e1fd
END DESCRIPTION:
XS GIS Cut Line= 4
      2063999.89     13489626.99      2063921.76     13489429.05
      2063499.89     13489069.68      2063248.63     13489048.96
#Sta/Elev= 30
  4533.5  508.55  4610.2  506.02  4745.8  502.50  4754.4  502.62  4768.3  501.92
  4775.3  502.14  4781.9  501.72  4789.6  502.22  4824.7  501.37  4832.4  501.63
  4839.0  501.21  4881.8  500.95  4902.7  500.40  5020.4  499.66  5020.9  498.86
  5025.9  498.86  5026.4  499.66  5080.6  500.36  5115.7  500.31  5165.1  501.07
  5172.8  501.58  5179.4  501.22  5207.9  501.66  5236.5  501.02  5285.9  501.11
  5405.7  504.19  5445.9  504.42  5496.0  505.75  5546.2  506.13  5552.6  506.59
#Mann=3,-1,0
  4533.5     0.1       0  5020.4    0.07       0  5026.4     0.1       0
Bank Sta=5020.4,5026.4
Exp/Cntr=0.3,0.1

Type RM Length L Ch R = 1,947,271,271,271
BEGIN DESCRIPTION:
Mapping XS 5ae56e81
END DESCRIPTION:
XS GIS Cut Line= 4
      2064075.41     13489593.14      2064012.91     13489285.82
      2063734.26     13488952.49      2063269.04     13488955.09
#Sta/Elev= 30
  4485.2  507.72  4493.5  507.28  4534.3  506.35  4561.2  505.07  4585.4  504.80
  4636.4  503.62  4697.6  501.90  4707.8  501.93  4713.0  501.50  4748.6  500.60
  4796.7  499.66  4804.9  499.80  4862.1  499.18  4897.3  498.60  4904.2  498.23
  4940.2  498.37  4954.5  497.94  4961.0  498.18  4965.8  497.73  4966.3  496.93
  4971.3  496.93  4971.8  497.73  5013.6  498.00  5102.9  498.35  5217.0  497.79
  5252.5  498.03  5472.5  502.34  5552.5  503.46  5602.5  504.51  5698.5  505.57
#Mann=4,-1,0
  4485.2     0.1       0  4965.8    0.07       0  4971.8     0.1       0
  5013.6    0.05       0
Bank Sta=4965.8,4971.8
Exp/Cntr=0.3,0.1

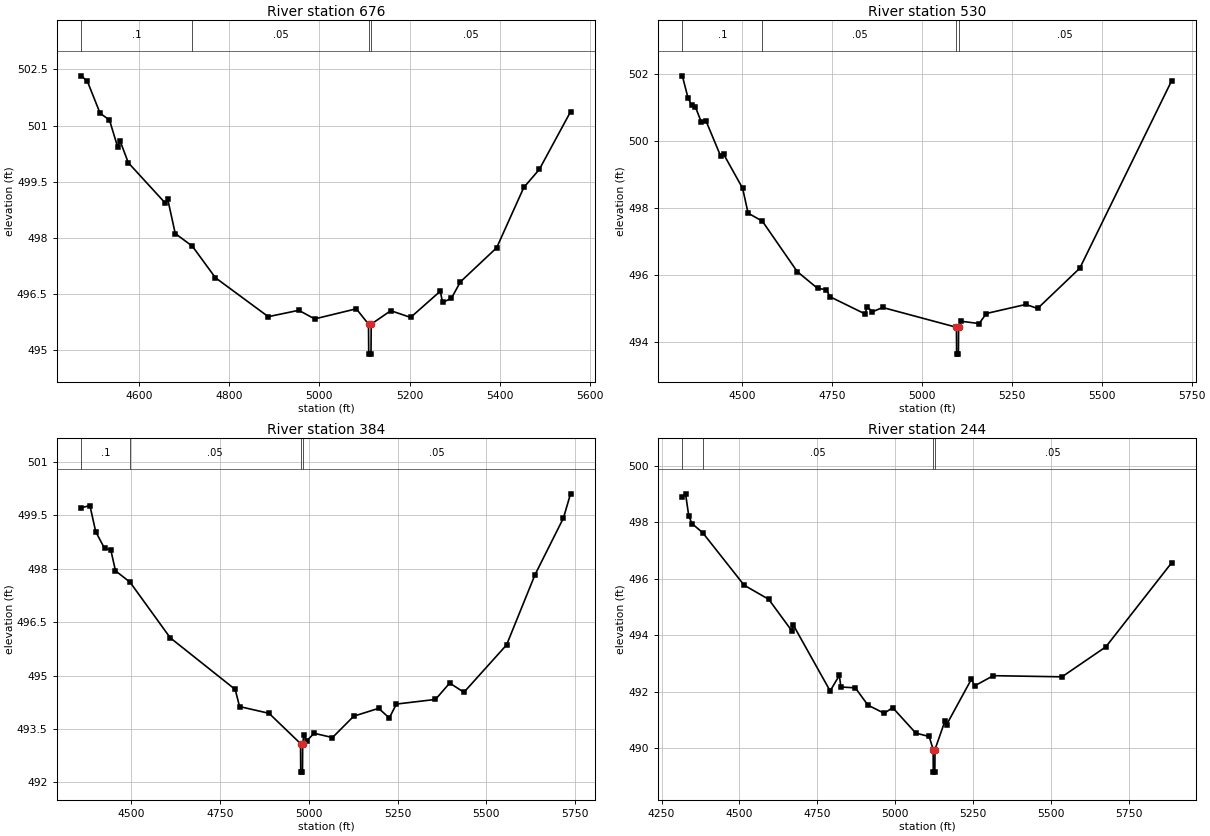
Type RM Length L Ch R = 1,676,146,146,146
BEGIN DESCRIPTION:
Mapping XS 47cf3205
END DESCRIPTION:
XS GIS Cut Line= 4
      2064273.23     13489445.14      2064156.53     13489043.77
      2063990.56     13488904.89      2063541.86     13488863.56
#Sta/Elev= 30
  4472.0  502.33  4485.7  502.18  4513.8  501.33  4534.6  501.15  4552.7  500.43
  4557.9  500.60  4576.3  500.01  4658.5  498.93  4663.7  499.04  4680.4  498.12
  4718.5  497.78  4769.5  496.94  4886.7  495.90  4954.4  496.07  4989.6  495.84
  5082.0  496.11  5109.0  495.70  5109.5  494.90  5114.5  494.90  5115.0  495.70
  5158.4  496.06  5202.4  495.88  5268.2  496.58  5273.2  496.28  5292.8  496.39
  5312.8  496.83  5393.2  497.74  5453.4  499.35  5487.7  499.83  5557.0  501.37
#Mann=4,-1,0
  4472.0     0.1       0  4718.5    0.05       0  5109.0    0.03       0
  5115.0    0.05       0
Bank Sta=5109,5115
Exp/Cntr=0.3,0.1

Type RM Length L Ch R = 1,530,146,146,146
BEGIN DESCRIPTION:
Mapping XS 0289f06a
END DESCRIPTION:
XS GIS Cut Line= 4
      2064398.32     13489470.68      2064330.61     13489038.43
      2064114.98     13488804.79      2063509.77     13488792.21
#Sta/Elev= 30
  4333.4  501.94  4349.3  501.28  4359.4  501.07  4369.5  501.02  4385.9  500.57
  4399.9  500.58  4440.4  499.54  4448.6  499.60  4501.1  498.59  4516.3  497.85
  4556.0  497.61  4652.9  496.11  4709.4  495.61  4733.9  495.57  4744.0  495.36
  4841.2  494.85  4848.0  495.06  4862.2  494.91  4890.5  495.04  5095.8  494.45
  5096.3  493.65  5101.3  493.65  5101.8  494.45  5108.8  494.63  5158.9  494.56
  5178.9  494.86  5288.9  495.13  5321.6  495.01  5438.9  496.21  5694.2  501.79
#Mann=4,-1,0
  4333.4     0.1       0  4556.0    0.05       0  5095.8    0.03       0
  5101.8    0.05       0
Bank Sta=5095.8,5101.8
Exp/Cntr=0.3,0.1

Type RM Length L Ch R = 1,384,140,140,140
BEGIN DESCRIPTION:
Mapping XS 1b2c1c4d
END DESCRIPTION:
XS GIS Cut Line= 4
      2064449.41     13489398.81      2064312.11     13488811.67
      2064252.49     13488735.79      2063575.02     13488750.24
#Sta/Elev= 30
  4359.9  499.71  4384.3  499.77  4400.5  499.04  4425.4  498.57  4443.0  498.53
  4456.2  497.94  4497.2  497.62  4610.3  496.06  4793.2  494.61  4805.4  494.13
  4888.5  493.94  4977.1  493.09  4977.6  492.29  4982.6  492.29  4983.1  493.09
  4986.5  493.33  4994.6  493.17  5015.4  493.38  5066.9  493.26  5126.9  493.86
  5196.9  494.08  5226.9  493.81  5246.9  494.20  5356.9  494.33  5396.9  494.79
  5437.0  494.53  5557.0  495.86  5637.0  497.83  5717.0  499.42  5737.0  500.10
#Mann=4,-1,0
  4359.9     0.1       0  4497.2    0.05       0  4977.1    0.03       0
  4983.1    0.05       0
Bank Sta=4977.1,4983.1
Exp/Cntr=0.3,0.1

Type RM Length L Ch R = 1,244,0,0,0
BEGIN DESCRIPTION:
UNT 147 in Lagunillas Cr Wtrshd 1.0
END DESCRIPTION:
XS GIS Cut Line= 4
      2064485.91     13489345.32      2064405.26     13488728.98
      2064306.65     13488561.62      2063554.00     13488517.34
#Sta/Elev= 30
  4316.8  498.90  4327.2  499.00  4337.3  498.23  4347.4  497.95  4381.8  497.63
  4515.1  495.77  4594.0  495.27  4667.8  494.16  4672.9  494.36  4791.1  492.03
  4820.6  492.58  4825.6  492.17  4871.8  492.14  4912.2  491.53  4964.4  491.24
  4991.7  491.44  5065.9  490.54  5108.8  490.42  5121.5  489.96  5122.0  489.16
  5127.0  489.16  5127.5  489.96  5159.8  490.98  5164.8  490.84  5244.5  492.45
  5254.5  492.21  5314.6  492.57  5535.0  492.53  5675.7  493.59  5886.6  496.56
#Mann=4,-1,0
  4316.8     0.1       0  4381.8    0.05       0  5121.5    0.03       0
  5127.5    0.05       0
Bank Sta=5121.5,5127.5
Exp/Cntr=0.3,0.1

Chan Stop Cuts=-1