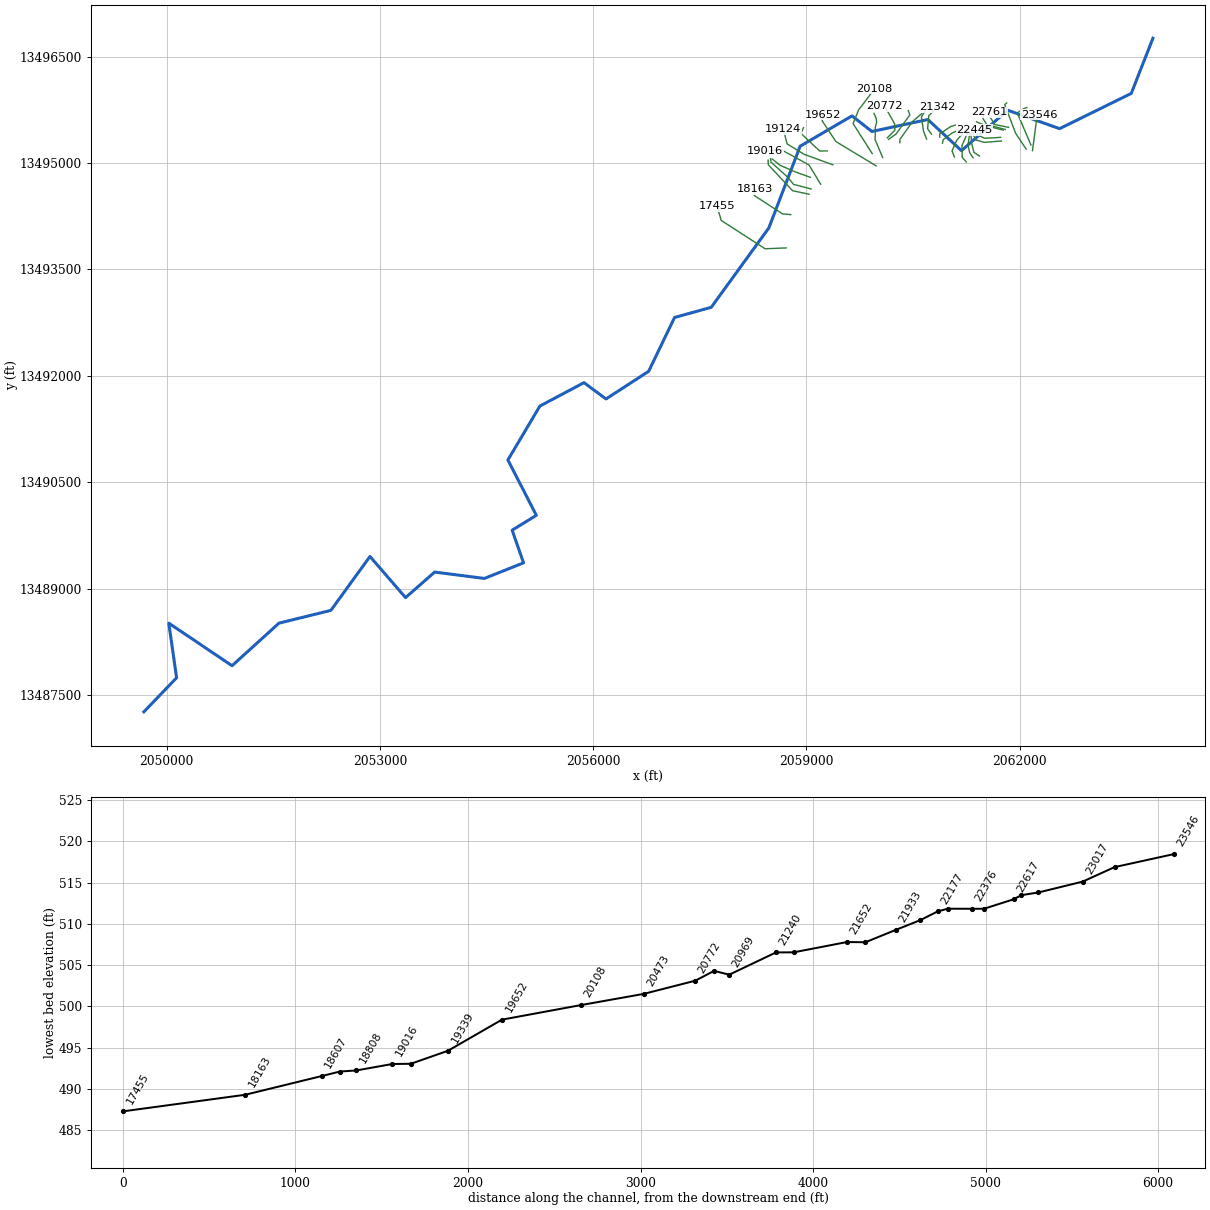
--- UNT 150 in Lagunillas Cr Wtrshd.prj (project) ---

Proj Title=UNT 150 in Lagunillas Cr Wtrshd Base Level Engineering
Current Plan=p01
Default Exp/Contr=0.3,0.1
English Units
Geom File=g01
Flow File=f01
Plan File=p01
BEGIN DESCRIPTION:
UNT 150 in Lagunillas Cr Wtrshd
END DESCRIPTION:

--- UNT 150 in Lagunillas Cr Wtrshd.p01 (plan) ---

Plan Title=Multiple Run
Short Identifier=Multiple
Geom File=g01
Flow File=f01
Subcritical Flow
K Sum by GR= 0
Std Step Tol= 0.01
Critical Tol= 0.01
Num of Std Step Trials= 20
Max Error Tol= 0.3
Flow Tol Ratio= 0.001
Split Flow NTrial= 30
Split Flow Tol= 0.02
Split Flow Ratio= 0.02
Log Output Level= 0
Friction Slope Method= 1
Unsteady Friction Slope Method= 2
Unsteady Bridges Friction Slope Method= 1
Parabolic Critical Depth
Global Vel Dist=  1 , 1 , 1
Global Log Level= 0
CheckData=True
Encroach Param= -1, 0, 0, 0
BEGIN DESCRIPTION:
Multiple Run
END DESCRIPTION:

--- UNT 150 in Lagunillas Cr Wtrshd.f01 (steady flow) ---

Flow Title=Multiple
Number of Profiles=7
Profile Names=10-year,25-year,50-year,1pct_min,100-year,1pct_plu,500-year
River Rch & RM= UNT 150 in Lagun,Reach-1,23546
      56      70      81      47      93     186     126
River Rch & RM= UNT 150 in Lagun,Reach-1,23202
      98     128     151      89     178     355     251
River Rch & RM= UNT 150 in Lagun,Reach-1,20108
     196     265     322     195     389     776     575
River Rch & RM= UNT 150 in Lagun,Reach-1,10248
     282     390     480     294     587    1171     891
River Rch & RM= UNT 150 in Lagun,Reach-1,5998
     339     473     586     361     719    1436    1103
Boundary for River Rch & Prof#=UNT 150 in Lagun,Reach-1,1
Up Type=0
Dn Type=3
Dn Slope=0.005
Boundary for River Rch & Prof#=UNT 150 in Lagun,Reach-1,2
Up Type=0
Dn Type=3
Dn Slope=0.005
Boundary for River Rch & Prof#=UNT 150 in Lagun,Reach-1,3
Up Type=0
Dn Type=3
Dn Slope=0.005
Boundary for River Rch & Prof#=UNT 150 in Lagun,Reach-1,4
Up Type=0
Dn Type=3
Dn Slope=0.005
Boundary for River Rch & Prof#=UNT 150 in Lagun,Reach-1,5
Up Type=0
Dn Type=3
Dn Slope=0.005
Boundary for River Rch & Prof#=UNT 150 in Lagun,Reach-1,6
Up Type=0
Dn Type=3
Dn Slope=0.005
Boundary for River Rch & Prof#=UNT 150 in Lagun,Reach-1,7
Up Type=0
Dn Type=3
Dn Slope=0.005

--- UNT 150 in Lagunillas Cr Wtrshd.g01 (geometry) ---

Geom Title=Existing Conditions

River Reach=UNT 150 in Lagun,Reach-1
Reach XY= 30
      2063873.92     13496758.85      2063568.71     13495981.20
      2062560.80     13495484.54      2061830.80     13495744.54
      2061180.80     13495174.54      2060707.27     13495613.41
      2059920.80     13495444.54      2059640.80     13495664.54
      2058911.48     13495237.11      2058470.80     13494084.54
      2057660.61     13492966.27      2057144.98     13492823.05
      2056780.80     13492064.54      2056180.80     13491674.54
      2055870.80     13491904.54      2055250.80     13491574.54
      2054800.80     13490814.54      2055200.80     13490034.54
      2054860.80     13489824.54      2055020.80     13489364.54
      2054470.80     13489144.54      2053770.80     13489234.54
      2053360.80     13488874.54      2052860.80     13489454.54
      2052310.80     13488694.54      2051580.80     13488514.54
      2050920.80     13487914.54      2050030.80     13488514.54
      2050140.80     13487744.54      2049680.80     13487264.54

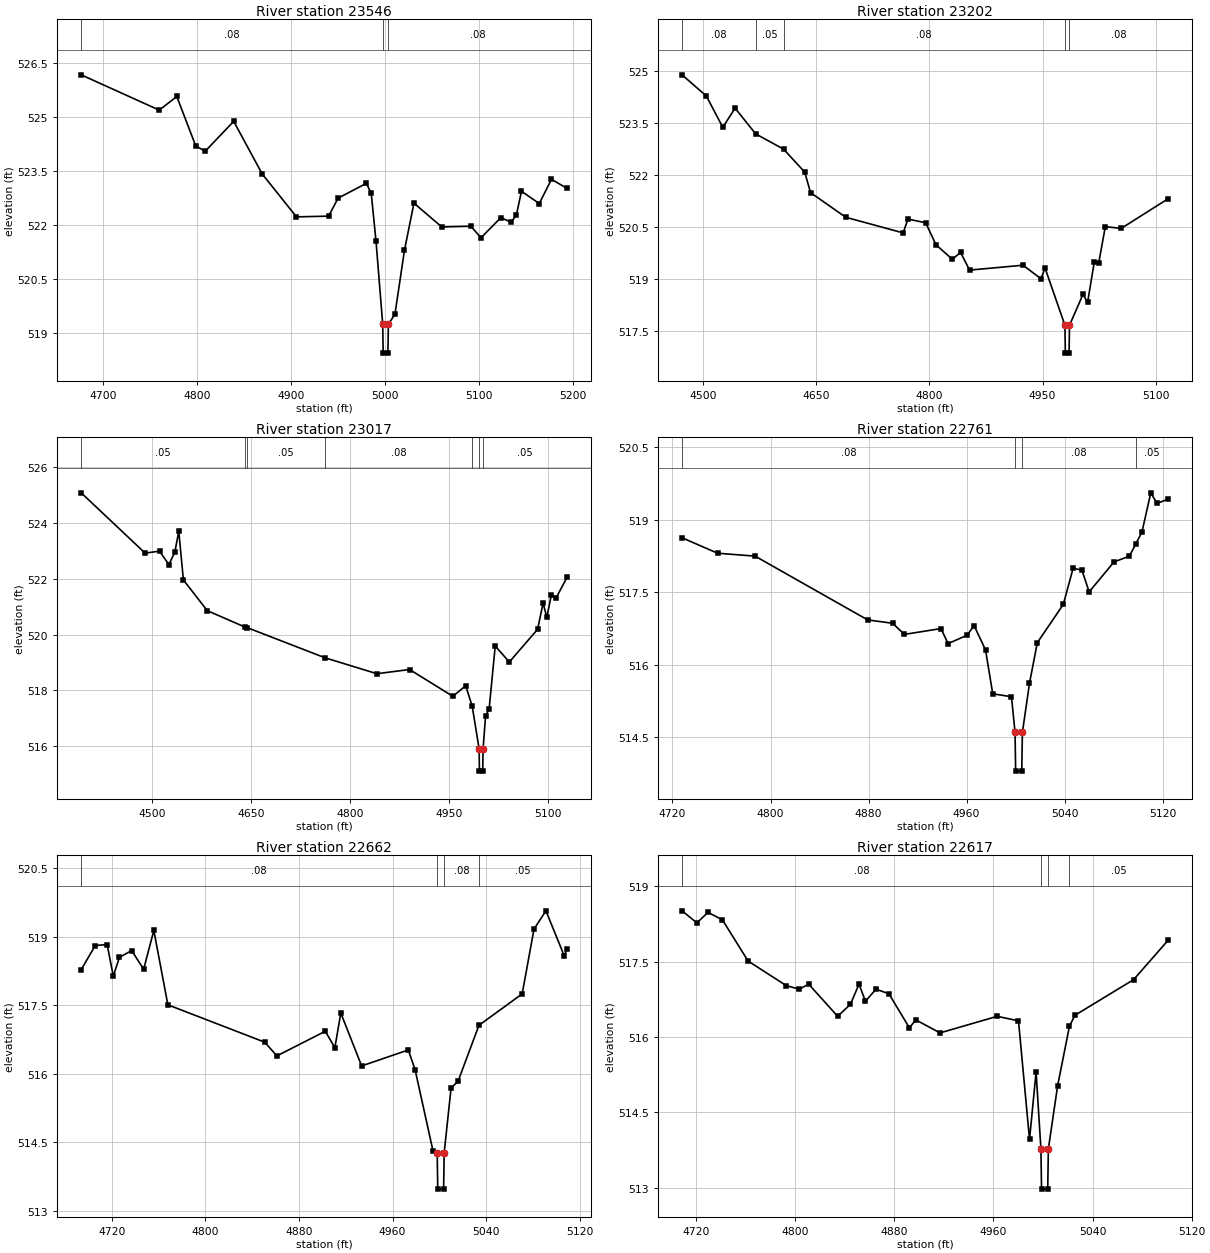
Type RM Length L Ch R = 1,23546,344,344,344
BEGIN DESCRIPTION:
Mapping XS d19cc761
END DESCRIPTION:
XS GIS Cut Line= 4
      2062179.43     13495174.34      2062213.22     13495426.28
      2062234.06     13495590.87      2062269.86     13495680.37
#Sta/Elev= 30
  4677.0  526.17  4760.0  525.19  4778.6  525.57  4798.7  524.20  4808.8  524.05
  4839.1  524.88  4869.4  523.42  4905.8  522.23  4940.0  522.25  4950.1  522.75
  4980.2  523.16  4985.3  522.88  4990.4  521.55  4997.5  519.25  4998.0  518.45
  5003.0  518.45  5003.5  519.25  5010.5  519.53  5020.6  521.30  5030.7  522.61
  5060.3  521.95  5091.2  521.97  5102.0  521.65  5123.1  522.21  5133.9  522.08
  5139.6  522.28  5145.0  522.94  5163.9  522.60  5176.9  523.27  5193.5  523.02
#Mann=3,-1,0
  4677.0    0.08       0  4997.5    0.07       0  5003.5    0.08       0
Bank Sta=4997.5,5003.5
Exp/Cntr=0.3,0.1

Type RM Length L Ch R = 1,23202,185,185,185
BEGIN DESCRIPTION:
Mapping XS 8dce90ac
END DESCRIPTION:
XS GIS Cut Line= 4
      2062157.58     13495255.34      2061966.00     13495705.45
      2062050.03     13495763.78      2062099.35     13495781.85
#Sta/Elev= 30
  4472.1  524.88  4504.3  524.27  4526.1  523.37  4542.4  523.92  4569.7  523.18
  4606.7  522.74  4634.7  522.08  4642.4  521.49  4689.1  520.78  4765.2  520.33
  4771.5  520.73  4795.1  520.62  4808.6  519.99  4830.4  519.57  4841.2  519.77
  4853.2  519.26  4924.1  519.40  4947.8  519.01  4953.2  519.32  4979.6  517.67
  4980.1  516.87  4985.1  516.87  4985.6  517.67  5003.5  518.56  5009.6  518.33
  5018.4  519.48  5024.4  519.47  5033.1  520.51  5054.2  520.46  5116.1  521.31
#Mann=5,-1,0
  4472.1    0.08       0  4569.7    0.05       0  4606.7    0.08       0
  4979.6    0.07       0  4985.6    0.08       0
Bank Sta=4979.6,4985.6
Exp/Cntr=0.3,0.1

Type RM Length L Ch R = 1,23017,256,256,256
BEGIN DESCRIPTION:
Mapping XS 5db40de9
END DESCRIPTION:
XS GIS Cut Line= 4
      2062091.61     13495196.30      2061943.08     13495418.64
      2061789.61     13495822.81      2061816.69     13495847.11
#Sta/Elev= 30
  4392.9  525.08  4489.7  522.92  4511.6  522.99  4525.7  522.51  4534.7  522.95
  4540.7  523.70  4547.7  521.96  4583.8  520.86  4641.1  520.27  4644.4  520.25
  4762.3  519.17  4840.8  518.60  4890.4  518.75  4956.0  517.79  4975.4  518.17
  4985.2  517.44  4995.7  515.91  4996.2  515.11  5001.2  515.11  5001.7  515.91
  5005.5  517.08  5010.9  517.34  5020.1  519.59  5041.5  519.02  5084.3  520.19
  5092.6  521.13  5098.3  520.62  5105.0  521.41  5112.5  521.32  5129.0  522.06
#Mann=7,-1,0
  4392.9    0.05       0  4641.1    0.08       0  4644.4    0.05       0
  4762.3    0.08       0  4985.2    0.05       0  4995.7    0.04       0
  5001.7    0.05       0
Bank Sta=4995.7,5001.7
Exp/Cntr=0.3,0.1

Type RM Length L Ch R = 1,22761,99,99,99
BEGIN DESCRIPTION:
Mapping XS 794f0438
END DESCRIPTION:
XS GIS Cut Line= 4
      2061843.45     13495502.90      2061650.03     13495542.26
      2061564.61     13495676.28      2061572.25     13495715.84
#Sta/Elev= 30
  4727.8  518.63  4756.8  518.31  4787.4  518.25  4879.3  516.93  4899.7  516.86
  4909.3  516.63  4939.1  516.75  4945.0  516.44  4960.3  516.61  4966.2  516.81
  4975.5  516.31  4981.4  515.40  4996.7  515.34  4999.6  514.60  5000.1  513.80
  5005.1  513.80  5005.6  514.60  5011.4  515.62  5017.8  516.46  5039.0  517.25
  5047.0  518.00  5054.2  517.96  5060.1  517.51  5080.4  518.13  5093.0  518.25
  5098.3  518.51  5103.2  518.75  5110.4  519.56  5115.5  519.34  5124.4  519.43
#Mann=4,-1,0
  4727.8    0.08       0  4999.6    0.07       0  5005.6    0.08       0
  5098.3    0.05       0
Bank Sta=4999.6,5005.6
Exp/Cntr=0.3,0.1

Type RM Length L Ch R = 1,22662,45,45,45
BEGIN DESCRIPTION:
Mapping XS fd1105dd
END DESCRIPTION:
XS GIS Cut Line= 4
      2061796.59     13495472.95      2061536.14     13495542.95
      2061482.67     13495629.06      2061490.31     13495672.85
#Sta/Elev= 30
  4693.8  518.28  4705.8  518.81  4716.0  518.83  4721.2  518.14  4726.5  518.55
  4736.9  518.70  4747.2  518.29  4755.9  519.14  4767.9  517.51  4850.8  516.69
  4861.1  516.39  4902.5  516.93  4910.7  516.57  4915.8  517.33  4933.6  516.17
  4973.5  516.52  4979.3  516.09  4994.7  514.30  4998.2  514.27  4998.7  513.47
  5003.7  513.47  5004.2  514.27  5010.1  515.69  5016.0  515.83  5033.9  517.06
  5070.9  517.75  5081.0  519.17  5091.2  519.57  5106.9  518.58  5109.3  518.74
#Mann=4,-1,0
  4693.8    0.08       0  4998.2    0.07       0  5004.2    0.08       0
  5033.9    0.05       0
Bank Sta=4998.2,5004.2
Exp/Cntr=0.3,0.1

Type RM Length L Ch R = 1,22617,172,172,172
BEGIN DESCRIPTION:
Mapping XS d7267cee
END DESCRIPTION:
XS GIS Cut Line= 4
      2061766.57     13495463.85      2061559.75     13495517.26
      2061439.61     13495558.23      2061393.78     13495581.84
#Sta/Elev= 30
  4708.7  518.51  4720.7  518.27  4729.6  518.48  4741.3  518.33  4762.0  517.51
  4792.9  517.02  4803.3  516.95  4810.9  517.05  4834.3  516.41  4844.6  516.65
  4851.5  517.05  4856.7  516.71  4865.2  516.95  4875.6  516.86  4892.2  516.18
  4897.3  516.34  4916.9  516.08  4963.0  516.41  4980.2  516.32  4989.1  513.96
  4994.4  515.30  4998.3  513.77  4998.8  512.97  5003.8  512.97  5004.3  513.77
  5011.8  515.03  5021.3  516.21  5025.7  516.43  5073.1  517.14  5100.8  517.92
#Mann=4,-1,0
  4708.7    0.08       0  4998.3    0.07       0  5004.3    0.08       0
  5021.3    0.05       0
Bank Sta=4998.3,5004.3
Exp/Cntr=0.3,0.1

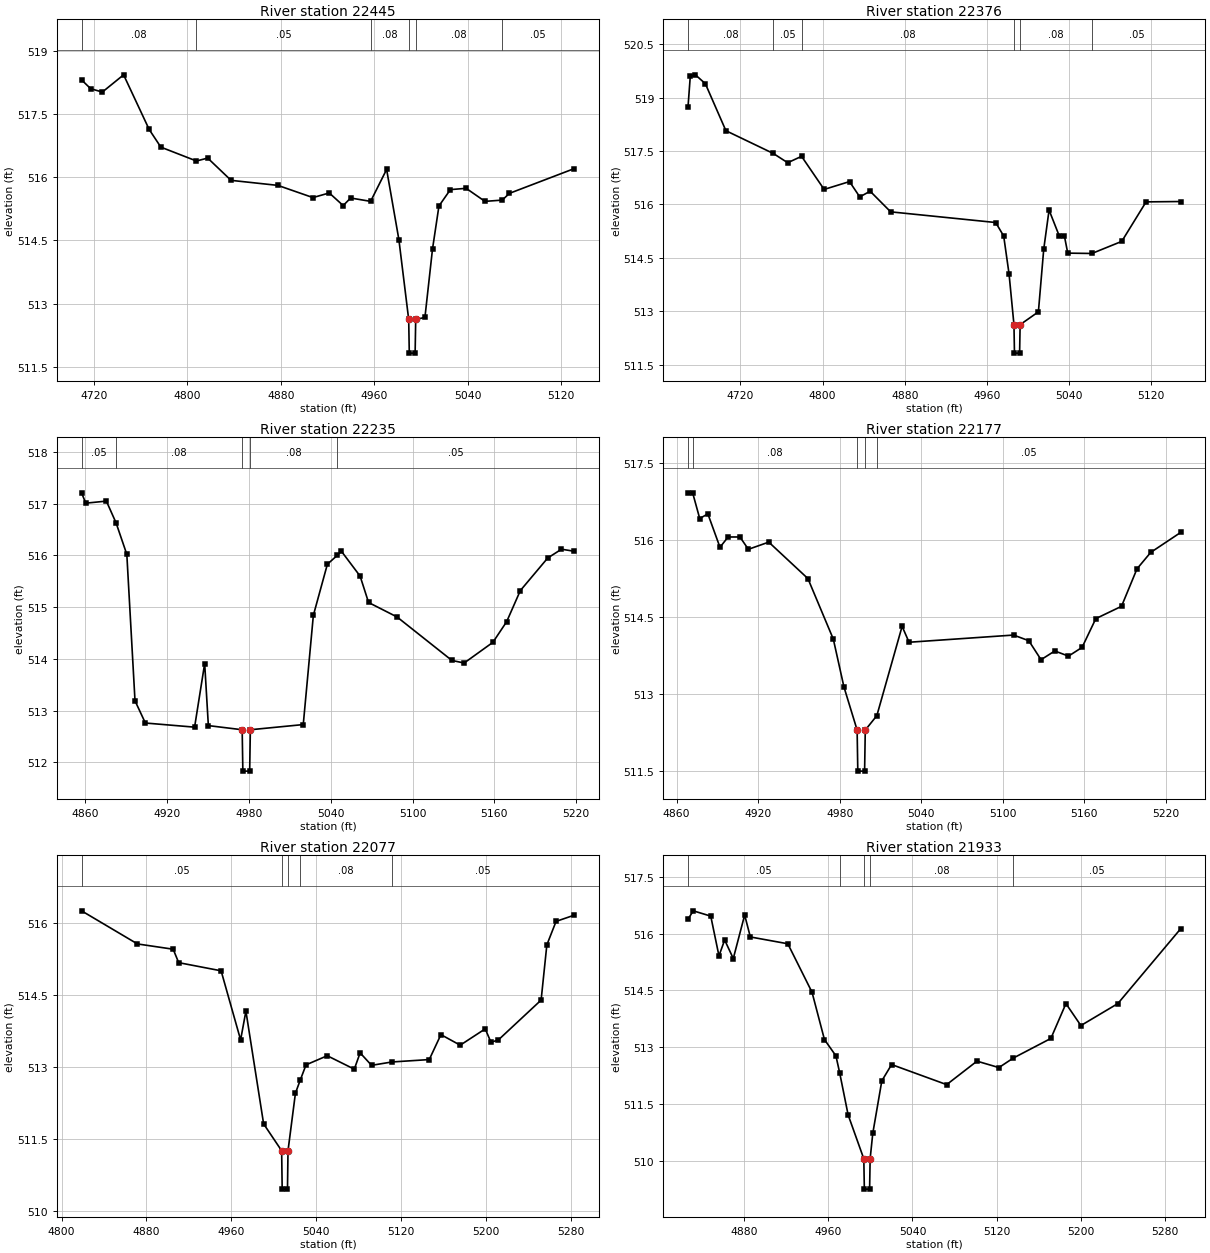
Type RM Length L Ch R = 1,22445,69,69,69
BEGIN DESCRIPTION:
Mapping XS fb92dbb2
END DESCRIPTION:
XS GIS Cut Line= 4
      2061732.80     13495362.28      2061508.36     13495349.20
      2061395.86     13495398.51      2061363.21     13495465.20
#Sta/Elev= 30
  4709.4  518.32  4717.2  518.11  4727.2  518.03  4745.4  518.44  4767.3  517.14
  4777.3  516.72  4807.8  516.39  4817.4  516.46  4837.4  515.93  4877.5  515.81
  4907.5  515.52  4921.5  515.63  4933.4  515.33  4939.8  515.51  4956.9  515.43
  4970.6  516.19  4981.1  514.52  4989.5  512.62  4990.0  511.82  4995.0  511.82
  4995.5  512.62  5003.4  512.67  5009.9  514.30  5015.4  515.32  5025.2  515.71
  5038.7  515.74  5054.8  515.43  5069.6  515.46  5075.7  515.62  5131.3  516.21
#Mann=6,-1,0
  4709.4    0.08       0  4807.8    0.05       0  4956.9    0.08       0
  4989.5    0.07       0  4995.5    0.08       0  5069.6    0.05       0
Bank Sta=4989.5,4995.5
Exp/Cntr=0.3,0.1

Type RM Length L Ch R = 1,22376,141,141,141
BEGIN DESCRIPTION:
Mapping XS f75c9e71
END DESCRIPTION:
XS GIS Cut Line= 4
      2061741.83     13495310.19      2061499.33     13495291.56
      2061380.58     13495325.59      2061336.14     13495429.76
#Sta/Elev= 30
  4668.9  518.74  4671.1  519.60  4676.1  519.64  4685.8  519.39  4705.8  518.07
  4752.0  517.43  4766.0  517.17  4779.5  517.35  4801.5  516.42  4826.2  516.64
  4836.2  516.21  4846.3  516.37  4866.3  515.79  4968.6  515.49  4976.4  515.11
  4981.6  514.05  4986.4  512.62  4986.9  511.82  4991.9  511.82  4992.4  512.62
  5010.2  512.98  5015.4  514.74  5020.6  515.84  5030.7  515.10  5035.6  515.10
  5038.8  514.63  5062.3  514.62  5091.4  514.96  5115.1  516.07  5148.9  516.08
#Mann=6,-1,0
  4668.9    0.08       0  4752.0    0.05       0  4779.5    0.08       0
  4986.4    0.07       0  4992.4    0.08       0  5062.3    0.05       0
Bank Sta=4986.4,4992.4
Exp/Cntr=0.3,0.1

Type RM Length L Ch R = 1,22235,58,58,58
BEGIN DESCRIPTION:
Mapping XS 1da3ca12
END DESCRIPTION:
XS GIS Cut Line= 4
      2061434.03     13495099.22      2061355.58     13495151.28
      2061327.11     13495268.64      2061312.18     13495414.36
#Sta/Elev= 30
  4857.2  517.21  4860.3  517.01  4875.4  517.05  4882.5  516.63  4890.4  516.02
  4896.4  513.19  4904.0  512.76  4940.1  512.68  4947.5  513.91  4950.2  512.71
  4975.0  512.63  4975.5  511.83  4980.5  511.83  4981.0  512.63  5019.8  512.73
  5027.2  514.84  5037.5  515.83  5044.7  516.00  5047.8  516.08  5061.5  515.60
  5067.7  515.09  5088.6  514.81  5128.8  513.97  5137.8  513.92  5158.9  514.32
  5169.0  514.72  5179.0  515.32  5199.1  515.95  5209.2  516.12  5218.6  516.08
#Mann=5,-1,0
  4857.2    0.05       0  4882.5    0.08       0  4975.0    0.07       0
  4981.0    0.08       0  5044.7    0.05       0
Bank Sta=4975,4981
Exp/Cntr=0.3,0.1

Type RM Length L Ch R = 1,22177,100,100,100
BEGIN DESCRIPTION:
Mapping XS 5064eb31
END DESCRIPTION:
XS GIS Cut Line= 4
      2061345.19     13495073.47      2061297.25     13495143.64
      2061272.95     13495249.20      2061295.25     13495416.92
#Sta/Elev= 30
  4868.4  516.92  4871.8  516.92  4877.0  516.42  4883.0  516.51  4891.9  515.86
  4897.9  516.06  4906.6  516.06  4912.8  515.82  4927.8  515.96  4956.6  515.25
  4975.3  514.07  4983.1  513.14  4992.8  512.30  4993.3  511.50  4998.3  511.50
  4998.8  512.30  5007.3  512.58  5025.9  514.32  5031.0  514.01  5107.9  514.15
  5119.1  514.04  5128.1  513.67  5138.2  513.84  5148.3  513.74  5158.3  513.91
  5168.4  514.47  5187.3  514.71  5198.7  515.44  5208.8  515.76  5230.9  516.15
#Mann=5,-1,0
  4868.4    0.05       0  4871.8    0.08       0  4992.8    0.07       0
  4998.8    0.08       0  5007.3    0.05       0
Bank Sta=4992.8,4998.8
Exp/Cntr=0.3,0.1

Type RM Length L Ch R = 1,22077,144,144,144
BEGIN DESCRIPTION:
Mapping XS 039ac759
END DESCRIPTION:
XS GIS Cut Line= 4
      2061248.41     13495014.59      2061191.70     13495079.76
      2061187.53     13495244.34      2061271.45     13495440.85
#Sta/Elev= 30
  4818.8  516.25  4871.5  515.56  4905.2  515.45  4910.4  515.17  4950.4  515.00
  4968.8  513.56  4973.8  514.16  4990.5  511.81  5007.5  511.25  5008.0  510.45
  5013.0  510.45  5013.5  511.25  5020.5  512.45  5025.0  512.72  5030.5  513.04
  5050.5  513.23  5076.0  512.95  5081.5  513.29  5092.3  513.03  5111.5  513.10
  5146.7  513.15  5157.7  513.67  5175.9  513.45  5199.5  513.79  5204.9  513.51
  5211.9  513.56  5252.2  514.39  5257.6  515.54  5266.3  516.03  5283.5  516.16
#Mann=5,-1,0
  4818.8    0.05       0  5007.5    0.04       0  5013.5    0.05       0
  5025.0    0.08       0  5111.5    0.05       0
Bank Sta=5007.5,5013.5
Exp/Cntr=0.3,0.1

Type RM Length L Ch R = 1,21933,175,175,175
BEGIN DESCRIPTION:
Mapping XS 564ab472
END DESCRIPTION:
XS GIS Cut Line= 4
      2061081.71     13495084.95      2061047.95     13495170.73
      2061112.53     13495318.64      2061252.69     13495481.03
#Sta/Elev= 30
  4826.8  516.38  4831.8  516.60  4848.4  516.46  4856.2  515.41  4861.6  515.83
  4869.8  515.34  4880.6  516.49  4886.0  515.91  4921.6  515.73  4944.6  514.45
  4956.4  513.20  4967.3  512.77  4970.8  512.33  4978.9  511.21  4993.8  510.05
  4994.3  509.25  4999.3  509.25  4999.8  510.05  5002.3  510.72  5010.9  512.11
  5020.2  512.54  5072.5  512.01  5101.3  512.63  5122.1  512.46  5135.7  512.71
  5171.5  513.23  5185.8  514.15  5200.0  513.57  5235.1  514.15  5294.9  516.13
#Mann=5,-1,0
  4826.8    0.05       0  4970.8    0.08       0  4993.8    0.07       0
  4999.8    0.08       0  5135.7    0.05       0
Bank Sta=4993.8,4999.8
Exp/Cntr=0.3,0.1

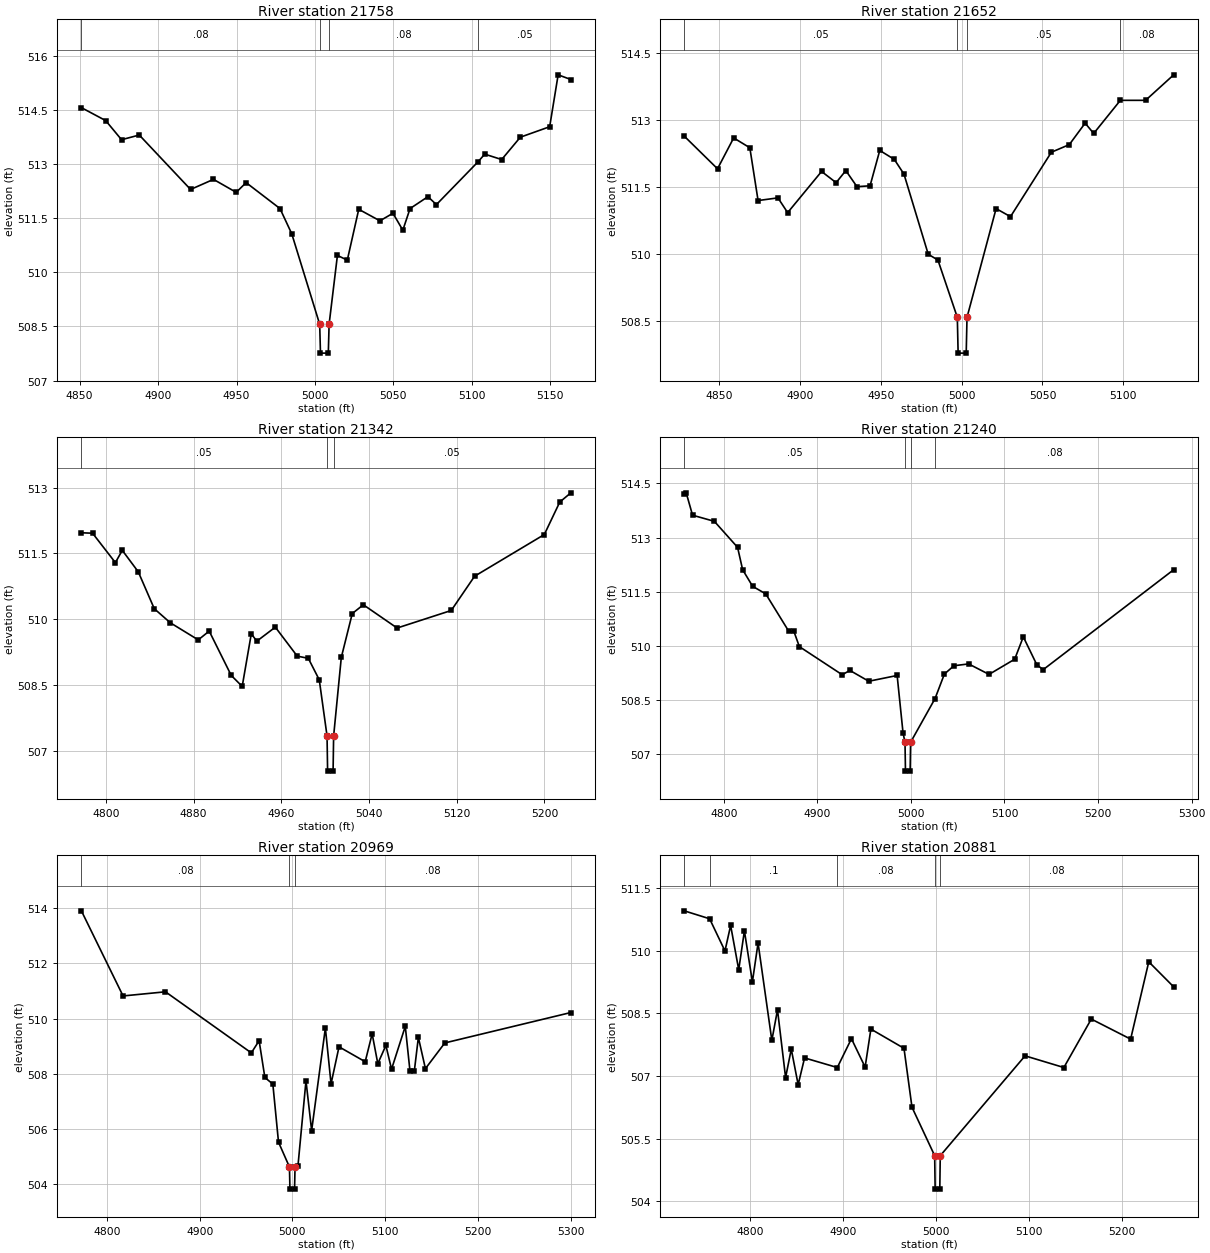
Type RM Length L Ch R = 1,21758,106,106,106
BEGIN DESCRIPTION:
Mapping XS 1eef1075
END DESCRIPTION:
XS GIS Cut Line= 4
      2060913.93     13495279.80      2060922.95     13495327.67
      2061052.11     13495425.59      2061145.83     13495463.77
#Sta/Elev= 30
  4851.1  514.57  4866.6  514.21  4876.7  513.68  4888.0  513.81  4920.7  512.30
  4935.3  512.58  4949.8  512.22  4956.1  512.49  4977.7  511.77  4985.2  511.07
  5003.0  508.56  5003.5  507.76  5008.5  507.76  5009.0  508.56  5014.3  510.47
  5020.6  510.34  5027.9  511.75  5041.4  511.43  5049.7  511.64  5056.0  511.17
  5060.6  511.77  5072.0  512.10  5077.4  511.88  5104.0  513.07  5108.2  513.28
  5119.0  513.13  5130.9  513.75  5149.6  514.04  5155.0  515.48  5163.1  515.35
#Mann=4,-1,0
  4851.1    0.08       0  5003.0    0.07       0  5009.0    0.08       0
  5104.0    0.05       0
Bank Sta=5003,5009
Exp/Cntr=0.3,0.1

Type RM Length L Ch R = 1,21652,310,310,310
BEGIN DESCRIPTION:
Mapping XS 5e790369
END DESCRIPTION:
XS GIS Cut Line= 4
      2060875.72     13495364.46      2060874.33     13495410.31
      2061027.11     13495513.09      2061096.54     13495535.31
#Sta/Elev= 30
  4828.3  512.64  4848.9  511.91  4858.9  512.60  4868.9  512.38  4874.0  511.20
  4886.3  511.26  4892.3  510.93  4913.3  511.85  4922.3  511.60  4928.3  511.87
  4935.2  511.51  4943.3  511.53  4949.3  512.32  4958.3  512.12  4964.3  511.79
  4979.3  510.00  4985.3  509.87  4997.3  508.59  4997.8  507.79  5002.8  507.79
  5003.3  508.59  5021.3  511.02  5030.2  510.84  5055.5  512.28  5066.6  512.45
  5076.4  512.93  5081.7  512.70  5098.2  513.44  5113.8  513.44  5131.2  514.01
#Mann=4,-1,0
  4828.3    0.05       0  4997.3    0.04       0  5003.3    0.05       0
  5098.2    0.08       0
Bank Sta=4997.3,5003.3
Exp/Cntr=0.3,0.1

Type RM Length L Ch R = 1,21342,102,102,102
BEGIN DESCRIPTION:
Mapping XS ae9c54f2
END DESCRIPTION:
XS GIS Cut Line= 4
      2060759.77     13495406.81      2060704.20     13495481.84
      2060720.86     13495667.26      2060837.53     13495786.70
#Sta/Elev= 30
  4777.6  511.97  4787.8  511.96  4808.6  511.29  4814.9  511.57  4829.5  511.08
  4844.1  510.24  4858.7  509.92  4884.2  509.53  4894.2  509.73  4914.3  508.72
  4924.3  508.47  4932.6  509.67  4937.6  509.50  4954.5  509.82  4974.5  509.16
  4984.6  509.11  4994.6  508.62  5001.7  507.34  5002.2  506.54  5007.2  506.54
  5007.7  507.34  5014.7  509.13  5024.7  510.13  5034.8  510.33  5065.6  509.80
  5115.0  510.20  5136.3  510.98  5199.9  511.93  5214.0  512.67  5224.1  512.88
#Mann=3,-1,0
  4777.6    0.05       0  5001.7    0.04       0  5007.7    0.05       0
Bank Sta=5001.7,5007.7
Exp/Cntr=0.3,0.1

Type RM Length L Ch R = 1,21240,271,271,271
BEGIN DESCRIPTION:
Mapping XS 8405d1fe
END DESCRIPTION:
XS GIS Cut Line= 4
      2060690.21     13495336.69      2060645.86     13495453.37
      2060617.39     13495649.20      2060723.18     13495819.27
#Sta/Elev= 30
  4757.8  514.21  4759.9  514.24  4766.7  513.62  4790.0  513.45  4814.8  512.73
  4820.2  512.11  4830.9  511.65  4844.9  511.44  4869.6  510.40  4875.0  510.40
  4880.8  509.98  4926.6  509.20  4934.8  509.32  4955.0  509.02  4985.3  509.18
  4991.6  507.59  4993.7  507.33  4994.2  506.53  4999.2  506.53  4999.7  507.33
  5025.8  508.54  5035.8  509.22  5046.0  509.45  5061.7  509.50  5083.5  509.21
  5110.9  509.63  5120.1  510.25  5134.5  509.48  5141.3  509.34  5280.8  512.11
#Mann=4,-1,0
  4757.8    0.05       0  4993.7    0.04       0  4999.7    0.05       0
  5025.8    0.08       0
Bank Sta=4993.7,4999.7
Exp/Cntr=0.3,0.1

Type RM Length L Ch R = 1,20969,88,88,88
BEGIN DESCRIPTION:
Mapping XS 65bf5dcb
END DESCRIPTION:
XS GIS Cut Line= 4
      2060313.22     13495287.06      2060314.96     13495333.92
      2060495.52     13495588.26      2060623.09     13495698.48
#Sta/Elev= 30
  4772.6  513.90  4817.5  510.82  4863.2  510.97  4955.7  508.76  4964.1  509.20
  4970.3  507.87  4978.9  507.63  4985.0  505.53  4996.8  504.63  4997.3  503.83
  5002.3  503.83  5002.8  504.63  5005.9  504.65  5014.6  507.75  5020.7  505.95
  5035.5  509.66  5041.6  507.64  5050.2  508.98  5078.4  508.44  5085.9  509.45
  5092.0  508.37  5100.7  509.03  5106.8  508.17  5121.6  509.72  5126.6  508.12
  5131.4  508.12  5135.7  509.32  5143.3  508.19  5164.2  509.12  5300.0  510.22
#Mann=3,-1,0
  4772.6    0.08       0  4996.8    0.07       0  5002.8    0.08       0
Bank Sta=4996.8,5002.8
Exp/Cntr=0.3,0.1

Type RM Length L Ch R = 1,20881,109,109,109
BEGIN DESCRIPTION:
Mapping XS 24df4aab
END DESCRIPTION:
XS GIS Cut Line= 4
      2060155.24     13495333.92      2060261.14     13495409.44
      2060454.72     13495679.41      2060432.14     13495739.33
#Sta/Elev= 30
  4728.9  510.95  4756.2  510.76  4772.7  509.99  4778.8  510.60  4787.5  509.54
  4793.6  510.47  4802.2  509.25  4808.3  510.18  4823.1  507.85  4829.2  508.58
  4837.9  506.96  4844.0  507.64  4851.4  506.79  4858.3  507.43  4893.5  507.20
  4908.7  507.89  4923.4  507.21  4929.6  508.12  4965.2  507.66  4973.8  506.25
  4998.2  505.09  4998.7  504.29  5003.7  504.29  5004.2  505.09  5095.4  507.48
  5137.1  507.20  5166.6  508.36  5208.9  507.88  5228.4  509.73  5255.2  509.13
#Mann=5,-1,0
  4728.9    0.05       0  4756.2     0.1       0  4893.5    0.08       0
  4998.2    0.07       0  5004.2    0.08       0
Bank Sta=4998.2,5004.2
Exp/Cntr=0.3,0.1

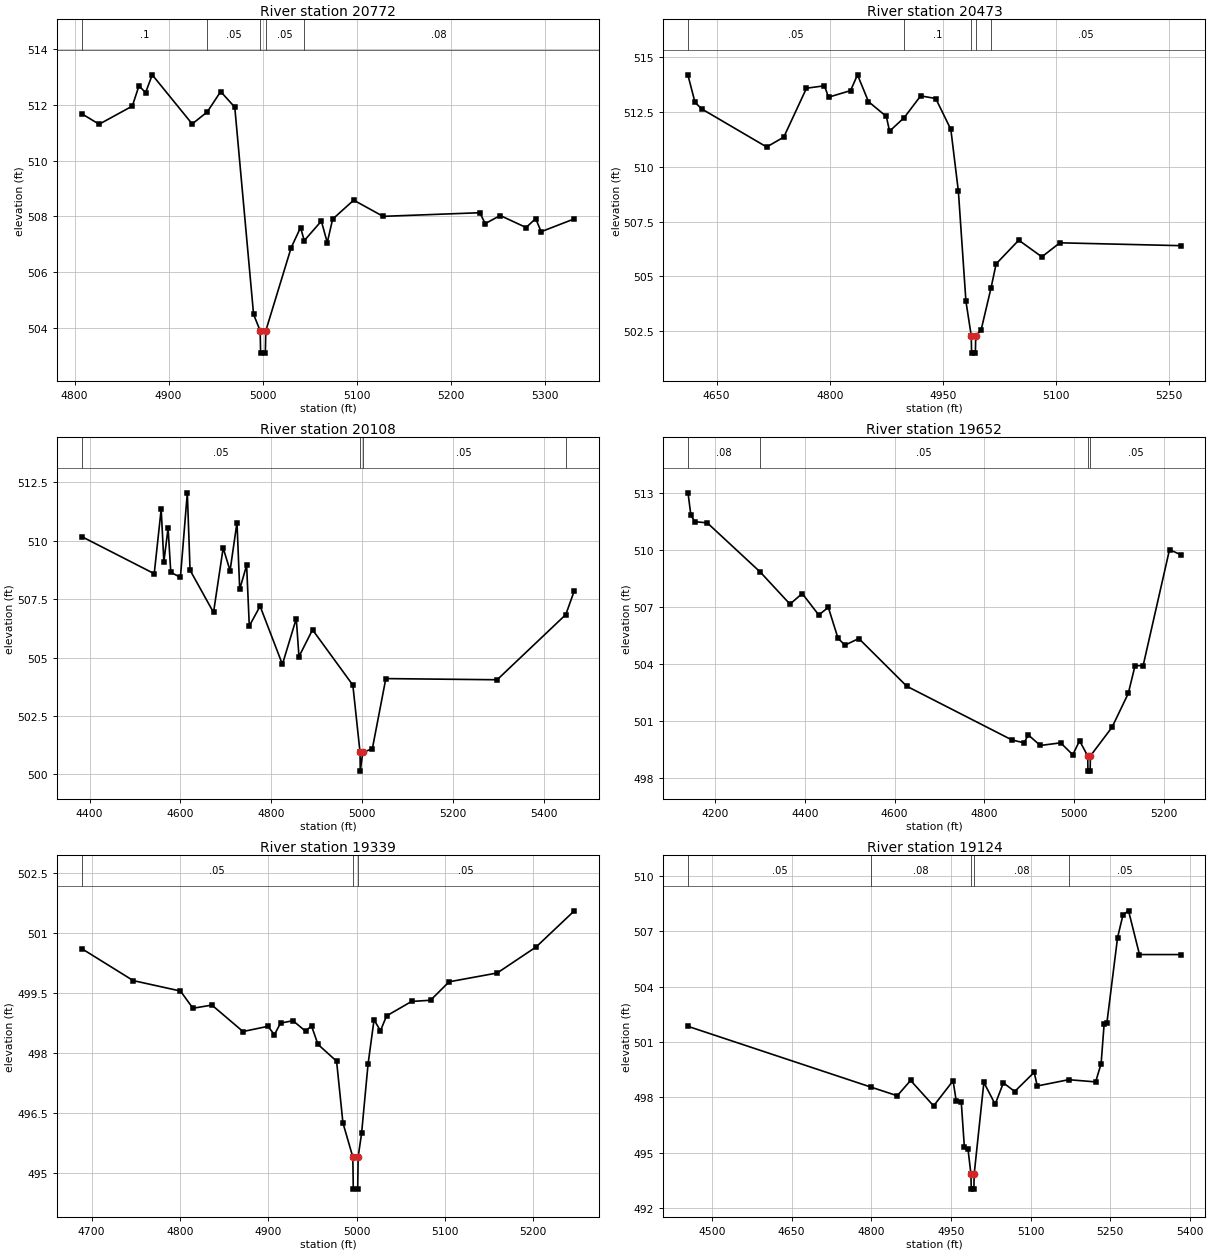
Type RM Length L Ch R = 1,20772,299,299,299
BEGIN DESCRIPTION:
Mapping XS 6e71303f
END DESCRIPTION:
XS GIS Cut Line= 4
      2060137.51     13495356.10      2060242.95     13495460.24
      2060241.65     13495550.08      2060102.35     13495800.04
#Sta/Elev= 30
  4807.5  511.68  4826.2  511.30  4861.5  511.95  4868.6  512.68  4875.6  512.43
  4882.7  513.07  4925.2  511.31  4941.2  511.74  4955.5  512.47  4970.5  511.91
  4990.5  504.49  4997.5  503.90  4998.0  503.10  5003.0  503.10  5003.5  503.90
  5030.5  506.88  5040.5  507.60  5044.4  507.13  5062.6  507.83  5068.9  507.06
  5074.6  507.90  5097.0  508.58  5128.3  508.00  5231.2  508.13  5236.9  507.74
  5252.9  508.03  5280.4  507.60  5290.6  507.92  5296.4  507.45  5331.7  507.91
#Mann=5,-1,0
  4807.5     0.1       0  4941.2    0.05       0  4997.5    0.04       0
  5003.5    0.05       0  5044.4    0.08       0
Bank Sta=4997.5,5003.5
Exp/Cntr=0.3,0.1

Type RM Length L Ch R = 1,20473,365,365,365
BEGIN DESCRIPTION:
Mapping XS 5a3d6798
END DESCRIPTION:
XS GIS Cut Line= 6
      2060072.15     13495078.03      2059966.87     13495327.85
      2059969.47     13495510.14      2059987.74     13495572.21
      2059981.23     13495629.51      2059949.99     13495700.02
#Sta/Elev= 30
  4612.2  514.16  4621.5  512.93  4630.6  512.63  4716.4  510.90  4739.1  511.35
  4769.2  513.58  4793.0  513.69  4798.4  513.17  4827.6  513.47  4836.8  514.19
  4851.3  512.97  4875.0  512.29  4879.3  511.62  4898.7  512.24  4920.5  513.23
  4940.5  513.11  4960.5  511.70  4970.5  508.87  4980.5  503.86  4987.5  502.30
  4988.0  501.50  4993.0  501.50  4993.5  502.30  5000.5  502.54  5013.8  504.48
  5020.5  505.57  5050.5  506.65  5081.1  505.89  5105.0  506.53  5265.2  506.40
#Mann=5,-1,0
  4612.2    0.05       0  4898.7     0.1       0  4987.5    0.07       0
  4993.5     0.1       0  5013.8    0.05       0
Bank Sta=4987.5,4993.5
Exp/Cntr=0.3,0.1

Type RM Length L Ch R = 1,20108,456,456,456
BEGIN DESCRIPTION:
Mapping XS fdb8a6e0
END DESCRIPTION:
XS GIS Cut Line= 4
      2059924.95     13495133.80      2059656.11     13495556.14
      2059733.36     13495747.99      2059960.53     13496047.78
#Sta/Elev= 30
  4382.5  510.18  4542.3  508.59  4557.6  511.35  4563.5  509.10  4572.8  510.54
  4578.7  508.65  4599.9  508.43  4615.1  512.05  4621.1  508.74  4672.7  506.93
  4693.9  509.69  4709.1  508.72  4724.3  510.78  4730.3  507.92  4745.5  508.95
  4751.4  506.35  4775.1  507.20  4824.2  504.71  4854.7  506.67  4860.6  505.04
  4890.4  506.19  4979.1  503.82  4994.9  500.94  4995.4  500.14  5000.9  500.94
  5022.0  501.10  5051.6  504.10  5296.4  504.05  5447.4  506.84  5466.1  507.86
#Mann=4,-1,0
  4382.5    0.05       0  4994.9    0.04       0  5000.9    0.05       0
  5447.4    0.08       0
Bank Sta=4994.9,5000.9
Exp/Cntr=0.3,0.1

Type RM Length L Ch R = 1,19652,313,313,313
BEGIN DESCRIPTION:
Mapping XS 15b5417a
END DESCRIPTION:
XS GIS Cut Line= 4
      2059980.49     13494960.20      2059413.61     13495303.58
      2059222.64     13495593.17      2059231.67     13495679.94
#Sta/Elev= 30
  4140.2  513.03  4146.6  511.84  4155.8  511.51  4183.0  511.45  4301.0  508.86
  4367.2  507.17  4394.4  507.73  4431.2  506.60  4452.5  507.00  4474.0  505.38
  4489.4  505.01  4520.4  505.36  4627.1  502.85  4861.3  500.02  4888.5  499.87
  4897.4  500.29  4924.5  499.73  4969.7  499.87  4996.7  499.24  5011.8  499.98
  5029.9  499.18  5030.4  498.38  5035.4  498.38  5035.9  499.18  5084.1  500.69
  5120.2  502.47  5135.3  503.93  5153.3  503.93  5212.0  510.04  5237.1  509.77
#Mann=4,-1,0
  4140.2    0.08       0  4301.0    0.05       0  5029.9    0.03       0
  5035.9    0.05       0
Bank Sta=5029.9,5035.9
Exp/Cntr=0.3,0.1

Type RM Length L Ch R = 1,19339,215,215,215
BEGIN DESCRIPTION:
Mapping XS 9b663a55
END DESCRIPTION:
XS GIS Cut Line= 4
      2059293.47     13495170.95      2059185.84     13495169.56
      2058921.95     13495418.86      2058958.76     13495498.05
#Sta/Elev= 30
  4688.6  500.61  4747.1  499.81  4800.6  499.55  4814.7  499.12  4836.2  499.20
  4871.4  498.54  4899.7  498.67  4907.0  498.46  4913.9  498.75  4928.0  498.81
  4942.2  498.55  4949.0  498.68  4956.3  498.22  4977.4  497.80  4984.6  496.26
  4995.8  495.41  4996.3  494.61  5001.3  494.61  5001.8  495.41  5005.7  496.00
  5013.0  497.72  5019.8  498.83  5027.1  498.56  5034.0  498.93  5062.3  499.29
  5083.8  499.32  5104.8  499.78  5159.3  500.00  5203.4  500.65  5246.6  501.55
#Mann=3,-1,0
  4688.6    0.05       0  4995.8    0.03       0  5001.8    0.05       0
Bank Sta=4995.8,5001.8
Exp/Cntr=0.3,0.1

Type RM Length L Ch R = 1,19124,108,108,108
BEGIN DESCRIPTION:
Mapping XS fc4a0ffa
END DESCRIPTION:
XS GIS Cut Line= 4
      2059371.78     13494974.92      2058969.17     13495122.51
      2058728.28     13495270.08      2058674.10     13495480.31
#Sta/Elev= 30
  4454.7  501.85  4799.2  498.56  4848.9  498.09  4874.1  498.92  4917.4  497.54
  4954.1  498.90  4959.9  497.83  4969.5  497.75  4975.4  495.29  4982.2  495.20
  4987.8  493.83  4988.3  493.03  4993.3  493.03  4993.8  493.83  5012.1  498.81
  5033.4  497.63  5048.9  498.79  5070.2  498.32  5106.9  499.36  5112.7  498.62
  5171.9  498.96  5222.7  498.84  5233.0  499.83  5238.7  501.98  5243.9  502.04
  5264.0  506.66  5274.3  507.90  5284.7  508.11  5305.3  505.74  5383.1  505.74
#Mann=5,-1,0
  4454.7    0.05       0  4799.2    0.08       0  4987.8    0.07       0
  4993.8    0.08       0  5171.9    0.05       0
Bank Sta=4987.8,4993.8
Exp/Cntr=0.3,0.1

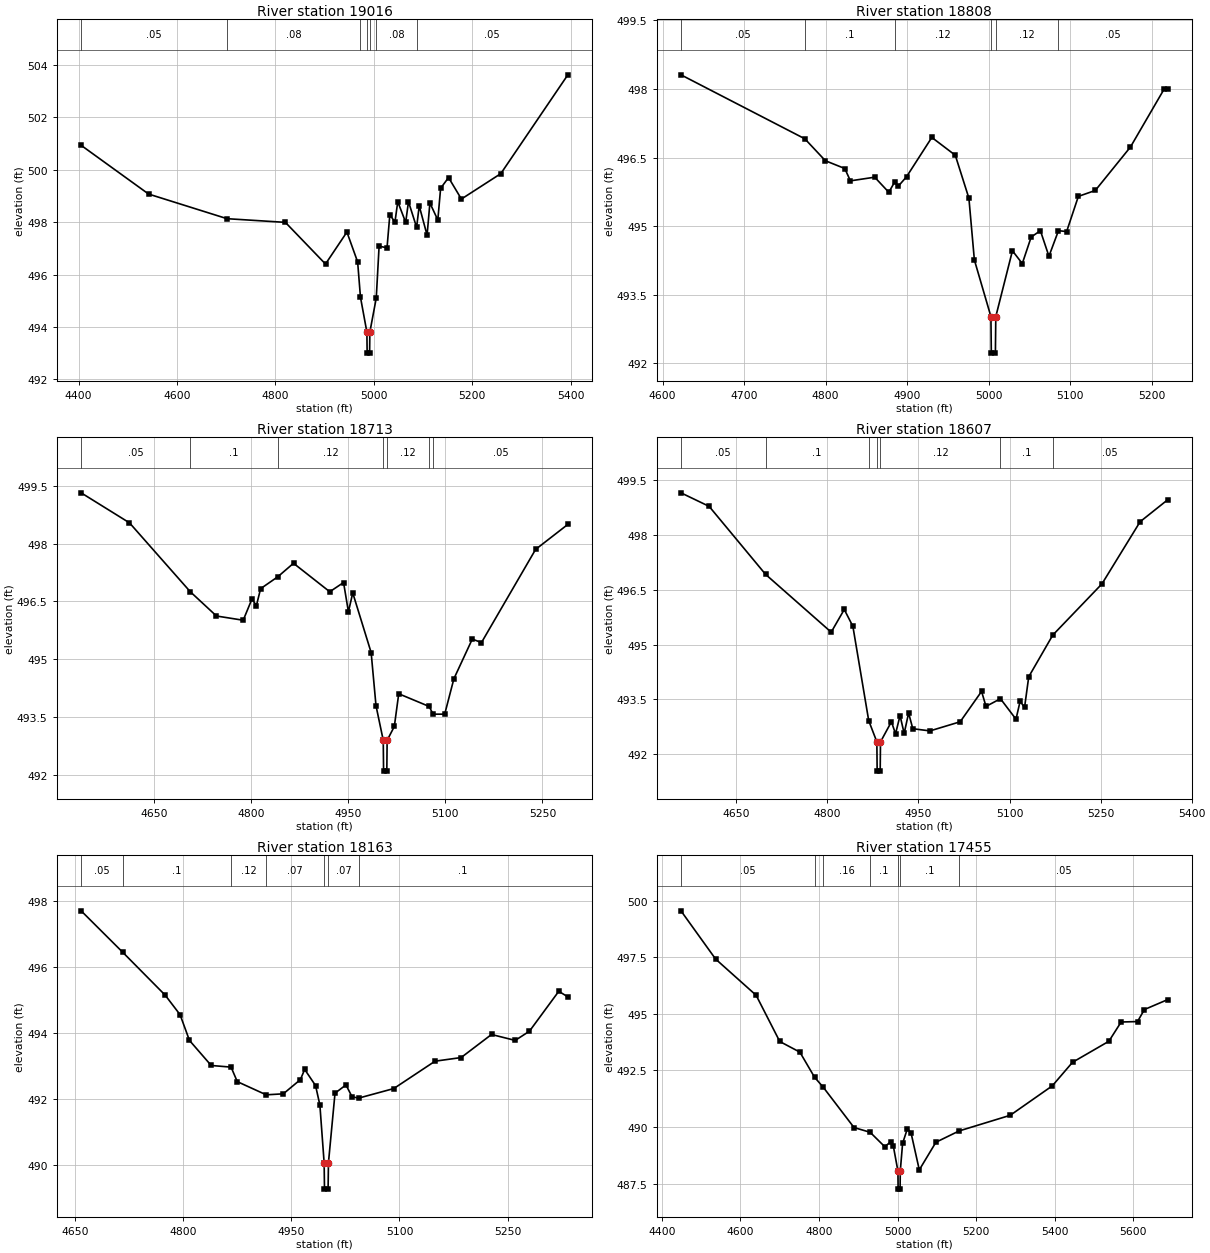
Type RM Length L Ch R = 1,19016,208,208,208
BEGIN DESCRIPTION:
Mapping XS f479e553
END DESCRIPTION:
XS GIS Cut Line= 4
      2059200.30     13494701.48      2059035.36     13494973.85
      2058654.50     13495183.27      2058418.96     13495171.39
#Sta/Elev= 30
  4405.3  500.93  4542.4  499.07  4701.8  498.13  4820.3  497.99  4901.8  496.40
  4945.3  497.62  4967.1  496.48  4972.8  495.14  4985.9  493.80  4986.4  493.00
  4991.4  493.00  4991.9  493.80  5004.9  495.10  5010.7  497.08  5026.8  497.02
  5032.5  498.28  5042.9  498.00  5048.6  498.78  5064.7  497.99  5070.4  498.78
  5086.9  497.80  5092.2  498.62  5108.2  497.50  5113.9  498.73  5130.0  498.08
  5135.7  499.29  5151.8  499.70  5177.9  498.88  5258.0  499.85  5394.2  503.62
#Mann=7,-1,0
  4405.3    0.05       0  4701.8    0.08       0  4972.8     0.1       0
  4985.9    0.07       0  4991.9     0.1       0  5004.9    0.08       0
  5086.9    0.05       0
Bank Sta=4985.9,4991.9
Exp/Cntr=0.3,0.1

Type RM Length L Ch R = 1,18808,95,95,95
BEGIN DESCRIPTION:
Mapping XS a16e2c52
END DESCRIPTION:
XS GIS Cut Line= 4
      2059054.26     13494799.37      2058843.30     13494874.89
      2058623.68     13494971.25      2058520.36     13495055.47
#Sta/Elev= 30
  4622.5  498.31  4774.5  496.91  4799.7  496.43  4823.5  496.26  4830.4  495.99
  4860.2  496.07  4877.5  495.74  4884.9  495.97  4889.0  495.87  4899.3  496.08
  4930.3  496.94  4959.1  496.55  4975.8  495.61  4982.5  494.26  5002.8  493.02
  5003.3  492.22  5008.3  492.22  5008.8  493.02  5029.2  494.46  5041.3  494.18
  5052.2  494.76  5063.5  494.90  5074.0  494.34  5085.7  494.90  5095.7  494.88
  5110.1  495.65  5130.9  495.78  5174.0  496.73  5215.4  498.00  5219.7  498.00
#Mann=6,-1,0
  4622.5    0.05       0  4774.5     0.1       0  4884.9    0.12       0
  5002.8    0.07       0  5008.8    0.12       0  5085.7    0.05       0
Bank Sta=5002.8,5008.8
Exp/Cntr=0.3,0.1

Type RM Length L Ch R = 1,18713,106,106,106
BEGIN DESCRIPTION:
Mapping XS 73744cd3
END DESCRIPTION:
XS GIS Cut Line= 5
      2059067.28     13494634.44      2058819.86     13494698.68
      2058730.45     13494806.32      2058501.29     13495012.92
      2058496.98     13495060.33
#Sta/Elev= 30
  4537.6  499.32  4612.3  498.54  4706.2  496.75  4746.6  496.12  4787.9  496.01
  4801.4  496.56  4808.3  496.39  4814.8  496.83  4841.4  497.14  4865.6  497.49
  4921.6  496.75  4942.9  496.99  4950.4  496.23  4957.1  496.72  4985.5  495.17
  4993.0  493.79  5004.2  492.89  5004.7  492.09  5009.7  492.09  5010.2  492.89
  5021.3  493.25  5028.1  494.10  5075.1  493.77  5081.1  493.57  5099.1  493.57
  5113.3  494.49  5141.7  495.52  5155.9  495.43  5239.5  497.85  5289.3  498.50
#Mann=7,-1,0
  4537.6    0.05       0  4706.2     0.1       0  4841.4    0.12       0
  5004.2    0.07       0  5010.2    0.12       0  5075.1     0.1       0
  5081.1    0.05       0
Bank Sta=5004.2,5010.2
Exp/Cntr=0.3,0.1

Type RM Length L Ch R = 1,18607,444,444,444
BEGIN DESCRIPTION:
Mapping XS f3958c12
END DESCRIPTION:
XS GIS Cut Line= 4
      2059036.92     13494560.65      2058805.11     13494610.14
      2058463.96     13494975.59      2058460.51     13495040.33
#Sta/Elev= 30
  4558.7  499.15  4605.1  498.78  4698.1  496.92  4806.2  495.34  4827.7  495.96
  4841.9  495.50  4868.0  492.92  4881.4  492.34  4881.9  491.54  4886.9  491.54
  4887.4  492.34  4905.4  492.89  4912.2  492.56  4919.6  493.06  4926.4  492.57
  4933.7  493.13  4940.6  492.70  4968.9  492.64  5018.7  492.89  5053.9  493.72
  5061.2  493.31  5085.0  493.52  5110.6  492.96  5117.4  493.45  5124.7  493.28
  5131.6  494.12  5171.2  495.26  5252.2  496.66  5315.1  498.36  5360.5  498.96
#Mann=7,-1,0
  4558.7    0.05       0  4698.1     0.1       0  4868.0    0.12       0
  4881.4    0.07       0  4887.4    0.12       0  5085.0     0.1       0
  5171.2    0.05       0
Bank Sta=4881.4,4887.4
Exp/Cntr=0.3,0.1

Type RM Length L Ch R = 1,18163,708,708,708
BEGIN DESCRIPTION:
Mapping XS 56fe8d1b
END DESCRIPTION:
XS GIS Cut Line= 4
      2058778.21     13494273.33      2058664.48     13494282.88
      2058265.18     13494543.30      2058276.46     13494627.49
#Sta/Elev= 30
  4658.0  497.71  4715.9  496.45  4774.8  495.15  4795.4  494.56  4808.4  493.78
  4838.6  493.02  4866.2  492.97  4874.8  492.53  4915.0  492.13  4938.7  492.16
  4962.4  492.59  4968.4  492.90  4983.5  492.41  4989.5  491.82  4995.4  490.07
  4995.9  489.27  5000.9  489.27  5001.4  490.07  5010.5  492.18  5025.7  492.43
  5034.2  492.07  5043.3  492.03  5092.1  492.32  5149.4  493.15  5185.6  493.26
  5227.8  493.96  5260.7  493.78  5280.5  494.06  5321.2  495.27  5333.8  495.10
#Mann=7,-1,0
  4658.0    0.05       0  4715.9     0.1       0  4866.2    0.12       0
  4915.0    0.07       0  4995.4    0.07       0  5001.4    0.07       0
  5043.3     0.1       0
Bank Sta=4995.4,5001.4
Exp/Cntr=0.3,0.1

Type RM Length L Ch R = 1,17455,513,513,513
BEGIN DESCRIPTION:
Mapping XS ff817376
END DESCRIPTION:
XS GIS Cut Line= 4
      2058716.24     13493803.68      2058419.39     13493791.53
      2057801.33     13494190.84      2057744.03     13494388.78
#Sta/Elev= 30
  4448.6  499.55  4536.8  497.42  4640.0  495.82  4700.1  493.78  4751.3  493.31
  4788.7  492.20  4810.8  491.76  4889.1  489.98  4930.2  489.77  4967.6  489.13
  4982.8  489.36  4989.0  489.18  5000.9  488.06  5001.4  487.26  5006.4  487.26
  5006.9  488.06  5012.8  489.28  5025.0  489.93  5034.2  489.75  5055.3  488.11
  5097.6  489.33  5156.7  489.83  5286.7  490.52  5393.8  491.82  5445.3  492.86
  5537.9  493.79  5569.1  494.64  5610.8  494.66  5628.3  495.19  5687.6  495.63
#Mann=7,-1,0
  4448.6    0.05       0  4788.7     0.1       0  4810.8    0.16       0
  4930.2     0.1       0  5000.9    0.07       0  5006.9     0.1       0
  5156.7    0.05       0
Bank Sta=5000.9,5006.9
Exp/Cntr=0.3,0.1