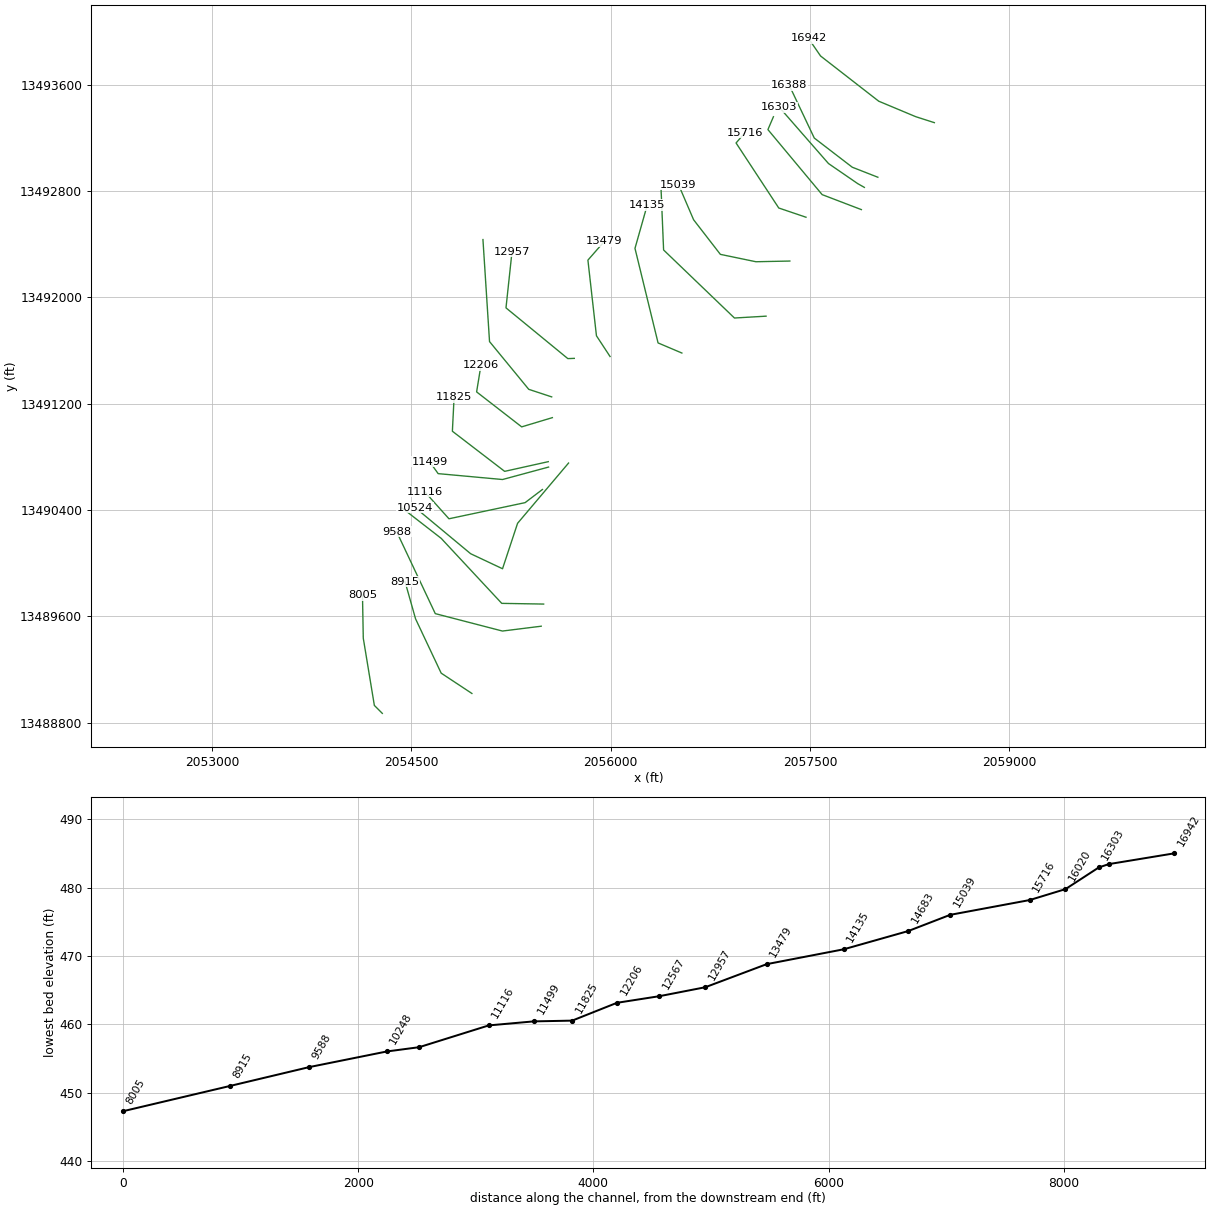
HEC-RAS study UNT 150 in Lagunillas Cr Wtrshd.prj: UNT 150 in Lagunillas Cr Wtrshd Base Level Engineering

--- UNT 150 in Lagunillas Cr Wtrshd.g01 (geometry) --- (continued)

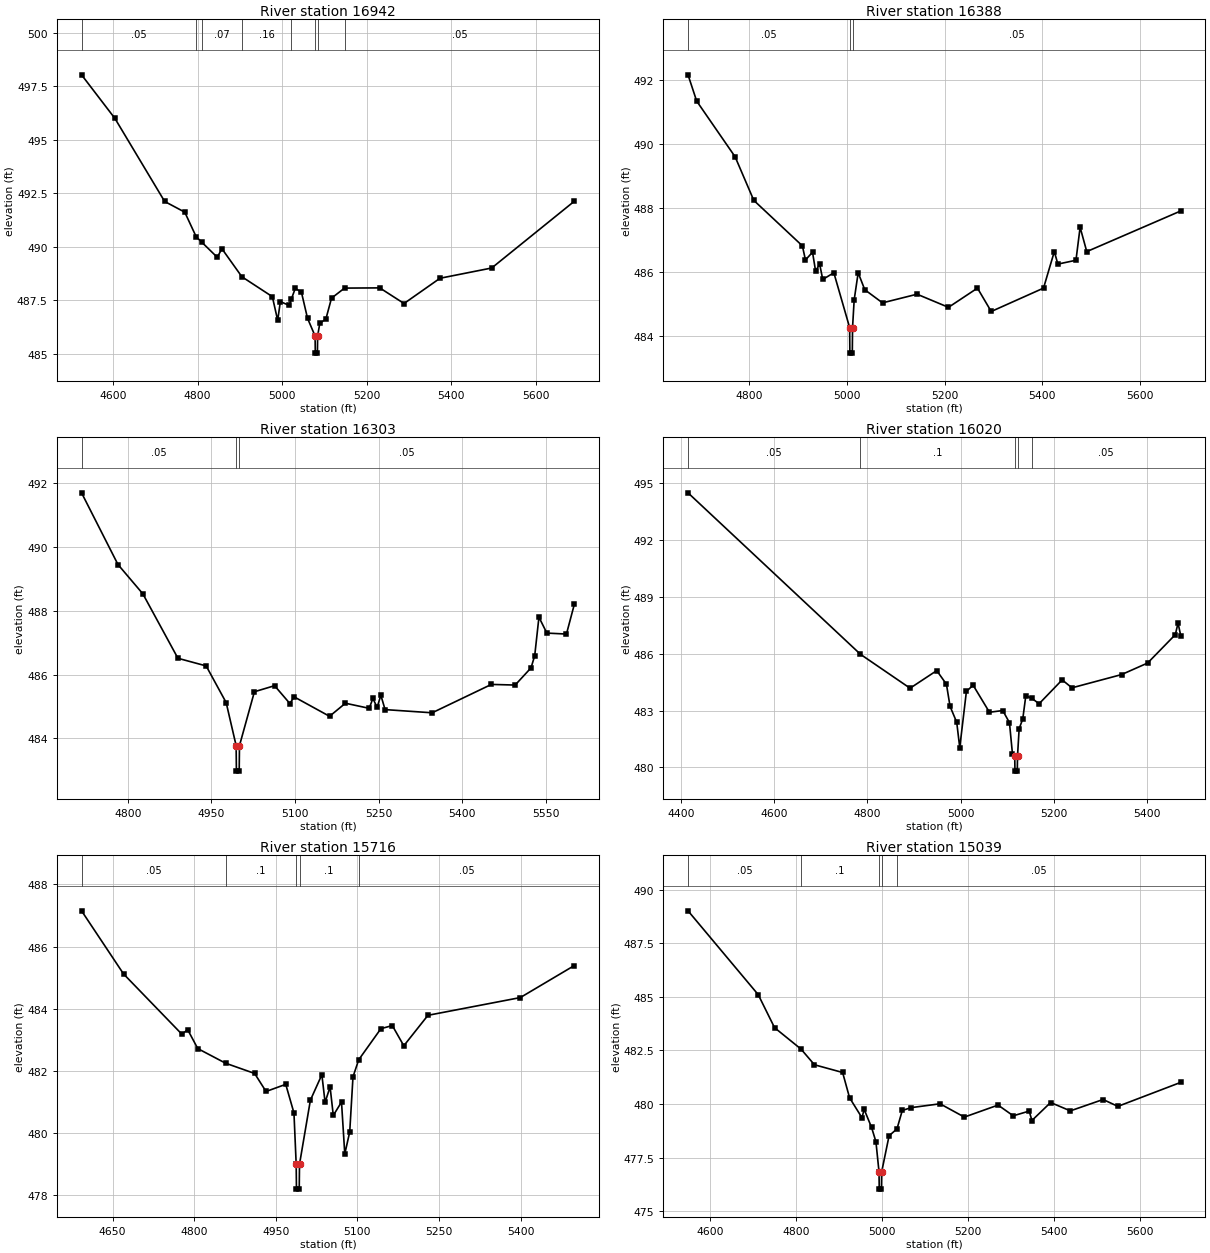
Type RM Length L Ch R = 1,16942,554,554,554
BEGIN DESCRIPTION:
Mapping XS 0fd14964
END DESCRIPTION:
XS GIS Cut Line= 5
      2058435.34     13493315.98      2058294.72     13493361.12
      2058016.95     13493477.44      2057579.45     13493817.72
      2057487.93     13493950.68
#Sta/Elev= 30
  4525.9  498.04  4604.8  496.00  4722.3  492.12  4769.8  491.62  4796.8  490.47
  4809.8  490.22  4846.6  489.51  4857.6  489.91  4904.8  488.60  4976.8  487.67
  4989.4  486.56  4995.7  487.44  5016.5  487.26  5022.0  487.57  5031.0  488.06
  5045.5  487.88  5059.9  486.66  5077.8  485.83  5078.3  485.03  5083.3  485.03
  5083.8  485.83  5088.9  486.42  5103.4  486.63  5116.6  487.60  5147.4  488.07
  5230.6  488.08  5288.0  487.35  5373.0  488.53  5495.2  489.01  5690.4  492.13
#Mann=8,-1,0
  4525.9    0.05       0  4796.8     0.1       0  4809.8    0.07       0
  4904.8    0.16       0  5022.0     0.1       0  5077.8    0.07       0
  5083.8     0.1       0  5147.4    0.05       0
Bank Sta=5077.8,5083.8
Exp/Cntr=0.3,0.1

Type RM Length L Ch R = 1,16388,85,85,85
BEGIN DESCRIPTION:
Mapping XS d0130611
END DESCRIPTION:
XS GIS Cut Line= 4
      2058010.31     13492905.03      2057817.65     13492980.54
      2057532.06     13493200.16      2057343.01     13493598.80
#Sta/Elev= 30
  4675.0  492.15  4692.7  491.33  4771.4  489.59  4809.6  488.23  4909.0  486.81
  4915.3  486.37  4929.8  486.61  4936.1  486.02  4944.4  486.24  4950.7  485.76
  4973.4  485.97  5005.7  484.26  5006.2  483.46  5011.2  483.46  5011.7  484.26
  5015.0  485.12  5023.2  485.97  5036.7  485.44  5073.0  485.03  5143.7  485.30
  5208.0  484.89  5267.3  485.49  5295.5  484.76  5402.5  485.49  5424.6  486.63
  5431.9  486.24  5468.9  486.36  5477.4  487.39  5491.0  486.63  5683.4  487.90
#Mann=3,-1,0
  4675.0    0.05       0  5005.7    0.04       0  5011.7    0.05       0
Bank Sta=5005.7,5011.7
Exp/Cntr=0.3,0.1

Type RM Length L Ch R = 1,16303,283,283,283
BEGIN DESCRIPTION:
Mapping XS ddce4fbe
END DESCRIPTION:
XS GIS Cut Line= 4
      2057908.76     13492828.65      2057858.45     13492857.27
      2057638.83     13493008.31      2057270.29     13493430.18
#Sta/Elev= 30
  4716.9  491.70  4782.3  489.45  4827.0  488.53  4889.9  486.51  4940.6  486.27
  4976.5  485.12  4994.4  483.77  4994.9  482.97  4999.9  482.97  5000.4  483.77
  5027.2  485.46  5063.4  485.65  5090.9  485.09  5098.5  485.30  5162.1  484.69
  5190.6  485.10  5233.3  484.94  5239.9  485.25  5247.5  484.97  5254.2  485.35
  5261.8  484.90  5346.3  484.80  5452.6  485.69  5495.3  485.67  5523.8  486.21
  5530.4  486.59  5538.0  487.80  5552.2  487.30  5587.4  487.27  5601.5  488.20
#Mann=3,-1,0
  4716.9    0.05       0  4994.4    0.04       0  5000.4    0.05       0
Bank Sta=4994.4,5000.4
Exp/Cntr=0.3,0.1

Type RM Length L Ch R = 1,16020,304,304,304
BEGIN DESCRIPTION:
Mapping XS 44335255
END DESCRIPTION:
XS GIS Cut Line= 4
      2057886.42     13492661.32      2057591.26     13492774.17
      2057183.27     13493263.75      2057224.72     13493360.46
#Sta/Elev= 30
  4414.6  494.50  4785.1  485.97  4891.6  484.18  4948.9  485.11  4969.7  484.39
  4977.5  483.22  4991.8  482.38  4998.3  481.04  5012.6  484.01  5027.0  484.34
  5062.1  482.91  5090.7  483.00  5105.1  482.36  5111.6  480.69  5116.4  480.60
  5116.9  479.80  5121.9  479.80  5122.4  480.60  5125.9  482.04  5133.7  482.56
  5140.2  483.78  5152.8  483.65  5168.8  483.36  5218.3  484.62  5239.3  484.20
  5345.9  484.90  5401.9  485.51  5461.4  487.01  5467.2  487.62  5473.1  486.95
#Mann=5,-1,0
  4414.6    0.05       0  4785.1     0.1       0  5116.4    0.07       0
  5122.4     0.1       0  5152.8    0.05       0
Bank Sta=5116.4,5122.4
Exp/Cntr=0.3,0.1

Type RM Length L Ch R = 1,15716,677,677,677
BEGIN DESCRIPTION:
Mapping XS 11522d98
END DESCRIPTION:
XS GIS Cut Line= 4
      2057469.72     13492604.04      2057264.87     13492673.48
      2056943.69     13493163.06      2057011.85     13493241.44
#Sta/Elev= 30
  4593.1  487.15  4670.3  485.12  4777.6  483.18  4788.1  483.33  4806.7  482.72
  4857.8  482.25  4911.2  481.92  4932.2  481.34  4968.4  481.57  4983.5  480.65
  4987.6  479.00  4988.1  478.20  4993.2  478.20  4993.7  479.00  5013.7  481.06
  5034.8  481.88  5040.7  480.99  5049.9  481.49  5055.8  480.57  5070.9  481.00
  5076.9  479.33  5086.0  480.04  5092.0  481.81  5102.5  482.36  5143.3  483.36
  5164.3  483.46  5185.4  482.81  5229.8  483.79  5399.5  484.36  5498.8  485.39
#Mann=5,-1,0
  4593.1    0.05       0  4857.8     0.1       0  4987.6    0.07       0
  4993.7     0.1       0  5102.5    0.05       0
Bank Sta=4987.6,4993.7
Exp/Cntr=0.3,0.1

Type RM Length L Ch R = 1,15039,356,356,356
BEGIN DESCRIPTION:
Mapping XS 338aef0f
END DESCRIPTION:
XS GIS Cut Line= 5
      2057348.24     13492274.17      2057093.00     13492268.96
      2056825.64     13492324.52      2056624.25     13492584.93
      2056510.47     13492850.19
#Sta/Elev= 30
  4548.4  489.01  4711.7  485.10  4749.7  483.56  4811.3  482.56  4842.5  481.83
  4908.0  481.47  4924.2  480.29  4953.0  479.36  4958.1  479.75  4975.3  478.91
  4985.5  478.24  4992.7  476.83  4993.2  476.03  4998.3  476.03  4998.8  476.83
  5016.1  478.52  5034.5  478.84  5046.8  479.70  5067.2  479.83  5134.6  480.01
  5191.2  479.39  5269.6  479.95  5304.9  479.45  5342.0  479.67  5348.3  479.23
  5391.8  480.07  5437.7  479.68  5513.8  480.21  5548.3  479.89  5694.6  481.01
#Mann=5,-1,0
  4548.4    0.05       0  4811.3     0.1       0  4992.7    0.07       0
  4998.8     0.1       0  5034.5    0.05       0
Bank Sta=4992.7,4998.8
Exp/Cntr=0.3,0.1

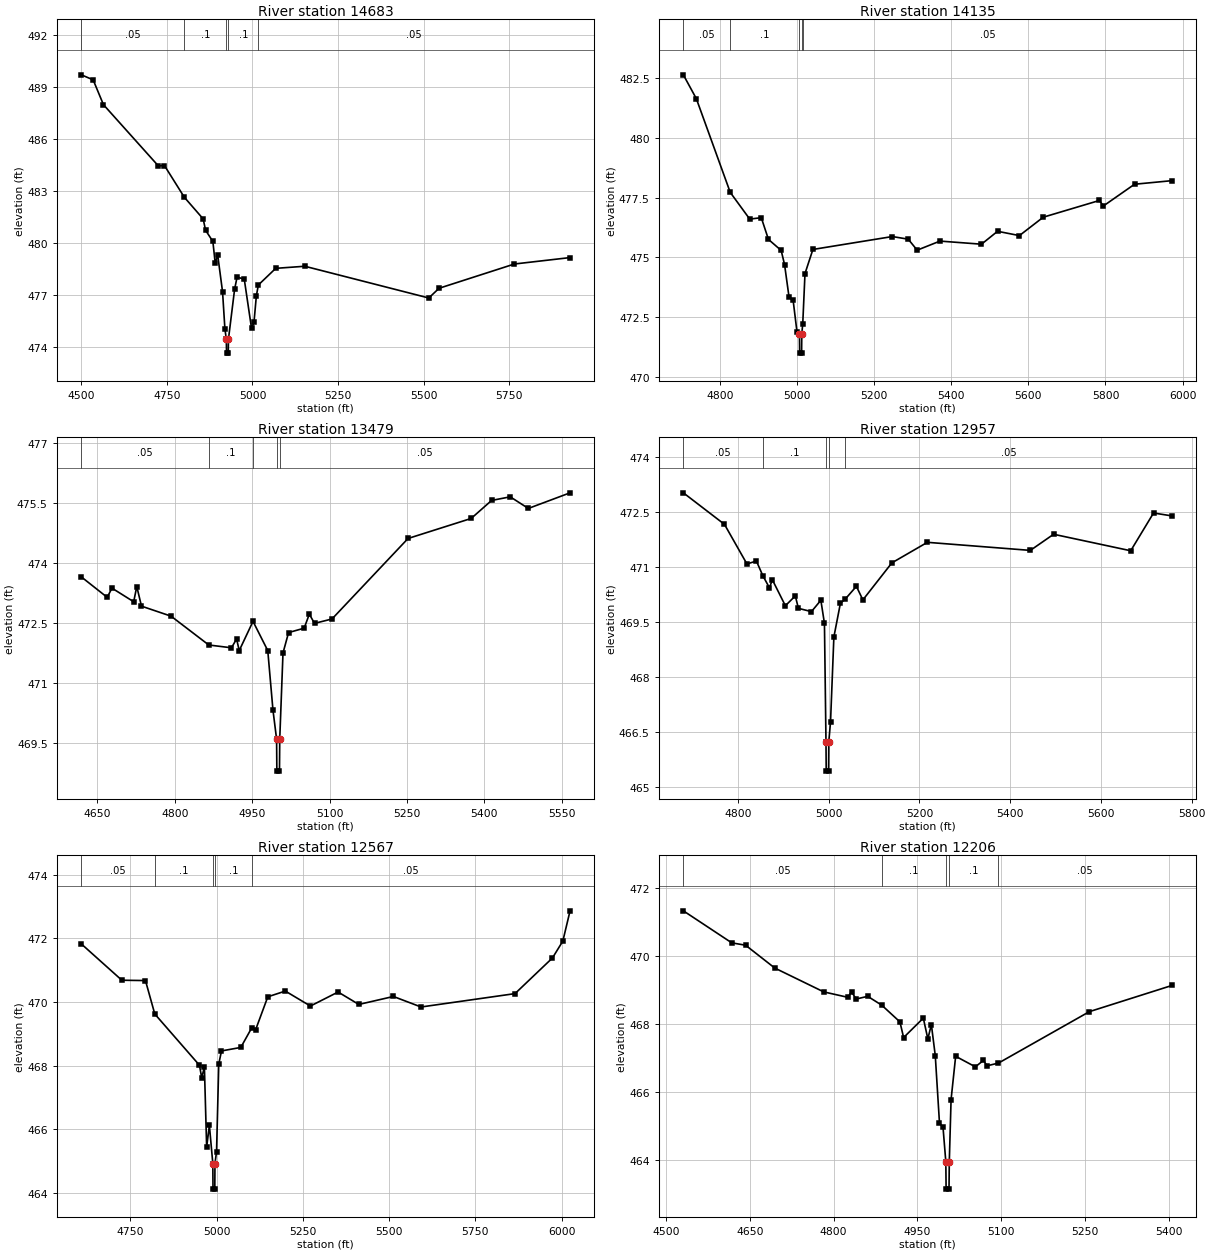
Type RM Length L Ch R = 1,14683,548,548,548
BEGIN DESCRIPTION:
Mapping XS 6b7a9857
END DESCRIPTION:
XS GIS Cut Line= 4
      2057169.40     13491859.24      2056931.54     13491845.35
      2056398.55     13492357.50      2056379.81     13492807.37
#Sta/Elev= 30
  4500.1  489.71  4534.6  489.42  4564.6  487.99  4724.9  484.46  4742.8  484.48
  4800.9  482.65  4856.0  481.40  4862.9  480.75  4884.3  480.10  4891.2  478.84
  4898.4  479.32  4912.6  477.20  4919.5  475.05  4923.7  474.46  4924.2  473.66
  4929.3  473.66  4929.8  474.46  4947.8  477.34  4955.1  478.05  4976.1  477.92
  4997.2  475.10  5004.4  475.43  5011.4  476.97  5017.2  477.59  5068.0  478.55
  5152.9  478.67  5515.1  476.84  5545.1  477.40  5765.3  478.80  5927.8  479.17
#Mann=5,-1,0
  4500.1    0.05       0  4800.9     0.1       0  4923.7    0.07       0
  4929.8     0.1       0  5017.2    0.05       0
Bank Sta=4923.7,4929.8
Exp/Cntr=0.3,0.1

Type RM Length L Ch R = 1,14135,656,656,656
BEGIN DESCRIPTION:
Mapping XS 3f04699a
END DESCRIPTION:
XS GIS Cut Line= 4
      2056536.06     13491581.72      2056356.89     13491657.85
      2056183.27     13492369.66      2056275.64     13492696.30
#Sta/Elev= 30
  4705.8  482.64  4739.5  481.64  4827.3  477.72  4877.9  476.60  4907.8  476.66
  4926.4  475.75  4959.3  475.29  4968.1  474.70  4979.9  473.32  4990.2  473.22
  5000.5  471.86  5006.7  471.79  5007.2  470.99  5012.3  470.99  5012.8  471.79
  5015.3  472.22  5021.1  474.32  5041.6  475.33  5247.5  475.87  5288.7  475.76
  5311.9  475.30  5371.0  475.68  5478.6  475.55  5520.3  476.09  5576.9  475.91
  5638.7  476.68  5784.2  477.38  5794.6  477.15  5875.4  478.06  5972.6  478.21
#Mann=5,-1,0
  4705.8    0.05       0  4827.3     0.1       0  5006.7    0.07       0
  5012.8     0.1       0  5015.3    0.05       0
Bank Sta=5006.7,5012.8
Exp/Cntr=0.3,0.1

Type RM Length L Ch R = 1,13479,522,522,522
BEGIN DESCRIPTION:
Mapping XS 293ef07d
END DESCRIPTION:
XS GIS Cut Line= 4
      2055995.76     13491555.44      2055893.34     13491711.67
      2055829.11     13492281.11      2055952.39     13492421.76
#Sta/Elev= 30
  4619.1  473.66  4669.2  473.15  4678.4  473.38  4720.5  473.04  4726.5  473.42
  4735.6  472.93  4792.9  472.68  4866.0  471.96  4909.9  471.89  4919.9  472.11
  4925.0  471.82  4951.7  472.55  4980.3  471.82  4990.4  470.33  4997.4  469.61
  4997.9  468.81  5003.0  468.81  5003.5  469.61  5009.8  471.76  5020.6  472.27
  5050.8  472.38  5060.8  472.73  5070.9  472.50  5104.8  472.61  5252.1  474.62
  5374.4  475.12  5414.0  475.57  5450.1  475.66  5485.2  475.37  5566.0  475.76
#Mann=5,-1,0
  4619.1    0.05       0  4866.0     0.1       0  4951.7    0.05       0
  4997.4    0.03       0  5003.5    0.05       0
Bank Sta=4997.4,5003.5
Exp/Cntr=0.3,0.1

Type RM Length L Ch R = 1,12957,390,390,390
BEGIN DESCRIPTION:
Mapping XS 1ab423ce
END DESCRIPTION:
XS GIS Cut Line= 4
      2055726.71     13491541.53      2055678.07     13491539.79
      2055212.79     13491921.74      2055258.27     13492345.56
#Sta/Elev= 30
  4679.9  473.02  4770.5  472.16  4820.0  471.08  4840.9  471.16  4855.0  470.76
  4869.6  470.43  4876.0  470.65  4904.7  469.94  4926.6  470.21  4933.4  469.87
  4962.1  469.78  4982.9  470.09  4990.8  469.46  4994.2  466.23  4994.7  465.43
  4999.9  465.43  5000.4  466.23  5004.2  466.77  5011.6  469.09  5026.0  470.01
  5036.5  470.12  5061.2  470.47  5075.5  470.10  5139.4  471.11  5217.6  471.67
  5444.5  471.45  5495.8  471.89  5665.7  471.44  5716.0  472.47  5756.8  472.39
#Mann=5,-1,0
  4679.9    0.05       0  4855.0     0.1       0  4994.2    0.07       0
  5000.4     0.1       0  5036.5    0.05       0
Bank Sta=4994.2,5000.4
Exp/Cntr=0.3,0.1

Type RM Length L Ch R = 1,12567,361,361,361
BEGIN DESCRIPTION:
Mapping XS 358ccd23
END DESCRIPTION:
XS GIS Cut Line= 4
      2055556.58     13491251.59      2055384.06     13491308.52
      2055089.02     13491667.92      2055039.53     13492435.86
#Sta/Elev= 30
  4608.3  471.82  4725.7  470.68  4794.1  470.67  4821.1  469.62  4950.6  468.01
  4957.0  467.62  4964.9  467.95  4971.4  465.44  4979.3  466.12  4989.3  464.92
  4989.8  464.12  4995.0  464.12  4995.5  464.92  5000.1  465.30  5006.5  468.05
  5014.4  468.46  5070.4  468.57  5102.3  469.19  5113.5  469.13  5148.6  470.16
  5199.4  470.34  5272.1  469.87  5352.3  470.31  5412.4  469.92  5512.6  470.17
  5592.7  469.84  5865.0  470.26  5973.5  471.38  6003.6  471.91  6024.5  472.86
#Mann=5,-1,0
  4608.3    0.05       0  4821.1     0.1       0  4989.3    0.07       0
  4995.5     0.1       0  5102.3    0.05       0
Bank Sta=4989.3,4995.5
Exp/Cntr=0.3,0.1

Type RM Length L Ch R = 1,12206,381,381,381
BEGIN DESCRIPTION:
Double Mapping XS 6790c630
END DESCRIPTION:
XS GIS Cut Line= 4
      2055561.78     13491095.36      2055330.84     13491025.91
      2054991.83     13491289.14      2055024.81     13491491.20
#Sta/Elev= 30
  4530.9  471.32  4617.6  470.38  4642.4  470.31  4694.6  469.64  4782.3  468.94
  4825.7  468.78  4832.0  468.95  4840.2  468.73  4861.0  468.81  4886.2  468.55
  4918.7  468.06  4925.3  467.60  4960.6  468.17  4968.7  467.56  4975.0  467.98
  4982.0  467.07  4989.5  465.10  4995.9  464.96  5000.9  463.95  5001.4  463.15
  5006.6  463.15  5007.1  463.95  5010.3  465.78  5018.5  467.05  5053.8  466.74
  5068.3  466.93  5074.6  466.77  5095.1  466.85  5257.9  468.36  5406.0  469.13
#Mann=5,-1,0
  4530.9    0.05       0  4886.2     0.1       0  5000.9    0.07       0
  5007.1     0.1       0  5095.1    0.05       0
Bank Sta=5000.9,5007.1
Exp/Cntr=0.3,0.1

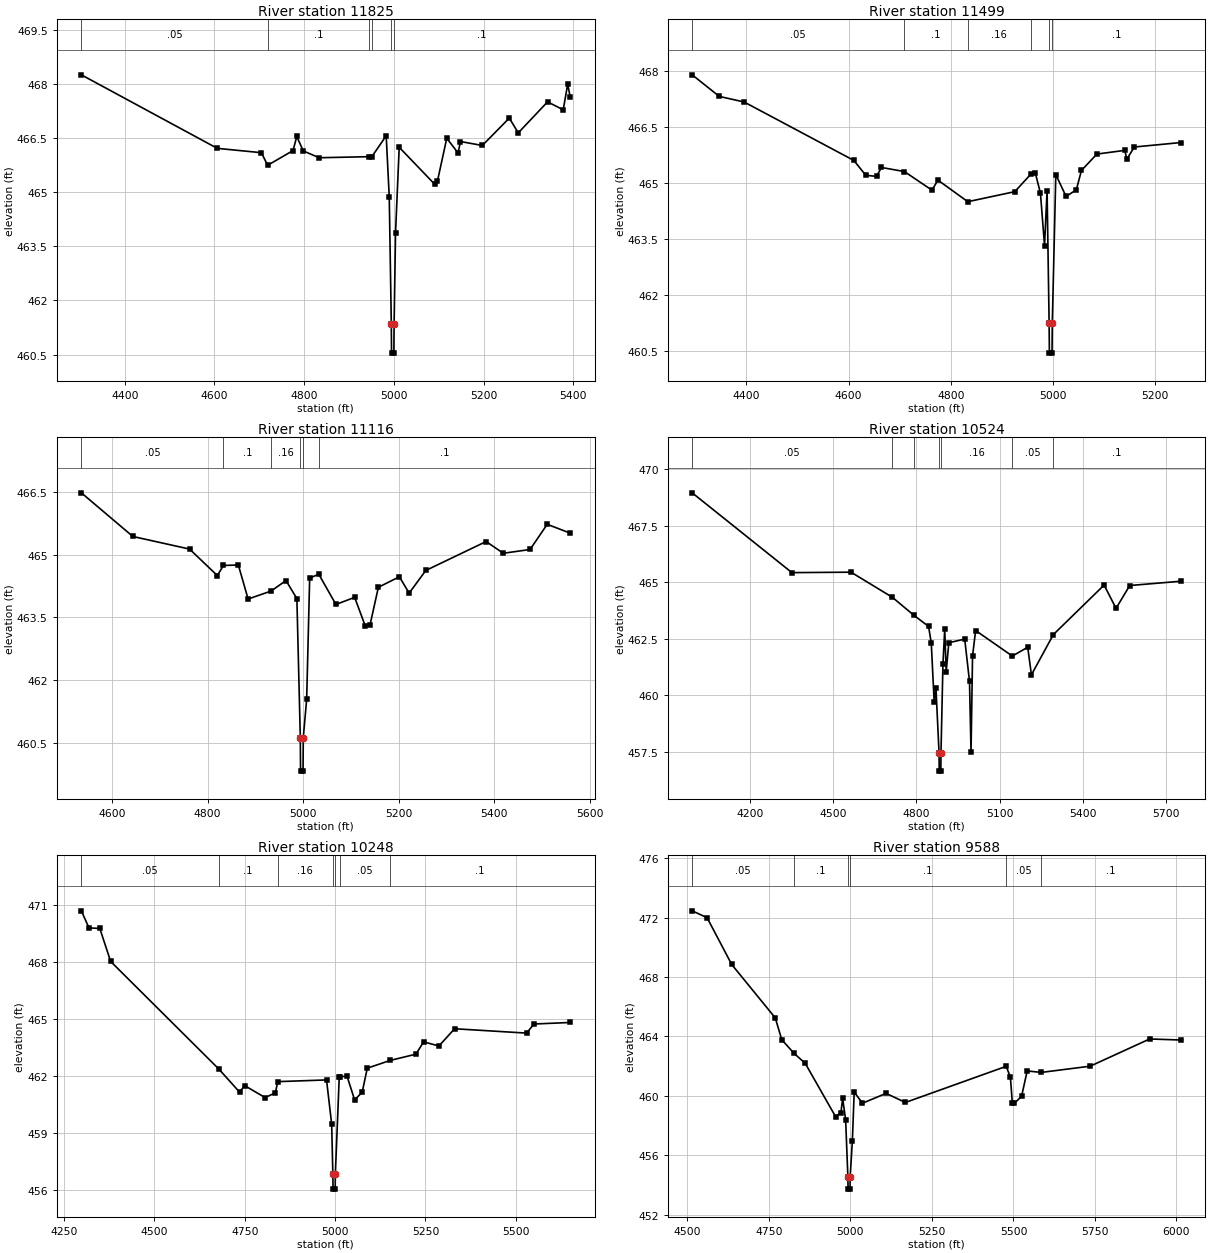
Type RM Length L Ch R = 1,11825,326,326,326
BEGIN DESCRIPTION:
Double Mapping XS 2d16e75a
END DESCRIPTION:
XS GIS Cut Line= 4
      2055530.89     13490763.96      2055202.77     13490691.04
      2054809.54     13490993.13      2054822.54     13491250.51
#Sta/Elev= 30
  4303.4  468.26  4606.5  466.22  4704.8  466.10  4718.6  465.75  4775.4  466.16
  4783.6  466.55  4798.1  466.15  4833.5  465.96  4945.7  465.99  4950.5  465.98
  4983.0  466.57  4989.8  464.87  4994.4  461.34  4994.9  460.54  5000.1  460.54
  5000.6  461.34  5003.8  463.88  5012.0  466.25  5090.7  465.23  5097.2  465.31
  5118.0  466.50  5143.4  466.09  5148.4  466.41  5197.3  466.30  5257.4  467.06
  5277.4  466.65  5342.7  467.51  5377.6  467.29  5387.6  468.00  5393.1  467.65
#Mann=6,-1,0
  4303.4    0.05       0  4718.6     0.1       0  4945.7    0.16       0
  4950.5     0.1       0  4994.4    0.07       0  5000.6     0.1       0
Bank Sta=4994.4,5000.6
Exp/Cntr=0.3,0.1

Type RM Length L Ch R = 1,11499,383,383,383
BEGIN DESCRIPTION:
Mapping XS 0fbfdbc7
END DESCRIPTION:
XS GIS Cut Line= 4
      2055533.19     13490723.33      2055186.88     13490629.59
      2054702.51     13490673.86      2054637.39     13490765.02
#Sta/Elev= 30
  4293.7  467.91  4346.8  467.33  4395.4  467.18  4610.2  465.61  4633.7  465.21
  4654.7  465.18  4664.4  465.42  4709.3  465.31  4763.3  464.81  4774.9  465.08
  4833.5  464.50  4925.5  464.77  4956.9  465.24  4965.7  465.27  4975.7  464.73
  4983.7  463.32  4988.7  464.80  4992.7  461.23  4993.2  460.43  4998.4  460.43
  4998.9  461.23  5005.8  465.23  5025.9  464.64  5046.0  464.82  5056.0  465.34
  5086.2  465.78  5141.0  465.88  5144.8  465.64  5159.5  465.97  5250.9  466.09
#Mann=6,-1,0
  4293.7    0.05       0  4709.3     0.1       0  4833.5    0.16       0
  4956.9     0.1       0  4992.7    0.07       0  4998.9     0.1       0
Bank Sta=4992.7,4998.9
Exp/Cntr=0.3,0.1

Type RM Length L Ch R = 1,11116,592,592,592
BEGIN DESCRIPTION:
Double Mapping XS bf95e1d5
END DESCRIPTION:
XS GIS Cut Line= 4
      2055486.94     13490554.54      2055356.71     13490455.57
      2054783.80     13490334.04      2054600.57     13490538.80
#Sta/Elev= 30
  4535.4  466.47  4643.3  465.43  4762.1  465.13  4820.2  464.50  4833.1  464.74
  4864.3  464.75  4884.7  463.94  4932.9  464.13  4964.1  464.38  4986.9  463.95
  4994.1  460.64  4994.6  459.84  4999.8  459.84  5000.3  460.64  5007.4  461.55
  5013.7  464.44  5032.8  464.53  5068.7  463.81  5107.9  463.98  5130.1  463.30
  5140.3  463.33  5157.6  464.22  5201.6  464.47  5222.1  464.08  5256.9  464.62
  5383.4  465.31  5419.3  465.03  5475.4  465.12  5511.3  465.72  5559.4  465.51
#Mann=6,-1,0
  4535.4    0.05       0  4833.1     0.1       0  4932.9    0.16       0
  4994.1    0.07       0  5000.3    0.16       0  5032.8     0.1       0
Bank Sta=4994.1,5000.3
Exp/Cntr=0.3,0.1

Type RM Length L Ch R = 1,10524,276,276,276
BEGIN DESCRIPTION:
Mapping XS 69e4094a
END DESCRIPTION:
XS GIS Cut Line= 5
      2055683.48     13490753.57      2055300.00     13490300.00
      2055186.80     13489957.94      2054947.00     13490071.00
      2054528.77     13490418.92
#Sta/Elev= 30
  3991.2  468.96  4351.1  465.43  4564.3  465.45  4713.3  464.34  4790.5  463.55
  4844.1  463.05  4853.8  462.31  4864.3  459.69  4870.6  460.34  4881.9  457.45
  4882.4  456.65  4888.3  456.65  4888.8  457.45  4895.9  461.39  4902.3  462.92
  4907.6  461.04  4917.0  462.33  4974.4  462.49  4991.7  460.62  4997.2  457.51
  5002.7  461.75  5013.8  462.87  5146.2  461.74  5201.7  462.13  5215.1  460.91
  5294.2  462.69  5477.3  464.88  5520.3  463.85  5569.8  464.86  5754.6  465.05
#Mann=7,-1,0
  3991.2    0.05       0  4713.3     0.1       0  4790.5    0.16       0
  4881.9    0.07       0  4888.8    0.16       0  5146.2    0.05       0
  5294.2     0.1       0
Bank Sta=4881.9,4888.8
Exp/Cntr=0.3,0.1

Type RM Length L Ch R = 1,10248,660,660,660
BEGIN DESCRIPTION:
Mapping XS 48e93cdf
END DESCRIPTION:
XS GIS Cut Line= 4
      2055496.06     13489692.04      2055180.96     13489697.25
      2054725.23     13490186.83      2054433.59     13490413.37
#Sta/Elev= 30
  4297.5  470.70  4318.6  469.80  4348.6  469.77  4378.6  468.03  4677.3  462.37
  4735.4  461.14  4749.6  461.48  4806.3  460.85  4834.6  461.10  4841.3  461.69
  4976.3  461.78  4990.5  459.45  4993.8  456.82  4994.3  456.02  5000.2  456.02
  5000.7  456.82  5011.5  461.94  5013.6  461.95  5033.0  461.98  5054.0  460.73
  5075.0  461.13  5089.1  462.40  5152.8  462.81  5224.0  463.14  5245.0  463.79
  5287.4  463.57  5330.9  464.48  5530.0  464.25  5550.8  464.73  5650.8  464.81
#Mann=7,-1,0
  4297.5    0.05       0  4677.3     0.1       0  4841.3    0.16       0
  4993.8    0.07       0  5000.7    0.16       0  5013.6    0.05       0
  5152.8     0.1       0
Bank Sta=4993.8,5000.7
Exp/Cntr=0.3,0.1

Type RM Length L Ch R = 1,9588,673,673,673
BEGIN DESCRIPTION:
Mapping XS 3f1b43d1
END DESCRIPTION:
XS GIS Cut Line= 4
      2055477.79     13489525.36      2055186.17     13489488.91
      2054680.92     13489620.05      2054389.64     13490238.18
#Sta/Elev= 30
  4514.6  472.45  4560.3  471.99  4635.9  468.84  4769.4  465.25  4789.5  463.78
  4826.7  462.87  4861.4  462.19  4954.3  458.61  4970.9  458.88  4976.1  459.83
  4985.3  458.39  4992.2  454.53  4992.7  453.73  4998.6  453.73  4999.1  454.53
  5006.0  457.00  5011.5  460.26  5037.0  459.51  5109.3  460.17  5168.6  459.56
  5477.8  461.99  5490.7  461.25  5496.5  459.54  5502.1  459.49  5524.9  459.97
  5542.1  461.68  5585.2  461.58  5735.4  462.00  5917.7  463.83  6013.8  463.76
#Mann=6,-1,0
  4514.6    0.05       0  4826.7     0.1       0  4992.2    0.07       0
  4999.1     0.1       0  5477.8    0.05       0  5585.2     0.1       0
Bank Sta=4992.2,4999.1
Exp/Cntr=0.3,0.1

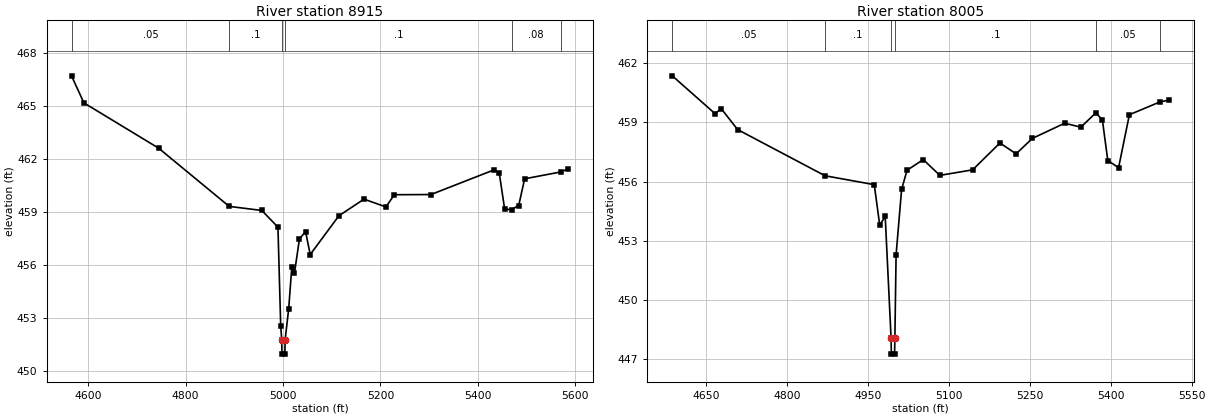
Type RM Length L Ch R = 1,8915,910,910,910
BEGIN DESCRIPTION:
Mapping XS b1b4b2e6
END DESCRIPTION:
XS GIS Cut Line= 4
      2054956.23     13489019.20      2054725.19     13489172.13
      2054532.48     13489580.98      2054453.13     13489861.52
#Sta/Elev= 30
  4565.5  466.70  4591.0  465.17  4744.5  462.61  4889.4  459.32  4956.3  459.09
  4989.5  458.15  4995.2  452.56  4997.3  451.77  4997.8  450.97  5003.7  450.97
  5004.2  451.77  5011.6  453.54  5018.0  455.91  5023.5  455.56  5033.7  457.49
  5046.3  457.89  5055.8  456.60  5114.7  458.79  5166.3  459.73  5211.3  459.29
  5228.6  459.98  5303.8  459.99  5433.8  461.39  5444.2  461.18  5455.2  459.16
  5469.3  459.14  5484.0  459.37  5496.2  460.88  5570.9  461.27  5586.1  461.45
#Mann=6,-1,0
  4565.5    0.05       0  4889.4     0.1       0  4997.3    0.07       0
  5004.2     0.1       0  5469.3    0.08       0  5570.9     0.1       0
Bank Sta=4997.3,5004.2
Exp/Cntr=0.3,0.1

Type RM Length L Ch R = 1,8005,575,575,575
BEGIN DESCRIPTION:
Mapping XS 83eca214
END DESCRIPTION:
XS GIS Cut Line= 4
      2054282.50     13488869.17      2054222.59     13488929.07
      2054139.25     13489435.15      2054133.28     13489758.78
#Sta/Elev= 30
  4587.0  461.36  4666.5  459.44  4677.7  459.70  4708.1  458.64  4870.3  456.30
  4961.5  455.85  4971.6  453.80  4981.8  454.24  4992.7  448.07  4993.2  447.27
  4999.2  447.27  4999.7  448.07  5002.0  452.31  5012.2  455.61  5022.3  456.58
  5052.3  457.12  5083.1  456.32  5143.9  456.60  5194.5  457.96  5224.5  457.41
  5254.5  458.19  5314.5  458.96  5344.5  458.76  5372.5  459.49  5384.5  459.12
  5394.5  457.07  5414.5  456.71  5434.5  459.39  5491.2  460.04  5508.3  460.13
#Mann=6,-1,0
  4587.0    0.05       0  4870.3     0.1       0  4992.7    0.07       0
  4999.7     0.1       0  5372.5    0.05       0  5491.2     0.1       0
Bank Sta=4992.7,4999.7
Exp/Cntr=0.3,0.1