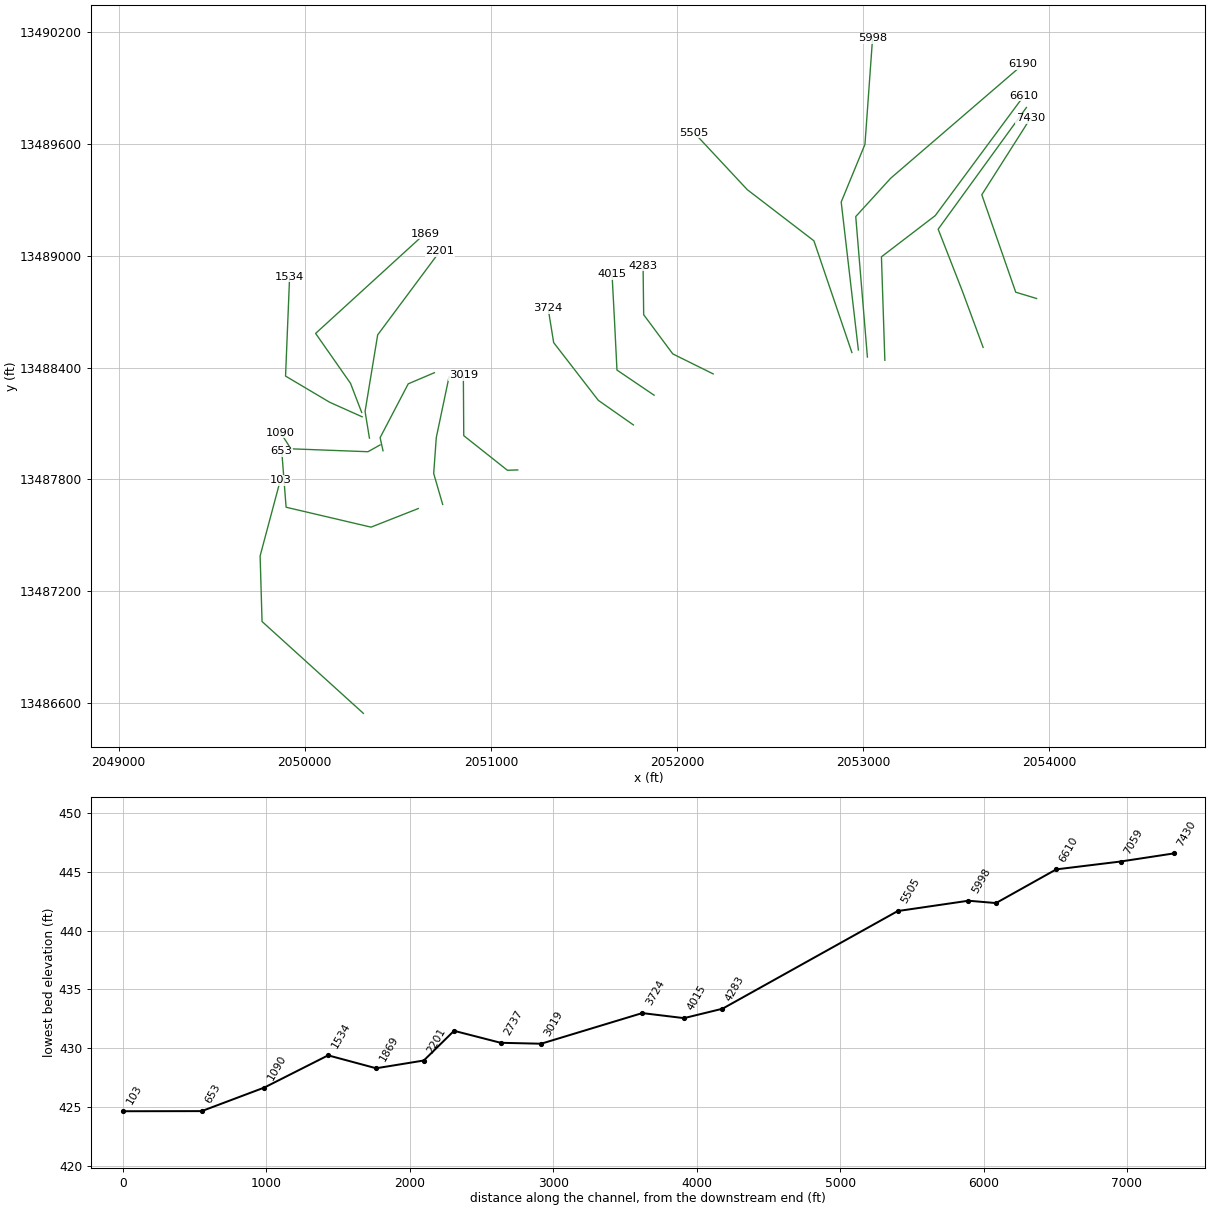
HEC-RAS study UNT 150 in Lagunillas Cr Wtrshd.prj: UNT 150 in Lagunillas Cr Wtrshd Base Level Engineering

--- UNT 150 in Lagunillas Cr Wtrshd.g01 (geometry) --- (continued)

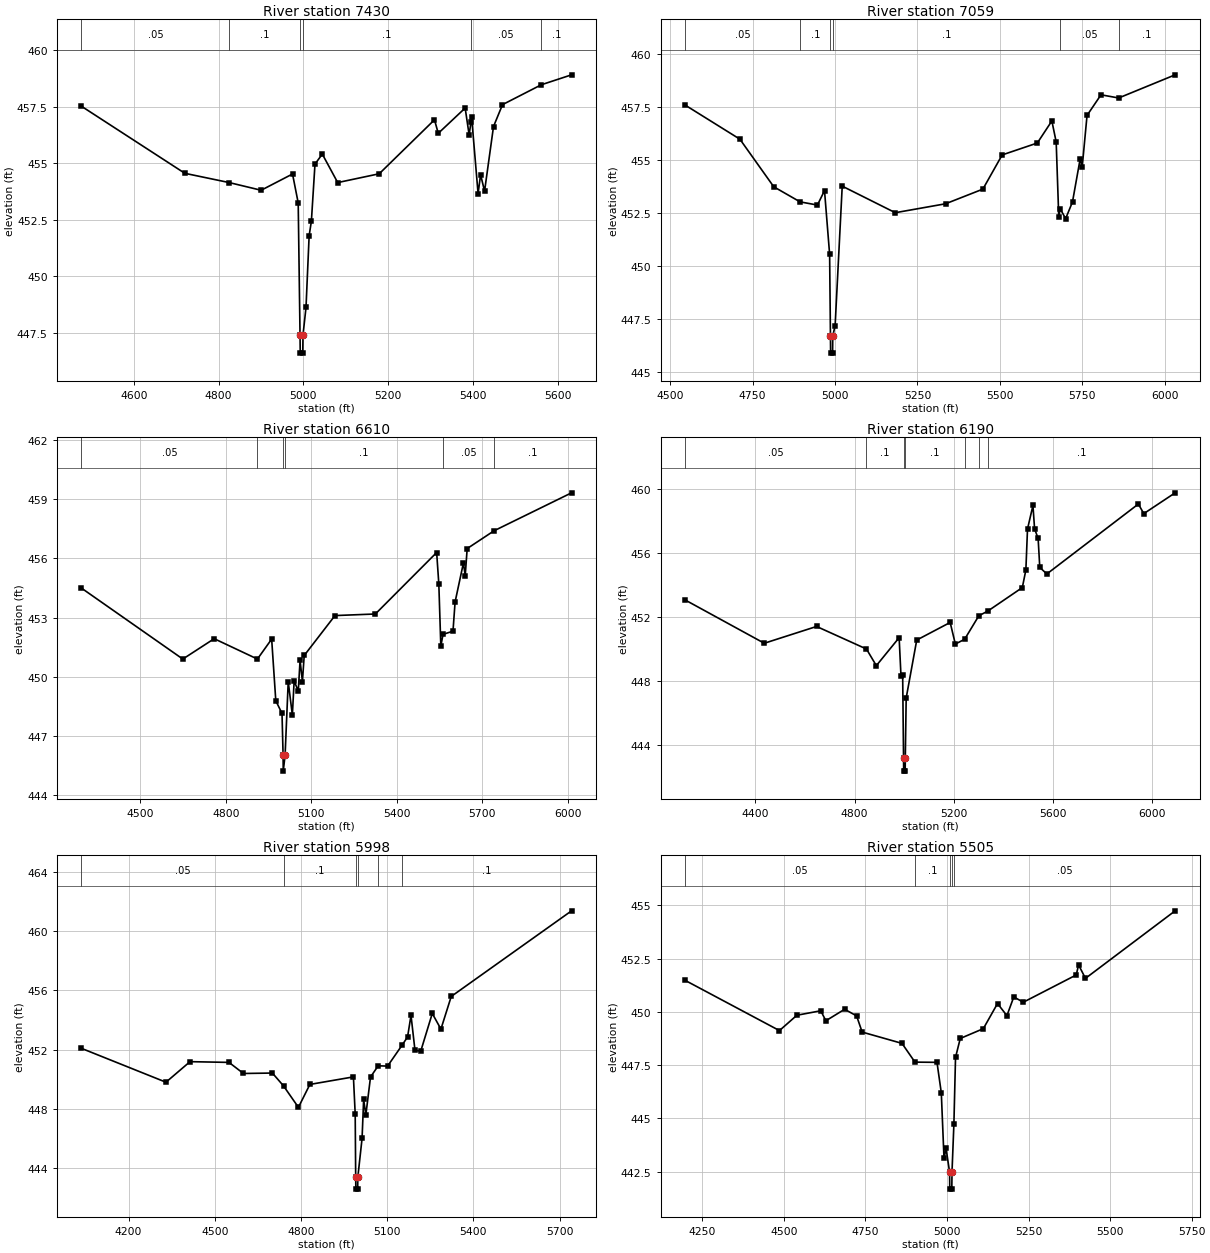
Type RM Length L Ch R = 1,7430,371,371,371
BEGIN DESCRIPTION:
Mapping XS bd773cd1
END DESCRIPTION:
XS GIS Cut Line= 4
      2053930.91     13488771.09      2053818.94     13488804.94
      2053636.65     13489328.38      2053897.19     13489738.00
#Sta/Elev= 30
  4476.4  457.52  4720.5  454.55  4825.2  454.14  4900.5  453.80  4974.6  454.52
  4988.0  453.24  4992.3  447.39  4992.8  446.59  4998.8  446.59  4999.3  447.39
  5006.4  448.61  5013.8  451.79  5019.1  452.43  5027.6  454.96  5044.9  455.40
  5081.2  454.14  5179.2  454.53  5309.6  456.92  5318.5  456.32  5382.0  457.44
  5391.4  456.25  5395.8  456.83  5397.3  457.03  5412.5  453.65  5418.4  454.49
  5427.8  453.76  5448.9  456.62  5470.1  457.59  5561.7  458.47  5633.1  458.91
#Mann=6,-1,0
  4476.4    0.05       0  4825.2     0.1       0  4992.3    0.07       0
  4999.3     0.1       0  5395.8    0.05       0  5561.7     0.1       0
Bank Sta=4992.3,4999.3
Exp/Cntr=0.3,0.1

Type RM Length L Ch R = 1,7059,449,449,449
BEGIN DESCRIPTION:
Mapping XS cfe31868
END DESCRIPTION:
XS GIS Cut Line= 4
      2053643.71     13488508.76      2053532.48     13488810.15
      2053402.27     13489143.48      2053876.35     13489797.02
#Sta/Elev= 30
  4545.2  457.58  4711.7  455.97  4814.4  453.73  4894.2  453.02  4946.8  452.87
  4968.3  453.55  4983.8  450.55  4986.3  446.70  4986.8  445.90  4992.8  445.90
  4993.3  446.70  5000.5  447.20  5022.0  453.76  5183.0  452.51  5335.4  452.93
  5448.6  453.62  5507.1  455.23  5613.7  455.79  5657.8  456.83  5670.9  455.84
  5678.7  452.33  5683.2  452.69  5699.6  452.23  5720.4  453.02  5743.6  455.04
  5749.8  454.66  5764.5  457.09  5806.8  458.06  5860.4  457.91  6031.7  459.00
#Mann=6,-1,0
  4545.2    0.05       0  4894.2     0.1       0  4986.3    0.07       0
  4993.3     0.1       0  5683.2    0.05       0  5860.4     0.1       0
Bank Sta=4986.3,4993.3
Exp/Cntr=0.3,0.1

Type RM Length L Ch R = 1,6610,420,420,420
BEGIN DESCRIPTION:
Mapping XS 597b92fa
END DESCRIPTION:
XS GIS Cut Line= 4
      2053115.92     13488439.37      2053097.59     13488995.05
      2053386.65     13489216.40      2053862.42     13489859.47
#Sta/Elev= 30
  4293.2  454.49  4649.0  450.90  4759.1  451.93  4910.8  450.90  4960.8  451.91
  4975.3  448.79  4997.1  448.15  5000.9  446.03  5001.4  445.23  5007.9  446.03
  5018.9  449.76  5033.4  448.07  5039.7  449.79  5054.2  449.28  5060.5  450.84
  5068.7  449.76  5075.0  451.08  5183.0  453.10  5324.7  453.18  5539.8  456.29
  5547.4  454.70  5554.4  451.56  5562.2  452.15  5597.1  452.31  5604.5  453.79
  5633.7  455.76  5640.0  455.12  5646.9  456.49  5741.3  457.39  6013.2  459.31
#Mann=6,-1,0
  4293.2    0.05       0  4910.8     0.1       0  5000.9    0.07       0
  5007.9     0.1       0  5562.2    0.05       0  5741.3     0.1       0
Bank Sta=5000.9,5007.9
Exp/Cntr=0.3,0.1

Type RM Length L Ch R = 1,6190,192,192,192
BEGIN DESCRIPTION:
Mapping XS 6c7a57f3
END DESCRIPTION:
XS GIS Cut Line= 4
      2053022.17     13488456.68      2052959.57     13489211.19
      2053147.07     13489416.92      2053858.95     13490029.62
#Sta/Elev= 30
  4116.6  453.06  4436.0  450.35  4646.7  451.40  4847.7  449.99  4887.4  448.95
  4979.3  450.70  4986.7  448.32  4993.5  448.36  4997.1  443.16  4997.6  442.36
  5003.6  442.36  5004.1  443.16  5007.7  446.93  5050.2  450.55  5184.9  451.65
  5205.7  450.30  5243.2  450.60  5300.5  452.07  5336.4  452.36  5475.6  453.83
  5489.9  454.93  5496.5  457.49  5518.4  458.96  5525.0  457.50  5539.3  456.90
  5545.9  455.09  5574.4  454.68  5943.1  459.05  5965.0  458.45  6091.3  459.75
#Mann=7,-1,0
  4116.6    0.05       0  4847.7     0.1       0  4997.1    0.07       0
  5004.1     0.1       0  5243.2    0.05       0  5300.5    0.08       0
  5336.4     0.1       0
Bank Sta=4997.1,5004.1
Exp/Cntr=0.3,0.1

Type RM Length L Ch R = 1,5998,493,493,493
BEGIN DESCRIPTION:
Mapping XS 738ede5d
END DESCRIPTION:
XS GIS Cut Line= 4
      2052973.56     13488494.91      2052881.44     13489289.32
      2053009.05     13489599.21      2053049.94     13490168.48
#Sta/Elev= 30
  4035.9  452.08  4330.1  449.79  4413.8  451.18  4549.4  451.13  4599.7  450.38
  4700.4  450.41  4739.2  449.54  4791.0  448.09  4830.9  449.64  4982.4  450.15
  4988.6  447.64  4990.3  443.36  4990.9  442.56  4997.2  442.56  4997.7  443.36
  5012.5  445.99  5018.0  448.63  5025.6  447.57  5041.9  450.14  5068.6  450.90
  5101.3  450.88  5151.2  452.28  5170.8  452.85  5182.8  454.31  5196.6  451.95
  5216.7  451.89  5256.8  454.44  5286.9  453.38  5322.8  455.59  5741.5  461.38
#Mann=6,-1,0
  4035.9    0.05       0  4739.2     0.1       0  4990.3    0.07       0
  4997.7     0.1       0  5068.6    0.05       0  5151.2     0.1       0
Bank Sta=4990.3,4997.7
Exp/Cntr=0.3,0.1

Type RM Length L Ch R = 1,5505,1222,1222,1222
BEGIN DESCRIPTION:
Mapping XS f9c45ff6
END DESCRIPTION:
XS GIS Cut Line= 4
      2052938.85     13488480.99      2052734.87     13489081.08
      2052376.80     13489355.82      2052092.33     13489660.81
#Sta/Elev= 30
  4197.2  451.48  4486.6  449.12  4540.1  449.84  4613.3  450.05  4628.9  449.58
  4686.4  450.12  4723.1  449.81  4740.1  449.05  4862.2  448.52  4902.0  447.64
  4969.5  447.63  4982.7  446.20  4991.0  443.12  4997.3  443.59  5008.1  442.48
  5008.6  441.68  5014.9  441.68  5015.5  442.48  5021.3  444.73  5026.3  447.86
  5040.8  448.75  5111.5  449.21  5155.0  450.39  5183.8  449.82  5204.9  450.70
  5233.9  450.45  5396.2  451.73  5403.5  452.20  5424.5  451.57  5699.4  454.74
#Mann=5,-1,0
  4197.2    0.05       0  4902.0     0.1       0  5008.1    0.07       0
  5015.5     0.1       0  5021.3    0.05       0
Bank Sta=5008.1,5015.5
Exp/Cntr=0.3,0.1

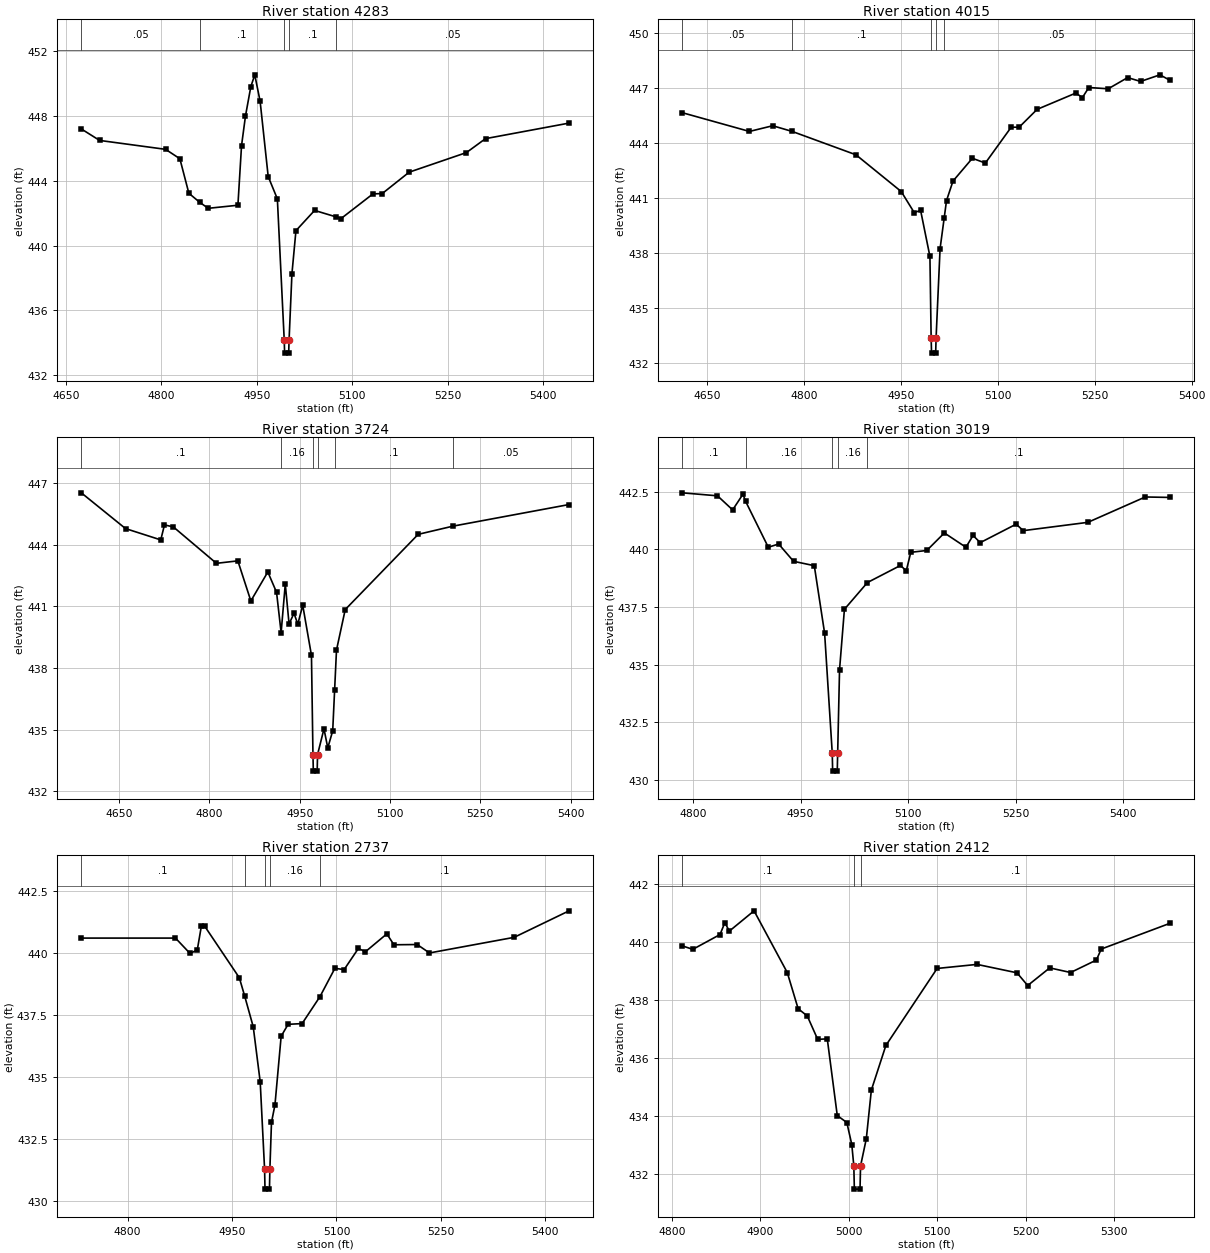
Type RM Length L Ch R = 1,4283,268,268,268
BEGIN DESCRIPTION:
Mapping XS 729eeb6f
END DESCRIPTION:
XS GIS Cut Line= 4
      2052193.79     13488366.20      2051976.79     13488473.61
      2051820.54     13488684.11      2051817.31     13488946.31
#Sta/Elev= 30
  4674.3  447.20  4703.1  446.49  4806.8  445.94  4829.2  445.36  4843.3  443.23
  4860.7  442.66  4873.8  442.30  4920.4  442.49  4926.1  446.17  4932.3  448.00
  4940.7  449.81  4946.9  450.54  4955.3  448.91  4968.0  444.26  4982.4  442.88
  4993.2  434.16  4993.8  433.36  5000.2  433.36  5000.8  434.16  5005.3  438.26
  5011.6  440.92  5040.9  442.17  5074.7  441.77  5082.6  441.67  5132.6  443.19
  5147.2  443.21  5189.5  444.53  5279.5  445.74  5309.5  446.60  5440.8  447.56
#Mann=5,-1,0
  4674.3    0.05       0  4860.7     0.1       0  4993.2    0.07       0
  5000.8     0.1       0  5074.7    0.05       0
Bank Sta=4993.2,5000.8
Exp/Cntr=0.3,0.1

Type RM Length L Ch R = 1,4015,291,291,291
BEGIN DESCRIPTION:
Mapping XS 80488e5c
END DESCRIPTION:
XS GIS Cut Line= 4
      2051876.37     13488251.83      2051677.09     13488386.81
      2051663.20     13488664.58      2051650.67     13488900.54
#Sta/Elev= 30
  4611.4  445.64  4715.4  444.62  4751.4  444.93  4781.6  444.62  4880.3  443.35
  4950.4  441.35  4970.4  440.21  4980.4  440.32  4994.8  437.82  4996.7  433.36
  4997.3  432.56  5003.7  432.56  5004.3  433.36  5010.5  438.24  5016.9  439.92
  5020.5  440.86  5030.5  441.92  5060.5  443.16  5080.6  442.90  5120.6  444.85
  5132.9  444.85  5160.7  445.82  5220.8  446.71  5230.8  446.46  5240.8  447.01
  5270.8  446.94  5300.9  447.55  5320.9  447.34  5350.9  447.70  5366.5  447.40
#Mann=5,-1,0
  4611.4    0.05       0  4781.6     0.1       0  4996.7    0.07       0
  5004.3     0.1       0  5016.9    0.05       0
Bank Sta=4996.7,5004.3
Exp/Cntr=0.3,0.1

Type RM Length L Ch R = 1,3724,705,705,705
BEGIN DESCRIPTION:
Mapping XS f44c68bb
END DESCRIPTION:
XS GIS Cut Line= 4
      2051765.19     13488092.16      2051576.75     13488224.21
      2051337.17     13488534.11      2051306.95     13488720.26
#Sta/Elev= 30
  4587.2  446.53  4660.7  444.79  4719.2  444.24  4725.4  444.97  4740.2  444.87
  4811.7  443.10  4847.3  443.22  4868.9  441.27  4897.1  442.68  4911.6  441.69
  4919.2  439.73  4926.1  442.09  4932.4  440.15  4940.6  440.67  4946.9  440.14
  4955.1  441.06  4969.6  438.62  4972.1  433.79  4972.7  432.99  4979.1  432.99
  4979.7  433.79  4990.4  435.05  4996.7  434.12  5004.9  434.95  5008.1  436.95
  5011.2  438.88  5025.7  440.85  5146.9  444.51  5204.9  444.91  5397.6  445.96
#Mann=6,-1,0
  4587.2     0.1       0  4919.2    0.16       0  4972.1    0.07       0
  4979.7    0.16       0  5008.1     0.1       0  5204.9    0.05       0
Bank Sta=4972.1,4979.7
Exp/Cntr=0.3,0.1

Type RM Length L Ch R = 1,3019,282,282,282
BEGIN DESCRIPTION:
Mapping XS 4eb4e08f
END DESCRIPTION:
XS GIS Cut Line= 4
      2051144.10     13487850.35      2051088.55     13487848.61
      2050854.18     13488034.38      2050852.03     13488359.52
#Sta/Elev= 30
  4785.2  442.45  4834.3  442.32  4855.4  441.71  4869.8  442.39  4873.5  442.08
  4905.1  440.09  4919.5  440.23  4940.3  439.48  4969.2  439.29  4983.6  436.36
  4994.2  431.18  4994.8  430.38  5001.2  430.38  5001.8  431.18  5004.4  434.78
  5011.2  437.40  5043.3  438.56  5089.3  439.30  5097.4  439.07  5103.7  439.87
  5126.0  439.95  5150.5  440.71  5180.5  440.09  5190.5  440.60  5200.5  440.29
  5250.5  441.09  5260.5  440.81  5350.5  441.17  5430.5  442.27  5465.0  442.25
#Mann=5,-1,0
  4785.2     0.1       0  4873.5    0.16       0  4994.2    0.07       0
  5001.8    0.16       0  5043.3     0.1       0
Bank Sta=4994.2,5001.8
Exp/Cntr=0.3,0.1

Type RM Length L Ch R = 1,2737,325,325,325
BEGIN DESCRIPTION:
Mapping XS 91a23e7a
END DESCRIPTION:
XS GIS Cut Line= 4
      2050740.93     13487665.03      2050692.72     13487831.25
      2050706.61     13488023.96      2050775.36     13488351.24
#Sta/Elev= 30
  4733.4  440.59  4868.7  440.59  4889.6  439.97  4900.0  440.11  4905.8  441.06
  4910.9  441.06  4960.4  438.99  4967.9  438.27  4980.4  437.01  4990.4  434.79
  4996.7  431.26  4997.3  430.46  5003.7  430.46  5004.3  431.26  5006.6  433.15
  5011.6  433.86  5020.5  436.63  5030.5  437.11  5050.6  437.14  5076.3  438.23
  5097.7  439.37  5111.0  439.32  5131.4  440.17  5141.6  440.04  5172.3  440.76
  5182.5  440.32  5215.9  440.33  5233.6  439.99  5355.2  440.62  5434.1  441.69
#Mann=5,-1,0
  4733.4     0.1       0  4967.9    0.16       0  4996.7    0.07       0
  5004.3    0.16       0  5076.3     0.1       0
Bank Sta=4996.7,5004.3
Exp/Cntr=0.3,0.1

Type RM Length L Ch R = 1,2412,211,211,211
BEGIN DESCRIPTION:
Mapping XS efd9d2c9
END DESCRIPTION:
XS GIS Cut Line= 4
      2050420.50     13487953.38      2050404.88     13488023.69
      2050555.92     13488312.75      2050696.53     13488372.64
#Sta/Elev= 30
  4811.8  439.88  4823.7  439.76  4854.4  440.27  4859.9  440.68  4865.0  440.39
  4892.9  441.09  4930.4  438.96  4942.7  437.71  4953.0  437.46  4964.8  436.65
  4975.6  436.67  4986.9  434.02  4997.7  433.78  5003.3  433.02  5005.6  432.28
  5006.2  431.48  5012.6  431.48  5013.2  432.28  5019.7  433.22  5025.4  434.90
  5041.8  436.44  5099.7  439.10  5144.8  439.24  5189.9  438.95  5202.0  438.51
  5226.9  439.12  5250.5  438.96  5279.6  439.39  5285.1  439.77  5362.8  440.66
#Mann=3,-1,0
  4811.8     0.1       0  5005.6    0.07       0  5013.2     0.1       0
Bank Sta=5005.6,5013.2
Exp/Cntr=0.3,0.1

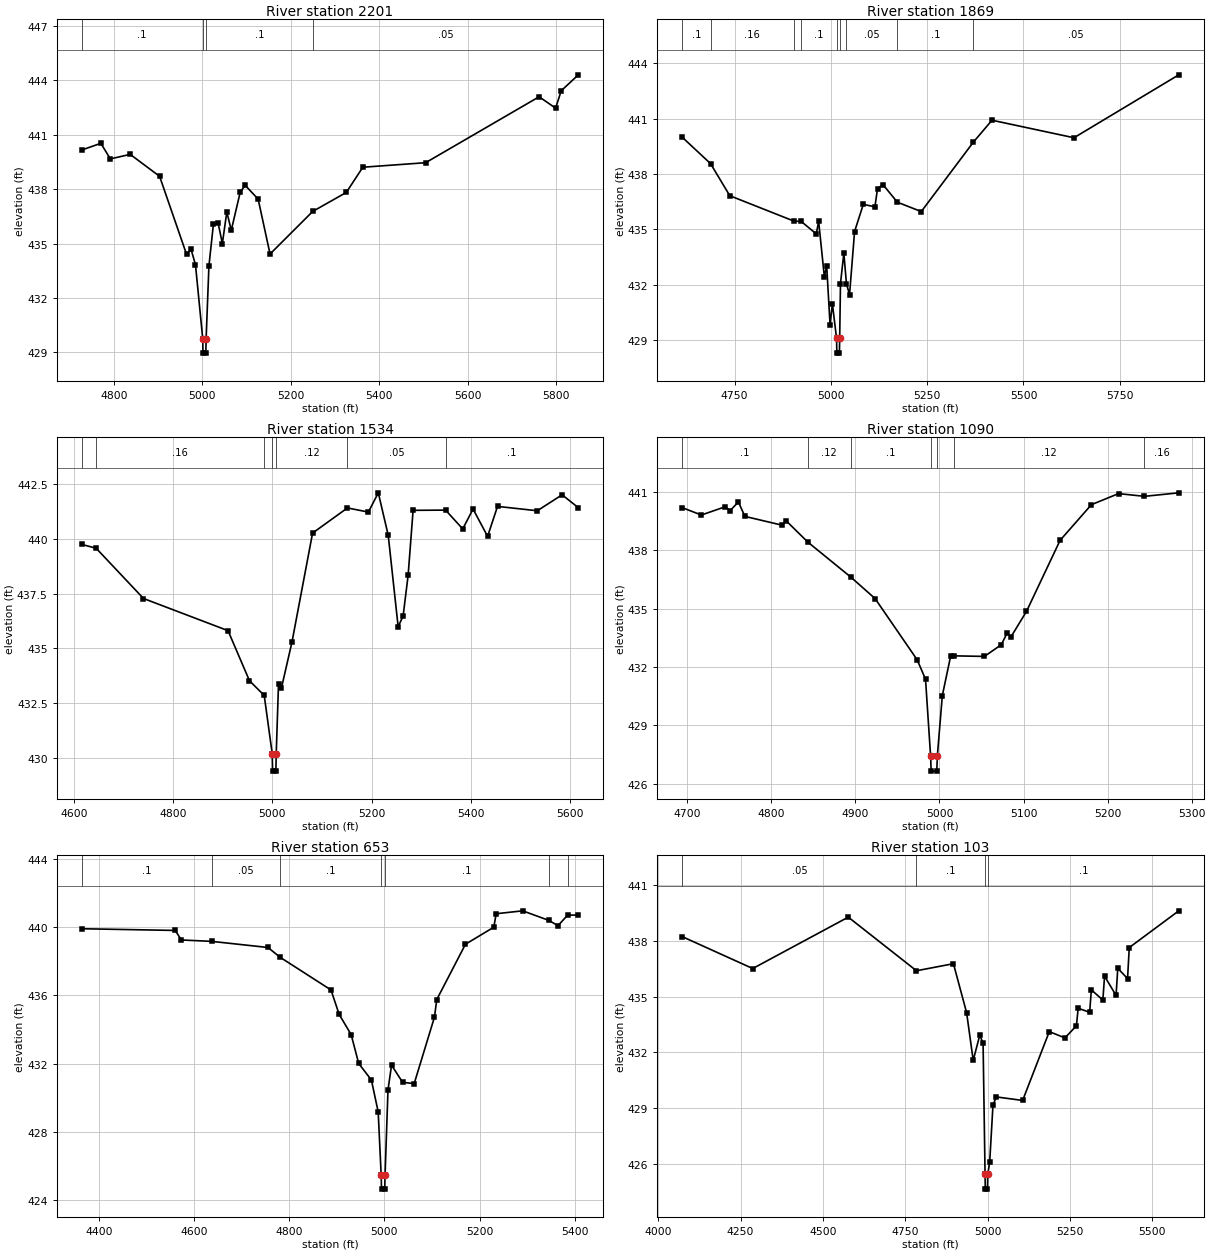
Type RM Length L Ch R = 1,2201,332,332,332
BEGIN DESCRIPTION:
Mapping XS 059f98f9
END DESCRIPTION:
XS GIS Cut Line= 4
      2050347.58     13488021.13      2050324.15     13488164.32
      2050391.86     13488575.78      2050727.03     13489026.17
#Sta/Elev= 30
  4727.1  440.16  4770.3  440.53  4791.8  439.67  4836.7  439.92  4903.2  438.71
  4964.1  434.41  4974.5  434.67  4984.4  433.83  5000.8  429.75  5001.4  428.95
  5007.8  428.95  5008.5  429.75  5014.8  433.75  5024.9  436.05  5035.7  436.12
  5045.2  435.00  5055.3  436.74  5065.4  435.73  5085.7  437.84  5096.9  438.21
  5126.2  437.45  5153.1  434.42  5249.6  436.77  5325.7  437.82  5363.0  439.21
  5505.1  439.46  5761.9  443.10  5799.2  442.47  5811.8  443.43  5850.6  444.31
#Mann=4,-1,0
  4727.1     0.1       0  5000.8    0.07       0  5008.5     0.1       0
  5249.6    0.05       0
Bank Sta=5000.8,5008.5
Exp/Cntr=0.3,0.1

Type RM Length L Ch R = 1,1869,335,335,335
BEGIN DESCRIPTION:
Mapping XS 576c93d0
END DESCRIPTION:
XS GIS Cut Line= 4
      2050305.94     13488159.06      2050246.02     13488315.36
      2050058.52     13488583.59      2050645.35     13489119.41
#Sta/Elev= 30
  4614.0  439.99  4687.6  438.56  4737.6  436.82  4904.6  435.44  4922.8  435.43
  4962.2  434.75  4968.3  435.43  4983.1  432.43  4989.2  433.01  4997.9  429.83
  5004.0  430.96  5014.8  429.09  5015.5  428.29  5022.2  428.29  5022.9  429.09
  5025.0  432.06  5033.7  433.71  5040.5  432.05  5048.5  431.46  5061.6  434.88
  5084.2  436.35  5114.4  436.22  5121.2  437.21  5135.4  437.42  5172.5  436.47
  5234.7  435.96  5369.9  439.72  5418.4  440.91  5631.2  439.96  5903.3  443.37
#Mann=9,-1,0
  4614.0     0.1       0  4687.6    0.16       0  4904.6    0.12       0
  4922.8     0.1       0  5014.8    0.07       0  5022.9     0.1       0
  5040.5    0.05       0  5172.5     0.1       0  5369.9    0.05       0
Bank Sta=5014.8,5022.9
Exp/Cntr=0.3,0.1

Type RM Length L Ch R = 1,1534,444,444,444
BEGIN DESCRIPTION:
Mapping XS 6343b40a
END DESCRIPTION:
XS GIS Cut Line= 4
      2050308.51     13488135.68      2050134.05     13488213.80
      2049897.07     13488354.42      2049918.82     13488887.66
#Sta/Elev= 30
  4616.2  439.75  4645.1  439.58  4740.6  437.28  4910.9  435.81  4954.1  433.52
  4983.8  432.85  4999.9  430.19  5000.6  429.39  5007.3  429.39  5008.0  430.19
  5012.6  433.39  5018.4  433.18  5039.8  435.30  5081.2  440.27  5151.5  441.42
  5193.6  441.23  5213.6  442.11  5233.6  440.17  5253.6  435.99  5263.6  436.48
  5273.7  438.34  5283.7  441.31  5349.2  441.32  5383.7  440.46  5404.5  441.37
  5433.8  440.12  5453.8  441.49  5533.9  441.29  5583.9  442.02  5616.6  441.43
#Mann=7,-1,0
  4616.2     0.1       0  4645.1    0.16       0  4983.8    0.12       0
  4999.9    0.07       0  5008.0    0.12       0  5151.5    0.05       0
  5349.2     0.1       0
Bank Sta=4999.9,5008
Exp/Cntr=0.3,0.1

Type RM Length L Ch R = 1,1090,437,437,437
BEGIN DESCRIPTION:
Mapping XS ec2fa1c0
END DESCRIPTION:
XS GIS Cut Line= 4
      2050404.86     13487984.62      2050339.77     13487948.17
      2049925.71     13487963.80      2049871.03     13488049.72
#Sta/Elev= 30
  4693.9  440.18  4716.7  439.80  4744.8  440.22  4751.0  440.03  4760.8  440.47
  4768.5  439.73  4812.6  439.28  4817.7  439.50  4843.4  438.41  4894.6  436.61
  4923.4  435.51  4973.4  432.37  4983.4  431.37  4989.4  427.45  4990.1  426.65
  4996.8  426.65  4997.5  427.45  5003.4  430.53  5013.4  432.58  5017.1  432.57
  5053.5  432.54  5073.5  433.14  5080.3  433.72  5085.3  433.56  5103.5  434.85
  5143.5  438.50  5180.7  440.33  5213.0  440.90  5243.9  440.76  5284.7  440.94
#Mann=7,-1,0
  4693.9     0.1       0  4843.4    0.12       0  4894.6     0.1       0
  4989.4    0.07       0  4997.5     0.1       0  5017.1    0.12       0
  5243.9    0.16       0
Bank Sta=4989.4,4997.5
Exp/Cntr=0.3,0.1

Type RM Length L Ch R = 1,653,550,550,550
BEGIN DESCRIPTION:
Mapping XS da5c5714
END DESCRIPTION:
XS GIS Cut Line= 4
      2050609.98     13487642.93      2050356.08     13487543.11
      2049900.00     13487650.00      2049876.61     13487951.63
#Sta/Elev= 30
  4363.8  439.91  4560.2  439.81  4573.3  439.25  4636.6  439.17  4755.2  438.81
  4781.1  438.23  4887.7  436.32  4904.8  434.89  4930.1  433.70  4945.9  432.01
  4972.6  431.04  4986.9  429.17  4993.2  425.44  4993.9  424.64  5000.6  424.64
  5001.3  425.44  5007.5  430.46  5015.0  431.91  5038.3  430.90  5062.6  430.83
  5105.1  434.72  5110.1  435.76  5170.3  439.00  5229.9  440.00  5234.9  440.79
  5290.6  440.96  5345.5  440.40  5364.8  440.09  5385.2  440.71  5407.6  440.71
#Mann=7,-1,0
  4363.8     0.1       0  4636.6    0.05       0  4781.1     0.1       0
  4993.2    0.07       0  5001.3     0.1       0  5345.5    0.07       0
  5385.2    0.16       0
Bank Sta=4993.2,5001.3
Exp/Cntr=0.3,0.1

Type RM Length L Ch R = 1,103,0,0,0
BEGIN DESCRIPTION:
UNT 150 in Lagunillas Cr Wtrshd 63.0
END DESCRIPTION:
XS GIS Cut Line= 4
      2050315.10     13486542.81      2049770.84     13487036.11
      2049760.43     13487388.54      2049868.88     13487794.79
#Sta/Elev= 30
  4072.6  438.24  4286.8  436.52  4576.8  439.29  4783.9  436.40  4896.1  436.78
  4936.1  434.14  4956.1  431.57  4976.1  432.93  4986.1  432.49  4992.1  425.43
  4992.8  424.63  4999.5  424.63  5000.2  425.43  5006.1  426.07  5016.1  429.15
  5026.1  429.60  5106.2  429.41  5187.1  433.12  5234.7  432.78  5269.6  433.44
  5274.7  434.38  5309.6  434.16  5314.8  435.37  5349.7  434.82  5354.9  436.11
  5389.8  435.07  5395.0  436.53  5424.7  435.98  5429.9  437.65  5580.2  439.63
#Mann=4,-1,0
  4072.6    0.05       0  4783.9     0.1       0  4992.1    0.07       0
  5000.2     0.1       0
Bank Sta=4992.1,5000.2
Exp/Cntr=0.3,0.1

Chan Stop Cuts=-1