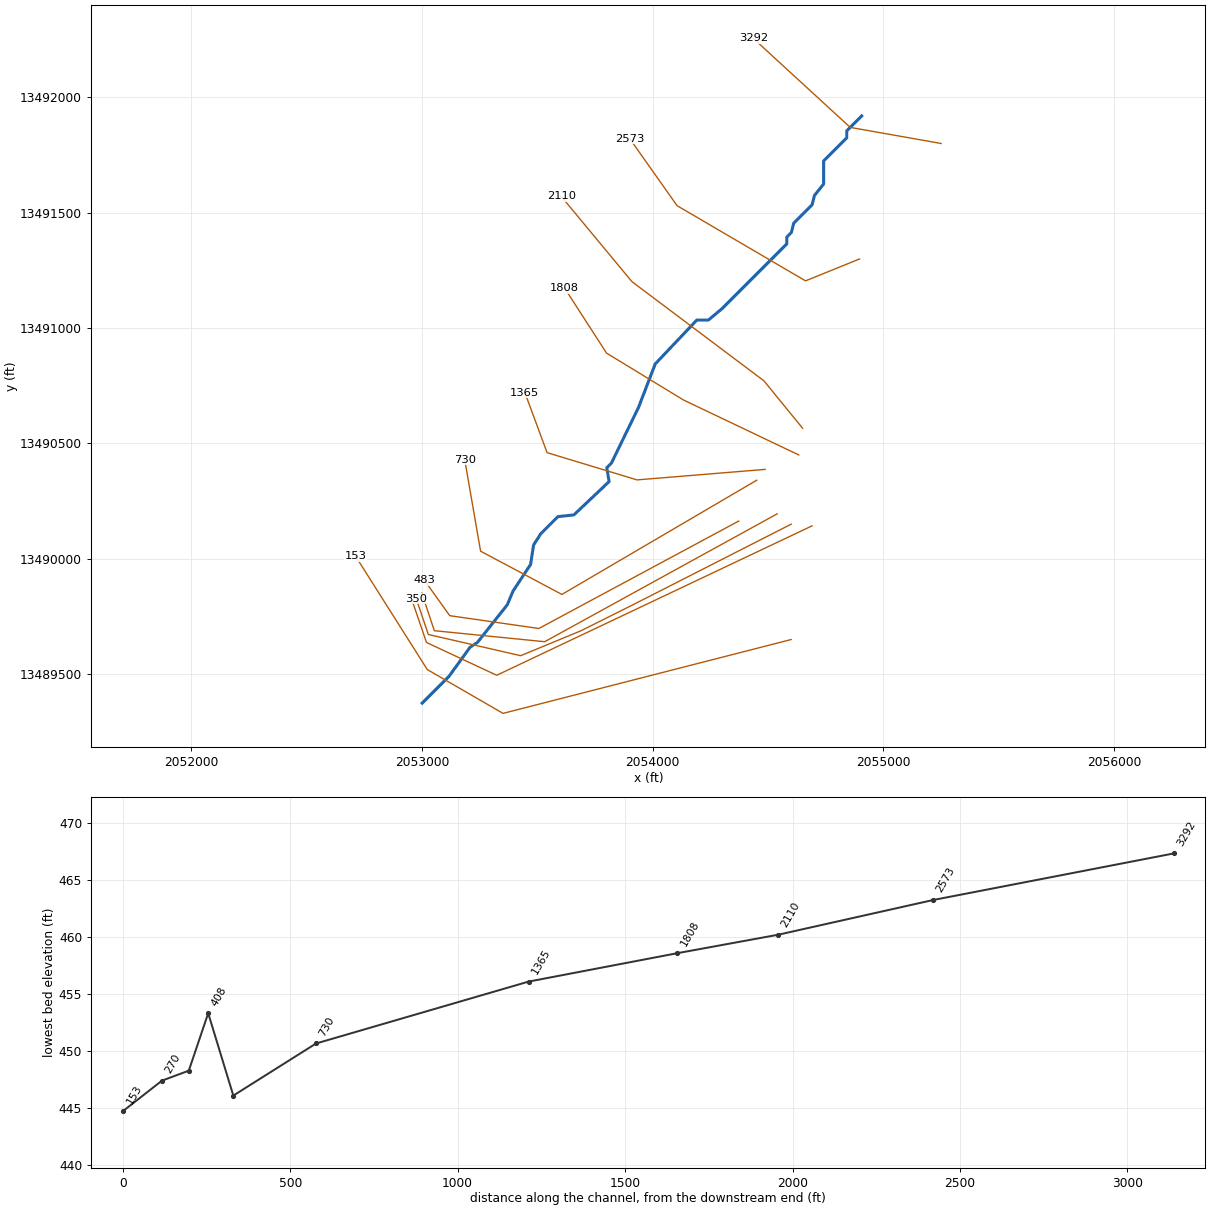
--- UNT 151 in Lagunillas Cr Wtrshd.prj (project) ---

Proj Title=UNT 151 in Lagunillas Cr Wtrshd Base Level Engineering
Current Plan=p01
Default Exp/Contr=0.3,0.1
English Units
Geom File=g01
Flow File=f01
Plan File=p01
BEGIN DESCRIPTION:
UNT 151 in Lagunillas Cr Wtrshd
END DESCRIPTION:

--- UNT 151 in Lagunillas Cr Wtrshd.p01 (plan) ---

Plan Title=Multiple Run
Short Identifier=Multiple
Geom File=g01
Flow File=f01
Subcritical Flow
K Sum by GR= 0
Std Step Tol= 0.01
Critical Tol= 0.01
Num of Std Step Trials= 20
Max Error Tol= 0.3
Flow Tol Ratio= 0.001
Split Flow NTrial= 30
Split Flow Tol= 0.02
Split Flow Ratio= 0.02
Log Output Level= 0
Friction Slope Method= 1
Unsteady Friction Slope Method= 2
Unsteady Bridges Friction Slope Method= 1
Parabolic Critical Depth
Global Vel Dist=  1 , 1 , 1
Global Log Level= 0
CheckData=True
Encroach Param= -1, 0, 0, 0
BEGIN DESCRIPTION:
Multiple Run
END DESCRIPTION:

--- UNT 151 in Lagunillas Cr Wtrshd.f01 (steady flow) ---

Flow Title=Multiple
Number of Profiles=7
Profile Names=10-year,25-year,50-year,1pct_min,100-year,1pct_plu,500-year
River Rch & RM= UNT 151 in Lagun,Reach-1,3292
      65      83      96      56     112     222     152
Boundary for River Rch & Prof#=UNT 151 in Lagun,Reach-1,1
Up Type=0
Dn Type=3
Dn Slope=0.005
Boundary for River Rch & Prof#=UNT 151 in Lagun,Reach-1,2
Up Type=0
Dn Type=3
Dn Slope=0.005
Boundary for River Rch & Prof#=UNT 151 in Lagun,Reach-1,3
Up Type=0
Dn Type=3
Dn Slope=0.005
Boundary for River Rch & Prof#=UNT 151 in Lagun,Reach-1,4
Up Type=0
Dn Type=3
Dn Slope=0.005
Boundary for River Rch & Prof#=UNT 151 in Lagun,Reach-1,5
Up Type=0
Dn Type=3
Dn Slope=0.005
Boundary for River Rch & Prof#=UNT 151 in Lagun,Reach-1,6
Up Type=0
Dn Type=3
Dn Slope=0.005
Boundary for River Rch & Prof#=UNT 151 in Lagun,Reach-1,7
Up Type=0
Dn Type=3
Dn Slope=0.005

--- UNT 151 in Lagunillas Cr Wtrshd.g01 (geometry) ---

Geom Title=Existing Conditions

River Reach=UNT 151 in Lagun,Reach-1
Reach XY= 30
      2054905.80     13491919.54      2054840.80     13491854.54
      2054840.80     13491824.54      2054740.80     13491724.54
      2054740.80     13491624.54      2054700.80     13491574.54
      2054690.80     13491534.54      2054610.80     13491454.54
      2054600.80     13491414.54      2054580.80     13491394.54
      2054580.80     13491364.54      2054300.80     13491084.54
      2054240.80     13491034.54      2054190.80     13491034.54
      2054010.80     13490844.54      2053938.17     13490655.69
      2053820.80     13490414.54      2053800.80     13490394.54
      2053810.80     13490334.54      2053658.22     13490190.20
      2053588.82     13490182.56      2053514.49     13490108.23
      2053483.52     13490059.99      2053470.50     13489975.36
      2053394.55     13489860.34      2053369.59     13489800.66
      2053240.47     13489637.90      2053207.92     13489616.20
      2053117.22     13489490.96      2053000.80     13489374.54

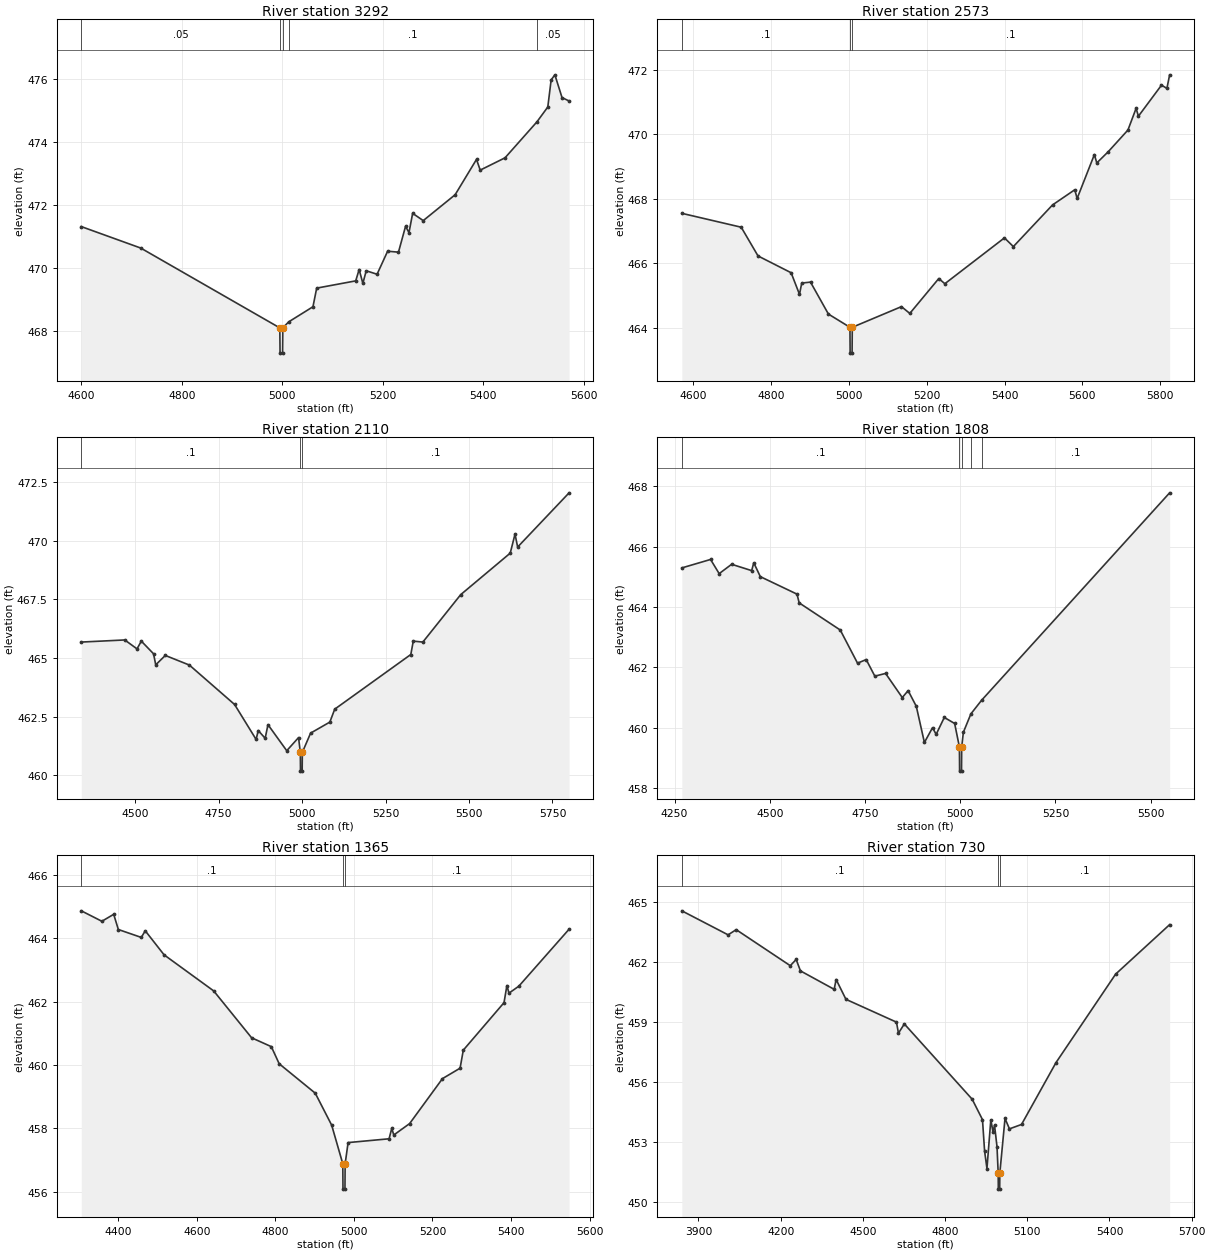
Type RM Length L Ch R = 1,3292,719,719,719
BEGIN DESCRIPTION:
UNT 151 in Lagunillas Cr Wtrshd 17.0
END DESCRIPTION:
XS GIS Cut Line= 3
      2055250.02     13491800.00      2054856.06     13491869.79
      2054435.57     13492255.80
#Sta/Elev= 30
  4599.9  471.31  4718.2  470.63  4995.0  468.10  4995.5  467.30  5000.5  467.30
  5001.0  468.10  5012.6  468.29  5061.0  468.77  5068.4  469.36  5146.1  469.59
  5152.9  469.95  5160.3  469.51  5167.0  469.91  5188.6  469.80  5209.6  470.53
  5231.2  470.50  5245.3  471.32  5252.1  471.12  5259.4  471.73  5280.5  471.50
  5344.0  472.32  5386.5  473.44  5393.9  473.10  5443.3  473.49  5506.8  474.63
  5528.4  475.10  5535.1  475.96  5542.5  476.12  5556.7  475.40  5570.8  475.29
#Mann=5,-1,0
  4599.9    0.05       0  4995.0    0.03       0  5001.0    0.05       0
  5012.6     0.1       0  5506.8    0.05       0
Bank Sta=4995,5001
Exp/Cntr=0.3,0.1

Type RM Length L Ch R = 1,2573,463,463,463
BEGIN DESCRIPTION:
Mapping XS 940b166e
END DESCRIPTION:
XS GIS Cut Line= 4
      2054896.34     13491299.52      2054662.27     13491204.63
      2054105.60     13491530.41      2053900.50     13491820.70
#Sta/Elev= 30
  4571.0  467.55  4723.5  467.12  4766.7  466.23  4851.7  465.71  4873.2  465.04
  4879.0  465.39  4901.5  465.42  4947.5  464.43  5002.8  464.02  5003.3  463.22
  5008.3  463.22  5008.8  464.02  5135.1  464.66  5156.6  464.45  5231.0  465.53
  5246.6  465.37  5399.7  466.79  5422.6  466.52  5523.2  467.81  5580.3  468.28
  5586.4  468.01  5630.7  469.37  5636.9  469.11  5666.4  469.46  5716.9  470.13
  5737.8  470.80  5743.9  470.56  5803.1  471.52  5817.0  471.42  5824.0  471.84
#Mann=3,-1,0
  4571.0     0.1       0  5002.8    0.07       0  5008.8     0.1       0
Bank Sta=5002.8,5008.8
Exp/Cntr=0.3,0.1

Type RM Length L Ch R = 1,2110,302,302,302
BEGIN DESCRIPTION:
Mapping XS 84e2535f
END DESCRIPTION:
XS GIS Cut Line= 4
      2054649.60     13490565.74      2054481.98     13490771.31
      2053909.50     13491201.47      2053603.35     13491570.74
#Sta/Elev= 30
  4338.8  465.68  4469.0  465.77  4505.6  465.39  4518.6  465.72  4555.2  465.18
  4561.7  464.71  4590.4  465.11  4662.5  464.70  4797.9  463.02  4862.4  461.53
  4868.7  461.91  4889.5  461.58  4897.9  462.16  4954.1  461.05  4989.5  461.61
  4994.8  460.98  4995.3  460.18  5000.3  460.18  5000.8  460.98  5025.6  461.80
  5083.2  462.27  5097.8  462.82  5325.7  465.15  5333.1  465.72  5361.8  465.68
  5475.1  467.70  5623.5  469.47  5637.8  470.28  5645.7  469.73  5799.8  472.04
#Mann=3,-1,0
  4338.8     0.1       0  4994.8    0.07       0  5000.8     0.1       0
Bank Sta=4994.8,5000.8
Exp/Cntr=0.3,0.1

Type RM Length L Ch R = 1,1808,443,443,443
BEGIN DESCRIPTION:
Mapping XS ca5b0486
END DESCRIPTION:
XS GIS Cut Line= 4
      2054633.01     13490449.95      2054133.18     13490688.29
      2053799.85     13490891.41      2053617.40     13491173.93
#Sta/Elev= 30
  4269.2  465.30  4344.6  465.58  4367.2  465.11  4399.9  465.42  4452.5  465.21
  4458.0  465.47  4475.2  465.01  4571.5  464.43  4577.2  464.14  4685.0  463.24
  4730.4  462.14  4753.1  462.26  4775.8  461.71  4804.0  461.80  4847.8  461.00
  4863.2  461.23  4884.6  460.71  4905.9  459.51  4927.2  460.00  4936.8  459.78
  4958.1  460.34  4985.3  460.14  4997.8  459.36  4998.3  458.56  5003.3  458.56
  5003.8  459.36  5008.2  459.85  5028.0  460.46  5056.0  460.91  5549.6  467.79
#Mann=5,-1,0
  4269.2     0.1       0  4997.8    0.07       0  5003.8     0.1       0
  5028.0    0.16       0  5056.0     0.1       0
Bank Sta=4997.8,5003.8
Exp/Cntr=0.3,0.1

Type RM Length L Ch R = 1,1365,635,635,635
BEGIN DESCRIPTION:
Mapping XS 39cdb957
END DESCRIPTION:
XS GIS Cut Line= 4
      2054487.26     13490387.43      2053931.79     13490341.93
      2053542.03     13490459.99      2053445.70     13490720.36
#Sta/Elev= 30
  4305.8  464.87  4358.2  464.54  4388.3  464.76  4400.1  464.28  4458.6  464.03
  4468.6  464.24  4516.6  463.48  4643.0  462.34  4739.5  460.86  4789.7  460.58
  4809.7  460.04  4901.6  459.11  4943.4  458.10  4971.7  456.88  4972.2  456.08
  4977.2  456.08  4977.7  456.88  4985.2  457.55  5089.6  457.67  5096.4  458.00
  5101.6  457.79  5141.9  458.15  5225.5  459.57  5270.4  459.90  5278.6  460.47
  5382.3  461.97  5389.6  462.51  5394.9  462.27  5420.0  462.49  5548.0  464.29
#Mann=3,-1,0
  4305.8     0.1       0  4971.7    0.07       0  4977.7     0.1       0
Bank Sta=4971.7,4977.7
Exp/Cntr=0.3,0.1

Type RM Length L Ch R = 1,730,247,247,247
BEGIN DESCRIPTION:
Mapping XS fd3ae71a
END DESCRIPTION:
XS GIS Cut Line= 4
      2054450.72     13490340.53      2053606.27     13489845.40
      2053253.84     13490032.90      2053185.13     13490429.09
#Sta/Elev= 30
  3839.4  464.56  4008.3  463.36  4037.7  463.62  4235.1  461.82  4256.6  462.13
  4272.3  461.56  4395.3  460.64  4402.5  461.13  4438.3  460.14  4622.7  459.00
  4629.9  458.45  4651.4  458.91  4899.0  455.15  4936.6  454.13  4944.3  452.56
  4952.9  451.69  4967.0  454.12  4974.9  453.53  4980.6  453.85  4989.6  452.78
  4993.9  451.46  4994.4  450.66  4999.4  450.66  4999.9  451.46  5018.8  454.19
  5035.0  453.67  5079.1  453.89  5204.9  456.98  5422.6  461.40  5619.6  463.87
#Mann=3,-1,0
  3839.4     0.1       0  4993.9    0.07       0  4999.9     0.1       0
Bank Sta=4993.9,4999.9
Exp/Cntr=0.3,0.1

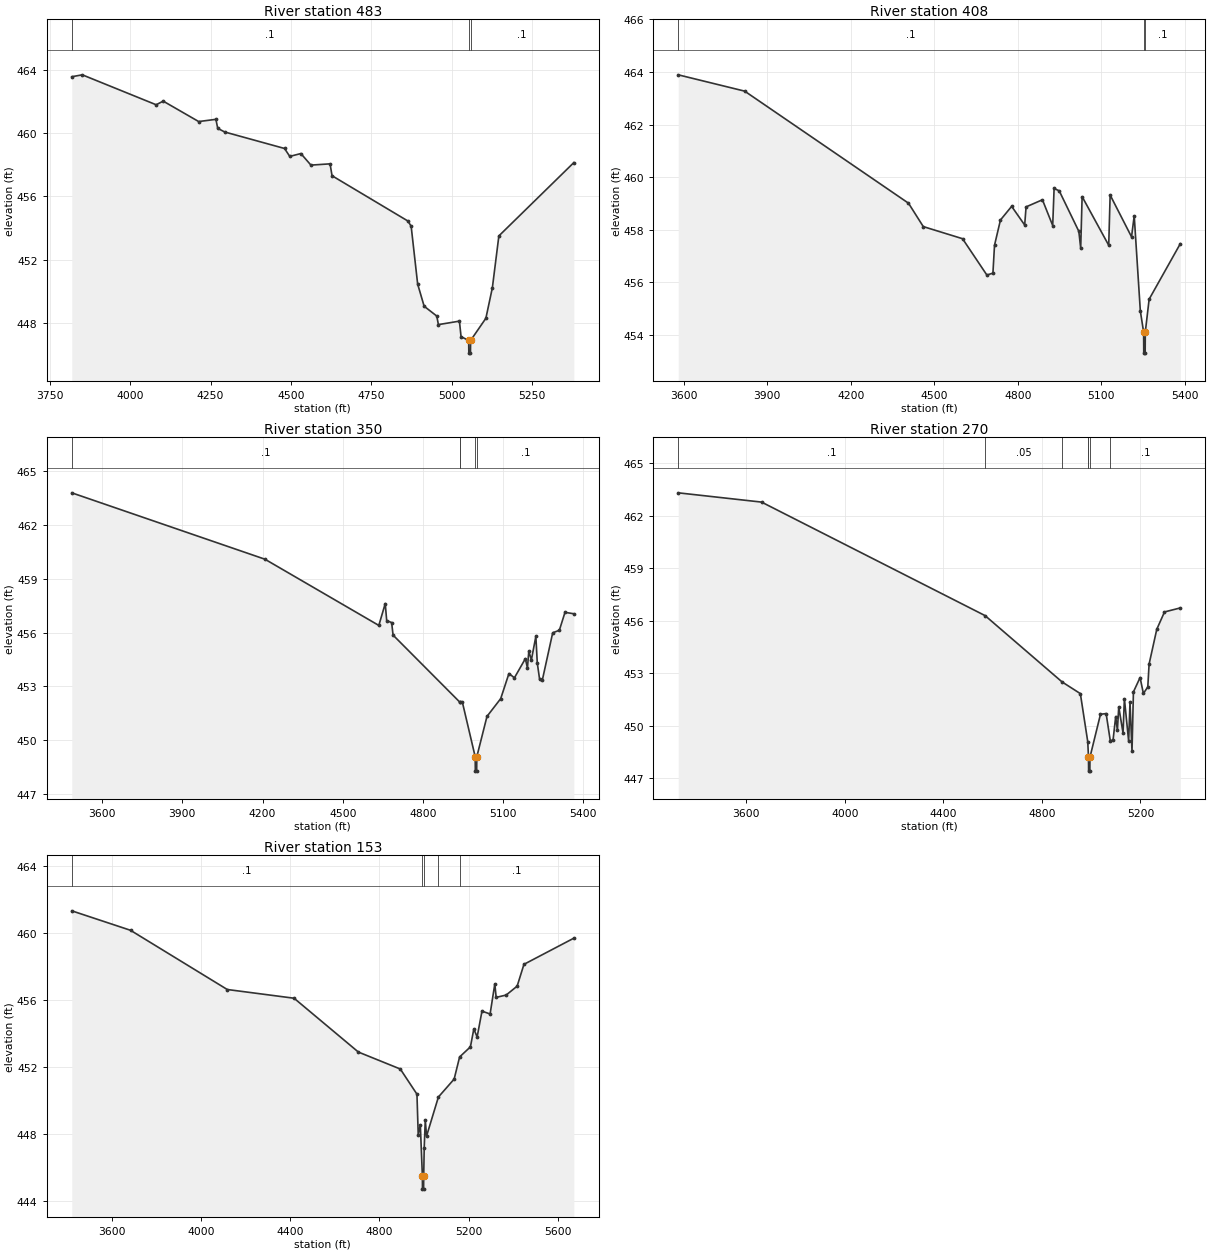
Type RM Length L Ch R = 1,483,75,75,75
BEGIN DESCRIPTION:
Mapping XS 58113c8e
END DESCRIPTION:
XS GIS Cut Line= 4
      2054372.64     13490163.48      2053506.44     13489697.84
      2053120.16     13489753.39      2053010.77     13489906.19
#Sta/Elev= 30
  3818.5  463.55  3851.3  463.67  4081.0  461.78  4102.9  462.01  4213.2  460.72
  4266.8  460.86  4272.5  460.29  4294.4  460.06  4480.3  459.02  4496.5  458.52
  4531.1  458.70  4562.3  457.97  4621.9  458.05  4628.0  457.30  4864.0  454.44
  4874.1  454.11  4894.3  450.46  4914.5  449.06  4953.8  448.44  4958.8  447.90
  5024.2  448.12  5029.3  447.14  5053.0  446.90  5053.5  446.10  5058.5  446.10
  5059.0  446.90  5106.5  448.30  5126.7  450.23  5146.9  453.50  5380.1  458.13
#Mann=3,-1,0
  3818.5     0.1       0  5053.0    0.07       0  5059.0     0.1       0
Bank Sta=5053,5059
Exp/Cntr=0.3,0.1

Type RM Length L Ch R = 1,408,58,58,58
BEGIN DESCRIPTION:
Mapping XS 16ca0588
END DESCRIPTION:
XS GIS Cut Line= 4
      2054539.31     13490194.73      2053531.62     13489640.54
      2053053.32     13489688.29      2052999.02     13489851.17
#Sta/Elev= 30
  3580.8  463.89  3819.3  463.27  4407.4  459.01  4460.5  458.12  4601.4  457.66
  4688.7  456.28  4710.5  456.35  4716.2  457.41  4737.5  458.37  4777.7  458.89
  4824.5  458.18  4829.5  458.87  4888.2  459.14  4925.1  458.16  4930.1  459.57
  4948.5  459.48  5018.9  457.94  5025.6  457.30  5030.7  459.26  5126.2  457.41
  5131.3  459.32  5208.1  457.73  5217.7  458.53  5239.7  454.91  5251.5  454.11
  5252.0  453.31  5257.0  453.31  5257.5  454.11  5271.3  455.36  5383.2  457.47
#Mann=3,-1,0
  3580.8     0.1       0  5251.5    0.07       0  5257.5     0.1       0
Bank Sta=5251.5,5257.5
Exp/Cntr=0.3,0.1

Type RM Length L Ch R = 1,350,80,80,80
BEGIN DESCRIPTION:
Mapping XS 43a182df
END DESCRIPTION:
XS GIS Cut Line= 6
      2054599.98     13490149.99      2053924.02     13489805.62
      2053687.91     13489687.56      2053427.49     13489579.92
      2053027.28     13489671.79      2052975.18     13489826.34
#Sta/Elev= 30
  3486.5  463.79  4209.1  460.09  4635.1  456.40  4659.1  457.62  4664.5  456.67
  4683.0  456.56  4688.4  455.86  4937.7  452.13  4939.2  452.13  4947.3  452.14
  4995.6  449.08  4996.1  448.28  5001.1  448.28  5001.6  449.08  5039.7  451.33
  5091.0  452.32  5121.8  453.72  5142.3  453.48  5183.3  454.55  5191.0  454.03
  5196.1  454.96  5205.8  454.48  5222.5  455.79  5227.8  454.31  5236.6  453.39
  5247.1  453.38  5285.5  455.99  5310.4  456.13  5331.5  457.13  5364.6  457.05
#Mann=5,-1,0
  3486.5     0.1       0  4937.7    0.08       0  4939.2     0.1       0
  4995.6    0.07       0  5001.6     0.1       0
Bank Sta=4995.6,5001.6
Exp/Cntr=0.3,0.1

Type RM Length L Ch R = 1,270,117,117,117
BEGIN DESCRIPTION:
Mapping XS bf92d2b1
END DESCRIPTION:
XS GIS Cut Line= 4
      2054690.34     13490142.64      2053323.83     13489495.10
      2053019.46     13489637.07      2052957.83     13489816.78
#Sta/Elev= 30
  3323.8  463.32  3662.1  462.79  4569.4  456.30  4881.8  452.51  4956.1  451.84
  4986.1  449.09  4989.1  448.21  4989.6  447.41  4994.6  447.41  4995.1  448.21
  5037.8  450.66  5060.7  450.70  5077.7  449.13  5089.0  449.21  5099.5  450.53
  5106.4  449.74  5111.9  451.09  5129.3  449.59  5134.8  451.55  5152.1  449.12
  5157.6  451.36  5165.7  448.54  5171.5  451.94  5198.5  452.76  5211.9  451.85
  5229.8  452.22  5235.1  453.53  5266.3  455.52  5297.6  456.51  5361.8  456.74
#Mann=7,-1,0
  3323.8     0.1       0  4569.4    0.05       0  4881.8    0.08       0
  4986.1    0.05       0  4989.1    0.04       0  4995.1    0.05       0
  5077.7     0.1       0
Bank Sta=4989.1,4995.1
Exp/Cntr=0.3,0.1

Type RM Length L Ch R = 1,153,0,0,0
BEGIN DESCRIPTION:
UNT 151 in Lagunillas Cr Wtrshd 2.0
END DESCRIPTION:
XS GIS Cut Line= 4
      2054600.01     13489650.00      2053351.10     13489329.92
      2053022.77     13489519.88      2052711.94     13490011.22
#Sta/Elev= 30
  3421.7  461.32  3684.9  460.16  4118.5  456.63  4417.9  456.11  4706.2  452.90
  4894.0  451.89  4968.6  450.39  4974.3  447.97  4983.7  448.56  4992.9  445.53
  4993.4  444.73  4998.4  444.73  4998.9  445.53  5001.1  447.19  5005.9  448.85
  5011.6  447.89  5064.7  450.22  5135.3  451.29  5159.8  452.61  5208.2  453.21
  5223.5  454.28  5238.3  453.80  5260.0  455.34  5296.4  455.17  5317.6  456.97
  5323.5  456.16  5368.5  456.30  5417.6  456.83  5448.1  458.13  5671.7  459.69
#Mann=5,-1,0
  3421.7     0.1       0  4992.9    0.07       0  4998.9     0.1       0
  5064.7    0.05       0  5159.8     0.1       0
Bank Sta=4992.9,4998.9
Exp/Cntr=0.3,0.1

Chan Stop Cuts=-1