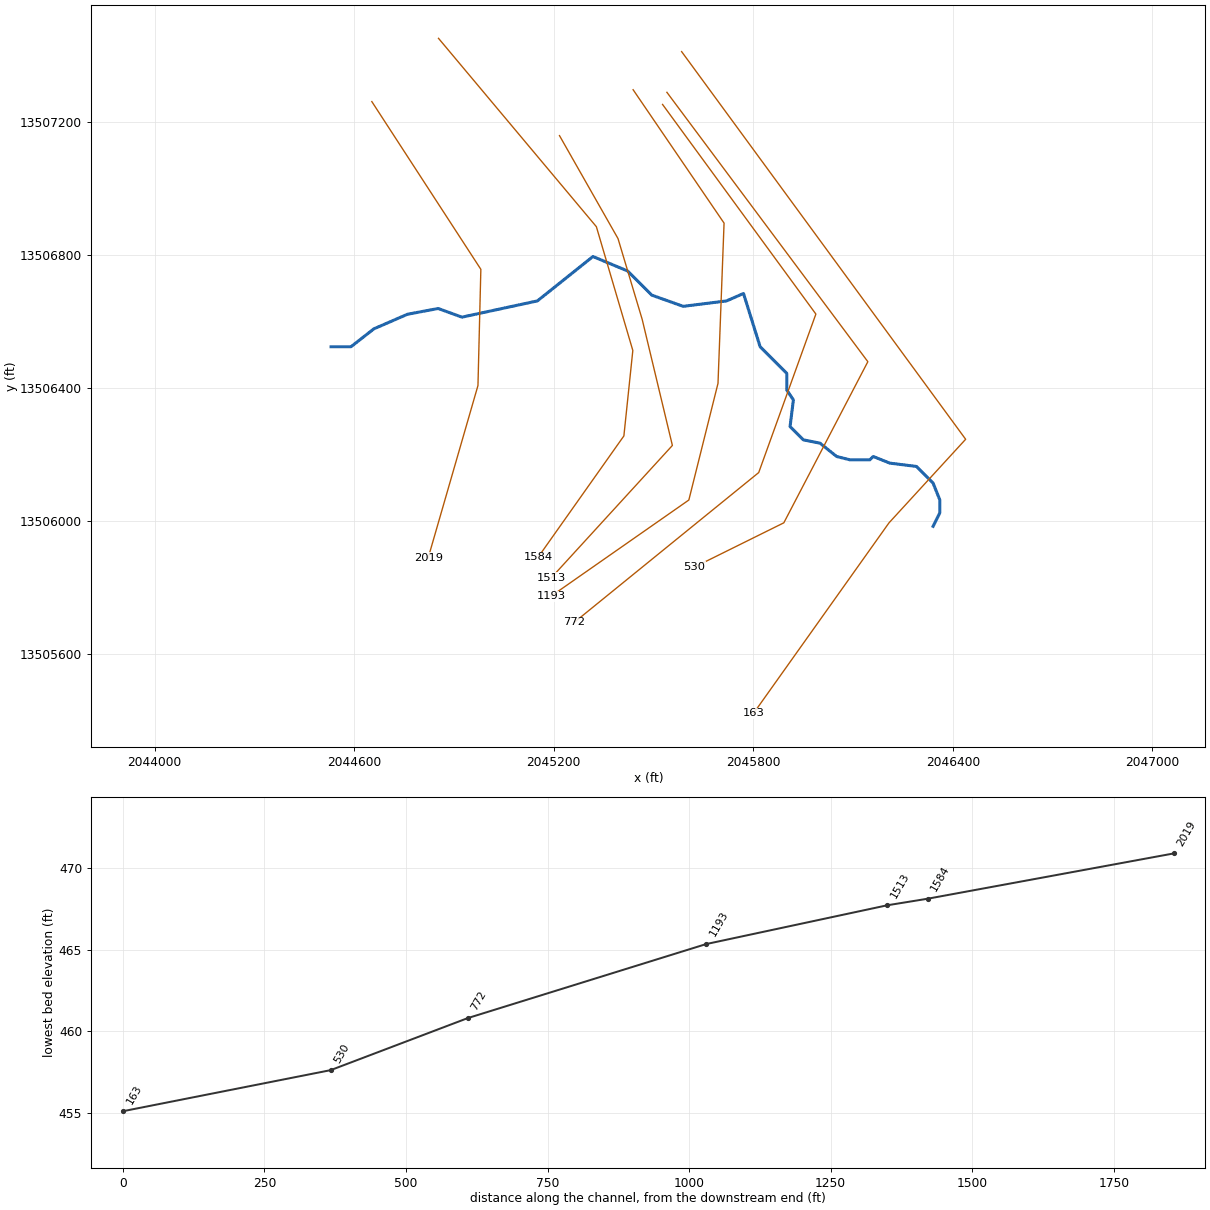
--- UNT 153 in Lagunillas Cr Wtrshd.prj (project) ---

Proj Title=UNT 153 in Lagunillas Cr Wtrshd Base Level Engineering
Current Plan=p01
Default Exp/Contr=0.3,0.1
English Units
Geom File=g01
Flow File=f01
Plan File=p01
BEGIN DESCRIPTION:
UNT 153 in Lagunillas Cr Wtrshd
END DESCRIPTION:

--- UNT 153 in Lagunillas Cr Wtrshd.p01 (plan) ---

Plan Title=Multiple Run
Short Identifier=Multiple
Geom File=g01
Flow File=f01
Subcritical Flow
K Sum by GR= 0
Std Step Tol= 0.01
Critical Tol= 0.01
Num of Std Step Trials= 20
Max Error Tol= 0.3
Flow Tol Ratio= 0.001
Split Flow NTrial= 30
Split Flow Tol= 0.02
Split Flow Ratio= 0.02
Log Output Level= 0
Friction Slope Method= 1
Unsteady Friction Slope Method= 2
Unsteady Bridges Friction Slope Method= 1
Parabolic Critical Depth
Global Vel Dist=  1 , 1 , 1
Global Log Level= 0
CheckData=True
Encroach Param= -1, 0, 0, 0
BEGIN DESCRIPTION:
Multiple Run
END DESCRIPTION:

--- UNT 153 in Lagunillas Cr Wtrshd.f01 (steady flow) ---

Flow Title=Multiple
Number of Profiles=7
Profile Names=10-year,25-year,50-year,1pct_min,100-year,1pct_plu,500-year
River Rch & RM= UNT 153 in Lagun,Reach-1,2019
     158     214     258     156     312     622     459
Boundary for River Rch & Prof#=UNT 153 in Lagun,Reach-1,1
Up Type=0
Dn Type=3
Dn Slope=0.005
Boundary for River Rch & Prof#=UNT 153 in Lagun,Reach-1,2
Up Type=0
Dn Type=3
Dn Slope=0.005
Boundary for River Rch & Prof#=UNT 153 in Lagun,Reach-1,3
Up Type=0
Dn Type=3
Dn Slope=0.005
Boundary for River Rch & Prof#=UNT 153 in Lagun,Reach-1,4
Up Type=0
Dn Type=3
Dn Slope=0.005
Boundary for River Rch & Prof#=UNT 153 in Lagun,Reach-1,5
Up Type=0
Dn Type=3
Dn Slope=0.005
Boundary for River Rch & Prof#=UNT 153 in Lagun,Reach-1,6
Up Type=0
Dn Type=3
Dn Slope=0.005
Boundary for River Rch & Prof#=UNT 153 in Lagun,Reach-1,7
Up Type=0
Dn Type=3
Dn Slope=0.005

--- UNT 153 in Lagunillas Cr Wtrshd.g01 (geometry) ---

Geom Title=Existing Conditions

River Reach=UNT 153 in Lagun,Reach-1
Reach XY= 30
      2044530.80     13506524.54      2044590.80     13506524.54
      2044659.52     13506578.26      2044760.45     13506622.11
      2044852.68     13506639.47      2044924.30     13506613.43
      2045151.08     13506662.26      2045318.18     13506795.72
      2045422.34     13506752.32      2045495.04     13506679.62
      2045589.45     13506645.98      2045719.65     13506662.26
      2045770.80     13506684.54      2045820.80     13506524.54
      2045900.80     13506444.54      2045900.80     13506394.54
      2045920.80     13506364.54      2045910.80     13506284.54
      2045950.80     13506244.54      2046000.80     13506234.54
      2046050.80     13506194.54      2046090.80     13506184.54
      2046150.80     13506184.54      2046160.80     13506194.54
      2046210.80     13506174.54      2046290.80     13506164.54
      2046340.80     13506114.54      2046360.80     13506064.54
      2046360.80     13506024.54      2046340.80     13505984.54

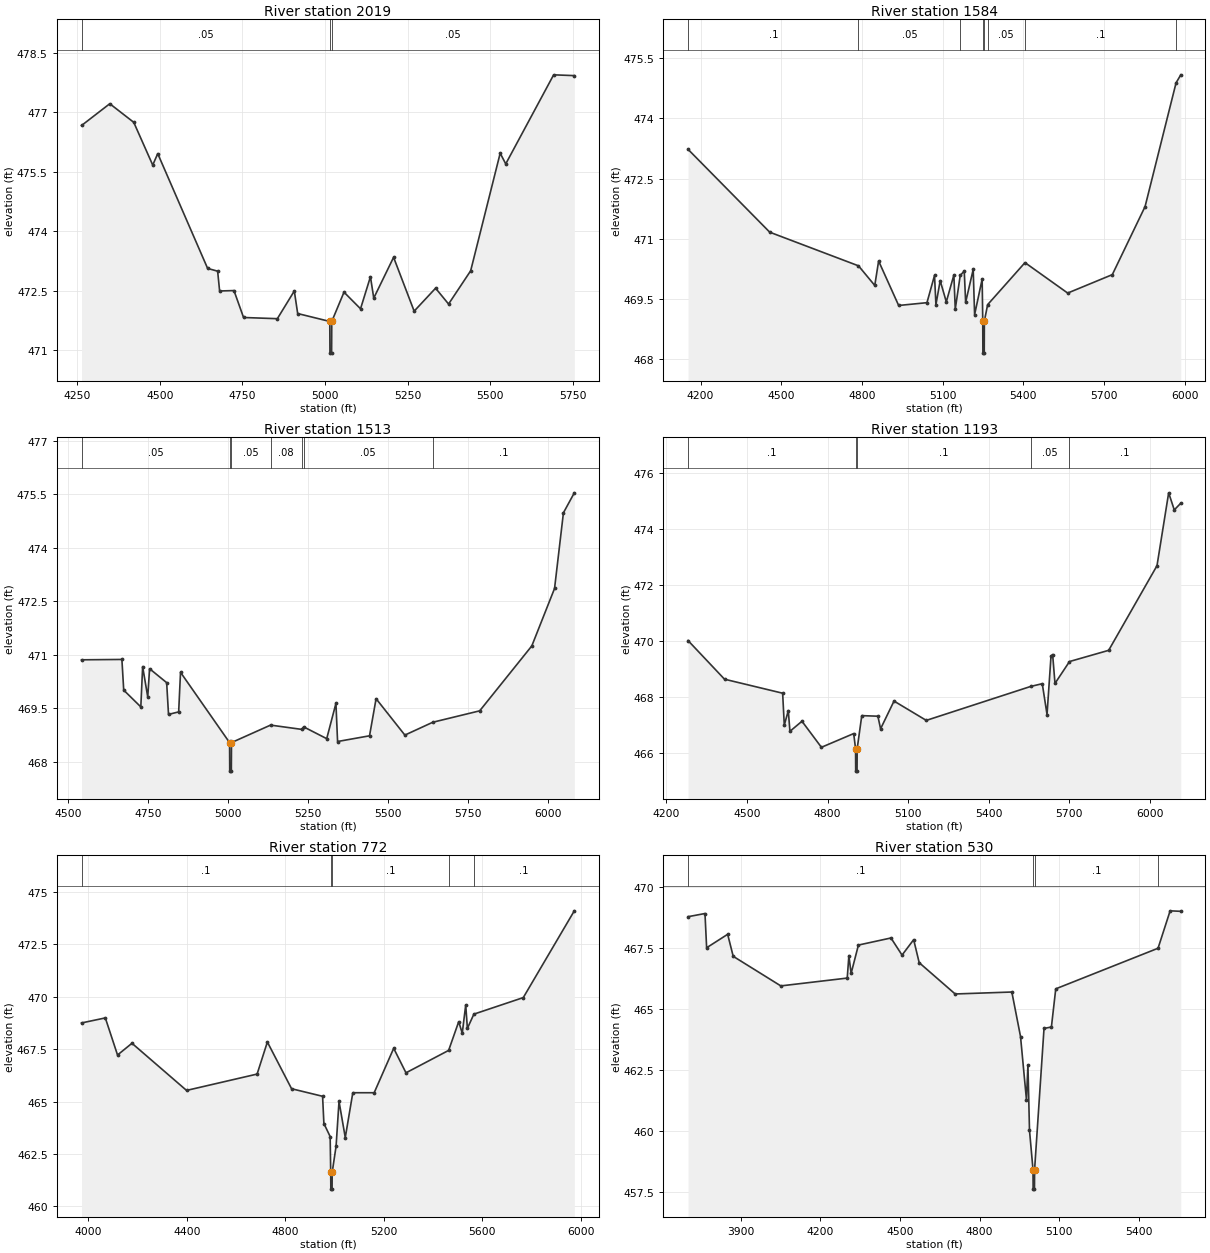
Type RM Length L Ch R = 1,2019,435,435,435
BEGIN DESCRIPTION:
Mapping XS c6e5b57e
END DESCRIPTION:
XS GIS Cut Line= 4
      2044653.38     13507261.54      2044981.16     13506757.23
      2044972.48     13506407.84      2044822.77     13505889.61
#Sta/Elev= 30
  4263.4  476.67  4348.8  477.22  4421.3  476.75  4478.7  475.67  4493.8  475.96
  4644.7  473.06  4675.0  472.99  4681.0  472.49  4724.4  472.50  4753.4  471.82
  4855.6  471.79  4906.9  472.49  4917.1  471.92  5014.2  471.72  5014.7  470.92
  5019.7  470.92  5020.2  471.72  5057.2  472.46  5107.2  472.04  5137.2  472.85
  5147.2  472.31  5207.2  473.34  5269.4  471.98  5334.2  472.56  5373.5  472.16
  5440.3  473.00  5529.6  475.97  5546.4  475.70  5691.3  477.95  5753.8  477.93
#Mann=3,-1,0
  4263.4    0.05       0  5014.2    0.03       0  5020.2    0.05       0
Bank Sta=5014.2,5020.2
Exp/Cntr=0.3,0.1

Type RM Length L Ch R = 1,1584,71,71,71
BEGIN DESCRIPTION:
Mapping XS be6bb50e
END DESCRIPTION:
XS GIS Cut Line= 5
      2044853.86     13507451.70      2045328.46     13506885.41
      2045438.05     13506513.23      2045411.18     13506256.35
      2045153.34     13505891.73
#Sta/Elev= 30
  4153.5  473.23  4457.3  471.16  4787.2  470.32  4847.7  469.83  4862.0  470.44
  4936.5  469.33  5041.7  469.40  5069.8  470.08  5075.0  469.35  5090.9  469.95
  5113.6  469.42  5141.7  470.09  5146.9  469.24  5165.4  470.08  5180.3  470.19
  5185.5  469.41  5213.6  470.23  5218.8  469.10  5246.9  469.99  5249.1  468.94
  5249.6  468.14  5254.6  468.14  5255.1  468.94  5267.2  469.35  5406.1  470.40
  5564.8  469.64  5730.7  470.10  5852.5  471.80  5967.7  474.89  5985.2  475.09
#Mann=8,-1,0
  4153.5     0.1       0  4787.2    0.05       0  5165.4    0.08       0
  5249.1    0.04       0  5255.1    0.08       0  5267.2    0.05       0
  5406.1     0.1       0  5967.7    0.05       0
Bank Sta=5249.1,5255.1
Exp/Cntr=0.3,0.1

Type RM Length L Ch R = 1,1513,320,320,320
BEGIN DESCRIPTION:
Mapping XS 87c481d5
END DESCRIPTION:
XS GIS Cut Line= 5
      2045217.57     13507159.22      2045393.56     13506849.60
      2045466.26     13506606.55      2045557.01     13506227.70
      2045192.75     13505829.61
#Sta/Elev= 30
  4541.7  470.86  4667.7  470.87  4673.4  470.01  4726.8  469.54  4732.5  470.67
  4748.4  469.82  4754.2  470.61  4807.5  470.22  4813.3  469.33  4845.0  469.40
  4850.8  470.51  5004.0  468.54  5004.5  467.74  5009.5  467.74  5010.0  468.54
  5132.0  469.03  5229.3  468.91  5235.5  468.98  5307.4  468.65  5336.2  469.64
  5341.3  468.57  5441.1  468.73  5461.6  469.77  5551.5  468.75  5638.7  469.11
  5785.2  469.43  5948.0  471.25  6019.0  472.86  6046.7  474.98  6080.7  475.54
#Mann=7,-1,0
  4541.7    0.05       0  5004.0    0.04       0  5010.0    0.05       0
  5132.0    0.08       0  5229.3     0.1       0  5235.5    0.05       0
  5638.7     0.1       0
Bank Sta=5004,5010
Exp/Cntr=0.3,0.1

Type RM Length L Ch R = 1,1193,421,421,421
BEGIN DESCRIPTION:
Mapping XS c9159f92
END DESCRIPTION:
XS GIS Cut Line= 5
      2045438.95     13507297.20      2045712.37     13506896.18
      2045694.14     13506414.41      2045606.49     13506063.64
      2045192.44     13505774.58
#Sta/Elev= 30
  4280.5  470.02  4416.3  468.64  4632.7  468.14  4638.8  467.00  4653.7  467.52
  4659.8  466.78  4704.6  467.14  4777.0  466.21  4897.1  466.70  4904.1  466.16
  4904.6  465.36  4909.6  465.36  4910.1  466.16  4927.2  467.34  4987.2  467.32
  4997.2  466.87  5047.2  467.86  5167.3  467.17  5555.3  468.38  5599.0  468.48
  5616.7  467.38  5631.5  469.46  5637.6  469.52  5646.3  468.49  5700.3  469.27
  5846.1  469.67  6026.0  472.69  6069.4  475.29  6090.3  474.68  6114.5  474.92
#Mann=5,-1,0
  4280.5     0.1       0  4904.1    0.07       0  4910.1     0.1       0
  5555.3    0.05       0  5700.3     0.1       0
Bank Sta=4904.1,4910.1
Exp/Cntr=0.3,0.1

Type RM Length L Ch R = 1,772,242,242,242
BEGIN DESCRIPTION:
Mapping XS 05222c8c
END DESCRIPTION:
XS GIS Cut Line= 4
      2045527.49     13507252.93      2045988.41     13506622.74
      2045816.54     13506146.18      2045262.72     13505696.43
#Sta/Elev= 30
  3972.5  468.75  4069.0  468.99  4118.6  467.22  4177.2  467.78  4398.8  465.53
  4685.3  466.31  4727.0  467.84  4825.3  465.61  4951.2  465.25  4956.5  463.95
  4981.9  463.33  4984.2  461.62  4984.7  460.82  4989.7  460.82  4990.2  461.62
  5006.0  462.87  5017.9  465.01  5043.3  463.28  5073.9  465.42  5160.7  465.42
  5239.9  467.54  5289.8  466.37  5463.0  467.44  5503.9  468.81  5518.3  468.26
  5532.4  469.61  5539.1  468.49  5565.5  469.17  5766.1  469.96  5973.3  474.10
#Mann=5,-1,0
  3972.5     0.1       0  4984.2    0.07       0  4990.2     0.1       0
  5463.0    0.05       0  5565.5     0.1       0
Bank Sta=4984.2,4990.2
Exp/Cntr=0.3,0.1

Type RM Length L Ch R = 1,530,367,367,367
BEGIN DESCRIPTION:
Mapping XS d50c2d27
END DESCRIPTION:
XS GIS Cut Line= 4
      2045540.49     13507289.42      2046144.66     13506479.51
      2045892.06     13505995.14      2045623.86     13505862.34
#Sta/Elev= 30
  3702.0  468.77  3765.9  468.90  3772.1  467.50  3851.3  468.05  3872.2  467.15
  4051.5  465.94  4301.7  466.26  4307.9  467.18  4316.3  466.45  4343.8  467.61
  4466.4  467.90  4508.1  467.20  4551.9  467.83  4572.7  466.89  4708.2  465.61
  4921.7  465.69  4954.4  463.87  4976.7  461.29  4982.3  462.71  4988.2  460.03
  5001.4  458.43  5001.9  457.63  5006.9  457.63  5007.4  458.43  5042.9  464.20
  5070.7  464.26  5087.1  465.82  5472.4  467.48  5517.9  469.01  5558.0  468.99
#Mann=4,-1,0
  3702.0     0.1       0  5001.4    0.07       0  5007.4     0.1       0
  5472.4    0.08       0
Bank Sta=5001.4,5007.4
Exp/Cntr=0.3,0.1

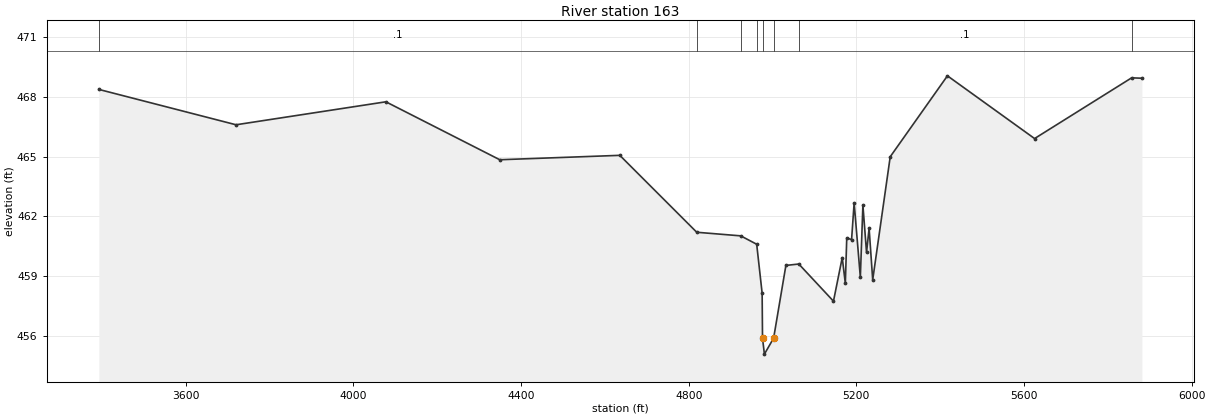
Type RM Length L Ch R = 1,163,0,0,0
BEGIN DESCRIPTION:
UNT 153 in Lagunillas Cr Wtrshd 2.0
END DESCRIPTION:
XS GIS Cut Line= 4
      2045584.77     13507411.80      2046438.70     13506246.30
      2046208.23     13505995.00      2045800.90     13505422.20
#Sta/Elev= 30
  3392.6  468.36  3720.0  466.59  4077.5  467.74  4349.2  464.84  4635.6  465.06
  4819.2  461.21  4924.1  461.03  4962.2  460.61  4975.2  458.16  4976.1  455.91
  4980.6  455.11  5002.6  455.91  5031.9  459.55  5062.7  459.62  5145.4  457.76
  5166.3  459.94  5173.7  458.65  5177.1  460.93  5188.6  460.84  5194.7  462.68
  5209.5  458.96  5215.6  462.57  5224.3  460.20  5230.4  461.41  5239.0  458.83
  5280.8  464.99  5417.3  469.04  5625.2  465.90  5856.8  468.94  5881.3  468.92
#Mann=8,-1,0
  3392.6     0.1       0  4819.2    0.07       0  4924.1     0.1       0
  4962.2    0.07       0  4976.1    0.07       0  5002.6    0.07       0
  5062.7     0.1       0  5856.8    0.05       0
Bank Sta=4976.1,5002.6
Exp/Cntr=0.3,0.1

Chan Stop Cuts=-1