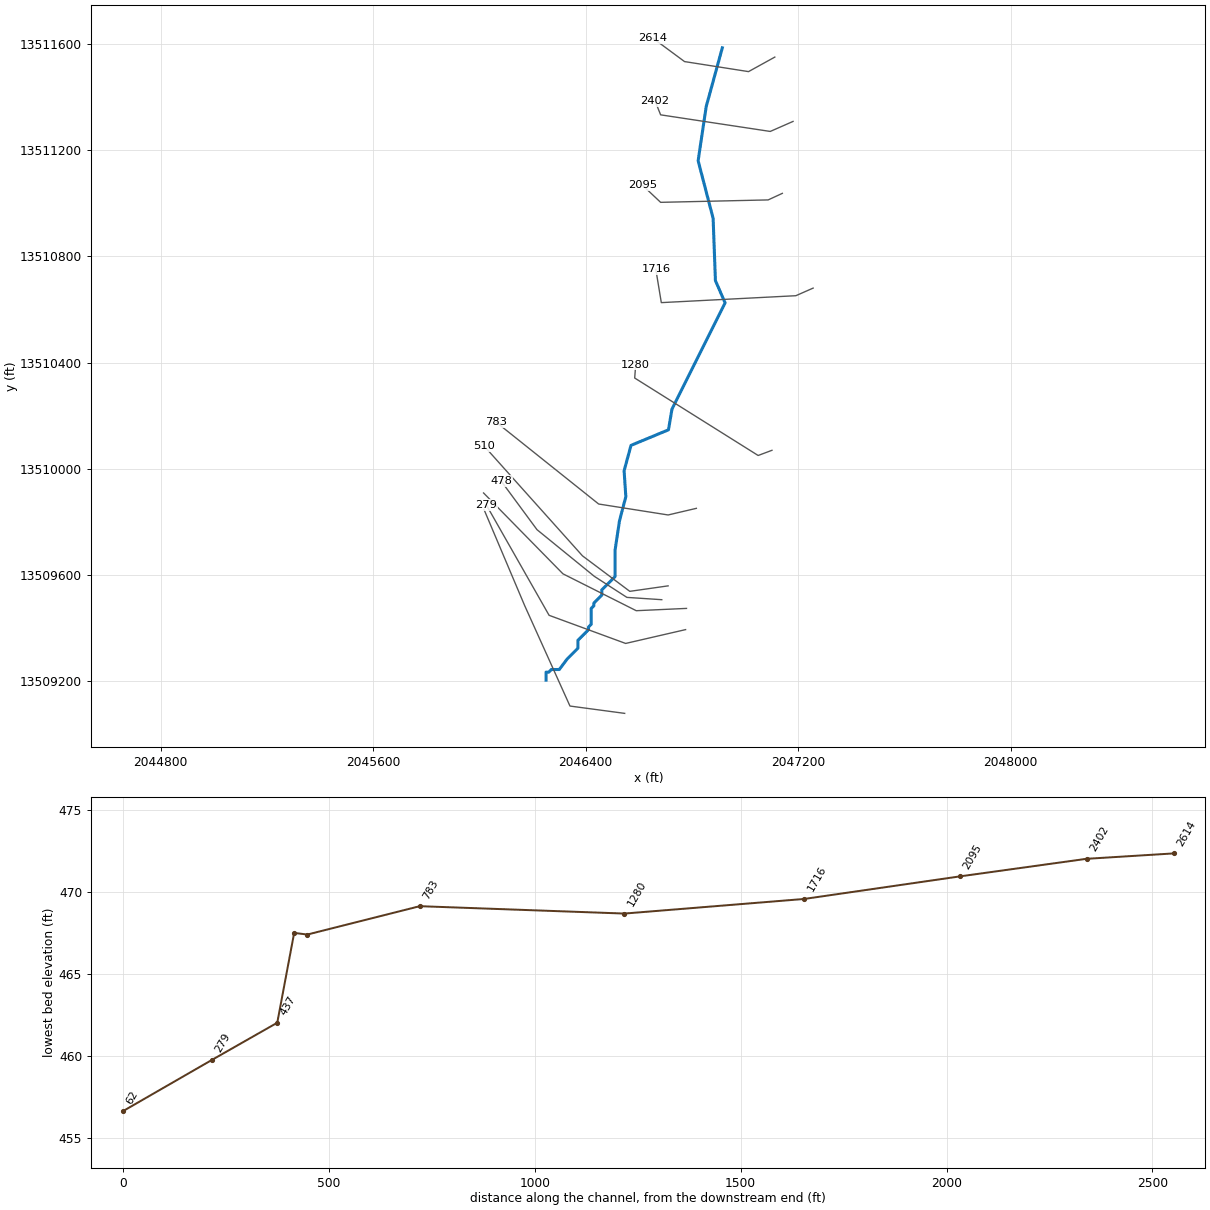
--- UNT 155 in Lagunillas Cr Wtrshd.prj (project) ---

Proj Title=UNT 155 in Lagunillas Cr Wtrshd Base Level Engineering
Current Plan=p01
Default Exp/Contr=0.3,0.1
English Units
Geom File=g01
Flow File=f01
Plan File=p01
BEGIN DESCRIPTION:
UNT 155 in Lagunillas Cr Wtrshd
END DESCRIPTION:

--- UNT 155 in Lagunillas Cr Wtrshd.p01 (plan) ---

Plan Title=Multiple Run
Short Identifier=Multiple
Geom File=g01
Flow File=f01
Subcritical Flow
K Sum by GR= 0
Std Step Tol= 0.01
Critical Tol= 0.01
Num of Std Step Trials= 20
Max Error Tol= 0.3
Flow Tol Ratio= 0.001
Split Flow NTrial= 30
Split Flow Tol= 0.02
Split Flow Ratio= 0.02
Log Output Level= 0
Friction Slope Method= 1
Unsteady Friction Slope Method= 2
Unsteady Bridges Friction Slope Method= 1
Parabolic Critical Depth
Global Vel Dist=  1 , 1 , 1
Global Log Level= 0
CheckData=True
Encroach Param= -1, 0, 0, 0
BEGIN DESCRIPTION:
Multiple Run
END DESCRIPTION:

--- UNT 155 in Lagunillas Cr Wtrshd.f01 (steady flow) ---

Flow Title=Multiple
Number of Profiles=7
Profile Names=10-year,25-year,50-year,1pct_min,100-year,1pct_plu,500-year
River Rch & RM= UNT 155 in Lagun,Reach-1,2614
      63      79      92      54     107     214     147
Boundary for River Rch & Prof#=UNT 155 in Lagun,Reach-1,1
Up Type=0
Dn Type=3
Dn Slope=0.005
Boundary for River Rch & Prof#=UNT 155 in Lagun,Reach-1,2
Up Type=0
Dn Type=3
Dn Slope=0.005
Boundary for River Rch & Prof#=UNT 155 in Lagun,Reach-1,3
Up Type=0
Dn Type=3
Dn Slope=0.005
Boundary for River Rch & Prof#=UNT 155 in Lagun,Reach-1,4
Up Type=0
Dn Type=3
Dn Slope=0.005
Boundary for River Rch & Prof#=UNT 155 in Lagun,Reach-1,5
Up Type=0
Dn Type=3
Dn Slope=0.005
Boundary for River Rch & Prof#=UNT 155 in Lagun,Reach-1,6
Up Type=0
Dn Type=3
Dn Slope=0.005
Boundary for River Rch & Prof#=UNT 155 in Lagun,Reach-1,7
Up Type=0
Dn Type=3
Dn Slope=0.005

--- UNT 155 in Lagunillas Cr Wtrshd.g01 (geometry) ---

Geom Title=Existing Conditions

River Reach=UNT 155 in Lagun,Reach-1
Reach XY= 30
      2046914.63     13511585.51      2046853.87     13511364.16
      2046823.48     13511160.16      2046879.91     13510943.15
      2046888.59     13510708.78      2046925.00     13510625.00
      2046725.00     13510225.00      2046711.84     13510147.02
      2046570.78     13510088.42      2046544.74     13509992.94
      2046551.25     13509895.28      2046527.37     13509804.14
      2046510.80     13509694.54      2046510.80     13509594.54
      2046460.80     13509544.54      2046460.80     13509524.54
      2046430.80     13509494.54      2046430.80     13509484.54
      2046420.80     13509474.54      2046420.80     13509414.54
      2046410.80     13509404.54      2046410.80     13509394.54
      2046370.80     13509354.54      2046370.80     13509324.54
      2046330.80     13509284.54      2046300.80     13509244.54
      2046270.80     13509244.54      2046260.80     13509234.54
      2046250.80     13509234.54      2046250.80     13509204.54

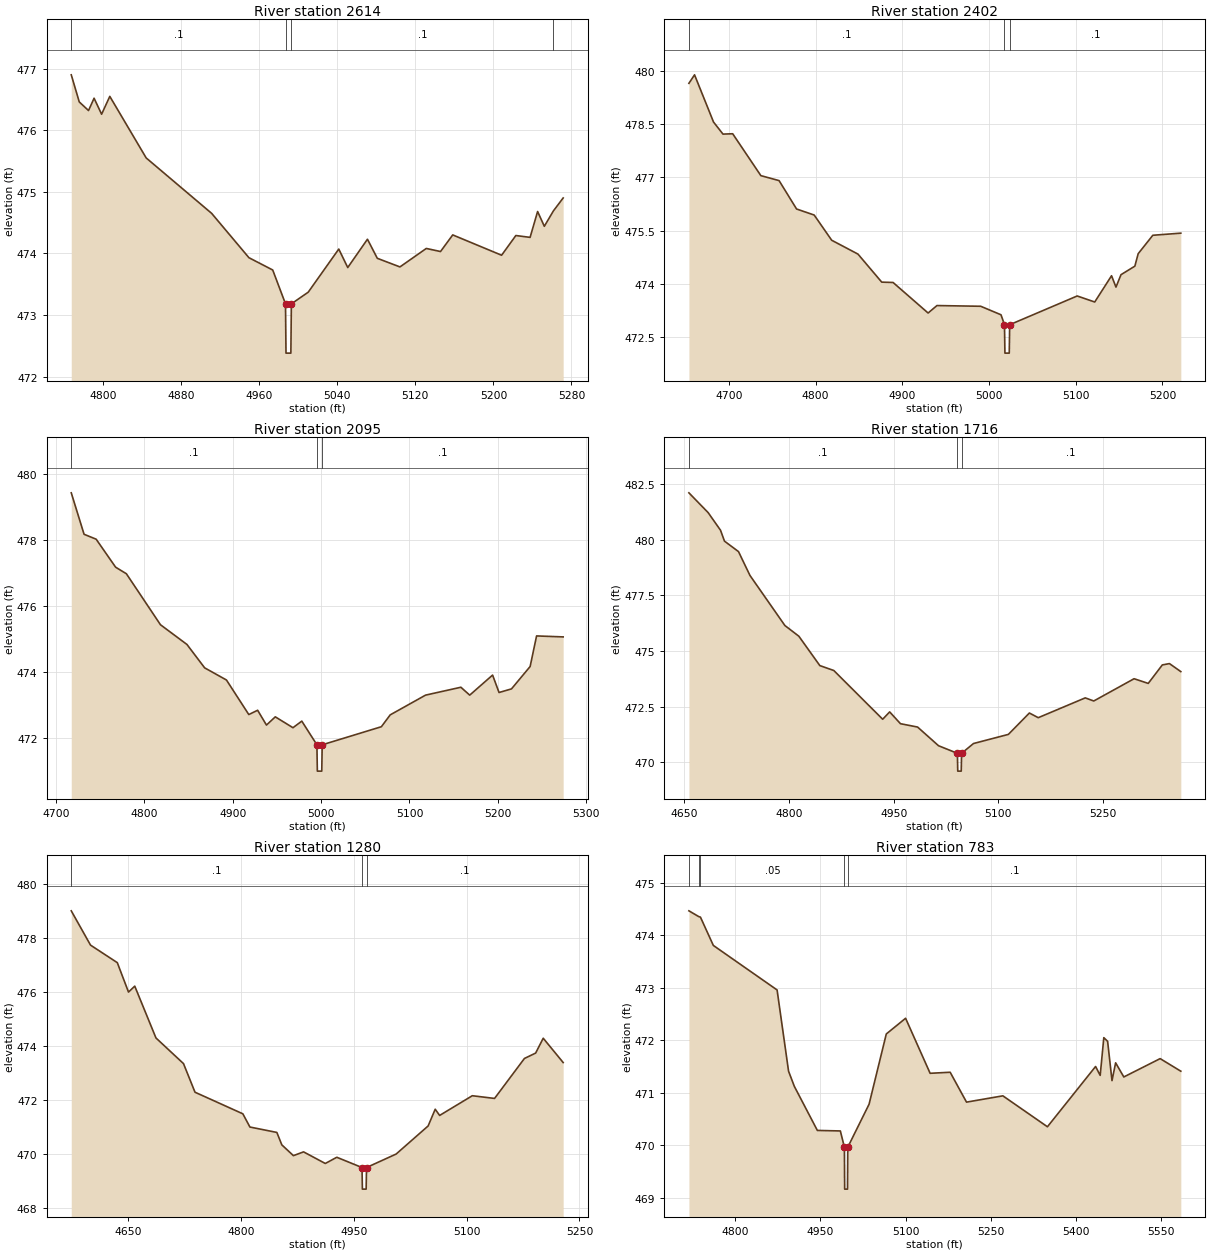
Type RM Length L Ch R = 1,2614,212,212,212
BEGIN DESCRIPTION:
UNT 155 in Lagunillas Cr Wtrshd 2.0
END DESCRIPTION:
XS GIS Cut Line= 4
      2047112.20     13511550.38      2047013.22     13511495.68
      2046772.33     13511533.44      2046653.89     13511620.98
#Sta/Elev= 30
  4767.3  476.90  4775.5  476.46  4785.0  476.32  4790.7  476.52  4798.4  476.26
  4806.8  476.55  4844.1  475.55  4911.2  474.65  4949.4  473.93  4973.8  473.73
  4986.9  473.18  4987.4  472.38  4992.4  472.38  4992.9  473.18  5010.2  473.37
  5041.5  474.07  5050.7  473.77  5070.9  474.23  5081.0  473.92  5104.2  473.78
  5131.2  474.08  5145.8  474.03  5158.3  474.30  5208.4  473.97  5223.0  474.29
  5237.6  474.26  5245.3  474.68  5252.2  474.44  5261.5  474.69  5271.5  474.90
#Mann=4,-1,0
  4767.3     0.1       0  4986.9    0.07       0  4992.9     0.1       0
  5261.5    0.05       0
Bank Sta=4986.9,4992.9
Exp/Cntr=0.3,0.1

Type RM Length L Ch R = 1,2402,307,307,307
BEGIN DESCRIPTION:
Mapping XS 9cead934
END DESCRIPTION:
XS GIS Cut Line= 4
      2047180.96     13511308.20      2047095.02     13511270.44
      2046682.26     13511332.94      2046661.44     13511384.99
#Sta/Elev= 30
  4653.8  479.65  4660.3  479.89  4682.2  478.56  4693.1  478.22  4704.3  478.23
  4736.8  477.05  4757.8  476.91  4778.0  476.11  4798.3  475.94  4818.5  475.23
  4848.8  474.84  4876.2  474.05  4889.3  474.04  4929.7  473.18  4939.9  473.39
  4990.4  473.37  5013.8  473.13  5017.8  472.85  5018.3  472.05  5023.3  472.05
  5023.8  472.85  5101.7  473.66  5121.9  473.49  5141.3  474.23  5146.4  473.91
  5152.2  474.26  5168.2  474.50  5172.0  474.85  5188.9  475.37  5221.2  475.43
#Mann=3,-1,0
  4653.8     0.1       0  5017.8    0.07       0  5023.8     0.1       0
Bank Sta=5017.8,5023.8
Exp/Cntr=0.3,0.1

Type RM Length L Ch R = 1,2095,379,379,379
BEGIN DESCRIPTION:
Mapping XS c39c4cc4
END DESCRIPTION:
XS GIS Cut Line= 4
      2047140.55     13511037.35      2047087.20     13511012.63
      2046682.26     13511003.51      2046614.53     13511067.33
#Sta/Elev= 30
  4717.1  479.44  4731.6  478.18  4745.3  478.03  4767.3  477.18  4779.5  476.98
  4818.1  475.43  4848.1  474.83  4868.1  474.12  4892.8  473.75  4918.1  472.70
  4928.1  472.83  4938.1  472.38  4948.1  472.63  4968.1  472.30  4978.1  472.50
  4995.2  471.78  4995.7  470.98  5000.7  470.98  5001.2  471.78  5068.2  472.33
  5078.2  472.69  5118.2  473.29  5158.2  473.53  5168.2  473.29  5194.1  473.90
  5201.4  473.37  5215.5  473.48  5236.6  474.16  5243.9  475.09  5274.0  475.06
#Mann=3,-1,0
  4717.1     0.1       0  4995.2    0.07       0  5001.2     0.1       0
Bank Sta=4995.2,5001.2
Exp/Cntr=0.3,0.1

Type RM Length L Ch R = 1,1716,436,436,436
BEGIN DESCRIPTION:
Mapping XS 266fae75
END DESCRIPTION:
XS GIS Cut Line= 4
      2047256.48     13510680.60      2047191.37     13510651.95
      2046684.86     13510625.91      2046664.21     13510751.10
#Sta/Elev= 30
  4656.5  482.10  4684.1  481.21  4701.8  480.42  4707.5  479.93  4727.6  479.46
  4744.0  478.39  4794.1  476.14  4814.1  475.66  4844.2  474.34  4864.2  474.12
  4934.3  471.93  4944.3  472.26  4959.8  471.73  4984.3  471.58  5014.4  470.74
  5041.4  470.40  5041.9  469.60  5046.9  469.60  5047.4  470.40  5064.5  470.84
  5114.5  471.25  5144.6  472.21  5157.3  472.00  5224.7  472.89  5236.9  472.75
  5294.7  473.75  5315.0  473.54  5335.2  474.37  5345.4  474.43  5361.7  474.07
#Mann=3,-1,0
  4656.5     0.1       0  5041.4    0.07       0  5047.4     0.1       0
Bank Sta=5041.4,5047.4
Exp/Cntr=0.3,0.1

Type RM Length L Ch R = 1,1280,497,497,497
BEGIN DESCRIPTION:
Mapping XS 4fe4c0f8
END DESCRIPTION:
XS GIS Cut Line= 4
      2047101.49     13510069.90      2047049.44     13510050.39
      2046584.60     13510342.05      2046588.40     13510391.45
#Sta/Elev= 30
  4574.4  479.02  4600.0  477.75  4635.6  477.10  4650.5  476.01  4658.8  476.23
  4687.0  474.31  4723.6  473.36  4738.9  472.30  4802.5  471.50  4811.9  471.01
  4847.7  470.81  4854.3  470.35  4869.7  469.95  4883.2  470.09  4912.1  469.66
  4927.4  469.89  4960.9  469.51  4961.4  468.71  4966.4  468.71  4966.9  469.51
  5006.3  470.01  5048.8  471.05  5058.2  471.67  5064.1  471.44  5107.5  472.17
  5137.1  472.07  5176.8  473.55  5191.7  473.75  5201.8  474.30  5228.3  473.40
#Mann=3,-1,0
  4574.4     0.1       0  4960.9    0.07       0  4966.9     0.1       0
Bank Sta=4960.9,4966.9
Exp/Cntr=0.3,0.1

Type RM Length L Ch R = 1,783,273,273,273
BEGIN DESCRIPTION:
Mapping XS 53e2a423
END DESCRIPTION:
XS GIS Cut Line= 4
      2046816.85     13509851.39      2046710.47     13509826.43
      2046448.97     13509867.66      2046064.29     13510174.87
#Sta/Elev= 30
  4718.4  474.47  4735.7  474.36  4738.7  474.35  4761.4  473.81  4873.7  472.96
  4893.9  471.41  4904.1  471.12  4944.6  470.28  4985.1  470.27  4992.2  469.96
  4992.7  469.16  4997.7  469.16  4998.2  469.96  5035.7  470.78  5066.0  472.12
  5100.0  472.42  5143.2  471.37  5178.5  471.39  5207.3  470.82  5271.3  470.94
  5349.8  470.35  5434.6  471.50  5442.7  471.33  5449.1  472.05  5455.8  471.98
  5463.5  471.23  5469.9  471.57  5484.3  471.30  5548.3  471.65  5584.7  471.41
#Mann=5,-1,0
  4718.4    0.05       0  4735.7     0.1       0  4738.7    0.05       0
  4992.2    0.07       0  4998.2     0.1       0
Bank Sta=4992.2,4998.2
Exp/Cntr=0.3,0.1

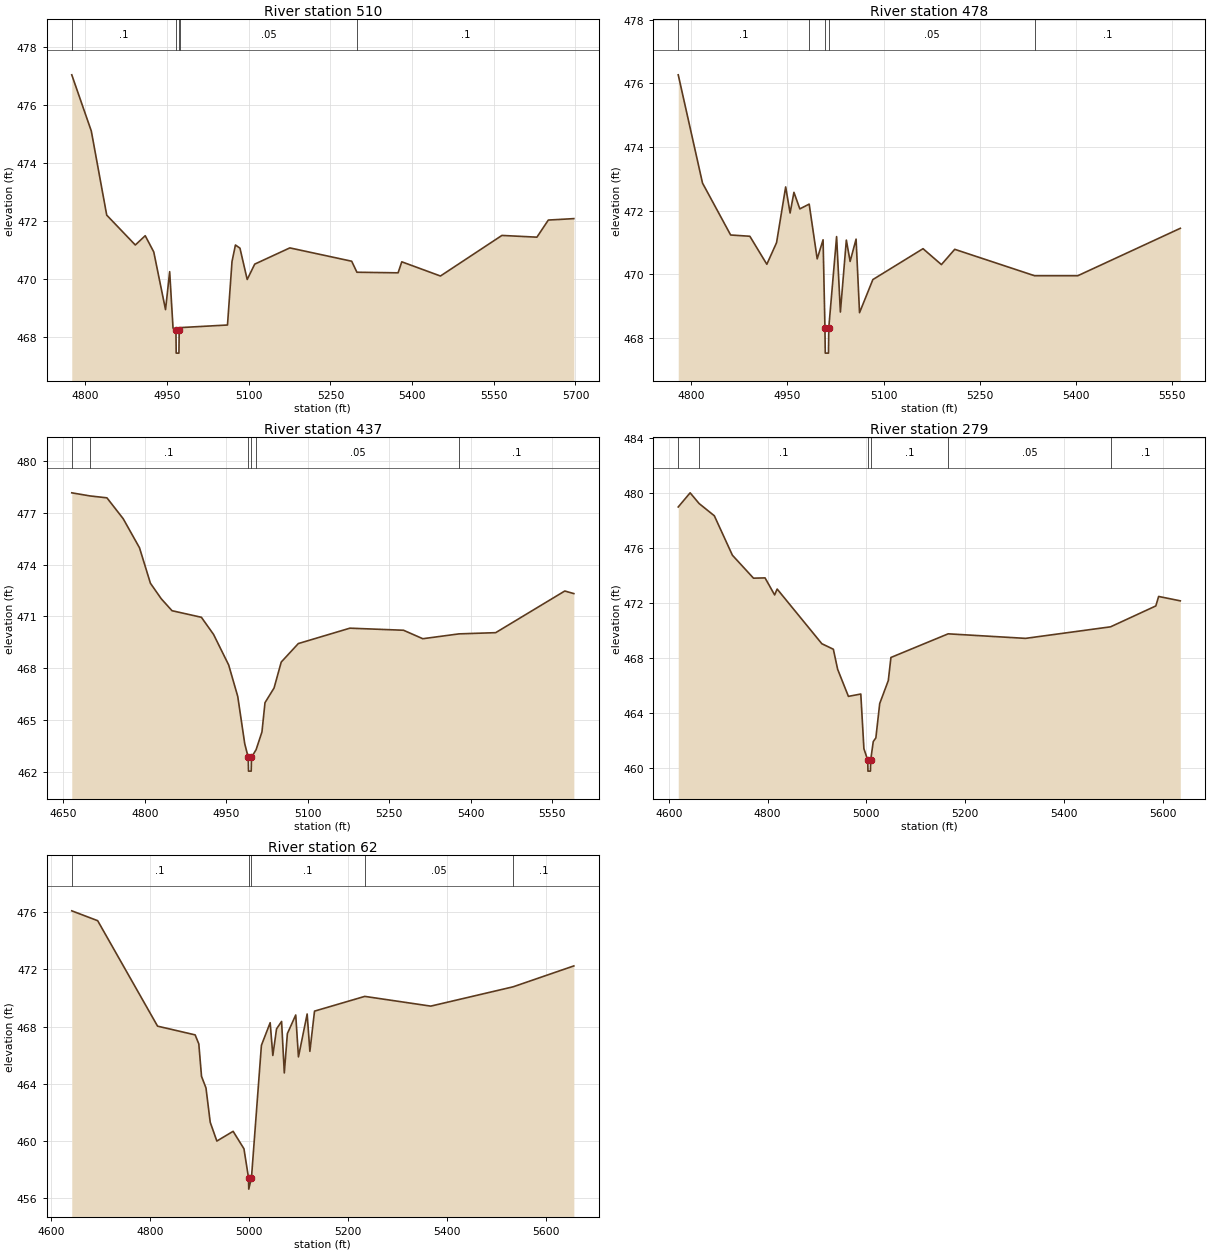
Type RM Length L Ch R = 1,510,32,32,32
BEGIN DESCRIPTION:
Mapping XS adb3cd4b
END DESCRIPTION:
XS GIS Cut Line= 4
      2046710.50     13509559.50      2046566.15     13509538.88
      2046388.20     13509672.35      2046018.68     13510084.91
#Sta/Elev= 30
  4774.9  477.03  4810.8  475.09  4839.1  472.19  4891.6  471.16  4909.8  471.48
  4925.5  470.92  4947.1  468.93  4954.7  470.24  4960.9  468.29  4966.2  468.23
  4966.7  467.43  4971.7  467.43  4972.2  468.23  4973.9  468.31  5060.9  468.40
  5069.2  470.59  5075.5  471.16  5083.8  471.05  5097.1  469.97  5110.9  470.50
  5175.4  471.06  5289.0  470.60  5298.6  470.22  5374.2  470.20  5381.0  470.58
  5452.0  470.09  5564.9  471.49  5629.2  471.43  5650.1  472.02  5697.0  472.07
#Mann=5,-1,0
  4774.9     0.1       0  4966.2    0.03       0  4972.2     0.1       0
  4973.9    0.05       0  5298.6     0.1       0
Bank Sta=4966.2,4972.2
Exp/Cntr=0.3,0.1

Type RM Length L Ch R = 1,478,41,41,41
BEGIN DESCRIPTION:
Mapping XS 7b5bc882
END DESCRIPTION:
XS GIS Cut Line= 5
      2046686.59     13509507.42      2046555.30     13509516.10
      2046432.69     13509595.31      2046216.76     13509771.09
      2046081.64     13509954.38
#Sta/Elev= 30
  4779.5  476.27  4817.4  472.87  4861.3  471.24  4891.3  471.20  4917.8  470.32
  4933.0  471.00  4947.2  472.75  4954.1  471.93  4960.1  472.58  4969.3  472.06
  4983.9  472.21  4996.4  470.49  5005.6  471.09  5008.5  468.33  5009.0  467.53
  5014.0  467.53  5014.5  468.33  5026.7  471.19  5032.6  468.82  5041.9  471.08
  5047.8  470.41  5057.1  471.11  5062.5  468.80  5083.3  469.84  5161.6  470.81
  5190.3  470.31  5211.1  470.79  5335.8  469.96  5403.1  469.96  5563.2  471.45
#Mann=5,-1,0
  4779.5     0.1       0  4983.9    0.05       0  5008.5    0.03       0
  5014.5    0.05       0  5335.8     0.1       0
Bank Sta=5008.5,5014.5
Exp/Cntr=0.3,0.1

Type RM Length L Ch R = 1,437,158,158,158
BEGIN DESCRIPTION:
Mapping XS 4a9fae8d
END DESCRIPTION:
XS GIS Cut Line= 4
      2046779.71     13509474.65      2046590.46     13509465.97
      2046314.42     13509604.86      2046015.64     13509909.27
#Sta/Elev= 30
  4665.4  478.15  4699.1  477.97  4730.2  477.86  4760.2  476.65  4790.2  474.97
  4810.3  472.92  4830.3  472.02  4850.1  471.33  4904.2  470.95  4926.6  469.96
  4954.5  468.19  4971.2  466.37  4984.1  463.63  4990.5  462.85  4991.0  462.05
  4996.0  462.05  4996.5  462.85  5005.0  463.29  5015.8  464.32  5021.4  466.01
  5038.1  466.86  5051.3  468.36  5082.8  469.43  5177.8  470.32  5276.6  470.20
  5312.1  469.71  5378.8  469.99  5446.4  470.06  5573.7  472.47  5590.4  472.32
#Mann=6,-1,0
  4665.4    0.05       0  4699.1     0.1       0  4990.5    0.07       0
  4996.5     0.1       0  5005.0    0.05       0  5378.8     0.1       0
Bank Sta=4990.5,4996.5
Exp/Cntr=0.3,0.1

Type RM Length L Ch R = 1,279,217,217,217
BEGIN DESCRIPTION:
Mapping XS a71d49ef
END DESCRIPTION:
XS GIS Cut Line= 4
      2046776.25     13509394.79      2046550.53     13509342.70
      2046262.33     13509448.61      2046026.06     13509864.14
#Sta/Elev= 30
  4619.1  479.01  4643.2  480.04  4661.4  479.26  4692.2  478.37  4728.8  475.50
  4771.5  473.83  4794.9  473.85  4814.3  472.61  4819.4  473.04  4909.9  469.06
  4933.2  468.66  4941.9  467.20  4963.7  465.23  4988.8  465.40  4995.1  461.42
  5002.8  460.59  5003.3  459.79  5008.3  459.79  5008.8  460.59  5014.0  461.94
  5019.3  462.21  5027.1  464.71  5044.5  466.38  5049.8  468.06  5165.7  469.78
  5322.4  469.45  5494.6  470.29  5586.2  471.81  5591.9  472.50  5635.8  472.18
#Mann=6,-1,0
  4619.1    0.05       0  4661.4     0.1       0  5002.8    0.07       0
  5008.8     0.1       0  5165.7    0.05       0  5494.6     0.1       0
Bank Sta=5002.8,5008.8
Exp/Cntr=0.3,0.1

Type RM Length L Ch R = 1,62,0,0,0
BEGIN DESCRIPTION:
UNT 155 in Lagunillas Cr Wtrshd 1.0
END DESCRIPTION:
XS GIS Cut Line= 4
      2046546.94     13509079.40      2046340.97     13509106.99
      2046170.16     13509485.66      2046017.39     13509846.75
#Sta/Elev= 30
  4641.3  476.10  4693.7  475.41  4814.8  468.04  4890.8  467.43  4898.2  466.80
  4903.7  464.53  4912.7  463.72  4921.3  461.32  4934.7  460.01  4967.6  460.69
  4989.5  459.47  4998.7  457.45  4999.2  456.65  5004.7  457.45  5024.8  466.70
  5042.5  468.28  5047.9  465.99  5055.4  467.85  5065.6  468.37  5071.1  464.77
  5077.3  467.52  5094.2  468.82  5099.7  465.89  5117.3  468.89  5122.8  466.28
  5132.2  469.09  5233.8  470.12  5367.3  469.44  5533.9  470.79  5656.6  472.25
#Mann=5,-1,0
  4641.3     0.1       0  4998.7    0.07       0  5004.7     0.1       0
  5233.8    0.05       0  5533.9     0.1       0
Bank Sta=4998.7,5004.7
Exp/Cntr=0.3,0.1

Chan Stop Cuts=-1