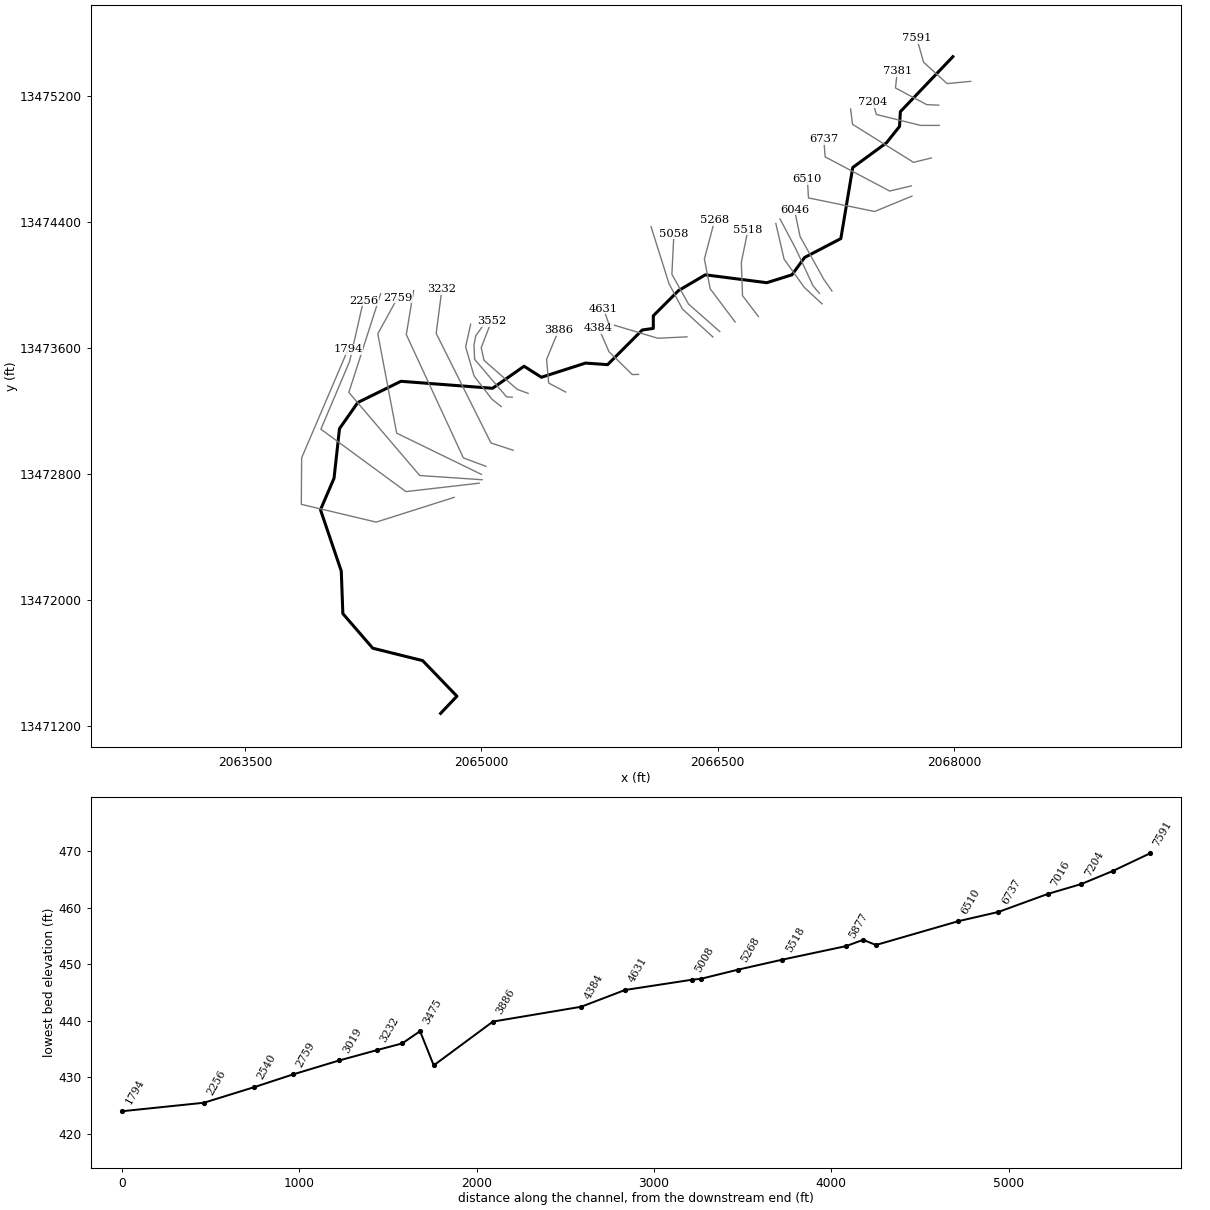
--- UNT 156 in Lagunillas Cr Wtrshd.prj (project) ---

Proj Title=UNT 156 in Lagunillas Cr Wtrshd Base Level Engineering
Current Plan=p01
Default Exp/Contr=0.3,0.1
English Units
Geom File=g01
Flow File=f01
Plan File=p01
BEGIN DESCRIPTION:
UNT 156 in Lagunillas Cr Wtrshd
END DESCRIPTION:

--- UNT 156 in Lagunillas Cr Wtrshd.p01 (plan) ---

Plan Title=Multiple Run
Short Identifier=Multiple
Geom File=g01
Flow File=f01
Subcritical Flow
K Sum by GR= 0
Std Step Tol= 0.01
Critical Tol= 0.01
Num of Std Step Trials= 20
Max Error Tol= 0.3
Flow Tol Ratio= 0.001
Split Flow NTrial= 30
Split Flow Tol= 0.02
Split Flow Ratio= 0.02
Log Output Level= 0
Friction Slope Method= 1
Unsteady Friction Slope Method= 2
Unsteady Bridges Friction Slope Method= 1
Parabolic Critical Depth
Global Vel Dist=  1 , 1 , 1
Global Log Level= 0
CheckData=True
Encroach Param= -1, 0, 0, 0
BEGIN DESCRIPTION:
Multiple Run
END DESCRIPTION:

--- UNT 156 in Lagunillas Cr Wtrshd.f01 (steady flow) ---

Flow Title=Multiple
Number of Profiles=7
Profile Names=10-year,25-year,50-year,1pct_min,100-year,1pct_plu,500-year
River Rch & RM= UNT 156 in Lagun,Reach-1,7591
      84     109     128      75     150     300     210
Boundary for River Rch & Prof#=UNT 156 in Lagun,Reach-1,1
Up Type=0
Dn Type=3
Dn Slope=0.005
Boundary for River Rch & Prof#=UNT 156 in Lagun,Reach-1,2
Up Type=0
Dn Type=3
Dn Slope=0.005
Boundary for River Rch & Prof#=UNT 156 in Lagun,Reach-1,3
Up Type=0
Dn Type=3
Dn Slope=0.005
Boundary for River Rch & Prof#=UNT 156 in Lagun,Reach-1,4
Up Type=0
Dn Type=3
Dn Slope=0.005
Boundary for River Rch & Prof#=UNT 156 in Lagun,Reach-1,5
Up Type=0
Dn Type=3
Dn Slope=0.005
Boundary for River Rch & Prof#=UNT 156 in Lagun,Reach-1,6
Up Type=0
Dn Type=3
Dn Slope=0.005
Boundary for River Rch & Prof#=UNT 156 in Lagun,Reach-1,7
Up Type=0
Dn Type=3
Dn Slope=0.005

--- UNT 156 in Lagunillas Cr Wtrshd.g01 (geometry) ---

Geom Title=Existing Conditions

River Reach=UNT 156 in Lagun,Reach-1
Reach XY= 30
      2067991.80     13475448.74      2067658.46     13475099.78
      2067653.25     13475006.03      2067569.92     13474901.86
      2067356.38     13474745.61      2067280.80     13474294.54
      2067050.80     13474174.54      2066970.80     13474064.54
      2066810.80     13474014.54      2066420.80     13474064.54
      2066250.80     13473964.54      2066090.80     13473804.54
      2066090.80     13473724.54      2066020.80     13473714.54
      2065800.80     13473494.54      2065660.80     13473504.54
      2065380.80     13473414.54      2065270.80     13473484.54
      2065070.80     13473344.54      2064489.27     13473388.89
      2064215.83     13473254.34      2064099.51     13473088.54
      2064064.79     13472773.44      2063978.85     13472573.79
      2064110.80     13472184.54      2064120.80     13471914.54
      2064310.45     13471695.31      2064627.29     13471616.32
      2064844.71     13471390.63      2064741.00     13471281.68

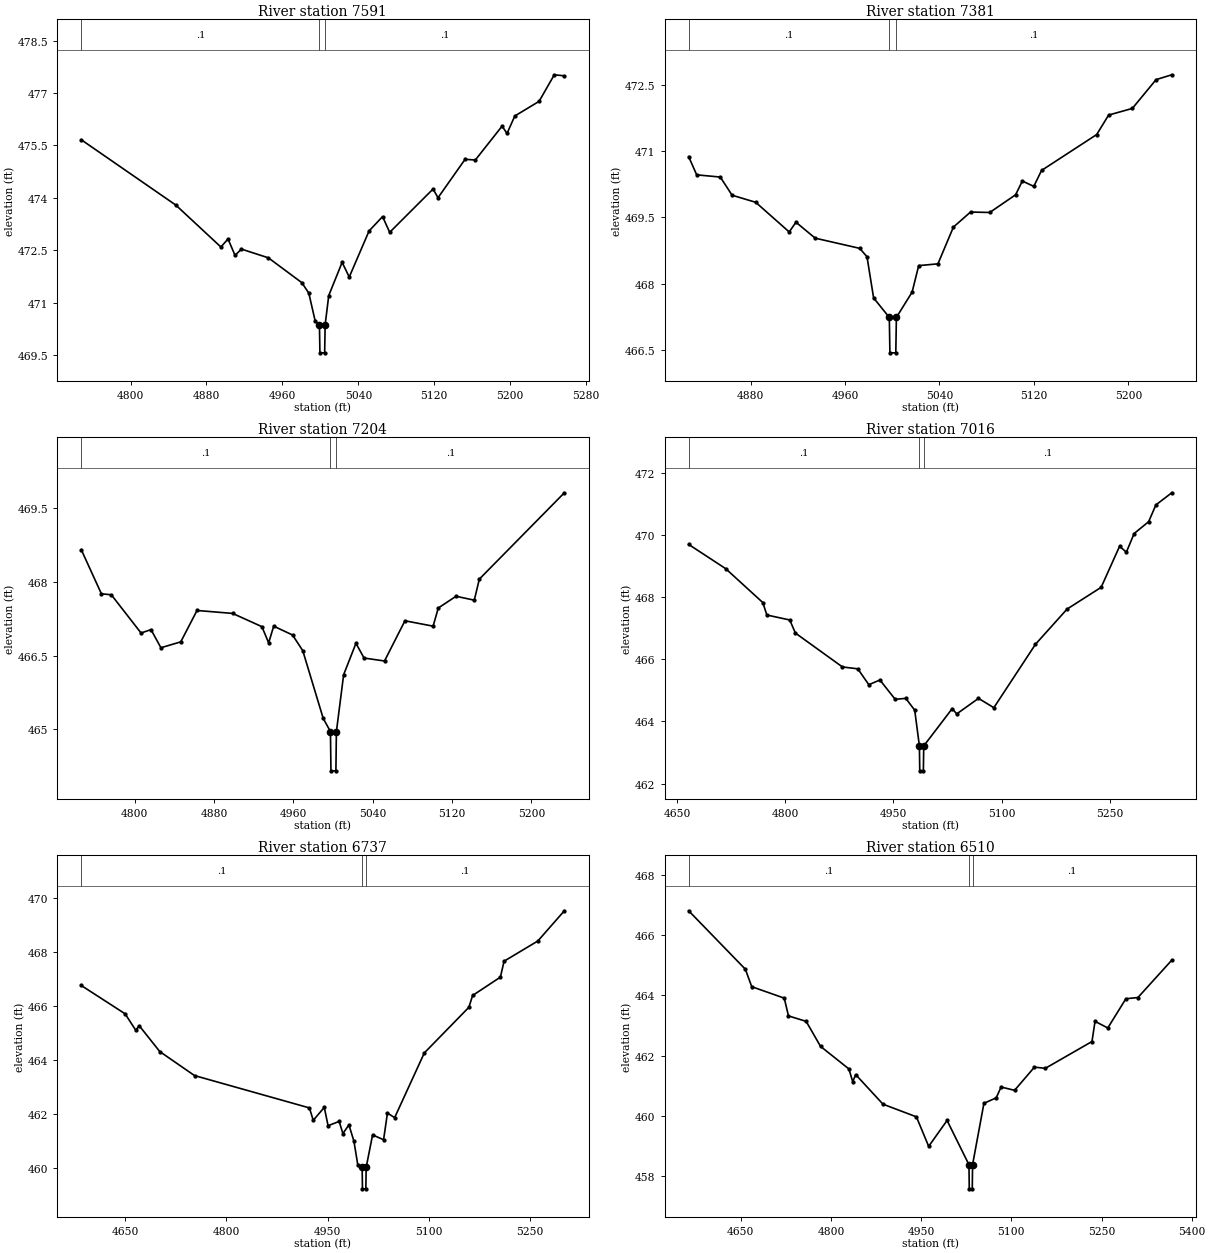
Type RM Length L Ch R = 1,7591,210,210,210
BEGIN DESCRIPTION:
UNT 156 in Lagunillas Cr Wtrshd 5.0
END DESCRIPTION:
XS GIS Cut Line= 4
      2068104.13     13475292.17      2067955.28     13475278.02
      2067805.98     13475413.44      2067762.58     13475565.17
#Sta/Elev= 30
  4748.1  475.66  4847.7  473.79  4895.2  472.59  4902.7  472.82  4910.1  472.35
  4916.8  472.53  4945.2  472.28  4980.4  471.57  4987.8  471.27  4994.6  470.46
  4999.0  470.36  4999.5  469.56  5004.5  469.56  5005.0  470.36  5008.8  471.20
  5022.9  472.15  5030.4  471.73  5051.3  473.05  5065.5  473.46  5073.0  473.01
  5118.7  474.25  5123.9  474.00  5152.4  475.10  5163.2  475.08  5191.4  476.05
  5196.6  475.84  5204.8  476.34  5230.4  476.76  5246.4  477.52  5257.0  477.49
#Mann=3,-1,0
  4748.1     0.1       0  4999.0    0.07       0  5005.0     0.1       0
Bank Sta=4999,5005
Exp/Cntr=0.3,0.1

Type RM Length L Ch R = 1,7381,177,177,177
BEGIN DESCRIPTION:
Mapping XS 5e3d7406
END DESCRIPTION:
XS GIS Cut Line= 4
      2067901.76     13475141.13      2067825.36     13475144.60
      2067627.45     13475250.50      2067639.60     13475358.18
#Sta/Elev= 30
  4827.5  470.87  4834.3  470.46  4854.3  470.41  4864.3  470.00  4884.3  469.84
  4912.7  469.17  4918.4  469.39  4934.7  469.03  4972.4  468.80  4978.6  468.61
  4984.2  467.68  4997.5  467.24  4998.0  466.44  5003.0  466.44  5003.5  467.24
  5016.8  467.81  5022.4  468.41  5038.7  468.45  5051.8  469.28  5066.3  469.62
  5082.6  469.61  5104.5  470.01  5110.2  470.32  5119.9  470.20  5126.5  470.56
  5173.2  471.37  5183.3  471.81  5203.4  471.96  5223.5  472.61  5236.8  472.72
#Mann=3,-1,0
  4827.5     0.1       0  4997.5    0.07       0  5003.5     0.1       0
Bank Sta=4997.5,5003.5
Exp/Cntr=0.3,0.1

Type RM Length L Ch R = 1,7204,188,188,188
BEGIN DESCRIPTION:
Mapping XS 69eea8ae
END DESCRIPTION:
XS GIS Cut Line= 4
      2067905.27     13475012.65      2067787.17     13475012.65
      2067505.92     13475082.10      2067485.08     13475158.51
#Sta/Elev= 30
  4746.2  468.66  4766.5  467.76  4776.5  467.74  4806.5  466.96  4816.5  467.03
  4826.5  466.66  4846.5  466.78  4862.9  467.42  4898.8  467.36  4928.3  467.09
  4935.1  466.76  4940.2  467.10  4959.2  466.92  4969.5  466.60  4990.1  465.22
  4997.4  464.95  4997.9  464.15  5002.9  464.15  5003.4  464.95  5010.7  466.11
  5023.1  466.75  5031.3  466.45  5051.9  466.39  5072.5  467.21  5100.9  467.10
  5106.1  467.47  5124.0  467.71  5142.4  467.63  5147.5  468.06  5233.2  469.82
#Mann=3,-1,0
  4746.2     0.1       0  4997.4    0.07       0  5003.4     0.1       0
Bank Sta=4997.4,5003.4
Exp/Cntr=0.3,0.1

Type RM Length L Ch R = 1,7016,279,279,279
BEGIN DESCRIPTION:
Mapping XS bde11837
END DESCRIPTION:
XS GIS Cut Line= 4
      2067854.88     13474806.06      2067742.03     13474778.28
      2067354.88     13475019.60      2067342.73     13475116.82
#Sta/Elev= 30
  4665.8  469.69  4717.2  468.91  4768.7  467.82  4774.3  467.42  4806.1  467.26
  4813.9  466.84  4879.2  465.75  4900.5  465.69  4915.8  465.18  4931.2  465.33
  4952.4  464.71  4967.1  464.74  4979.5  464.36  4986.0  463.21  4986.5  462.41
  4991.5  462.41  4992.0  463.21  5031.5  464.41  5037.8  464.24  5068.0  464.74
  5089.3  464.44  5147.1  466.48  5190.9  467.61  5238.2  468.31  5263.8  469.63
  5273.2  469.44  5284.0  470.04  5304.1  470.42  5314.2  470.96  5336.2  471.35
#Mann=3,-1,0
  4665.8     0.1       0  4986.0    0.07       0  4992.0     0.1       0
Bank Sta=4986,4992
Exp/Cntr=0.3,0.1

Type RM Length L Ch R = 1,6737,227,227,227
BEGIN DESCRIPTION:
Mapping XS ea95c1e4
END DESCRIPTION:
XS GIS Cut Line= 4
      2067728.16     13474628.98      2067590.99     13474595.99
      2067181.27     13474813.00      2067172.58     13474924.14
#Sta/Elev= 30
  4584.9  466.76  4649.9  465.71  4665.7  465.10  4670.8  465.27  4701.3  464.31
  4752.8  463.42  4923.2  462.22  4928.8  461.76  4945.2  462.24  4950.8  461.56
  4967.2  461.72  4972.8  461.27  4981.7  461.59  4989.1  460.99  4994.8  460.12
  5001.3  460.02  5001.8  459.22  5006.8  459.22  5007.3  460.02  5016.8  461.22
  5033.1  461.04  5038.8  462.03  5049.5  461.86  5093.5  464.26  5159.5  465.95
  5165.1  466.39  5206.3  467.07  5211.7  467.66  5261.8  468.41  5301.1  469.53
#Mann=3,-1,0
  4584.9     0.1       0  5001.3    0.07       0  5007.3     0.1       0
Bank Sta=5001.3,5007.3
Exp/Cntr=0.3,0.1

Type RM Length L Ch R = 1,6510,464,464,464
BEGIN DESCRIPTION:
Mapping XS 8cd0511b
END DESCRIPTION:
XS GIS Cut Line= 4
      2067731.92     13474563.99      2067495.41     13474466.35
      2067075.36     13474552.58      2067068.49     13474671.20
#Sta/Elev= 30
  4563.3  466.81  4657.6  464.87  4668.2  464.29  4722.3  463.91  4729.3  463.32
  4758.7  463.14  4782.6  462.31  4829.8  461.56  4836.1  461.14  4841.2  461.37
  4886.5  460.39  4942.1  459.97  4962.5  458.99  4993.1  459.85  5029.5  458.38
  5030.0  457.58  5035.0  457.58  5035.5  458.38  5054.4  460.42  5074.8  460.60
  5082.9  460.96  5105.4  460.85  5138.4  461.62  5156.5  461.58  5234.1  462.47
  5239.2  463.14  5260.4  462.92  5290.5  463.89  5310.5  463.93  5366.8  465.17
#Mann=3,-1,0
  4563.3     0.1       0  5029.5    0.07       0  5035.5     0.1       0
Bank Sta=5029.5,5035.5
Exp/Cntr=0.3,0.1

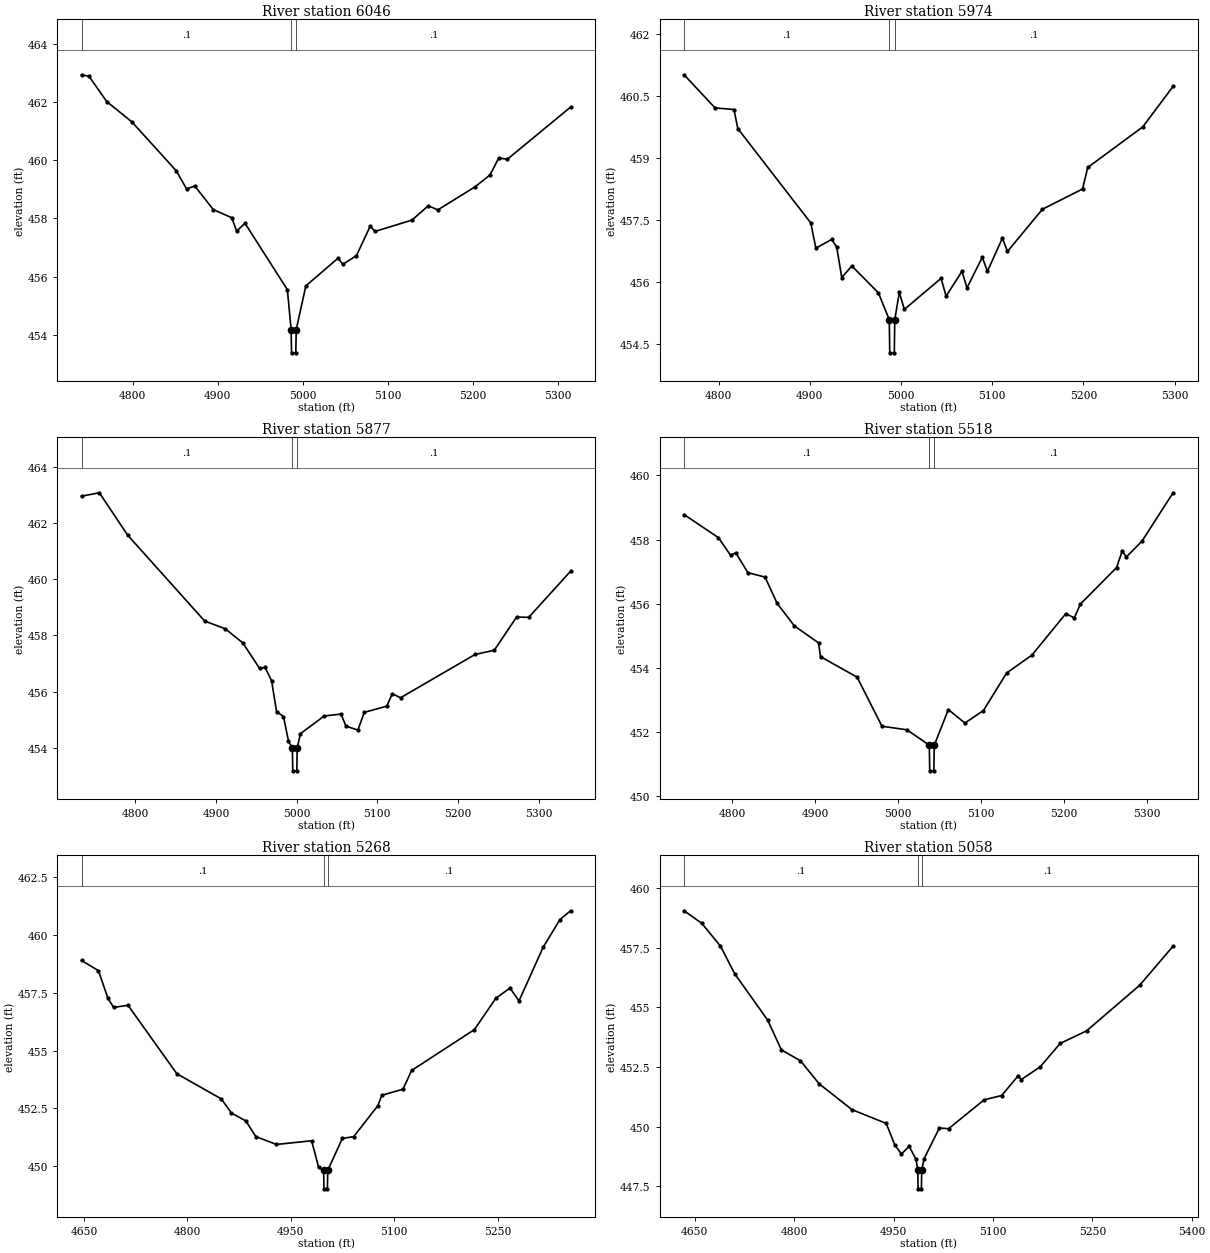
Type RM Length L Ch R = 1,6046,72,72,72
BEGIN DESCRIPTION:
Mapping XS 7c5e0e07
END DESCRIPTION:
XS GIS Cut Line= 4
      2067224.37     13473962.05      2067173.17     13474034.96
      2067022.12     13474307.53      2066986.54     13474477.63
#Sta/Elev= 30
  4739.9  462.93  4748.6  462.88  4769.5  462.01  4799.1  461.31  4851.2  459.63
  4863.3  459.01  4872.9  459.11  4894.7  458.30  4916.4  458.02  4922.1  457.56
  4931.9  457.83  4981.7  455.55  4986.1  454.18  4986.6  453.38  4991.6  453.38
  4992.1  454.18  5003.4  455.68  5041.2  456.63  5046.9  456.42  5062.9  456.72
  5079.0  457.73  5084.7  457.55  5128.2  457.94  5147.1  458.43  5158.5  458.29
  5202.1  459.08  5219.8  459.49  5230.0  460.07  5240.2  460.03  5314.4  461.82
#Mann=3,-1,0
  4739.9     0.1       0  4986.1    0.07       0  4992.1     0.1       0
Bank Sta=4986.1,4992.1
Exp/Cntr=0.3,0.1

Type RM Length L Ch R = 1,5974,97,97,97
BEGIN DESCRIPTION:
Mapping XS 7ee2d1c0
END DESCRIPTION:
XS GIS Cut Line= 4
      2067144.55     13473947.25      2067104.59     13473994.16
      2066995.21     13474229.41      2066894.51     13474419.53
#Sta/Elev= 30
  4762.1  461.01  4796.0  460.21  4816.8  460.17  4821.0  459.71  4901.0  457.43
  4906.6  456.82  4923.9  457.03  4929.4  456.85  4935.0  456.11  4946.0  456.39
  4975.2  455.74  4987.1  455.09  4987.6  454.29  4992.6  454.29  4993.1  455.09
  4998.1  455.75  5003.6  455.34  5043.9  456.09  5049.4  455.66  5066.8  456.26
  5072.3  455.86  5089.1  456.60  5094.7  456.26  5111.1  457.06  5116.7  456.74
  5155.0  457.76  5199.0  458.25  5204.7  458.77  5265.0  459.75  5298.3  460.73
#Mann=3,-1,0
  4762.1     0.1       0  4987.1    0.07       0  4993.1     0.1       0
Bank Sta=4987.1,4993.1
Exp/Cntr=0.3,0.1

Type RM Length L Ch R = 1,5877,359,359,359
BEGIN DESCRIPTION:
Mapping XS 3dfcc6d4
END DESCRIPTION:
XS GIS Cut Line= 4
      2067161.23     13473880.39      2067049.03     13473984.62
      2066920.56     13474164.30      2066868.28     13474390.21
#Sta/Elev= 30
  4733.5  462.95  4755.6  463.07  4790.7  461.56  4886.0  458.51  4911.7  458.23
  4933.3  457.73  4954.2  456.82  4960.9  456.86  4969.0  456.38  4975.1  455.29
  4983.7  455.11  4989.9  454.24  4994.7  453.98  4995.2  453.18  5000.2  453.18
  5000.7  453.98  5004.6  454.50  5034.1  455.13  5055.0  455.20  5061.1  454.77
  5075.9  454.63  5083.8  455.26  5111.7  455.48  5118.5  455.92  5128.8  455.78
  5221.1  457.32  5244.9  457.47  5272.5  458.65  5287.6  458.64  5339.4  460.28
#Mann=3,-1,0
  4733.5     0.1       0  4994.7    0.07       0  5000.7     0.1       0
Bank Sta=4994.7,5000.7
Exp/Cntr=0.3,0.1

Type RM Length L Ch R = 1,5518,250,250,250
BEGIN DESCRIPTION:
Mapping XS 92a1bcf2
END DESCRIPTION:
XS GIS Cut Line= 4
      2066757.56     13473800.12      2066656.89     13473932.53
      2066649.29     13474144.12      2066692.10     13474351.79
#Sta/Elev= 30
  4741.6  458.78  4783.1  458.06  4797.7  457.51  4804.0  457.59  4818.5  456.97
  4839.3  456.83  4853.9  456.01  4874.7  455.31  4903.8  454.78  4906.3  454.35
  4950.4  453.71  4980.4  452.18  5010.5  452.07  5037.5  451.59  5038.0  450.79
  5043.0  450.79  5043.5  451.59  5060.5  452.70  5080.5  452.28  5102.8  452.67
  5130.8  453.84  5161.4  454.40  5202.2  455.69  5212.5  455.56  5219.9  455.99
  5263.5  457.13  5270.2  457.64  5275.3  457.46  5294.1  457.95  5331.7  459.46
#Mann=3,-1,0
  4741.6     0.1       0  5037.5    0.07       0  5043.5     0.1       0
Bank Sta=5037.5,5043.5
Exp/Cntr=0.3,0.1

Type RM Length L Ch R = 1,5268,210,210,210
BEGIN DESCRIPTION:
Mapping XS 85e905b4
END DESCRIPTION:
XS GIS Cut Line= 4
      2066609.98     13473765.41      2066451.81     13473975.94
      2066414.92     13474164.74      2066479.78     13474409.91
#Sta/Elev= 30
  4646.4  458.90  4670.9  458.46  4684.7  457.26  4693.0  456.87  4713.8  456.96
  4784.6  454.00  4849.2  452.91  4863.8  452.30  4884.6  451.96  4899.2  451.28
  4929.1  450.94  4980.1  451.10  4990.3  449.95  4997.5  449.82  4998.0  449.02
  5003.0  449.02  5003.5  449.82  5024.7  451.20  5041.2  451.28  5076.2  452.62
  5082.0  453.07  5112.7  453.33  5125.1  454.14  5216.2  455.91  5247.2  457.26
  5267.9  457.71  5280.9  457.15  5315.9  459.47  5340.3  460.67  5355.7  461.05
#Mann=3,-1,0
  4646.4     0.1       0  4997.5    0.07       0  5003.5     0.1       0
Bank Sta=4997.5,5003.5
Exp/Cntr=0.3,0.1

Type RM Length L Ch R = 1,5058,50,50,50
BEGIN DESCRIPTION:
Mapping XS ddef6e21
END DESCRIPTION:
XS GIS Cut Line= 4
      2066512.30     13473704.66      2066314.01     13473879.36
      2066208.76     13474068.17      2066221.54     13474325.32
#Sta/Elev= 30
  4634.0  459.05  4660.5  458.53  4688.9  457.57  4710.4  456.41  4760.1  454.47
  4780.9  453.22  4809.4  452.77  4837.9  451.80  4887.2  450.72  4939.1  450.14
  4951.9  449.24  4962.0  448.86  4973.6  449.18  4983.9  448.64  4986.6  448.20
  4987.1  447.40  4992.1  447.40  4992.6  448.20  4996.3  448.67  5019.2  449.95
  5033.1  449.92  5086.8  451.13  5113.2  451.31  5137.9  452.13  5142.9  451.98
  5171.3  452.51  5201.4  453.49  5241.4  454.02  5321.5  455.93  5371.9  457.57
#Mann=3,-1,0
  4634.0     0.1       0  4986.6    0.07       0  4992.6     0.1       0
Bank Sta=4986.6,4992.6
Exp/Cntr=0.3,0.1

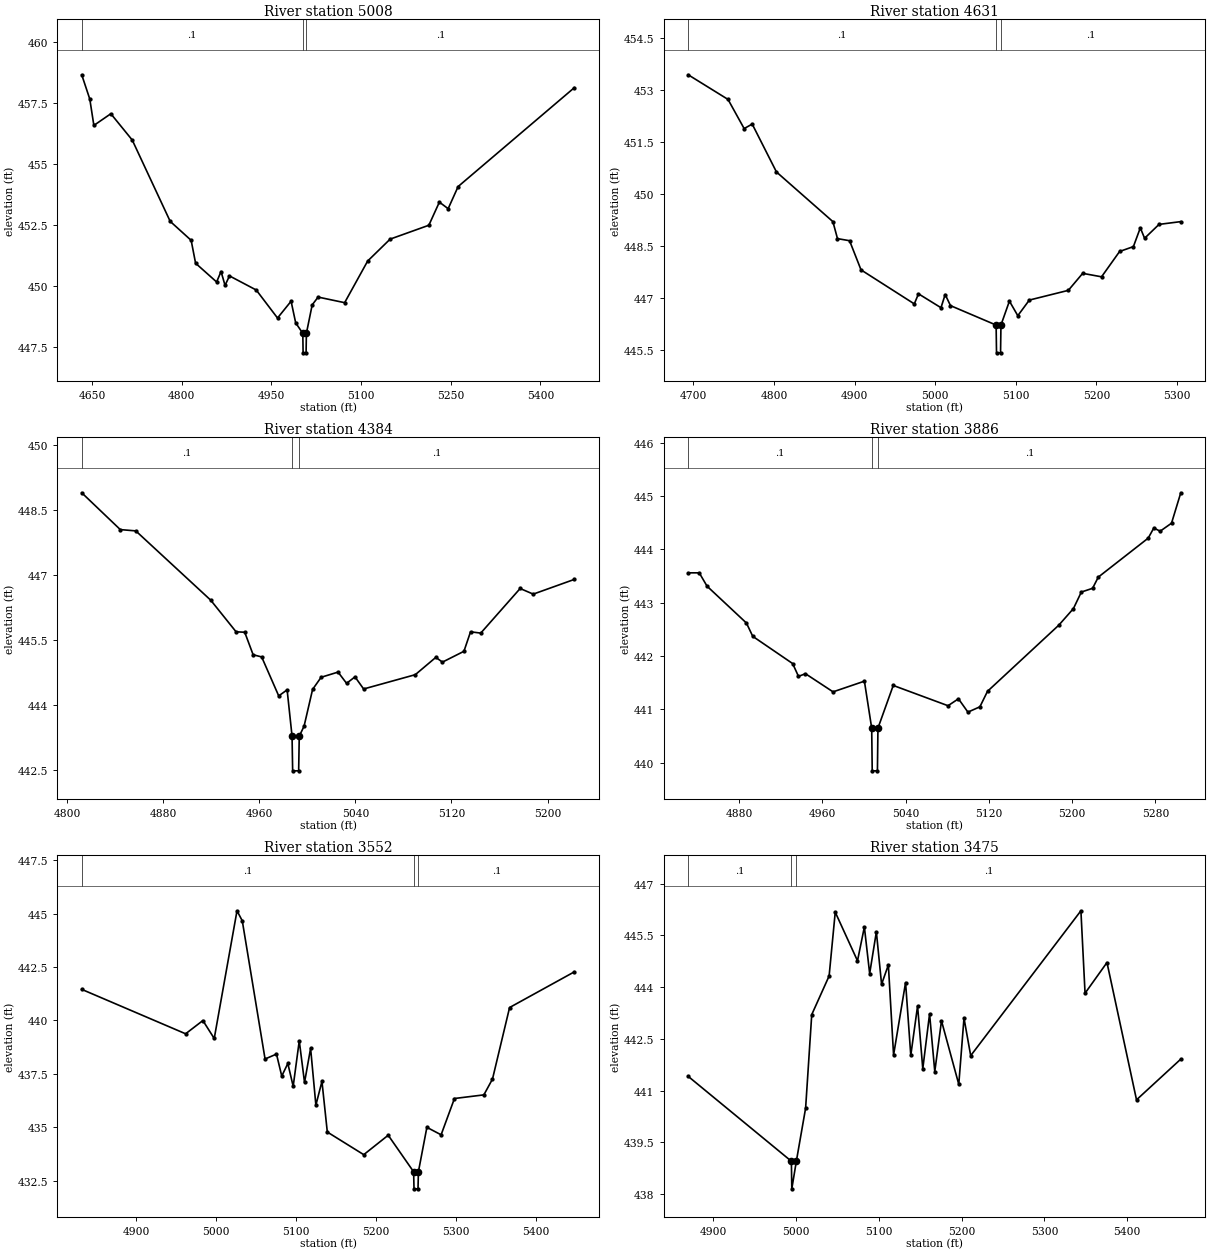
Type RM Length L Ch R = 1,5008,377,377,377
BEGIN DESCRIPTION:
Mapping XS 71592868
END DESCRIPTION:
XS GIS Cut Line= 4
      2066468.95     13473669.90      2066276.03     13473846.81
      2066190.31     13474008.49      2066076.28     13474370.40
#Sta/Elev= 30
  4632.5  458.66  4646.0  457.66  4652.8  456.58  4681.2  457.06  4717.0  455.98
  4780.5  452.64  4815.6  451.86  4823.0  450.92  4858.2  450.15  4865.6  450.58
  4872.3  450.01  4879.7  450.40  4924.5  449.82  4960.1  448.67  4982.8  449.36
  4990.5  448.47  5002.4  448.04  5002.9  447.24  5007.9  447.24  5008.4  448.04
  5018.1  449.21  5028.0  449.53  5072.4  449.30  5110.9  451.01  5148.5  451.91
  5213.3  452.48  5230.9  453.43  5245.6  453.16  5262.3  454.07  5456.7  458.13
#Mann=3,-1,0
  4632.5     0.1       0  5002.4    0.07       0  5008.4     0.1       0
Bank Sta=5002.4,5008.4
Exp/Cntr=0.3,0.1

Type RM Length L Ch R = 1,4631,247,247,247
BEGIN DESCRIPTION:
Mapping XS 45cad72e
END DESCRIPTION:
XS GIS Cut Line= 4
      2066304.35     13473670.83      2066118.74     13473662.21
      2065807.87     13473755.40      2065774.38     13473850.43
#Sta/Elev= 30
  4693.5  453.44  4742.9  452.73  4762.9  451.89  4772.9  452.02  4803.0  450.64
  4873.0  449.21  4878.7  448.72  4893.7  448.66  4907.9  447.82  4974.0  446.84
  4979.2  447.13  5007.1  446.73  5012.3  447.11  5018.9  446.79  5075.5  446.23
  5076.0  445.43  5081.0  445.43  5081.5  446.23  5092.0  446.92  5102.4  446.50
  5116.7  446.95  5165.1  447.23  5182.9  447.72  5206.3  447.62  5228.7  448.35
  5245.8  448.49  5254.4  449.03  5259.7  448.73  5277.6  449.13  5304.6  449.21
#Mann=3,-1,0
  4693.5     0.1       0  5075.5    0.07       0  5081.5     0.1       0
Bank Sta=5075.5,5081.5
Exp/Cntr=0.3,0.1

Type RM Length L Ch R = 1,4384,498,498,498
BEGIN DESCRIPTION:
Mapping XS 468ddbd6
END DESCRIPTION:
XS GIS Cut Line= 4
      2065997.07     13473432.66      2065957.09     13473431.79
      2065809.52     13473576.76      2065744.11     13473726.34
#Sta/Elev= 30
  4812.2  448.89  4844.3  448.04  4857.2  448.01  4919.6  446.41  4940.7  445.68
  4947.9  445.67  4954.9  445.15  4962.0  445.10  4976.2  444.20  4983.2  444.34
  4987.3  443.27  4987.8  442.47  4992.8  442.47  4993.3  443.27  4997.3  443.50
  5004.4  444.35  5011.5  444.63  5025.6  444.75  5032.7  444.49  5039.7  444.64
  5046.9  444.36  5089.9  444.69  5107.0  445.09  5112.5  444.98  5130.4  445.23
  5135.9  445.68  5144.4  445.65  5177.2  446.68  5188.1  446.55  5222.3  446.89
#Mann=3,-1,0
  4812.2     0.1       0  4987.3    0.07       0  4993.3     0.1       0
Bank Sta=4987.3,4993.3
Exp/Cntr=0.3,0.1

Type RM Length L Ch R = 1,3886,334,334,334
BEGIN DESCRIPTION:
Mapping XS 595beafd
END DESCRIPTION:
XS GIS Cut Line= 4
      2065534.37     13473320.67      2065426.71     13473377.98
      2065413.69     13473528.15      2065490.18     13473713.27
#Sta/Elev= 30
  4831.3  443.56  4841.9  443.56  4849.4  443.31  4887.2  442.62  4893.3  442.37
  4931.6  441.86  4937.2  441.62  4943.9  441.67  4970.4  441.33  5000.5  441.53
  5007.5  440.65  5008.0  439.85  5013.0  439.85  5013.5  440.65  5028.2  441.45
  5080.8  441.07  5090.8  441.20  5099.9  440.95  5111.4  441.05  5118.7  441.34
  5187.2  442.58  5201.2  442.89  5208.8  443.20  5219.6  443.27  5225.1  443.48
  5273.0  444.21  5278.4  444.40  5284.5  444.34  5295.4  444.49  5304.3  445.06
#Mann=3,-1,0
  4831.3     0.1       0  5007.5    0.07       0  5013.5     0.1       0
Bank Sta=5007.5,5013.5
Exp/Cntr=0.3,0.1

Type RM Length L Ch R = 1,3552,77,77,77
BEGIN DESCRIPTION:
Mapping XS aff2836a
END DESCRIPTION:
XS GIS Cut Line= 5
      2065296.54     13473311.99      2065227.06     13473338.04
      2065016.99     13473521.20      2064998.76     13473601.93
      2065063.63     13473770.61
#Sta/Elev= 30
  4831.7  441.45  4961.7  439.37  4983.3  439.99  4997.5  439.15  5026.0  445.13
  5032.6  444.66  5061.1  438.19  5075.4  438.42  5082.0  437.39  5089.6  437.98
  5096.3  436.91  5103.9  439.04  5110.5  437.09  5118.1  438.69  5124.7  436.03
  5132.3  437.14  5139.0  434.77  5184.6  433.71  5215.2  434.62  5247.0  432.91
  5247.5  432.11  5252.5  432.11  5253.0  432.91  5263.6  434.99  5281.4  434.64
  5298.1  436.34  5334.9  436.51  5345.7  437.25  5367.1  440.60  5448.1  442.27
#Mann=3,-1,0
  4831.7     0.1       0  5247.0    0.07       0  5253.0     0.1       0
Bank Sta=5247,5253
Exp/Cntr=0.3,0.1

Type RM Length L Ch R = 1,3475,101,101,101
BEGIN DESCRIPTION:
Mapping XS c59da543
END DESCRIPTION:
XS GIS Cut Line= 6
      2065195.76     13473287.70      2065159.35     13473290.30
      2064957.09     13473528.15      2064952.75     13473617.56
      2064964.04     13473677.45      2065019.60     13473755.59
#Sta/Elev= 30
  4869.5  441.41  4994.2  438.95  4994.7  438.15  5000.2  438.95  5011.4  440.49
  5018.8  443.20  5039.8  444.32  5047.2  446.17  5074.1  444.76  5082.4  445.74
  5088.8  444.39  5096.9  445.60  5103.2  444.08  5111.4  444.64  5117.7  442.03
  5132.2  444.13  5138.5  442.02  5146.7  443.45  5153.0  441.63  5161.2  443.22
  5167.5  441.55  5175.6  443.02  5196.5  441.18  5202.8  443.10  5210.9  442.01
  5344.1  446.21  5349.1  443.82  5375.6  444.71  5411.3  440.73  5464.8  441.91
#Mann=3,-1,0
  4869.5     0.1       0  4994.2    0.07       0  5000.2     0.1       0
Bank Sta=4994.2,5000.2
Exp/Cntr=0.3,0.1

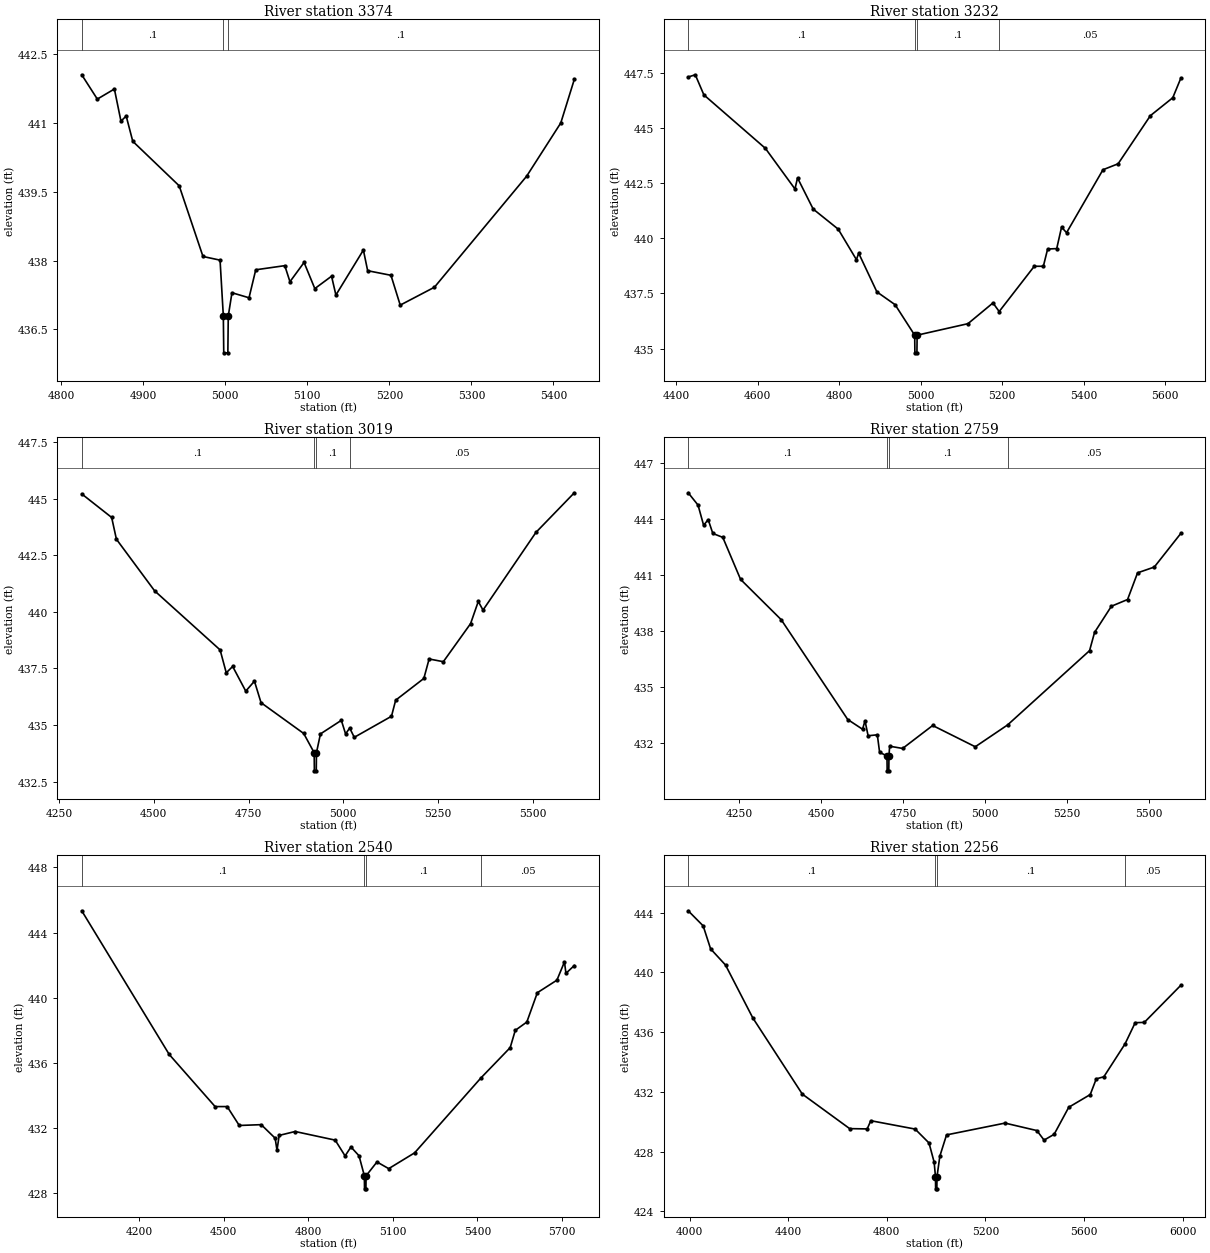
Type RM Length L Ch R = 1,3374,142,142,142
BEGIN DESCRIPTION:
Mapping XS 7320a264
END DESCRIPTION:
XS GIS Cut Line= 5
      2065125.47     13473228.69      2065066.47     13473275.54
      2064953.62     13473422.25      2064899.80     13473608.01
      2064931.69     13473751.07
#Sta/Elev= 30
  4825.0  442.05  4844.0  441.52  4864.8  441.74  4872.8  441.04  4879.2  441.15
  4887.2  440.60  4943.8  439.63  4972.8  438.09  4993.6  438.01  4997.6  436.79
  4998.1  435.99  5003.1  435.99  5003.6  436.79  5008.1  437.30  5028.9  437.19
  5037.1  437.80  5072.5  437.89  5078.8  437.54  5096.0  437.96  5109.1  437.39
  5129.5  437.66  5134.8  437.25  5168.3  438.23  5173.5  437.78  5201.9  437.68
  5213.2  437.03  5254.9  437.42  5367.3  439.84  5408.9  441.00  5425.4  441.95
#Mann=3,-1,0
  4825.0     0.1       0  4997.6    0.07       0  5003.6     0.1       0
Bank Sta=4997.6,5003.6
Exp/Cntr=0.3,0.1

Type RM Length L Ch R = 1,3232,213,213,213
BEGIN DESCRIPTION:
Mapping XS 7d9ac795
END DESCRIPTION:
XS GIS Cut Line= 4
      2065201.56     13472951.37      2065060.59     13472997.54
      2064713.05     13473692.62      2064749.51     13473974.52
#Sta/Elev= 30
  4429.2  447.30  4446.6  447.40  4467.7  446.49  4618.7  444.07  4691.4  442.23
  4697.7  442.73  4736.1  441.32  4797.6  440.41  4842.3  439.03  4847.9  439.32
  4892.6  437.57  4937.3  436.99  4985.4  435.61  4985.9  434.81  4990.9  434.81
  4991.4  435.61  5116.2  436.13  5177.7  437.07  5192.9  436.68  5279.1  438.73
  5301.4  438.73  5311.9  439.51  5334.2  439.53  5346.1  440.50  5358.4  440.25
  5447.8  443.10  5485.0  443.37  5564.3  445.55  5619.2  446.36  5638.9  447.24
#Mann=4,-1,0
  4429.2     0.1       0  4985.4    0.07       0  4991.4     0.1       0
  5192.9    0.05       0
Bank Sta=4985.4,4991.4
Exp/Cntr=0.3,0.1

Type RM Length L Ch R = 1,3019,260,260,260
BEGIN DESCRIPTION:
Mapping XS abdda739
END DESCRIPTION:
XS GIS Cut Line= 4
      2065028.97     13472849.30      2064885.61     13472902.76
      2064523.49     13473685.33      2064569.67     13473964.84
#Sta/Elev= 30
  4310.3  445.21  4389.2  444.17  4401.7  443.21  4502.4  440.93  4675.1  438.32
  4691.3  437.31  4708.2  437.59  4742.7  436.50  4765.6  436.94  4783.0  435.99
  4895.5  434.63  4923.1  433.78  4923.6  432.98  4928.6  432.98  4929.1  433.78
  4939.6  434.61  4994.7  435.21  5005.9  434.61  5016.7  434.87  5028.8  434.46
  5126.9  435.39  5137.9  436.10  5212.2  437.06  5226.1  437.92  5263.6  437.80
  5335.4  439.48  5355.7  440.46  5368.2  440.08  5507.7  443.51  5608.9  445.26
#Mann=4,-1,0
  4310.3     0.1       0  4923.1    0.07       0  4929.1     0.1       0
  5016.7    0.05       0
Bank Sta=4923.1,4929.1
Exp/Cntr=0.3,0.1

Type RM Length L Ch R = 1,2759,219,219,219
BEGIN DESCRIPTION:
Mapping XS 20775db1
END DESCRIPTION:
XS GIS Cut Line= 4
      2064999.84     13472798.25      2064462.36     13473059.90
      2064342.57     13473690.11      2064469.03     13473920.51
#Sta/Elev= 30
  4094.8  445.42  4124.8  444.76  4141.8  443.68  4155.8  443.98  4169.9  443.24
  4200.3  443.03  4254.5  440.78  4378.4  438.62  4581.3  433.27  4626.4  432.75
  4634.0  433.20  4643.4  432.40  4671.5  432.45  4678.5  431.51  4701.0  431.32
  4701.5  430.52  4706.5  430.52  4707.0  431.32  4709.1  431.84  4748.7  431.72
  4840.3  432.95  4970.2  431.81  5068.8  432.98  5318.7  436.96  5334.0  437.94
  5385.3  439.34  5434.6  439.70  5465.1  441.13  5516.1  441.44  5596.9  443.24
#Mann=4,-1,0
  4094.8     0.1       0  4701.0    0.07       0  4707.0     0.1       0
  5068.8    0.05       0
Bank Sta=4701,4707
Exp/Cntr=0.3,0.1

Type RM Length L Ch R = 1,2540,284,284,284
BEGIN DESCRIPTION:
Mapping XS be5bf1bd
END DESCRIPTION:
XS GIS Cut Line= 4
      2065004.66     13472764.23      2064608.55     13472790.96
      2064158.93     13473318.35      2064360.34     13473944.41
#Sta/Elev= 30
  3996.1  445.34  4306.5  436.52  4469.3  433.32  4512.1  433.32  4555.0  432.16
  4632.9  432.21  4682.3  431.38  4688.9  430.64  4696.6  431.55  4753.2  431.79
  4895.4  431.26  4930.5  430.29  4951.3  430.84  4979.9  430.30  4998.9  429.07
  4999.4  428.27  5004.4  428.27  5004.9  429.07  5043.6  429.92  5085.3  429.51
  5177.2  430.48  5412.0  435.07  5516.3  436.94  5534.3  438.00  5575.3  438.51
  5612.6  440.31  5682.0  441.08  5708.8  442.20  5714.1  441.50  5743.8  441.98
#Mann=4,-1,0
  3996.1     0.1       0  4998.9    0.07       0  5004.9     0.1       0
  5412.0    0.05       0
Bank Sta=4998.9,5004.9
Exp/Cntr=0.3,0.1

Type RM Length L Ch R = 1,2256,462,462,462
BEGIN DESCRIPTION:
Mapping XS a3ec6fa2
END DESCRIPTION:
XS GIS Cut Line= 5
      2064985.27     13472742.36      2064521.06     13472688.89
      2063981.52     13473085.04      2064163.79     13473515.21
      2064251.29     13473899.24
#Sta/Elev= 30
  3994.6  444.12  4055.3  443.11  4085.5  441.57  4145.9  440.49  4256.6  436.95
  4457.4  431.85  4649.4  429.54  4720.5  429.52  4735.1  430.07  4914.9  429.51
  4971.2  428.58  4992.1  427.29  4997.5  426.31  4998.0  425.51  5003.0  425.51
  5003.5  426.31  5015.2  427.70  5042.3  429.12  5279.5  429.91  5408.7  429.41
  5437.8  428.77  5478.7  429.16  5538.0  430.97  5625.1  431.82  5649.5  432.87
  5680.3  433.01  5766.2  435.21  5807.4  436.63  5844.4  436.65  5992.3  439.13
#Mann=4,-1,0
  3994.6     0.1       0  4997.5    0.07       0  5003.5     0.1       0
  5766.2    0.05       0
Bank Sta=4997.5,5003.5
Exp/Cntr=0.3,0.1

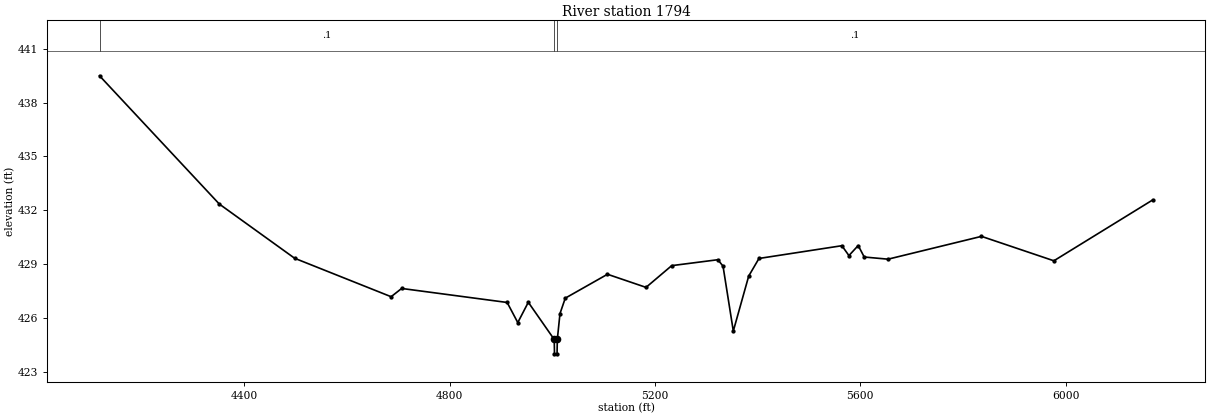
Type RM Length L Ch R = 1,1794,0,0,0
BEGIN DESCRIPTION:
Mapping XS da94e035
END DESCRIPTION:
XS GIS Cut Line= 5
      2064827.33     13472652.45      2064332.47     13472495.34
      2063857.21     13472608.18      2063859.38     13472903.32
      2064153.78     13473591.69
#Sta/Elev= 30
  4118.3  439.49  4351.6  432.35  4498.4  429.33  4686.3  427.19  4706.8  427.65
  4912.3  426.87  4933.0  425.75  4953.5  426.88  5004.0  424.81  5004.5  424.01
  5009.5  424.01  5010.0  424.81  5015.2  426.25  5025.5  427.11  5107.7  428.44
  5182.8  427.71  5232.8  428.92  5322.8  429.25  5332.8  428.89  5352.8  425.28
  5382.8  428.34  5402.8  429.32  5564.3  430.03  5578.0  429.48  5596.1  430.04
  5607.8  429.40  5654.2  429.28  5836.2  430.55  5977.2  429.19  6169.8  432.58
#Mann=3,-1,0
  4118.3     0.1       0  5004.0    0.07       0  5010.0     0.1       0
Bank Sta=5004,5010
Exp/Cntr=0.3,0.1

Chan Stop Cuts=-1