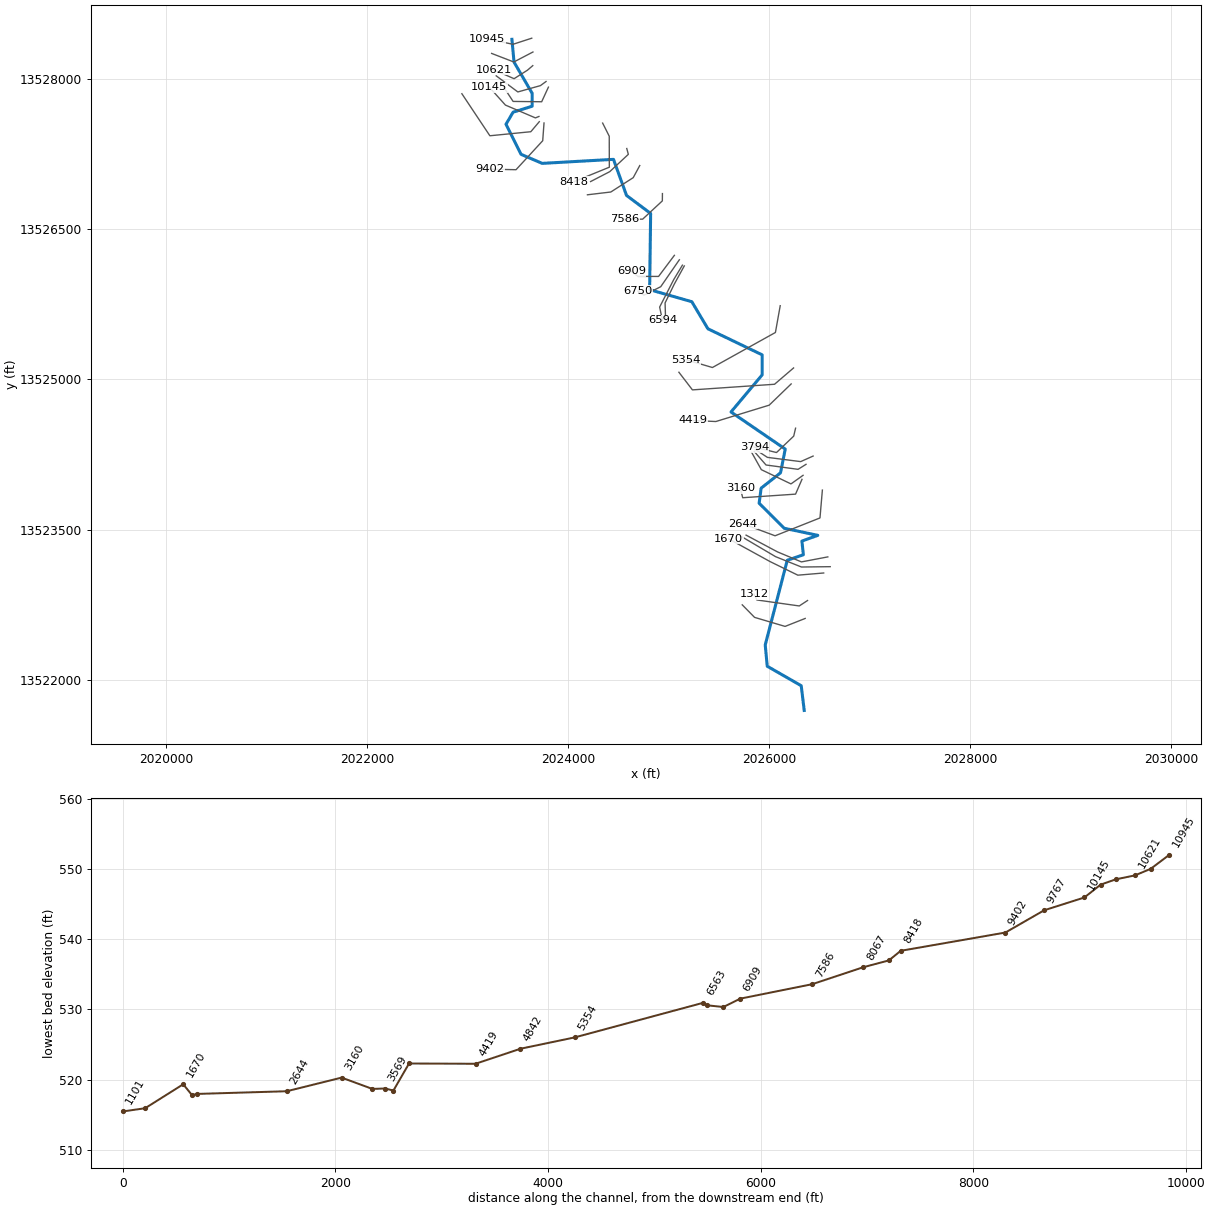
--- UNT 158 in Lagunillas Cr Wtrshd.prj (project) ---

Proj Title=UNT 158 in Lagunillas Cr Wtrshd Base Level Engineering
Current Plan=p01
Default Exp/Contr=0.3,0.1
English Units
Geom File=g01
Flow File=f01
Plan File=p01
BEGIN DESCRIPTION:
UNT 158 in Lagunillas Cr Wtrshd
END DESCRIPTION:

--- UNT 158 in Lagunillas Cr Wtrshd.p01 (plan) ---

Plan Title=Multiple Run
Short Identifier=Multiple
Geom File=g01
Flow File=f01
Subcritical Flow
K Sum by GR= 0
Std Step Tol= 0.01
Critical Tol= 0.01
Num of Std Step Trials= 20
Max Error Tol= 0.3
Flow Tol Ratio= 0.001
Split Flow NTrial= 30
Split Flow Tol= 0.02
Split Flow Ratio= 0.02
Log Output Level= 0
Friction Slope Method= 1
Unsteady Friction Slope Method= 2
Unsteady Bridges Friction Slope Method= 1
Parabolic Critical Depth
Global Vel Dist=  1 , 1 , 1
Global Log Level= 0
CheckData=True
Encroach Param= -1, 0, 0, 0
BEGIN DESCRIPTION:
Multiple Run
END DESCRIPTION:

--- UNT 158 in Lagunillas Cr Wtrshd.f01 (steady flow) ---

Flow Title=Multiple
Number of Profiles=7
Profile Names=10-year,25-year,50-year,1pct_min,100-year,1pct_plu,500-year
River Rch & RM= UNT 158 in Lagun,Reach-1,10945
     120     159     189     113     225     450     324
River Rch & RM= UNT 158 in Lagun,Reach-1,9767
     255     353     434     266     531    1059     806
River Rch & RM= UNT 158 in Lagun,Reach-1,5354
     264     364     447     273     545    1088     825
Boundary for River Rch & Prof#=UNT 158 in Lagun,Reach-1,1
Up Type=0
Dn Type=3
Dn Slope=0.005
Boundary for River Rch & Prof#=UNT 158 in Lagun,Reach-1,2
Up Type=0
Dn Type=3
Dn Slope=0.005
Boundary for River Rch & Prof#=UNT 158 in Lagun,Reach-1,3
Up Type=0
Dn Type=3
Dn Slope=0.005
Boundary for River Rch & Prof#=UNT 158 in Lagun,Reach-1,4
Up Type=0
Dn Type=3
Dn Slope=0.005
Boundary for River Rch & Prof#=UNT 158 in Lagun,Reach-1,5
Up Type=0
Dn Type=3
Dn Slope=0.005
Boundary for River Rch & Prof#=UNT 158 in Lagun,Reach-1,6
Up Type=0
Dn Type=3
Dn Slope=0.005
Boundary for River Rch & Prof#=UNT 158 in Lagun,Reach-1,7
Up Type=0
Dn Type=3
Dn Slope=0.005

--- UNT 158 in Lagunillas Cr Wtrshd.g01 (geometry) ---

Geom Title=Existing Conditions

River Reach=UNT 158 in Lagun,Reach-1
Reach XY= 30
      2023439.55     13528391.92      2023460.80     13528164.54
      2023640.80     13527854.54      2023640.80     13527724.54
      2023450.80     13527664.54      2023380.80     13527544.54
      2023530.80     13527244.54      2023740.80     13527154.54
      2024450.80     13527194.54      2024580.80     13526834.54
      2024820.80     13526654.54      2024810.80     13525894.54
      2025230.80     13525774.54      2025390.80     13525504.54
      2025930.80     13525244.54      2025930.80     13525044.54
      2025620.80     13524674.54      2026160.80     13524304.54
      2026113.68     13524067.42      2025920.80     13523914.54
      2025900.80     13523764.54      2026150.80     13523514.54
      2026485.12     13523443.91      2026326.78     13523386.96
      2026341.37     13523250.16      2026180.95     13523195.30
      2025961.51     13522350.16      2025981.65     13522138.35
      2026319.84     13521943.91      2026349.82     13521697.45

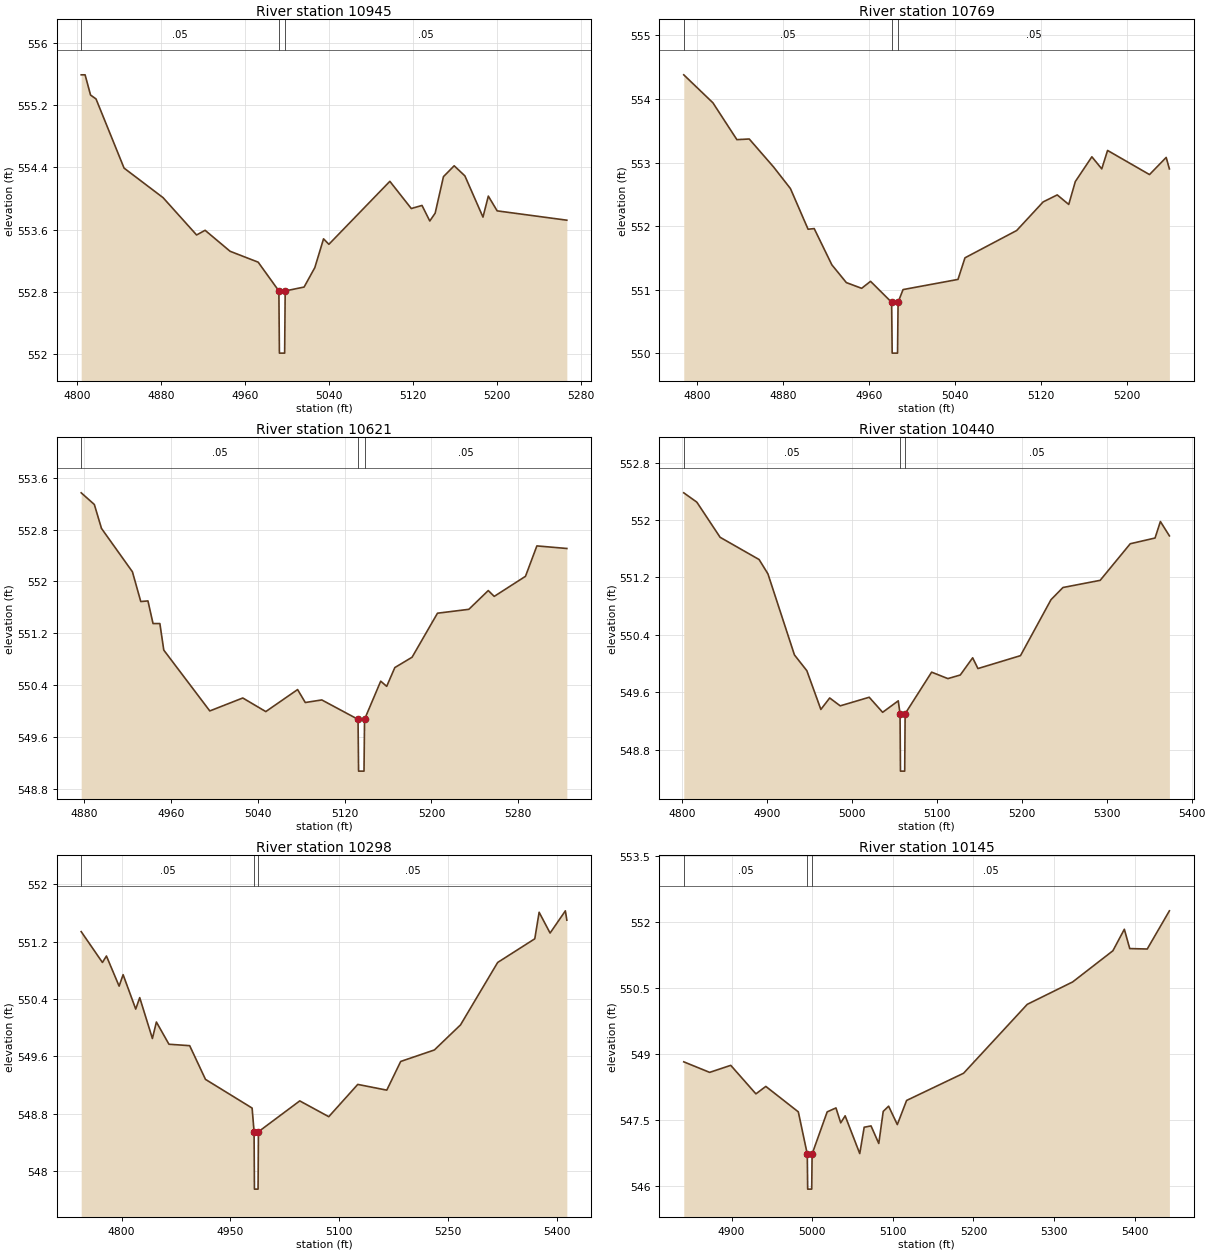
Type RM Length L Ch R = 1,10945,176,176,176
BEGIN DESCRIPTION:
UNT 158 in Lagunillas Cr Wtrshd 15.0
END DESCRIPTION:
XS GIS Cut Line= 3
      2023637.08     13528403.19      2023450.84     13528342.44
      2023190.00     13528395.58
#Sta/Elev= 30
  4804.1  555.59  4807.8  555.59  4813.0  555.33  4818.2  555.28  4844.9  554.39
  4882.0  554.01  4913.9  553.53  4922.0  553.59  4945.8  553.32  4972.5  553.18
  4992.2  552.81  4992.7  552.01  4997.7  552.01  4998.2  552.81  5016.2  552.86
  5026.4  553.11  5034.7  553.48  5039.8  553.41  5097.8  554.22  5118.2  553.87
  5128.4  553.91  5135.8  553.71  5140.9  553.81  5148.8  554.28  5159.0  554.42
  5169.2  554.29  5186.4  553.76  5191.5  554.03  5199.9  553.84  5266.2  553.72
#Mann=3,-1,0
  4804.1    0.05       0  4992.2   0.035       0  4998.2    0.05       0
Bank Sta=4992.2,4998.2
Exp/Cntr=0.3,0.1

Type RM Length L Ch R = 1,10769,148,148,148
BEGIN DESCRIPTION:
Mapping XS baf88682
END DESCRIPTION:
XS GIS Cut Line= 3
      2023648.98     13528265.38      2023458.61     13528165.90
      2023237.73     13528251.27
#Sta/Elev= 30
  4787.6  554.38  4814.7  553.94  4837.0  553.36  4848.5  553.37  4871.1  552.93
  4886.8  552.59  4903.2  551.95  4908.9  551.96  4925.3  551.39  4938.8  551.11
  4953.0  551.02  4961.3  551.13  4980.9  550.80  4981.4  550.00  4986.4  550.00
  4986.9  550.80  4991.5  551.00  5042.6  551.16  5049.1  551.50  5097.2  551.93
  5121.8  552.38  5134.9  552.49  5145.6  552.34  5151.7  552.70  5167.1  553.09
  5176.3  552.90  5181.7  553.19  5220.7  552.81  5236.2  553.08  5239.2  552.90
#Mann=3,-1,0
  4787.6    0.05       0  4980.9   0.035       0  4986.9    0.05       0
Bank Sta=4980.9,4986.9
Exp/Cntr=0.3,0.1

Type RM Length L Ch R = 1,10621,181,181,181
BEGIN DESCRIPTION:
Mapping XS e33885f5
END DESCRIPTION:
XS GIS Cut Line= 4
      2023647.38     13528129.41      2023594.03     13528083.87
      2023461.22     13527999.24      2023259.75     13528087.28
#Sta/Elev= 30
  4877.3  553.37  4889.4  553.19  4896.0  552.82  4924.5  552.15  4932.2  551.69
  4938.8  551.70  4943.5  551.35  4949.8  551.35  4953.4  550.94  4995.8  550.00
  5026.2  550.20  5047.4  549.99  5076.7  550.33  5083.8  550.13  5099.0  550.17
  5132.4  549.87  5132.9  549.07  5137.9  549.07  5138.4  549.87  5153.3  550.46
  5158.8  550.38  5166.3  550.67  5182.2  550.83  5205.6  551.51  5234.5  551.57
  5252.4  551.86  5257.9  551.77  5286.7  552.08  5297.2  552.55  5324.8  552.51
#Mann=3,-1,0
  4877.3    0.05       0  5132.4   0.035       0  5138.4    0.05       0
Bank Sta=5132.4,5138.4
Exp/Cntr=0.3,0.1

Type RM Length L Ch R = 1,10440,142,142,142
BEGIN DESCRIPTION:
Mapping XS 4096d7cc
END DESCRIPTION:
XS GIS Cut Line= 4
      2023779.57     13527971.23      2023723.15     13527930.01
      2023498.54     13527867.07      2023283.32     13528027.73
#Sta/Elev= 30
  4802.1  552.38  4817.5  552.25  4844.9  551.76  4890.8  551.45  4901.2  551.25
  4932.4  550.12  4947.0  549.90  4963.5  549.36  4973.9  549.52  4986.3  549.41
  5020.4  549.53  5036.2  549.32  5054.6  549.48  5056.7  549.30  5057.2  548.50
  5062.2  548.50  5062.7  549.30  5093.9  549.88  5113.0  549.79  5127.6  549.84
  5142.2  550.08  5148.4  549.93  5198.5  550.11  5234.4  550.89  5248.5  551.06
  5292.3  551.16  5327.7  551.67  5356.9  551.75  5363.2  551.98  5373.8  551.78
#Mann=3,-1,0
  4802.1    0.05       0  5056.7   0.035       0  5062.7    0.05       0
Bank Sta=5056.7,5062.7
Exp/Cntr=0.3,0.1

Type RM Length L Ch R = 1,10298,153,153,153
BEGIN DESCRIPTION:
Mapping XS 4b7e7aff
END DESCRIPTION:
XS GIS Cut Line= 4
      2023803.06     13527914.91      2023735.90     13527769.15
      2023451.62     13527772.40      2023327.94     13527960.25
#Sta/Elev= 30
  4744.4  551.34  4773.7  550.91  4779.2  551.00  4796.7  550.58  4802.2  550.74
  4819.6  550.26  4825.1  550.42  4842.6  549.85  4848.1  550.08  4865.4  549.77
  4894.0  549.75  4915.8  549.28  4980.1  548.88  4982.8  548.55  4983.3  547.75
  4988.3  547.75  4988.8  548.55  5045.8  548.98  5085.8  548.76  5125.8  549.21
  5165.8  549.13  5185.0  549.53  5231.4  549.69  5267.5  550.04  5318.7  550.91
  5369.9  551.24  5375.9  551.61  5391.0  551.32  5412.1  551.63  5414.1  551.50
#Mann=3,-1,0
  4744.4    0.05       0  4982.8   0.035       0  4988.8    0.05       0
Bank Sta=4982.8,4988.8
Exp/Cntr=0.3,0.1

Type RM Length L Ch R = 1,10145,378,378,378
BEGIN DESCRIPTION:
Mapping XS f9dc4e1b
END DESCRIPTION:
XS GIS Cut Line= 4
      2023708.82     13527622.46      2023673.62     13527608.12
      2023375.18     13527735.85      2023215.00     13527914.27
#Sta/Elev= 30
  4840.7  548.82  4872.8  548.58  4899.0  548.74  4930.2  548.09  4942.5  548.26
  4982.8  547.68  4993.9  546.72  4994.4  545.92  4999.4  545.92  4999.9  546.72
  5018.6  547.68  5029.5  547.77  5035.4  547.43  5040.9  547.59  5059.0  546.73
  5064.5  547.33  5073.0  547.36  5082.6  546.96  5088.1  547.69  5094.8  547.81
  5105.6  547.39  5117.1  547.94  5187.8  548.56  5266.8  550.13  5323.1  550.64
  5373.0  551.35  5387.2  551.84  5393.9  551.40  5415.6  551.39  5443.1  552.26
#Mann=3,-1,0
  4840.7    0.05       0  4993.9    0.03       0  4999.9    0.05       0
Bank Sta=4993.9,4999.9
Exp/Cntr=0.3,0.1

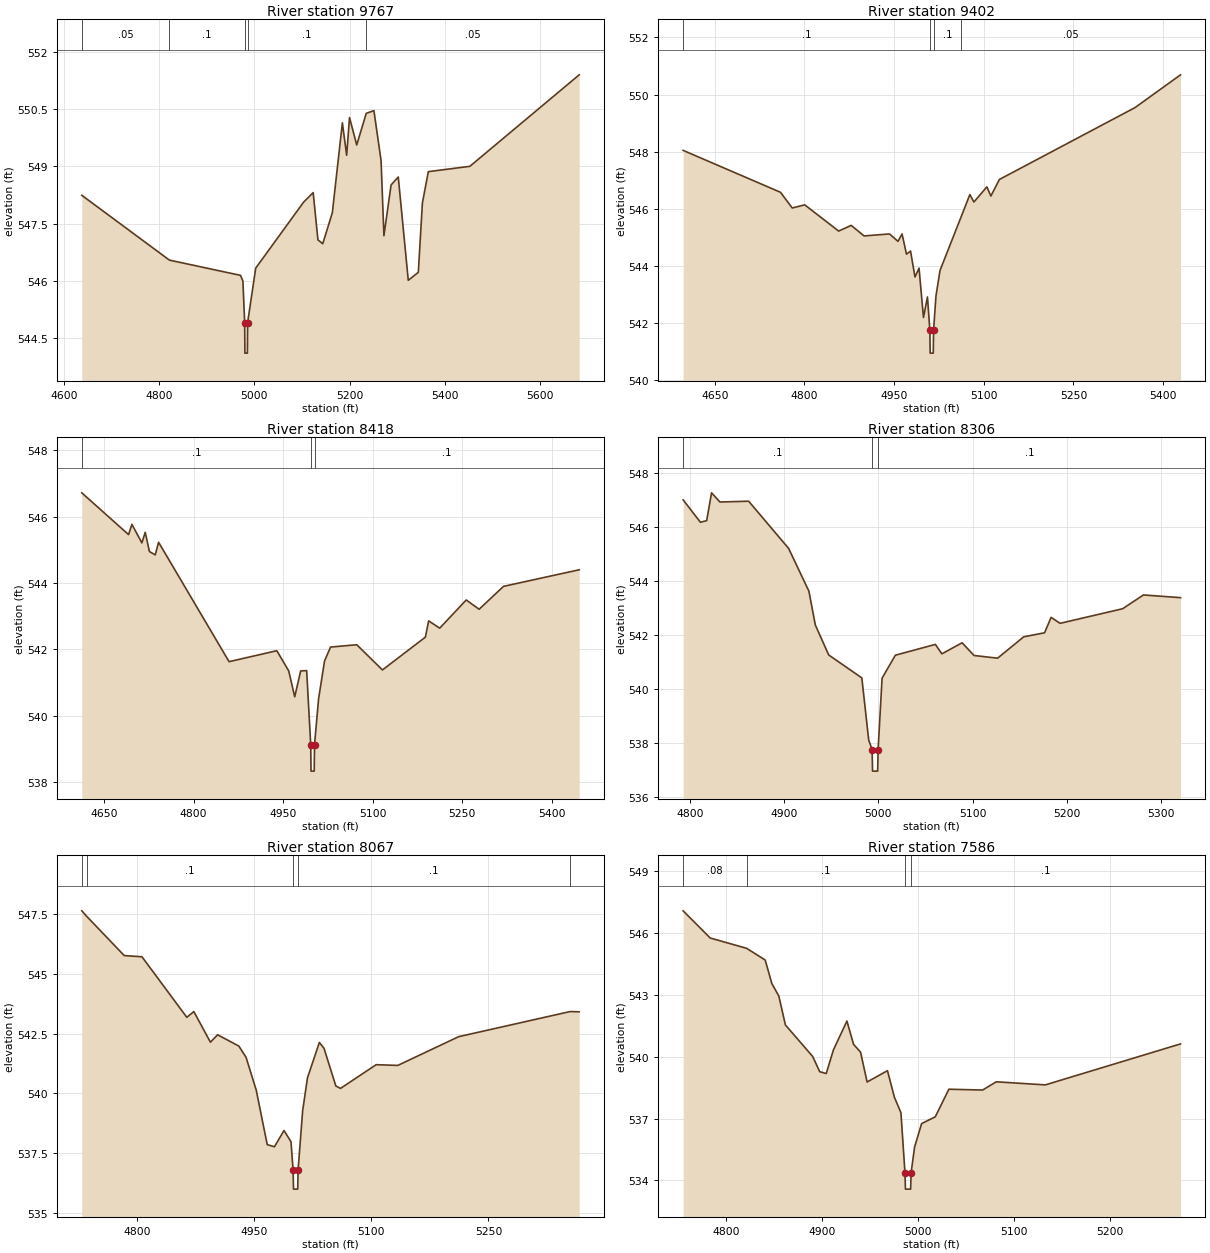
Type RM Length L Ch R = 1,9767,365,365,365
BEGIN DESCRIPTION:
Mapping XS 6c0448ae
END DESCRIPTION:
XS GIS Cut Line= 4
      2023712.40     13527570.46      2023627.79     13527470.23
      2023220.23     13527429.86      2022941.61     13527849.11
#Sta/Elev= 30
  4637.8  548.24  4821.7  546.54  4971.0  546.14  4976.0  545.99  4979.7  544.90
  4980.2  544.10  4985.4  544.10  4985.9  544.90  5002.9  546.33  5103.4  548.06
  5123.5  548.31  5133.5  547.07  5143.6  546.97  5163.7  547.78  5184.8  550.14
  5193.8  549.29  5199.8  550.28  5214.9  549.56  5234.9  550.39  5251.0  550.46
  5266.0  549.15  5272.0  547.18  5287.0  548.51  5302.1  548.72  5323.1  546.01
  5344.2  546.22  5352.8  548.04  5365.2  548.86  5452.4  549.00  5681.9  551.40
#Mann=5,-1,0
  4637.8    0.05       0  4821.7     0.1       0  4979.7    0.07       0
  4985.9     0.1       0  5234.9    0.05       0
Bank Sta=4979.7,4985.9
Exp/Cntr=0.3,0.1

Type RM Length L Ch R = 1,9402,984,984,984
BEGIN DESCRIPTION:
Mapping XS 316391b2
END DESCRIPTION:
XS GIS Cut Line= 4
      2023759.30     13527557.47      2023746.28     13527380.39
      2023480.65     13527091.32      2023218.84     13527096.51
#Sta/Elev= 30
  4597.2  548.04  4760.1  546.57  4779.7  546.02  4800.6  546.13  4857.4  545.21
  4878.3  545.41  4899.9  545.04  4942.4  545.11  4956.6  544.85  4963.4  545.11
  4970.8  544.40  4977.6  544.51  4985.0  543.60  4991.8  543.91  4999.2  542.18
  5005.9  542.90  5009.9  541.73  5010.4  540.93  5015.6  540.93  5016.1  541.73
  5020.1  542.93  5026.9  543.83  5062.4  545.72  5076.8  546.49  5083.6  546.23
  5105.2  546.76  5112.0  546.44  5126.2  547.02  5353.0  549.54  5429.2  550.69
#Mann=4,-1,0
  4597.2     0.1       0  5009.9    0.07       0  5016.1     0.1       0
  5062.4    0.05       0
Bank Sta=5009.9,5016.1
Exp/Cntr=0.3,0.1

Type RM Length L Ch R = 1,8418,112,112,112
BEGIN DESCRIPTION:
Mapping XS b3342942
END DESCRIPTION:
XS GIS Cut Line= 4
      2024343.02     13527556.32      2024408.66     13527425.22
      2024409.53     13527116.19      2024059.81     13526973.12
#Sta/Elev= 30
  4612.7  546.72  4691.1  545.46  4696.7  545.77  4713.4  545.21  4719.0  545.53
  4726.0  544.95  4735.8  544.85  4741.4  545.23  4859.5  541.63  4939.5  541.96
  4959.5  541.35  4969.5  540.57  4979.5  541.35  4989.5  541.36  4996.3  539.13
  4996.8  538.33  5002.2  538.33  5002.7  539.13  5009.5  540.51  5019.5  541.65
  5029.5  542.07  5073.5  542.14  5116.5  541.38  5188.5  542.37  5193.9  542.86
  5212.5  542.64  5256.9  543.49  5278.5  543.21  5319.4  543.90  5446.2  544.40
#Mann=3,-1,0
  4612.7     0.1       0  4996.3    0.07       0  5002.7     0.1       0
Bank Sta=4996.3,5002.7
Exp/Cntr=0.3,0.1

Type RM Length L Ch R = 1,8306,239,239,239
BEGIN DESCRIPTION:
Mapping XS 3ebfbbdb
END DESCRIPTION:
XS GIS Cut Line= 4
      2024583.15     13527302.77      2024598.77     13527244.66
      2024413.87     13527071.92      2024222.85     13526973.05
#Sta/Elev= 30
  4792.6  547.00  4811.0  546.17  4817.6  546.23  4822.8  547.26  4831.7  546.92
  4862.2  546.95  4904.7  545.20  4926.2  543.62  4933.0  542.37  4947.2  541.26
  4982.4  540.41  4989.7  538.11  4993.3  537.76  4993.8  536.96  4999.2  536.96
  4999.7  537.76  5003.9  540.40  5018.0  541.25  5060.5  541.65  5067.4  541.30
  5088.9  541.71  5101.6  541.24  5126.6  541.14  5154.3  541.93  5176.5  542.08
  5183.4  542.65  5193.0  542.43  5259.4  542.97  5281.5  543.48  5320.9  543.38
#Mann=3,-1,0
  4792.6     0.1       0  4993.3    0.07       0  4999.7     0.1       0
Bank Sta=4993.3,4999.7
Exp/Cntr=0.3,0.1

Type RM Length L Ch R = 1,8067,481,481,481
BEGIN DESCRIPTION:
Mapping XS d849d457
END DESCRIPTION:
XS GIS Cut Line= 4
      2024712.45     13527132.78      2024647.38     13527012.02
      2024424.26     13526868.90      2024191.67     13526841.12
#Sta/Elev= 30
  4729.6  547.63  4735.9  547.40  4783.9  545.76  4806.6  545.71  4864.0  543.18
  4873.0  543.42  4894.2  542.14  4903.4  542.45  4930.5  541.98  4939.8  541.51
  4952.8  540.14  4966.9  537.86  4976.1  537.77  4988.4  538.45  4997.3  537.98
  5000.0  536.80  5000.5  536.00  5005.9  536.00  5006.4  536.80  5012.2  539.27
  5018.4  540.65  5033.6  542.13  5039.5  541.89  5054.7  540.31  5060.7  540.21
  5106.3  541.20  5134.0  541.17  5211.8  542.37  5354.4  543.42  5366.1  543.41
#Mann=5,-1,0
  4729.6    0.05       0  4735.9     0.1       0  5000.0    0.07       0
  5006.4     0.1       0  5354.4    0.05       0
Bank Sta=5000,5006.4
Exp/Cntr=0.3,0.1

Type RM Length L Ch R = 1,7586,677,677,677
BEGIN DESCRIPTION:
Mapping XS 1e0a0310
END DESCRIPTION:
XS GIS Cut Line= 4
      2024938.17     13526853.15      2024937.31     13526780.25
      2024741.13     13526597.96      2024564.34     13526597.10
#Sta/Elev= 30
  4755.7  547.09  4783.9  545.77  4821.8  545.27  4841.1  544.70  4848.0  543.56
  4855.3  542.95  4862.1  541.55  4890.5  540.02  4897.8  539.28  4904.6  539.19
  4912.0  540.33  4926.1  541.74  4933.0  540.61  4940.3  540.23  4947.1  538.78
  4968.3  539.33  4975.5  538.04  4982.3  537.29  4986.5  534.38  4987.0  533.58
  4992.4  533.58  4992.9  534.38  4996.5  535.62  5003.8  536.76  5018.0  537.09
  5032.2  538.43  5067.3  538.39  5081.5  538.79  5132.5  538.64  5273.2  540.63
#Mann=4,-1,0
  4755.7    0.08       0  4821.8     0.1       0  4986.5    0.07       0
  4992.9     0.1       0
Bank Sta=4986.5,4992.9
Exp/Cntr=0.3,0.1

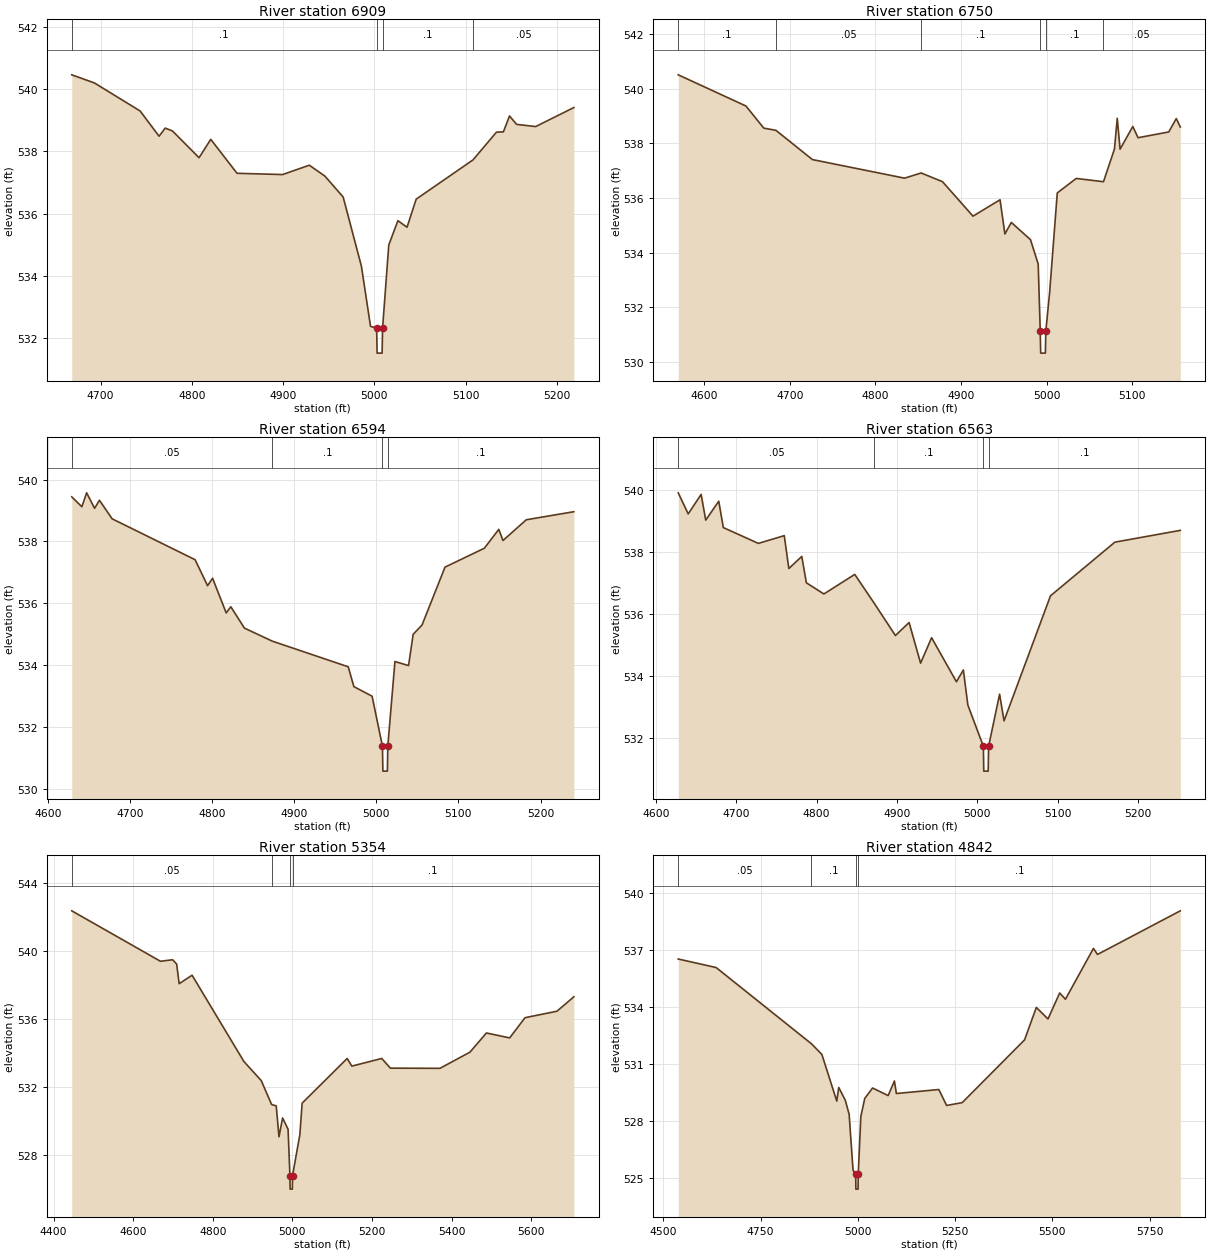
Type RM Length L Ch R = 1,6909,159,159,159
BEGIN DESCRIPTION:
Mapping XS fd5a0d65
END DESCRIPTION:
XS GIS Cut Line= 4
      2025057.07     13526236.95      2024899.69     13526026.60
      2024693.96     13526027.47      2024628.97     13526077.08
#Sta/Elev= 30
  4668.4  540.45  4693.2  540.19  4743.3  539.29  4764.1  538.48  4770.8  538.74
  4778.7  538.65  4807.9  537.79  4820.7  538.38  4849.5  537.29  4899.5  537.25
  4928.7  537.55  4945.8  537.20  4965.8  536.53  4985.8  534.31  4995.8  532.38
  5002.5  532.32  5003.0  531.52  5008.5  531.52  5009.0  532.32  5015.8  534.99
  5025.8  535.77  5035.8  535.56  5045.8  536.46  5108.1  537.72  5133.8  538.61
  5141.4  538.62  5148.1  539.13  5155.9  538.86  5176.8  538.79  5218.6  539.40
#Mann=4,-1,0
  4668.4     0.1       0  5002.5    0.07       0  5009.0     0.1       0
  5108.1    0.05       0
Bank Sta=5002.5,5009
Exp/Cntr=0.3,0.1

Type RM Length L Ch R = 1,6750,156,156,156
BEGIN DESCRIPTION:
Mapping XS 4a1a151c
END DESCRIPTION:
XS GIS Cut Line= 4
      2025106.56     13526192.70      2024921.26     13525924.22
      2024754.16     13525839.58      2024693.69     13525880.95
#Sta/Elev= 30
  4569.5  540.51  4648.6  539.37  4669.5  538.56  4683.7  538.48  4726.3  537.41
  4834.0  536.73  4853.4  536.92  4878.4  536.60  4914.0  535.34  4945.6  535.94
  4951.3  534.69  4958.8  535.11  4981.2  534.48  4990.2  533.59  4992.6  531.13
  4993.1  530.33  4998.6  530.33  4999.1  531.13  5003.6  532.56  5012.5  536.19
  5034.7  536.72  5066.5  536.60  5079.3  537.79  5082.6  538.92  5085.9  537.79
  5100.8  538.62  5106.9  538.21  5142.8  538.42  5151.6  538.91  5156.3  538.60
#Mann=6,-1,0
  4569.5     0.1       0  4683.7    0.05       0  4853.4     0.1       0
  4992.6    0.07       0  4999.1     0.1       0  5066.5    0.05       0
Bank Sta=4992.6,4999.1
Exp/Cntr=0.3,0.1

Type RM Length L Ch R = 1,6594,31,31,31
BEGIN DESCRIPTION:
Mapping XS 0f7ed58a
END DESCRIPTION:
XS GIS Cut Line= 4
      2025137.21     13526139.10      2025050.39     13525994.75
      2024910.41     13525721.31      2024938.29     13525588.33
#Sta/Elev= 30
  4629.1  539.44  4641.4  539.12  4647.2  539.57  4656.9  539.07  4662.8  539.33
  4678.3  538.73  4779.3  537.41  4794.5  536.57  4800.6  536.81  4817.2  535.69
  4822.8  535.89  4839.4  535.20  4873.2  534.78  4965.8  533.95  4972.7  533.31
  4994.9  533.00  5007.5  531.38  5008.0  530.58  5013.5  530.58  5014.0  531.38
  5022.7  534.12  5039.3  533.99  5044.9  535.00  5055.7  535.30  5083.7  537.17
  5131.6  537.78  5149.2  538.39  5154.3  538.03  5182.7  538.70  5240.6  538.96
#Mann=4,-1,0
  4629.1    0.05       0  4873.2     0.1       0  5007.5    0.07       0
  5014.0     0.1       0
Bank Sta=5007.5,5014
Exp/Cntr=0.3,0.1

Type RM Length L Ch R = 1,6563,1209,1209,1209
BEGIN DESCRIPTION:
Mapping XS fffeacd1
END DESCRIPTION:
XS GIS Cut Line= 5
      2025155.65     13526131.49      2025055.81     13525949.17
      2024964.67     13525762.54      2024969.01     13525610.63
      2024977.68     13525554.23
#Sta/Elev= 30
  4627.9  539.91  4640.3  539.23  4656.4  539.86  4662.1  539.03  4678.3  539.64
  4684.0  538.79  4727.6  538.28  4759.8  538.53  4765.5  537.47  4781.6  537.86
  4787.3  537.01  4809.1  536.65  4847.5  537.28  4872.0  536.34  4898.1  535.31
  4915.1  535.73  4929.4  534.42  4943.1  535.24  4974.0  533.82  4982.6  534.20
  4988.2  533.07  5007.5  531.74  5008.0  530.94  5013.5  530.94  5014.0  531.74
  5027.7  533.42  5033.2  532.56  5091.0  536.59  5171.1  538.32  5252.5  538.70
#Mann=4,-1,0
  4627.9    0.05       0  4872.0     0.1       0  5007.5    0.07       0
  5014.0     0.1       0
Bank Sta=5007.5,5014
Exp/Cntr=0.3,0.1

Type RM Length L Ch R = 1,5354,512,512,512
BEGIN DESCRIPTION:
Mapping XS 4b03554a
END DESCRIPTION:
XS GIS Cut Line= 4
      2026110.79     13525734.49      2026063.04     13525467.53
      2025435.87     13525118.13      2025174.23     13525195.29
#Sta/Elev= 30
  4445.6  542.39  4668.6  539.42  4699.0  539.51  4709.2  539.26  4715.5  538.10
  4748.0  538.60  4878.3  533.52  4921.8  532.40  4947.9  530.99  4959.5  530.91
  4966.4  529.09  4975.5  530.20  4989.3  529.53  4993.9  526.81  4994.4  526.01
  5000.0  526.01  5000.5  526.81  5018.9  529.22  5024.6  531.07  5137.8  533.70
  5149.5  533.25  5224.7  533.70  5246.4  533.13  5371.0  533.12  5446.3  534.07
  5487.8  535.20  5546.2  534.91  5584.8  536.10  5665.0  536.48  5707.5  537.33
#Mann=4,-1,0
  4445.6    0.05       0  4947.9     0.1       0  4993.9    0.07       0
  5000.5     0.1       0
Bank Sta=4993.9,5000.5
Exp/Cntr=0.3,0.1

Type RM Length L Ch R = 1,4842,423,423,423
BEGIN DESCRIPTION:
Mapping XS df2dd47e
END DESCRIPTION:
XS GIS Cut Line= 4
      2026243.71     13525113.69      2026054.36     13524951.03
      2025236.76     13524894.94      2025102.11     13525071.01
#Sta/Elev= 30
  4538.3  536.52  4635.8  536.07  4880.9  532.05  4907.6  531.49  4945.9  529.03
  4950.9  529.75  4967.7  529.08  4977.7  528.33  4987.7  525.39  4994.5  525.19
  4995.0  524.39  5000.6  524.39  5001.1  525.19  5007.8  528.22  5017.8  529.17
  5037.9  529.72  5078.0  529.32  5094.1  530.09  5099.1  529.43  5208.3  529.64
  5228.3  528.80  5268.4  528.95  5428.8  532.26  5458.9  533.97  5488.9  533.36
  5519.0  534.73  5533.8  534.40  5605.8  537.08  5616.2  536.76  5829.1  539.06
#Mann=4,-1,0
  4538.3    0.05       0  4880.9     0.1       0  4994.5    0.07       0
  5001.1     0.1       0
Bank Sta=4994.5,5001.1
Exp/Cntr=0.3,0.1

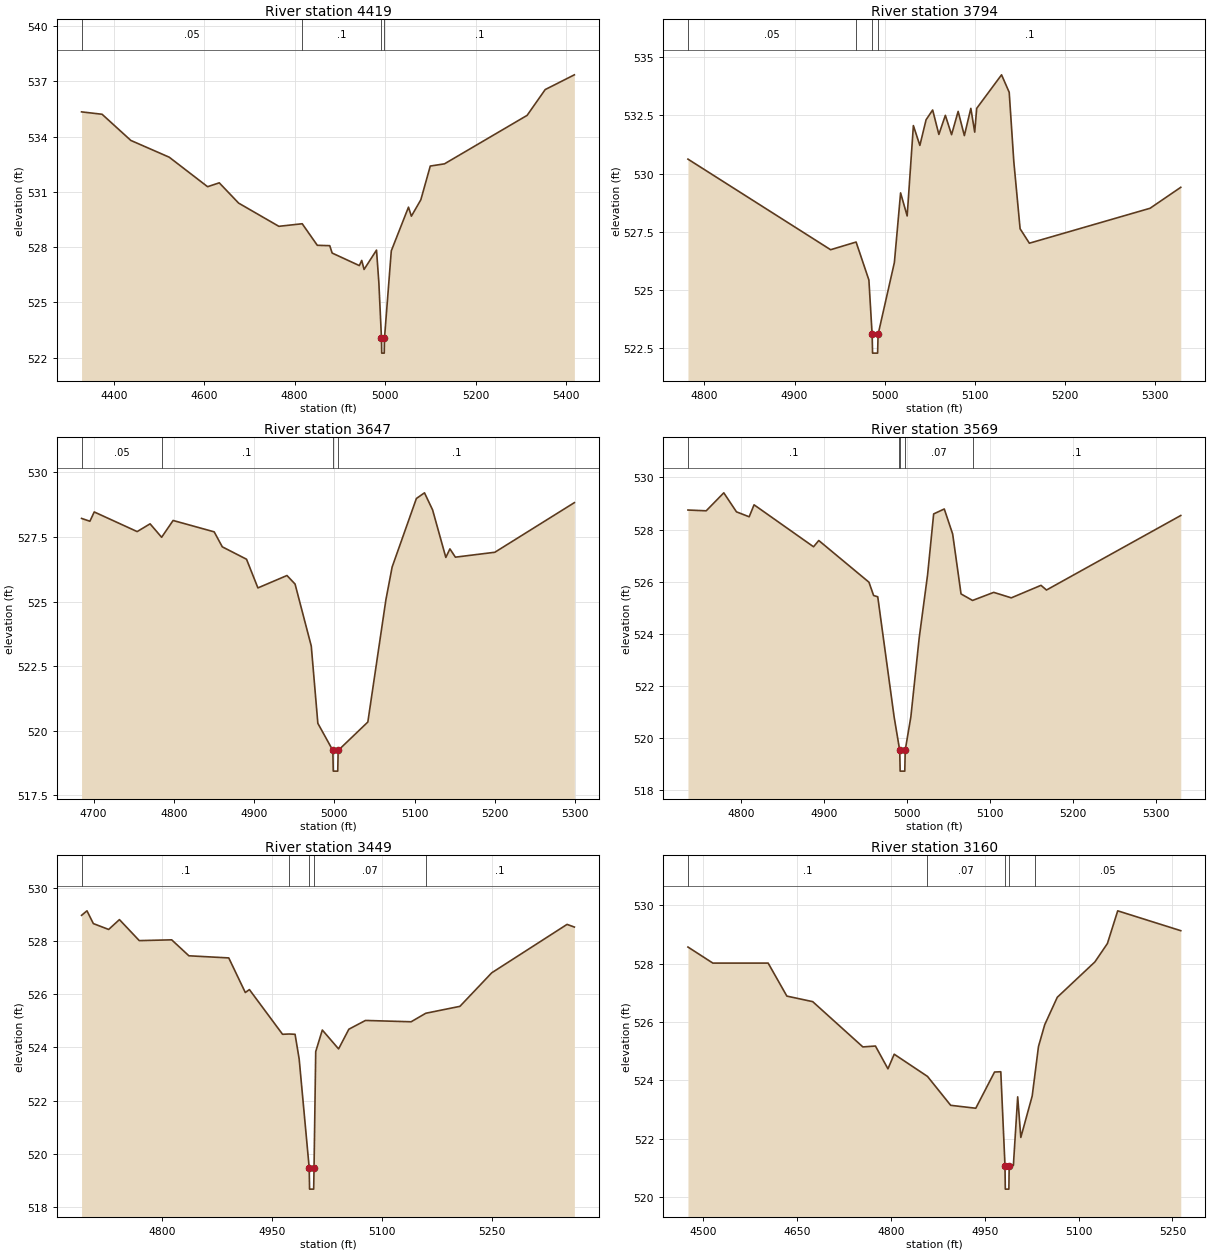
Type RM Length L Ch R = 1,4419,625,625,625
BEGIN DESCRIPTION:
Mapping XS 88724915
END DESCRIPTION:
XS GIS Cut Line= 4
      2026219.78     13524954.35      2026001.00     13524742.51
      2025469.75     13524579.31      2025240.57     13524589.73
#Sta/Elev= 30
  4328.8  535.34  4374.2  535.21  4437.8  533.79  4522.7  532.88  4607.5  531.28
  4633.3  531.49  4676.1  530.39  4765.1  529.13  4816.7  529.27  4850.1  528.10
  4877.6  528.08  4882.9  527.68  4943.0  527.00  4948.3  527.28  4953.5  526.79
  4981.0  527.84  4986.2  526.07  4992.0  523.05  4992.5  522.25  4998.1  522.25
  4998.6  523.05  5013.7  527.80  5051.7  530.17  5058.1  529.68  5079.0  530.57
  5099.9  532.40  5131.3  532.52  5314.0  535.15  5354.0  536.55  5418.5  537.35
#Mann=4,-1,0
  4328.8    0.05       0  4816.7     0.1       0  4992.0    0.07       0
  4998.6     0.1       0
Bank Sta=4992,4998.6
Exp/Cntr=0.3,0.1

Type RM Length L Ch R = 1,3794,147,147,147
BEGIN DESCRIPTION:
Mapping XS 6a4a3465
END DESCRIPTION:
XS GIS Cut Line= 4
      2026263.70     13524512.95      2026245.26     13524433.77
      2026073.82     13524269.92      2025851.89     13524325.37
#Sta/Elev= 30
  4781.7  530.62  4940.1  526.73  4968.4  527.06  4982.6  525.43  4986.2  523.09
  4986.7  522.29  4992.3  522.29  4992.8  523.09  5010.9  526.18  5017.8  529.17
  5025.1  528.18  5032.0  532.06  5039.2  531.21  5046.1  532.31  5053.4  532.73
  5060.3  531.68  5067.5  532.50  5074.4  531.67  5081.7  532.67  5088.6  531.63
  5095.8  532.80  5100.1  531.78  5102.3  532.80  5129.9  534.24  5138.4  533.49
  5143.5  530.52  5150.5  527.63  5160.8  527.01  5294.8  528.51  5328.9  529.41
#Mann=4,-1,0
  4781.7    0.05       0  4968.4     0.1       0  4986.2    0.07       0
  4992.8     0.1       0
Bank Sta=4986.2,4992.8
Exp/Cntr=0.3,0.1

Type RM Length L Ch R = 1,3647,78,78,78
BEGIN DESCRIPTION:
Mapping XS af87d55a
END DESCRIPTION:
XS GIS Cut Line= 4
      2026438.22     13524234.78      2026314.49     13524179.43
      2025983.55     13524221.74      2025862.08     13524300.95
#Sta/Elev= 30
  4685.0  528.22  4695.4  528.11  4700.8  528.47  4754.3  527.71  4770.4  528.01
  4784.8  527.49  4799.1  528.14  4850.3  527.70  4860.4  527.12  4890.6  526.64
  4904.8  525.53  4941.0  526.01  4951.1  525.68  4971.3  523.28  4979.5  520.29
  4998.2  519.24  4998.7  518.44  5004.3  518.44  5004.8  519.24  5041.8  520.34
  5064.3  525.07  5072.1  526.34  5102.3  528.99  5112.4  529.21  5122.5  528.55
  5139.0  526.71  5144.1  527.04  5150.9  526.72  5200.1  526.91  5299.2  528.83
#Mann=4,-1,0
  4685.0    0.05       0  4784.8     0.1       0  4998.2    0.07       0
  5004.8     0.1       0
Bank Sta=4998.2,5004.8
Exp/Cntr=0.3,0.1

Type RM Length L Ch R = 1,3569,120,120,120
BEGIN DESCRIPTION:
Mapping XS 525dfe4a
END DESCRIPTION:
XS GIS Cut Line= 4
      2026367.66     13524152.30      2026288.45     13524102.39
      2025969.44     13524145.79      2025852.36     13524280.55
#Sta/Elev= 30
  4735.5  528.75  4757.5  528.72  4778.7  529.41  4794.0  528.68  4809.3  528.49
  4815.2  528.95  4886.9  527.34  4893.2  527.58  4953.7  525.98  4959.3  525.47
  4964.3  525.42  4984.0  520.82  4990.3  519.62  4990.8  519.53  4991.3  518.73
  4996.9  518.73  4997.4  519.53  5004.2  520.81  5014.3  523.85  5024.4  526.27
  5031.7  528.60  5044.5  528.79  5054.6  527.83  5064.7  525.53  5078.6  525.28
  5104.1  525.59  5125.3  525.38  5161.1  525.86  5167.7  525.68  5329.6  528.54
#Mann=5,-1,0
  4735.5     0.1       0  4990.3    0.07       0  4990.8    0.07       0
  4997.4    0.07       0  5078.6     0.1       0
Bank Sta=4990.8,4997.4
Exp/Cntr=0.3,0.1

Type RM Length L Ch R = 1,3449,289,289,289
BEGIN DESCRIPTION:
Mapping XS e2a7a812
END DESCRIPTION:
XS GIS Cut Line= 4
      2026338.35     13524042.70      2026217.92     13523956.99
      2025922.78     13524099.13      2025826.50     13524271.23
#Sta/Elev= 30
  4689.7  528.96  4697.1  529.13  4705.8  528.65  4726.7  528.43  4741.4  528.80
  4768.5  528.01  4812.7  528.04  4836.2  527.44  4890.6  527.36  4913.2  526.06
  4918.8  526.17  4964.0  524.49  4973.2  524.50  4981.1  524.49  4986.7  523.56
  5000.4  519.47  5000.9  518.67  5006.5  518.67  5007.0  519.47  5009.3  523.84
  5018.3  524.65  5040.5  523.94  5054.5  524.68  5077.2  525.01  5139.5  524.96
  5159.5  525.28  5206.1  525.54  5249.5  526.80  5352.3  528.62  5362.3  528.52
#Mann=5,-1,0
  4689.7     0.1       0  4973.2    0.07       0  5000.4    0.07       0
  5007.0    0.07       0  5159.5     0.1       0
Bank Sta=5000.4,5007
Exp/Cntr=0.3,0.1

Type RM Length L Ch R = 1,3160,516,516,516
BEGIN DESCRIPTION:
Mapping XS c316425d
END DESCRIPTION:
XS GIS Cut Line= 4
      2026327.52     13524002.57      2026263.49     13523854.99
      2025737.23     13523819.18      2025713.37     13523915.73
#Sta/Elev= 30
  4475.6  528.57  4515.4  528.02  4603.8  528.02  4633.7  526.89  4675.0  526.70
  4755.2  525.15  4775.3  525.18  4795.3  524.40  4805.3  524.90  4858.5  524.14
  4895.6  523.15  4935.7  523.05  4965.7  524.29  4975.7  524.30  4982.4  521.08
  4982.9  520.28  4988.6  520.28  4989.1  521.08  4995.8  521.09  5002.7  523.44
  5007.7  522.05  5025.9  523.47  5030.3  524.21  5035.9  525.16  5045.9  525.91
  5066.0  526.85  5126.1  528.06  5146.1  528.69  5162.6  529.81  5263.4  529.13
#Mann=5,-1,0
  4475.6     0.1       0  4858.5    0.07       0  4982.4    0.07       0
  4989.1    0.07       0  5030.3    0.05       0
Bank Sta=4982.4,4989.1
Exp/Cntr=0.3,0.1

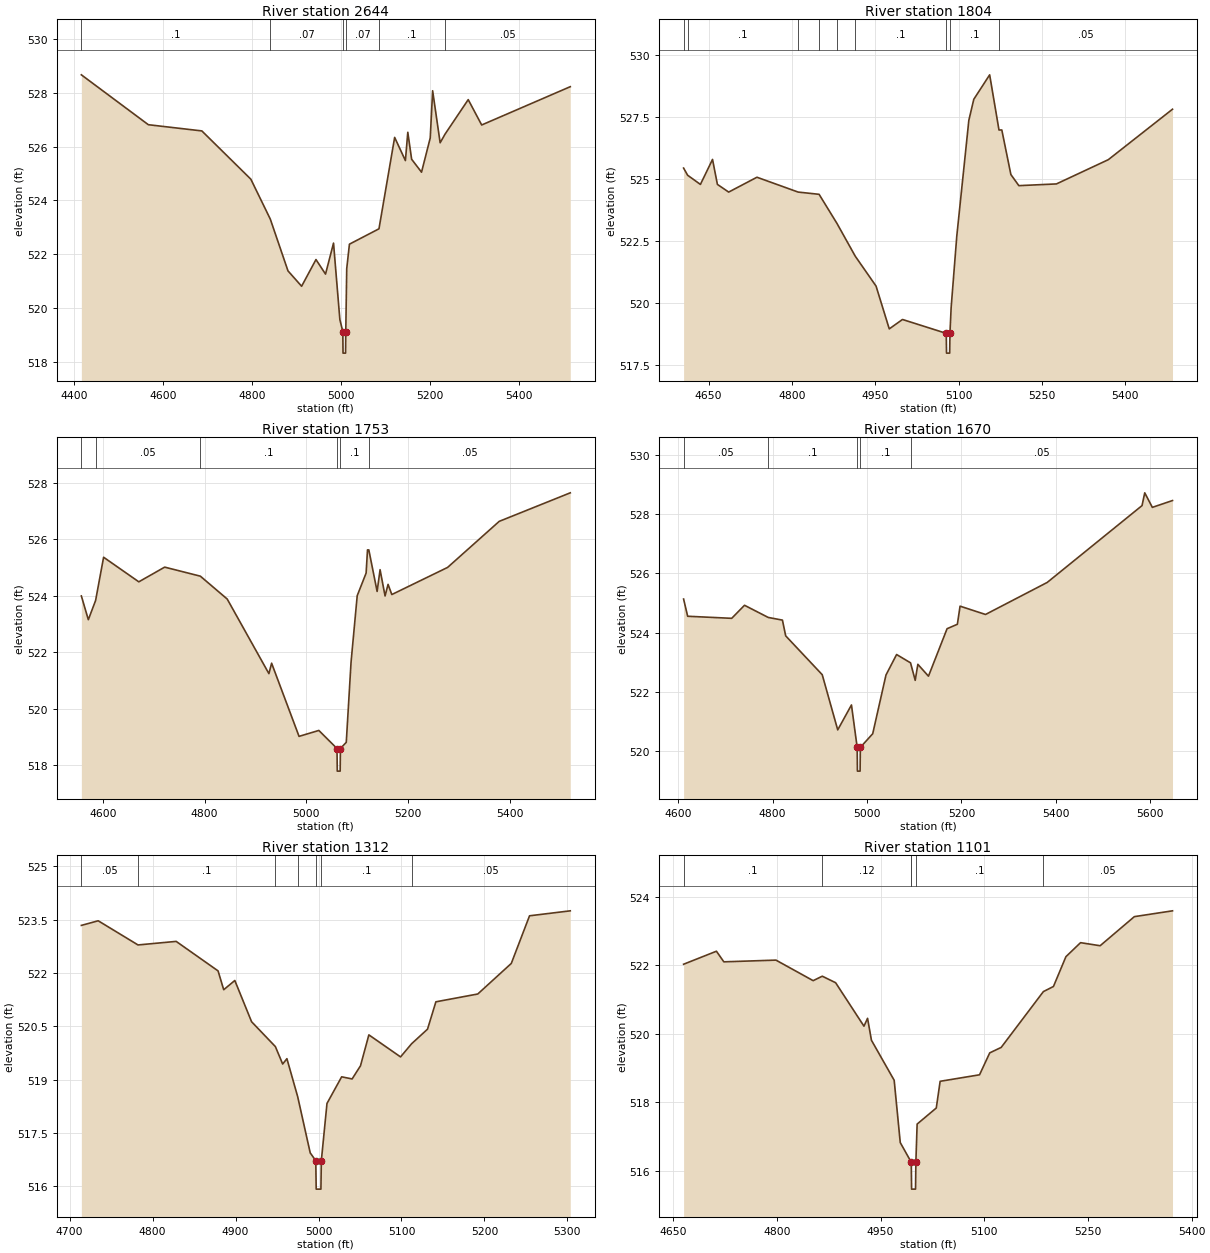
Type RM Length L Ch R = 1,2644,840,840,840
BEGIN DESCRIPTION:
Mapping XS 73d6285e
END DESCRIPTION:
XS GIS Cut Line= 4
      2026530.53     13523895.24      2026506.66     13523617.50
      2026059.61     13523439.55      2025740.64     13523558.89
#Sta/Elev= 30
  4415.8  528.66  4566.6  526.81  4687.0  526.58  4797.3  524.79  4841.1  523.31
  4880.9  521.39  4911.6  520.82  4943.9  521.81  4965.4  521.27  4983.4  522.42
  4997.7  519.58  5004.3  519.14  5004.8  518.34  5010.5  518.34  5011.0  519.14
  5013.1  521.47  5019.2  522.38  5085.7  522.95  5121.0  526.34  5145.2  525.48
  5150.6  526.53  5159.2  525.53  5181.5  525.05  5201.1  526.32  5206.5  528.07
  5223.4  526.14  5234.4  526.46  5286.6  527.74  5316.9  526.80  5516.3  528.22
#Mann=6,-1,0
  4415.8     0.1       0  4841.1    0.07       0  5004.3    0.07       0
  5011.0    0.07       0  5085.7     0.1       0  5234.4    0.05       0
Bank Sta=5004.3,5011
Exp/Cntr=0.3,0.1

Type RM Length L Ch R = 1,1804,51,51,51
BEGIN DESCRIPTION:
Mapping XS 6721bccc
END DESCRIPTION:
XS GIS Cut Line= 4
      2026584.80     13523229.05      2026322.09     13523178.99
      2026083.48     13523278.96      2025770.99     13523446.05
#Sta/Elev= 30
  4604.9  525.44  4612.2  525.15  4635.2  524.78  4657.0  525.79  4665.8  524.78
  4686.1  524.47  4737.0  525.07  4811.2  524.47  4848.9  524.38  4881.2  523.20
  4914.0  521.88  4951.5  520.67  4975.3  518.94  4999.1  519.32  5077.9  518.76
  5078.4  517.96  5084.1  517.96  5084.6  518.76  5086.7  519.79  5096.9  522.69
  5118.6  527.37  5127.5  528.22  5156.1  529.21  5172.9  526.98  5178.0  526.98
  5194.3  525.18  5208.7  524.73  5276.4  524.80  5369.8  525.78  5485.4  527.82
#Mann=9,-1,0
  4604.9    0.08       0  4612.2     0.1       0  4811.2    0.12       0
  4848.9     0.1       0  4881.2    0.12       0  4914.0     0.1       0
  5077.9    0.07       0  5084.6     0.1       0  5172.9    0.05       0
Bank Sta=5077.9,5084.6
Exp/Cntr=0.3,0.1

Type RM Length L Ch R = 1,1753,83,83,83
BEGIN DESCRIPTION:
Mapping XS bbf0da26
END DESCRIPTION:
XS GIS Cut Line= 4
      2026608.69     13523131.39      2026322.09     13523127.99
      2026064.93     13523231.08      2025723.22     13523433.04
#Sta/Elev= 30
  4558.0  523.99  4571.7  523.15  4586.0  523.83  4601.7  525.36  4670.9  524.49
  4721.7  525.01  4791.8  524.69  4844.6  523.88  4926.5  521.24  4931.8  521.61
  4985.7  519.02  5024.6  519.23  5060.3  518.59  5060.8  517.79  5066.5  517.79
  5067.0  518.59  5078.5  518.81  5087.9  521.65  5100.0  524.00  5117.5  524.80
  5120.2  525.62  5122.8  525.62  5139.1  524.15  5144.9  524.92  5154.7  523.99
  5160.6  524.40  5168.0  524.04  5277.6  525.00  5379.0  526.63  5518.6  527.64
#Mann=6,-1,0
  4558.0    0.08       0  4586.0    0.05       0  4791.8     0.1       0
  5060.3    0.07       0  5067.0     0.1       0  5122.8    0.05       0
Bank Sta=5060.3,5067
Exp/Cntr=0.3,0.1

Type RM Length L Ch R = 1,1670,358,358,358
BEGIN DESCRIPTION:
Mapping XS b6aa718f
END DESCRIPTION:
XS GIS Cut Line= 4
      2026543.52     13523068.45      2026286.28     13523046.61
      2026011.76     13523181.16      2025598.65     13523408.46
#Sta/Elev= 30
  4611.7  525.13  4620.3  524.55  4713.6  524.48  4740.7  524.92  4790.9  524.51
  4821.0  524.42  4827.9  523.89  4905.3  522.58  4938.1  520.72  4967.2  521.56
  4979.3  520.13  4979.8  519.33  4985.5  519.33  4986.0  520.13  5012.2  520.59
  5040.3  522.57  5062.8  523.26  5092.3  522.98  5102.2  522.39  5107.8  522.93
  5130.3  522.53  5169.7  524.13  5191.5  524.28  5197.2  524.89  5251.1  524.61
  5381.8  525.69  5582.6  528.28  5588.3  528.71  5604.4  528.22  5647.1  528.45
#Mann=5,-1,0
  4611.7    0.05       0  4790.9     0.1       0  4979.3    0.07       0
  4986.0     0.1       0  5092.3    0.05       0
Bank Sta=4979.3,4986
Exp/Cntr=0.3,0.1

Type RM Length L Ch R = 1,1312,211,211,211
BEGIN DESCRIPTION:
Mapping XS ae3b3d7f
END DESCRIPTION:
XS GIS Cut Line= 4
      2026382.87     13522793.81      2026300.39     13522739.54
      2025878.29     13522799.22      2025849.50     13522856.80
#Sta/Elev= 30
  4714.1  523.34  4734.4  523.47  4782.4  522.79  4828.4  522.89  4878.9  522.06
  4885.7  521.53  4899.1  521.79  4919.3  520.63  4948.0  519.93  4956.8  519.44
  4961.9  519.59  4974.9  518.52  4990.0  516.94  4996.7  516.72  4997.2  515.92
  5002.9  515.92  5003.4  516.72  5010.2  518.33  5027.9  519.08  5040.5  519.02
  5050.6  519.39  5060.7  520.26  5098.9  519.64  5112.2  520.01  5131.4  520.42
  5141.5  521.19  5192.0  521.41  5232.4  522.27  5254.4  523.61  5303.5  523.75
#Mann=7,-1,0
  4714.1    0.05       0  4782.4     0.1       0  4948.0    0.12       0
  4974.9     0.1       0  4996.7    0.07       0  5003.4     0.1       0
  5112.2    0.05       0
Bank Sta=4996.7,5003.4
Exp/Cntr=0.3,0.1

Type RM Length L Ch R = 1,1101,236,236,236
BEGIN DESCRIPTION:
Mapping XS 9ddc22f9
END DESCRIPTION:
XS GIS Cut Line= 4
      2026359.13     13522614.91      2026159.33     13522535.55
      2025855.51     13522625.61      2025732.74     13522750.77
#Sta/Elev= 30
  4665.1  522.03  4712.6  522.41  4723.3  522.10  4798.7  522.15  4852.5  521.55
  4865.7  521.68  4885.0  521.49  4926.0  520.22  4931.2  520.45  4936.8  519.81
  4969.7  518.64  4978.5  516.82  4994.0  516.26  4994.4  516.26  4994.9  515.46
  5000.6  515.46  5001.1  516.26  5002.9  517.36  5030.6  517.83  5036.2  518.61
  5093.2  518.80  5107.9  519.44  5124.5  519.60  5185.5  521.23  5200.1  521.38
  5218.1  522.25  5239.3  522.66  5267.6  522.57  5317.1  523.42  5372.3  523.59
#Mann=6,-1,0
  4665.1     0.1       0  4865.7    0.12       0  4994.0     0.1       0
  4994.4    0.07       0  5001.1     0.1       0  5185.5    0.05       0
Bank Sta=4994.4,5001.1
Exp/Cntr=0.3,0.1