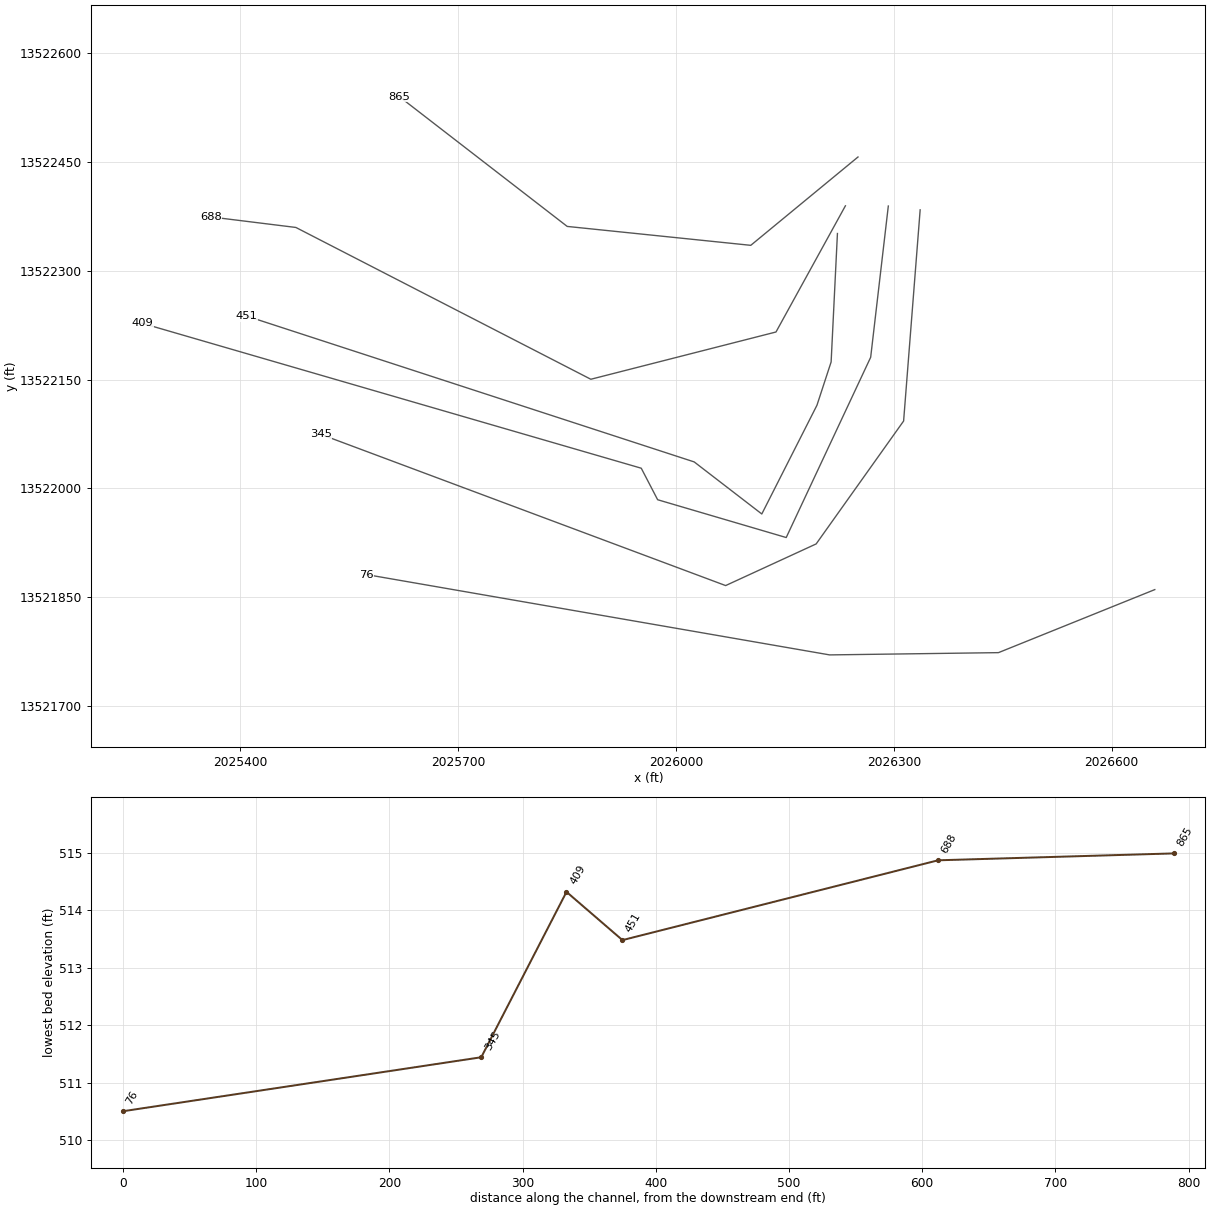
HEC-RAS study UNT 158 in Lagunillas Cr Wtrshd.prj: UNT 158 in Lagunillas Cr Wtrshd Base Level Engineering

--- UNT 158 in Lagunillas Cr Wtrshd.g01 (geometry) --- (continued)

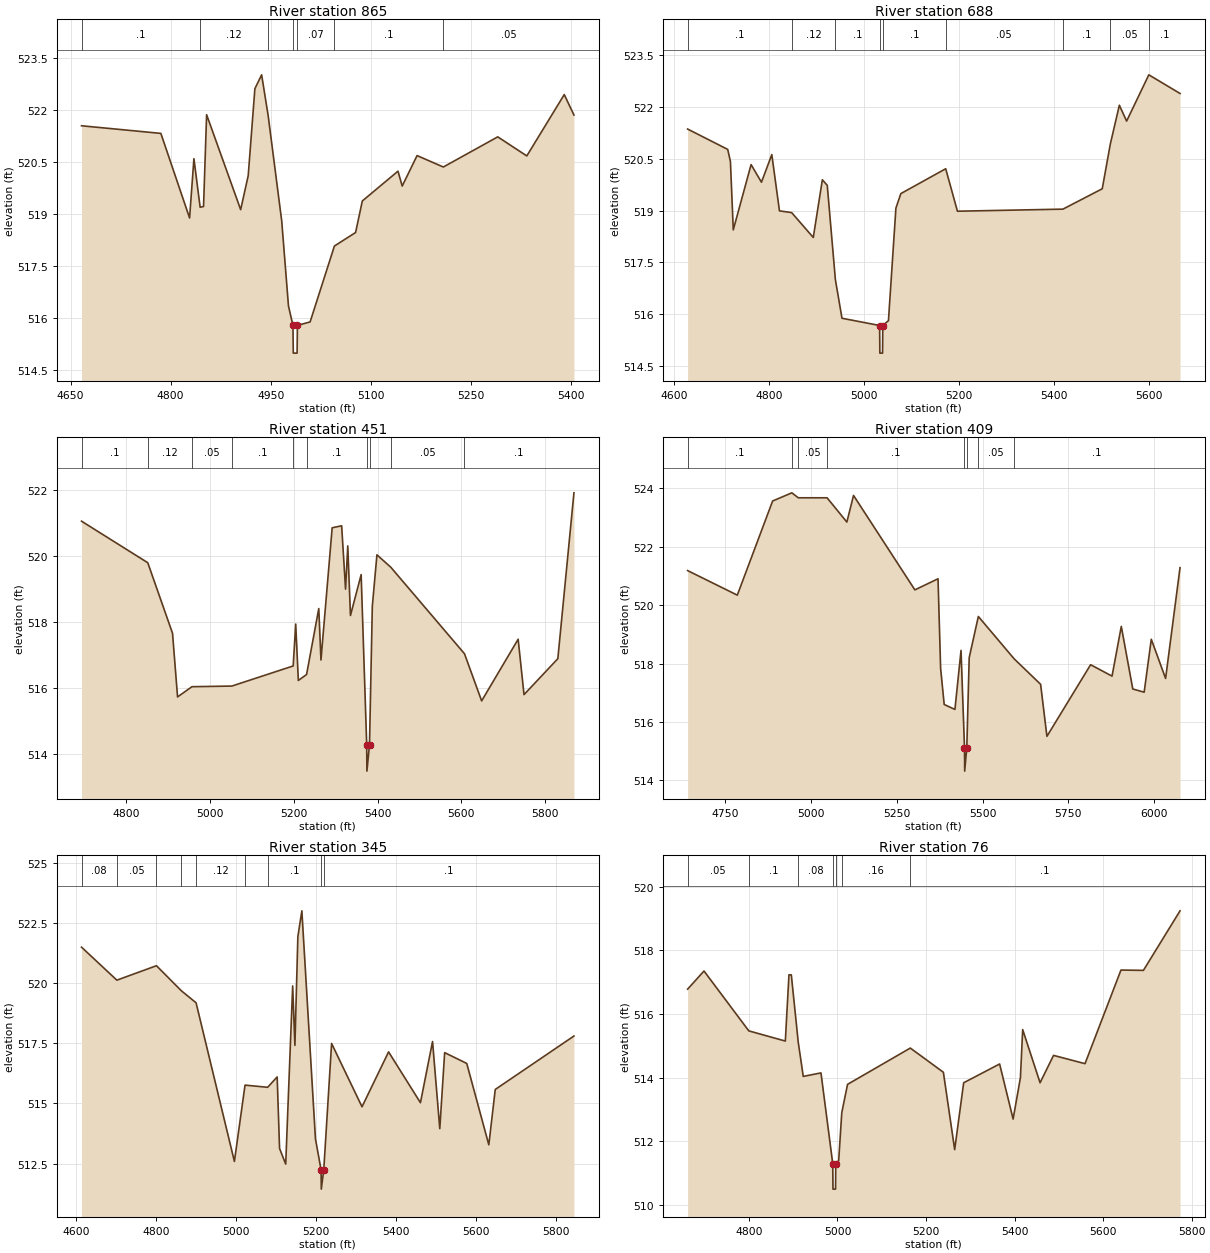
Type RM Length L Ch R = 1,865,177,177,177
BEGIN DESCRIPTION:
Mapping XS 386f61d6
END DESCRIPTION:
XS GIS Cut Line= 4
      2026250.59     13522456.48      2026102.90     13522334.81
      2025850.08     13522360.85      2025619.15     13522539.37
#Sta/Elev= 30
  4666.5  521.55  4785.3  521.33  4828.3  518.89  4834.8  520.60  4844.1  519.20
  4849.2  519.22  4853.8  521.87  4904.8  519.13  4916.1  520.11  4926.1  522.62
  4936.2  523.02  4946.0  521.84  4966.3  518.80  4976.4  516.35  4983.1  515.79
  4983.6  514.99  4989.3  514.99  4989.8  515.79  5008.8  515.89  5045.2  518.08
  5076.9  518.47  5087.0  519.38  5140.4  520.24  5146.7  519.81  5169.0  520.69
  5208.3  520.36  5289.8  521.23  5333.3  520.68  5389.4  522.45  5403.9  521.86
#Mann=7,-1,0
  4666.5     0.1       0  4844.1    0.12       0  4946.0    0.07       0
  4983.1    0.07       0  4989.8    0.07       0  5045.2     0.1       0
  5208.3    0.05       0
Bank Sta=4983.1,4989.8
Exp/Cntr=0.3,0.1

Type RM Length L Ch R = 1,688,237,237,237
BEGIN DESCRIPTION:
Mapping XS b218a59a
END DESCRIPTION:
XS GIS Cut Line= 5
      2026233.24     13522389.23      2026137.63     13522215.45
      2025882.63     13522150.35      2025476.37     13522359.43
      2025359.29     13522373.93
#Sta/Elev= 30
  4628.7  521.36  4713.1  520.77  4718.8  520.42  4724.8  518.44  4762.3  520.33
  4784.1  519.82  4805.9  520.62  4822.0  518.99  4847.6  518.94  4893.2  518.22
  4912.3  519.89  4922.6  519.73  4939.7  517.00  4953.6  515.88  5032.8  515.67
  5033.3  514.87  5039.0  514.87  5039.5  515.67  5051.4  515.81  5067.1  519.07
  5077.5  519.49  5171.9  520.21  5196.6  518.98  5418.6  519.04  5501.4  519.63
  5518.3  520.92  5537.4  522.05  5552.7  521.59  5599.4  522.93  5665.1  522.39
#Mann=9,-1,0
  4628.7     0.1       0  4847.6    0.12       0  4939.7     0.1       0
  5032.8    0.07       0  5039.5     0.1       0  5171.9    0.05       0
  5418.6     0.1       0  5518.3    0.05       0  5599.4     0.1       0
Bank Sta=5032.8,5039.5
Exp/Cntr=0.3,0.1

Type RM Length L Ch R = 1,451,42,42,42
BEGIN DESCRIPTION:
Mapping XS 3ae6c8c5
END DESCRIPTION:
XS GIS Cut Line= 6
      2026222.26     13522351.10      2026213.58     13522174.22
      2026194.05     13522114.54      2026118.09     13521964.80
      2026024.98     13522036.51      2025408.51     13522237.39
#Sta/Elev= 30
  4694.5  521.06  4852.4  519.80  4911.4  517.66  4923.4  515.73  4957.6  516.04
  5052.9  516.06  5199.0  516.67  5205.0  517.94  5211.3  516.23  5230.9  516.41
  5260.0  518.41  5265.2  516.85  5291.9  520.86  5314.5  520.92  5323.8  519.00
  5329.1  520.31  5335.5  518.20  5361.0  519.44  5374.2  514.28  5374.7  513.48
  5380.9  514.28  5387.6  518.48  5398.6  520.04  5431.9  519.66  5607.3  517.04
  5648.2  515.61  5735.2  517.48  5749.2  515.80  5829.8  516.89  5868.2  521.92
#Mann=10,-1,0
  4694.5     0.1       0  4852.4    0.12       0  4957.6    0.05       0
  5052.9     0.1       0  5199.0    0.05       0  5230.9     0.1       0
  5374.2   0.033       0  5380.9     0.1       0  5431.9    0.05       0
  5607.3     0.1       0
Bank Sta=5374.2,5380.9
Exp/Cntr=0.3,0.1

Type RM Length L Ch R = 1,409,64,64,64
BEGIN DESCRIPTION:
Mapping XS ea460297
END DESCRIPTION:
XS GIS Cut Line= 6
      2026292.34     13522388.93      2026268.04     13522180.61
      2026151.72     13521932.35      2025974.63     13521984.43
      2025952.07     13522027.83      2025264.52     13522227.50
#Sta/Elev= 30
  4639.7  521.18  4784.6  520.34  4887.6  523.56  4943.7  523.84  4962.4  523.67
  5046.4  523.67  5104.1  522.84  5123.6  523.75  5302.5  520.52  5370.0  520.90
  5377.6  517.83  5388.0  516.60  5419.3  516.43  5437.1  518.45  5447.2  515.12
  5447.7  514.32  5453.9  515.12  5460.9  518.20  5487.6  519.61  5592.1  518.16
  5669.2  517.29  5687.6  515.51  5815.0  517.96  5877.5  517.57  5904.5  519.27
  5938.0  517.13  5971.2  517.02  5992.0  518.83  6033.7  517.49  6075.8  521.28
#Mann=8,-1,0
  4639.7     0.1       0  4943.7    0.12       0  4962.4    0.05       0
  5046.4     0.1       0  5447.2   0.033       0  5453.9     0.1       0
  5487.6    0.05       0  5592.1     0.1       0
Bank Sta=5447.2,5453.9
Exp/Cntr=0.3,0.1

Type RM Length L Ch R = 1,345,269,269,269
BEGIN DESCRIPTION:
Mapping XS dd293e6a
END DESCRIPTION:
XS GIS Cut Line= 5
      2026336.20     13522383.68      2026313.41     13522092.84
      2026192.96     13521923.57      2026068.29     13521866.20
      2025510.55     13522074.53
#Sta/Elev= 30
  4613.4  521.49  4701.8  520.12  4800.9  520.72  4863.1  519.68  4900.0  519.18
  4995.9  512.59  5022.5  515.76  5079.1  515.67  5102.9  516.10  5108.9  513.13
  5124.3  512.48  5141.7  519.88  5147.3  517.41  5154.7  521.93  5164.7  523.00
  5198.7  513.53  5212.8  512.24  5213.3  511.44  5219.5  512.24  5239.1  517.49
  5315.2  514.86  5381.7  517.14  5461.4  515.03  5491.7  517.57  5509.8  513.95
  5522.0  517.11  5577.3  516.66  5632.5  513.28  5648.6  515.58  5845.5  517.80
#Mann=9,-1,0
  4613.4    0.08       0  4701.8    0.05       0  4800.9    0.08       0
  4863.1     0.1       0  4900.0    0.12       0  5022.5    0.16       0
  5079.1     0.1       0  5212.8    0.07       0  5219.5     0.1       0
Bank Sta=5212.8,5219.5
Exp/Cntr=0.3,0.1

Type RM Length L Ch R = 1,76,0,0,0
BEGIN DESCRIPTION:
UNT 158 in Lagunillas Cr Wtrshd 1.0
END DESCRIPTION:
XS GIS Cut Line= 4
      2026659.34     13521860.64      2026444.05     13521773.83
      2026211.52     13521770.71      2025573.53     13521881.38
#Sta/Elev= 30
  4661.6  516.78  4698.6  517.35  4799.8  515.47  4882.3  515.15  4890.5  517.23
  4895.8  517.23  4911.5  515.11  4922.8  514.04  4962.8  514.15  4989.4  511.30
  4989.9  510.50  4995.7  510.50  4996.2  511.30  5002.8  511.39  5009.8  512.90
  5022.8  513.79  5164.6  514.93  5239.3  514.17  5264.8  511.74  5285.1  513.84
  5366.3  514.43  5396.8  512.70  5413.3  514.00  5418.4  515.51  5457.7  513.84
  5488.1  514.70  5559.2  514.44  5640.4  517.38  5691.1  517.37  5773.8  519.24
#Mann=7,-1,0
  4661.6    0.05       0  4799.8     0.1       0  4911.5    0.08       0
  4989.4    0.07       0  4996.2    0.08       0  5009.8    0.16       0
  5164.6     0.1       0
Bank Sta=4989.4,4996.2
Exp/Cntr=0.3,0.1

Chan Stop Cuts=-1