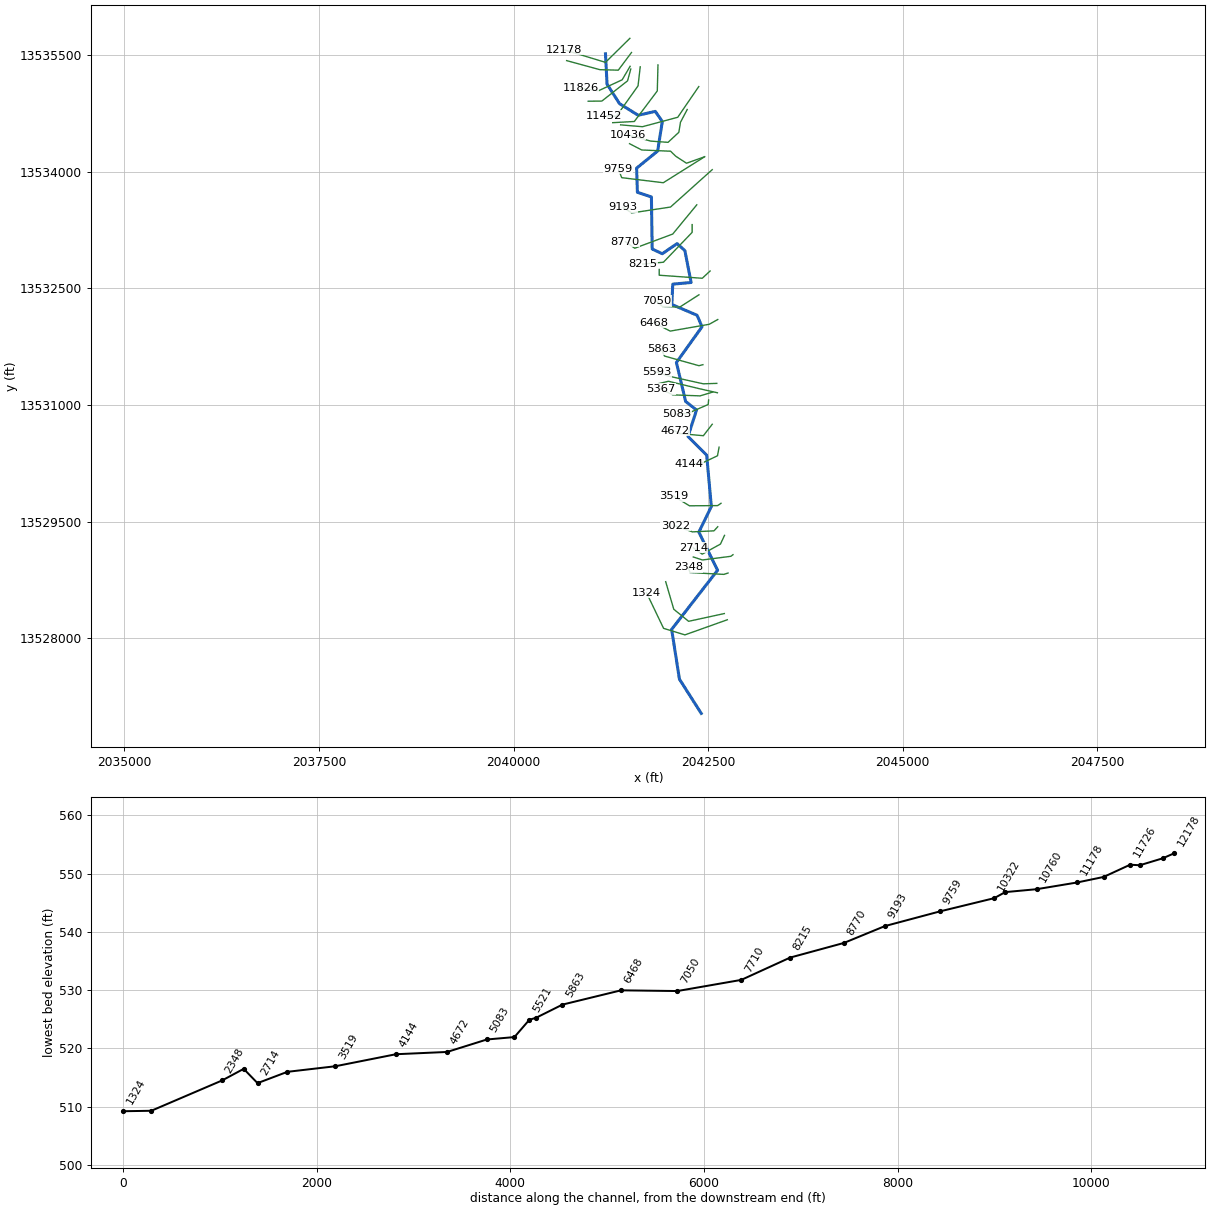
--- UNT 160 in Lagunillas Cr Wtrshd.prj (project) ---

Proj Title=UNT 160 in Lagunillas Cr Wtrshd Base Level Engineering
Current Plan=p01
Default Exp/Contr=0.3,0.1
English Units
Geom File=g01
Flow File=f01
Plan File=p01
BEGIN DESCRIPTION:
UNT 160 in Lagunillas Cr Wtrshd
END DESCRIPTION:

--- UNT 160 in Lagunillas Cr Wtrshd.p01 (plan) ---

Plan Title=Multiple Run
Short Identifier=Multiple
Geom File=g01
Flow File=f01
Subcritical Flow
K Sum by GR= 0
Std Step Tol= 0.01
Critical Tol= 0.01
Num of Std Step Trials= 20
Max Error Tol= 0.3
Flow Tol Ratio= 0.001
Split Flow NTrial= 30
Split Flow Tol= 0.02
Split Flow Ratio= 0.02
Log Output Level= 0
Friction Slope Method= 1
Unsteady Friction Slope Method= 2
Unsteady Bridges Friction Slope Method= 1
Parabolic Critical Depth
Global Vel Dist=  1 , 1 , 1
Global Log Level= 0
CheckData=True
Encroach Param= -1, 0, 0, 0
BEGIN DESCRIPTION:
Multiple Run
END DESCRIPTION:

--- UNT 160 in Lagunillas Cr Wtrshd.f01 (steady flow) ---

Flow Title=Multiple
Number of Profiles=7
Profile Names=10-year,25-year,50-year,1pct_min,100-year,1pct_plu,500-year
River Rch & RM= UNT 160 in Lagun,Reach-1,12178
     116     152     180     107     213     425     302
River Rch & RM= UNT 160 in Lagun,Reach-1,10760
     223     304     370     225     448     894     667
River Rch & RM= UNT 160 in Lagun,Reach-1,6468
     286     395     485     297     592    1181     894
Boundary for River Rch & Prof#=UNT 160 in Lagun,Reach-1,1
Up Type=0
Dn Type=3
Dn Slope=0.005
Boundary for River Rch & Prof#=UNT 160 in Lagun,Reach-1,2
Up Type=0
Dn Type=3
Dn Slope=0.005
Boundary for River Rch & Prof#=UNT 160 in Lagun,Reach-1,3
Up Type=0
Dn Type=3
Dn Slope=0.005
Boundary for River Rch & Prof#=UNT 160 in Lagun,Reach-1,4
Up Type=0
Dn Type=3
Dn Slope=0.005
Boundary for River Rch & Prof#=UNT 160 in Lagun,Reach-1,5
Up Type=0
Dn Type=3
Dn Slope=0.005
Boundary for River Rch & Prof#=UNT 160 in Lagun,Reach-1,6
Up Type=0
Dn Type=3
Dn Slope=0.005
Boundary for River Rch & Prof#=UNT 160 in Lagun,Reach-1,7
Up Type=0
Dn Type=3
Dn Slope=0.005

--- UNT 160 in Lagunillas Cr Wtrshd.g01 (geometry) ---

Geom Title=Existing Conditions

River Reach=UNT 160 in Lagun,Reach-1
Reach XY= 30
      2041180.80     13535514.54      2041200.80     13535124.54
      2041360.80     13534874.54      2041600.80     13534724.54
      2041820.80     13534774.54      2041910.80     13534644.54
      2041850.80     13534264.54      2041580.80     13534044.54
      2041590.80     13533734.54      2041770.80     13533674.54
      2041780.80     13533004.54      2041910.80     13532944.54
      2042100.80     13533074.54      2042200.80     13532984.54
      2042280.80     13532574.54      2042045.20     13532553.32
      2042033.05     13532292.04      2042357.70     13532153.15
      2042420.80     13532004.54      2042091.96     13531545.51
      2042210.80     13531044.54      2042350.80     13530934.54
      2042240.80     13530594.54      2042480.80     13530354.54
      2042540.80     13529694.54      2042380.80     13529364.54
      2042620.80     13528874.54      2042030.80     13528114.54
      2042130.80     13527474.54      2042410.80     13527034.54

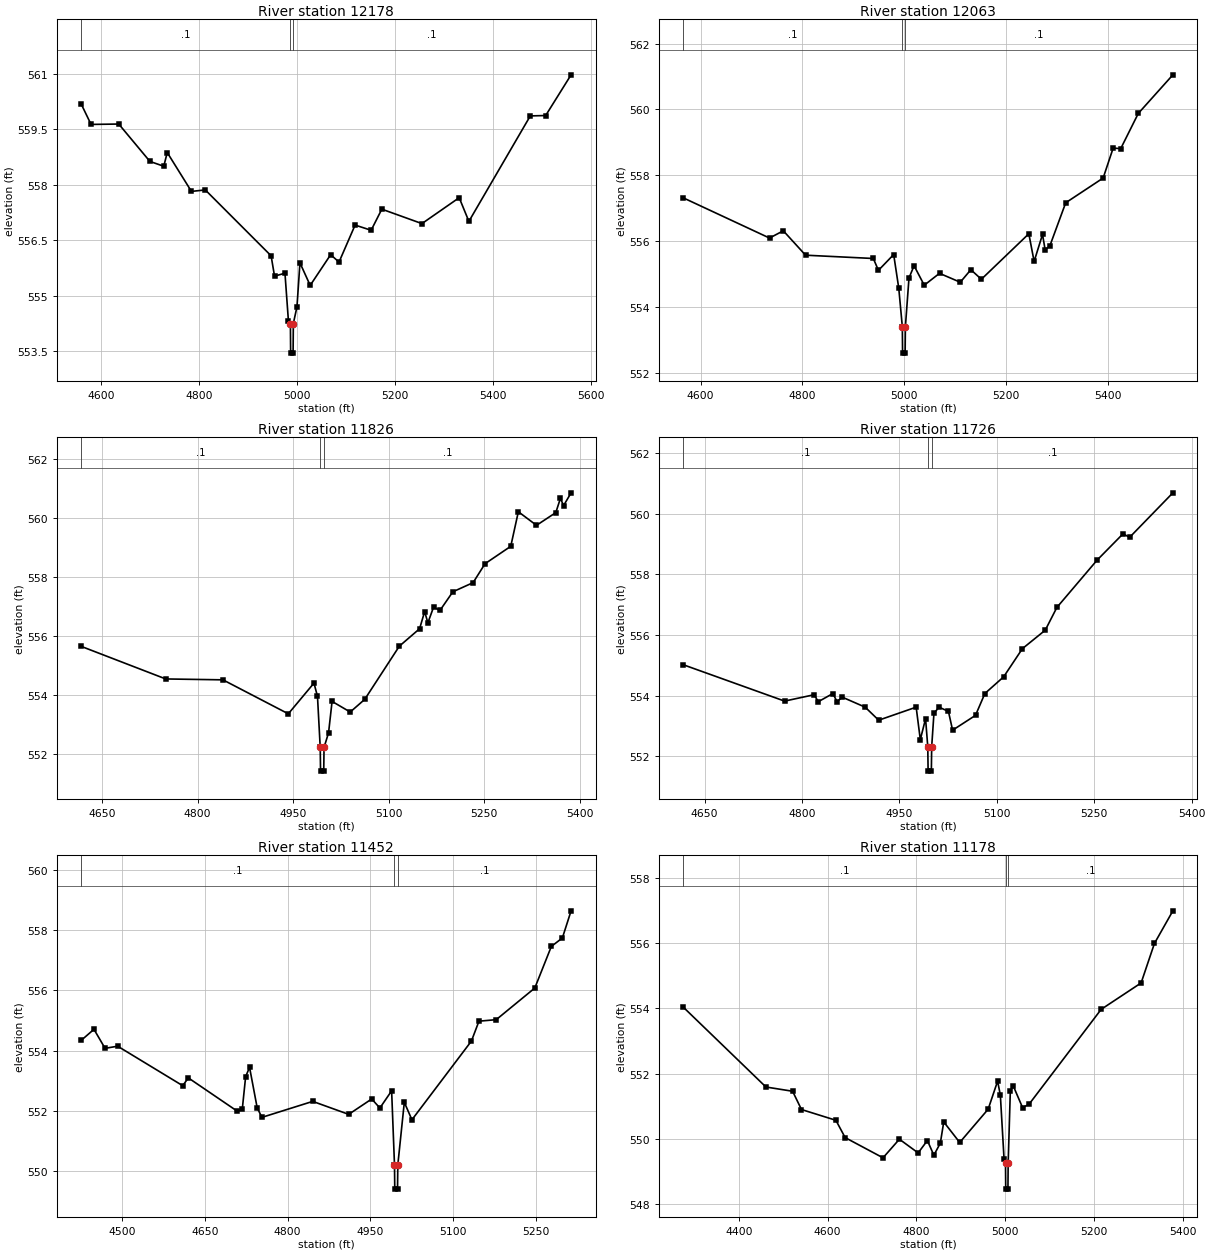
Type RM Length L Ch R = 1,12178,115,115,115
BEGIN DESCRIPTION:
UNT 160 in Lagunillas Cr Wtrshd 19.0
END DESCRIPTION:
XS GIS Cut Line= 3
      2041494.24     13535713.62      2041180.80     13535404.54
      2040645.34     13535567.80
#Sta/Elev= 30
  4559.8  560.17  4579.5  559.63  4636.1  559.64  4699.7  558.63  4728.0  558.50
  4735.1  558.87  4784.5  557.82  4812.8  557.86  4947.2  556.08  4954.2  555.53
  4975.5  555.61  4982.5  554.33  4986.6  554.25  4987.1  553.45  4992.1  553.45
  4992.6  554.25  5000.0  554.70  5006.1  555.89  5027.0  555.28  5068.8  556.11
  5085.9  555.91  5118.7  556.91  5151.5  556.77  5173.3  557.34  5255.2  556.95
  5331.3  557.65  5351.1  557.01  5476.5  559.86  5507.9  559.87  5559.8  560.97
#Mann=3,-1,0
  4559.8     0.1       0  4986.6    0.07       0  4992.6     0.1       0
Bank Sta=4986.6,4992.6
Exp/Cntr=0.3,0.1

Type RM Length L Ch R = 1,12063,237,237,237
BEGIN DESCRIPTION:
Mapping XS 958cad84
END DESCRIPTION:
XS GIS Cut Line= 4
      2041515.09     13535531.34      2041345.14     13535304.24
      2041108.59     13535310.75      2040681.78     13535427.18
#Sta/Elev= 30
  4565.8  557.32  4735.5  556.10  4762.6  556.32  4806.4  555.58  4939.6  555.48
  4949.6  555.12  4979.6  555.60  4989.6  554.58  4996.6  553.41  4997.1  552.61
  5002.1  552.61  5002.6  553.41  5009.7  554.89  5019.7  555.26  5039.7  554.67
  5069.7  555.03  5110.5  554.76  5131.3  555.14  5152.0  554.85  5245.3  556.23
  5255.7  555.39  5272.2  556.21  5277.4  555.74  5286.8  555.87  5317.8  557.17
  5391.4  557.92  5411.1  558.83  5425.9  558.81  5460.5  559.88  5528.5  561.05
#Mann=3,-1,0
  4565.8     0.1       0  4996.6    0.07       0  5002.6     0.1       0
Bank Sta=4996.6,5002.6
Exp/Cntr=0.3,0.1

Type RM Length L Ch R = 1,11826,100,100,100
BEGIN DESCRIPTION:
Mapping XS fc22a8dc
END DESCRIPTION:
XS GIS Cut Line= 4
      2041497.07     13535354.19      2041395.05     13535180.55
      2041091.23     13535039.49      2040861.19     13535072.04
#Sta/Elev= 30
  4617.7  555.64  4750.1  554.54  4839.9  554.51  4942.5  553.36  4982.8  554.40
  4988.3  553.95  4992.6  552.22  4993.1  551.42  4998.1  551.42  4998.6  552.22
  5005.7  552.72  5011.2  553.78  5039.7  553.42  5062.5  553.85  5116.8  555.65
  5148.6  556.24  5156.5  556.82  5161.6  556.44  5170.5  556.97  5180.6  556.86
  5200.8  557.49  5232.6  557.80  5251.3  558.44  5291.7  559.03  5303.6  560.20
  5332.1  559.74  5362.4  560.17  5369.6  560.65  5374.7  560.41  5386.4  560.84
#Mann=3,-1,0
  4617.7     0.1       0  4992.6    0.07       0  4998.6     0.1       0
Bank Sta=4992.6,4998.6
Exp/Cntr=0.3,0.1

Type RM Length L Ch R = 1,11726,274,274,274
BEGIN DESCRIPTION:
Mapping XS ba44a46d
END DESCRIPTION:
XS GIS Cut Line= 4
      2041505.73     13535319.45      2041464.50     13535167.53
      2041134.64     13534907.11      2040958.34     13534904.96
#Sta/Elev= 30
  4617.1  555.02  4773.2  553.82  4818.7  554.03  4825.1  553.80  4847.6  554.07
  4854.0  553.80  4862.0  553.95  4897.3  553.62  4918.1  553.19  4975.8  553.62
  4982.2  552.55  4990.3  553.24  4993.7  552.31  4994.2  551.51  4999.2  551.51
  4999.7  552.31  5003.2  553.42  5011.1  553.62  5025.5  553.48  5031.9  552.86
  5067.2  553.35  5081.6  554.07  5110.5  554.62  5139.4  555.55  5174.6  556.16
  5192.5  556.91  5254.4  558.47  5294.4  559.34  5304.4  559.22  5371.1  560.69
#Mann=3,-1,0
  4617.1     0.1       0  4993.7    0.07       0  4999.7     0.1       0
Bank Sta=4993.7,4999.7
Exp/Cntr=0.3,0.1

Type RM Length L Ch R = 1,11452,274,274,274
BEGIN DESCRIPTION:
Mapping XS bdbe0967
END DESCRIPTION:
XS GIS Cut Line= 4
      2041627.25     13535347.61      2041599.04     13535102.42
      2041321.27     13534711.80      2041159.25     13534716.12
#Sta/Elev= 30
  4426.1  554.35  4448.9  554.71  4469.0  554.08  4491.9  554.15  4609.9  552.84
  4620.0  553.10  4709.2  551.99  4717.9  552.06  4724.0  553.14  4731.1  553.45
  4744.9  552.11  4753.5  551.79  4845.7  552.32  4910.9  551.89  4952.7  552.40
  4967.5  552.10  4988.8  552.67  4994.0  550.21  4994.5  549.41  4999.5  549.41
  5000.0  550.21  5011.8  552.29  5025.6  551.71  5133.5  554.32  5147.2  554.98
  5178.5  555.03  5248.5  556.08  5278.5  557.46  5298.5  557.74  5314.3  558.64
#Mann=3,-1,0
  4426.1     0.1       0  4994.0    0.07       0  5000.0     0.1       0
Bank Sta=4994,5000
Exp/Cntr=0.3,0.1

Type RM Length L Ch R = 1,11178,418,418,418
BEGIN DESCRIPTION:
Mapping XS 3c953f49
END DESCRIPTION:
XS GIS Cut Line= 4
      2041855.12     13535371.47      2041846.44     13535037.32
      2041551.30     13534644.52      2041273.50     13534629.33
#Sta/Elev= 30
  4274.5  554.04  4461.0  551.59  4521.1  551.46  4541.1  550.90  4618.7  550.57
  4639.5  550.04  4724.9  549.42  4761.8  549.99  4804.1  549.57  4824.9  549.95
  4839.5  549.50  4854.1  549.87  4861.8  550.52  4897.8  549.89  4961.9  550.91
  4983.2  551.77  4989.4  551.34  4997.8  549.37  5001.0  549.26  5001.5  548.46
  5006.5  548.46  5007.0  549.26  5011.9  551.48  5018.6  551.62  5039.4  550.96
  5054.0  551.06  5216.6  553.97  5306.7  554.78  5336.7  555.99  5378.3  556.99
#Mann=3,-1,0
  4274.5     0.1       0  5001.0    0.07       0  5007.0     0.1       0
Bank Sta=5001,5007
Exp/Cntr=0.3,0.1

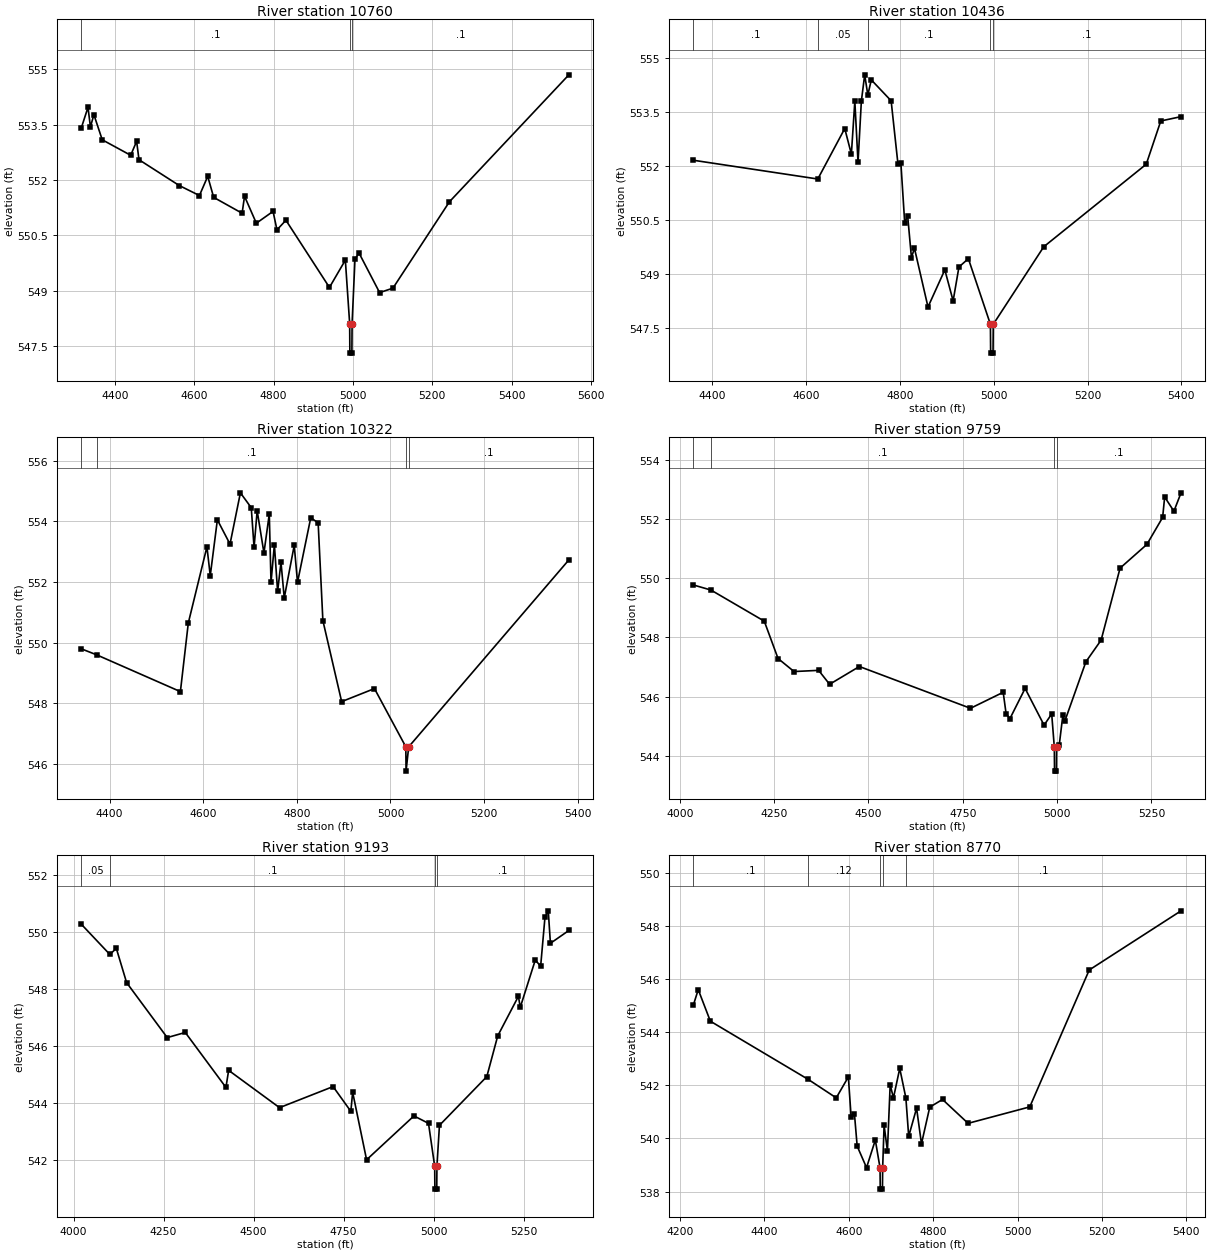
Type RM Length L Ch R = 1,10760,324,324,324
BEGIN DESCRIPTION:
Mapping XS aa977e82
END DESCRIPTION:
XS GIS Cut Line= 4
      2042379.66     13535093.82      2042109.03     13534698.78
      2041655.47     13534577.25      2041375.50     13534601.12
#Sta/Elev= 30
  4315.0  553.41  4331.9  553.97  4338.0  553.44  4346.8  553.77  4367.8  553.09
  4439.6  552.67  4454.5  553.05  4460.5  552.55  4562.1  551.85  4612.9  551.58
  4633.8  552.10  4648.8  551.53  4720.5  551.10  4726.6  551.56  4756.4  550.83
  4798.5  551.15  4808.4  550.65  4831.0  550.91  4940.7  549.09  4980.8  549.83
  4991.7  548.11  4992.2  547.31  4997.3  547.31  4997.8  548.11  5005.1  549.86
  5015.4  550.02  5067.2  548.95  5100.8  549.07  5243.2  551.41  5544.4  554.85
#Mann=3,-1,0
  4315.0     0.1       0  4991.7    0.07       0  4997.8     0.1       0
Bank Sta=4991.7,4997.8
Exp/Cntr=0.3,0.1

Type RM Length L Ch R = 1,10436,114,114,114
BEGIN DESCRIPTION:
Mapping XS 1bcfaf95
END DESCRIPTION:
XS GIS Cut Line= 6
      2042230.86     13534798.77      2042144.05     13534633.84
      2042123.22     13534505.37      2041984.58     13534376.49
      2041763.23     13534392.11      2041463.07     13534474.05
#Sta/Elev= 30
  4359.5  552.16  4624.6  551.64  4682.1  553.04  4696.2  552.33  4703.6  553.80
  4710.4  552.10  4717.5  553.80  4724.6  554.53  4731.3  553.97  4738.7  554.39
  4781.0  553.81  4795.5  552.06  4801.8  552.08  4809.9  550.43  4816.3  550.61
  4824.3  549.46  4830.7  549.72  4859.6  548.09  4895.5  549.12  4913.2  548.26
  4925.6  549.20  4945.7  549.43  4992.7  547.61  4993.2  546.81  4998.3  546.81
  4998.8  547.61  5106.4  549.76  5325.0  552.05  5356.0  553.25  5399.2  553.37
#Mann=5,-1,0
  4359.5     0.1       0  4624.6    0.05       0  4731.3     0.1       0
  4992.7    0.07       0  4998.8     0.1       0
Bank Sta=4992.7,4998.8
Exp/Cntr=0.3,0.1

Type RM Length L Ch R = 1,10322,563,563,563
BEGIN DESCRIPTION:
Mapping XS 043d729c
END DESCRIPTION:
XS GIS Cut Line= 6
      2042444.24     13534187.60      2042222.18     13534107.80
      2042083.29     13534198.08      2042017.31     13534262.31
      2041646.04     13534278.12      2041489.57     13534359.21
#Sta/Elev= 30
  4339.5  549.80  4372.6  549.60  4551.2  548.39  4568.1  550.65  4607.9  553.16
  4615.0  552.21  4630.2  554.05  4657.2  553.25  4679.4  554.94  4702.6  554.45
  4708.6  553.14  4715.2  554.35  4729.7  552.96  4741.1  554.24  4744.8  551.99
  4752.0  553.23  4758.9  551.69  4766.1  552.65  4773.1  551.48  4794.4  553.21
  4801.4  551.99  4829.7  554.12  4845.5  553.95  4855.6  550.73  4895.7  548.06
  4965.8  548.49  5032.8  546.57  5033.3  545.77  5038.9  546.57  5381.1  552.73
#Mann=4,-1,0
  4339.5    0.05       0  4372.6     0.1       0  5032.8    0.07       0
  5038.9     0.1       0
Bank Sta=5032.8,5038.9
Exp/Cntr=0.3,0.1

Type RM Length L Ch R = 1,9759,566,566,566
BEGIN DESCRIPTION:
Mapping XS e7180972
END DESCRIPTION:
XS GIS Cut Line= 4
      2042455.91     13534191.77      2041923.26     13533857.09
      2041389.41     13533922.19      2041343.84     13534039.36
#Sta/Elev= 30
  4036.0  549.77  4082.3  549.60  4223.7  548.55  4260.2  547.29  4302.6  546.85
  4367.8  546.89  4396.9  546.42  4475.8  547.02  4770.4  545.61  4857.1  546.15
  4864.8  545.43  4874.9  545.26  4915.2  546.28  4965.5  545.04  4985.7  545.42
  4992.7  544.29  4993.2  543.49  4998.3  543.49  4998.8  544.29  5005.8  544.38
  5015.2  545.37  5020.3  545.17  5076.4  547.18  5116.7  547.91  5167.0  550.34
  5238.1  551.14  5279.8  552.05  5285.2  552.74  5309.7  552.26  5328.6  552.88
#Mann=4,-1,0
  4036.0    0.05       0  4082.3     0.1       0  4992.7    0.07       0
  4998.8     0.1       0
Bank Sta=4992.7,4998.8
Exp/Cntr=0.3,0.1

Type RM Length L Ch R = 1,9193,423,423,423
BEGIN DESCRIPTION:
Mapping XS 8b8a4e88
END DESCRIPTION:
XS GIS Cut Line= 4
      2042552.31     13534025.13      2042016.58     13533544.59
      2041517.45     13533468.63      2041409.66     13533539.77
#Sta/Elev= 30
  4021.6  550.28  4100.8  549.22  4118.9  549.43  4147.4  548.23  4260.2  546.30
  4310.3  546.48  4423.2  544.55  4430.7  545.15  4572.0  543.84  4720.7  544.58
  4770.0  543.71  4775.0  544.38  4813.7  542.01  4945.2  543.55  4985.6  543.29
  5002.8  541.78  5003.3  540.98  5008.5  540.98  5009.0  541.78  5016.0  543.22
  5147.5  544.93  5177.8  546.36  5235.3  547.75  5240.3  547.36  5282.0  549.02
  5297.0  548.81  5309.0  550.53  5318.1  550.75  5324.1  549.61  5375.3  550.06
#Mann=4,-1,0
  4021.6    0.05       0  4100.8     0.1       0  5002.8    0.07       0
  5009.0     0.1       0
Bank Sta=5002.8,5009
Exp/Cntr=0.3,0.1

Type RM Length L Ch R = 1,8770,555,555,555
BEGIN DESCRIPTION:
Mapping XS 7ddb1113
END DESCRIPTION:
XS GIS Cut Line= 4
      2042353.64     13533573.01      2042044.79     13533197.37
      2041556.51     13533015.07      2041434.99     13533099.71
#Sta/Elev= 30
  4231.9  545.04  4243.2  545.61  4271.9  544.42  4503.4  542.23  4570.3  541.53
  4599.0  542.32  4605.5  540.82  4613.4  540.93  4619.9  539.71  4642.1  538.90
  4662.9  539.94  4674.1  538.89  4674.6  538.09  4679.8  538.09  4680.3  538.89
  4683.7  540.50  4691.6  539.53  4698.1  542.02  4705.9  541.53  4720.8  542.64
  4735.3  541.53  4742.0  540.08  4760.7  541.14  4772.3  539.80  4791.9  541.18
  4822.2  541.47  4882.8  540.57  5029.0  541.19  5169.9  546.35  5387.5  548.58
#Mann=5,-1,0
  4231.9     0.1       0  4503.4    0.12       0  4674.1    0.07       0
  4680.3    0.12       0  4735.3     0.1       0
Bank Sta=4674.1,4680.3
Exp/Cntr=0.3,0.1

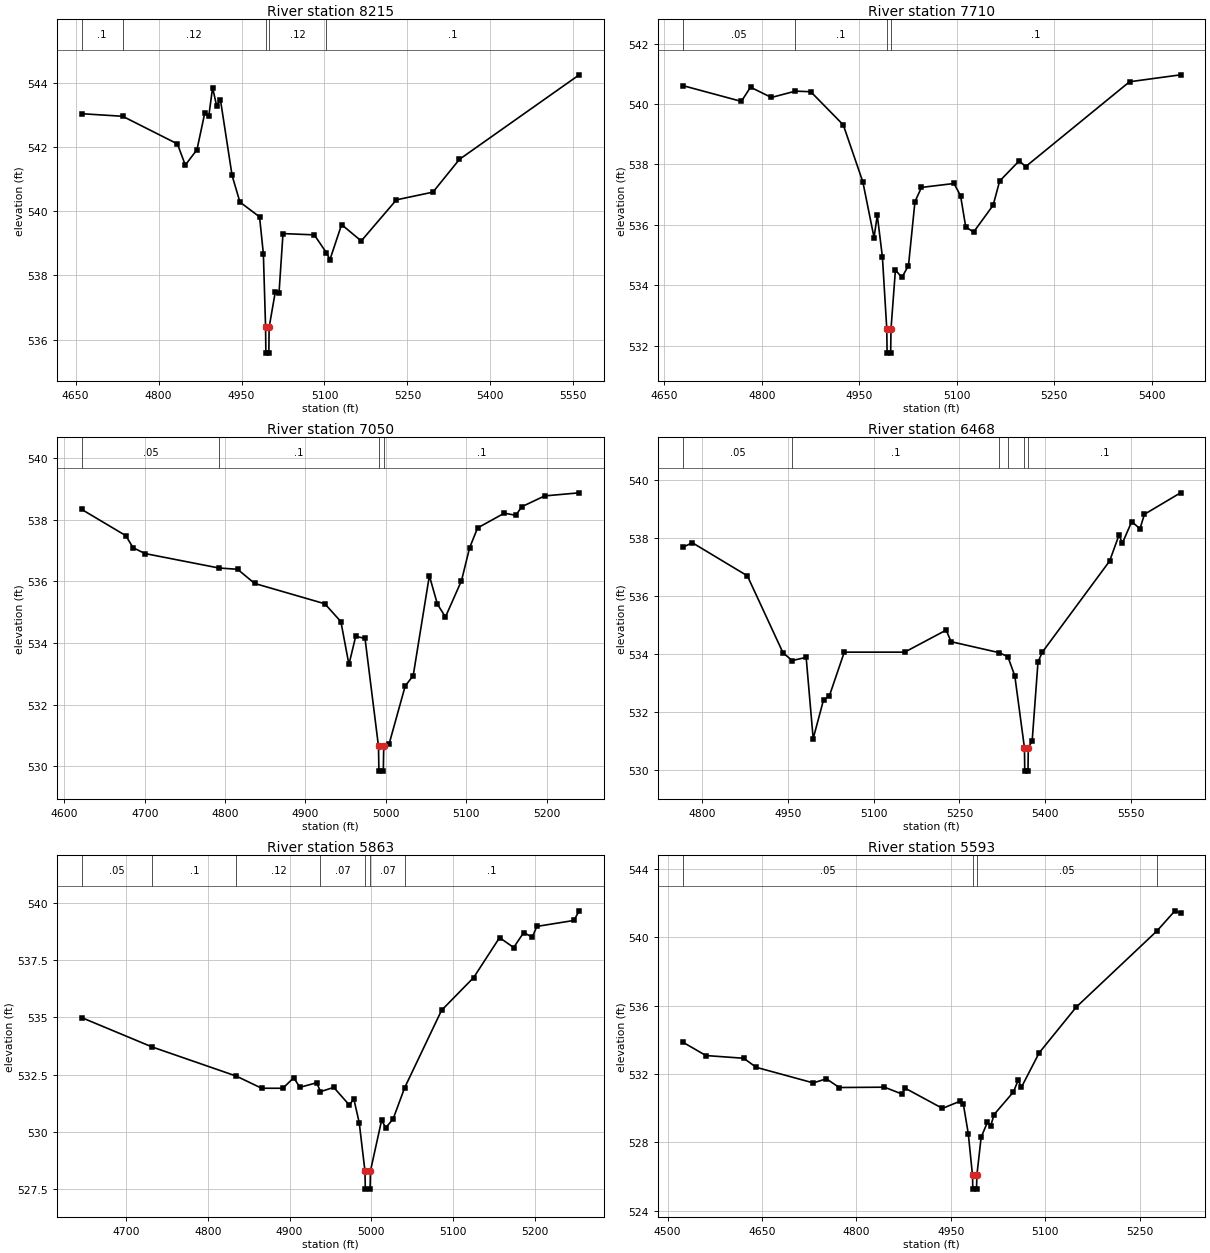
Type RM Length L Ch R = 1,8215,505,505,505
BEGIN DESCRIPTION:
Mapping XS 3e4dedf4
END DESCRIPTION:
XS GIS Cut Line= 4
      2042294.36     13533318.85      2042294.36     13533219.07
      2041925.43     13532834.95      2041659.27     13532811.15
#Sta/Elev= 30
  4661.1  543.03  4735.0  542.95  4834.1  542.09  4848.3  541.43  4869.4  541.91
  4883.5  543.05  4890.7  542.95  4897.7  543.84  4904.9  543.28  4911.8  543.47
  4932.9  541.11  4947.1  540.28  4982.6  539.82  4989.5  538.67  4993.5  536.38
  4994.0  535.58  4999.4  535.58  4999.9  536.38  5010.9  537.47  5017.8  537.45
  5025.0  539.30  5081.6  539.26  5103.3  538.71  5109.9  538.49  5131.0  539.58
  5166.5  539.07  5230.1  540.35  5296.2  540.59  5344.1  541.61  5560.7  544.24
#Mann=5,-1,0
  4661.1     0.1       0  4735.0    0.12       0  4993.5    0.07       0
  4999.9    0.12       0  5103.3     0.1       0
Bank Sta=4993.5,4999.9
Exp/Cntr=0.3,0.1

Type RM Length L Ch R = 1,7710,660,660,660
BEGIN DESCRIPTION:
Mapping XS aede6c52
END DESCRIPTION:
XS GIS Cut Line= 4
      2042524.41     13532722.12      2042424.57     13532628.79
      2041871.18     13532667.85      2041871.18     13532741.91
#Sta/Elev= 30
  4679.1  540.61  4768.7  540.09  4782.8  540.56  4814.9  540.22  4851.9  540.43
  4875.5  540.41  4925.6  539.31  4955.7  537.42  4972.9  535.58  4977.9  536.32
  4985.8  534.93  4992.5  532.55  4993.0  531.75  4998.5  531.75  4999.0  532.55
  5005.8  534.50  5015.8  534.26  5025.9  534.65  5035.9  536.77  5045.9  537.24
  5096.0  537.37  5106.1  536.96  5114.0  535.93  5126.1  535.76  5156.2  536.65
  5166.2  537.45  5196.3  538.12  5206.3  537.93  5366.1  540.74  5444.6  540.97
#Mann=4,-1,0
  4679.1    0.05       0  4851.9     0.1       0  4992.5    0.07       0
  4999.0     0.1       0
Bank Sta=4992.5,4999
Exp/Cntr=0.3,0.1

Type RM Length L Ch R = 1,7050,582,582,582
BEGIN DESCRIPTION:
Mapping XS b1f0b4c2
END DESCRIPTION:
XS GIS Cut Line= 4
      2042381.12     13532416.09      2042134.83     13532258.06
      2041913.30     13532266.39      2041834.83     13532335.83
#Sta/Elev= 30
  4621.6  538.33  4676.4  537.48  4685.4  537.09  4700.2  536.90  4792.4  536.43
  4815.5  536.39  4836.7  535.93  4924.1  535.27  4944.1  534.69  4954.1  533.30
  4962.5  534.21  4974.1  534.15  4990.9  530.64  4991.4  529.84  4996.9  529.84
  4997.4  530.64  5004.1  530.72  5024.1  532.60  5034.1  532.94  5054.2  536.18
  5064.2  535.26  5074.2  534.84  5094.2  536.02  5104.2  537.08  5114.2  537.73
  5147.5  538.21  5161.7  538.14  5169.3  538.42  5197.7  538.77  5240.7  538.87
#Mann=4,-1,0
  4621.6    0.05       0  4792.4     0.1       0  4990.9    0.07       0
  4997.4     0.1       0
Bank Sta=4990.9,4997.4
Exp/Cntr=0.3,0.1

Type RM Length L Ch R = 1,6468,605,605,605
BEGIN DESCRIPTION:
Mapping XS 7e585fa6
END DESCRIPTION:
XS GIS Cut Line= 4
      2042623.20     13532098.34      2042513.82     13532037.14
      2042012.24     13531949.54      2041801.77     13532058.03
#Sta/Elev= 30
  4766.1  537.68  4782.2  537.83  4878.6  536.69  4941.0  534.04  4957.0  533.77
  4981.6  533.88  4993.9  531.08  5012.1  532.42  5022.2  532.55  5048.4  534.06
  5154.2  534.06  5226.9  534.82  5235.4  534.42  5320.2  534.04  5335.0  533.90
  5347.1  533.24  5364.0  530.76  5364.5  529.96  5370.2  529.96  5370.7  530.76
  5377.5  531.00  5387.7  533.72  5395.3  534.06  5513.2  537.20  5529.7  538.10
  5535.4  537.81  5551.9  538.56  5566.3  538.31  5574.1  538.81  5637.4  539.55
#Mann=6,-1,0
  4766.1    0.05       0  4957.0     0.1       0  5320.2    0.07       0
  5335.0     0.1       0  5364.0    0.07       0  5370.7     0.1       0
Bank Sta=5364,5370.7
Exp/Cntr=0.3,0.1

Type RM Length L Ch R = 1,5863,270,270,270
BEGIN DESCRIPTION:
Mapping XS af80d48a
END DESCRIPTION:
XS GIS Cut Line= 4
      2042432.24     13531517.61      2042381.88     13531504.58
      2041939.17     13531628.72      2041897.49     13531716.41
#Sta/Elev= 30
  4645.6  534.99  4731.8  533.71  4834.8  532.44  4865.8  531.91  4891.7  531.91
  4905.1  532.37  4912.5  531.95  4933.2  532.15  4937.8  531.76  4954.0  531.95
  4973.3  531.17  4978.5  531.46  4985.2  530.41  4992.2  528.31  4992.7  527.51
  4998.5  527.51  4999.0  528.31  5012.6  530.51  5017.8  530.19  5026.7  530.57
  5040.8  531.93  5086.0  535.31  5125.3  536.74  5157.0  538.48  5174.3  538.05
  5186.5  538.70  5197.1  538.50  5202.6  538.97  5248.0  539.23  5254.5  539.65
#Mann=7,-1,0
  4645.6    0.05       0  4731.8     0.1       0  4834.8    0.12       0
  4937.8    0.07       0  4992.2    0.07       0  4999.0    0.07       0
  5040.8     0.1       0
Bank Sta=4992.2,4999
Exp/Cntr=0.3,0.1

Type RM Length L Ch R = 1,5593,72,72,72
BEGIN DESCRIPTION:
Mapping XS bbcf6343
END DESCRIPTION:
XS GIS Cut Line= 4
      2042611.13     13531277.24      2042437.56     13531271.81
      2041982.92     13531372.73      2041840.79     13531422.63
#Sta/Elev= 30
  4524.8  533.85  4561.0  533.08  4621.0  532.92  4641.0  532.39  4731.5  531.48
  4752.3  531.72  4772.8  531.21  4844.5  531.23  4872.4  530.83  4877.5  531.17
  4936.7  529.99  4964.6  530.41  4969.8  530.25  4977.7  528.51  4984.4  526.07
  4984.9  525.27  4990.8  525.27  4991.3  526.07  4998.1  528.30  5008.2  529.19
  5013.3  528.96  5018.6  529.63  5049.4  530.95  5056.9  531.64  5062.0  531.22
  5090.3  533.24  5149.1  535.91  5277.5  540.37  5305.9  541.54  5314.8  541.41
#Mann=4,-1,0
  4524.8    0.05       0  4984.4    0.04       0  4991.3    0.05       0
  5277.5     0.1       0
Bank Sta=4984.4,4991.3
Exp/Cntr=0.3,0.1

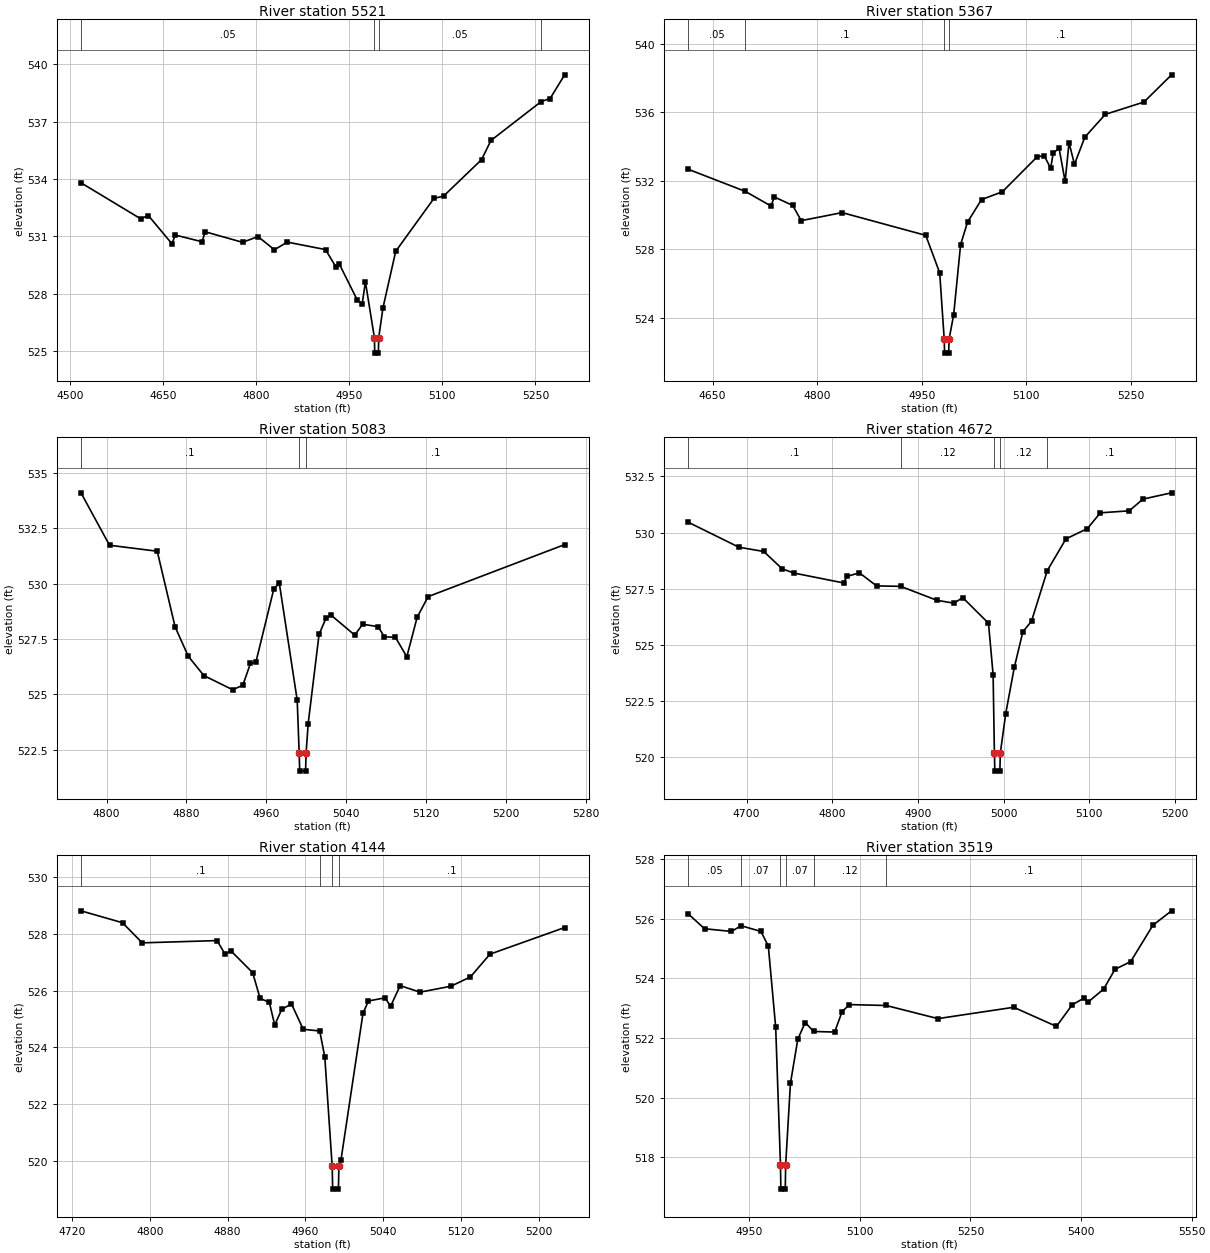
Type RM Length L Ch R = 1,5521,154,154,154
BEGIN DESCRIPTION:
Mapping XS 1f36c081
END DESCRIPTION:
XS GIS Cut Line= 4
      2042618.75     13531156.80      2042387.65     13531208.88
      2041990.52     13531304.37      2041860.26     13531273.97
#Sta/Elev= 30
  4518.0  533.80  4614.1  531.92  4626.5  532.09  4664.6  530.61  4669.7  531.07
  4713.0  530.72  4718.1  531.24  4778.2  530.69  4803.2  530.99  4829.6  530.30
  4850.3  530.70  4911.9  530.31  4929.1  529.38  4934.2  529.55  4963.3  527.66
  4971.0  527.48  4976.2  528.62  4990.7  525.70  4991.2  524.90  4997.1  524.90
  4997.6  525.70  5004.5  527.27  5025.0  530.22  5086.7  532.99  5102.0  533.10
  5163.3  535.01  5178.4  536.01  5259.2  538.04  5273.7  538.20  5297.1  539.44
#Mann=4,-1,0
  4518.0    0.05       0  4990.7    0.04       0  4997.6    0.05       0
  5259.2     0.1       0
Bank Sta=4990.7,4997.6
Exp/Cntr=0.3,0.1

Type RM Length L Ch R = 1,5367,284,284,284
BEGIN DESCRIPTION:
Mapping XS 531c39b1
END DESCRIPTION:
XS GIS Cut Line= 4
      2042559.13     13531165.49      2042395.25     13531116.65
      2042045.85     13531129.67      2041889.22     13531204.21
#Sta/Elev= 30
  4614.4  532.69  4696.8  531.39  4733.5  530.54  4738.7  531.06  4764.8  530.57
  4777.1  529.68  4835.7  530.15  4955.8  528.82  4975.8  526.63  4982.3  522.74
  4982.8  521.94  4988.7  521.94  4989.2  522.74  4995.8  524.17  5005.8  528.28
  5015.8  529.60  5035.8  530.91  5065.8  531.37  5115.9  533.42  5125.9  533.47
  5135.0  532.74  5138.7  533.63  5147.1  533.91  5155.8  531.97  5161.4  534.24
  5169.2  532.97  5184.1  534.56  5213.5  535.89  5268.9  536.61  5308.5  538.20
#Mann=4,-1,0
  4614.4    0.05       0  4696.8     0.1       0  4982.3    0.07       0
  4989.2     0.1       0
Bank Sta=4982.3,4989.2
Exp/Cntr=0.3,0.1

Type RM Length L Ch R = 1,5083,411,411,411
BEGIN DESCRIPTION:
Mapping XS b21912ff
END DESCRIPTION:
XS GIS Cut Line= 4
      2042505.92     13531063.49      2042500.50     13531005.97
      2042233.57     13530888.78      2042098.38     13530886.64
#Sta/Elev= 30
  4774.4  534.11  4803.0  531.74  4850.8  531.47  4868.7  528.05  4881.9  526.72
  4897.5  525.85  4926.3  525.21  4936.5  525.41  4944.2  526.40  4949.7  526.47
  4967.6  529.77  4973.1  530.02  4991.0  524.74  4993.0  522.33  4993.5  521.53
  4999.4  521.53  4999.9  522.33  5002.0  523.68  5012.9  527.71  5019.8  528.44
  5025.2  528.57  5048.6  527.68  5056.6  528.17  5072.0  528.06  5078.4  527.60
  5089.4  527.58  5100.8  526.70  5111.2  528.49  5122.2  529.42  5258.9  531.77
#Mann=3,-1,0
  4774.4     0.1       0  4993.0    0.07       0  4999.9     0.1       0
Bank Sta=4993,4999.9
Exp/Cntr=0.3,0.1

Type RM Length L Ch R = 1,4672,528,528,528
BEGIN DESCRIPTION:
Mapping XS 5f71c885
END DESCRIPTION:
XS GIS Cut Line= 4
      2042552.59     13530752.08      2042438.65     13530604.50
      2042130.49     13530632.71      2042070.81     13530666.34
#Sta/Elev= 30
  4631.5  530.47  4691.1  529.35  4720.1  529.16  4741.5  528.39  4755.4  528.20
  4813.4  527.76  4816.8  528.05  4831.7  528.21  4851.7  527.63  4879.8  527.61
  4922.0  526.99  4942.1  526.86  4952.2  527.11  4982.3  525.97  4987.7  523.68
  4989.2  520.19  4989.7  519.39  4995.6  519.39  4996.1  520.19  5002.4  521.95
  5012.4  524.00  5022.4  525.59  5032.5  526.06  5050.9  528.31  5072.7  529.72
  5097.7  530.18  5112.8  530.88  5146.6  530.97  5162.5  531.49  5195.9  531.77
#Mann=5,-1,0
  4631.5     0.1       0  4879.8    0.12       0  4989.2    0.07       0
  4996.1    0.12       0  5050.9     0.1       0
Bank Sta=4989.2,4996.1
Exp/Cntr=0.3,0.1

Type RM Length L Ch R = 1,4144,625,625,625
BEGIN DESCRIPTION:
Mapping XS fa73e2af
END DESCRIPTION:
XS GIS Cut Line= 4
      2042640.11     13530457.02      2042620.14     13530346.76
      2042403.13     13530243.46      2042258.24     13530241.74
#Sta/Elev= 30
  4729.2  528.82  4771.9  528.40  4792.2  527.69  4869.1  527.77  4877.4  527.29
  4883.0  527.42  4905.7  526.64  4913.4  525.73  4922.9  525.59  4928.4  524.79
  4935.6  525.34  4945.6  525.54  4957.7  524.64  4974.7  524.58  4979.9  523.66
  4987.5  519.80  4988.0  519.00  4993.9  519.00  4994.4  519.80  4996.5  520.02
  5019.2  525.21  5024.8  525.64  5041.9  525.75  5047.5  525.45  5057.4  526.18
  5077.8  525.95  5109.7  526.16  5129.7  526.49  5149.7  527.29  5226.5  528.23
#Mann=4,-1,0
  4729.2     0.1       0  4974.7    0.12       0  4987.5    0.07       0
  4994.4     0.1       0
Bank Sta=4987.5,4994.4
Exp/Cntr=0.3,0.1

Type RM Length L Ch R = 1,3519,497,497,497
BEGIN DESCRIPTION:
Mapping XS 5d25cf35
END DESCRIPTION:
XS GIS Cut Line= 4
      2042664.86     13529735.51      2042622.31     13529705.99
      2042259.64     13529703.44      2042053.49     13529829.30
#Sta/Elev= 30
  4866.7  526.17  4889.3  525.66  4925.8  525.57  4939.0  525.76  4965.8  525.57
  4975.8  525.08  4985.8  522.36  4992.3  517.74  4992.8  516.94  4998.8  516.94
  4999.3  517.74  5005.8  520.48  5015.8  521.96  5025.8  522.52  5037.3  522.22
  5065.8  522.20  5075.8  522.88  5085.8  523.12  5135.6  523.09  5205.8  522.65
  5308.6  523.03  5366.6  522.39  5387.9  523.11  5403.4  523.33  5409.3  523.20
  5430.6  523.64  5446.0  524.30  5467.3  524.56  5497.5  525.78  5522.7  526.26
#Mann=6,-1,0
  4866.7    0.05       0  4939.0    0.07       0  4992.3    0.07       0
  4999.3    0.07       0  5037.3    0.12       0  5135.6     0.1       0
Bank Sta=4992.3,4999.3
Exp/Cntr=0.3,0.1

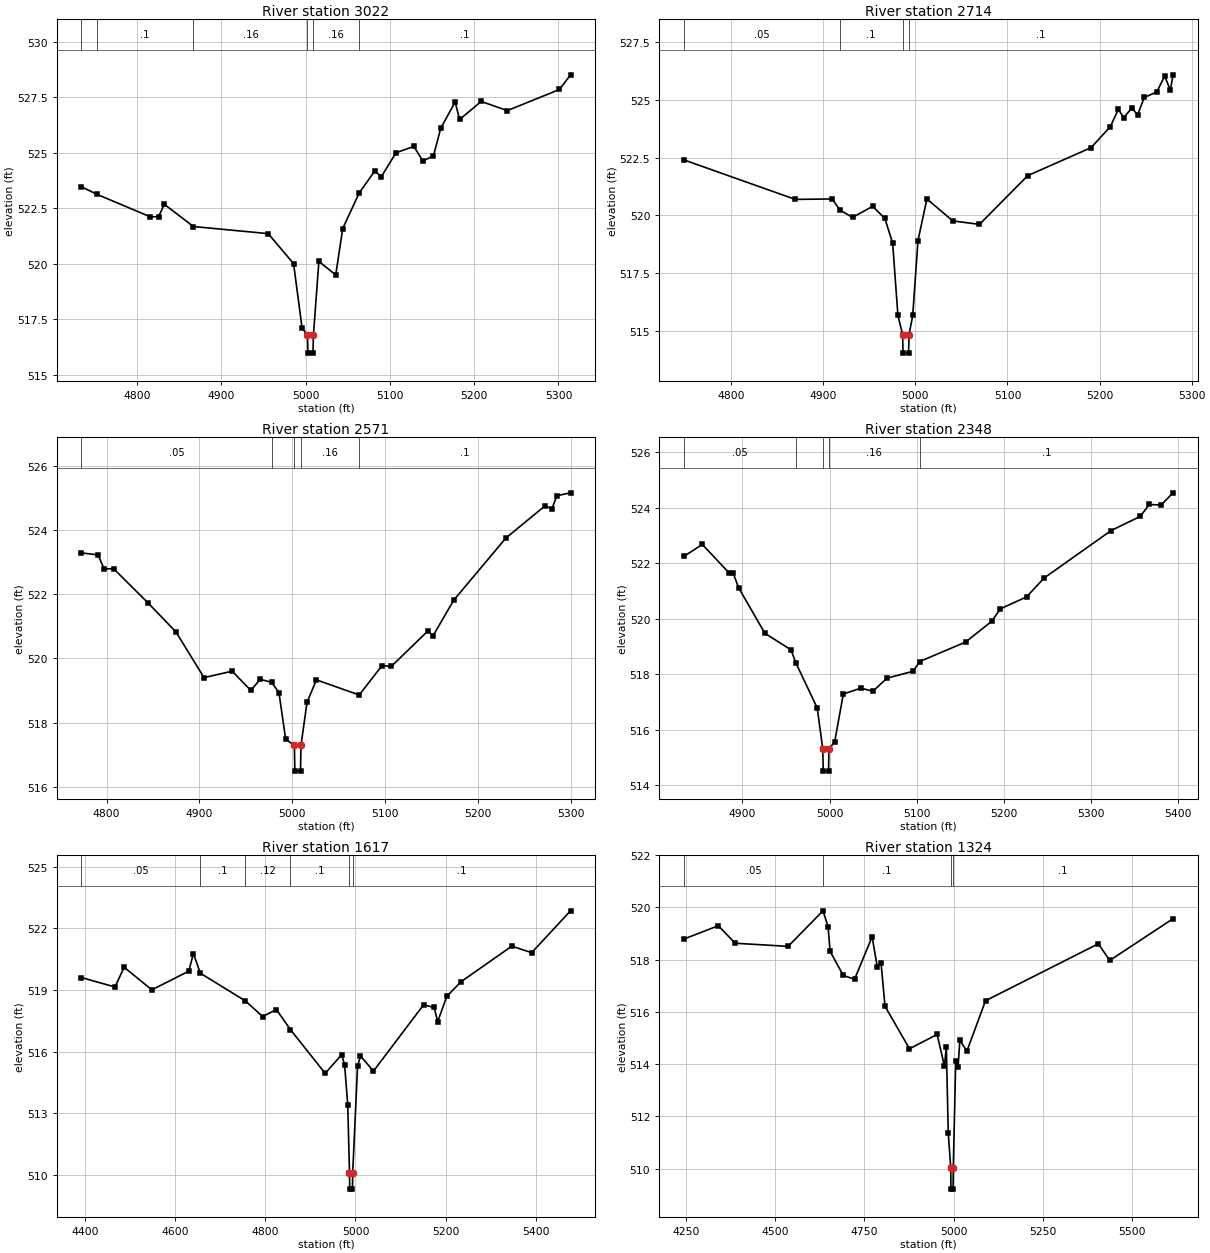
Type RM Length L Ch R = 1,3022,308,308,308
BEGIN DESCRIPTION:
Mapping XS 5460e11a
END DESCRIPTION:
XS GIS Cut Line= 4
      2042623.20     13529434.31      2042574.57     13529381.33
      2042297.66     13529368.31      2042079.73     13529445.12
#Sta/Elev= 30
  4734.1  523.47  4752.6  523.13  4815.6  522.12  4825.6  522.12  4832.5  522.68
  4867.0  521.68  4955.7  521.36  4985.8  520.01  4995.8  517.13  5002.3  516.78
  5002.8  515.98  5008.8  515.98  5009.3  516.78  5015.8  520.11  5035.8  519.50
  5044.1  521.59  5063.6  523.19  5082.1  524.18  5089.8  523.92  5107.3  525.00
  5128.5  525.29  5139.1  524.63  5151.7  524.86  5160.3  526.10  5177.4  527.29
  5182.7  526.50  5208.3  527.31  5239.3  526.90  5301.2  527.85  5314.3  528.51
#Mann=6,-1,0
  4734.1    0.05       0  4752.6     0.1       0  4867.0    0.16       0
  5002.3    0.07       0  5009.3    0.16       0  5063.6     0.1       0
Bank Sta=5002.3,5009.3
Exp/Cntr=0.3,0.1

Type RM Length L Ch R = 1,2714,143,143,143
BEGIN DESCRIPTION:
Mapping XS 2180df80
END DESCRIPTION:
XS GIS Cut Line= 4
      2042709.99     13529323.18      2042657.91     13529211.19
      2042423.53     13529081.85      2042309.49     13529163.06
#Sta/Elev= 30
  4748.6  522.40  4869.6  520.69  4909.7  520.71  4917.8  520.24  4931.7  519.91
  4953.5  520.39  4966.8  519.87  4975.3  518.80  4981.0  515.68  4986.1  514.84
  4986.6  514.04  4992.6  514.04  4993.1  514.84  4997.1  515.67  5002.8  518.91
  5012.5  520.71  5040.6  519.76  5069.6  519.61  5122.0  521.72  5190.8  522.93
  5211.7  523.84  5220.3  524.58  5226.4  524.23  5235.1  524.65  5241.2  524.34
  5248.5  525.10  5262.1  525.34  5270.7  526.02  5276.9  525.42  5279.8  526.08
#Mann=4,-1,0
  4748.6    0.05       0  4917.8     0.1       0  4986.1    0.07       0
  4993.1     0.1       0
Bank Sta=4986.1,4993.1
Exp/Cntr=0.3,0.1

Type RM Length L Ch R = 1,2571,223,223,223
BEGIN DESCRIPTION:
Mapping XS 03ed8680
END DESCRIPTION:
XS GIS Cut Line= 4
      2042819.36     13529074.91      2042791.59     13529054.08
      2042426.74     13529006.83      2042308.71     13529045.45
#Sta/Elev= 30
  4772.9  523.28  4790.9  523.22  4797.4  522.78  4807.6  522.79  4844.5  521.73
  4874.8  520.82  4905.0  519.40  4935.3  519.60  4955.4  519.00  4965.5  519.35
  4977.9  519.25  4985.7  518.93  4992.9  517.48  5002.3  517.29  5002.8  516.49
  5008.9  516.49  5009.4  517.29  5015.9  518.63  5026.0  519.33  5072.1  518.86
  5096.6  519.77  5106.7  519.75  5146.4  520.86  5151.4  520.69  5173.9  521.81
  5230.0  523.74  5272.0  524.74  5279.7  524.66  5285.0  525.06  5299.7  525.15
#Mann=5,-1,0
  4772.9    0.05       0  4977.9    0.16       0  5002.3    0.07       0
  5009.4    0.16       0  5072.1     0.1       0
Bank Sta=5002.3,5009.4
Exp/Cntr=0.3,0.1

Type RM Length L Ch R = 1,2348,731,731,731
BEGIN DESCRIPTION:
Mapping XS 96a77a68
END DESCRIPTION:
XS GIS Cut Line= 4
      2042755.11     13528838.79      2042701.31     13528821.44
      2042266.41     13528844.88      2042245.00     13528910.83
#Sta/Elev= 30
  4832.8  522.24  4853.9  522.67  4884.8  521.64  4889.3  521.64  4895.6  521.11
  4925.7  519.47  4955.7  518.87  4961.6  518.38  4985.8  516.78  4992.2  515.30
  4992.7  514.50  4998.8  514.50  4999.3  515.30  5005.8  515.55  5015.8  517.28
  5035.9  517.49  5049.7  517.38  5065.9  517.85  5095.9  518.10  5103.4  518.45
  5156.0  519.15  5186.1  519.90  5196.1  520.35  5226.1  520.78  5246.2  521.46
  5323.1  523.17  5356.5  523.68  5367.0  524.11  5380.4  524.09  5394.2  524.53
#Mann=5,-1,0
  4832.8    0.05       0  4961.6    0.16       0  4992.2    0.07       0
  4999.3    0.16       0  5103.4     0.1       0
Bank Sta=4992.2,4999.3
Exp/Cntr=0.3,0.1

Type RM Length L Ch R = 1,1617,293,293,293
BEGIN DESCRIPTION:
Mapping XS fd34042c
END DESCRIPTION:
XS GIS Cut Line= 4
      2042707.74     13528318.02      2042249.05     13528218.14
      2042058.08     13528373.52      2041954.28     13528727.79
#Sta/Elev= 30
  4392.2  519.61  4466.6  519.15  4487.1  520.11  4548.5  519.01  4630.4  519.92
  4640.6  520.78  4656.0  519.82  4756.0  518.47  4794.1  517.71  4824.8  518.05
  4855.9  517.07  4932.9  514.94  4969.5  515.85  4976.0  515.34  4982.9  513.42
  4986.8  510.10  4987.3  509.30  4993.4  509.30  4993.9  510.10  5004.7  515.29
  5011.2  515.79  5039.9  515.05  5151.1  518.28  5174.6  518.15  5182.3  517.46
  5202.8  518.70  5234.4  519.41  5346.9  521.14  5390.7  520.82  5477.0  522.86
#Mann=6,-1,0
  4392.2    0.05       0  4656.0     0.1       0  4756.0    0.12       0
  4855.9     0.1       0  4986.8    0.07       0  4993.9     0.1       0
Bank Sta=4986.8,4993.9
Exp/Cntr=0.3,0.1

Type RM Length L Ch R = 1,1324,239,239,239
BEGIN DESCRIPTION:
Mapping XS c5824e8f
END DESCRIPTION:
XS GIS Cut Line= 4
      2042745.96     13528238.17      2042201.31     13528043.66
      2041927.00     13528127.86      2041707.77     13528585.37
#Sta/Elev= 30
  4243.3  518.79  4339.9  519.30  4387.1  518.63  4535.8  518.51  4633.6  519.87
  4647.8  519.27  4653.6  518.32  4690.3  517.40  4722.2  517.25  4771.5  518.88
  4785.9  517.72  4796.5  517.88  4807.6  516.22  4876.3  514.59  4953.8  515.14
  4974.5  513.93  4979.7  514.67  4985.1  511.38  4992.1  510.02  4992.6  509.22
  4998.7  509.22  4999.2  510.02  5006.1  514.14  5012.5  513.88  5017.7  514.92
  5037.4  514.50  5089.7  516.43  5406.4  518.61  5438.1  517.97  5615.9  519.57
#Mann=4,-1,0
  4243.3    0.05       0  4633.6     0.1       0  4992.1    0.07       0
  4999.2     0.1       0
Bank Sta=4992.1,4999.2
Exp/Cntr=0.3,0.1