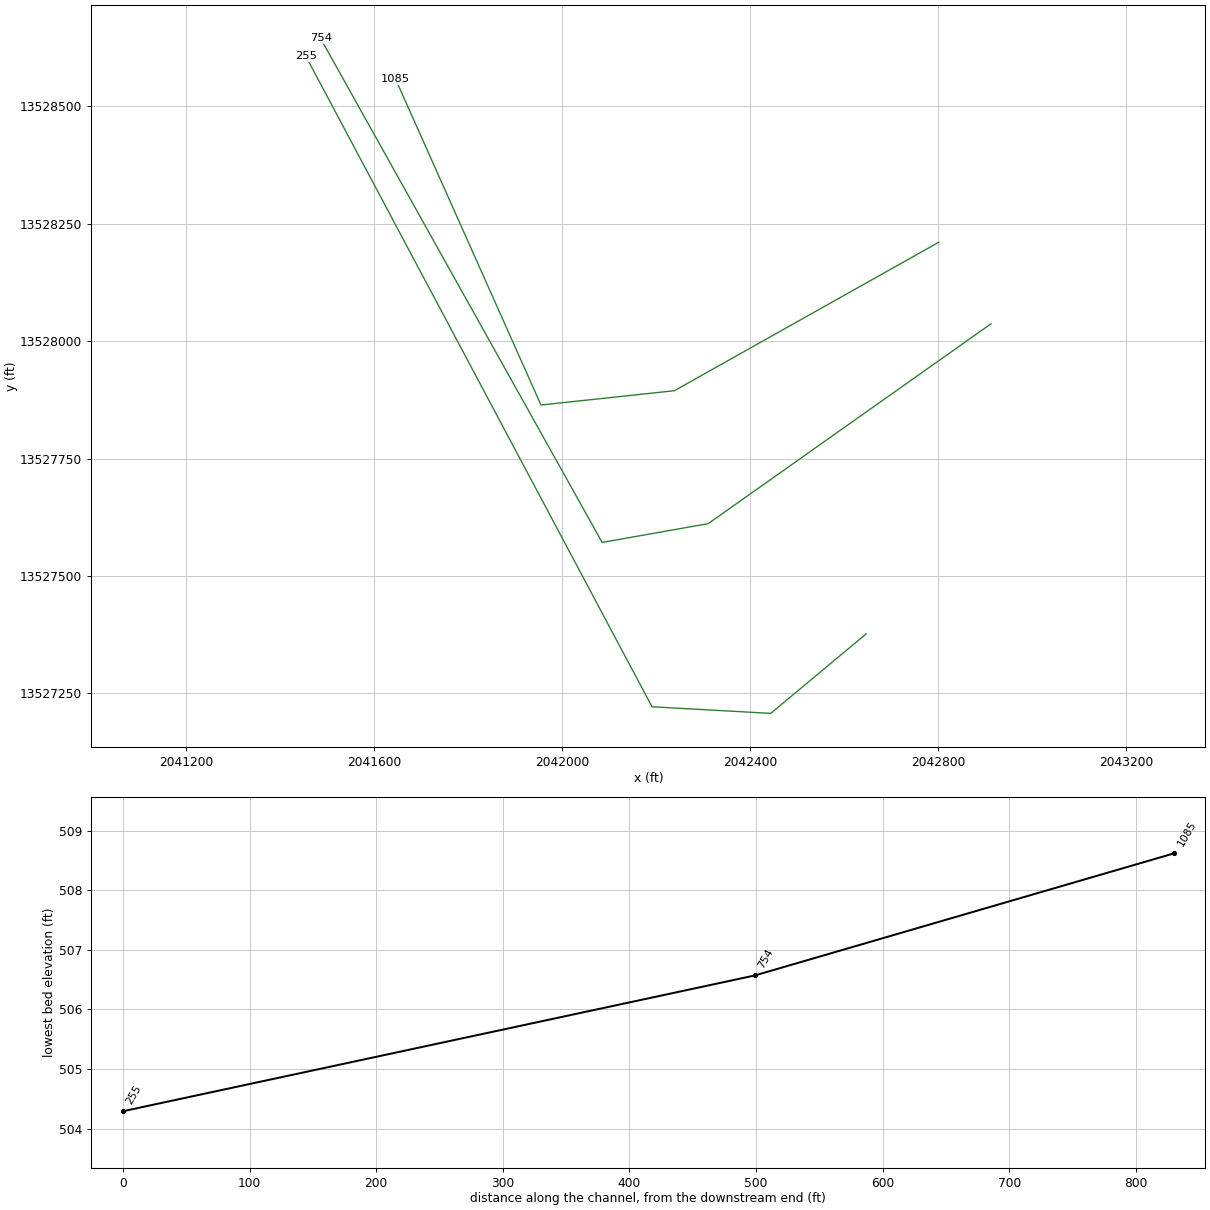
HEC-RAS study UNT 160 in Lagunillas Cr Wtrshd.prj: UNT 160 in Lagunillas Cr Wtrshd Base Level Engineering

--- UNT 160 in Lagunillas Cr Wtrshd.g01 (geometry) --- (continued)

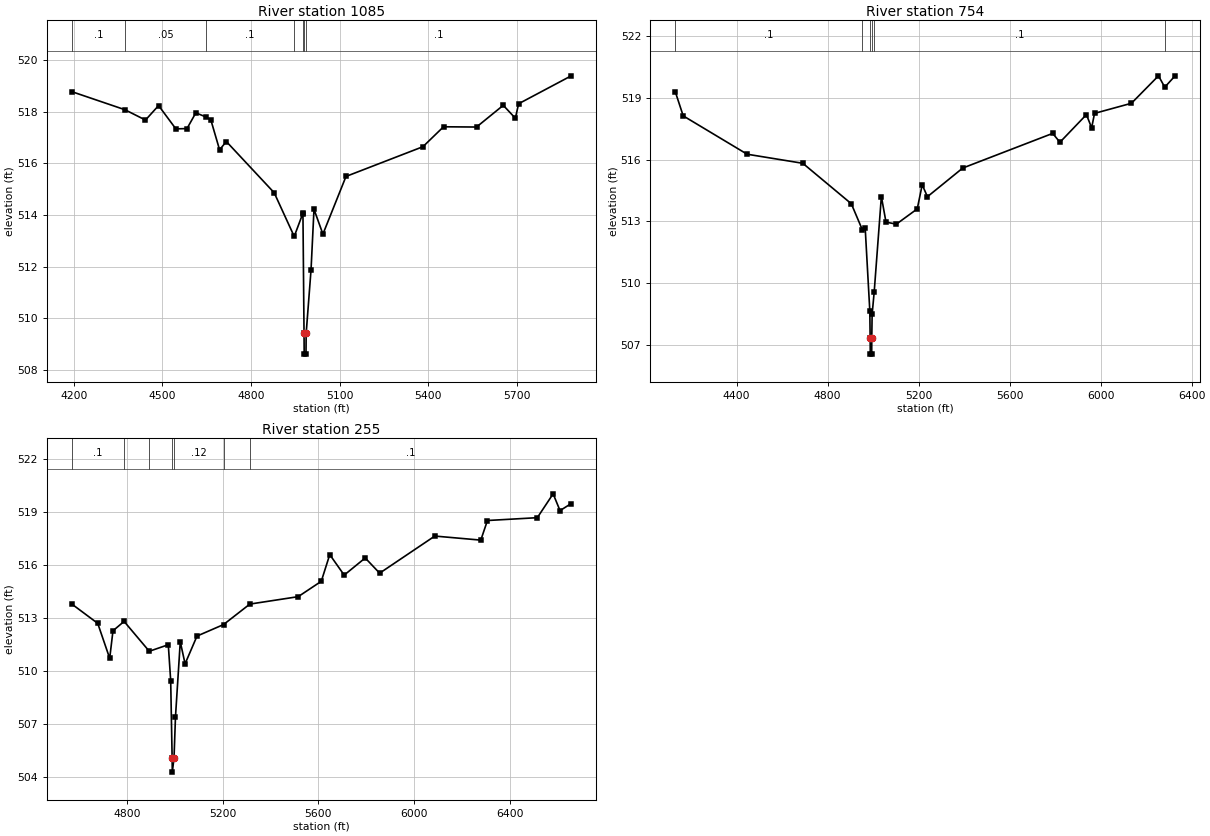
Type RM Length L Ch R = 1,1085,331,331,331
BEGIN DESCRIPTION:
Mapping XS 34bc9766
END DESCRIPTION:
XS GIS Cut Line= 4
      2042801.49     13528210.38      2042238.63     13527894.35
      2041954.78     13527863.97      2041645.28     13528557.57
#Sta/Elev= 30
  4193.1  518.77  4373.3  518.07  4443.0  517.67  4487.3  518.23  4545.7  517.33
  4583.4  517.34  4613.4  517.95  4647.4  517.79  4664.3  517.67  4693.7  516.52
  4716.6  516.84  4878.5  514.86  4946.3  513.17  4974.8  514.04  4975.8  514.08
  4979.5  509.42  4980.0  508.62  4986.1  508.62  4986.7  509.42  5003.2  511.88
  5013.2  514.22  5043.4  513.26  5121.5  515.49  5381.9  516.64  5451.5  517.41
  5563.2  517.40  5653.7  518.24  5694.6  517.74  5705.6  518.30  5883.6  519.38
#Mann=7,-1,0
  4193.1     0.1       0  4373.3    0.05       0  4647.4     0.1       0
  4946.3    0.12       0  4974.8     0.1       0  4979.5    0.07       0
  4986.7     0.1       0
Bank Sta=4979.5,4986.7
Exp/Cntr=0.3,0.1

Type RM Length L Ch R = 1,754,499,499,499
BEGIN DESCRIPTION:
Mapping XS aec2a4f7
END DESCRIPTION:
XS GIS Cut Line= 4
      2042912.63     13528036.78      2042310.68     13527611.37
      2042084.99     13527571.44      2041485.53     13528644.44
#Sta/Elev= 30
  4131.0  519.28  4165.5  518.12  4446.5  516.26  4691.2  515.82  4904.3  513.86
  4952.3  512.61  4965.3  512.69  4985.6  508.67  4987.1  507.37  4987.7  506.57
  4993.8  506.57  4994.3  507.37  4995.8  508.50  5005.0  509.60  5036.4  514.21
  5056.7  512.97  5102.2  512.87  5194.1  513.61  5215.9  514.78  5238.8  514.20
  5394.0  515.59  5789.3  517.27  5821.2  516.84  5937.6  518.18  5960.5  517.54
  5973.2  518.24  6135.4  518.73  6254.2  520.06  6281.9  519.51  6326.4  520.05
#Mann=6,-1,0
  4131.0     0.1       0  4952.3    0.12       0  4987.1    0.07       0
  4994.3    0.12       0  5005.0     0.1       0  6281.9    0.05       0
Bank Sta=4987.1,4994.3
Exp/Cntr=0.3,0.1

Type RM Length L Ch R = 1,255,0,0,0
BEGIN DESCRIPTION:
UNT 160 in Lagunillas Cr Wtrshd 1.0
END DESCRIPTION:
XS GIS Cut Line= 4
      2042647.04     13527376.85      2042443.89     13527207.55
      2042191.11     13527221.61      2041454.28     13528606.25
#Sta/Elev= 30
  4570.0  513.81  4678.9  512.71  4728.9  510.73  4742.6  512.29  4789.0  512.82
  4894.2  511.13  4973.6  511.50  4983.6  509.47  4989.6  505.09  4990.3  504.29
  4997.5  505.09  5003.6  507.42  5023.6  511.67  5043.7  510.42  5093.5  511.99
  5204.2  512.64  5314.1  513.80  5516.0  514.22  5612.5  515.09  5647.8  516.60
  5708.1  515.44  5795.9  516.41  5856.2  515.55  6086.5  517.65  6278.6  517.42
  6306.3  518.53  6514.6  518.69  6580.6  520.04  6609.4  519.09  6656.1  519.49
#Mann=7,-1,0
  4570.0     0.1       0  4789.0    0.07       0  4894.2    0.12       0
  4989.6    0.07       0  4997.5    0.12       0  5204.2    0.07       0
  5314.1     0.1       0
Bank Sta=4989.6,4997.5
Exp/Cntr=0.3,0.1

Chan Stop Cuts=-1