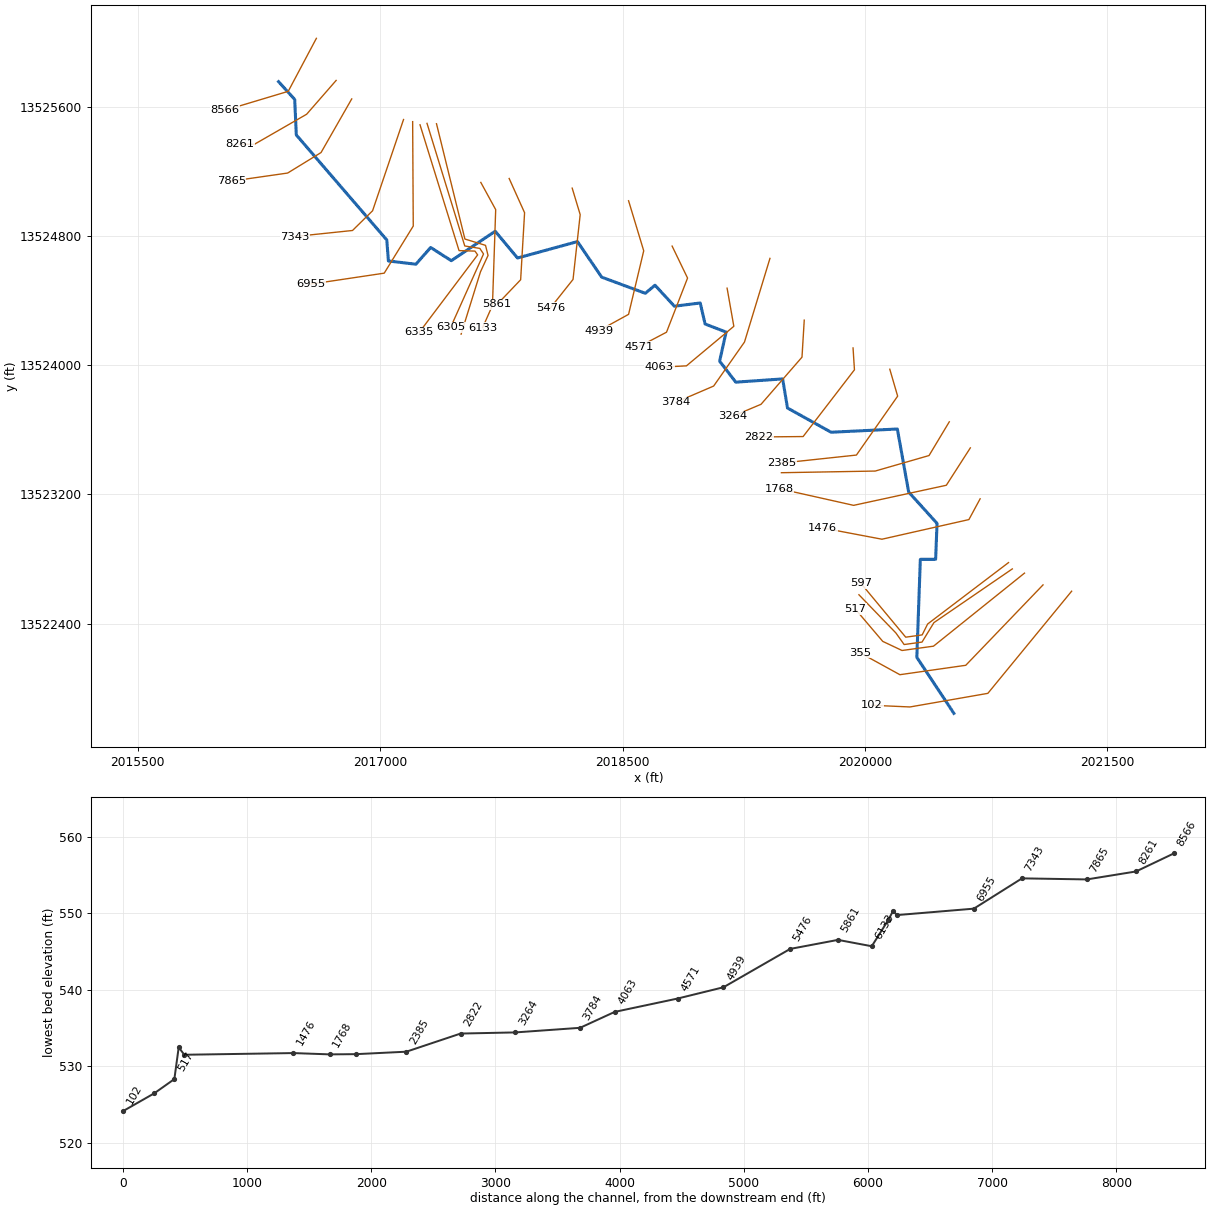
--- UNT 165 in Lagunillas Cr Wtrshd.prj (project) ---

Proj Title=UNT 165 in Lagunillas Cr Wtrshd Base Level Engineering
Current Plan=p01
Default Exp/Contr=0.3,0.1
English Units
Geom File=g01
Flow File=f01
Plan File=p01
BEGIN DESCRIPTION:
UNT 165 in Lagunillas Cr Wtrshd
END DESCRIPTION:

--- UNT 165 in Lagunillas Cr Wtrshd.p01 (plan) ---

Plan Title=Multiple Run
Short Identifier=Multiple
Geom File=g01
Flow File=f01
Subcritical Flow
K Sum by GR= 0
Std Step Tol= 0.01
Critical Tol= 0.01
Num of Std Step Trials= 20
Max Error Tol= 0.3
Flow Tol Ratio= 0.001
Split Flow NTrial= 30
Split Flow Tol= 0.02
Split Flow Ratio= 0.02
Log Output Level= 0
Friction Slope Method= 1
Unsteady Friction Slope Method= 2
Unsteady Bridges Friction Slope Method= 1
Parabolic Critical Depth
Global Vel Dist=  1 , 1 , 1
Global Log Level= 0
CheckData=True
Encroach Param= -1, 0, 0, 0
BEGIN DESCRIPTION:
Multiple Run
END DESCRIPTION:

--- UNT 165 in Lagunillas Cr Wtrshd.f01 (steady flow) ---

Flow Title=Multiple
Number of Profiles=7
Profile Names=10-year,25-year,50-year,1pct_min,100-year,1pct_plu,500-year
River Rch & RM= UNT 165 in Lagun,Reach-1,8566
     141     189     227     136     272     543     396
River Rch & RM= UNT 165 in Lagun,Reach-1,4063
     259     357     439     268     535    1068     810
Boundary for River Rch & Prof#=UNT 165 in Lagun,Reach-1,1
Up Type=0
Dn Type=3
Dn Slope=0.005
Boundary for River Rch & Prof#=UNT 165 in Lagun,Reach-1,2
Up Type=0
Dn Type=3
Dn Slope=0.005
Boundary for River Rch & Prof#=UNT 165 in Lagun,Reach-1,3
Up Type=0
Dn Type=3
Dn Slope=0.005
Boundary for River Rch & Prof#=UNT 165 in Lagun,Reach-1,4
Up Type=0
Dn Type=3
Dn Slope=0.005
Boundary for River Rch & Prof#=UNT 165 in Lagun,Reach-1,5
Up Type=0
Dn Type=3
Dn Slope=0.005
Boundary for River Rch & Prof#=UNT 165 in Lagun,Reach-1,6
Up Type=0
Dn Type=3
Dn Slope=0.005
Boundary for River Rch & Prof#=UNT 165 in Lagun,Reach-1,7
Up Type=0
Dn Type=3
Dn Slope=0.005

--- UNT 165 in Lagunillas Cr Wtrshd.g01 (geometry) ---

Geom Title=Existing Conditions

River Reach=UNT 165 in Lagun,Reach-1
Reach XY= 30
      2016370.80     13525754.54      2016470.80     13525644.54
      2016480.80     13525424.54      2017040.80     13524774.54
      2017050.80     13524644.54      2017220.80     13524624.54
      2017312.44     13524728.03      2017440.05     13524646.43
      2017711.75     13524828.73      2017849.77     13524662.93
      2018220.80     13524764.54      2018370.80     13524544.54
      2018640.80     13524444.54      2018700.80     13524494.54
      2018820.80     13524364.54      2018980.80     13524384.54
      2019010.80     13524254.54      2019140.80     13524204.54
      2019100.80     13524024.54      2019200.80     13523894.54
      2019490.80     13523914.54      2019520.80     13523734.54
      2019790.80     13523584.54      2020200.80     13523604.54
      2020270.80     13523214.54      2020446.42     13523020.33
      2020437.73     13522798.11      2020343.12     13522798.11
      2020321.41     13522191.34      2020550.80     13521844.54

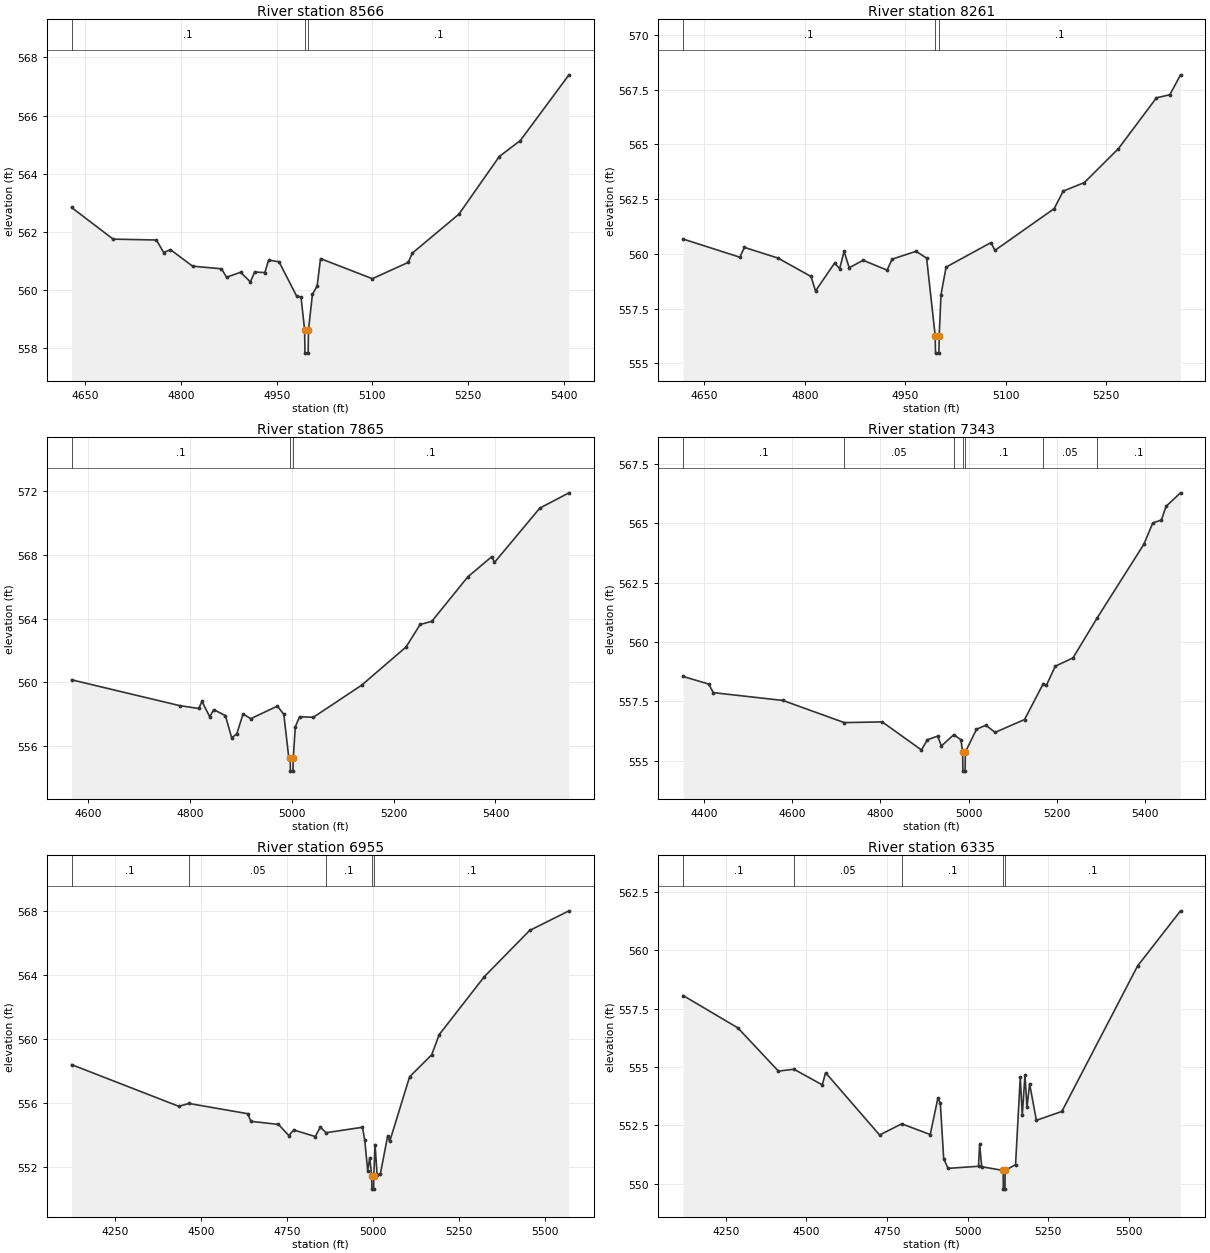
Type RM Length L Ch R = 1,8566,305,305,305
BEGIN DESCRIPTION:
UNT 165 in Lagunillas Cr Wtrshd 10.0
END DESCRIPTION:
XS GIS Cut Line= 3
      2016604.99     13526022.55      2016430.80     13525694.54
      2016039.92     13525577.24
#Sta/Elev= 30
  4628.6  562.84  4693.8  561.75  4761.6  561.72  4773.0  561.29  4783.6  561.39
  4818.3  560.82  4863.6  560.73  4871.5  560.44  4893.5  560.61  4908.9  560.28
  4915.5  560.62  4931.5  560.60  4937.5  561.03  4953.8  560.97  4981.4  559.79
  4988.2  559.76  4993.9  558.63  4994.4  557.83  4999.4  557.83  4999.9  558.63
  5006.1  559.85  5013.5  560.14  5018.8  561.08  5100.0  560.39  5156.2  560.95
  5162.7  561.27  5235.7  562.61  5298.9  564.59  5331.9  565.14  5408.1  567.40
#Mann=3,-1,0
  4628.6     0.1       0  4993.9    0.07       0  4999.9     0.1       0
Bank Sta=4993.9,4999.9
Exp/Cntr=0.3,0.1

Type RM Length L Ch R = 1,8261,396,396,396
BEGIN DESCRIPTION:
Mapping XS 41e4b0be
END DESCRIPTION:
XS GIS Cut Line= 4
      2016727.35     13525762.09      2016544.67     13525552.68
      2016221.75     13525366.91      2016128.99     13525366.91
#Sta/Elev= 30
  4618.1  560.68  4702.9  559.85  4709.6  560.30  4759.9  559.81  4809.2  558.97
  4815.9  558.31  4844.4  559.58  4852.0  559.33  4858.6  560.12  4866.2  559.37
  4887.1  559.71  4922.9  559.26  4930.2  559.76  4966.1  560.12  4981.9  559.81
  4994.7  556.27  4995.2  555.47  5000.2  555.47  5000.7  556.27  5003.4  558.14
  5011.0  559.40  5078.1  560.52  5083.9  560.16  5172.5  562.07  5186.0  562.87
  5217.6  563.26  5268.5  564.81  5325.3  567.13  5345.3  567.27  5361.3  568.18
#Mann=3,-1,0
  4618.1     0.1       0  4994.7    0.07       0  5000.7     0.1       0
Bank Sta=4994.7,5000.7
Exp/Cntr=0.3,0.1

Type RM Length L Ch R = 1,7865,522,522,522
BEGIN DESCRIPTION:
Mapping XS 158c151c
END DESCRIPTION:
XS GIS Cut Line= 4
      2016823.71     13525647.50      2016633.85     13525315.57
      2016427.25     13525188.83      2016078.30     13525138.74
#Sta/Elev= 30
  4567.1  560.16  4779.5  558.54  4817.0  558.36  4823.4  558.80  4838.6  557.84
  4846.5  558.29  4869.5  557.91  4881.7  556.52  4891.8  556.77  4904.1  558.02
  4919.2  557.72  4971.6  558.51  4984.2  557.99  4993.8  555.31  4996.7  555.23
  4997.2  554.43  5002.2  554.43  5002.7  555.23  5006.8  557.22  5015.1  557.84
  5042.3  557.81  5137.0  559.82  5224.4  562.22  5251.9  563.63  5275.0  563.83
  5345.7  566.62  5393.0  567.89  5398.0  567.52  5487.1  570.93  5544.4  571.89
#Mann=3,-1,0
  4567.1     0.1       0  4996.7    0.07       0  5002.7     0.1       0
Bank Sta=4996.7,5002.7
Exp/Cntr=0.3,0.1

Type RM Length L Ch R = 1,7343,388,388,388
BEGIN DESCRIPTION:
Mapping XS 1c9e0909
END DESCRIPTION:
XS GIS Cut Line= 4
      2017144.45     13525520.00      2016952.93     13524955.48
      2016828.63     13524833.26      2016472.22     13524795.99
#Sta/Elev= 30
  4352.2  558.55  4410.3  558.23  4420.8  557.87  4578.9  557.54  4717.9  556.61
  4804.0  556.64  4893.0  555.46  4906.6  555.89  4929.7  556.04  4938.3  555.63
  4966.4  556.10  4982.6  555.89  4986.6  555.37  4987.1  554.57  4992.1  554.57
  4992.6  555.37  5017.9  556.33  5039.2  556.50  5060.3  556.20  5127.0  556.74
  5168.7  558.22  5176.6  558.18  5196.7  558.98  5236.9  559.33  5291.1  560.99
  5397.8  564.11  5417.9  565.00  5437.7  565.13  5448.0  565.70  5481.0  566.27
#Mann=7,-1,0
  4352.2     0.1       0  4717.9    0.05       0  4966.4     0.1       0
  4986.6    0.07       0  4992.6     0.1       0  5168.7    0.05       0
  5291.1     0.1       0
Bank Sta=4986.6,4992.6
Exp/Cntr=0.3,0.1

Type RM Length L Ch R = 1,6955,620,620,620
BEGIN DESCRIPTION:
Mapping XS 6207292b
END DESCRIPTION:
XS GIS Cut Line= 4
      2017200.88     13525506.97      2017204.63     13524860.82
      2017024.94     13524569.16      2016571.80     13524501.45
#Sta/Elev= 30
  4123.3  558.40  4435.3  555.79  4464.7  555.97  4635.3  555.33  4645.3  554.85
  4725.3  554.66  4755.3  553.96  4769.5  554.31  4832.3  553.90  4846.8  554.49
  4863.9  554.14  4969.5  554.48  4976.0  553.70  4984.9  551.76  4990.8  552.58
  4996.5  551.41  4997.0  550.61  5002.0  550.61  5002.5  551.41  5006.2  553.40
  5012.1  551.52  5021.6  551.56  5042.9  553.94  5048.8  553.59  5106.7  557.64
  5170.8  559.01  5192.9  560.28  5324.3  563.91  5455.7  566.79  5570.2  568.02
#Mann=5,-1,0
  4123.3     0.1       0  4464.7    0.05       0  4863.9     0.1       0
  4996.5    0.07       0  5002.5     0.1       0
Bank Sta=4996.5,5002.5
Exp/Cntr=0.3,0.1

Type RM Length L Ch R = 1,6335,30,30,30
BEGIN DESCRIPTION:
Mapping XS cbc480d1
END DESCRIPTION:
XS GIS Cut Line= 5
      2017246.46     13525487.44      2017488.00     13524708.78
      2017586.44     13524705.65      2017603.10     13524682.22
      2017241.10     13524201.98
#Sta/Elev= 30
  4117.2  558.07  4287.3  556.68  4412.9  554.83  4461.2  554.91  4549.0  554.24
  4559.5  554.76  4727.0  552.09  4795.7  552.57  4884.1  552.11  4907.9  553.67
  4915.5  553.46  4925.9  551.08  4939.5  550.66  5034.0  550.75  5037.5  551.70
  5044.0  550.73  5110.6  550.57  5111.1  549.77  5116.1  549.77  5116.6  550.57
  5149.0  550.82  5163.6  554.56  5169.9  552.94  5178.2  554.66  5184.4  553.28
  5192.7  554.28  5213.6  552.72  5292.7  553.10  5527.9  559.34  5661.1  561.70
#Mann=5,-1,0
  4117.2     0.1       0  4461.2    0.05       0  4795.7     0.1       0
  5110.6    0.07       0  5116.6     0.1       0
Bank Sta=5110.6,5116.6
Exp/Cntr=0.3,0.1

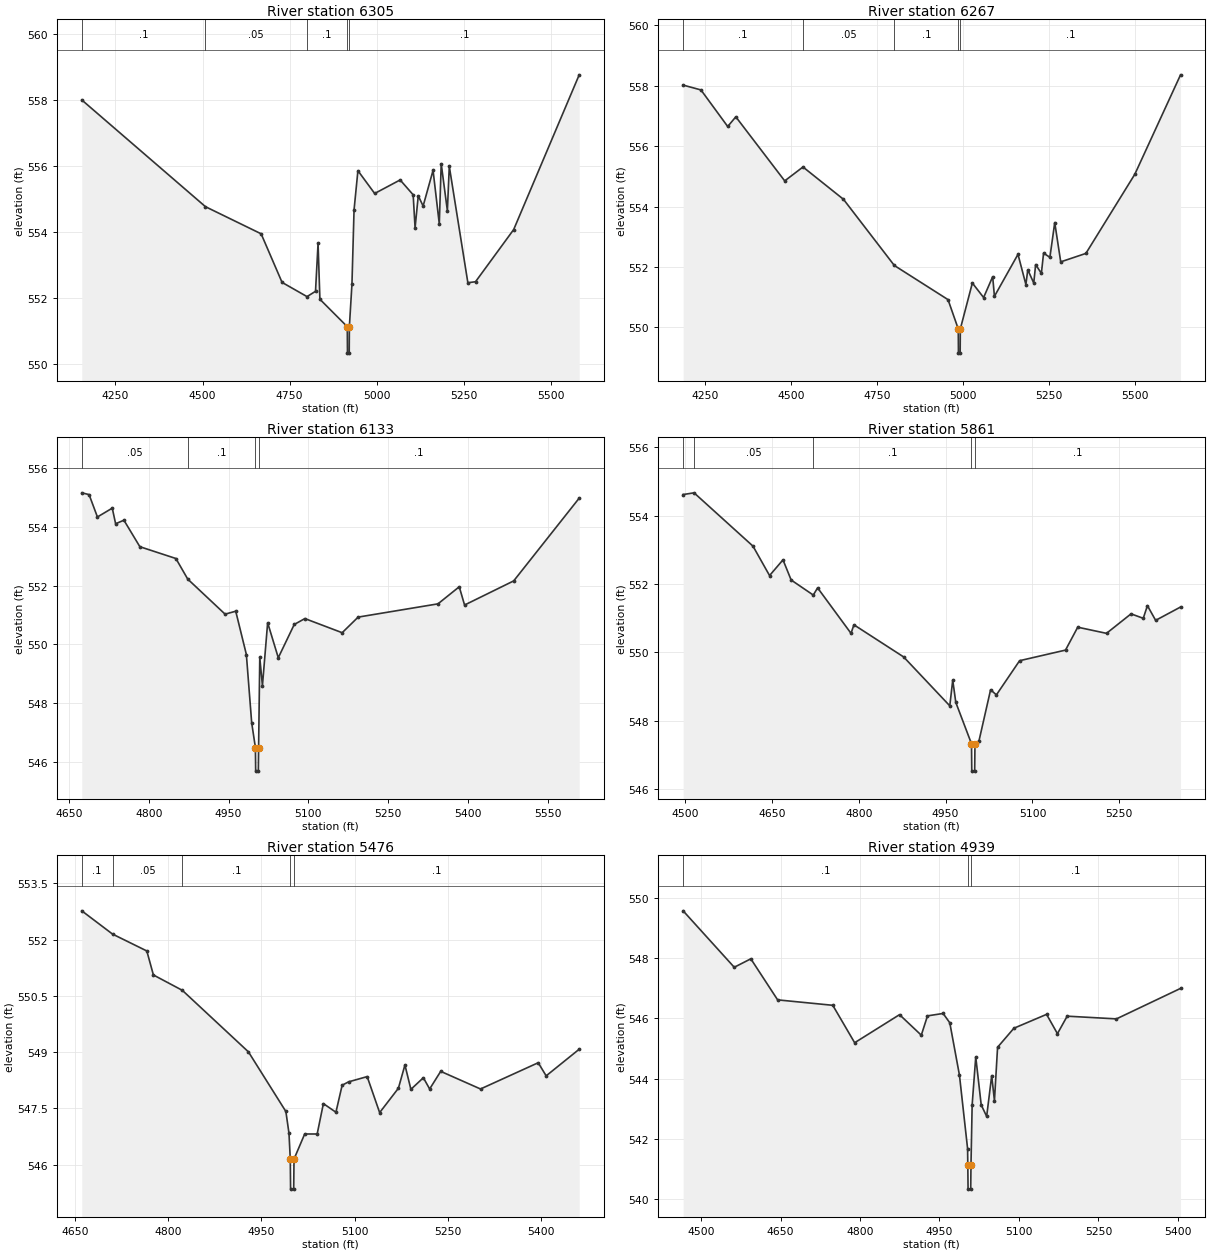
Type RM Length L Ch R = 1,6305,38,38,38
BEGIN DESCRIPTION:
Mapping XS 44b5e594
END DESCRIPTION:
XS GIS Cut Line= 6
      2017289.84     13525496.19      2017523.42     13524737.42
      2017616.65     13524722.32      2017639.56     13524687.95
      2017605.71     13524612.42      2017435.70     13524233.44
#Sta/Elev= 30
  4153.3  557.99  4508.4  554.76  4668.1  553.94  4728.2  552.47  4799.8  552.04
  4824.2  552.20  4831.5  553.65  4836.8  551.96  4915.4  551.13  4915.9  550.33
  4920.9  550.33  4921.4  551.13  4928.8  552.42  4934.8  554.66  4945.9  555.85
  4994.0  555.16  5067.1  555.57  5104.5  555.12  5110.0  554.12  5119.1  555.09
  5133.1  554.78  5161.6  555.86  5179.5  554.24  5185.0  556.06  5202.7  554.64
  5208.2  555.98  5261.5  552.46  5283.5  552.49  5393.1  554.07  5581.1  558.75
#Mann=5,-1,0
  4153.3     0.1       0  4508.4    0.05       0  4799.8     0.1       0
  4915.4    0.07       0  4921.4     0.1       0
Bank Sta=4915.4,4921.4
Exp/Cntr=0.3,0.1

Type RM Length L Ch R = 1,6267,134,134,134
BEGIN DESCRIPTION:
Mapping XS df083ca0
END DESCRIPTION:
XS GIS Cut Line= 6
      2017348.45     13525493.96      2017524.26     13524780.36
      2017651.86     13524741.29      2017667.49     13524678.79
      2017620.61     13524577.23      2017500.81     13524191.79
#Sta/Elev= 30
  4185.2  558.02  4237.1  557.86  4315.0  556.65  4338.6  556.97  4481.0  554.85
  4534.2  555.31  4652.1  554.24  4800.2  552.05  4956.5  550.92  4986.3  549.95
  4986.8  549.15  4991.8  549.15  4992.3  549.95  5027.3  551.47  5060.1  550.99
  5086.5  551.68  5091.6  551.03  5160.2  552.42  5183.2  551.42  5188.7  551.91
  5206.1  551.47  5211.6  552.08  5228.3  551.79  5234.7  552.46  5253.1  552.32
  5267.2  553.47  5284.6  552.17  5357.9  552.45  5500.4  555.07  5633.5  558.36
#Mann=5,-1,0
  4185.2     0.1       0  4534.2    0.05       0  4800.2     0.1       0
  4986.3    0.07       0  4992.3     0.1       0
Bank Sta=4986.3,4992.3
Exp/Cntr=0.3,0.1

Type RM Length L Ch R = 1,6133,272,272,272
BEGIN DESCRIPTION:
Mapping XS 7976574c
END DESCRIPTION:
XS GIS Cut Line= 4
      2017622.78     13525130.82      2017714.81     13524962.40
      2017694.84     13524369.52      2017634.10     13524232.41
#Sta/Elev= 30
  4674.0  555.15  4687.7  555.09  4703.4  554.33  4731.3  554.63  4737.6  554.10
  4753.2  554.22  4783.2  553.32  4850.9  552.92  4873.2  552.22  4943.4  551.03
  4963.4  551.13  4983.4  549.66  4993.4  547.34  5000.4  546.50  5000.9  545.70
  5005.9  545.70  5006.4  546.50  5008.6  549.56  5013.6  548.60  5023.4  550.74
  5043.4  549.55  5073.4  550.68  5093.4  550.88  5163.5  550.40  5193.5  550.93
  5343.6  551.38  5383.6  551.96  5393.6  551.34  5486.0  552.16  5609.1  554.97
#Mann=4,-1,0
  4674.0    0.05       0  4873.2     0.1       0  5000.4    0.07       0
  5006.4     0.1       0
Bank Sta=5000.4,5006.4
Exp/Cntr=0.3,0.1

Type RM Length L Ch R = 1,5861,385,385,385
BEGIN DESCRIPTION:
Mapping XS 8f00dd16
END DESCRIPTION:
XS GIS Cut Line= 4
      2017798.15     13525155.08      2017893.62     13524943.30
      2017869.32     13524528.37      2017723.46     13524375.56
#Sta/Elev= 30
  4496.6  554.62  4515.5  554.67  4617.3  553.11  4645.9  552.25  4669.1  552.71
  4683.2  552.12  4721.4  551.68  4728.9  551.89  4786.6  550.56  4791.6  550.81
  4877.5  549.87  4957.2  548.44  4962.3  549.19  4967.6  548.54  4994.7  547.33
  4995.2  546.53  5000.2  546.53  5000.7  547.33  5007.7  547.42  5027.7  548.91
  5037.7  548.76  5077.8  549.76  5157.1  550.07  5178.2  550.74  5227.9  550.56
  5270.3  551.13  5291.4  551.00  5298.6  551.37  5312.8  550.94  5355.8  551.33
#Mann=5,-1,0
  4496.6     0.1       0  4515.5    0.05       0  4721.4     0.1       0
  4994.7    0.07       0  5000.7     0.1       0
Bank Sta=4994.7,5000.7
Exp/Cntr=0.3,0.1

Type RM Length L Ch R = 1,5476,537,537,537
BEGIN DESCRIPTION:
Mapping XS 50f9836e
END DESCRIPTION:
XS GIS Cut Line= 4
      2018188.33     13525095.43      2018237.80     13524931.40
      2018193.53     13524530.36      2018052.93     13524353.30
#Sta/Elev= 30
  4660.8  552.77  4710.3  552.15  4765.5  551.70  4776.1  551.06  4822.7  550.65
  4929.1  549.01  4989.4  547.42  4994.4  546.84  4996.5  546.15  4997.0  545.35
  5002.0  545.35  5002.5  546.15  5019.7  546.82  5039.8  546.82  5049.8  547.63
  5070.0  547.40  5080.0  548.12  5090.3  548.21  5120.3  548.35  5140.4  547.39
  5170.6  548.04  5181.1  548.66  5190.7  548.01  5210.8  548.32  5220.9  548.02
  5238.7  548.49  5302.8  548.02  5395.7  548.72  5408.5  548.37  5461.7  549.08
#Mann=5,-1,0
  4660.8     0.1       0  4710.3    0.05       0  4822.7     0.1       0
  4996.5    0.07       0  5002.5     0.1       0
Bank Sta=4996.5,5002.5
Exp/Cntr=0.3,0.1

Type RM Length L Ch R = 1,4939,368,368,368
BEGIN DESCRIPTION:
Mapping XS 1395f1cb
END DESCRIPTION:
XS GIS Cut Line= 4
      2018537.28     13525017.34      2018631.03     13524707.44
      2018537.28     13524314.21      2018352.36     13524212.63
#Sta/Elev= 30
  4466.1  549.56  4562.6  547.69  4593.9  547.97  4644.5  546.61  4748.6  546.43
  4789.9  545.19  4874.6  546.12  4915.7  545.44  4927.4  546.08  4956.9  546.16
  4969.5  545.85  4987.7  544.12  5003.1  541.68  5003.5  541.14  5004.0  540.34
  5009.0  540.34  5009.5  541.14  5011.7  543.13  5018.5  544.72  5028.8  543.13
  5039.1  542.75  5048.6  544.10  5053.8  543.27  5059.7  545.04  5090.5  545.67
  5152.2  546.13  5172.7  545.49  5191.1  546.07  5284.1  545.98  5405.1  546.99
#Mann=3,-1,0
  4466.1     0.1       0  5003.5    0.07       0  5009.5     0.1       0
Bank Sta=5003.5,5009.5
Exp/Cntr=0.3,0.1

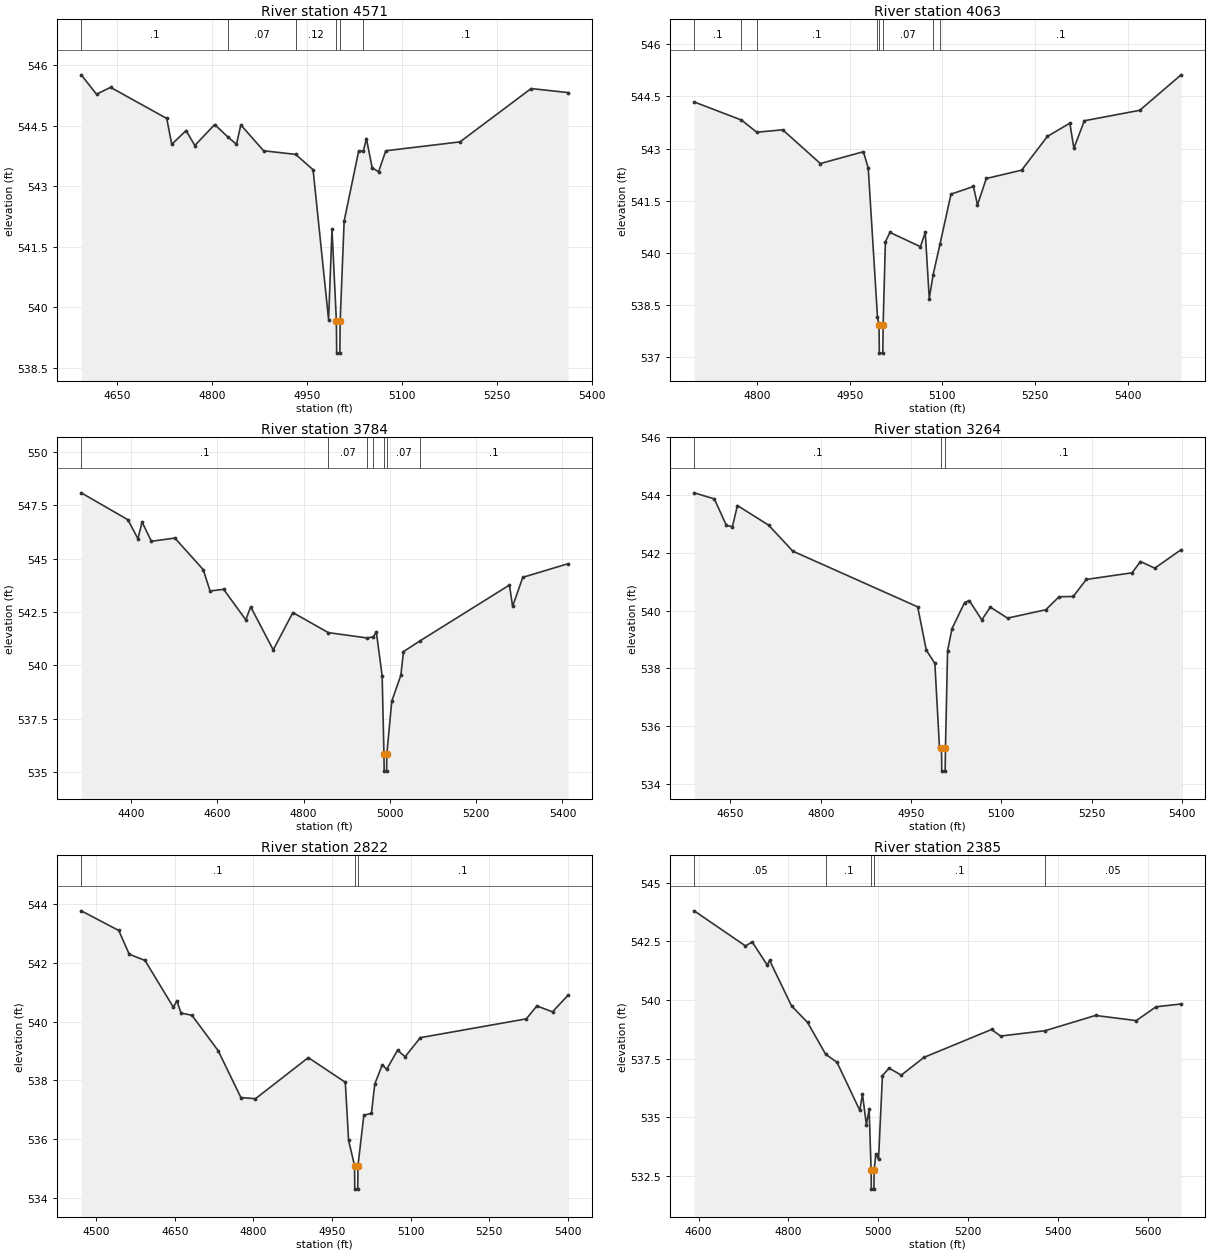
Type RM Length L Ch R = 1,4571,508,508,508
BEGIN DESCRIPTION:
Mapping XS 1720e743
END DESCRIPTION:
XS GIS Cut Line= 4
      2018806.81     13524736.71      2018902.31     13524538.79
      2018772.10     13524203.72      2018603.69     13524115.17
#Sta/Elev= 30
  4593.3  545.76  4617.4  545.28  4639.6  545.45  4728.4  544.68  4736.3  544.04
  4759.0  544.38  4772.8  544.01  4804.2  544.53  4825.1  544.22  4838.6  544.04
  4845.5  544.52  4881.5  543.88  4932.2  543.79  4959.7  543.41  4984.2  539.70
  4989.6  541.94  4996.5  539.67  4997.0  538.87  5002.0  538.87  5002.5  539.67
  5008.8  542.14  5031.7  543.87  5039.3  543.88  5044.0  544.18  5053.1  543.46
  5063.2  543.36  5074.6  543.88  5191.9  544.10  5304.3  545.42  5362.8  545.32
#Mann=6,-1,0
  4593.3     0.1       0  4825.1    0.07       0  4932.2    0.12       0
  4996.5    0.07       0  5002.5    0.12       0  5039.3     0.1       0
Bank Sta=4996.5,5002.5
Exp/Cntr=0.3,0.1

Type RM Length L Ch R = 1,4063,279,279,279
BEGIN DESCRIPTION:
Mapping XS 89bb6ac5
END DESCRIPTION:
XS GIS Cut Line= 4
      2019147.10     13524476.26      2019188.76     13524240.18
      2018895.36     13523995.38      2018728.53     13523986.78
#Sta/Elev= 30
  4697.8  544.34  4774.4  543.82  4799.2  543.47  4841.2  543.54  4902.2  542.57
  4972.0  542.91  4979.8  542.44  4994.8  538.16  4997.3  537.92  4997.8  537.12
  5003.4  537.12  5003.9  537.92  5007.6  540.32  5015.0  540.59  5064.4  540.18
  5072.2  540.59  5078.7  538.69  5085.0  539.38  5096.3  540.27  5113.9  541.69
  5150.3  541.91  5156.8  541.38  5171.1  542.14  5228.4  542.38  5270.1  543.35
  5306.5  543.73  5313.0  543.01  5330.0  543.80  5419.7  544.10  5486.7  545.12
#Mann=8,-1,0
  4697.8     0.1       0  4774.4    0.07       0  4799.2     0.1       0
  4994.8    0.07       0  4997.3    0.07       0  5003.9    0.07       0
  5085.0    0.12       0  5096.3     0.1       0
Bank Sta=4997.3,5003.9
Exp/Cntr=0.3,0.1

Type RM Length L Ch R = 1,3784,520,520,520
BEGIN DESCRIPTION:
Mapping XS ab9a4703
END DESCRIPTION:
XS GIS Cut Line= 4
      2019412.29     13524660.60      2019254.74     13524142.95
      2019063.76     13523870.38      2018830.03     13523769.96
#Sta/Elev= 30
  4284.9  548.08  4392.9  546.82  4416.2  545.93  4425.8  546.71  4447.6  545.81
  4501.9  545.96  4567.6  544.48  4583.4  543.48  4614.8  543.56  4666.2  542.13
  4677.5  542.74  4729.8  540.72  4775.2  542.47  4857.4  541.53  4947.3  541.28
  4960.8  541.33  4968.8  541.54  4982.2  539.51  4986.4  535.84  4986.9  535.04
  4992.5  535.04  4993.0  535.84  5004.5  538.32  5025.5  539.53  5031.6  540.64
  5070.4  541.15  5277.2  543.76  5284.5  542.76  5308.1  544.12  5413.2  544.76
#Mann=7,-1,0
  4284.9     0.1       0  4857.4    0.07       0  4947.3    0.12       0
  4960.8    0.07       0  4986.4    0.07       0  4993.0    0.07       0
  5070.4     0.1       0
Bank Sta=4986.4,4993
Exp/Cntr=0.3,0.1

Type RM Length L Ch R = 1,3264,442,442,442
BEGIN DESCRIPTION:
Mapping XS a782b05d
END DESCRIPTION:
XS GIS Cut Line= 4
      2019624.53     13524278.38      2019610.64     13524049.20
      2019357.17     13523757.54      2019180.07     13523682.88
#Sta/Elev= 30
  4590.0  544.08  4623.4  543.87  4643.5  542.95  4653.5  542.91  4661.7  543.64
  4713.6  542.96  4753.7  542.06  4961.0  540.13  4975.3  538.63  4989.5  538.17
  4997.1  535.29  5000.5  535.24  5001.0  534.44  5006.6  534.44  5007.1  535.24
  5010.6  538.61  5018.0  539.38  5038.9  540.28  5046.5  540.35  5067.4  539.68
  5081.6  540.12  5110.1  539.74  5173.7  540.03  5195.6  540.48  5219.2  540.49
  5240.9  541.08  5316.9  541.31  5330.8  541.70  5354.5  541.47  5398.2  542.11
#Mann=3,-1,0
  4590.0     0.1       0  5000.5    0.07       0  5007.1     0.1       0
Bank Sta=5000.5,5007.1
Exp/Cntr=0.3,0.1

Type RM Length L Ch R = 1,2822,437,437,437
BEGIN DESCRIPTION:
Mapping XS 06f41649
END DESCRIPTION:
XS GIS Cut Line= 4
      2019926.61     13524106.45      2019935.29     13523971.08
      2019617.58     13523557.88      2019345.16     13523555.43
#Sta/Elev= 30
  4471.4  543.77  4543.0  543.10  4563.0  542.29  4593.1  542.08  4647.4  540.48
  4653.7  540.71  4661.9  540.29  4682.7  540.21  4732.6  539.01  4776.1  537.41
  4803.9  537.37  4904.8  538.77  4975.4  537.93  4981.7  535.95  4993.0  535.09
  4993.5  534.29  4999.1  534.29  4999.6  535.09  5010.8  536.81  5025.3  536.87
  5031.6  537.87  5046.1  538.53  5054.3  538.37  5075.1  539.02  5089.6  538.80
  5118.6  539.45  5320.9  540.09  5340.9  540.53  5370.9  540.33  5400.7  540.90
#Mann=3,-1,0
  4471.4     0.1       0  4993.0    0.07       0  4999.6     0.1       0
Bank Sta=4993,4999.6
Exp/Cntr=0.3,0.1

Type RM Length L Ch R = 1,2385,404,404,404
BEGIN DESCRIPTION:
Mapping XS 4647d0b0
END DESCRIPTION:
XS GIS Cut Line= 4
      2020154.05     13523974.53      2020202.65     13523807.88
      2019947.44     13523443.30      2019485.79     13523393.97
#Sta/Elev= 30
  4590.4  543.81  4704.5  542.31  4719.5  542.48  4752.9  541.49  4758.2  541.69
  4806.9  539.75  4842.6  539.04  4882.9  537.68  4908.0  537.34  4958.6  535.29
  4964.7  535.97  4973.4  534.67  4979.5  535.34  4983.9  532.72  4984.4  531.92
  4990.1  531.92  4990.6  532.72  4994.3  533.41  5000.4  533.20  5009.1  536.77
  5023.8  537.09  5051.0  536.79  5101.6  537.55  5251.7  538.74  5271.8  538.46
  5371.2  538.69  5483.0  539.34  5573.5  539.12  5617.7  539.71  5673.3  539.83
#Mann=5,-1,0
  4590.4    0.05       0  4882.9     0.1       0  4983.9    0.07       0
  4990.6     0.1       0  5371.2    0.05       0
Bank Sta=4983.9,4990.6
Exp/Cntr=0.3,0.1

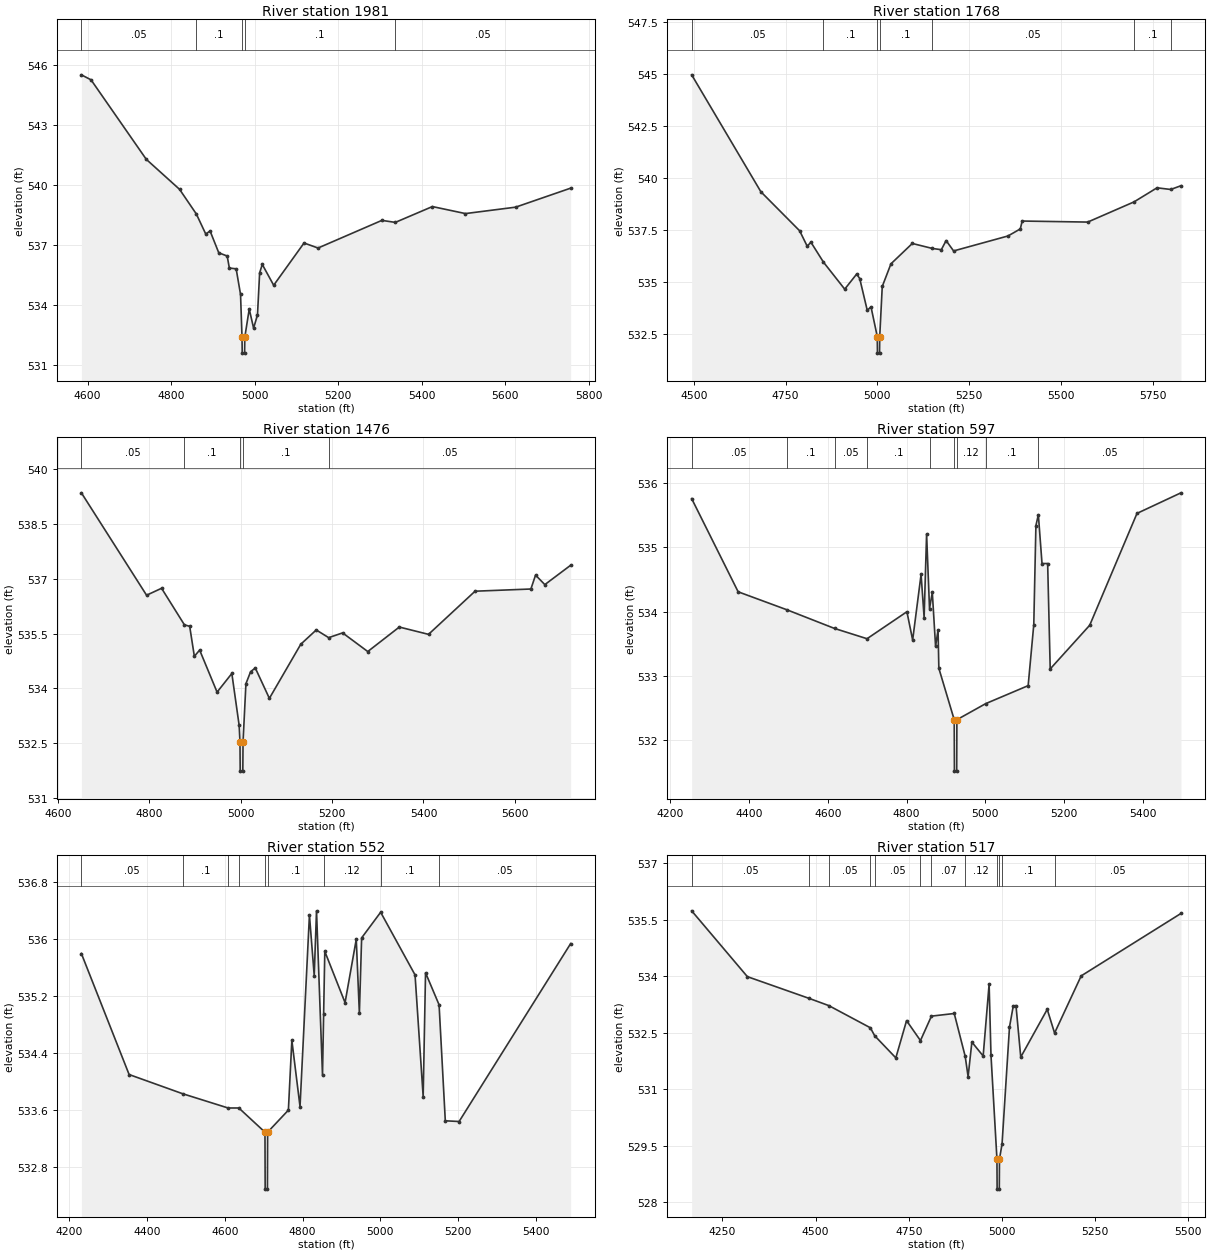
Type RM Length L Ch R = 1,1981,213,213,213
BEGIN DESCRIPTION:
Mapping XS bcdbd074
END DESCRIPTION:
XS GIS Cut Line= 4
      2020522.29     13523649.20      2020396.95     13523440.40
      2020063.76     13523344.34      2019483.24     13523334.08
#Sta/Elev= 30
  4585.2  545.50  4608.3  545.25  4740.5  541.28  4820.2  539.78  4860.3  538.55
  4882.8  537.55  4893.2  537.70  4914.0  536.61  4934.1  536.45  4939.3  535.85
  4955.6  535.81  4966.1  534.53  4969.6  532.40  4970.1  531.60  4975.8  531.60
  4976.3  532.40  4986.9  533.80  4997.3  532.85  5006.6  533.50  5011.8  535.61
  5018.1  536.03  5045.4  534.99  5118.0  537.10  5151.6  536.85  5304.3  538.23
  5336.5  538.13  5425.2  538.92  5504.3  538.57  5624.3  538.89  5756.1  539.84
#Mann=5,-1,0
  4585.2    0.05       0  4860.3     0.1       0  4969.6    0.07       0
  4976.3     0.1       0  5336.5    0.05       0
Bank Sta=4969.6,4976.3
Exp/Cntr=0.3,0.1

Type RM Length L Ch R = 1,1768,292,292,292
BEGIN DESCRIPTION:
Mapping XS 594e57f2
END DESCRIPTION:
XS GIS Cut Line= 4
      2020652.50     13523487.75      2020503.90     13523256.38
      2019930.29     13523132.07      2019470.20     13523235.12
#Sta/Elev= 30
  4493.8  544.97  4682.4  539.34  4788.1  537.46  4808.6  536.72  4818.8  536.91
  4853.0  535.95  4910.9  534.65  4943.6  535.38  4951.8  535.16  4972.3  533.63
  4982.5  533.80  4999.6  532.37  5000.1  531.57  5005.8  531.57  5006.3  532.37
  5013.2  534.78  5036.9  535.87  5095.1  536.85  5149.8  536.61  5174.2  536.55
  5187.2  536.99  5207.6  536.49  5355.7  537.21  5389.4  537.55  5394.5  537.93
  5573.1  537.88  5699.1  538.85  5762.0  539.53  5799.3  539.45  5827.2  539.63
#Mann=7,-1,0
  4493.8    0.05       0  4853.0     0.1       0  4999.6    0.07       0
  5006.3     0.1       0  5149.8    0.05       0  5699.1     0.1       0
  5799.3    0.05       0
Bank Sta=4999.6,5006.3
Exp/Cntr=0.3,0.1

Type RM Length L Ch R = 1,1476,879,879,879
BEGIN DESCRIPTION:
Mapping XS d76b0a24
END DESCRIPTION:
XS GIS Cut Line= 4
      2020713.06     13523172.45      2020643.62     13523043.99
      2020105.43     13522922.47      2019739.52     13522991.83
#Sta/Elev= 30
  4651.8  539.35  4794.4  536.55  4827.2  536.74  4877.2  535.74  4888.7  535.70
  4898.9  534.88  4910.5  535.05  4948.6  533.90  4980.9  534.41  4996.9  532.99
  4998.7  532.54  4999.2  531.74  5004.9  531.74  5005.4  532.54  5011.7  534.13
  5022.0  534.46  5032.2  534.56  5063.0  533.73  5131.7  535.21  5165.5  535.60
  5192.7  535.39  5223.2  535.52  5278.2  535.01  5347.2  535.68  5411.1  535.48
  5512.9  536.66  5635.0  536.72  5645.2  537.10  5665.5  536.84  5722.0  537.37
#Mann=5,-1,0
  4651.8    0.05       0  4877.2     0.1       0  4998.7    0.07       0
  5005.4     0.1       0  5192.7    0.05       0
Bank Sta=4998.7,5005.4
Exp/Cntr=0.3,0.1

Type RM Length L Ch R = 1,597,45,45,45
BEGIN DESCRIPTION:
Mapping XS 1b8f4cd5
END DESCRIPTION:
XS GIS Cut Line= 6
      2020888.81     13522777.73      2020388.18     13522397.57
      2020354.55     13522330.29      2020252.55     13522316.19
      2020209.15     13522368.27      2019974.15     13522650.83
#Sta/Elev= 30
  4254.4  535.76  4372.4  534.31  4496.3  534.03  4617.0  533.74  4699.6  533.58
  4800.8  534.00  4815.4  533.56  4836.8  534.58  4844.5  533.91  4850.8  535.21
  4858.2  534.05  4865.3  534.30  4873.6  533.46  4879.9  533.72  4881.9  533.12
  4920.9  532.32  4921.4  531.52  4927.2  531.52  4927.7  532.32  5000.8  532.57
  5108.6  532.85  5122.9  533.80  5128.3  535.34  5134.5  535.51  5143.8  534.75
  5158.1  534.75  5164.6  533.11  5264.9  533.79  5384.9  535.53  5496.5  535.85
#Mann=9,-1,0
  4254.4    0.05       0  4496.3     0.1       0  4617.0    0.05       0
  4699.6     0.1       0  4858.2    0.12       0  4920.9    0.07       0
  4927.7    0.12       0  5000.8     0.1       0  5134.5    0.05       0
Bank Sta=4920.9,4927.7
Exp/Cntr=0.3,0.1

Type RM Length L Ch R = 1,552,35,35,35
BEGIN DESCRIPTION:
Mapping XS 4dd31e90
END DESCRIPTION:
XS GIS Cut Line= 6
      2020912.27     13522738.68      2020427.25     13522406.25
      2020353.46     13522285.80      2020242.79     13522270.61
      2020191.79     13522342.23      2019963.06     13522578.73
#Sta/Elev= 30
  4231.2  535.80  4353.9  534.10  4491.7  533.83  4608.4  533.63  4636.0  533.63
  4703.2  533.29  4703.7  532.49  4709.5  532.49  4710.0  533.29  4763.4  533.60
  4772.3  534.58  4793.3  533.65  4817.5  536.34  4829.8  535.49  4835.7  536.40
  4851.1  534.09  4854.0  534.95  4857.0  535.83  4909.1  535.11  4937.9  536.00
  4945.9  534.96  4951.7  536.02  5000.6  536.38  5089.0  535.50  5109.9  533.79
  5116.0  535.53  5150.8  535.08  5166.8  533.45  5202.3  533.44  5489.1  535.94
#Mann=9,-1,0
  4231.2    0.05       0  4491.7     0.1       0  4608.4    0.05       0
  4636.0     0.1       0  4703.2    0.07       0  4710.0     0.1       0
  4854.0    0.12       0  5000.6     0.1       0  5150.8    0.05       0
Bank Sta=4703.2,4710
Exp/Cntr=0.3,0.1

Type RM Length L Ch R = 1,517,162,162,162
BEGIN DESCRIPTION:
Mapping XS 5a1b0c60
END DESCRIPTION:
XS GIS Cut Line= 5
      2020987.81     13522712.65      2020424.42     13522260.44
      2020229.76     13522233.72      2020110.41     13522290.14
      2019940.56     13522490.11
#Sta/Elev= 30
  4167.3  535.74  4316.8  533.99  4483.1  533.41  4535.4  533.22  4647.0  532.63
  4658.4  532.42  4715.3  531.83  4744.1  532.82  4781.4  532.29  4810.9  532.94
  4872.1  533.01  4901.5  531.87  4909.3  531.33  4919.4  532.25  4949.7  531.88
  4965.7  533.79  4970.7  531.90  4986.7  529.14  4987.2  528.34  4993.0  528.34
  4993.5  529.14  5000.4  529.54  5020.4  532.65  5030.5  533.21  5037.8  533.22
  5050.6  531.85  5121.7  533.12  5141.4  532.49  5212.8  534.01  5480.6  535.67
#Mann=12,-1,0
  4167.3    0.05       0  4483.1     0.1       0  4535.4    0.05       0
  4647.0     0.1       0  4658.4    0.05       0  4781.4     0.1       0
  4810.9    0.07       0  4901.5    0.12       0  4986.7    0.07       0
  4993.5    0.12       0  5000.4     0.1       0  5141.4    0.05       0
Bank Sta=4986.7,4993.5
Exp/Cntr=0.3,0.1

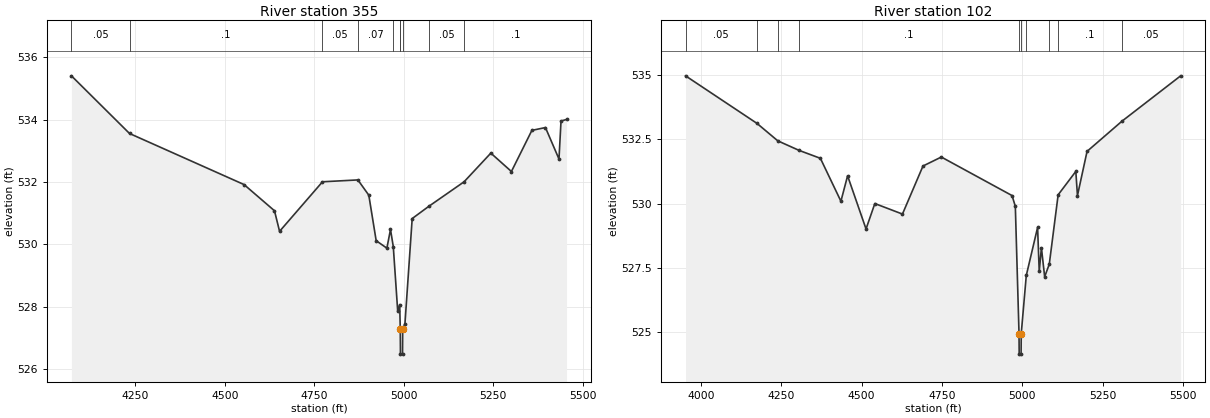
Type RM Length L Ch R = 1,355,253,253,253
BEGIN DESCRIPTION:
Mapping XS 2311b3b1
END DESCRIPTION:
XS GIS Cut Line= 4
      2021102.41     13522639.76      2020624.30     13522142.14
      2020216.54     13522083.93      2019970.05     13522219.32
#Sta/Elev= 30
  4071.6  535.41  4233.9  533.56  4554.0  531.92  4638.9  531.08  4653.1  530.42
  4773.0  532.01  4871.9  532.07  4902.4  531.58  4923.0  530.12  4952.9  529.88
  4963.0  530.48  4970.8  529.93  4983.2  527.85  4988.7  528.07  4990.2  527.33
  4990.3  527.28  4990.8  526.48  4996.6  526.48  4997.1  527.28  5003.4  527.46
  5023.6  530.83  5069.7  531.22  5168.6  532.01  5243.3  532.93  5300.8  532.34
  5358.0  533.66  5395.9  533.75  5433.7  532.74  5439.4  533.96  5454.8  534.01
#Mann=10,-1,0
  4071.6    0.05       0  4233.9     0.1       0  4773.0    0.05       0
  4871.9    0.07       0  4970.8    0.12       0  4990.2     0.1       0
  4990.3    0.07       0  4997.1     0.1       0  5069.7    0.05       0
  5168.6     0.1       0
Bank Sta=4990.3,4997.1
Exp/Cntr=0.3,0.1

Type RM Length L Ch R = 1,102,0,0,0
BEGIN DESCRIPTION:
UNT 165 in Lagunillas Cr Wtrshd 1.0
END DESCRIPTION:
XS GIS Cut Line= 4
      2021279.47     13522600.67      2020760.97     13521968.53
      2020279.04     13521884.27      2020044.70     13521894.69
#Sta/Elev= 30
  3951.7  534.97  4174.0  533.12  4238.9  532.44  4304.9  532.07  4371.5  531.76
  4435.4  530.09  4456.2  531.08  4513.6  529.01  4541.0  530.00  4627.0  529.59
  4690.9  531.46  4748.0  531.81  4968.2  530.31  4978.4  529.89  4989.9  524.94
  4990.4  524.14  4996.3  524.14  4996.8  524.94  5012.5  527.20  5047.7  529.07
  5052.8  527.36  5059.6  528.28  5069.7  527.15  5084.1  527.64  5111.7  530.34
  5166.7  531.25  5171.8  530.31  5201.7  532.03  5309.9  533.20  5493.1  534.97
#Mann=10,-1,0
  3951.7    0.05       0  4174.0     0.1       0  4238.9    0.05       0
  4304.9     0.1       0  4989.9    0.07       0  4996.8     0.1       0
  5012.5    0.07       0  5084.1    0.12       0  5111.7     0.1       0
  5309.9    0.05       0
Bank Sta=4989.9,4996.8
Exp/Cntr=0.3,0.1

Chan Stop Cuts=-1