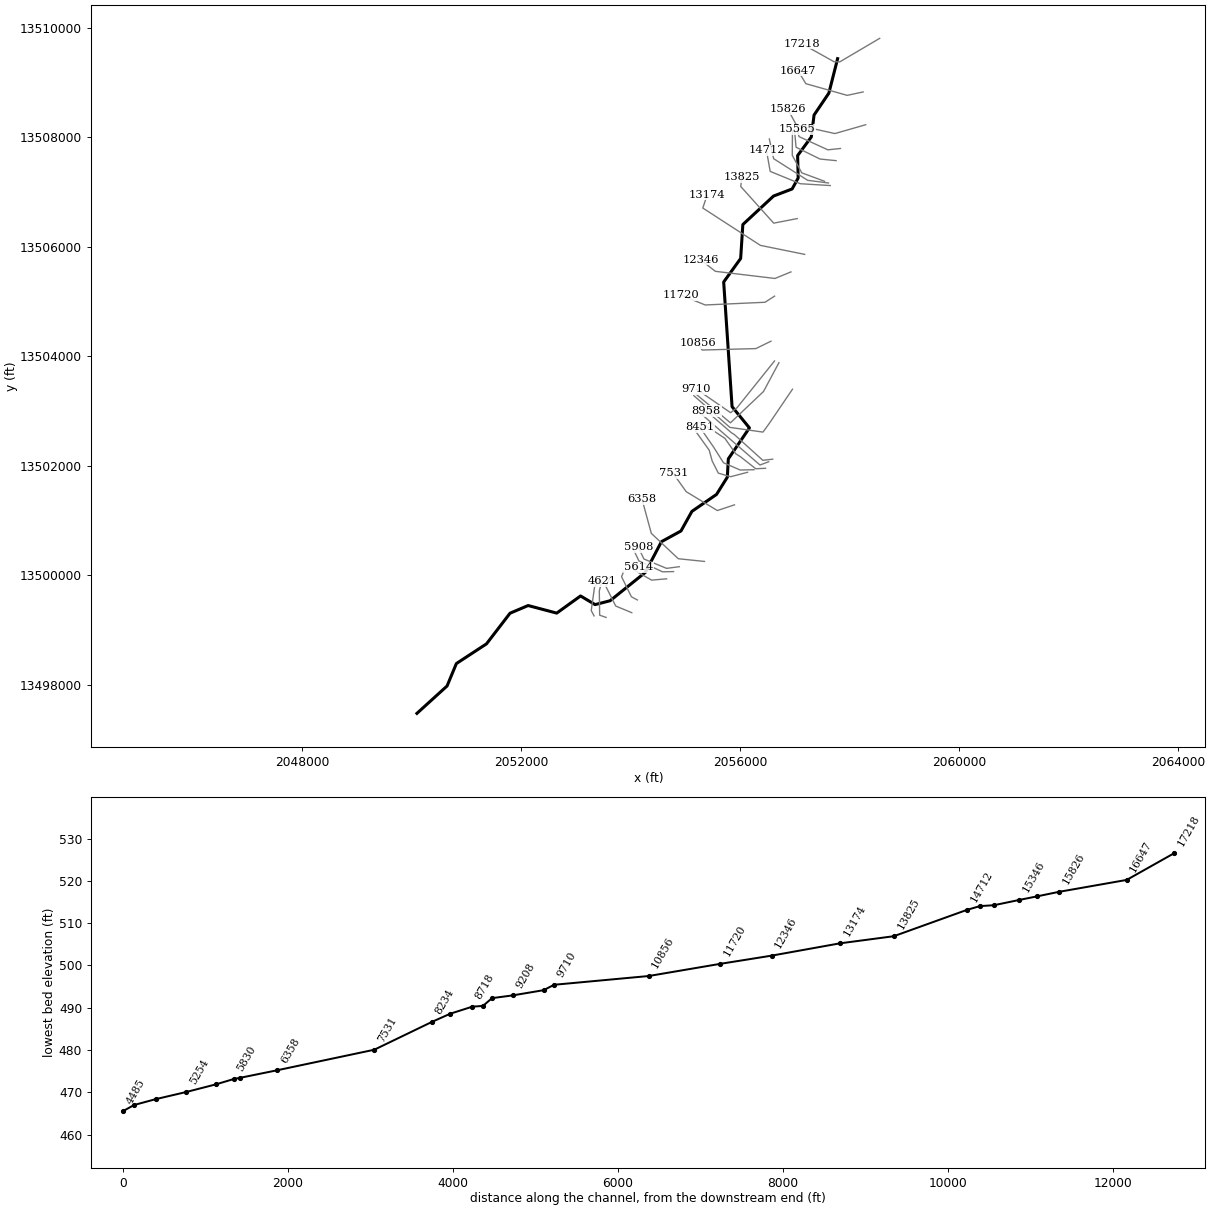
--- UNT 167 in Lagunillas Cr Wtrshd.prj (project) ---

Proj Title=UNT 167 in Lagunillas Cr Wtrshd Base Level Engineering
Current Plan=p01
Default Exp/Contr=0.3,0.1
English Units
Geom File=g01
Flow File=f01
Plan File=p01
BEGIN DESCRIPTION:
UNT 167 in Lagunillas Cr Wtrshd
END DESCRIPTION:

--- UNT 167 in Lagunillas Cr Wtrshd.p01 (plan) ---

Plan Title=Multiple Run
Short Identifier=Multiple
Geom File=g01
Flow File=f01
Subcritical Flow
K Sum by GR= 0
Std Step Tol= 0.01
Critical Tol= 0.01
Num of Std Step Trials= 20
Max Error Tol= 0.3
Flow Tol Ratio= 0.001
Split Flow NTrial= 30
Split Flow Tol= 0.02
Split Flow Ratio= 0.02
Log Output Level= 0
Friction Slope Method= 1
Unsteady Friction Slope Method= 2
Unsteady Bridges Friction Slope Method= 1
Parabolic Critical Depth
Global Vel Dist=  1 , 1 , 1
Global Log Level= 0
CheckData=True
Encroach Param= -1, 0, 0, 0
BEGIN DESCRIPTION:
Multiple Run
END DESCRIPTION:

--- UNT 167 in Lagunillas Cr Wtrshd.f01 (steady flow) ---

Flow Title=Multiple
Number of Profiles=7
Profile Names=10-year,25-year,50-year,1pct_min,100-year,1pct_plu,500-year
River Rch & RM= UNT 167 in Lagun,Reach-1,17218
     165     222     268     162     324     646     477
River Rch & RM= UNT 167 in Lagun,Reach-1,13825
     275     381     468     287     573    1143     870
River Rch & RM= UNT 167 in Lagun,Reach-1,8234
     378     532     661     409     817    1629    1266
River Rch & RM= UNT 167 in Lagun,Reach-1,5830
     471     671     840     524    1045    2085    1643
Boundary for River Rch & Prof#=UNT 167 in Lagun,Reach-1,1
Up Type=0
Dn Type=3
Dn Slope=0.005
Boundary for River Rch & Prof#=UNT 167 in Lagun,Reach-1,2
Up Type=0
Dn Type=3
Dn Slope=0.005
Boundary for River Rch & Prof#=UNT 167 in Lagun,Reach-1,3
Up Type=0
Dn Type=3
Dn Slope=0.005
Boundary for River Rch & Prof#=UNT 167 in Lagun,Reach-1,4
Up Type=0
Dn Type=3
Dn Slope=0.005
Boundary for River Rch & Prof#=UNT 167 in Lagun,Reach-1,5
Up Type=0
Dn Type=3
Dn Slope=0.005
Boundary for River Rch & Prof#=UNT 167 in Lagun,Reach-1,6
Up Type=0
Dn Type=3
Dn Slope=0.005
Boundary for River Rch & Prof#=UNT 167 in Lagun,Reach-1,7
Up Type=0
Dn Type=3
Dn Slope=0.005

--- UNT 167 in Lagunillas Cr Wtrshd.g01 (geometry) ---

Geom Title=Existing Conditions

River Reach=UNT 167 in Lagun,Reach-1
Reach XY= 30
      2057780.80     13509434.54      2057620.80     13508804.54
      2057350.80     13508404.54      2057300.80     13508004.54
      2057050.80     13507664.54      2057060.80     13507254.54
      2056950.80     13507054.54      2056610.80     13506924.54
      2056050.80     13506404.54      2056010.80     13505784.54
      2055700.80     13505354.54      2055854.00     13503077.09
      2056170.84     13502689.72      2055785.53     13502123.52
      2055767.52     13501789.25      2055570.80     13501474.54
      2055120.80     13501164.54      2054921.44     13500806.45
      2054564.23     13500610.70      2054270.50     13500050.41
      2053627.21     13499532.06      2053353.29     13499461.46
      2053087.84     13499619.60      2052652.96     13499306.15
      2052130.80     13499444.54      2051800.80     13499304.54
      2051370.80     13498744.54      2050820.80     13498384.54
      2050650.80     13497974.54      2050100.80     13497474.54

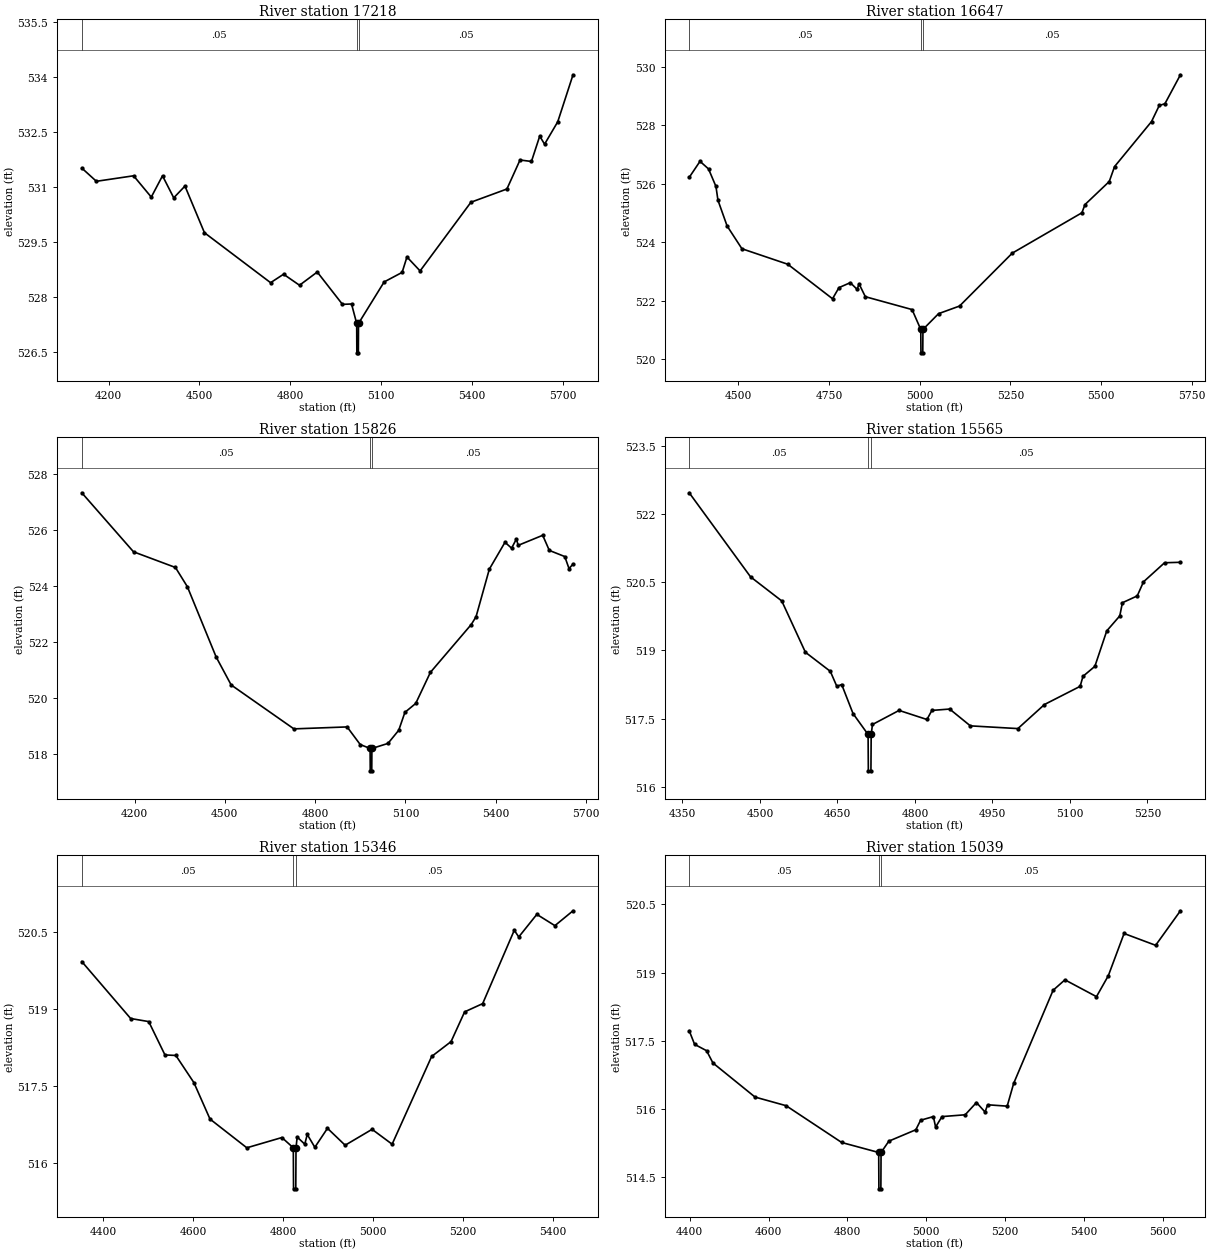
Type RM Length L Ch R = 1,17218,571,571,571
BEGIN DESCRIPTION:
UNT 167 in Lagunillas Cr Wtrshd 35.0
END DESCRIPTION:
XS GIS Cut Line= 4
      2058549.22     13509805.84      2057822.12     13509376.84
      2057716.87     13509377.92      2057128.65     13509706.19
#Sta/Elev= 30
  4111.3  531.52  4159.5  531.16  4282.4  531.31  4340.9  530.73  4378.0  531.31
  4415.1  530.71  4452.2  531.03  4516.6  529.76  4735.1  528.40  4778.0  528.63
  4830.7  528.33  4889.3  528.69  4972.6  527.81  5002.6  527.82  5019.6  527.29
  5020.1  526.49  5025.1  526.49  5025.6  527.29  5110.3  528.42  5169.7  528.68
  5185.7  529.10  5229.1  528.72  5397.1  530.59  5515.9  530.95  5559.3  531.74
  5597.0  531.70  5624.4  532.39  5640.4  532.17  5683.9  532.78  5734.4  534.06
#Mann=3,-1,0
  4111.3    0.05       0  5019.6   0.035       0  5025.6    0.05       0
Bank Sta=5019.6,5025.6
Exp/Cntr=0.3,0.1

Type RM Length L Ch R = 1,16647,821,821,821
BEGIN DESCRIPTION:
Mapping XS eca397a2
END DESCRIPTION:
XS GIS Cut Line= 4
      2058247.15     13508826.69      2057955.50     13508764.19
      2057200.29     13508977.73      2057060.44     13509210.81
#Sta/Elev= 30
  4364.3  526.22  4394.1  526.77  4417.6  526.51  4438.1  525.91  4443.6  525.44
  4468.8  524.56  4509.7  523.78  4636.2  523.25  4759.6  522.07  4777.4  522.45
  4808.6  522.62  4827.5  522.39  4832.7  522.58  4850.1  522.14  4979.0  521.70
  5003.0  521.02  5003.5  520.22  5008.5  520.22  5009.0  521.02  5052.1  521.56
  5109.9  521.82  5255.4  523.63  5447.4  525.01  5455.9  525.29  5522.9  526.08
  5537.5  526.59  5639.5  528.13  5660.8  528.68  5676.4  528.74  5719.2  529.73
#Mann=3,-1,0
  4364.3    0.05       0  5003.0   0.035       0  5009.0    0.05       0
Bank Sta=5003,5009
Exp/Cntr=0.3,0.1

Type RM Length L Ch R = 1,15826,261,261,261
BEGIN DESCRIPTION:
Mapping XS 586928a0
END DESCRIPTION:
XS GIS Cut Line= 4
      2058294.00     13508227.72      2057731.54     13508066.27
      2057028.41     13508222.52      2056872.14     13508509.03
#Sta/Elev= 30
  4024.8  527.34  4196.6  525.23  4335.9  524.67  4375.6  523.98  4471.1  521.47
  4521.0  520.47  4729.4  518.90  4906.2  518.97  4949.7  518.34  4982.5  518.20
  4983.0  517.40  4988.0  517.40  4988.5  518.20  5041.9  518.38  5077.6  518.85
  5098.1  519.49  5134.1  519.81  5182.8  520.92  5318.5  522.63  5334.5  522.91
  5378.6  524.61  5430.6  525.57  5452.5  525.36  5468.6  525.69  5474.3  525.46
  5555.9  525.82  5577.8  525.28  5629.2  525.06  5643.3  524.63  5656.6  524.79
#Mann=3,-1,0
  4024.8    0.05       0  4982.5   0.035       0  4988.5    0.05       0
Bank Sta=4982.5,4988.5
Exp/Cntr=0.3,0.1

Type RM Length L Ch R = 1,15565,219,219,219
BEGIN DESCRIPTION:
Mapping XS 63554d12
END DESCRIPTION:
XS GIS Cut Line= 4
      2057833.07     13507793.61      2057602.15     13507769.30
      2057076.11     13508010.62      2057041.40     13508145.99
#Sta/Elev= 30
  4363.1  522.47  4481.8  520.62  4542.2  520.09  4588.0  518.96  4636.2  518.54
  4648.8  518.21  4658.2  518.25  4680.2  517.61  4709.3  517.15  4709.8  516.35
  4714.8  516.35  4715.3  517.15  4717.8  517.37  4769.3  517.68  4823.2  517.48
  4832.8  517.68  4867.2  517.71  4907.2  517.34  4999.2  517.28  5050.7  517.81
  5119.7  518.21  5125.2  518.43  5148.2  518.65  5171.2  519.43  5196.4  519.76
  5201.5  520.05  5230.2  520.20  5242.3  520.51  5283.1  520.93  5313.8  520.94
#Mann=3,-1,0
  4363.1    0.05       0  4709.3   0.035       0  4715.3    0.05       0
Bank Sta=4709.3,4715.3
Exp/Cntr=0.3,0.1

Type RM Length L Ch R = 1,15346,307,307,307
BEGIN DESCRIPTION:
Mapping XS 3bdcbf71
END DESCRIPTION:
XS GIS Cut Line= 4
      2057753.18     13507571.39      2057459.79     13507600.90
      2057022.29     13507816.18      2056994.52     13508125.17
#Sta/Elev= 30
  4352.1  519.92  4460.8  518.81  4501.0  518.75  4537.1  518.10  4561.3  518.09
  4601.5  517.56  4637.3  516.85  4719.2  516.29  4797.2  516.49  4822.6  516.29
  4823.1  515.49  4828.1  515.49  4828.6  516.29  4831.2  516.50  4848.1  516.36
  4853.6  516.55  4870.5  516.30  4898.6  516.67  4937.9  516.34  4997.8  516.65
  5042.4  516.36  5130.3  518.07  5173.5  518.36  5203.7  518.94  5243.8  519.10
  5314.1  520.53  5324.1  520.40  5364.3  520.84  5404.5  520.62  5444.8  520.91
#Mann=3,-1,0
  4352.1    0.05       0  4822.6   0.035       0  4828.6    0.05       0
Bank Sta=4822.6,4828.6
Exp/Cntr=0.3,0.1

Type RM Length L Ch R = 1,15039,170,170,170
BEGIN DESCRIPTION:
Mapping XS cb16666b
END DESCRIPTION:
XS GIS Cut Line= 4
      2057541.38     13507194.65      2057126.46     13507349.16
      2056952.85     13507668.61      2056956.32     13508107.87
#Sta/Elev= 30
  4398.8  517.72  4412.5  517.42  4442.9  517.28  4459.0  517.01  4565.7  516.26
  4644.5  516.07  4785.5  515.26  4879.3  515.04  4879.8  514.24  4884.8  514.24
  4885.3  515.04  4905.1  515.29  4973.4  515.54  4985.6  515.75  5017.9  515.83
  5023.6  515.60  5039.8  515.83  5098.6  515.87  5127.2  516.14  5149.0  515.93
  5155.5  516.09  5205.1  516.06  5221.5  516.56  5321.5  518.61  5351.5  518.84
  5431.5  518.47  5461.5  518.93  5501.5  519.86  5581.5  519.60  5644.4  520.36
#Mann=3,-1,0
  4398.8    0.05       0  4879.3   0.035       0  4885.3    0.05       0
Bank Sta=4879.3,4885.3
Exp/Cntr=0.3,0.1

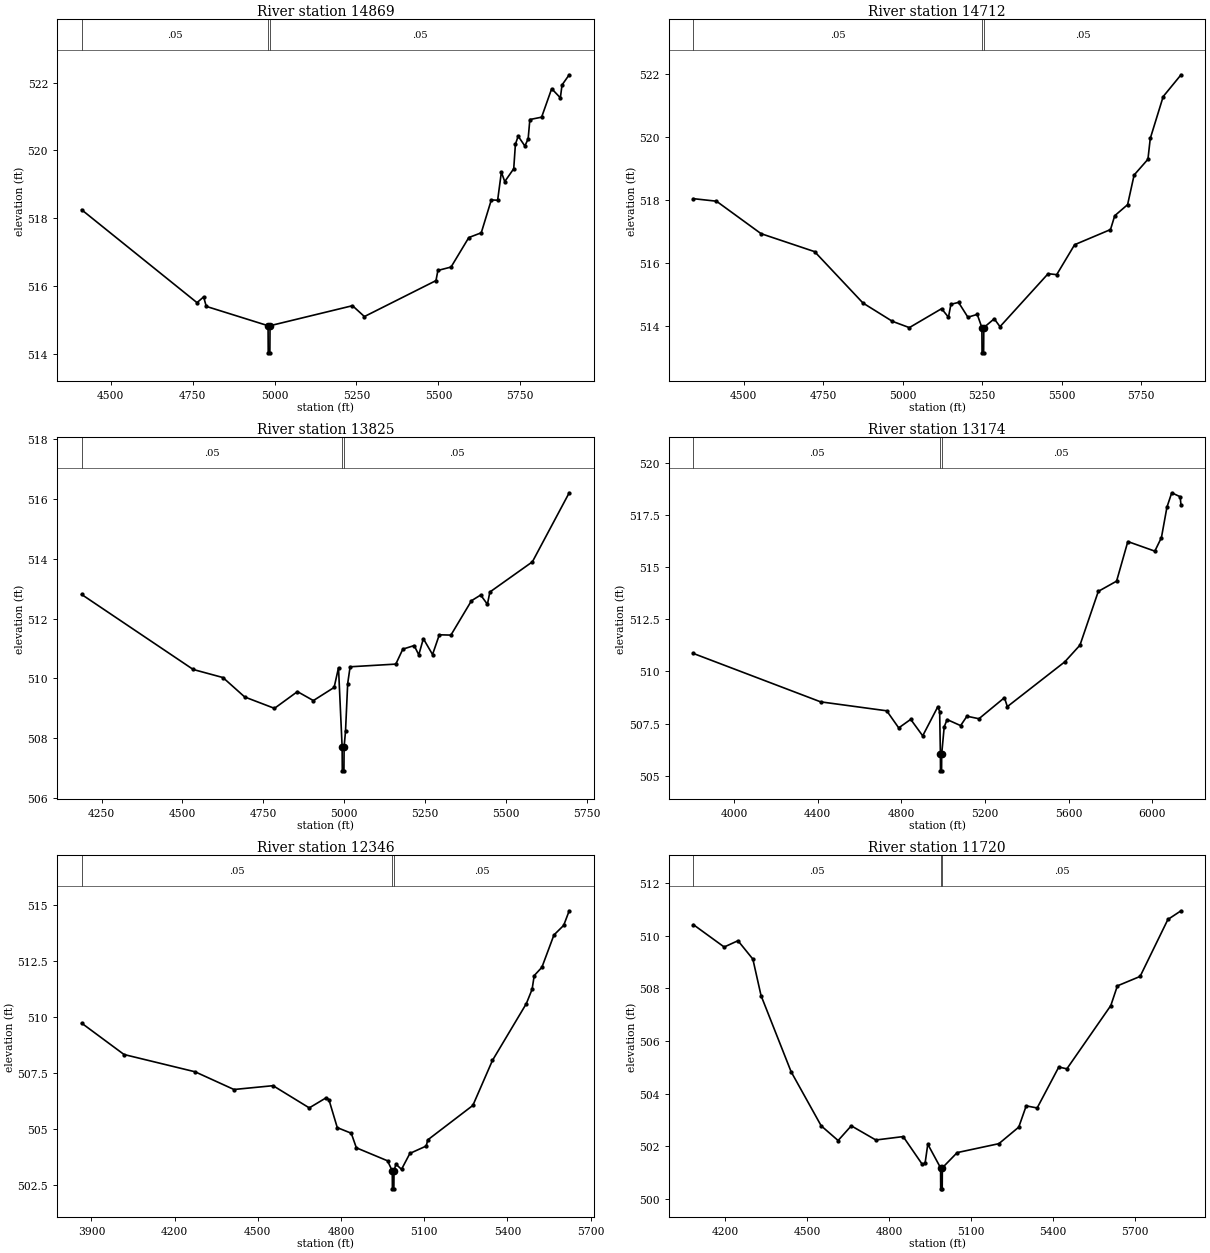
Type RM Length L Ch R = 1,14869,157,157,157
BEGIN DESCRIPTION:
Mapping XS 39992e44
END DESCRIPTION:
XS GIS Cut Line= 4
      2057614.34     13507163.39      2057234.10     13507212.01
      2056612.57     13507607.84      2056534.44     13507967.24
#Sta/Elev= 30
  4411.2  518.25  4763.4  515.51  4783.6  515.68  4791.6  515.40  4980.2  514.83
  4980.7  514.03  4985.7  514.03  4986.2  514.83  5237.8  515.42  5274.2  515.10
  5492.6  516.16  5498.5  516.46  5538.6  516.56  5592.8  517.43  5630.8  517.57
  5661.5  518.54  5680.8  518.53  5692.2  519.36  5702.5  519.08  5729.9  519.46
  5735.0  520.18  5743.4  520.42  5763.9  520.13  5773.9  520.34  5779.1  520.91
  5815.0  520.98  5845.7  521.82  5872.2  521.55  5877.3  521.93  5899.2  522.23
#Mann=3,-1,0
  4411.2    0.05       0  4980.2   0.035       0  4986.2    0.05       0
Bank Sta=4980.2,4986.2
Exp/Cntr=0.3,0.1

Type RM Length L Ch R = 1,14712,887,887,887
BEGIN DESCRIPTION:
Mapping XS 8312a772
END DESCRIPTION:
XS GIS Cut Line= 4
      2057647.28     13507116.53      2057100.00     13507150.00
      2056550.07     13507375.20      2056481.31     13507760.25
#Sta/Elev= 30
  4341.5  518.03  4413.9  517.95  4554.2  516.92  4722.7  516.35  4874.8  514.72
  4967.2  514.14  5020.6  513.94  5122.0  514.54  5143.7  514.27  5151.4  514.68
  5175.4  514.74  5204.8  514.27  5234.2  514.36  5248.8  513.94  5249.3  513.14
  5254.3  513.14  5254.8  513.94  5287.6  514.22  5305.8  513.97  5457.1  515.65
  5484.1  515.62  5540.5  516.57  5653.3  517.05  5666.7  517.49  5707.1  517.84
  5727.6  518.78  5771.1  519.28  5778.4  519.94  5819.1  521.27  5875.2  521.96
#Mann=3,-1,0
  4341.5    0.05       0  5248.8   0.035       0  5254.8    0.05       0
Bank Sta=5248.8,5254.8
Exp/Cntr=0.3,0.1

Type RM Length L Ch R = 1,13825,651,651,651
BEGIN DESCRIPTION:
Mapping XS c953c269
END DESCRIPTION:
XS GIS Cut Line= 4
      2057043.76     13506513.12      2056614.07     13506429.78
      2056012.51     13507099.05      2056030.74     13507268.29
#Sta/Elev= 30
  4188.4  512.81  4533.5  510.30  4625.5  510.03  4692.8  509.38  4784.8  509.00
  4855.8  509.56  4905.1  509.26  4969.3  509.70  4982.8  510.36  4994.0  507.71
  4994.5  506.91  4999.6  506.91  5000.1  507.71  5004.5  508.24  5011.2  509.83
  5018.7  510.39  5160.0  510.48  5181.7  510.98  5216.8  511.10  5231.0  510.79
  5245.2  511.33  5273.6  510.80  5294.5  511.46  5330.4  511.45  5394.0  512.60
  5422.4  512.79  5443.3  512.48  5450.8  512.89  5582.3  513.90  5696.2  516.21
#Mann=3,-1,0
  4188.4    0.05       0  4994.0    0.03       0  5000.1    0.05       0
Bank Sta=4994,5000.1
Exp/Cntr=0.3,0.1

Type RM Length L Ch R = 1,13174,828,828,828
BEGIN DESCRIPTION:
Mapping XS a09b785e
END DESCRIPTION:
XS GIS Cut Line= 4
      2057179.21     13505859.46      2056371.88     13506023.53
      2055319.80     13506705.82      2055400.26     13506947.19
#Sta/Elev= 30
  3805.4  510.86  4413.7  508.54  4729.9  508.11  4787.3  507.29  4844.6  507.70
  4902.0  506.91  4974.5  508.31  4983.1  508.07  4986.6  506.03  4987.1  505.23
  4992.3  505.23  4992.8  506.03  5004.8  507.34  5018.8  507.69  5083.3  507.40
  5113.6  507.85  5171.0  507.73  5293.0  508.74  5306.8  508.31  5581.7  510.46
  5654.2  511.26  5741.9  513.84  5829.3  514.33  5883.1  516.23  6012.2  515.77
  6043.8  516.42  6070.2  517.88  6093.1  518.57  6133.4  518.38  6137.6  517.96
#Mann=3,-1,0
  3805.4    0.05       0  4986.6    0.03       0  4992.8    0.05       0
Bank Sta=4986.6,4992.8
Exp/Cntr=0.3,0.1

Type RM Length L Ch R = 1,12346,626,626,626
BEGIN DESCRIPTION:
Mapping XS 55e96035
END DESCRIPTION:
XS GIS Cut Line= 4
      2056929.20     13505539.17      2056637.51     13505419.37
      2055548.97     13505549.57      2055275.51     13505763.13
#Sta/Elev= 30
  3864.4  509.71  4017.5  508.31  4273.6  507.54  4413.9  506.75  4554.9  506.92
  4685.5  505.93  4746.3  506.38  4756.3  506.30  4786.5  505.05  4836.9  504.80
  4855.3  504.15  4967.8  503.57  4984.8  503.12  4985.3  502.32  4990.6  502.32
  4991.1  503.12  4998.0  503.42  5018.2  503.19  5048.4  503.90  5107.5  504.23
  5112.5  504.50  5275.5  506.04  5346.3  508.05  5468.4  510.58  5489.2  511.22
  5496.8  511.83  5524.5  512.20  5567.9  513.64  5603.1  514.07  5623.0  514.72
#Mann=3,-1,0
  3864.4    0.05       0  4984.8    0.03       0  4991.1    0.05       0
Bank Sta=4984.8,4991.1
Exp/Cntr=0.3,0.1

Type RM Length L Ch R = 1,11720,864,864,864
BEGIN DESCRIPTION:
Mapping XS 80da943f
END DESCRIPTION:
XS GIS Cut Line= 4
      2056629.73     13505096.47      2056455.22     13504984.47
      2055364.07     13504934.99      2054913.58     13505117.27
#Sta/Elev= 30
  4083.1  510.43  4195.7  509.58  4246.2  509.82  4300.7  509.12  4330.7  507.73
  4440.8  504.83  4550.9  502.77  4612.9  502.21  4661.1  502.77  4751.1  502.23
  4851.2  502.36  4921.3  501.30  4931.3  501.34  4941.3  502.07  4988.1  501.17
  4988.6  500.37  4994.1  500.37  4994.6  501.17  5048.9  501.75  5201.6  502.09
  5274.4  502.72  5301.7  503.53  5341.8  503.45  5421.1  505.01  5450.6  504.94
  5611.5  507.35  5635.6  508.10  5718.8  508.46  5820.6  510.63  5868.7  510.96
#Mann=3,-1,0
  4083.1    0.05       0  4988.1    0.03       0  4994.6    0.05       0
Bank Sta=4988.1,4994.6
Exp/Cntr=0.3,0.1

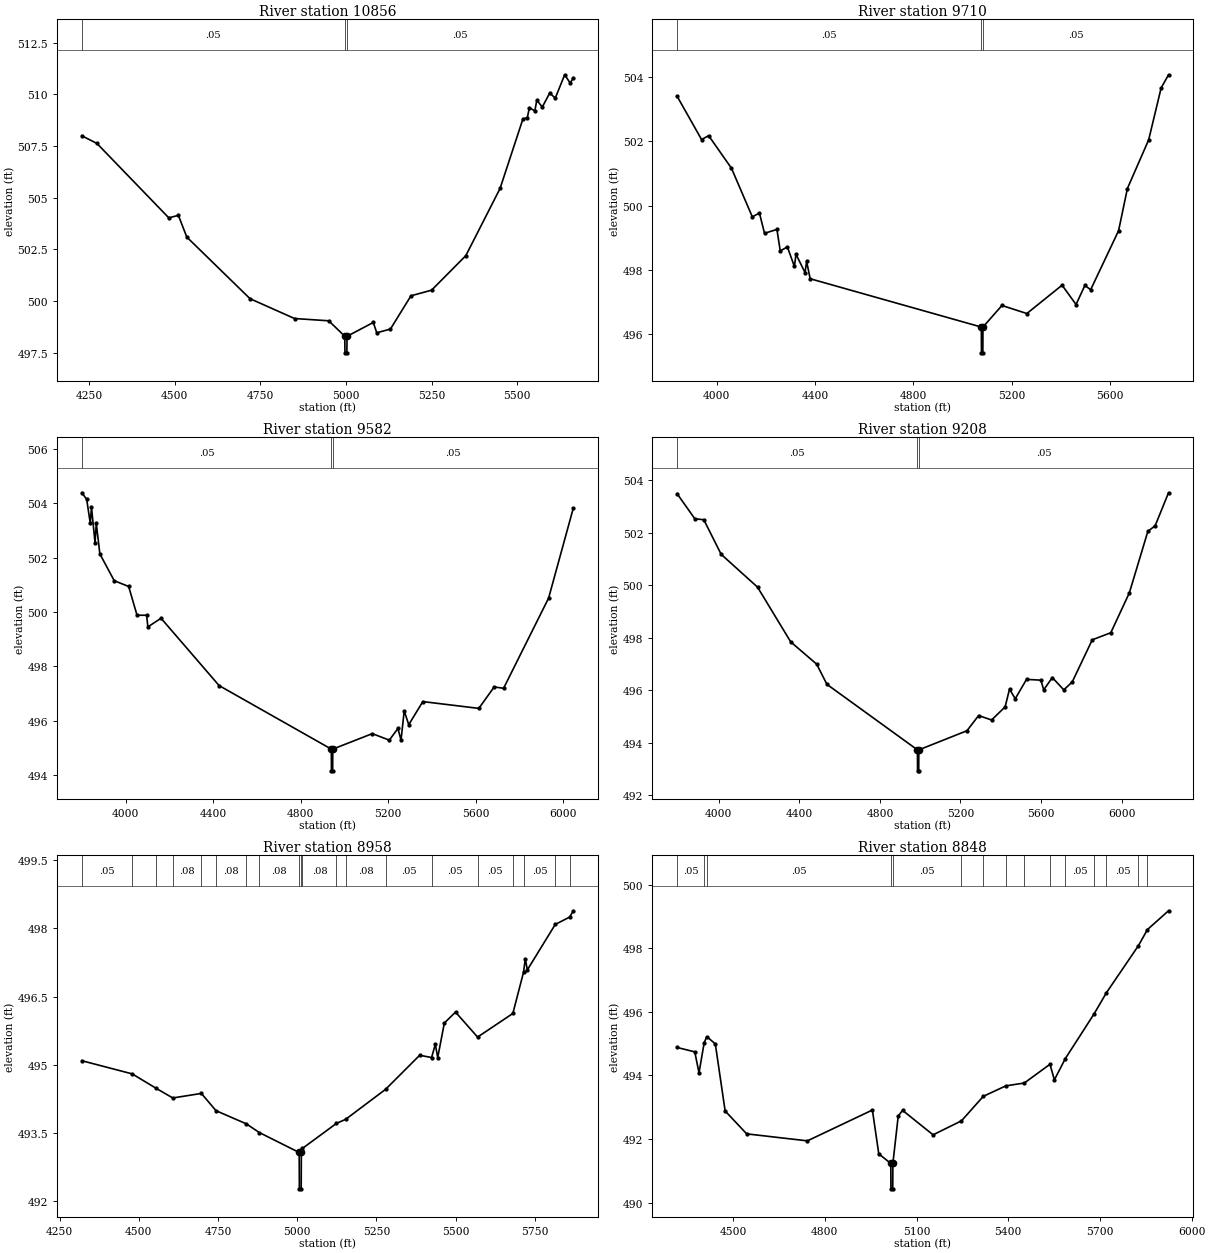
Type RM Length L Ch R = 1,10856,1146,1146,1146
BEGIN DESCRIPTION:
Mapping XS 062eeb85
END DESCRIPTION:
XS GIS Cut Line= 4
      2056564.58     13504273.52      2056288.55     13504138.12
      2055306.78     13504112.07      2055236.45     13504239.71
#Sta/Elev= 30
  4228.3  508.00  4272.4  507.63  4482.3  504.03  4510.3  504.15  4534.9  503.10
  4719.4  500.12  4849.4  499.16  4949.4  499.05  4996.2  498.30  4996.7  497.50
  5002.3  497.50  5002.8  498.30  5079.5  498.97  5089.5  498.47  5129.5  498.65
  5189.5  500.26  5249.6  500.53  5349.6  502.20  5449.6  505.45  5516.3  508.81
  5529.4  508.88  5535.1  509.36  5551.2  509.20  5556.9  509.72  5573.0  509.39
  5594.7  510.07  5610.8  509.82  5638.3  510.95  5654.4  510.55  5663.6  510.80
#Mann=3,-1,0
  4228.3    0.05       0  4996.2    0.03       0  5002.8    0.05       0
Bank Sta=4996.2,5002.8
Exp/Cntr=0.3,0.1

Type RM Length L Ch R = 1,9710,128,128,128
BEGIN DESCRIPTION:
Mapping XS e13c2054
END DESCRIPTION:
XS GIS Cut Line= 4
      2056629.10     13503912.32      2055946.80     13503060.75
      2055827.01     13502967.00      2055204.63     13503396.67
#Sta/Elev= 30
  3838.7  503.40  3938.7  502.05  3967.5  502.17  4060.3  501.16  4145.2  499.65
  4174.0  499.77  4194.8  499.14  4245.3  499.26  4258.8  498.59  4287.6  498.72
  4316.4  498.11  4322.8  498.49  4359.6  497.92  4366.0  498.27  4380.4  497.73
  5076.8  496.23  5077.3  495.43  5082.9  495.43  5083.4  496.23  5160.6  496.90
  5262.0  496.65  5405.3  497.53  5462.1  496.93  5497.9  497.52  5521.6  497.39
  5635.1  499.22  5671.0  500.53  5757.5  502.04  5808.2  503.65  5838.3  504.06
#Mann=3,-1,0
  3838.7    0.05       0  5076.8    0.03       0  5083.4    0.05       0
Bank Sta=5076.8,5083.4
Exp/Cntr=0.3,0.1

Type RM Length L Ch R = 1,9582,374,374,374
BEGIN DESCRIPTION:
Mapping XS 436273cc
END DESCRIPTION:
XS GIS Cut Line= 4
      2056709.80     13503881.02      2056428.57     13503355.02
      2055824.41     13502782.10      2055196.81     13503305.53
#Sta/Elev= 30
  3800.3  504.39  3822.6  504.15  3838.9  503.27  3844.6  503.85  3860.8  502.55
  3866.5  503.26  3882.8  502.14  3948.6  501.15  4014.4  500.94  4052.7  499.88
  4096.5  499.88  4102.2  499.45  4162.4  499.77  4427.7  497.29  4940.6  494.95
  4941.1  494.15  4946.7  494.15  4947.2  494.95  5127.9  495.52  5205.6  495.28
  5244.9  495.71  5259.2  495.28  5273.6  496.36  5294.4  495.85  5358.8  496.70
  5614.6  496.45  5684.9  497.24  5727.8  497.19  5933.5  500.51  6046.6  503.83
#Mann=3,-1,0
  3800.3    0.05       0  4940.6    0.03       0  4947.2    0.05       0
Bank Sta=4940.6,4947.2
Exp/Cntr=0.3,0.1

Type RM Length L Ch R = 1,9208,250,250,250
BEGIN DESCRIPTION:
Mapping XS 141841f9
END DESCRIPTION:
XS GIS Cut Line= 5
      2056957.20     13503396.66      2056530.13     13502766.48
      2056418.16     13502612.83      2055813.99     13502698.77
      2055155.12     13503279.51
#Sta/Elev= 30
  3792.8  503.50  3881.2  502.54  3926.0  502.50  4012.2  501.18  4192.6  499.93
  4357.4  497.84  4486.2  496.99  4537.1  496.22  4986.4  493.72  4986.9  492.92
  4992.7  492.92  4993.2  493.72  5232.2  494.45  5290.0  495.03  5354.4  494.86
  5421.6  495.36  5443.4  496.04  5471.8  495.67  5527.8  496.41  5599.0  496.38
  5613.2  496.01  5655.9  496.48  5712.8  496.01  5754.6  496.31  5854.2  497.92
  5946.2  498.19  6038.2  499.71  6130.2  502.06  6166.2  502.27  6232.7  503.53
#Mann=3,-1,0
  3792.8    0.05       0  4986.4    0.03       0  4993.2    0.05       0
Bank Sta=4986.4,4993.2
Exp/Cntr=0.3,0.1

Type RM Length L Ch R = 1,8958,110,110,110
BEGIN DESCRIPTION:
Mapping XS 09aadf99
END DESCRIPTION:
XS GIS Cut Line= 5
      2056595.34     13502118.23      2056415.61     13502097.39
      2055897.38     13502566.14      2055840.09     13502602.60
      2055384.32     13502998.46
#Sta/Elev= 30
  4320.0  495.09  4479.1  494.80  4555.2  494.48  4607.2  494.27  4697.3  494.37
  4743.6  493.99  4839.4  493.70  4880.0  493.51  5006.1  493.07  5006.6  492.27
  5012.4  492.27  5012.9  493.07  5016.4  493.16  5123.6  493.71  5152.8  493.80
  5278.7  494.46  5386.3  495.21  5423.9  495.16  5435.7  495.45  5443.3  495.16
  5464.2  495.92  5499.5  496.16  5569.1  495.61  5680.4  496.13  5714.2  497.04
  5719.6  497.33  5726.2  497.09  5814.3  498.09  5859.4  498.25  5871.3  498.39
#Mann=20,-1,0
  4320.0    0.05       0  4479.1    0.08       0  4555.2    0.05       0
  4607.2    0.08       0  4697.3    0.05       0  4743.6    0.08       0
  4839.4    0.05       0  4880.0    0.08       0  5006.1    0.03       0
  5012.9    0.05       0  5016.4    0.08       0  5123.6    0.05       0
  5152.8    0.08       0  5278.7    0.05       0  5423.9    0.05       0
  5569.1    0.05       0  5680.4    0.08       0  5714.2    0.05       0
  5814.3    0.08       0  5859.4    0.05       0
Bank Sta=5006.1,5012.9
Exp/Cntr=0.3,0.1

Type RM Length L Ch R = 1,8848,130,130,130
BEGIN DESCRIPTION:
Mapping XS 2f80335a
END DESCRIPTION:
XS GIS Cut Line= 4
      2056522.36     13502071.35      2056363.52     13502011.46
      2055735.92     13502555.73      2055278.79     13502955.71
#Sta/Elev= 30
  4316.4  494.88  4374.6  494.74  4388.4  494.08  4405.4  495.03  4414.0  495.22
  4441.8  494.99  4473.9  492.88  4544.4  492.16  4742.9  491.94  4955.6  492.91
  4976.5  491.53  5015.8  491.23  5016.3  490.43  5022.1  490.43  5022.6  491.23
  5040.1  492.72  5054.3  492.90  5154.1  492.13  5247.0  492.57  5318.3  493.34
  5391.9  493.67  5452.6  493.76  5536.5  494.35  5550.9  493.86  5586.8  494.53
  5681.1  495.94  5721.1  496.60  5825.7  498.08  5855.4  498.59  5924.3  499.18
#Mann=15,-1,0
  4316.4    0.05       0  4405.4    0.08       0  4414.0    0.05       0
  5015.8    0.04       0  5022.6    0.05       0  5247.0    0.08       0
  5318.3    0.05       0  5391.9    0.08       0  5452.6    0.05       0
  5536.5    0.08       0  5586.8    0.05       0  5681.1    0.08       0
  5721.1    0.05       0  5825.7    0.08       0  5855.4    0.05       0
Bank Sta=5015.8,5022.6
Exp/Cntr=0.3,0.1

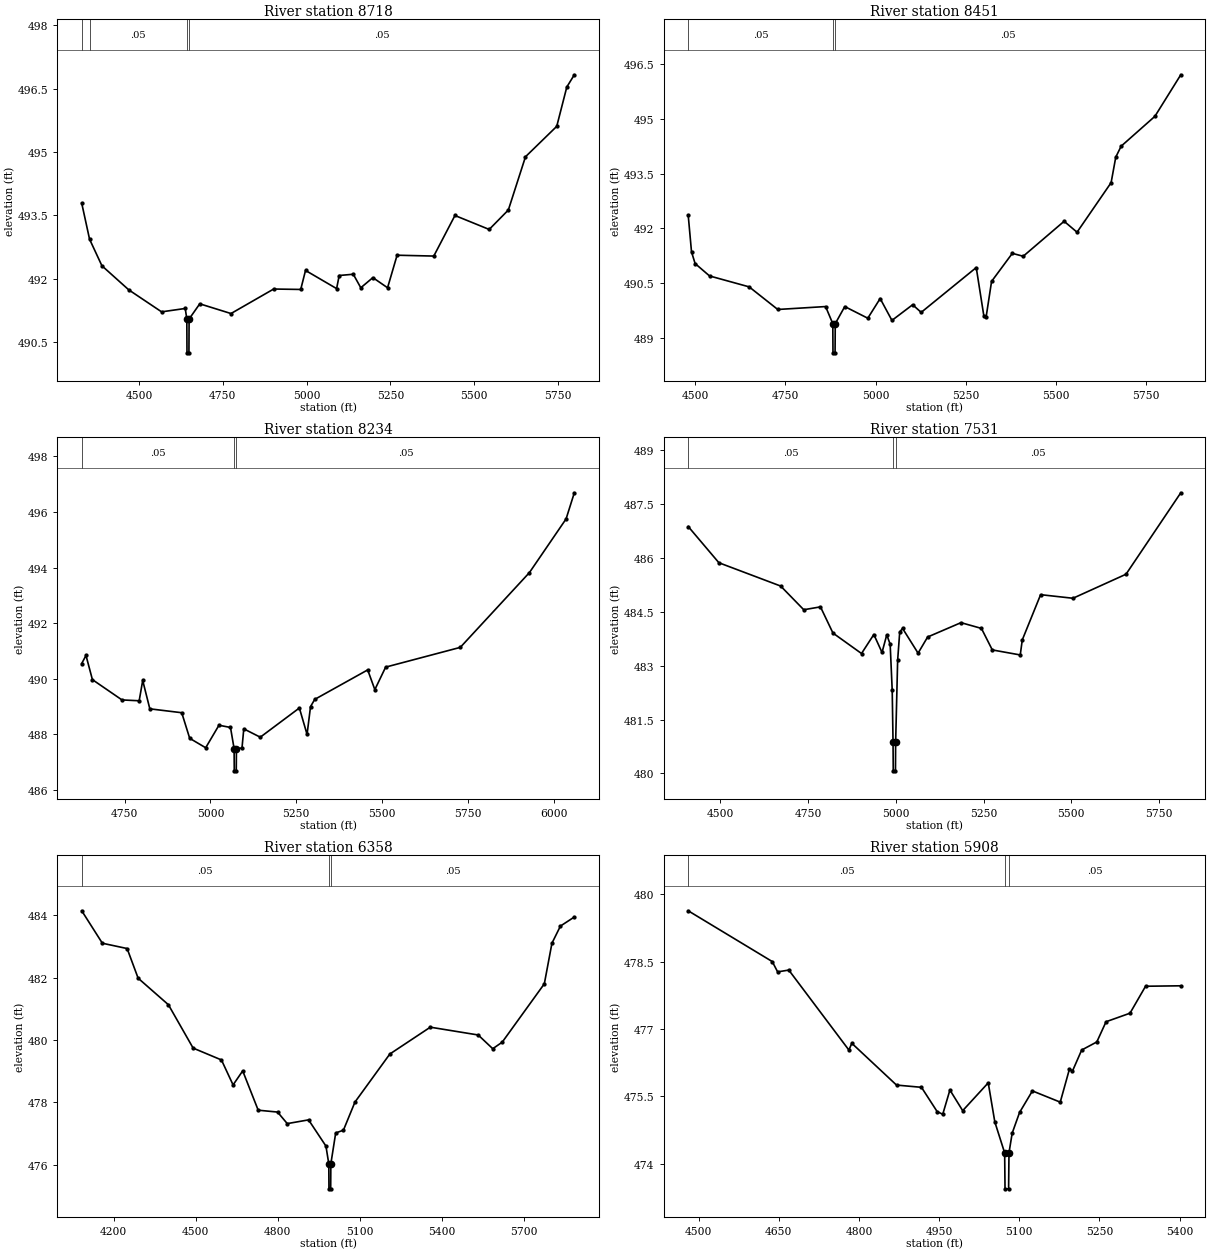
Type RM Length L Ch R = 1,8718,267,267,267
BEGIN DESCRIPTION:
Mapping XS 1d188e95
END DESCRIPTION:
XS GIS Cut Line= 6
      2056465.13     13501951.56      2056285.40     13501943.75
      2056004.15     13502165.10      2055920.82     13502217.19
      2055722.90     13502498.44      2055316.64     13502769.27
#Sta/Elev= 30
  4329.6  493.79  4352.9  492.94  4389.8  492.31  4469.9  491.74  4567.7  491.22
  4638.2  491.30  4642.9  491.05  4643.4  490.25  4649.2  490.25  4649.7  491.05
  4681.5  491.41  4774.6  491.18  4901.8  491.76  4982.5  491.75  4996.8  492.20
  5089.5  491.77  5097.2  492.08  5139.2  492.11  5161.6  491.79  5197.6  492.03
  5241.4  491.79  5269.8  492.56  5379.2  492.54  5442.3  493.50  5544.4  493.17
  5601.5  493.63  5652.6  494.89  5745.8  495.61  5775.8  496.54  5798.2  496.83
#Mann=4,-1,0
  4329.6    0.08       0  4352.9    0.05       0  4642.9    0.03       0
  4649.7    0.05       0
Bank Sta=4642.9,4649.7
Exp/Cntr=0.3,0.1

Type RM Length L Ch R = 1,8451,217,217,217
BEGIN DESCRIPTION:
Mapping XS 2bbc40d0
END DESCRIPTION:
XS GIS Cut Line= 5
      2056254.20     13501925.52      2056001.54     13501920.31
      2055696.86     13502053.12      2055519.77     13502334.37
      2055264.59     13502704.13
#Sta/Elev= 30
  4480.1  492.36  4489.3  491.35  4499.3  491.03  4539.3  490.69  4649.3  490.39
  4728.6  489.77  4861.3  489.85  4881.3  489.38  4881.8  488.58  4887.6  488.58
  4888.1  489.38  4914.5  489.85  4978.4  489.53  5012.7  490.07  5045.4  489.47
  5102.8  489.90  5126.5  489.69  5279.3  490.92  5300.6  489.58  5306.5  489.55
  5321.8  490.54  5379.4  491.31  5409.6  491.23  5523.1  492.19  5559.0  491.89
  5653.5  493.25  5666.4  493.95  5681.3  494.25  5775.0  495.07  5846.8  496.21
#Mann=3,-1,0
  4480.1    0.05       0  4881.3    0.03       0  4888.1    0.05       0
Bank Sta=4881.3,4888.1
Exp/Cntr=0.3,0.1

Type RM Length L Ch R = 1,8234,703,703,703
BEGIN DESCRIPTION:
Mapping XS 76f1209d
END DESCRIPTION:
XS GIS Cut Line= 6
      2056136.98     13501878.65      2055827.07     13501797.91
      2055603.11     13501863.02      2055491.13     13502084.37
      2055436.44     13502282.29      2055186.88     13502630.63
#Sta/Elev= 30
  4625.0  490.55  4637.4  490.84  4656.1  489.97  4742.3  489.24  4792.4  489.21
  4802.7  489.94  4823.4  488.92  4916.4  488.78  4939.6  487.86  4986.2  487.52
  5024.9  488.33  5058.5  488.25  5069.0  487.49  5069.5  486.69  5075.3  486.69
  5075.8  487.49  5092.0  487.51  5097.2  488.20  5145.3  487.90  5259.2  488.95
  5281.6  488.00  5291.7  489.00  5304.0  489.26  5458.3  490.32  5479.1  489.61
  5510.6  490.42  5728.1  491.13  5929.6  493.82  6036.4  495.75  6060.4  496.69
#Mann=3,-1,0
  4625.0    0.05       0  5069.0    0.03       0  5075.8    0.05       0
Bank Sta=5069,5075.8
Exp/Cntr=0.3,0.1

Type RM Length L Ch R = 1,7531,1173,1173,1173
BEGIN DESCRIPTION:
Mapping XS 832d6af1
END DESCRIPTION:
XS GIS Cut Line= 4
      2055897.94     13501283.95      2055585.43     13501179.78
      2055017.72     13501523.53      2054779.23     13501856.80
#Sta/Elev= 30
  4408.9  486.88  4496.3  485.87  4672.3  485.22  4738.0  484.56  4785.6  484.64
  4821.2  483.91  4902.5  483.34  4937.6  483.87  4960.9  483.37  4974.4  483.86
  4984.1  483.60  4989.9  482.32  4992.3  480.87  4992.9  480.07  4999.2  480.07
  4999.7  480.87  5005.4  483.15  5011.3  483.94  5019.4  484.04  5063.6  483.35
  5090.8  483.80  5185.8  484.20  5244.0  484.04  5275.0  483.44  5354.6  483.30
  5360.4  483.72  5412.6  484.98  5504.7  484.88  5655.8  485.55  5811.8  487.82
#Mann=3,-1,0
  4408.9    0.05       0  4992.3    0.03       0  4999.7    0.05       0
Bank Sta=4992.3,4999.7
Exp/Cntr=0.3,0.1

Type RM Length L Ch R = 1,6358,450,450,450
BEGIN DESCRIPTION:
Mapping XS 3358d120
END DESCRIPTION:
XS GIS Cut Line= 4
      2055349.97     13500250.00      2054871.88     13500299.57
      2054379.70     13500763.12      2054210.71     13501383.97
#Sta/Elev= 30
  4083.5  484.14  4158.9  483.10  4249.4  482.93  4289.6  481.98  4400.2  481.13
  4490.6  479.74  4594.1  479.36  4636.6  478.56  4671.8  479.01  4728.4  477.75
  4799.2  477.69  4834.6  477.32  4912.5  477.44  4976.0  476.60  4986.4  476.03
  4987.0  475.23  4993.3  475.23  4993.9  476.03  5011.6  477.02  5039.9  477.11
  5082.0  478.01  5209.5  479.55  5357.4  480.41  5532.4  480.16  5585.6  479.72
  5620.2  479.93  5774.1  481.80  5801.9  483.10  5832.9  483.65  5883.7  483.94
#Mann=3,-1,0
  4083.5    0.05       0  4986.4    0.03       0  4993.9    0.05       0
Bank Sta=4986.4,4993.9
Exp/Cntr=0.3,0.1

Type RM Length L Ch R = 1,5908,78,78,78
BEGIN DESCRIPTION:
Mapping XS 7c7f1d52
END DESCRIPTION:
XS GIS Cut Line= 4
      2054890.88     13500153.85      2054658.67     13500123.47
      2054244.17     13500294.91      2054142.61     13500510.99
#Sta/Elev= 30
  4480.6  479.63  4637.8  478.50  4647.9  478.27  4668.8  478.31  4781.2  476.53
  4786.7  476.68  4870.3  475.75  4917.0  475.70  4946.3  475.16  4956.8  475.10
  4970.2  475.64  4994.1  475.18  5041.9  475.80  5054.2  474.93  5072.6  474.24
  5073.3  473.44  5080.0  473.44  5080.7  474.24  5086.7  474.68  5100.5  475.14
  5124.5  475.62  5176.6  475.37  5193.9  476.11  5199.4  476.06  5216.7  476.53
  5245.0  476.71  5262.3  477.16  5307.1  477.35  5336.2  477.95  5402.1  477.96
#Mann=3,-1,0
  4480.6    0.05       0  5072.6    0.03       0  5080.7    0.05       0
Bank Sta=5072.6,5080.7
Exp/Cntr=0.3,0.1

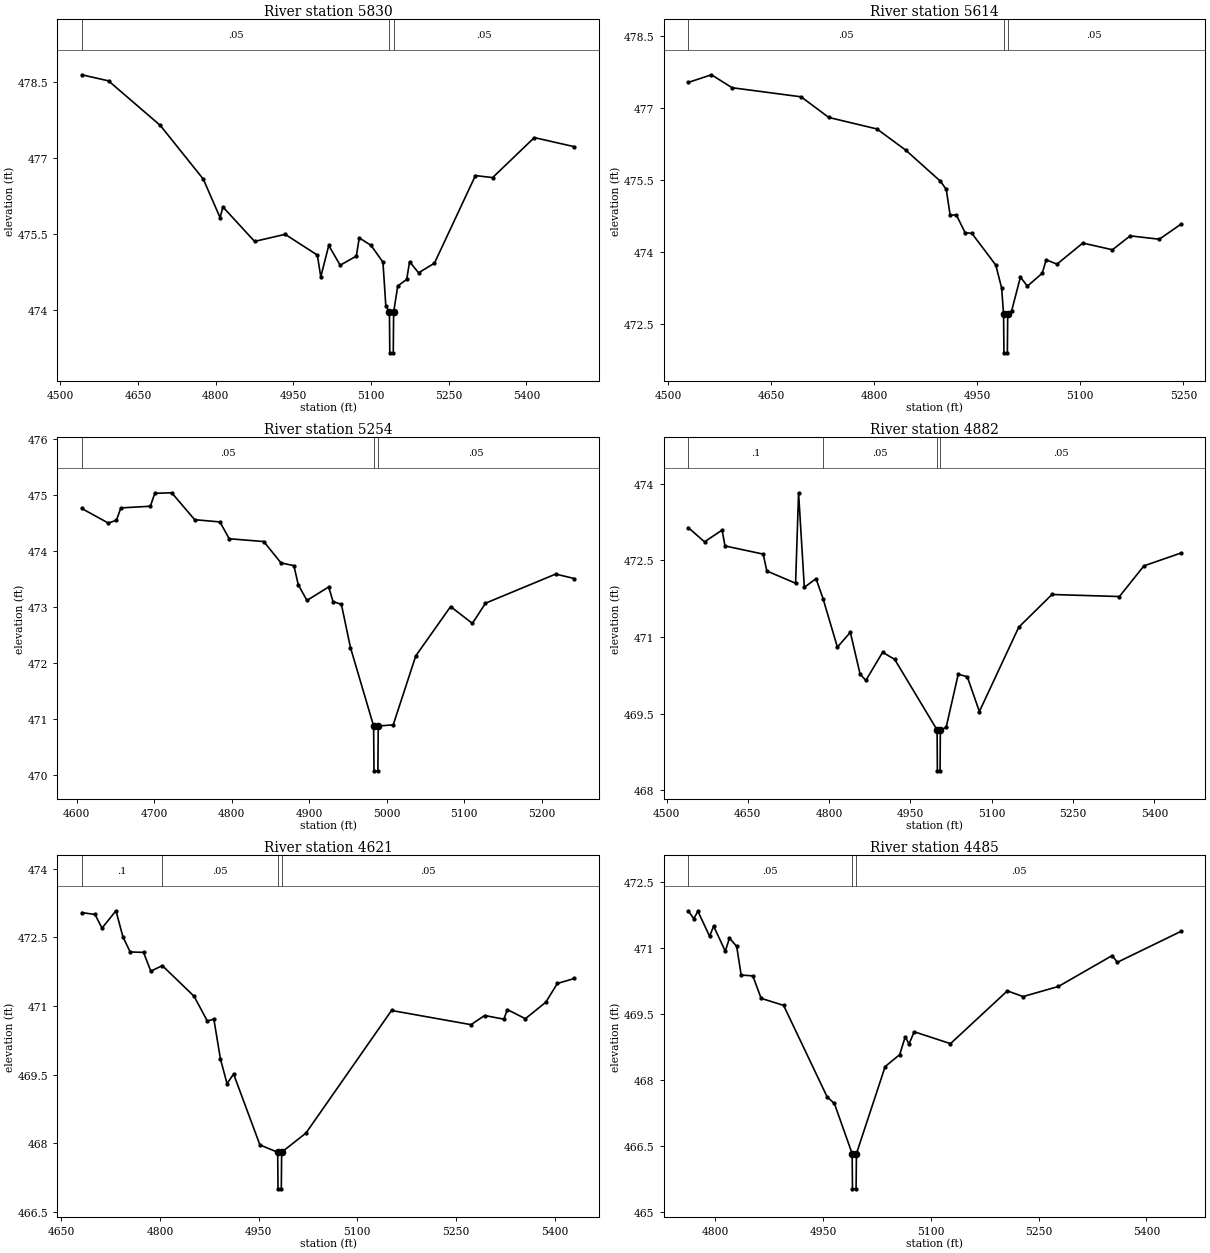
Type RM Length L Ch R = 1,5830,216,216,216
BEGIN DESCRIPTION:
Mapping XS 263bd90b
END DESCRIPTION:
XS GIS Cut Line= 4
      2054786.68     13500064.88      2054584.88     13500060.54
      2054153.03     13500260.19      2054035.82     13500507.62
#Sta/Elev= 30
  4541.3  478.64  4593.0  478.52  4693.0  477.64  4776.1  476.58  4808.5  475.82
  4814.0  476.03  4875.2  475.35  4934.2  475.49  4996.4  475.08  5003.0  474.65
  5018.4  475.27  5040.5  474.88  5071.7  475.06  5077.3  475.42  5100.2  475.27
  5123.1  474.94  5128.6  474.08  5135.6  473.95  5136.3  473.15  5143.0  473.15
  5143.7  473.95  5151.6  474.47  5169.0  474.60  5174.5  474.95  5191.9  474.73
  5222.5  474.92  5301.7  476.65  5334.9  476.61  5415.4  477.40  5492.7  477.22
#Mann=3,-1,0
  4541.3    0.05       0  5135.6    0.03       0  5143.7    0.05       0
Bank Sta=5135.6,5143.7
Exp/Cntr=0.3,0.1

Type RM Length L Ch R = 1,5614,360,360,360
BEGIN DESCRIPTION:
Mapping XS 7f5c6b65
END DESCRIPTION:
XS GIS Cut Line= 4
      2054658.71     13499932.50      2054385.23     13499908.63
      2054081.41     13500082.24      2054148.71     13500145.20
#Sta/Elev= 30
  4529.5  477.53  4563.3  477.69  4593.4  477.42  4693.8  477.23  4734.0  476.80
  4804.0  476.56  4845.8  476.12  4896.4  475.47  4904.9  475.30  4910.6  474.76
  4919.5  474.77  4932.2  474.40  4942.3  474.38  4977.0  473.72  4985.5  473.24
  4988.3  472.69  4988.8  471.89  4993.8  471.89  4994.3  472.69  5000.1  472.77
  5012.8  473.47  5022.9  473.28  5044.5  473.55  5050.3  473.83  5066.1  473.74
  5103.5  474.18  5146.7  474.04  5172.5  474.33  5214.8  474.26  5246.1  474.57
#Mann=3,-1,0
  4529.5    0.05       0  4988.3    0.03       0  4994.3    0.05       0
Bank Sta=4988.3,4994.3
Exp/Cntr=0.3,0.1

Type RM Length L Ch R = 1,5254,372,372,372
BEGIN DESCRIPTION:
Mapping XS 97d44a49
END DESCRIPTION:
XS GIS Cut Line= 4
      2054124.84     13499546.20      2054016.31     13499604.81
      2053836.19     13499971.56      2053877.40     13500067.00
#Sta/Elev= 30
  4606.4  474.76  4640.7  474.50  4651.2  474.55  4656.9  474.77  4695.0  474.80
  4700.7  475.03  4722.6  475.04  4752.2  474.56  4784.8  474.52  4796.8  474.22
  4841.4  474.17  4863.6  473.79  4880.3  473.74  4885.9  473.40  4897.1  473.12
  4925.2  473.36  4930.8  473.10  4941.6  473.05  4953.3  472.28  4983.2  470.88
  4983.7  470.08  4988.7  470.08  4989.2  470.88  5008.5  470.90  5037.6  472.13
  5082.6  473.01  5110.7  472.71  5127.6  473.07  5218.3  473.59  5242.3  473.51
#Mann=3,-1,0
  4606.4    0.05       0  4983.2    0.03       0  4989.2    0.05       0
Bank Sta=4983.2,4989.2
Exp/Cntr=0.3,0.1

Type RM Length L Ch R = 1,4882,261,261,261
BEGIN DESCRIPTION:
Mapping XS 87a2002f
END DESCRIPTION:
XS GIS Cut Line= 4
      2054022.83     13499314.00      2053729.85     13499435.54
      2053551.90     13499789.27      2053627.84     13499969.35
#Sta/Elev= 30
  4540.0  473.14  4570.1  472.86  4602.5  473.09  4607.9  472.78  4678.4  472.62
  4685.0  472.29  4738.1  472.05  4743.6  473.82  4754.2  471.97  4775.8  472.14
  4788.7  471.75  4815.2  470.80  4839.1  471.09  4857.1  470.27  4867.8  470.15
  4898.6  470.70  4920.9  470.56  4999.1  469.18  4999.6  468.38  5004.6  468.38
  5005.1  469.18  5015.8  469.23  5038.1  470.27  5054.8  470.22  5077.1  469.54
  5149.7  471.19  5211.0  471.83  5335.4  471.79  5380.6  472.39  5448.6  472.64
#Mann=4,-1,0
  4540.0     0.1       0  4788.7    0.05       0  4999.1    0.03       0
  5005.1    0.05       0
Bank Sta=4999.1,5005.1
Exp/Cntr=0.3,0.1

Type RM Length L Ch R = 1,4621,136,136,136
BEGIN DESCRIPTION:
Mapping XS 7409d5df
END DESCRIPTION:
XS GIS Cut Line= 4
      2053554.04     13499227.21      2053436.88     13499268.44
      2053430.37     13499711.14      2053475.95     13499886.97
#Sta/Elev= 30
  4681.1  473.04  4701.3  473.00  4711.9  472.70  4733.1  473.08  4743.7  472.51
  4754.7  472.18  4775.0  472.17  4786.1  471.76  4803.6  471.88  4851.9  471.21
  4871.9  470.67  4881.9  470.71  4891.9  469.84  4901.9  469.30  4911.9  469.51
  4951.9  467.96  4978.9  467.80  4979.4  467.00  4984.4  467.00  4984.9  467.80
  5021.9  468.22  5151.9  470.90  5272.7  470.59  5293.4  470.79  5322.7  470.71
  5327.9  470.92  5355.3  470.72  5386.3  471.08  5403.9  471.49  5429.7  471.60
#Mann=4,-1,0
  4681.1     0.1       0  4803.6    0.05       0  4978.9    0.03       0
  4984.9    0.05       0
Bank Sta=4978.9,4984.9
Exp/Cntr=0.3,0.1

Type RM Length L Ch R = 1,4485,290,290,290
BEGIN DESCRIPTION:
Mapping XS e1f711ca
END DESCRIPTION:
XS GIS Cut Line= 4
      2053334.89     13499255.40      2053282.80     13499353.07
      2053343.56     13499782.76      2053428.19     13499895.59
#Sta/Elev= 30
  4762.1  471.85  4769.9  471.67  4775.6  471.84  4791.9  471.27  4797.5  471.50
  4813.8  470.93  4819.5  471.23  4829.6  471.04  4835.8  470.39  4852.1  470.37
  4863.6  469.86  4894.9  469.70  4955.5  467.62  4965.6  467.47  4990.3  466.33
  4990.8  465.53  4995.8  465.53  4996.3  466.33  5036.3  468.31  5056.5  468.58
  5064.3  468.99  5069.4  468.82  5076.7  469.10  5127.2  468.83  5206.4  470.03
  5228.2  469.90  5277.5  470.13  5352.1  470.83  5359.6  470.68  5447.8  471.38
#Mann=3,-1,0
  4762.1    0.05       0  4990.3    0.03       0  4996.3    0.05       0
Bank Sta=4990.3,4996.3
Exp/Cntr=0.3,0.1