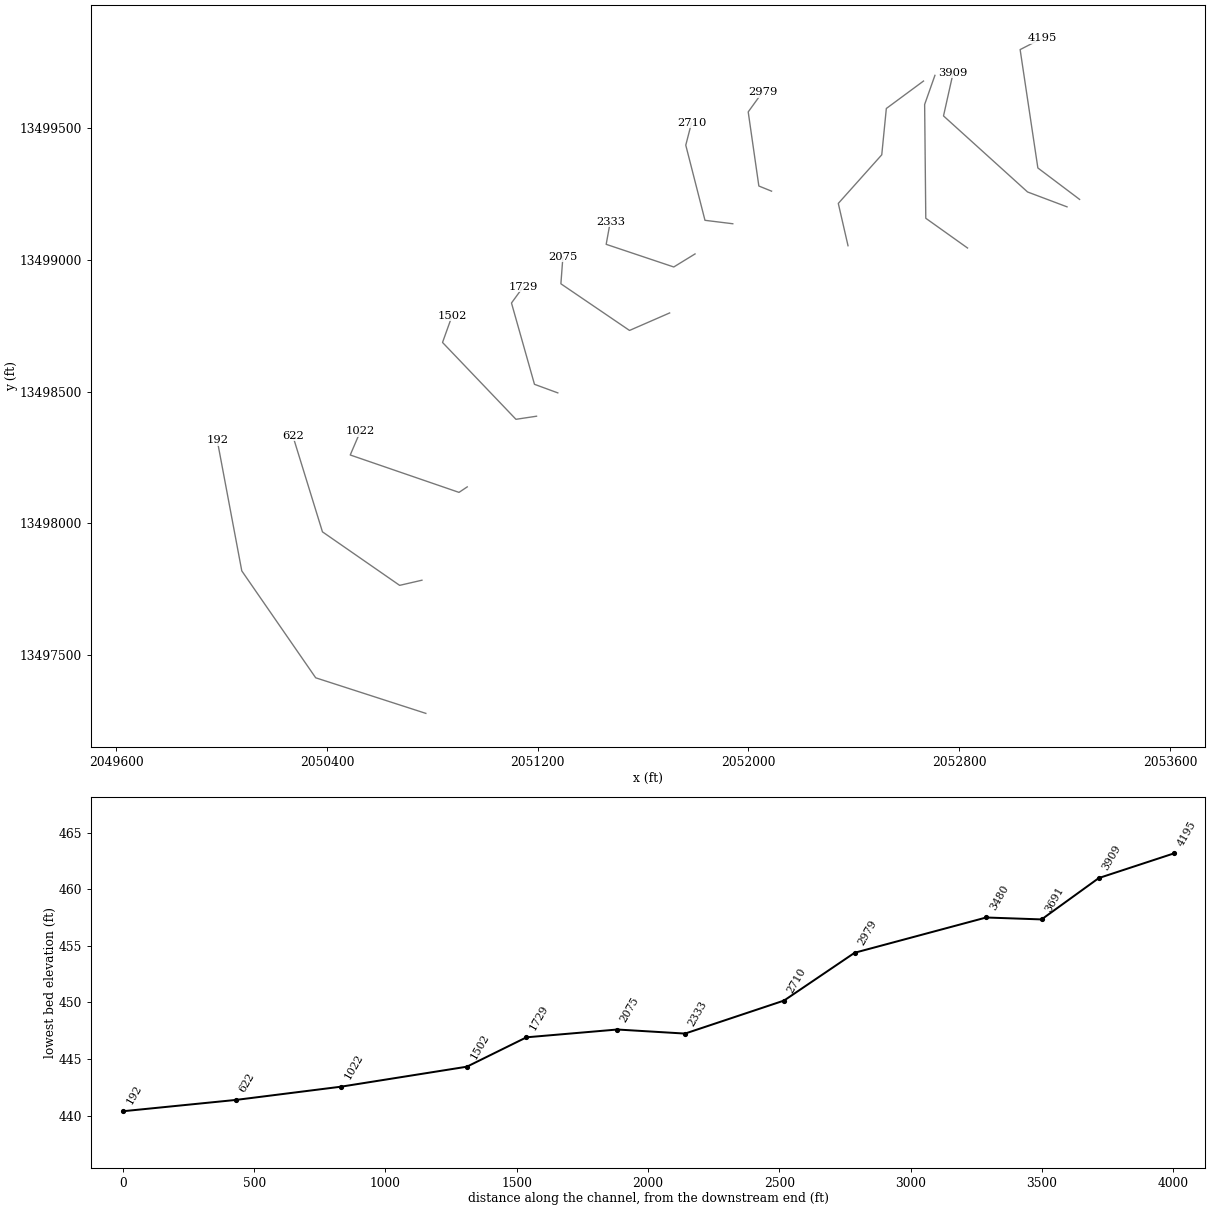
HEC-RAS study UNT 167 in Lagunillas Cr Wtrshd.prj: UNT 167 in Lagunillas Cr Wtrshd Base Level Engineering

--- UNT 167 in Lagunillas Cr Wtrshd.g01 (geometry) --- (continued)

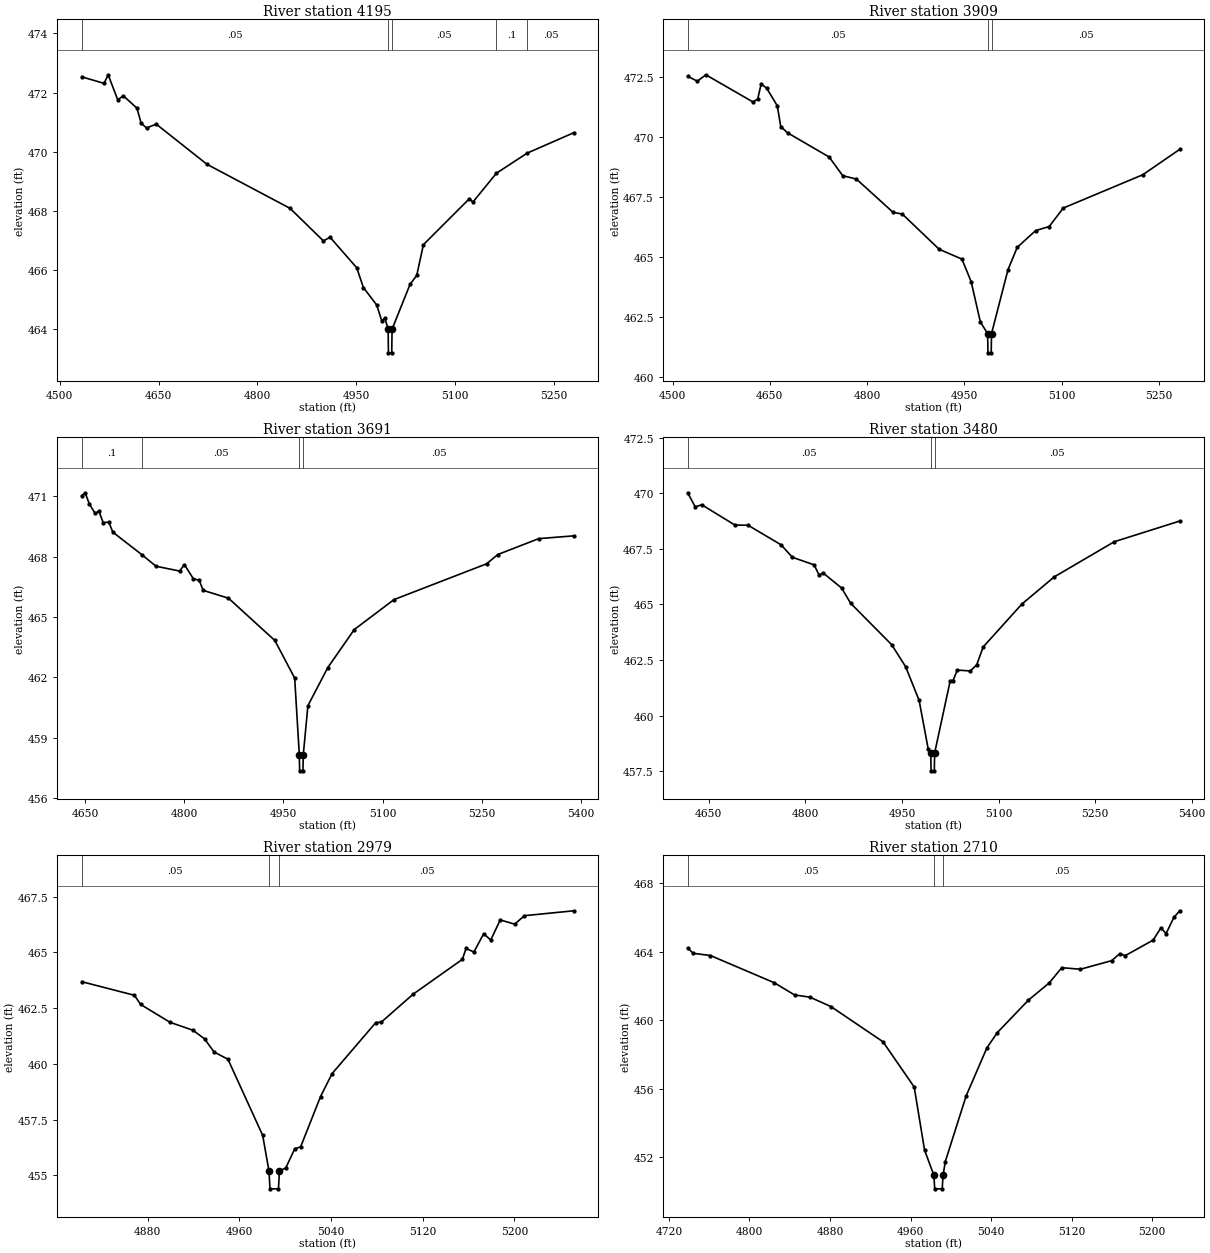
Type RM Length L Ch R = 1,4195,286,286,286
BEGIN DESCRIPTION:
Mapping XS bc734faa
END DESCRIPTION:
XS GIS Cut Line= 4
      2053256.74     13499229.39      2053098.34     13499348.73
      2053031.06     13499797.95      2053114.39     13499840.68
#Sta/Elev= 30
  4533.5  472.53  4567.4  472.31  4573.6  472.60  4588.2  471.75  4596.5  471.89
  4617.3  471.47  4623.6  470.96  4631.9  470.80  4646.5  470.93  4723.5  469.57
  4849.4  468.08  4899.9  466.98  4910.1  467.10  4950.5  466.07  4960.6  465.40
  4980.8  464.81  4988.3  464.28  4993.3  464.36  4998.1  463.99  4998.6  463.19
  5003.6  463.19  5004.1  463.99  5031.4  465.51  5041.5  465.81  5051.6  466.85
  5121.5  468.41  5126.6  468.29  5162.4  469.27  5209.1  469.95  5279.7  470.64
#Mann=5,-1,0
  4533.5    0.05       0  4998.1    0.03       0  5004.1    0.05       0
  5162.4     0.1       0  5209.1    0.05       0
Bank Sta=4998.1,5004.1
Exp/Cntr=0.3,0.1

Type RM Length L Ch R = 1,3909,218,218,218
BEGIN DESCRIPTION:
Mapping XS 964651c0
END DESCRIPTION:
XS GIS Cut Line= 4
      2053208.97     13499201.18      2053059.28     13499257.58
      2052740.27     13499546.21      2052777.03     13499710.58
#Sta/Elev= 30
  4523.3  472.55  4538.2  472.34  4551.3  472.61  4623.7  471.48  4631.2  471.59
  4636.6  472.23  4645.1  472.05  4661.4  471.32  4666.8  470.45  4677.2  470.19
  4741.4  469.18  4762.3  468.40  4783.4  468.26  4840.0  466.87  4854.2  466.80
  4911.0  465.33  4946.1  464.92  4960.3  463.98  4974.5  462.30  4985.7  461.81
  4986.2  461.01  4991.2  461.01  4991.7  461.81  5017.1  464.48  5031.3  465.41
  5059.7  466.11  5080.6  466.28  5102.3  467.05  5224.9  468.44  5281.9  469.50
#Mann=3,-1,0
  4523.3    0.05       0  4985.7    0.03       0  4991.7    0.05       0
Bank Sta=4985.7,4991.7
Exp/Cntr=0.3,0.1

Type RM Length L Ch R = 1,3691,211,211,211
BEGIN DESCRIPTION:
Mapping XS 51e587bc
END DESCRIPTION:
XS GIS Cut Line= 4
      2052831.42     13499044.90      2052672.99     13499157.76
      2052668.65     13499589.62      2052707.66     13499700.14
#Sta/Elev= 30
  4645.2  471.03  4650.5  471.17  4656.6  470.62  4665.2  470.16  4671.4  470.24
  4677.6  469.69  4686.1  469.71  4692.3  469.21  4736.6  468.08  4757.4  467.52
  4793.1  467.28  4800.4  467.60  4814.0  466.89  4822.6  466.83  4828.7  466.32
  4867.0  465.93  4937.0  463.83  4967.0  461.96  4974.0  458.15  4974.5  457.35
  4979.5  457.35  4980.0  458.15  4987.0  460.59  5017.0  462.48  5057.0  464.37
  5117.0  465.86  5257.0  467.64  5273.8  468.10  5335.7  468.89  5388.8  469.03
#Mann=4,-1,0
  4645.2     0.1       0  4736.6    0.05       0  4974.0    0.03       0
  4980.0    0.05       0
Bank Sta=4974,4980
Exp/Cntr=0.3,0.1

Type RM Length L Ch R = 1,3480,501,501,501
BEGIN DESCRIPTION:
Mapping XS 791b87b5
END DESCRIPTION:
XS GIS Cut Line= 5
      2052377.85     13499053.58      2052340.96     13499214.18
      2052505.89     13499398.64      2052523.25     13499574.42
      2052664.30     13499678.58
#Sta/Elev= 30
  4617.3  470.02  4629.0  469.39  4639.3  469.48  4690.6  468.57  4711.1  468.56
  4762.4  467.68  4779.9  467.12  4813.7  466.78  4821.2  466.33  4827.9  466.41
  4856.3  465.74  4870.5  465.05  4934.1  463.19  4955.8  462.20  4976.7  460.69
  4990.9  458.49  4994.8  458.32  4995.3  457.52  5000.3  457.52  5000.8  458.32
  5025.1  461.58  5029.5  461.58  5035.9  462.05  5056.0  462.01  5066.1  462.28
  5076.2  463.09  5136.4  465.02  5186.6  466.24  5279.8  467.82  5381.5  468.75
#Mann=3,-1,0
  4617.3    0.05       0  4994.8    0.03       0  5000.8    0.05       0
Bank Sta=4994.8,5000.8
Exp/Cntr=0.3,0.1

Type RM Length L Ch R = 1,2979,269,269,269
BEGIN DESCRIPTION:
Mapping XS 33e14c49
END DESCRIPTION:
XS GIS Cut Line= 4
      2052087.63     13499260.68      2052039.42     13499280.23
      2051999.06     13499561.48      2052053.75     13499637.01
#Sta/Elev= 30
  4822.4  463.69  4868.4  463.08  4873.8  462.67  4899.4  461.87  4919.6  461.51
  4929.7  461.12  4937.8  460.54  4950.0  460.21  4980.3  456.80  4985.8  455.20
  4986.7  454.40  4994.1  454.40  4994.9  455.20  5000.5  455.34  5008.3  456.20
  5013.4  456.28  5030.8  458.54  5040.9  459.57  5078.9  461.85  5083.9  461.88
  5111.6  463.13  5154.5  464.69  5157.8  465.18  5164.6  465.02  5173.1  465.84
  5179.3  465.56  5187.6  466.46  5200.2  466.27  5208.7  466.65  5251.8  466.87
#Mann=3,-1,0
  4822.4    0.05       0  4985.8    0.03       0  4994.9    0.05       0
Bank Sta=4985.8,4994.9
Exp/Cntr=0.3,0.1

Type RM Length L Ch R = 1,2710,377,377,377
BEGIN DESCRIPTION:
Mapping XS f9ce2641
END DESCRIPTION:
XS GIS Cut Line= 4
      2051940.47     13499137.00      2051834.99     13499150.02
      2051762.08     13499435.17      2051784.08     13499520.58
#Sta/Elev= 30
  4738.6  464.22  4744.1  463.91  4761.2  463.78  4824.7  462.19  4844.8  461.48
  4860.1  461.35  4881.0  460.80  4932.6  458.75  4963.6  456.11  4973.9  452.43
  4983.1  450.97  4984.0  450.17  4991.4  450.17  4992.3  450.97  4994.5  451.76
  5015.2  455.59  5035.8  458.39  5046.1  459.28  5077.1  461.18  5097.7  462.18
  5110.2  463.07  5128.7  462.98  5159.7  463.48  5167.9  463.89  5173.1  463.77
  5201.0  464.68  5208.6  465.39  5213.8  465.06  5221.6  466.01  5227.4  466.39
#Mann=3,-1,0
  4738.6    0.05       0  4983.1    0.03       0  4992.3    0.05       0
Bank Sta=4983.1,4992.3
Exp/Cntr=0.3,0.1

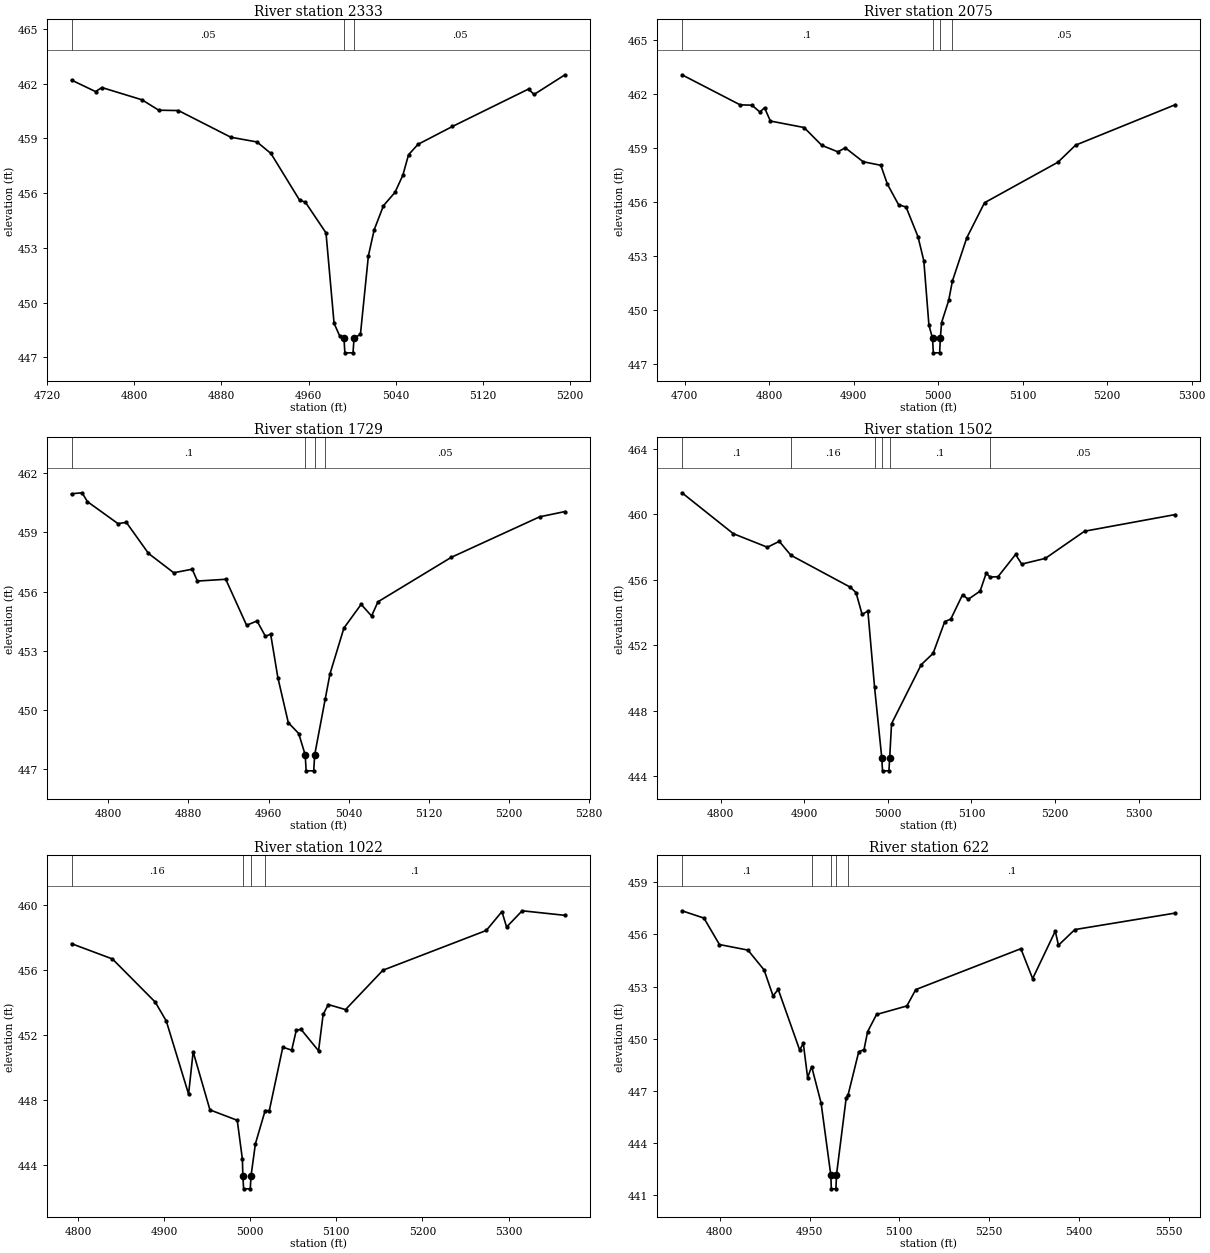
Type RM Length L Ch R = 1,2333,258,258,258
BEGIN DESCRIPTION:
Mapping XS e0ec7452
END DESCRIPTION:
XS GIS Cut Line= 4
      2051797.24     13499022.42      2051716.51     13498972.93
      2051459.99     13499058.87      2051475.63     13499144.85
#Sta/Elev= 30
  4742.6  462.19  4764.6  461.56  4770.5  461.78  4807.2  461.11  4822.6  460.54
  4840.7  460.52  4888.7  459.06  4912.7  458.80  4925.5  458.17  4951.8  455.61
  4957.1  455.50  4976.0  453.82  4983.4  448.87  4988.6  448.17  4992.5  448.05
  4993.3  447.25  5000.8  447.25  5001.7  448.05  5007.6  448.27  5014.9  452.57
  5020.2  453.99  5028.7  455.31  5039.3  456.04  5046.5  456.98  5051.7  458.10
  5060.4  458.67  5092.0  459.65  5161.8  461.70  5166.8  461.40  5195.2  462.48
#Mann=3,-1,0
  4742.6    0.05       0  4992.5    0.03       0  5001.7    0.05       0
Bank Sta=4992.5,5001.7
Exp/Cntr=0.3,0.1

Type RM Length L Ch R = 1,2075,346,346,346
BEGIN DESCRIPTION:
Mapping XS 3f9186c2
END DESCRIPTION:
XS GIS Cut Line= 4
      2051700.86     13498798.45      2051548.54     13498732.05
      2051288.12     13498909.13      2051295.81     13499011.65
#Sta/Elev= 30
  4696.9  463.06  4765.7  461.39  4779.7  461.37  4789.1  460.99  4794.6  461.23
  4801.5  460.49  4841.4  460.13  4862.3  459.14  4881.3  458.78  4890.2  459.00
  4911.2  458.23  4932.2  458.03  4939.9  456.99  4953.2  455.84  4962.1  455.71
  4976.2  454.06  4983.1  452.72  4989.1  449.16  4993.4  448.41  4994.3  447.61
  5001.8  447.61  5002.6  448.41  5004.1  449.29  5012.5  450.52  5016.9  451.60
  5033.9  454.00  5054.9  455.95  5141.7  458.20  5162.7  459.15  5280.8  461.40
#Mann=4,-1,0
  4696.9     0.1       0  4993.4    0.07       0  5002.6     0.1       0
  5016.9    0.05       0
Bank Sta=4993.4,5002.6
Exp/Cntr=0.3,0.1

Type RM Length L Ch R = 1,1729,227,227,227
BEGIN DESCRIPTION:
Mapping XS f4079b1e
END DESCRIPTION:
XS GIS Cut Line= 4
      2051276.38     13498495.08      2051187.86     13498527.62
      2051100.62     13498836.21      2051146.22     13498898.75
#Sta/Elev= 30
  4763.4  460.95  4773.9  461.00  4779.3  460.55  4809.7  459.44  4818.1  459.50
  4840.2  457.93  4865.4  456.95  4883.8  457.13  4889.0  456.53  4917.3  456.62
  4938.1  454.29  4948.5  454.51  4956.9  453.73  4962.1  453.84  4969.3  451.64
  4979.7  449.36  4990.1  448.81  4996.6  447.72  4997.5  446.92  5005.1  446.92
  5006.0  447.72  5016.6  450.57  5021.3  451.83  5035.2  454.15  5052.4  455.35
  5062.8  454.76  5069.2  455.48  5142.3  457.73  5230.4  459.78  5255.8  460.05
#Mann=4,-1,0
  4763.4     0.1       0  4996.6    0.07       0  5006.0     0.1       0
  5016.6    0.05       0
Bank Sta=4996.6,5006
Exp/Cntr=0.3,0.1

Type RM Length L Ch R = 1,1502,480,480,480
BEGIN DESCRIPTION:
Mapping XS 12754c70
END DESCRIPTION:
XS GIS Cut Line= 4
      2051195.71     13498406.53      2051117.55     13498394.81
      2050838.90     13498686.48      2050875.35     13498788.01
#Sta/Elev= 30
  4753.7  461.32  4815.1  458.82  4855.9  457.99  4870.1  458.35  4884.0  457.50
  4955.0  455.55  4961.9  455.22  4969.2  453.88  4976.1  454.09  4984.1  449.43
  4992.7  445.12  4993.6  444.32  5001.3  444.32  5002.2  445.12  5004.4  447.20
  5039.9  450.81  5054.1  451.50  5068.1  453.45  5075.2  453.59  5089.3  455.08
  5096.2  454.81  5110.4  455.31  5117.6  456.40  5122.3  456.17  5131.8  456.19
  5152.8  457.55  5160.1  456.96  5188.4  457.31  5235.3  458.97  5344.0  459.99
#Mann=6,-1,0
  4753.7     0.1       0  4884.0    0.16       0  4984.1     0.1       0
  4992.7    0.07       0  5002.2     0.1       0  5122.3    0.05       0
Bank Sta=4992.7,5002.2
Exp/Cntr=0.3,0.1

Type RM Length L Ch R = 1,1022,400,400,400
BEGIN DESCRIPTION:
Mapping XS 07cbf14d
END DESCRIPTION:
XS GIS Cut Line= 4
      2050932.66     13498138.30      2050901.40     13498117.46
      2050488.64     13498259.39      2050527.58     13498350.25
#Sta/Elev= 30
  4792.6  457.61  4840.1  456.67  4889.8  454.02  4902.6  452.86  4928.5  448.37
  4933.8  450.97  4953.3  447.40  4985.0  446.76  4991.0  444.36  4991.5  443.35
  4992.4  442.55  5000.1  442.55  5001.0  443.35  5006.1  445.32  5017.4  447.36
  5022.2  447.35  5037.9  451.25  5048.2  451.07  5053.5  452.28  5059.0  452.35
  5079.4  451.03  5084.7  453.26  5090.7  453.87  5110.7  453.56  5154.2  455.98
  5274.1  458.42  5292.3  459.58  5297.7  458.63  5315.8  459.63  5365.5  459.35
#Mann=4,-1,0
  4792.6    0.16       0  4991.5    0.07       0  5001.0    0.16       0
  5017.4     0.1       0
Bank Sta=4991.5,5001
Exp/Cntr=0.3,0.1

Type RM Length L Ch R = 1,622,430,430,430
BEGIN DESCRIPTION:
Mapping XS 8c76e823
END DESCRIPTION:
XS GIS Cut Line= 4
      2050760.76     13497784.13      2050676.14     13497764.60
      2050383.17     13497967.73      2050270.84     13498331.75
#Sta/Elev= 30
  4736.9  457.36  4773.6  456.94  4799.5  455.42  4847.1  455.10  4874.1  453.96
  4889.0  452.47  4897.7  452.84  4933.5  449.36  4939.6  449.74  4946.8  447.77
  4953.5  448.41  4969.3  446.31  4985.5  442.18  4986.4  441.38  4994.1  441.38
  4995.0  442.18  5011.2  446.60  5014.5  446.79  5032.2  449.26  5041.0  449.38
  5047.0  450.41  5061.9  451.40  5112.6  451.89  5127.4  452.83  5303.0  455.18
  5322.7  453.46  5360.5  456.19  5365.8  455.38  5393.2  456.28  5561.2  457.23
#Mann=5,-1,0
  4736.9     0.1       0  4953.5    0.16       0  4985.5    0.07       0
  4995.0    0.16       0  5014.5     0.1       0
Bank Sta=4985.5,4995
Exp/Cntr=0.3,0.1

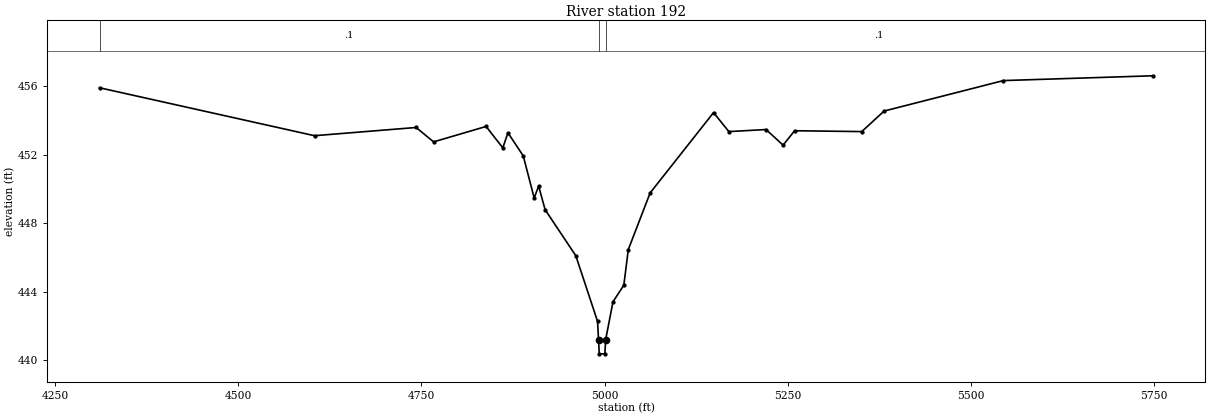
Type RM Length L Ch R = 1,192,0,0,0
BEGIN DESCRIPTION:
UNT 167 in Lagunillas Cr Wtrshd 1.0
END DESCRIPTION:
XS GIS Cut Line= 4
      2050775.57     13497278.73      2050357.51     13497413.76
      2050077.02     13497819.58      2049983.87     13498315.16
#Sta/Elev= 30
  4310.9  455.92  4604.2  453.12  4742.8  453.60  4766.7  452.76  4838.3  453.66
  4861.1  452.41  4868.1  453.29  4889.0  451.94  4903.9  449.48  4910.0  450.18
  4918.8  448.80  4960.7  446.11  4990.4  442.27  4991.7  441.18  4992.7  440.38
  5000.4  440.38  5001.3  441.18  5011.4  443.42  5026.2  444.39  5032.3  446.47
  5062.1  449.78  5148.6  454.47  5169.5  453.36  5220.2  453.48  5243.5  452.57
  5259.2  453.41  5350.8  453.36  5381.3  454.56  5544.1  456.34  5747.8  456.62
#Mann=3,-1,0
  4310.9     0.1       0  4991.7    0.07       0  5001.3     0.1       0
Bank Sta=4991.7,5001.3
Exp/Cntr=0.3,0.1

Chan Stop Cuts=-1