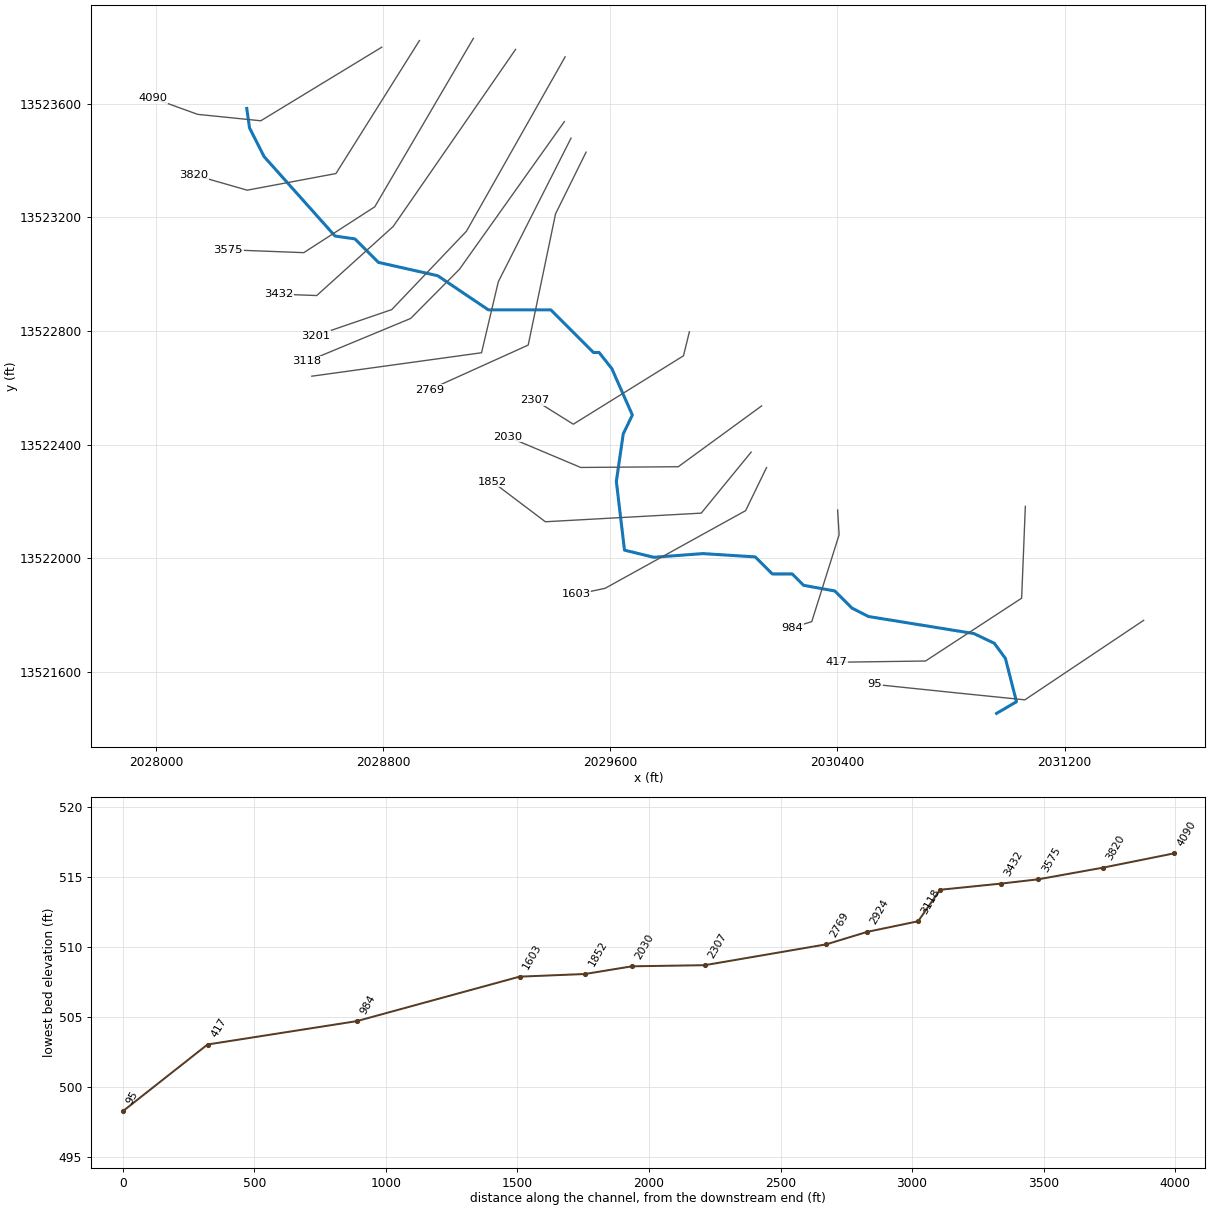
--- UNT 168 in Lagunillas Cr Wtrshd.prj (project) ---

Proj Title=UNT 168 in Lagunillas Cr Wtrshd Base Level Engineering
Current Plan=p01
Default Exp/Contr=0.3,0.1
English Units
Geom File=g01
Flow File=f01
Plan File=p01
BEGIN DESCRIPTION:
UNT 168 in Lagunillas Cr Wtrshd
END DESCRIPTION:

--- UNT 168 in Lagunillas Cr Wtrshd.p01 (plan) ---

Plan Title=Multiple Run
Short Identifier=Multiple
Geom File=g01
Flow File=f01
Subcritical Flow
K Sum by GR= 0
Std Step Tol= 0.01
Critical Tol= 0.01
Num of Std Step Trials= 20
Max Error Tol= 0.3
Flow Tol Ratio= 0.001
Split Flow NTrial= 30
Split Flow Tol= 0.02
Split Flow Ratio= 0.02
Log Output Level= 0
Friction Slope Method= 1
Unsteady Friction Slope Method= 2
Unsteady Bridges Friction Slope Method= 1
Parabolic Critical Depth
Global Vel Dist=  1 , 1 , 1
Global Log Level= 0
CheckData=True
Encroach Param= -1, 0, 0, 0
BEGIN DESCRIPTION:
Multiple Run
END DESCRIPTION:

--- UNT 168 in Lagunillas Cr Wtrshd.f01 (steady flow) ---

Flow Title=Multiple
Number of Profiles=7
Profile Names=10-year,25-year,50-year,1pct_min,100-year,1pct_plu,500-year
River Rch & RM= UNT 168 in Lagun,Reach-1,4090
     148     197     236     142     283     564     410
River Rch & RM= UNT 168 in Lagun,Reach-1,2307
     182     246     298     180     359     716     528
Boundary for River Rch & Prof#=UNT 168 in Lagun,Reach-1,1
Up Type=0
Dn Type=3
Dn Slope=0.005
Boundary for River Rch & Prof#=UNT 168 in Lagun,Reach-1,2
Up Type=0
Dn Type=3
Dn Slope=0.005
Boundary for River Rch & Prof#=UNT 168 in Lagun,Reach-1,3
Up Type=0
Dn Type=3
Dn Slope=0.005
Boundary for River Rch & Prof#=UNT 168 in Lagun,Reach-1,4
Up Type=0
Dn Type=3
Dn Slope=0.005
Boundary for River Rch & Prof#=UNT 168 in Lagun,Reach-1,5
Up Type=0
Dn Type=3
Dn Slope=0.005
Boundary for River Rch & Prof#=UNT 168 in Lagun,Reach-1,6
Up Type=0
Dn Type=3
Dn Slope=0.005
Boundary for River Rch & Prof#=UNT 168 in Lagun,Reach-1,7
Up Type=0
Dn Type=3
Dn Slope=0.005

--- UNT 168 in Lagunillas Cr Wtrshd.g01 (geometry) ---

Geom Title=Existing Conditions

River Reach=UNT 168 in Lagun,Reach-1
Reach XY= 30
      2028319.83     13523583.93      2028329.60     13523515.57
      2028380.80     13523414.54      2028630.80     13523134.54
      2028700.80     13523124.54      2028783.55     13523041.79
      2028992.58     13522994.74      2029170.80     13522874.54
      2029390.80     13522874.54      2029540.80     13522724.54
      2029560.80     13522724.54      2029605.91     13522667.21
      2029677.96     13522504.01      2029645.84     13522438.04
      2029621.54     13522270.51      2029650.18     13522028.32
      2029753.48     13522003.15      2029926.23     13522016.17
      2030110.80     13522004.54      2030170.80     13521944.54
      2030240.80     13521944.54      2030280.80     13521904.54
      2030390.80     13521884.54      2030450.80     13521824.54
      2030509.44     13521794.58      2030880.80     13521734.54
      2030952.67     13521700.31      2030991.73     13521647.19
      2031030.80     13521494.54      2030960.80     13521453.44

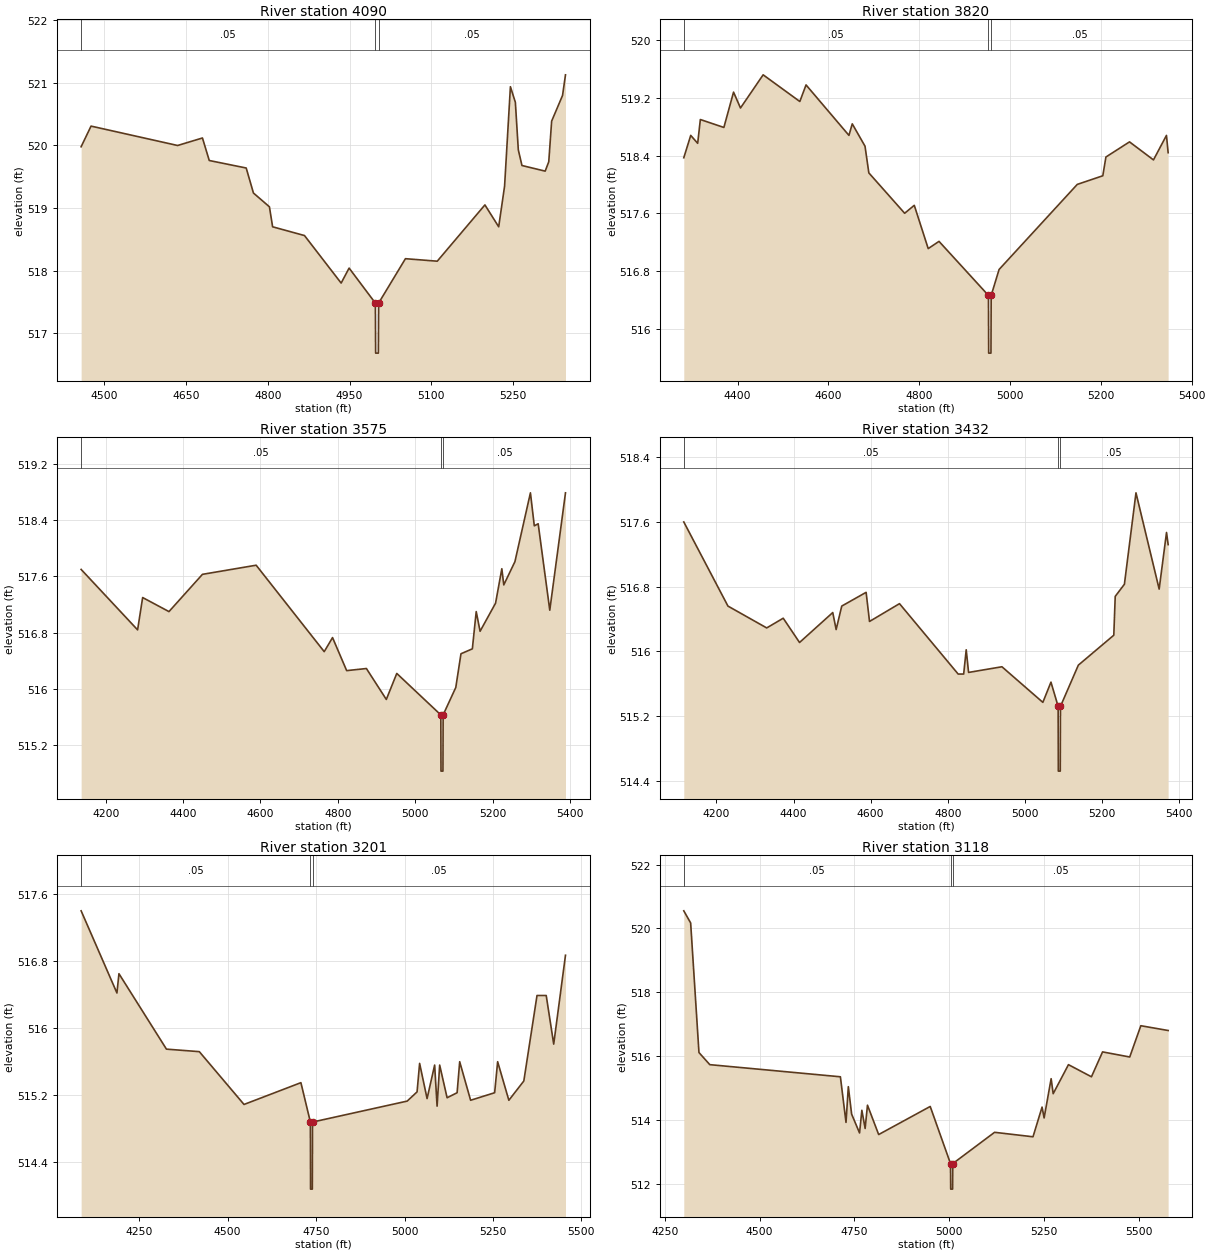
Type RM Length L Ch R = 1,4090,270,270,270
BEGIN DESCRIPTION:
UNT 168 in Lagunillas Cr Wtrshd 2.0
END DESCRIPTION:
XS GIS Cut Line= 4
      2028795.25     13523799.64      2028369.31     13523540.53
      2028147.09     13523563.10      2027989.89     13523619.97
#Sta/Elev= 30
  4457.3  519.98  4475.5  520.31  4634.4  520.00  4680.0  520.12  4692.5  519.76
  4760.3  519.64  4773.6  519.24  4802.9  519.02  4808.8  518.70  4867.3  518.56
  4934.6  517.80  4949.2  518.04  4997.4  517.48  4997.9  516.68  5002.9  516.68
  5003.4  517.48  5052.6  518.19  5111.0  518.15  5198.5  519.05  5223.8  518.70
  5234.6  519.35  5245.3  520.94  5254.4  520.69  5259.8  519.93  5266.5  519.68
  5309.1  519.59  5315.7  519.74  5321.0  520.39  5341.0  520.80  5346.4  521.13
#Mann=3,-1,0
  4457.3    0.05       0  4997.4    0.03       0  5003.4    0.05       0
Bank Sta=4997.4,5003.4
Exp/Cntr=0.3,0.1

Type RM Length L Ch R = 1,3820,245,245,245
BEGIN DESCRIPTION:
Mapping XS e78020b0
END DESCRIPTION:
XS GIS Cut Line= 4
      2028928.07     13523823.07      2028633.99     13523354.69
      2028321.49     13523296.10      2028133.16     13523350.08
#Sta/Elev= 30
  4281.3  518.37  4296.6  518.68  4311.9  518.57  4317.8  518.90  4369.6  518.79
  4390.9  519.28  4406.2  519.06  4456.1  519.52  4536.9  519.15  4550.6  519.38
  4645.1  518.68  4652.4  518.84  4680.5  518.53  4688.9  518.16  4767.8  517.60
  4789.0  517.71  4819.7  517.11  4843.5  517.21  4952.4  516.46  4952.9  515.66
  4957.9  515.66  4958.4  516.46  4975.8  516.82  5148.0  518.00  5204.3  518.12
  5211.1  518.38  5263.1  518.59  5315.9  518.34  5344.5  518.68  5348.2  518.44
#Mann=3,-1,0
  4281.3    0.05       0  4952.4    0.03       0  4958.4    0.05       0
Bank Sta=4952.4,4958.4
Exp/Cntr=0.3,0.1

Type RM Length L Ch R = 1,3575,143,143,143
BEGIN DESCRIPTION:
Mapping XS 55236628
END DESCRIPTION:
XS GIS Cut Line= 4
      2029118.18     13523830.88      2028770.70     13523237.51
      2028520.70     13523076.05      2028254.44     13523086.26
#Sta/Elev= 30
  4136.7  517.70  4282.6  516.84  4295.7  517.30  4363.7  517.10  4450.2  517.63
  4589.0  517.76  4764.9  516.53  4786.4  516.73  4822.9  516.26  4873.9  516.29
  4925.4  515.85  4952.4  516.22  5066.2  515.63  5066.7  514.83  5071.7  514.83
  5072.2  515.63  5104.9  516.02  5118.3  516.50  5147.7  516.57  5157.7  517.10
  5167.7  516.82  5207.7  517.22  5223.9  517.71  5228.9  517.48  5257.7  517.81
  5297.8  518.79  5307.8  518.32  5317.8  518.35  5347.8  517.12  5388.4  518.79
#Mann=3,-1,0
  4136.7    0.05       0  5066.2    0.03       0  5072.2    0.05       0
Bank Sta=5066.2,5072.2
Exp/Cntr=0.3,0.1

Type RM Length L Ch R = 1,3432,231,231,231
BEGIN DESCRIPTION:
Mapping XS 1a0491da
END DESCRIPTION:
XS GIS Cut Line= 4
      2029266.66     13523791.88      2028835.81     13523168.50
      2028566.28     13522925.01      2028431.68     13522930.00
#Sta/Elev= 30
  4115.5  517.60  4230.0  516.56  4330.5  516.29  4373.3  516.41  4415.6  516.11
  4501.7  516.48  4510.5  516.27  4525.0  516.56  4588.2  516.73  4597.0  516.37
  4674.7  516.59  4826.8  515.72  4841.1  515.72  4847.7  516.02  4853.8  515.74
  4940.3  515.81  5046.4  515.37  5067.4  515.62  5086.0  515.32  5086.5  514.52
  5091.5  514.52  5092.0  515.32  5138.4  515.83  5230.3  516.20  5234.0  516.68
  5257.8  516.83  5287.8  517.96  5347.9  516.77  5367.0  517.47  5371.2  517.32
#Mann=3,-1,0
  4115.5    0.05       0  5086.0    0.03       0  5092.0    0.05       0
Bank Sta=5086,5092
Exp/Cntr=0.3,0.1

Type RM Length L Ch R = 1,3201,83,83,83
BEGIN DESCRIPTION:
Mapping XS 14648e32
END DESCRIPTION:
XS GIS Cut Line= 4
      2029441.11     13523765.80      2029093.62     13523151.57
      2028830.60     13522875.53      2028563.53     13522784.04
#Sta/Elev= 30
  4085.8  517.40  4187.0  516.42  4192.7  516.65  4327.0  515.75  4419.9  515.72
  4546.3  515.09  4707.1  515.35  4733.9  514.88  4734.4  514.08  4739.4  514.08
  4739.9  514.88  5007.5  515.13  5035.5  515.24  5042.7  515.58  5063.8  515.16
  5085.2  515.56  5092.1  515.07  5099.4  515.56  5120.4  515.17  5148.7  515.23
  5156.0  515.60  5186.9  515.14  5254.8  515.23  5263.3  515.60  5295.0  515.14
  5337.3  515.37  5374.6  516.39  5400.6  516.39  5421.8  515.81  5455.1  516.87
#Mann=3,-1,0
  4085.8    0.05       0  4733.9    0.03       0  4739.9    0.05       0
Bank Sta=4733.9,4739.9
Exp/Cntr=0.3,0.1

Type RM Length L Ch R = 1,3118,194,194,194
BEGIN DESCRIPTION:
Mapping XS 4724a185
END DESCRIPTION:
XS GIS Cut Line= 4
      2029438.48     13523537.62      2029068.88     13523017.45
      2028897.01     13522844.28      2028532.26     13522692.89
#Sta/Elev= 30
  4300.2  520.55  4318.3  520.17  4340.2  516.11  4368.8  515.73  4713.1  515.35
  4727.9  513.92  4734.0  515.04  4742.7  514.18  4763.6  513.59  4769.7  514.30
  4778.3  513.73  4784.5  514.46  4814.0  513.54  4949.9  514.42  5003.4  512.63
  5003.9  511.83  5008.9  511.83  5009.4  512.63  5119.6  513.61  5220.9  513.47
  5244.8  514.40  5250.2  514.06  5268.7  515.29  5274.1  514.82  5314.4  515.73
  5375.0  515.35  5404.3  516.13  5475.9  515.97  5505.2  516.95  5577.2  516.80
#Mann=3,-1,0
  4300.2    0.05       0  5003.4    0.03       0  5009.4    0.05       0
Bank Sta=5003.4,5009.4
Exp/Cntr=0.3,0.1

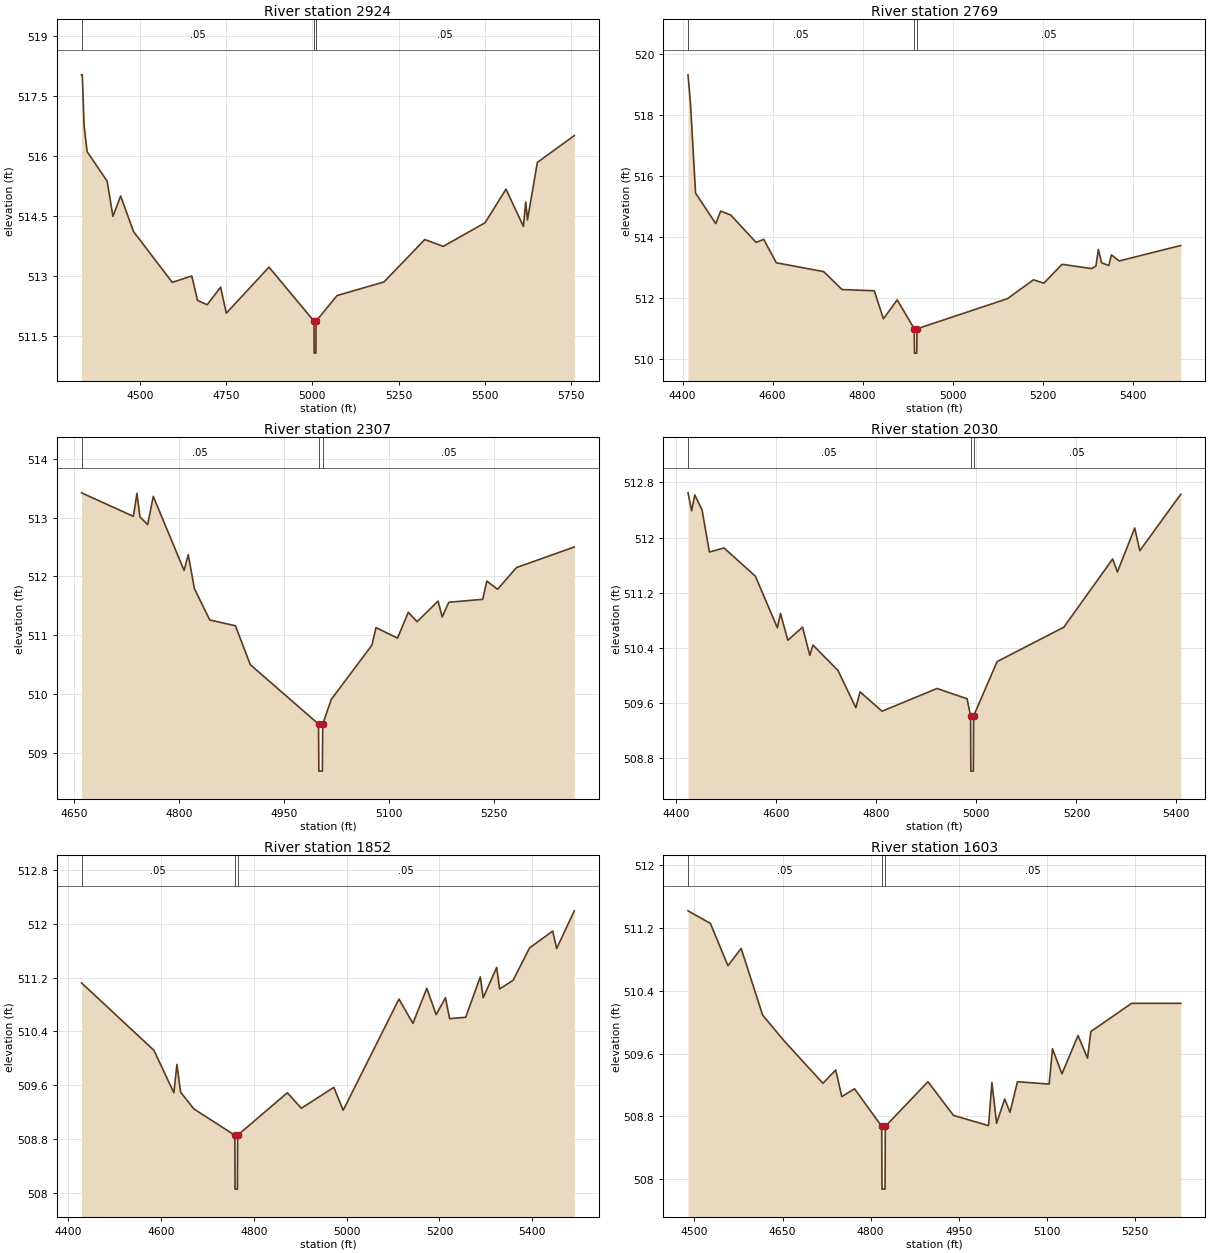
Type RM Length L Ch R = 1,2924,155,155,155
BEGIN DESCRIPTION:
Mapping XS 5ebc762b
END DESCRIPTION:
XS GIS Cut Line= 4
      2029461.94     13523479.35      2029205.78     13522973.56
      2029146.76     13522723.56      2028548.96     13522640.96
#Sta/Elev= 30
  4331.3  518.03  4333.4  518.03  4338.7  516.75  4347.4  516.11  4405.5  515.37
  4422.2  514.49  4444.5  515.00  4481.9  514.11  4594.0  512.84  4650.6  513.00
  4667.2  512.39  4695.1  512.28  4734.0  512.72  4750.7  512.07  4874.2  513.22
  5004.6  511.87  5005.1  511.07  5010.1  511.07  5010.6  511.87  5071.4  512.51
  5207.4  512.85  5325.4  513.91  5379.0  513.74  5500.1  514.33  5560.7  515.17
  5611.2  514.24  5617.9  514.85  5622.9  514.40  5651.6  515.84  5758.6  516.51
#Mann=3,-1,0
  4331.3    0.05       0  5004.6    0.03       0  5010.6    0.05       0
Bank Sta=5004.6,5010.6
Exp/Cntr=0.3,0.1

Type RM Length L Ch R = 1,2769,462,462,462
BEGIN DESCRIPTION:
Mapping XS f4e8bf09
END DESCRIPTION:
XS GIS Cut Line= 4
      2029514.90     13523430.04      2029407.42     13523212.77
      2029311.07     13522750.53      2028964.58     13522593.95
#Sta/Elev= 30
  4412.1  519.33  4417.6  518.38  4428.9  515.44  4473.7  514.44  4484.7  514.85
  4507.0  514.72  4563.4  513.82  4580.3  513.92  4608.3  513.15  4713.5  512.86
  4754.4  512.27  4825.9  512.23  4846.3  511.31  4876.9  511.93  4914.8  510.98
  4915.3  510.18  4920.3  510.18  4920.8  510.98  5121.8  511.97  5179.6  512.59
  5202.7  512.48  5243.1  513.10  5308.9  512.96  5318.3  513.04  5323.8  513.59
  5330.9  513.15  5346.9  513.06  5352.8  513.41  5370.0  513.21  5506.9  513.72
#Mann=3,-1,0
  4412.1    0.05       0  4914.8    0.03       0  4920.8    0.05       0
Bank Sta=4914.8,4920.8
Exp/Cntr=0.3,0.1

Type RM Length L Ch R = 1,2307,277,277,277
BEGIN DESCRIPTION:
Mapping XS d7767204
END DESCRIPTION:
XS GIS Cut Line= 4
      2029878.77     13522797.39      2029857.94     13522712.77
      2029469.92     13522471.88      2029334.55     13522556.49
#Sta/Elev= 30
  4661.2  513.42  4735.2  513.02  4740.3  513.41  4744.6  513.01  4755.6  512.88
  4763.6  513.36  4807.6  512.10  4813.5  512.37  4822.4  511.79  4844.2  511.26
  4880.9  511.16  4902.1  510.50  4999.5  509.49  5000.0  508.69  5005.0  508.69
  5005.5  509.49  5017.8  509.91  5075.7  510.83  5081.6  511.13  5112.3  510.95
  5127.7  511.39  5140.2  511.23  5170.2  511.58  5176.1  511.31  5185.5  511.56
  5233.9  511.61  5239.8  511.92  5255.1  511.78  5282.2  512.15  5364.7  512.50
#Mann=3,-1,0
  4661.2    0.05       0  4999.5    0.03       0  5005.5    0.05       0
Bank Sta=4999.5,5005.5
Exp/Cntr=0.3,0.1

Type RM Length L Ch R = 1,2030,178,178,178
BEGIN DESCRIPTION:
Mapping XS 5ab92442
END DESCRIPTION:
XS GIS Cut Line= 4
      2030133.15     13522536.27      2029839.71     13522322.14
      2029495.96     13522319.54      2029239.52     13522427.60
#Sta/Elev= 30
  4423.4  512.65  4430.7  512.39  4436.9  512.62  4451.5  512.40  4466.2  511.79
  4495.4  511.85  4558.1  511.44  4602.1  510.69  4608.3  510.90  4623.0  510.51
  4652.4  510.70  4667.0  510.29  4673.2  510.44  4723.4  510.07  4759.0  509.53
  4767.4  509.76  4811.4  509.48  4921.4  509.81  4981.4  509.66  4988.4  509.41
  4988.9  508.61  4993.9  508.61  4994.4  509.41  5041.4  510.20  5174.9  510.70
  5272.5  511.69  5282.0  511.50  5316.6  512.14  5326.8  511.81  5408.7  512.63
#Mann=3,-1,0
  4423.4    0.05       0  4988.4    0.03       0  4994.4    0.05       0
Bank Sta=4988.4,4994.4
Exp/Cntr=0.3,0.1

Type RM Length L Ch R = 1,1852,249,249,249
BEGIN DESCRIPTION:
Mapping XS e1c2dd9a
END DESCRIPTION:
XS GIS Cut Line= 4
      2030096.31     13522373.57      2029920.50     13522158.69
      2029371.46     13522128.31      2029184.79     13522269.39
#Sta/Elev= 30
  4429.1  511.12  4585.0  510.12  4628.0  509.49  4634.5  509.91  4642.4  509.50
  4671.1  509.25  4759.3  508.86  4759.8  508.06  4764.8  508.06  4765.3  508.86
  4872.5  509.49  4902.5  509.26  4972.6  509.57  4992.7  509.23  5112.9  510.88
  5142.9  510.52  5172.9  511.04  5193.0  510.65  5213.0  510.90  5222.0  510.59
  5256.6  510.61  5288.1  511.21  5294.3  510.90  5323.4  511.35  5329.7  511.03
  5358.8  511.16  5394.2  511.64  5444.2  511.89  5452.5  511.63  5490.6  512.19
#Mann=3,-1,0
  4429.1    0.05       0  4759.3    0.03       0  4765.3    0.05       0
Bank Sta=4759.3,4765.3
Exp/Cntr=0.3,0.1

Type RM Length L Ch R = 1,1603,619,619,619
BEGIN DESCRIPTION:
Mapping XS a32c5640
END DESCRIPTION:
XS GIS Cut Line= 4
      2030150.53     13522319.27      2030076.75     13522167.37
      2029581.96     13521893.93      2029479.93     13521872.22
#Sta/Elev= 30
  4489.2  511.42  4527.3  511.26  4557.1  510.72  4579.6  510.94  4616.2  510.09
  4652.9  509.76  4718.8  509.22  4740.5  509.39  4750.9  509.05  4772.6  509.15
  4818.8  508.67  4819.3  507.87  4824.4  507.87  4824.9  508.67  4897.5  509.24
  4941.0  508.81  5000.6  508.68  5006.3  509.23  5014.3  508.71  5028.1  509.02
  5037.1  508.85  5049.8  509.24  5103.7  509.21  5109.4  509.66  5125.5  509.34
  5152.9  509.83  5169.0  509.54  5174.7  509.88  5244.1  510.24  5327.7  510.24
#Mann=3,-1,0
  4489.2    0.05       0  4818.8    0.03       0  4824.9    0.05       0
Bank Sta=4818.8,4824.9
Exp/Cntr=0.3,0.1

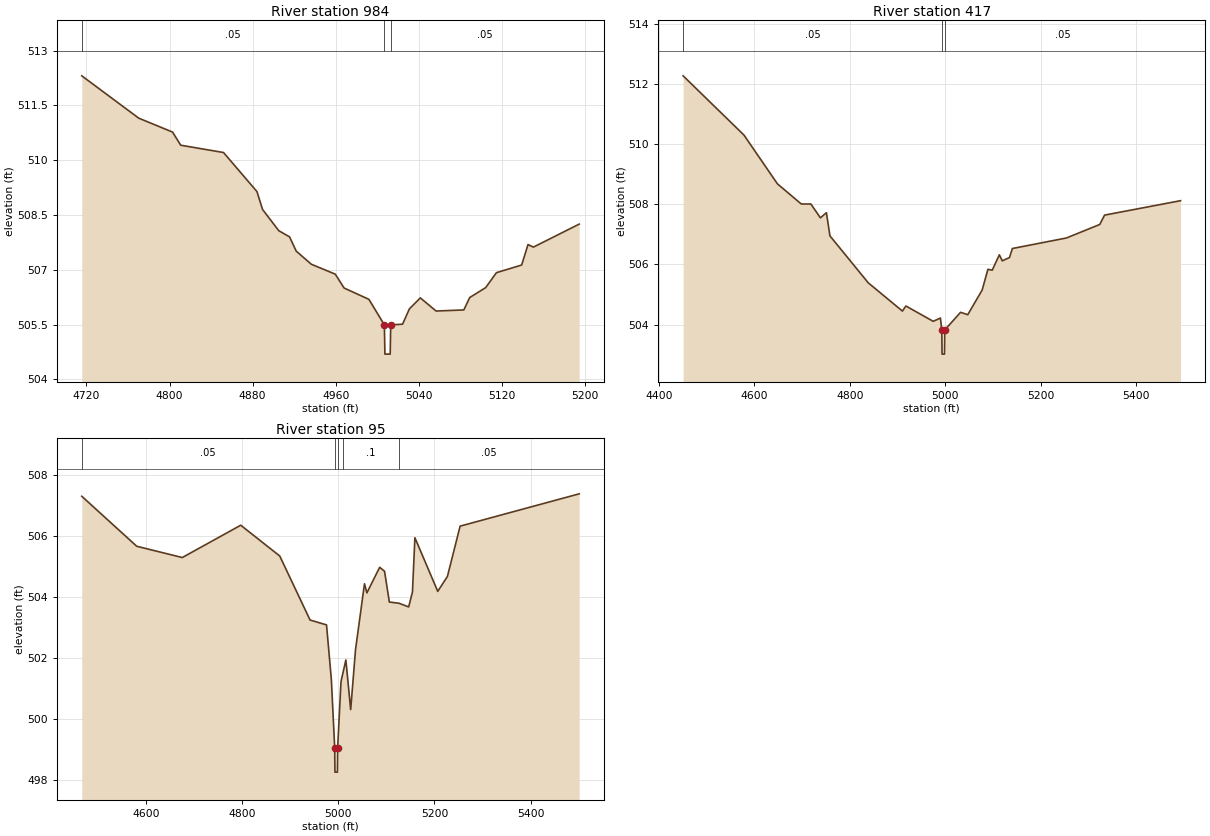
Type RM Length L Ch R = 1,984,567,567,567
BEGIN DESCRIPTION:
Mapping XS 3381b325
END DESCRIPTION:
XS GIS Cut Line= 4
      2030400.91     13522169.78      2030406.12     13522082.56
      2030309.77     13521776.57      2030242.08     13521755.74
#Sta/Elev= 30
  4715.5  512.31  4770.4  511.15  4802.9  510.77  4810.8  510.41  4852.0  510.21
  4884.2  509.14  4889.6  508.65  4905.2  508.07  4915.6  507.90  4922.0  507.51
  4936.6  507.15  4959.6  506.88  4968.1  506.50  4992.0  506.19  5006.9  505.49
  5007.4  504.69  5012.5  504.69  5013.0  505.49  5024.4  505.51  5031.0  505.93
  5041.5  506.23  5056.7  505.87  5083.4  505.90  5089.1  506.24  5104.4  506.51
  5114.8  506.92  5139.1  507.13  5145.2  507.69  5150.4  507.62  5194.5  508.25
#Mann=3,-1,0
  4715.5    0.05       0  5006.9    0.03       0  5013.0    0.05       0
Bank Sta=5006.9,5013
Exp/Cntr=0.3,0.1

Type RM Length L Ch R = 1,417,322,322,322
BEGIN DESCRIPTION:
Mapping XS 7c4de2fe
END DESCRIPTION:
XS GIS Cut Line= 4
      2031061.99     13522182.54      2031048.97     13521859.21
      2030710.43     13521637.85      2030395.74     13521633.51
#Sta/Elev= 30
  4450.4  512.27  4578.0  510.30  4648.1  508.68  4698.1  508.01  4718.2  508.01
  4738.2  507.55  4750.8  507.72  4758.2  506.95  4838.5  505.39  4910.2  504.45
  4917.4  504.62  4974.7  504.11  4989.8  504.22  4992.7  503.82  4993.2  503.02
  4998.3  503.02  4998.8  503.82  5032.0  504.41  5047.1  504.33  5077.3  505.15
  5089.4  505.84  5098.4  505.81  5113.3  506.32  5119.5  506.12  5134.6  506.23
  5140.6  506.53  5253.9  506.88  5323.9  507.33  5333.9  507.64  5493.2  508.12
#Mann=3,-1,0
  4450.4    0.05       0  4992.7    0.03       0  4998.8    0.05       0
Bank Sta=4992.7,4998.8
Exp/Cntr=0.3,0.1

Type RM Length L Ch R = 1,95,0,0,0
BEGIN DESCRIPTION:
UNT 168 in Lagunillas Cr Wtrshd 1.0
END DESCRIPTION:
XS GIS Cut Line= 4
      2031478.63     13521781.06      2031060.28     13521501.14
      2030838.06     13521523.70      2030532.53     13521555.38
#Sta/Elev= 30
  4467.0  507.30  4581.2  505.66  4675.9  505.29  4797.4  506.35  4878.5  505.34
  4941.5  503.24  4975.7  503.08  4985.7  501.30  4992.7  499.05  4993.2  498.25
  4998.3  498.25  4998.8  499.05  5005.8  501.22  5009.2  501.46  5015.9  501.93
  5025.9  500.30  5036.0  502.27  5054.6  504.43  5059.6  504.13  5086.2  504.97
  5096.3  504.84  5106.3  503.83  5126.4  503.79  5146.5  503.67  5154.3  504.16
  5159.4  505.94  5206.9  504.18  5227.0  504.67  5253.4  506.32  5500.9  507.38
#Mann=5,-1,0
  4467.0    0.05       0  4992.7    0.03       0  4998.8    0.05       0
  5009.2     0.1       0  5126.4    0.05       0
Bank Sta=4992.7,4998.8
Exp/Cntr=0.3,0.1

Chan Stop Cuts=-1