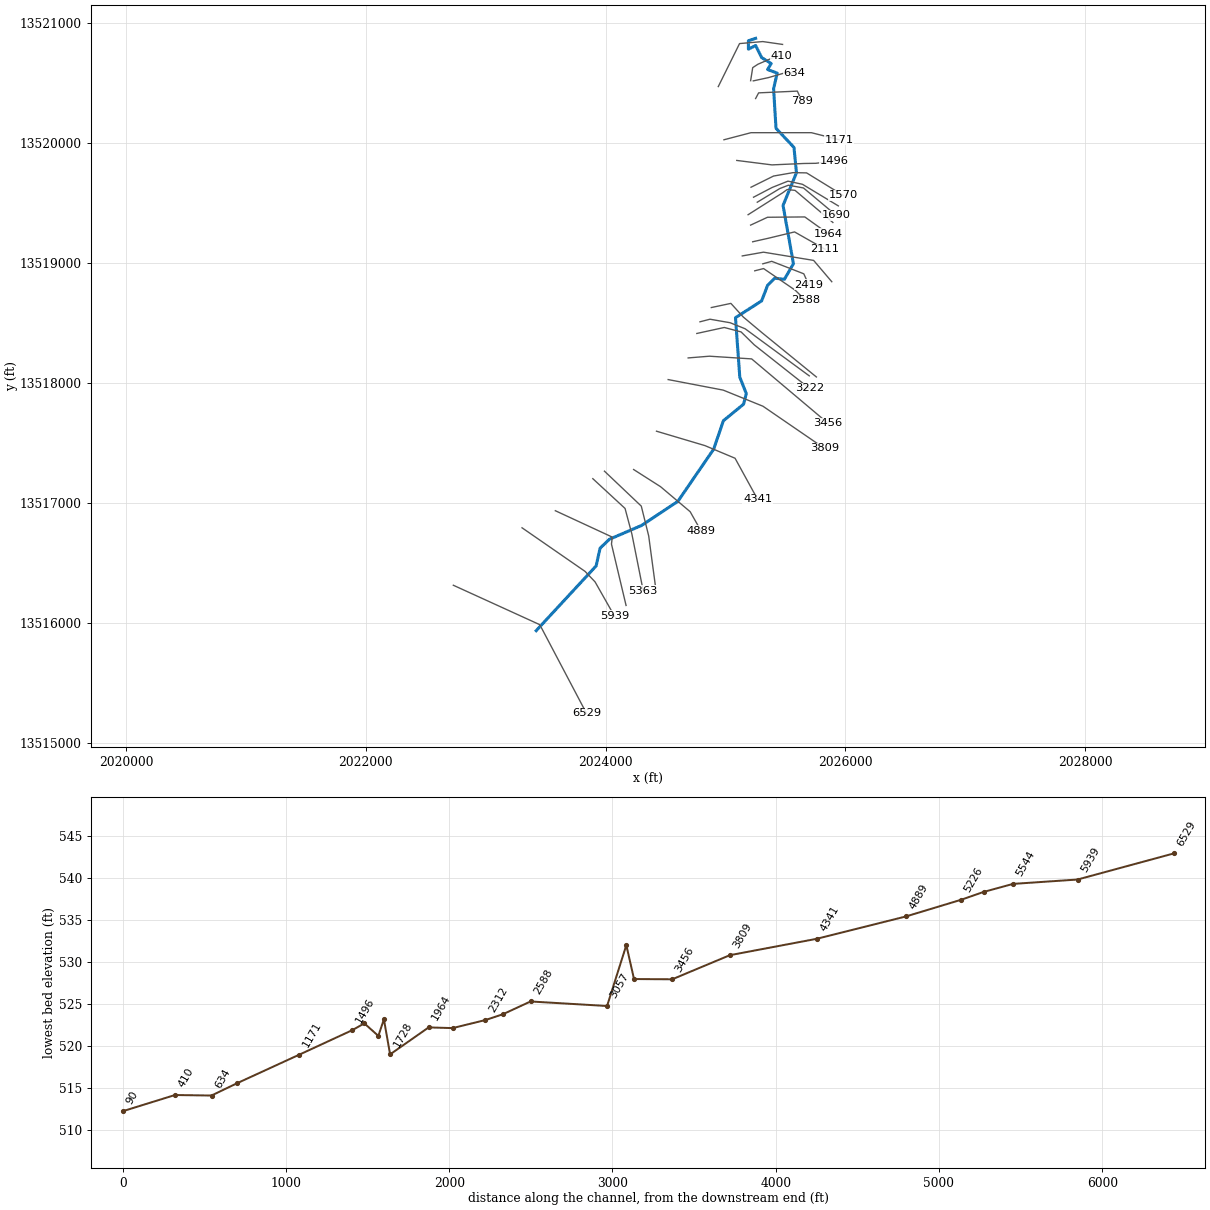
--- UNT 170 in Lagunillas Cr Wtrshd.prj (project) ---

Proj Title=UNT 170 in Lagunillas Cr Wtrshd Base Level Engineering
Current Plan=p01
Default Exp/Contr=0.3,0.1
English Units
Geom File=g01
Flow File=f01
Plan File=p01
BEGIN DESCRIPTION:
UNT 170 in Lagunillas Cr Wtrshd
END DESCRIPTION:

--- UNT 170 in Lagunillas Cr Wtrshd.p01 (plan) ---

Plan Title=Multiple Run
Short Identifier=Multiple
Geom File=g01
Flow File=f01
Subcritical Flow
K Sum by GR= 0
Std Step Tol= 0.01
Critical Tol= 0.01
Num of Std Step Trials= 20
Max Error Tol= 0.3
Flow Tol Ratio= 0.001
Split Flow NTrial= 30
Split Flow Tol= 0.02
Split Flow Ratio= 0.02
Log Output Level= 0
Friction Slope Method= 1
Unsteady Friction Slope Method= 2
Unsteady Bridges Friction Slope Method= 1
Parabolic Critical Depth
Global Vel Dist=  1 , 1 , 1
Global Log Level= 0
CheckData=True
Encroach Param= -1, 0, 0, 0
BEGIN DESCRIPTION:
Multiple Run
END DESCRIPTION:

--- UNT 170 in Lagunillas Cr Wtrshd.f01 (steady flow) ---

Flow Title=Multiple
Number of Profiles=7
Profile Names=10-year,25-year,50-year,1pct_min,100-year,1pct_plu,500-year
River Rch & RM= UNT 170 in Lagun,Reach-1,6529
     137     182     218     130     260     519     375
River Rch & RM= UNT 170 in Lagun,Reach-1,3809
     201     274     332     201     402     802     596
Boundary for River Rch & Prof#=UNT 170 in Lagun,Reach-1,1
Up Type=0
Dn Type=3
Dn Slope=0.005
Boundary for River Rch & Prof#=UNT 170 in Lagun,Reach-1,2
Up Type=0
Dn Type=3
Dn Slope=0.005
Boundary for River Rch & Prof#=UNT 170 in Lagun,Reach-1,3
Up Type=0
Dn Type=3
Dn Slope=0.005
Boundary for River Rch & Prof#=UNT 170 in Lagun,Reach-1,4
Up Type=0
Dn Type=3
Dn Slope=0.005
Boundary for River Rch & Prof#=UNT 170 in Lagun,Reach-1,5
Up Type=0
Dn Type=3
Dn Slope=0.005
Boundary for River Rch & Prof#=UNT 170 in Lagun,Reach-1,6
Up Type=0
Dn Type=3
Dn Slope=0.005
Boundary for River Rch & Prof#=UNT 170 in Lagun,Reach-1,7
Up Type=0
Dn Type=3
Dn Slope=0.005

--- UNT 170 in Lagunillas Cr Wtrshd.g01 (geometry) ---

Geom Title=Existing Conditions

River Reach=UNT 170 in Lagun,Reach-1
Reach XY= 30
      2023420.80     13515934.54      2023920.80     13516474.54
      2023953.46     13516622.14      2024031.58     13516697.01
      2024299.59     13516812.02      2024602.33     13517012.76
      2024900.72     13517447.88      2024982.10     13517685.51
      2025150.29     13517823.31      2025173.08     13517911.20
      2025118.82     13518049.00      2025083.01     13518544.88
      2025300.80     13518684.54      2025350.80     13518814.54
      2025410.80     13518874.54      2025490.80     13518864.54
      2025566.29     13518995.05      2025479.48     13519481.16
      2025591.46     13519752.86      2025570.80     13519964.54
      2025420.80     13520124.54      2025400.80     13520454.54
      2025430.80     13520584.54      2025350.80     13520614.54
      2025380.80     13520664.54      2025300.80     13520714.54
      2025250.80     13520814.54      2025190.80     13520784.54
      2025190.80     13520854.54      2025250.80     13520874.54

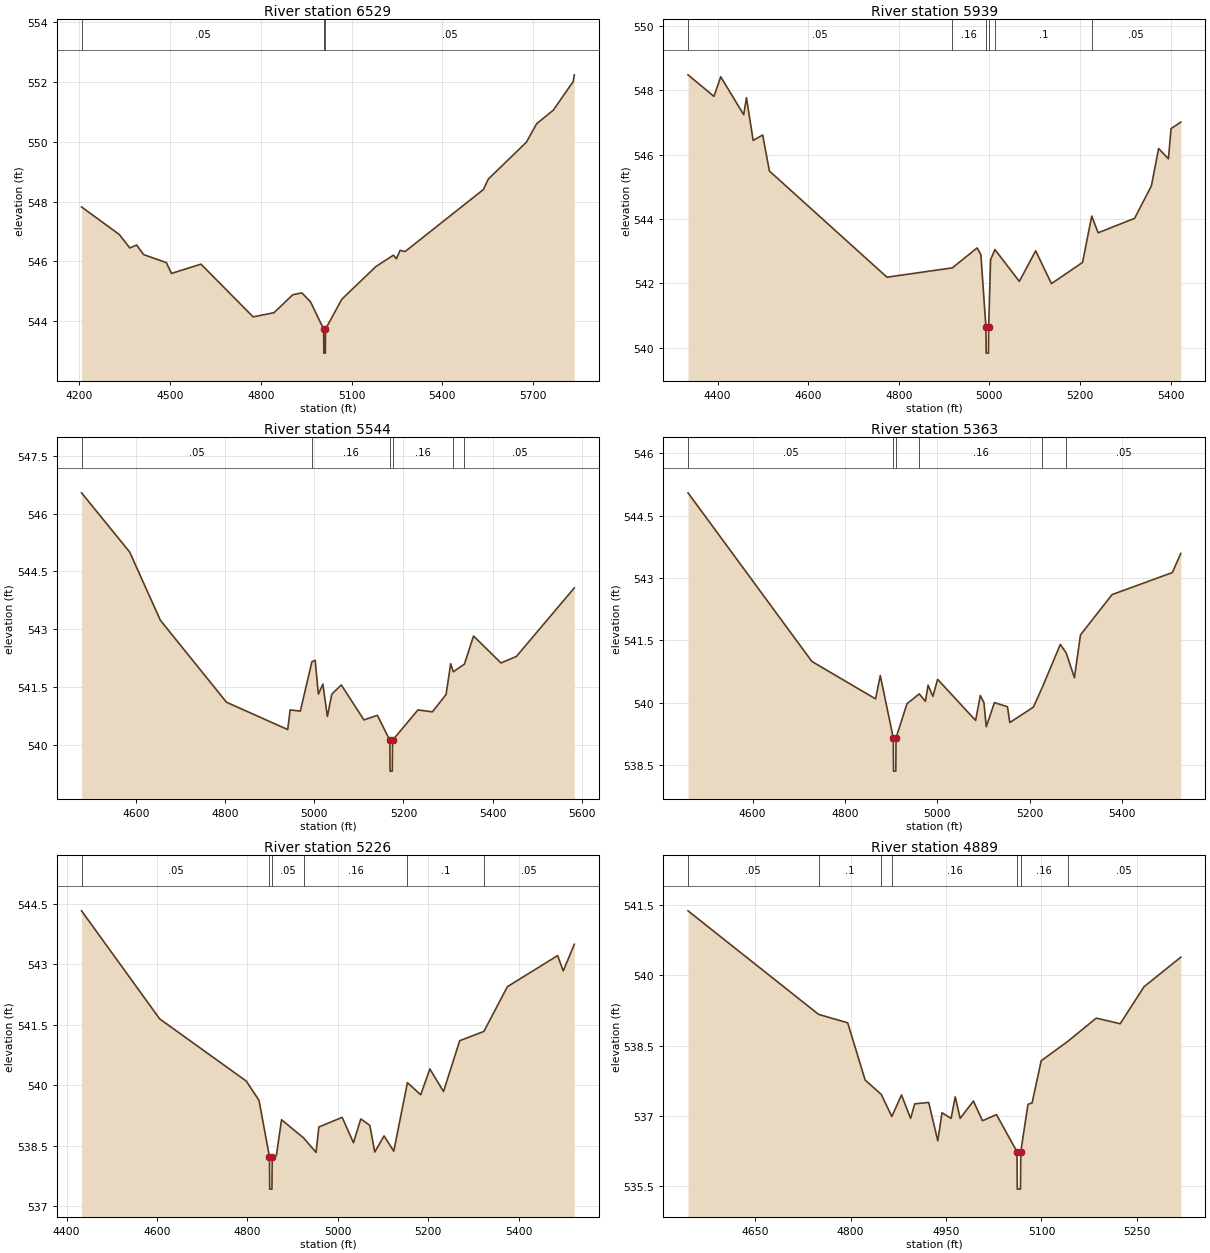
Type RM Length L Ch R = 1,6529,590,590,590
BEGIN DESCRIPTION:
UNT 170 in Lagunillas Cr Wtrshd 13.0
END DESCRIPTION:
XS GIS Cut Line= 3
      2022729.83     13516313.33      2023450.80     13515984.54
      2023840.46     13515244.79
#Sta/Elev= 30
  4207.6  547.82  4332.4  546.90  4367.2  546.45  4389.5  546.55  4412.5  546.23
  4488.0  545.96  4504.7  545.60  4602.3  545.91  4774.6  544.15  4843.7  544.29
  4905.7  544.89  4935.9  544.95  4964.4  544.65  5007.8  543.74  5008.3  542.94
  5013.3  542.94  5013.8  543.74  5067.8  544.74  5180.3  545.83  5238.4  546.21
  5248.1  546.09  5260.4  546.37  5276.8  546.33  5535.5  548.40  5551.9  548.75
  5677.6  549.98  5711.8  550.60  5766.6  551.05  5832.7  552.01  5836.1  552.23
#Mann=3,-1,0
  4207.6    0.05       0  5007.8   0.035       0  5013.8    0.05       0
Bank Sta=5007.8,5013.8
Exp/Cntr=0.3,0.1

Type RM Length L Ch R = 1,5939,395,395,395
BEGIN DESCRIPTION:
Mapping XS 3b63b387
END DESCRIPTION:
XS GIS Cut Line= 4
      2023302.72     13516792.52      2023828.55     13516428.85
      2023911.89     13516341.35      2024073.56     13516056.40
#Sta/Elev= 30
  4334.8  548.48  4392.1  547.81  4407.0  548.42  4457.7  547.24  4463.8  547.77
  4478.6  546.44  4499.6  546.61  4514.5  545.49  4774.0  542.19  4918.3  542.48
  4973.1  543.10  4981.3  542.89  4992.5  540.63  4993.0  539.83  4998.0  539.83
  4998.5  540.63  5002.7  542.73  5012.3  543.05  5066.2  542.06  5102.3  543.01
  5137.1  541.99  5205.8  542.65  5226.0  544.09  5240.2  543.57  5320.7  544.02
  5357.8  545.03  5373.7  546.19  5395.3  545.87  5401.2  546.81  5422.6  547.01
#Mann=6,-1,0
  4334.8    0.05       0  4918.3    0.16       0  4992.5    0.07       0
  4998.5    0.16       0  5012.3     0.1       0  5226.0    0.05       0
Bank Sta=4992.5,4998.5
Exp/Cntr=0.3,0.1

Type RM Length L Ch R = 1,5544,181,181,181
BEGIN DESCRIPTION:
Mapping XS 4a22bf93
END DESCRIPTION:
XS GIS Cut Line= 5
      2023580.47     13516934.89      2024050.78     13516717.04
      2024054.94     13516712.18      2024048.69     13516656.62
      2024170.40     13516144.82
#Sta/Elev= 30
  4477.0  546.54  4585.2  545.00  4654.0  543.23  4802.5  541.10  4940.0  540.39
  4945.5  540.90  4968.4  540.87  4994.3  542.15  5001.7  542.19  5008.9  541.31
  5019.0  541.57  5029.1  540.73  5039.1  541.31  5060.4  541.55  5111.2  540.64
  5141.5  540.76  5169.4  540.11  5169.9  539.31  5174.9  539.31  5175.4  540.11
  5232.5  540.90  5264.9  540.85  5295.7  541.30  5306.0  542.10  5312.0  541.89
  5336.9  542.09  5357.4  542.82  5419.1  542.12  5453.7  542.29  5583.7  544.07
#Mann=6,-1,0
  4477.0    0.05       0  4994.3    0.16       0  5169.4    0.07       0
  5175.4    0.16       0  5312.0     0.1       0  5336.9    0.05       0
Bank Sta=5169.4,5175.4
Exp/Cntr=0.3,0.1

Type RM Length L Ch R = 1,5363,137,137,137
BEGIN DESCRIPTION:
Mapping XS 10055707
END DESCRIPTION:
XS GIS Cut Line= 4
      2023893.01     13517202.23      2024161.89     13516953.85
      2024218.83     13516740.65      2024312.97     13516269.07
#Sta/Elev= 30
  4460.0  545.05  4728.4  540.99  4866.3  540.09  4876.6  540.65  4904.7  539.15
  4905.2  538.35  4910.2  538.35  4910.7  539.15  4934.3  539.97  4961.0  540.21
  4974.3  540.03  4980.1  540.42  4990.5  540.15  5000.8  540.56  5083.1  539.57
  5093.3  540.17  5101.1  540.00  5106.2  539.42  5123.9  540.00  5152.1  539.90
  5157.2  539.52  5208.2  539.89  5227.7  540.37  5266.6  541.40  5279.2  541.20
  5297.2  540.60  5310.3  541.63  5378.8  542.60  5509.3  543.13  5527.6  543.59
#Mann=6,-1,0
  4460.0    0.05       0  4904.7    0.07       0  4910.7    0.05       0
  4961.0    0.16       0  5227.7     0.1       0  5279.2    0.05       0
Bank Sta=4904.7,4910.7
Exp/Cntr=0.3,0.1

Type RM Length L Ch R = 1,5226,337,337,337
BEGIN DESCRIPTION:
Mapping XS 8b2edc03
END DESCRIPTION:
XS GIS Cut Line= 4
      2023990.20     13517264.76      2024297.30     13516973.29
      2024359.11     13516724.68      2024413.63     13516318.40
#Sta/Elev= 30
  4433.2  544.32  4606.0  541.64  4797.3  540.10  4825.6  539.62  4848.7  538.22
  4849.2  537.42  4854.2  537.42  4854.7  538.22  4863.9  538.25  4875.4  539.14
  4924.1  538.69  4951.7  538.33  4957.9  538.96  5009.4  539.20  5034.4  538.57
  5050.6  539.16  5070.6  539.00  5081.5  538.34  5102.1  538.74  5123.5  538.36
  5153.7  540.06  5183.1  539.76  5203.3  540.40  5233.5  539.84  5269.3  541.10
  5322.8  541.33  5374.8  542.44  5485.8  543.21  5498.2  542.83  5522.7  543.49
#Mann=6,-1,0
  4433.2    0.05       0  4848.7    0.07       0  4854.7    0.05       0
  4924.1    0.16       0  5153.7     0.1       0  5322.8    0.05       0
Bank Sta=4848.7,4854.7
Exp/Cntr=0.3,0.1

Type RM Length L Ch R = 1,4889,548,548,548
BEGIN DESCRIPTION:
Mapping XS fa8dfd4f
END DESCRIPTION:
XS GIS Cut Line= 4
      2024233.30     13517278.61      2024458.36     13517135.07
      2024704.89     13516926.74      2024796.22     13516765.64
#Sta/Elev= 30
  4544.2  541.38  4749.5  539.17  4795.3  538.99  4822.7  537.77  4848.2  537.46
  4864.7  536.99  4879.9  537.45  4894.2  536.95  4900.7  537.26  4922.7  537.29
  4937.0  536.47  4943.6  537.07  4957.9  536.95  4964.4  537.41  4972.2  536.95
  4993.0  537.32  5007.3  536.90  5029.3  537.03  5061.5  536.24  5062.0  535.44
  5067.0  535.44  5067.5  536.24  5078.8  537.25  5085.3  537.28  5099.6  538.18
  5141.1  538.59  5186.2  539.09  5223.8  538.97  5261.3  539.76  5319.1  540.39
#Mann=7,-1,0
  4544.2    0.05       0  4749.5     0.1       0  4848.2    0.05       0
  4864.7    0.16       0  5061.5    0.07       0  5067.5    0.16       0
  5141.1    0.05       0
Bank Sta=5061.5,5067.5
Exp/Cntr=0.3,0.1

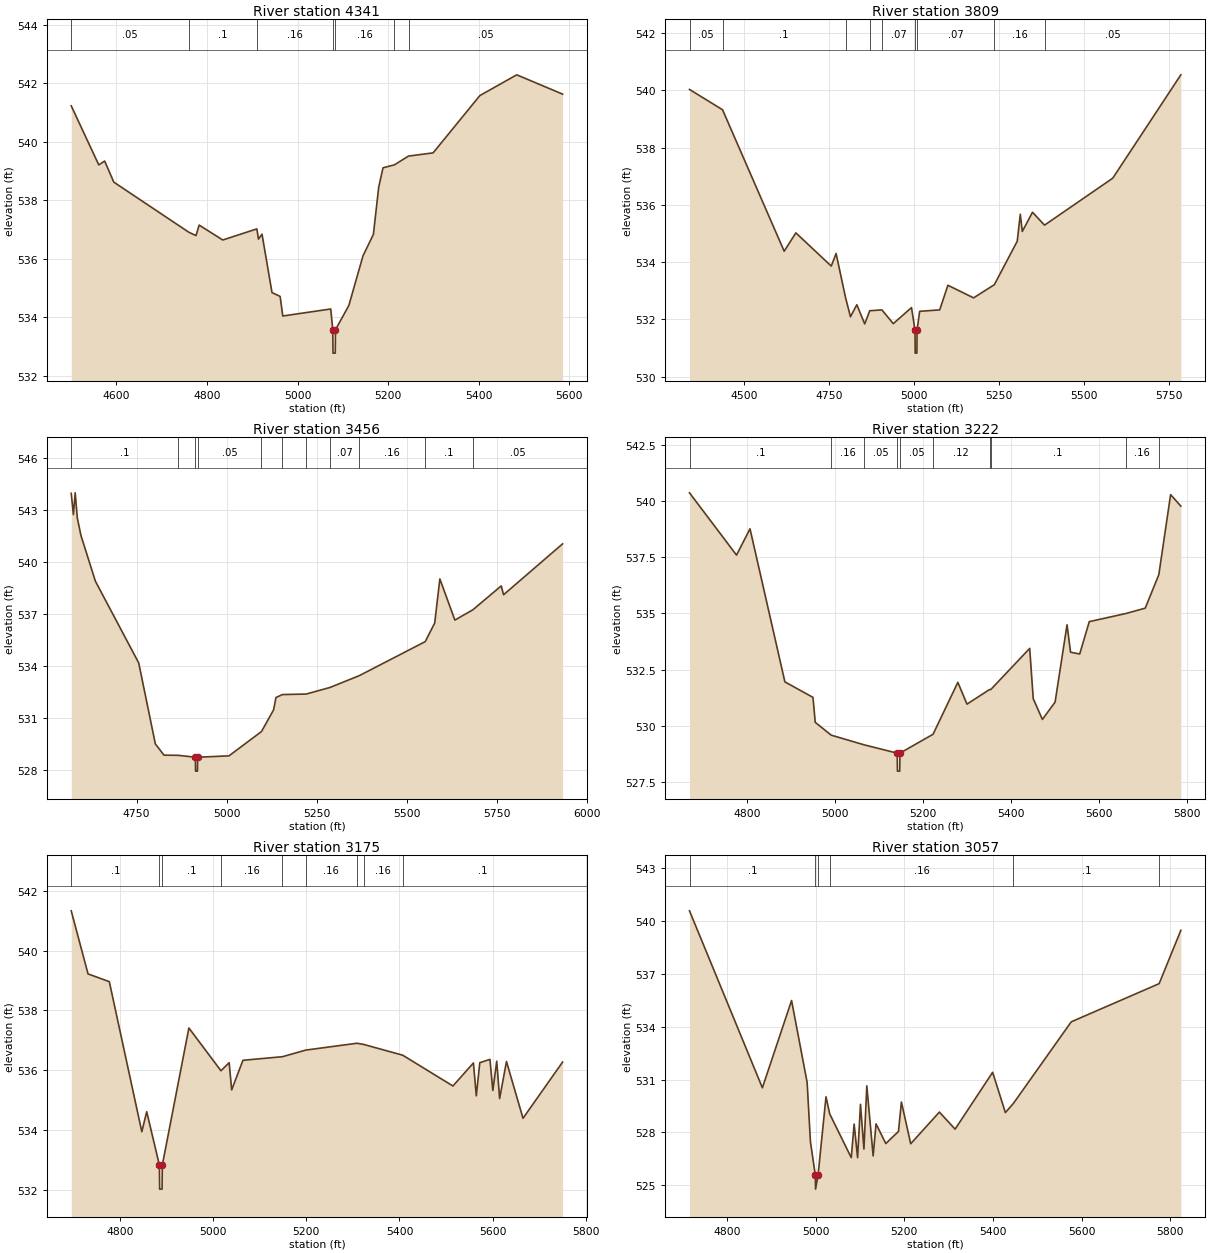
Type RM Length L Ch R = 1,4341,532,532,532
BEGIN DESCRIPTION:
Mapping XS d48a3283
END DESCRIPTION:
XS GIS Cut Line= 4
      2024424.22     13517598.07      2024828.16     13517477.96
      2025079.28     13517372.61      2025267.63     13517029.32
#Sta/Elev= 30
  4500.1  541.23  4560.9  539.21  4573.9  539.34  4594.1  538.62  4759.4  536.91
  4775.7  536.79  4782.6  537.15  4834.8  536.64  4910.1  537.02  4913.7  536.67
  4921.5  536.84  4943.6  534.84  4961.5  534.71  4967.4  534.04  5073.3  534.28
  5077.8  533.57  5078.3  532.77  5083.3  532.77  5083.8  533.57  5113.3  534.40
  5144.6  536.10  5167.5  536.83  5179.3  538.45  5188.8  539.11  5213.8  539.21
  5245.1  539.51  5299.4  539.62  5402.7  541.58  5484.2  542.29  5585.4  541.63
#Mann=7,-1,0
  4500.1    0.05       0  4759.4     0.1       0  4910.1    0.16       0
  5077.8    0.07       0  5083.8    0.16       0  5213.8     0.1       0
  5245.1    0.05       0
Bank Sta=5077.8,5083.8
Exp/Cntr=0.3,0.1

Type RM Length L Ch R = 1,3809,353,353,353
BEGIN DESCRIPTION:
Mapping XS 30ea9554
END DESCRIPTION:
XS GIS Cut Line= 4
      2024521.48     13518028.62      2024980.93     13517940.63
      2025312.53     13517806.08      2025823.59     13517455.68
#Sta/Elev= 30
  4338.7  540.03  4435.9  539.32  4617.2  534.38  4651.6  535.02  4755.7  533.86
  4769.9  534.30  4797.7  532.76  4812.2  532.09  4830.9  532.51  4854.1  531.84
  4868.8  532.30  4904.6  532.33  4938.1  531.85  4991.7  532.41  5002.1  531.62
  5002.6  530.82  5007.6  530.82  5008.1  531.62  5015.7  532.28  5074.7  532.33
  5098.8  533.19  5174.3  532.75  5235.4  533.21  5302.8  534.73  5311.7  535.67
  5317.7  535.07  5347.6  535.74  5383.0  535.29  5583.7  536.93  5784.0  540.54
#Mann=9,-1,0
  4338.7    0.05       0  4435.9     0.1       0  4797.7    0.07       0
  4868.8    0.16       0  4904.6    0.07       0  5002.1    0.07       0
  5008.1    0.07       0  5235.4    0.16       0  5383.0    0.05       0
Bank Sta=5002.1,5008.1
Exp/Cntr=0.3,0.1

Type RM Length L Ch R = 1,3456,234,234,234
BEGIN DESCRIPTION:
Mapping XS 001f9ebe
END DESCRIPTION:
XS GIS Cut Line= 4
      2024688.17     13518209.18      2024865.48     13518223.62
      2025217.91     13518201.05      2025854.79     13517664.06
#Sta/Elev= 30
  4568.8  543.95  4574.8  542.73  4579.8  543.98  4585.7  542.53  4595.7  541.53
  4635.9  538.89  4756.2  534.18  4802.3  529.52  4826.4  528.87  4866.0  528.86
  4913.5  528.75  4914.0  527.95  4919.2  527.95  4919.7  528.75  5006.8  528.83
  5097.0  530.23  5130.6  531.48  5137.2  532.19  5155.3  532.36  5221.1  532.39
  5287.4  532.77  5368.6  533.45  5551.6  535.41  5577.9  536.48  5592.2  539.02
  5633.9  536.65  5683.7  537.24  5762.6  538.62  5769.1  538.11  5932.9  541.04
#Mann=11,-1,0
  4568.8     0.1       0  4866.0    0.05       0  4913.5   0.033       0
  4919.7    0.05       0  5097.0    0.07       0  5155.3    0.05       0
  5221.1    0.12       0  5287.4    0.07       0  5368.6    0.16       0
  5551.6     0.1       0  5683.7    0.05       0
Bank Sta=4913.5,4919.7
Exp/Cntr=0.3,0.1

Type RM Length L Ch R = 1,3222,47,47,47
BEGIN DESCRIPTION:
Mapping XS 0410c96f
END DESCRIPTION:
XS GIS Cut Line= 5
      2024760.49     13518413.19      2024989.43     13518463.10
      2025129.40     13518426.21      2025240.08     13518317.70
      2025698.54     13517955.72
#Sta/Elev= 30
  4668.9  540.36  4775.9  537.59  4806.6  538.76  4886.0  531.95  4949.9  531.26
  4955.1  530.15  4991.4  529.58  5066.3  529.15  5141.6  528.78  5142.1  527.98
  5147.3  527.98  5147.8  528.78  5223.2  529.62  5279.6  531.93  5300.4  530.96
  5351.7  531.61  5354.1  531.60  5443.1  533.44  5451.2  531.20  5472.0  530.28
  5500.9  531.05  5528.1  534.49  5536.1  533.27  5556.9  533.19  5578.7  534.63
  5661.8  534.99  5706.1  535.23  5737.0  536.72  5763.8  540.28  5787.1  539.77
#Mann=10,-1,0
  4668.9     0.1       0  4991.4    0.16       0  5066.3    0.05       0
  5141.6    0.07       0  5147.8    0.05       0  5223.2    0.12       0
  5351.7    0.16       0  5354.1     0.1       0  5661.8    0.16       0
  5737.0     0.1       0
Bank Sta=5141.6,5147.8
Exp/Cntr=0.3,0.1

Type RM Length L Ch R = 1,3175,118,118,118
BEGIN DESCRIPTION:
Mapping XS 3838f293
END DESCRIPTION:
XS GIS Cut Line= 5
      2024786.83     13518510.43      2024870.14     13518532.12
      2025038.54     13518502.61      2025163.54     13518452.26
      2025698.31     13518059.53
#Sta/Elev= 30
  4695.0  541.33  4731.1  539.22  4776.8  538.96  4846.6  533.94  4857.1  534.61
  4884.4  532.82  4884.9  532.02  4890.1  532.02  4890.6  532.82  4947.7  537.41
  5016.6  535.98  5034.2  536.25  5039.6  535.34  5063.8  536.33  5148.7  536.45
  5198.4  536.67  5308.5  536.90  5323.2  536.86  5407.0  536.50  5514.8  535.47
  5558.8  536.24  5565.0  535.14  5572.5  536.25  5594.3  536.36  5600.5  535.32
  5608.9  536.30  5615.1  535.05  5629.8  536.29  5665.3  534.39  5750.3  536.27
#Mann=9,-1,0
  4695.0     0.1       0  4884.4    0.07       0  4890.6     0.1       0
  5016.6    0.16       0  5148.7    0.05       0  5198.4    0.16       0
  5308.5    0.12       0  5323.2    0.16       0  5407.0     0.1       0
Bank Sta=4884.4,4890.6
Exp/Cntr=0.3,0.1

Type RM Length L Ch R = 1,3057,469,469,469
BEGIN DESCRIPTION:
Mapping XS ec79fe35
END DESCRIPTION:
XS GIS Cut Line= 5
      2024881.41     13518629.34      2025044.62     13518664.07
      2025147.92     13518550.35      2025302.43     13518421.01
      2025757.60     13518050.34
#Sta/Elev= 30
  4715.2  540.59  4879.7  530.53  4945.6  535.49  4980.7  530.84  4988.2  527.45
  4999.2  525.57  4999.7  524.77  5005.4  525.57  5023.3  530.02  5031.6  529.05
  5080.3  526.56  5086.8  528.47  5094.6  526.56  5101.1  529.59  5108.9  527.05
  5115.4  530.64  5129.7  526.66  5136.2  528.48  5158.3  527.36  5186.9  528.05
  5193.5  529.72  5214.5  527.35  5279.2  529.15  5314.7  528.18  5399.4  531.41
  5428.2  529.12  5446.2  529.64  5576.8  534.28  5775.2  536.45  5824.2  539.48
#Mann=6,-1,0
  4715.2     0.1       0  4999.2    0.07       0  5005.4     0.1       0
  5031.6    0.16       0  5446.2     0.1       0  5775.2    0.05       0
Bank Sta=4999.2,5005.4
Exp/Cntr=0.3,0.1

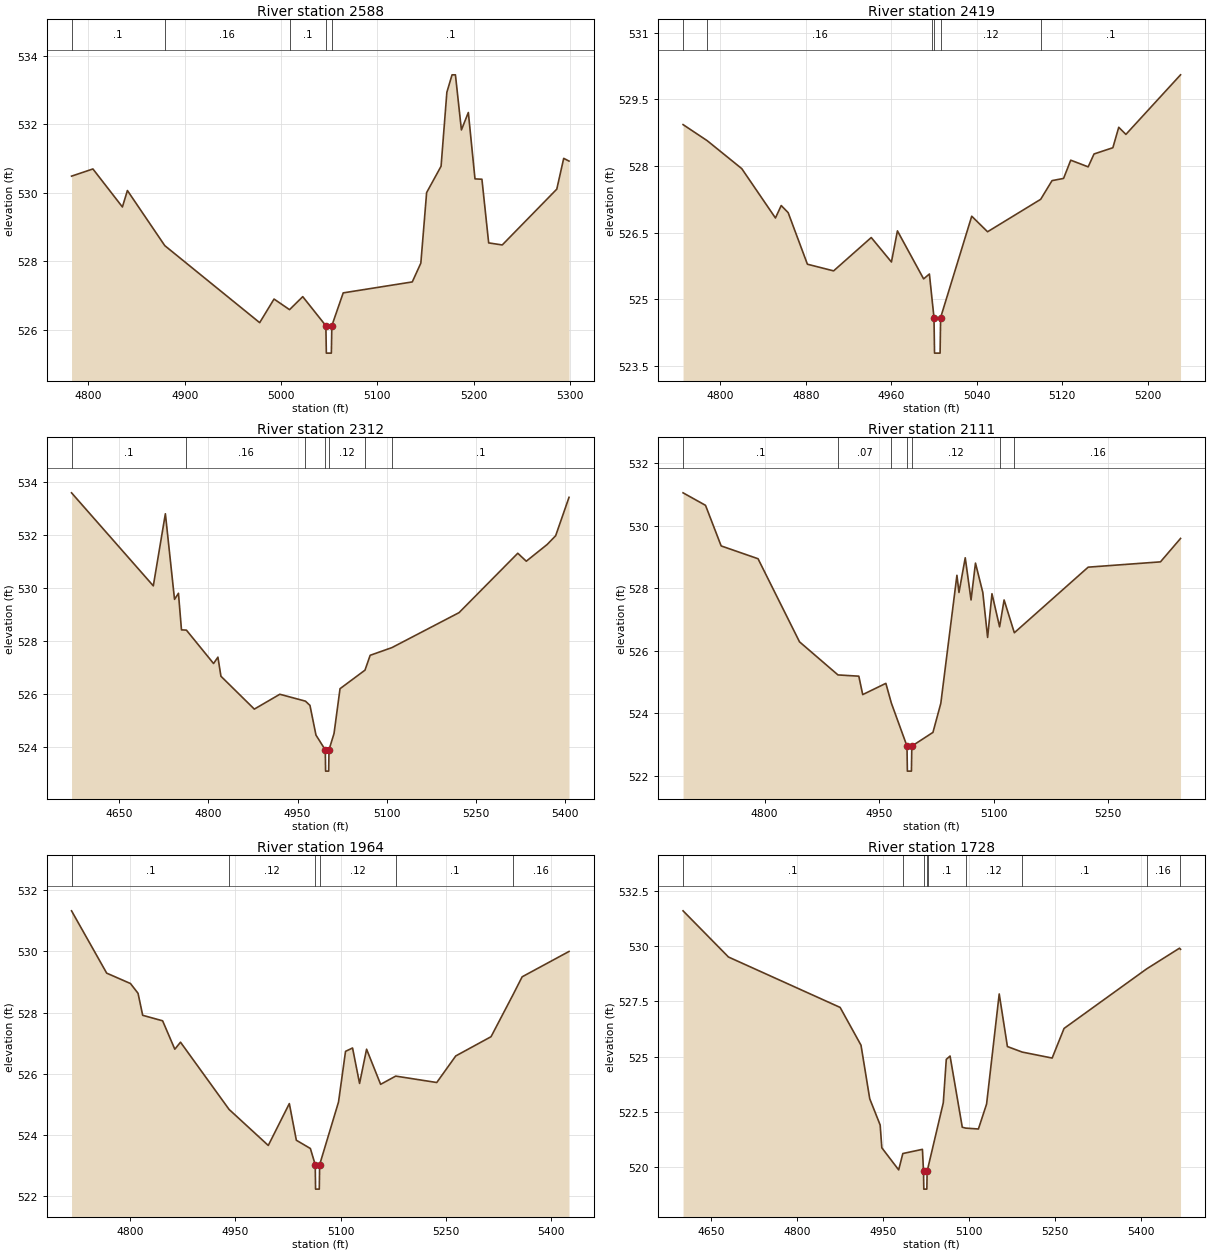
Type RM Length L Ch R = 1,2588,169,169,169
BEGIN DESCRIPTION:
Mapping XS 248510d5
END DESCRIPTION:
XS GIS Cut Line= 4
      2025243.64     13518935.73      2025317.23     13518954.48
      2025581.12     13518773.92      2025667.51     13518689.60
#Sta/Elev= 30
  4782.5  530.48  4804.7  530.69  4835.3  529.58  4840.5  530.06  4879.3  528.45
  4977.8  526.20  4992.7  526.89  5008.8  526.58  5022.5  526.96  5046.5  526.11
  5047.0  525.31  5052.2  525.31  5052.7  526.11  5064.5  527.07  5136.2  527.39
  5145.1  527.94  5151.1  530.00  5166.1  530.77  5172.1  532.93  5177.5  533.44
  5181.0  533.44  5187.2  531.83  5194.4  532.34  5201.3  530.40  5208.5  530.39
  5215.5  528.53  5229.6  528.47  5286.2  530.10  5293.4  531.00  5298.9  530.92
#Mann=5,-1,0
  4782.5     0.1       0  4879.3    0.16       0  5008.8     0.1       0
  5046.5    0.07       0  5052.7     0.1       0
Bank Sta=5046.5,5052.7
Exp/Cntr=0.3,0.1

Type RM Length L Ch R = 1,2419,107,107,107
BEGIN DESCRIPTION:
Mapping XS 3a010bb0
END DESCRIPTION:
XS GIS Cut Line= 4
      2025311.02     13518994.07      2025385.29     13519014.89
      2025652.65     13518910.73      2025694.34     13518818.47
#Sta/Elev= 30
  4765.3  528.93  4787.8  528.57  4820.2  527.94  4851.7  526.83  4857.1  527.11
  4863.6  526.95  4881.6  525.79  4906.1  525.64  4941.3  526.39  4960.2  525.84
  4965.8  526.54  4990.3  525.46  4995.7  525.57  4998.4  524.95  5000.0  524.59
  5000.5  523.79  5005.7  523.79  5006.2  524.59  5035.3  526.87  5050.1  526.52
  5099.8  527.25  5110.4  527.67  5121.2  527.72  5127.9  528.13  5144.2  527.98
  5149.7  528.27  5167.3  528.41  5172.8  528.87  5179.5  528.71  5230.6  530.05
#Mann=6,-1,0
  4765.3     0.1       0  4787.8    0.16       0  4998.4    0.12       0
  5000.0    0.07       0  5006.2    0.12       0  5099.8     0.1       0
Bank Sta=5000,5006.2
Exp/Cntr=0.3,0.1

Type RM Length L Ch R = 1,2312,201,201,201
BEGIN DESCRIPTION:
Mapping XS e4f9931f
END DESCRIPTION:
XS GIS Cut Line= 4
      2025139.50     13519059.86      2025316.62     13519091.12
      2025734.59     13519022.53      2025886.06     13518844.59
#Sta/Elev= 30
  4569.6  533.60  4707.2  530.09  4727.5  532.81  4742.9  529.58  4749.5  529.81
  4754.6  528.43  4762.9  528.42  4808.6  527.16  4815.9  527.40  4821.0  526.68
  4877.2  525.44  4920.1  526.00  4963.2  525.74  4970.8  525.58  4980.9  524.46
  4996.6  523.90  4997.1  523.10  5002.3  523.10  5002.8  523.90  5011.3  524.52
  5021.4  526.21  5063.4  526.91  5072.1  527.47  5108.7  527.76  5221.7  529.08
  5320.5  531.32  5334.8  531.02  5369.9  531.65  5384.2  531.98  5406.7  533.43
#Mann=7,-1,0
  4569.6     0.1       0  4762.9    0.16       0  4963.2    0.12       0
  4996.6    0.07       0  5002.8    0.12       0  5063.4    0.16       0
  5108.7     0.1       0
Bank Sta=4996.6,5002.8
Exp/Cntr=0.3,0.1

Type RM Length L Ch R = 1,2111,147,147,147
BEGIN DESCRIPTION:
Mapping XS b28da4bb
END DESCRIPTION:
XS GIS Cut Line= 4
      2025226.32     13519177.92      2025359.59     13519207.95
      2025575.57     13519260.03      2025830.26     13519115.56
#Sta/Elev= 30
  4693.2  531.05  4722.6  530.65  4743.1  529.35  4791.4  528.94  4845.7  526.28
  4896.1  525.22  4923.4  525.18  4928.5  524.59  4958.8  524.95  4966.0  524.32
  4986.5  522.94  4987.0  522.14  4992.3  522.14  4992.8  522.94  5020.5  523.38
  5030.8  524.31  5051.9  528.41  5054.6  527.86  5062.8  528.97  5070.4  527.62
  5076.2  528.80  5085.8  527.86  5092.1  526.42  5097.8  527.82  5107.8  526.76
  5113.7  527.62  5127.1  526.57  5223.8  528.67  5318.5  528.84  5344.8  529.59
#Mann=7,-1,0
  4693.2     0.1       0  4896.1    0.07       0  4966.0    0.12       0
  4986.5    0.07       0  4992.8    0.12       0  5107.8     0.1       0
  5127.1    0.16       0
Bank Sta=4986.5,4992.8
Exp/Cntr=0.3,0.1

Type RM Length L Ch R = 1,1964,236,236,236
BEGIN DESCRIPTION:
Mapping XS 3ef73549
END DESCRIPTION:
XS GIS Cut Line= 4
      2025209.01     13519316.83      2025349.87     13519382.25
      2025660.98     13519385.03      2025858.27     13519243.91
#Sta/Elev= 30
  4716.6  531.33  4766.7  529.29  4800.6  528.95  4811.4  528.63  4818.0  527.91
  4846.4  527.73  4863.8  526.80  4871.9  527.03  4941.1  524.83  4997.0  523.65
  5027.0  525.02  5037.0  523.82  5057.0  523.55  5063.9  523.02  5064.4  522.22
  5069.7  522.22  5070.2  523.02  5097.1  525.07  5107.1  526.73  5117.1  526.84
  5127.1  525.68  5137.1  526.80  5157.1  525.65  5178.6  525.92  5237.1  525.71
  5264.2  526.58  5314.5  527.21  5346.4  528.61  5358.8  529.17  5425.6  530.00
#Mann=6,-1,0
  4716.6     0.1       0  4941.1    0.12       0  5063.9    0.07       0
  5070.2    0.12       0  5178.6     0.1       0  5346.4    0.16       0
Bank Sta=5063.9,5070.2
Exp/Cntr=0.3,0.1

Type RM Length L Ch R = 1,1728,38,38,38
BEGIN DESCRIPTION:
Mapping XS 7ea67c90
END DESCRIPTION:
XS GIS Cut Line= 5
      2025188.17     13519403.63      2025478.34     13519587.81
      2025513.76     13519613.50      2025579.73     13519606.56
      2025895.12     13519338.81
#Sta/Elev= 30
  4601.3  531.60  4680.5  529.51  4875.2  527.23  4911.6  525.52  4926.8  523.10
  4945.0  521.91  4947.9  520.88  4977.3  519.88  4984.5  520.62  5018.7  520.81
  5020.6  519.81  5021.1  519.01  5026.4  519.01  5026.9  519.81  5028.3  519.97
  5055.1  522.92  5060.3  524.88  5066.9  525.03  5088.2  521.81  5094.2  521.77
  5116.3  521.73  5130.6  522.86  5152.6  527.84  5166.9  525.46  5192.7  525.21
  5244.9  524.94  5265.7  526.28  5409.5  528.97  5467.0  529.91  5468.8  529.86
#Mann=9,-1,0
  4601.3     0.1       0  4984.5    0.12       0  5020.6    0.07       0
  5026.9    0.12       0  5028.3     0.1       0  5094.2    0.12       0
  5192.7     0.1       0  5409.5    0.16       0  5467.0     0.1       0
Bank Sta=5020.6,5026.9
Exp/Cntr=0.3,0.1

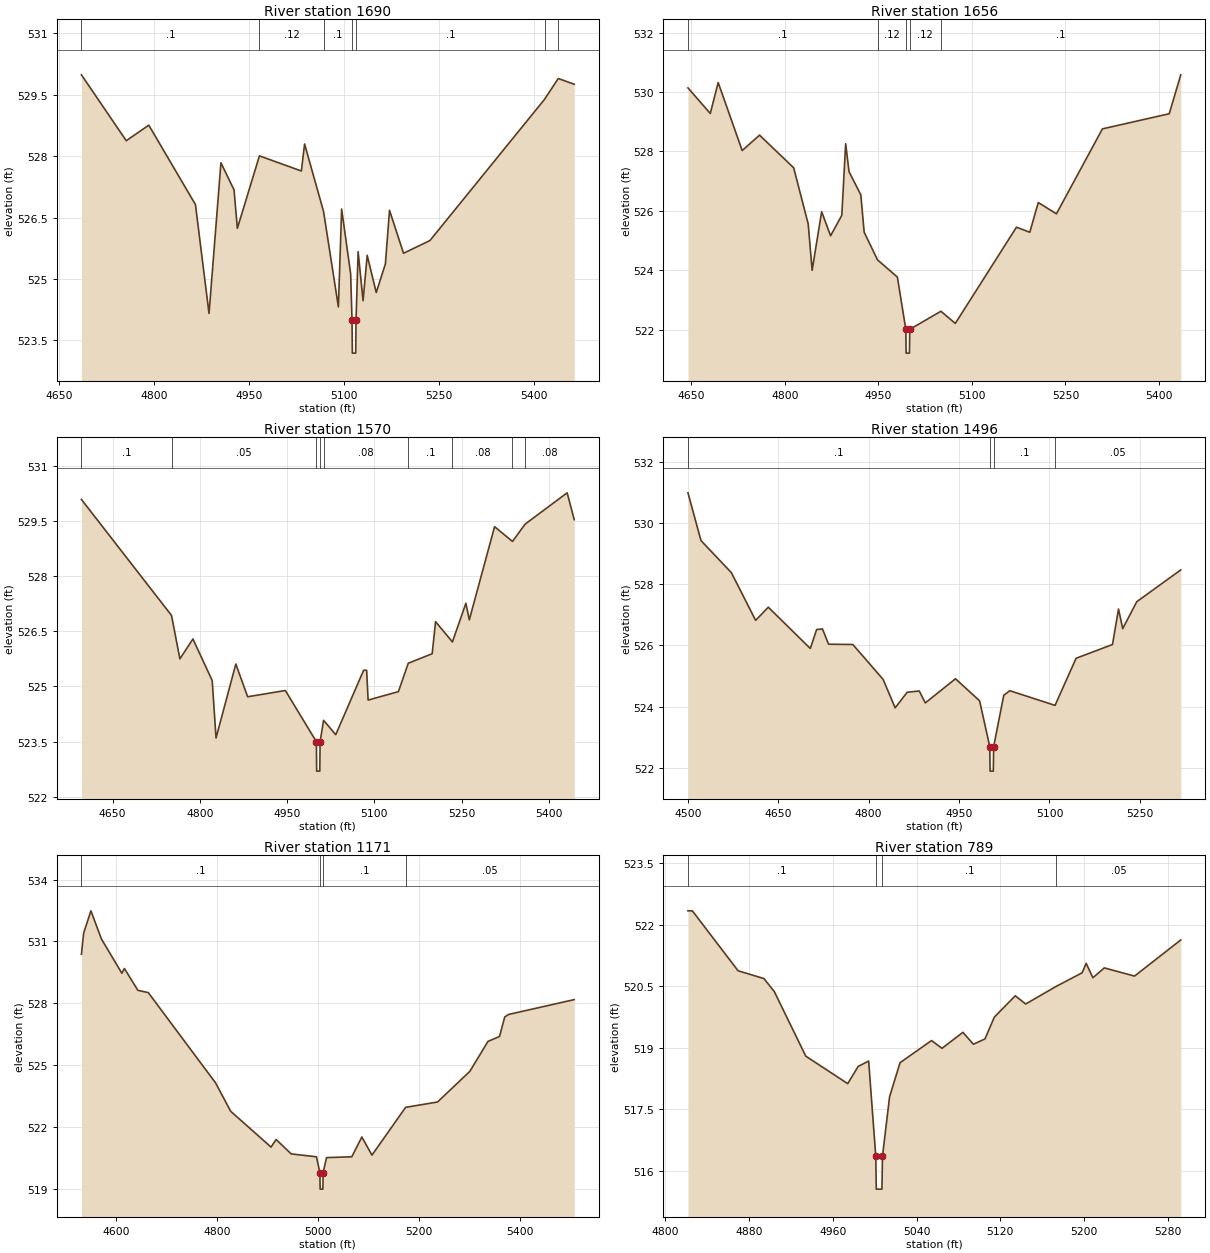
Type RM Length L Ch R = 1,1690,34,34,34
BEGIN DESCRIPTION:
Mapping XS 5a5939f3
END DESCRIPTION:
XS GIS Cut Line= 5
      2025264.53     13519507.78      2025452.65     13519621.84
      2025524.18     13519649.61      2025649.87     13519626.70
      2025920.36     13519400.50
#Sta/Elev= 30
  4685.7  529.99  4756.4  528.38  4791.9  528.76  4865.5  526.82  4886.9  524.16
  4905.7  527.84  4926.3  527.18  4931.6  526.24  4966.4  528.01  5032.5  527.64
  5037.6  528.30  5067.5  526.65  5090.9  524.32  5096.0  526.71  5110.2  525.13
  5112.4  523.99  5112.9  523.19  5118.2  523.19  5118.7  523.99  5122.0  525.67
  5129.8  524.47  5136.3  525.58  5150.6  524.67  5165.0  525.37  5171.5  526.68
  5193.6  525.63  5235.2  525.94  5415.9  529.39  5437.6  529.90  5462.8  529.76
#Mann=7,-1,0
  4685.7     0.1       0  4966.4    0.12       0  5067.5     0.1       0
  5112.4    0.07       0  5118.7     0.1       0  5415.9    0.16       0
  5437.6     0.1       0
Bank Sta=5112.4,5118.7
Exp/Cntr=0.3,0.1

Type RM Length L Ch R = 1,1656,86,86,86
BEGIN DESCRIPTION:
Mapping XS b88c83c7
END DESCRIPTION:
XS GIS Cut Line= 5
      2025233.32     13519549.47      2025388.76     13519630.86
      2025520.71     13519683.64      2025641.54     13519657.25
      2025940.81     13519477.02
#Sta/Elev= 30
  4644.4  530.14  4680.2  529.28  4692.9  530.32  4731.4  528.03  4759.2  528.55
  4814.0  527.45  4837.3  525.56  4843.6  524.00  4858.9  525.97  4873.2  525.16
  4891.2  525.85  4897.4  528.26  4902.8  527.32  4921.7  526.54  4927.1  525.28
  4948.5  524.35  4980.4  523.77  4993.9  522.01  4994.4  521.21  4999.7  521.21
  5000.2  522.01  5050.2  522.62  5073.3  522.21  5171.4  525.45  5192.8  525.28
  5206.4  526.28  5235.5  525.90  5309.3  528.76  5416.5  529.27  5435.0  530.58
#Mann=5,-1,0
  4644.4     0.1       0  4948.5    0.12       0  4993.9    0.07       0
  5000.2    0.12       0  5050.2     0.1       0
Bank Sta=4993.9,5000.2
Exp/Cntr=0.3,0.1

Type RM Length L Ch R = 1,1570,74,74,74
BEGIN DESCRIPTION:
Mapping XS 966bd10b
END DESCRIPTION:
XS GIS Cut Line= 5
      2025212.41     13519632.76      2025400.18     13519726.03
      2025563.37     13519754.50      2025675.87     13519752.42
      2025981.63     13519564.36
#Sta/Elev= 30
  4596.6  530.08  4751.4  526.93  4765.8  525.75  4788.2  526.29  4821.3  525.16
  4827.9  523.60  4861.9  525.61  4882.2  524.72  4947.0  524.89  5000.3  523.50
  5000.8  522.70  5006.2  522.70  5006.7  523.50  5012.7  524.08  5033.6  523.69
  5081.5  525.44  5086.7  525.44  5089.2  524.63  5141.3  524.86  5158.2  525.63
  5199.3  525.89  5205.1  526.76  5234.1  526.21  5257.2  527.26  5263.1  526.81
  5306.5  529.34  5337.3  528.94  5359.0  529.41  5431.2  530.26  5443.4  529.53
#Mann=9,-1,0
  4596.6     0.1       0  4751.4    0.05       0  5000.3    0.04       0
  5006.7    0.05       0  5012.7    0.08       0  5158.2     0.1       0
  5234.1    0.08       0  5337.3     0.1       0  5359.0    0.08       0
Bank Sta=5000.3,5006.7
Exp/Cntr=0.3,0.1

Type RM Length L Ch R = 1,1496,325,325,325
BEGIN DESCRIPTION:
Mapping XS e6399641
END DESCRIPTION:
XS GIS Cut Line= 5
      2025093.59     13519856.22      2025386.98     13519819.09
      2025653.65     13519830.89      2025752.95     13519832.28
      2025907.44     13519851.88
#Sta/Elev= 30
  4500.2  530.99  4521.8  529.43  4572.2  528.38  4612.5  526.82  4633.5  527.25
  4703.2  525.90  4713.7  526.52  4723.4  526.54  4733.5  526.04  4773.8  526.03
  4824.0  524.89  4844.0  523.96  4864.0  524.47  4884.0  524.51  4894.0  524.12
  4944.1  524.91  4984.1  524.19  5001.0  522.69  5001.5  521.89  5006.9  521.89
  5007.4  522.69  5024.2  524.37  5034.2  524.52  5109.3  524.04  5144.2  525.58
  5204.6  526.03  5214.6  527.19  5221.6  526.55  5244.9  527.43  5317.9  528.47
#Mann=4,-1,0
  4500.2     0.1       0  5001.0    0.07       0  5007.4     0.1       0
  5109.3    0.05       0
Bank Sta=5001,5007.4
Exp/Cntr=0.3,0.1

Type RM Length L Ch R = 1,1171,382,382,382
BEGIN DESCRIPTION:
Mapping XS b19e497e
END DESCRIPTION:
XS GIS Cut Line= 4
      2024986.78     13520028.62      2025212.45     13520087.65
      2025715.93     13520087.65      2025948.52     13520028.63
#Sta/Elev= 30
  4531.5  530.37  4535.9  531.40  4550.3  532.48  4571.0  531.12  4611.6  529.45
  4616.7  529.68  4643.4  528.62  4664.0  528.51  4797.3  524.13  4827.3  522.75
  4907.3  521.01  4917.3  521.38  4947.3  520.68  4997.3  520.54  5004.1  519.77
  5004.6  518.97  5010.0  518.97  5010.5  519.77  5017.3  520.50  5067.3  520.54
  5087.3  521.50  5107.3  520.62  5174.0  522.94  5237.3  523.20  5301.4  524.69
  5337.2  526.14  5360.1  526.38  5370.5  527.33  5378.1  527.45  5508.2  528.17
#Mann=4,-1,0
  4531.5     0.1       0  5004.1    0.07       0  5010.5     0.1       0
  5174.0    0.05       0
Bank Sta=5004.1,5010.5
Exp/Cntr=0.3,0.1

Type RM Length L Ch R = 1,789,155,155,155
BEGIN DESCRIPTION:
Mapping XS 7b95045c
END DESCRIPTION:
XS GIS Cut Line= 4
      2025250.86     13520372.55      2025275.87     13520419.78
      2025598.79     13520434.37      2025637.66     13520348.44
#Sta/Elev= 30
  4821.5  522.34  4825.7  522.34  4869.4  520.88  4894.1  520.69  4904.1  520.37
  4934.1  518.80  4974.2  518.13  4984.2  518.55  4994.2  518.68  5001.0  516.36
  5001.5  515.56  5006.9  515.56  5007.4  516.36  5014.2  517.81  5024.2  518.64
  5054.3  519.18  5064.3  518.99  5084.3  519.38  5094.3  519.09  5105.4  519.22
  5114.3  519.75  5134.3  520.27  5144.3  520.07  5173.5  520.50  5198.2  520.83
  5202.1  521.06  5208.5  520.71  5219.4  520.95  5248.3  520.75  5292.5  521.63
#Mann=4,-1,0
  4821.5     0.1       0  5001.0    0.07       0  5007.4     0.1       0
  5173.5    0.05       0
Bank Sta=5001,5007.4
Exp/Cntr=0.3,0.1

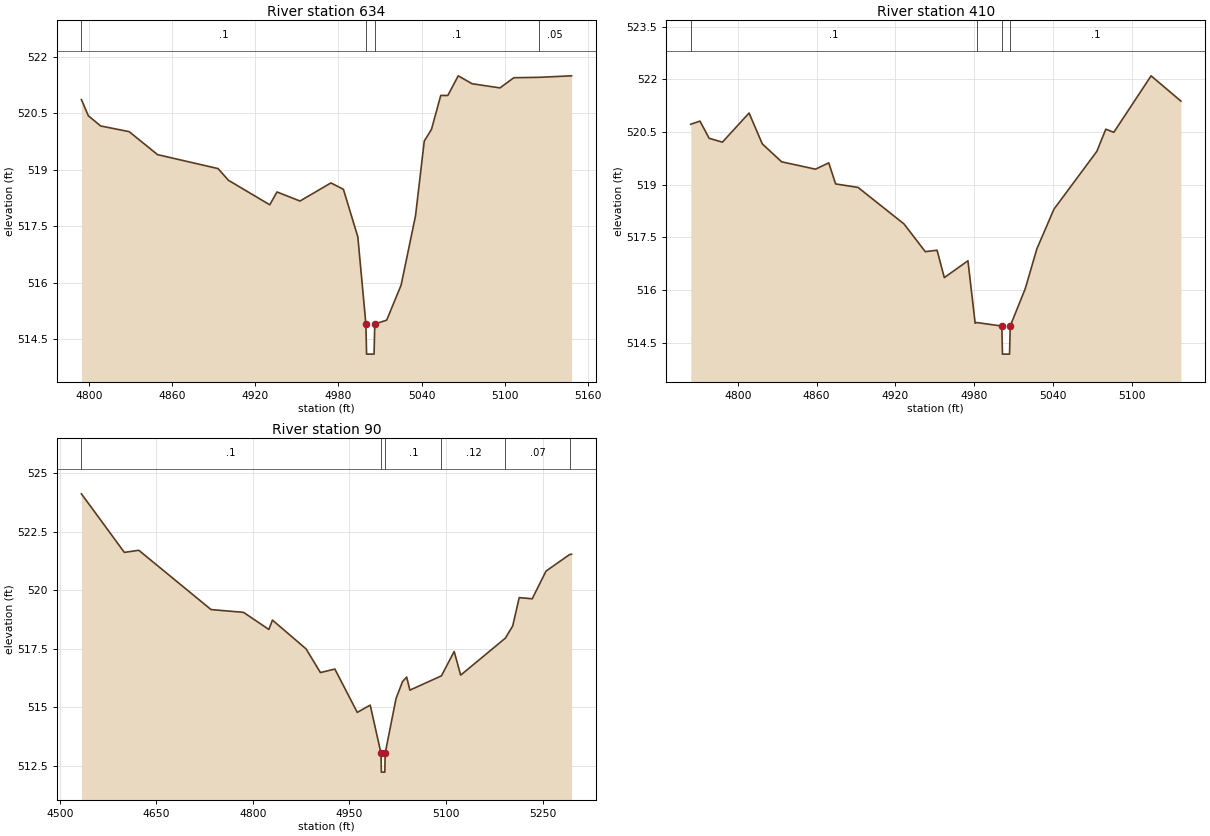
Type RM Length L Ch R = 1,634,224,224,224
BEGIN DESCRIPTION:
Mapping XS d4a2d679
END DESCRIPTION:
XS GIS Cut Line= 4
      2025231.38     13520519.77      2025357.12     13520546.87
      2025484.90     13520583.67      2025576.53     13520589.22
#Sta/Elev= 30
  4794.7  520.86  4799.7  520.43  4808.6  520.16  4829.1  520.01  4849.6  519.40
  4893.2  519.03  4900.7  518.72  4930.5  518.07  4935.7  518.41  4952.3  518.17
  4974.6  518.65  4983.6  518.48  4994.0  517.22  4999.8  514.91  5000.3  514.11
  5005.7  514.11  5006.2  514.91  5014.8  515.01  5025.2  515.94  5035.6  517.78
  5041.9  519.76  5047.1  520.07  5053.8  520.97  5058.9  520.97  5066.4  521.49
  5076.4  521.28  5096.5  521.17  5106.5  521.44  5124.4  521.45  5148.1  521.49
#Mann=4,-1,0
  4794.7     0.1       0  4999.8    0.07       0  5006.2     0.1       0
  5124.4    0.05       0
Bank Sta=4999.8,5006.2
Exp/Cntr=0.3,0.1

Type RM Length L Ch R = 1,410,320,320,320
BEGIN DESCRIPTION:
Mapping XS 319f5ee0
END DESCRIPTION:
XS GIS Cut Line= 5
      2025209.21     13520521.18      2025226.56     13520630.20
      2025270.31     13520658.67      2025416.84     13520721.87
      2025467.51     13520728.81
#Sta/Elev= 30
  4764.1  520.72  4771.1  520.81  4778.1  520.32  4788.2  520.21  4808.5  521.04
  4818.6  520.16  4833.3  519.65  4859.1  519.44  4869.2  519.62  4874.4  519.02
  4891.5  518.92  4926.5  517.88  4942.7  517.09  4951.7  517.13  4957.2  516.35
  4975.2  516.83  4980.7  515.05  4981.9  515.07  5001.0  514.97  5001.5  514.17
  5006.9  514.17  5007.4  514.97  5018.9  516.04  5027.7  517.17  5040.7  518.30
  5073.4  519.95  5080.2  520.58  5086.3  520.49  5114.7  522.10  5137.4  521.38
#Mann=4,-1,0
  4764.1     0.1       0  4981.9    0.07       0  5001.0    0.07       0
  5007.4     0.1       0
Bank Sta=5001,5007.4
Exp/Cntr=0.3,0.1

Type RM Length L Ch R = 1,90,0,0,0
BEGIN DESCRIPTION:
UNT 170 in Lagunillas Cr Wtrshd 1.0
END DESCRIPTION:
XS GIS Cut Line= 4
      2024939.46     13520472.20      2025116.71     13520830.76
      2025310.56     13520847.64      2025475.47     13520823.77
#Sta/Elev= 30
  4533.7  524.12  4600.4  521.62  4622.8  521.71  4735.0  519.18  4785.5  519.06
  4824.8  518.33  4830.4  518.73  4882.6  517.50  4904.9  516.49  4927.3  516.64
  4962.1  514.79  4982.2  515.10  4999.0  513.04  4999.5  512.24  5004.9  512.24
  5005.4  513.04  5022.3  515.38  5032.3  516.10  5038.8  516.30  5043.8  515.74
  5092.8  516.35  5112.6  517.39  5122.7  516.38  5192.1  517.96  5203.5  518.48
  5213.6  519.69  5233.8  519.64  5255.2  520.82  5291.9  521.53  5294.9  521.54
#Mann=6,-1,0
  4533.7     0.1       0  4999.0    0.07       0  5005.4     0.1       0
  5092.8    0.12       0  5192.1    0.07       0  5291.9     0.1       0
Bank Sta=4999,5005.4
Exp/Cntr=0.3,0.1

Chan Stop Cuts=-1