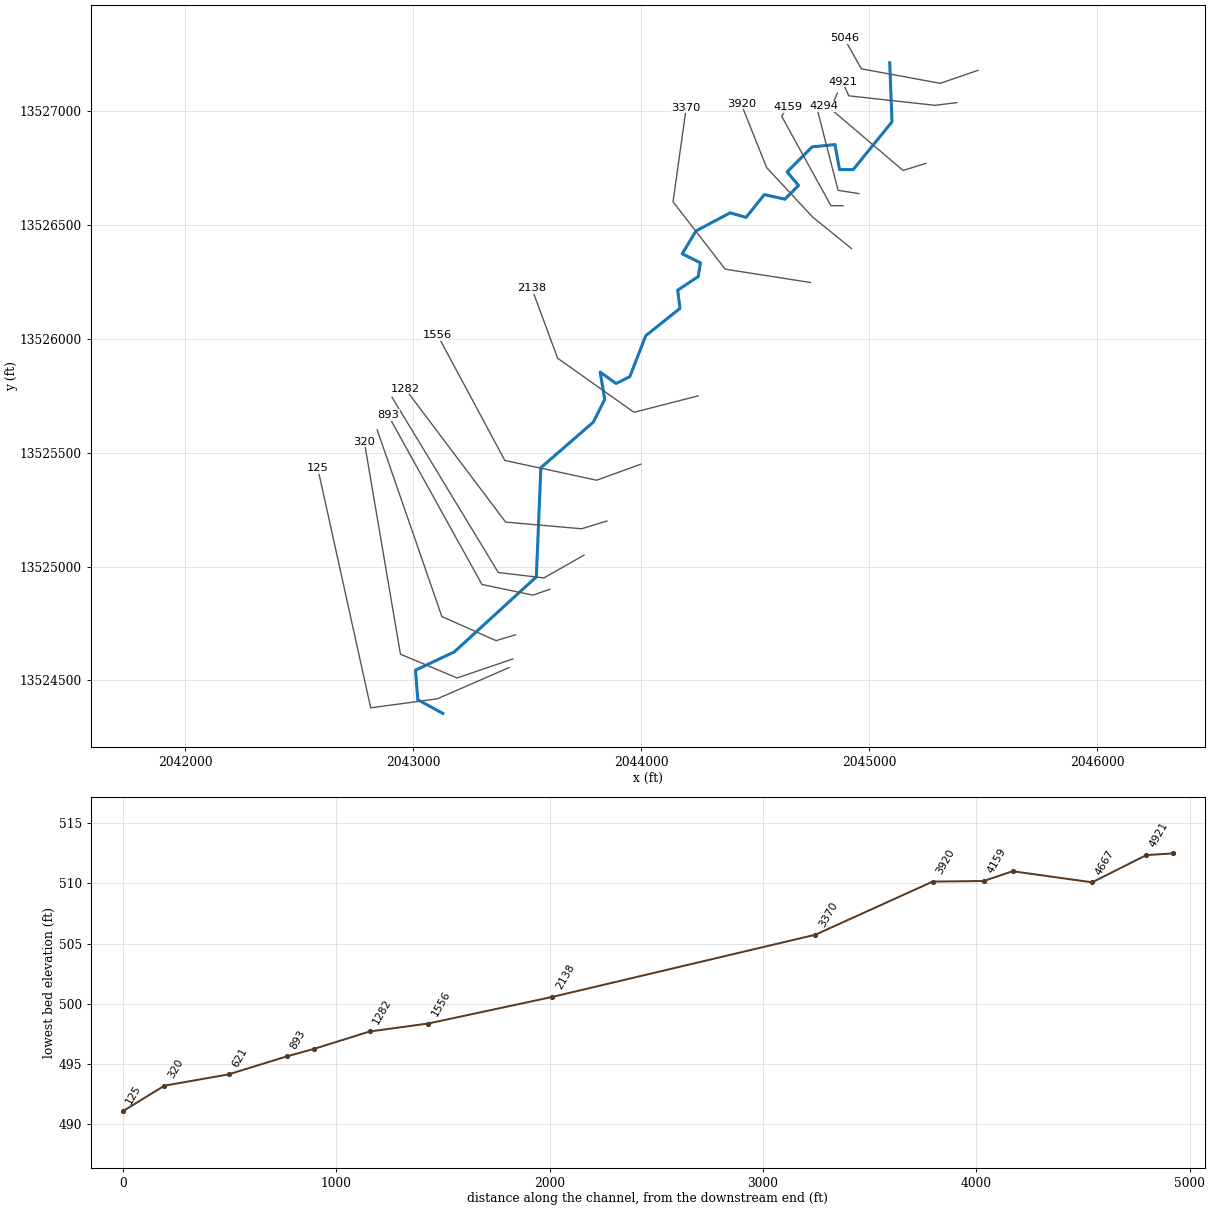
--- UNT 171 in Lagunillas Cr Wtrshd.prj (project) ---

Proj Title=UNT 171 in Lagunillas Cr Wtrshd Base Level Engineering
Current Plan=p01
Default Exp/Contr=0.3,0.1
English Units
Geom File=g01
Flow File=f01
Plan File=p01
BEGIN DESCRIPTION:
UNT 171 in Lagunillas Cr Wtrshd
END DESCRIPTION:

--- UNT 171 in Lagunillas Cr Wtrshd.p01 (plan) ---

Plan Title=Multiple Run
Short Identifier=Multiple
Geom File=g01
Flow File=f01
Subcritical Flow
K Sum by GR= 0
Std Step Tol= 0.01
Critical Tol= 0.01
Num of Std Step Trials= 20
Max Error Tol= 0.3
Flow Tol Ratio= 0.001
Split Flow NTrial= 30
Split Flow Tol= 0.02
Split Flow Ratio= 0.02
Log Output Level= 0
Friction Slope Method= 1
Unsteady Friction Slope Method= 2
Unsteady Bridges Friction Slope Method= 1
Parabolic Critical Depth
Global Vel Dist=  1 , 1 , 1
Global Log Level= 0
CheckData=True
Encroach Param= -1, 0, 0, 0
BEGIN DESCRIPTION:
Multiple Run
END DESCRIPTION:

--- UNT 171 in Lagunillas Cr Wtrshd.f01 (steady flow) ---

Flow Title=Multiple
Number of Profiles=7
Profile Names=10-year,25-year,50-year,1pct_min,100-year,1pct_plu,500-year
River Rch & RM= UNT 171 in Lagun,Reach-1,5046
     145     192     230     138     275     548     396
River Rch & RM= UNT 171 in Lagun,Reach-1,2138
     229     312     379     230     459     916     682
Boundary for River Rch & Prof#=UNT 171 in Lagun,Reach-1,1
Up Type=0
Dn Type=3
Dn Slope=0.005
Boundary for River Rch & Prof#=UNT 171 in Lagun,Reach-1,2
Up Type=0
Dn Type=3
Dn Slope=0.005
Boundary for River Rch & Prof#=UNT 171 in Lagun,Reach-1,3
Up Type=0
Dn Type=3
Dn Slope=0.005
Boundary for River Rch & Prof#=UNT 171 in Lagun,Reach-1,4
Up Type=0
Dn Type=3
Dn Slope=0.005
Boundary for River Rch & Prof#=UNT 171 in Lagun,Reach-1,5
Up Type=0
Dn Type=3
Dn Slope=0.005
Boundary for River Rch & Prof#=UNT 171 in Lagun,Reach-1,6
Up Type=0
Dn Type=3
Dn Slope=0.005
Boundary for River Rch & Prof#=UNT 171 in Lagun,Reach-1,7
Up Type=0
Dn Type=3
Dn Slope=0.005

--- UNT 171 in Lagunillas Cr Wtrshd.g01 (geometry) ---

Geom Title=Existing Conditions

River Reach=UNT 171 in Lagun,Reach-1
Reach XY= 30
      2045090.80     13527214.54      2045100.80     13526954.54
      2044930.80     13526744.54      2044870.80     13526744.54
      2044850.80     13526854.54      2044750.80     13526844.54
      2044640.80     13526734.54      2044690.80     13526674.54
      2044630.80     13526614.54      2044540.80     13526634.54
      2044460.80     13526534.54      2044390.80     13526554.54
      2044240.80     13526474.54      2044180.80     13526374.54
      2044260.80     13526334.54      2044250.80     13526274.54
      2044160.80     13526214.54      2044170.80     13526134.54
      2044020.80     13526014.54      2043950.80     13525834.54
      2043890.80     13525804.54      2043820.80     13525854.54
      2043840.80     13525734.54      2043790.80     13525634.54
      2043560.80     13525434.54      2043540.80     13524954.54
      2043180.80     13524624.54      2043010.80     13524544.54
      2043020.80     13524414.54      2043130.80     13524354.54

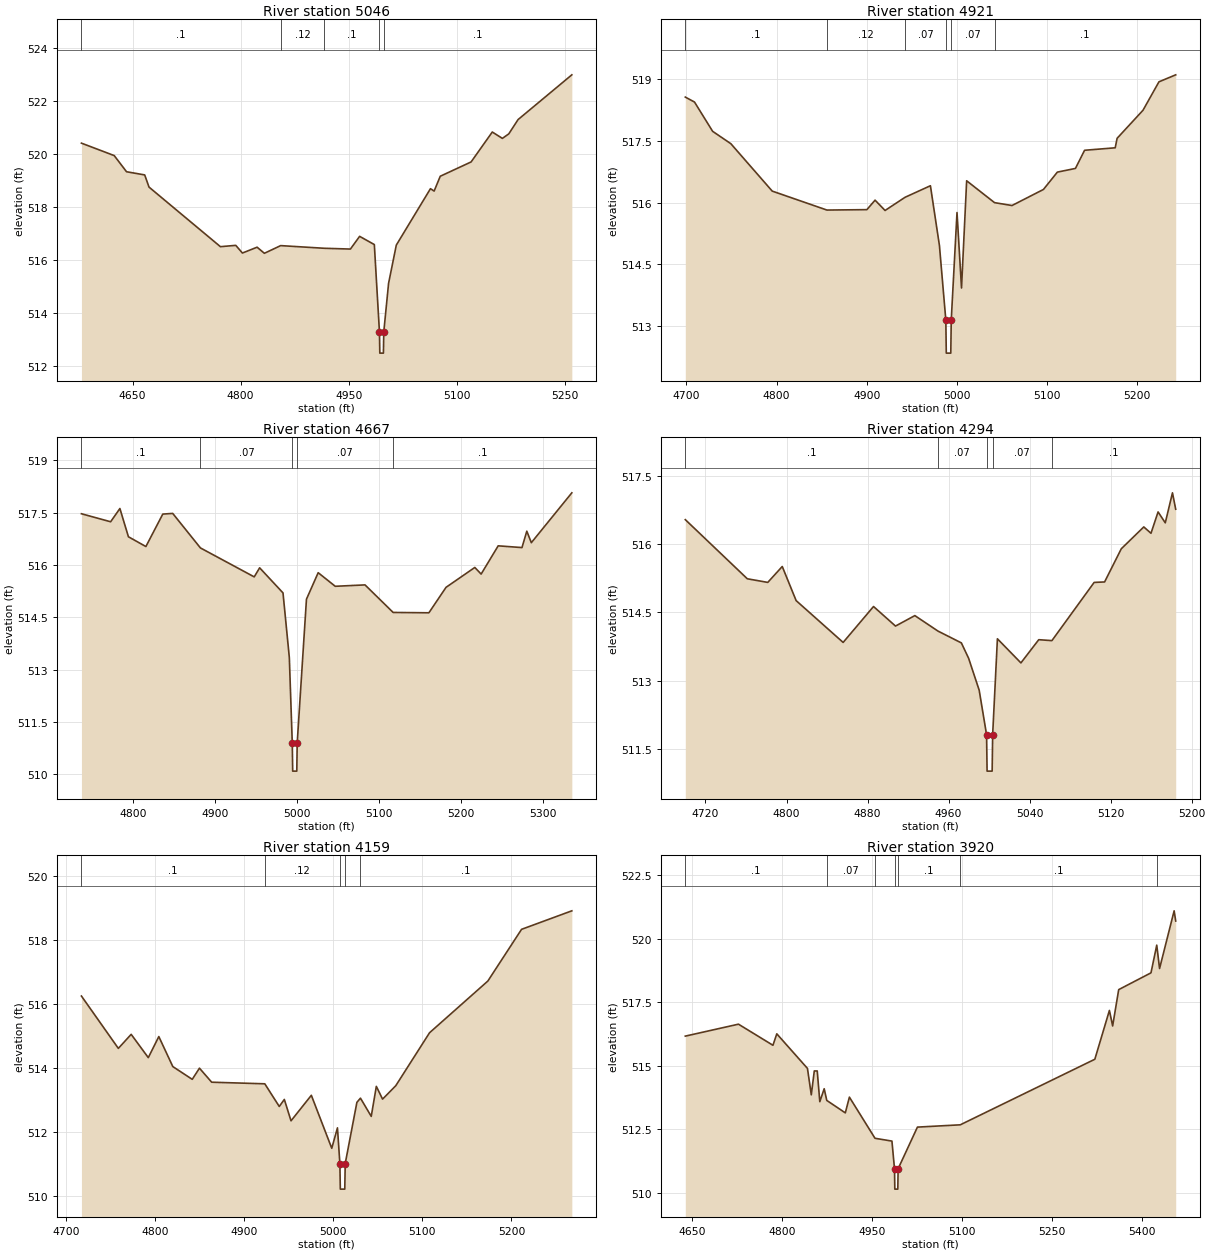
Type RM Length L Ch R = 1,5046,125,125,125
BEGIN DESCRIPTION:
UNT 171 in Lagunillas Cr Wtrshd 2.0
END DESCRIPTION:
XS GIS Cut Line= 4
      2045477.99     13527180.93      2045312.63     13527123.64
      2044966.28     13527187.44      2044891.55     13527321.43
#Sta/Elev= 30
  4579.1  520.42  4624.6  519.95  4641.7  519.34  4666.9  519.22  4672.9  518.76
  4772.0  516.51  4793.3  516.56  4802.5  516.27  4822.9  516.49  4833.0  516.26
  4855.6  516.55  4915.9  516.45  4952.4  516.42  4965.2  516.90  4985.6  516.59
  4992.7  513.29  4993.2  512.49  4998.2  512.49  4998.7  513.29  5005.4  515.13
  5016.1  516.57  5063.5  518.70  5068.6  518.61  5077.1  519.17  5119.9  519.71
  5149.3  520.84  5163.3  520.60  5172.2  520.77  5185.1  521.31  5259.7  523.00
#Mann=5,-1,0
  4579.1     0.1       0  4855.6    0.12       0  4915.9     0.1       0
  4992.7    0.07       0  4998.7     0.1       0
Bank Sta=4992.7,4998.7
Exp/Cntr=0.3,0.1

Type RM Length L Ch R = 1,4921,254,254,254
BEGIN DESCRIPTION:
Mapping XS 38512ee5
END DESCRIPTION:
XS GIS Cut Line= 4
      2045385.09     13527038.83      2045288.76     13527027.11
      2044911.16     13527068.78      2044883.80     13527130.00
#Sta/Elev= 30
  4698.8  518.56  4709.0  518.44  4729.1  517.73  4749.3  517.43  4795.2  516.28
  4855.9  515.82  4900.2  515.83  4909.3  516.06  4920.4  515.81  4942.6  516.13
  4970.7  516.41  4980.7  514.96  4987.8  513.15  4988.3  512.35  4993.3  512.35
  4993.8  513.15  5000.2  515.76  5005.2  513.93  5010.9  516.53  5041.8  516.00
  5061.2  515.93  5096.1  516.32  5111.5  516.74  5131.6  516.83  5141.7  517.27
  5175.7  517.33  5177.8  517.56  5206.5  518.24  5224.2  518.93  5242.8  519.10
#Mann=6,-1,0
  4698.8     0.1       0  4855.9    0.12       0  4942.6    0.07       0
  4987.8    0.07       0  4993.8    0.07       0  5041.8     0.1       0
Bank Sta=4987.8,4993.8
Exp/Cntr=0.3,0.1

Type RM Length L Ch R = 1,4667,373,373,373
BEGIN DESCRIPTION:
Mapping XS b317c8f0
END DESCRIPTION:
XS GIS Cut Line= 4
      2045249.73     13526771.91      2045149.44     13526740.65
      2044831.73     13527011.48      2044861.30     13527080.92
#Sta/Elev= 30
  4737.1  517.47  4772.7  517.24  4784.0  517.62  4794.4  516.81  4815.7  516.53
  4836.3  517.46  4848.4  517.48  4882.2  516.49  4947.8  515.66  4954.4  515.92
  4982.9  515.20  4990.6  513.35  4994.2  510.89  4994.7  510.09  4999.7  510.09
  5000.2  510.89  5011.5  515.02  5025.8  515.78  5046.6  515.39  5082.9  515.43
  5117.2  514.64  5160.8  514.63  5181.7  515.36  5216.8  515.93  5224.5  515.74
  5245.3  516.55  5274.3  516.50  5280.2  516.97  5285.7  516.64  5335.1  518.07
#Mann=5,-1,0
  4737.1     0.1       0  4882.2    0.07       0  4994.2    0.07       0
  5000.2    0.07       0  5117.2     0.1       0
Bank Sta=4994.2,5000.2
Exp/Cntr=0.3,0.1

Type RM Length L Ch R = 1,4294,135,135,135
BEGIN DESCRIPTION:
Mapping XS 52e5e66d
END DESCRIPTION:
XS GIS Cut Line= 4
      2044955.42     13526639.09      2044864.28     13526653.41
      2044775.74     13526998.46      2044800.92     13527023.64
#Sta/Elev= 30
  4700.1  516.54  4761.3  515.24  4781.5  515.16  4795.8  515.51  4809.5  514.76
  4855.9  513.84  4885.9  514.63  4907.6  514.20  4926.7  514.43  4949.5  514.09
  4972.6  513.83  4979.8  513.49  4990.2  512.79  4997.5  511.81  4998.0  511.01
  5003.0  511.01  5003.5  511.81  5008.2  513.92  5031.4  513.39  5049.0  513.90
  5062.0  513.88  5103.7  515.16  5114.0  515.17  5130.5  515.90  5152.7  516.38
  5159.8  516.24  5166.8  516.71  5173.9  516.47  5181.0  517.13  5184.2  516.77
#Mann=5,-1,0
  4700.1     0.1       0  4949.5    0.07       0  4997.5    0.07       0
  5003.5    0.07       0  5062.0     0.1       0
Bank Sta=4997.5,5003.5
Exp/Cntr=0.3,0.1

Type RM Length L Ch R = 1,4159,239,239,239
BEGIN DESCRIPTION:
Mapping XS 5422f58e
END DESCRIPTION:
XS GIS Cut Line= 4
      2044886.37     13526585.70      2044833.03     13526585.70
      2044616.89     13526978.93      2044642.93     13527019.30
#Sta/Elev= 30
  4717.6  516.25  4759.0  514.61  4773.4  515.05  4792.6  514.32  4804.4  514.98
  4820.1  514.04  4841.9  513.64  4850.0  513.99  4863.7  513.55  4923.3  513.50
  4939.5  512.79  4945.2  513.01  4952.7  512.34  4975.5  513.14  4998.4  511.48
  5004.8  512.12  5007.5  511.00  5008.0  510.20  5013.0  510.20  5013.5  511.00
  5026.6  512.92  5030.6  513.05  5042.7  512.48  5048.4  513.42  5055.4  513.02
  5070.2  513.44  5108.1  515.10  5173.5  516.72  5211.3  518.34  5267.7  518.92
#Mann=5,-1,0
  4717.6     0.1       0  4923.3    0.12       0  5007.5    0.07       0
  5013.5    0.12       0  5030.6     0.1       0
Bank Sta=5007.5,5013.5
Exp/Cntr=0.3,0.1

Type RM Length L Ch R = 1,3920,550,550,550
BEGIN DESCRIPTION:
Mapping XS 265fb8af
END DESCRIPTION:
XS GIS Cut Line= 4
      2044923.08     13526397.68      2044752.30     13526536.22
      2044550.91     13526753.24      2044439.34     13527033.26
#Sta/Elev= 30
  4638.7  516.17  4727.3  516.64  4784.8  515.81  4791.2  516.26  4842.3  514.90
  4848.7  513.86  4853.7  514.80  4858.6  514.80  4862.9  513.59  4870.2  514.10
  4874.5  513.64  4905.4  513.15  4912.2  513.77  4954.9  512.15  4983.1  512.04
  4987.4  510.95  4987.9  510.15  4992.9  510.15  4993.4  510.95  5025.6  512.59
  5097.0  512.68  5321.3  515.26  5345.6  517.18  5351.0  516.57  5361.1  518.00
  5414.9  518.66  5424.5  519.75  5429.2  518.83  5453.5  521.10  5456.1  520.70
#Mann=7,-1,0
  4638.7     0.1       0  4874.5    0.07       0  4954.9     0.1       0
  4987.4    0.07       0  4993.4     0.1       0  5097.0     0.1       0
  5424.5    0.05       0
Bank Sta=4987.4,4993.4
Exp/Cntr=0.3,0.1

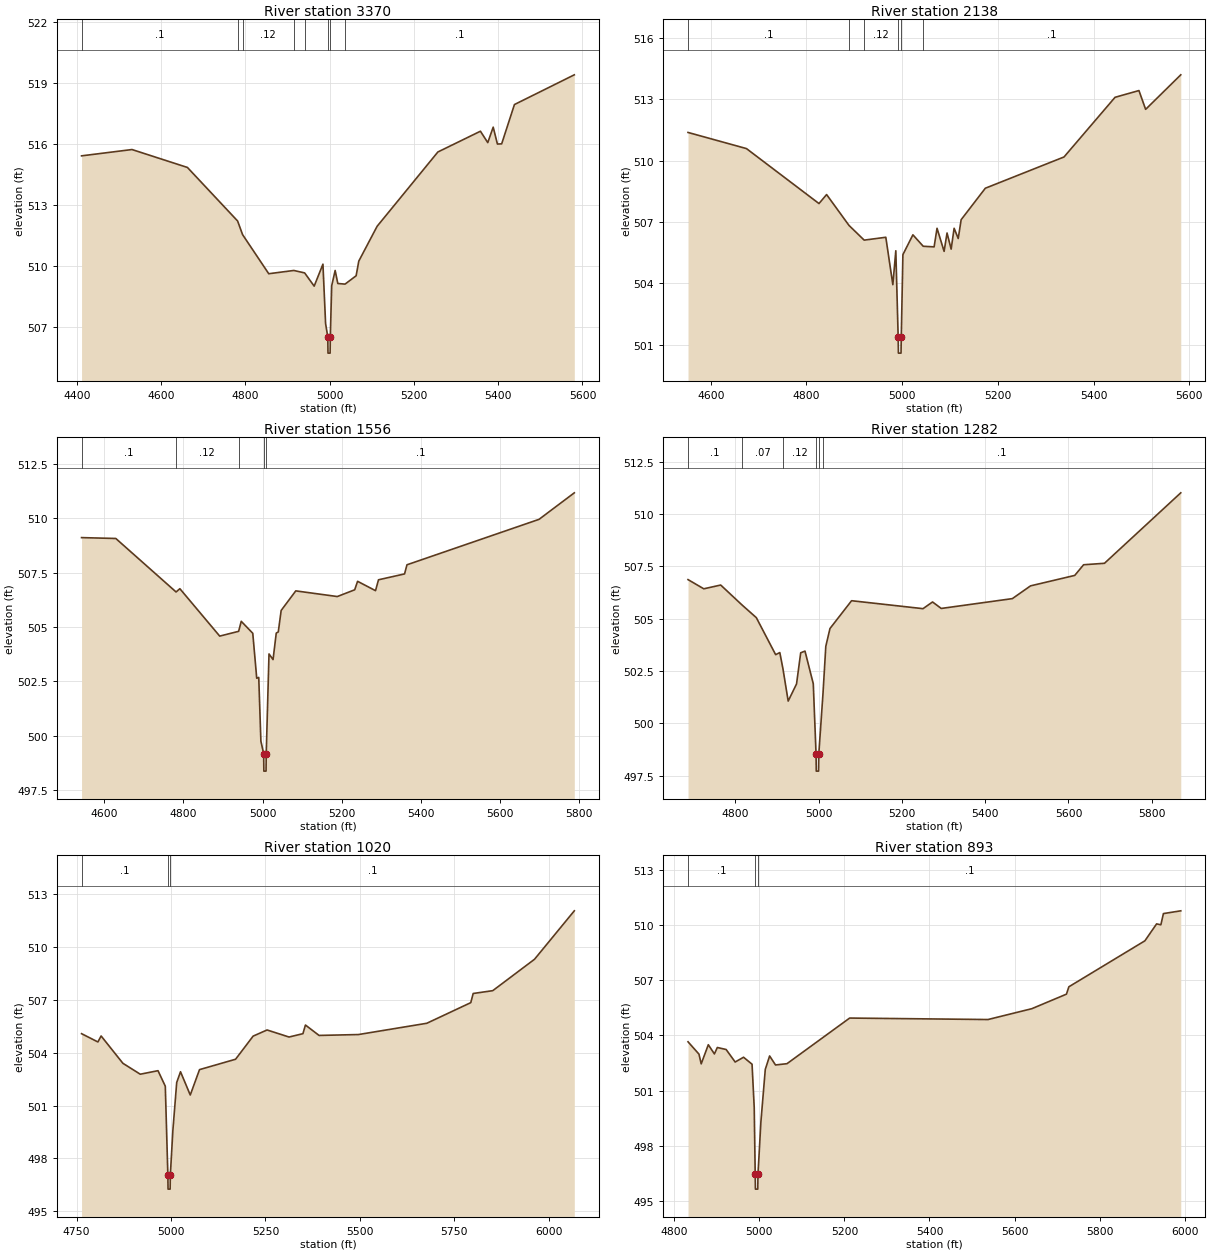
Type RM Length L Ch R = 1,3370,1232,1232,1232
BEGIN DESCRIPTION:
Mapping XS ef0900c3
END DESCRIPTION:
XS GIS Cut Line= 4
      2044743.29     13526248.29      2044369.31     13526306.80
      2044140.47     13526603.16      2044198.12     13527015.69
#Sta/Elev= 30
  4411.2  515.43  4530.9  515.74  4662.5  514.86  4781.6  512.23  4793.4  511.56
  4855.5  509.64  4915.0  509.80  4940.7  509.68  4963.3  509.03  4984.1  510.11
  4990.4  507.19  4995.6  506.54  4996.1  505.74  5001.1  505.74  5001.6  506.54
  5004.9  509.05  5013.1  509.80  5019.4  509.16  5036.6  509.13  5062.9  509.54
  5069.2  510.26  5112.7  511.97  5256.9  515.62  5357.9  516.64  5375.3  516.08
  5388.2  516.84  5398.2  516.01  5408.3  516.02  5438.6  517.95  5580.7  519.41
#Mann=8,-1,0
  4411.2     0.1       0  4781.6    0.07       0  4793.4    0.12       0
  4915.0    0.07       0  4940.7    0.12       0  4995.6    0.07       0
  5001.6    0.12       0  5036.6     0.1       0
Bank Sta=4995.6,5001.6
Exp/Cntr=0.3,0.1

Type RM Length L Ch R = 1,2138,582,582,582
BEGIN DESCRIPTION:
Mapping XS 359954f0
END DESCRIPTION:
XS GIS Cut Line= 4
      2044249.97     13525749.99      2043969.24     13525677.71
      2043634.17     13525915.56      2043520.42     13526223.85
#Sta/Elev= 30
  4552.6  511.38  4674.7  510.59  4826.2  507.90  4842.1  508.34  4888.9  506.83
  4920.6  506.11  4965.8  506.25  4980.5  503.93  4986.7  505.59  4991.6  501.38
  4992.1  500.58  4997.6  500.58  4998.1  501.38  5001.5  505.40  5022.4  506.37
  5043.9  505.81  5066.7  505.78  5072.8  506.69  5087.6  505.56  5093.7  506.46
  5102.3  505.67  5108.5  506.69  5117.1  506.19  5123.2  507.11  5173.7  508.65
  5338.1  510.18  5444.7  513.10  5494.6  513.43  5508.6  512.51  5582.0  514.20
#Mann=6,-1,0
  4552.6     0.1       0  4888.9    0.07       0  4920.6    0.12       0
  4991.6    0.07       0  4998.1    0.12       0  5043.9     0.1       0
Bank Sta=4991.6,4998.1
Exp/Cntr=0.3,0.1

Type RM Length L Ch R = 1,1556,274,274,274
BEGIN DESCRIPTION:
Mapping XS 3e0e8e43
END DESCRIPTION:
XS GIS Cut Line= 4
      2043999.97     13525449.99      2043805.40     13525379.39
      2043402.62     13525466.20      2043107.44     13526017.54
#Sta/Elev= 30
  4542.8  509.11  4629.3  509.07  4781.5  506.61  4791.1  506.76  4891.7  504.58
  4939.5  504.80  4946.1  505.26  4975.2  504.71  4985.2  502.64  4990.3  502.68
  4995.7  499.75  5002.7  499.17  5003.2  498.37  5008.7  498.37  5009.2  499.17
  5016.2  503.76  5026.4  503.50  5034.5  504.72  5039.6  504.77  5046.9  505.76
  5083.8  506.66  5188.7  506.40  5232.6  506.71  5239.9  507.10  5285.2  506.67
  5292.7  507.17  5358.5  507.44  5364.6  507.86  5698.1  509.95  5787.2  511.17
#Mann=5,-1,0
  4542.8     0.1       0  4781.5    0.12       0  4939.5     0.1       0
  5002.7    0.07       0  5009.2     0.1       0
Bank Sta=5002.7,5009.2
Exp/Cntr=0.3,0.1

Type RM Length L Ch R = 1,1282,262,262,262
BEGIN DESCRIPTION:
Mapping XS f67982c2
END DESCRIPTION:
XS GIS Cut Line= 4
      2043849.98     13525199.99      2043739.43     13525165.85
      2043406.09     13525195.36      2042965.42     13525781.55
#Sta/Elev= 30
  4686.1  506.87  4724.0  506.43  4764.6  506.61  4816.2  505.65  4850.2  505.05
  4896.6  503.28  4906.6  503.38  4914.2  502.60  4926.7  501.06  4946.8  501.88
  4956.8  503.37  4967.1  503.45  4987.0  501.89  4993.7  498.51  4994.2  497.71
  4999.7  497.71  5000.2  498.51  5010.4  501.44  5017.1  503.68  5027.1  504.53
  5079.0  505.86  5250.6  505.48  5273.5  505.80  5294.4  505.49  5465.2  505.96
  5508.9  506.57  5615.1  507.07  5636.4  507.58  5686.5  507.65  5869.8  511.02
#Mann=6,-1,0
  4686.1     0.1       0  4816.2    0.07       0  4914.2    0.12       0
  4993.7    0.07       0  5000.2    0.12       0  5010.4     0.1       0
Bank Sta=4993.7,5000.2
Exp/Cntr=0.3,0.1

Type RM Length L Ch R = 1,1020,127,127,127
BEGIN DESCRIPTION:
Mapping XS 64bed112
END DESCRIPTION:
XS GIS Cut Line= 4
      2043750.04     13525050.02      2043574.00     13524949.80
      2043373.83     13524973.72      2042907.81     13525744.07
#Sta/Elev= 30
  4763.3  505.08  4806.6  504.61  4815.1  504.95  4872.7  503.40  4918.7  502.78
  4965.7  502.98  4985.0  502.10  4991.8  497.06  4992.3  496.26  4997.8  496.26
  4998.3  497.06  5005.1  499.60  5015.2  502.31  5025.3  502.92  5051.1  501.60
  5075.6  503.04  5171.1  503.63  5217.5  504.94  5254.4  505.29  5312.6  504.89
  5349.4  505.08  5356.0  505.57  5392.1  504.98  5496.2  505.03  5677.3  505.67
  5793.7  506.84  5800.1  507.36  5851.9  507.52  5962.4  509.30  6067.8  512.05
#Mann=3,-1,0
  4763.3     0.1       0  4991.8    0.07       0  4998.3     0.1       0
Bank Sta=4991.8,4998.3
Exp/Cntr=0.3,0.1

Type RM Length L Ch R = 1,893,272,272,272
BEGIN DESCRIPTION:
Mapping XS 86f8a9ff
END DESCRIPTION:
XS GIS Cut Line= 4
      2043599.98     13524899.99      2043526.32     13524874.18
      2043302.36     13524921.06      2042890.42     13525665.98
#Sta/Elev= 30
  4832.5  503.65  4858.2  502.98  4863.5  502.45  4880.2  503.49  4894.5  502.99
  4901.4  503.34  4922.1  503.23  4943.3  502.55  4963.0  502.81  4983.0  502.43
  4988.1  500.07  4990.4  496.44  4990.9  495.64  4996.4  495.64  4996.9  496.44
  5003.8  499.30  5014.1  502.15  5024.3  502.88  5038.1  502.39  5065.1  502.46
  5212.4  504.94  5537.5  504.86  5640.6  505.45  5721.9  506.24  5727.6  506.64
  5906.3  509.14  5933.8  510.06  5943.8  510.01  5949.8  510.62  5990.6  510.77
#Mann=3,-1,0
  4832.5     0.1       0  4990.4    0.07       0  4996.9     0.1       0
Bank Sta=4990.4,4996.9
Exp/Cntr=0.3,0.1

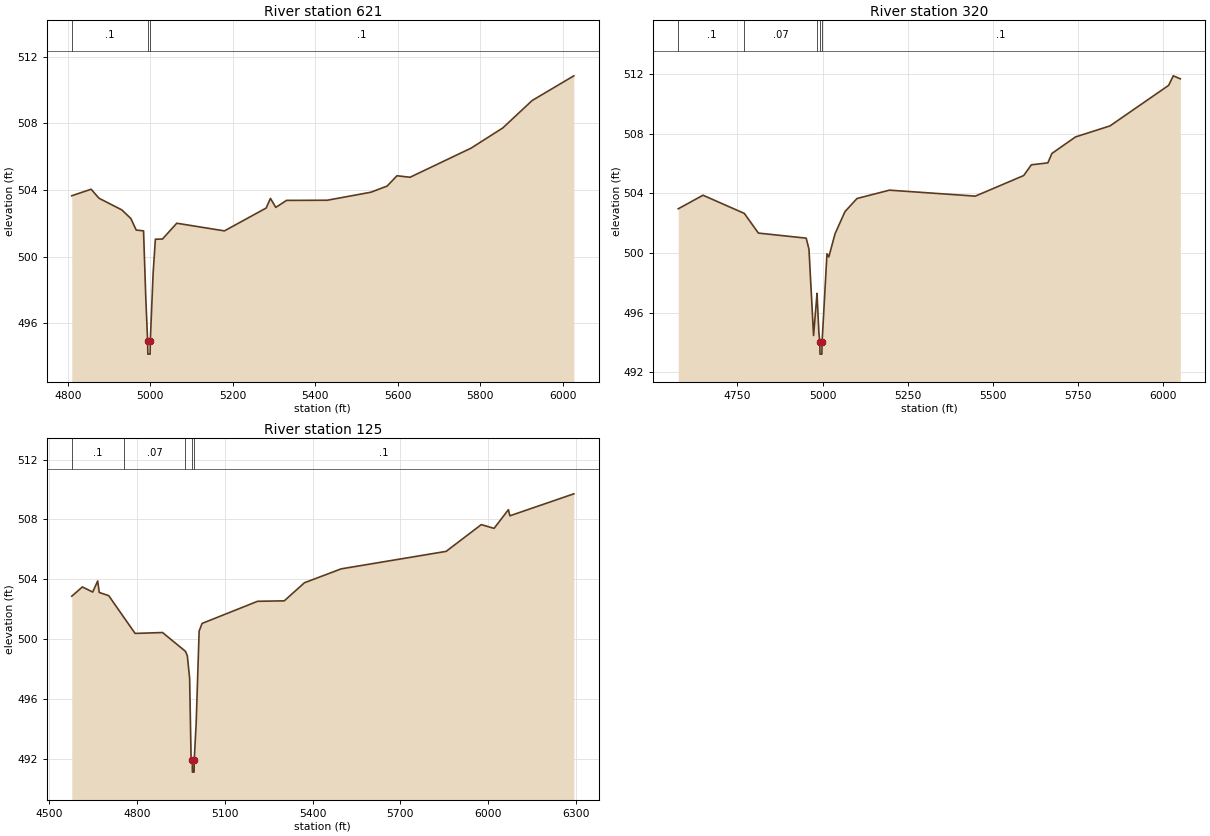
Type RM Length L Ch R = 1,621,301,301,301
BEGIN DESCRIPTION:
Mapping XS d7c39e0b
END DESCRIPTION:
XS GIS Cut Line= 4
      2043449.97     13524699.99      2043364.28     13524674.24
      2043126.43     13524780.14      2042842.82     13525600.47
#Sta/Elev= 30
  4809.2  503.66  4856.2  504.05  4875.2  503.51  4930.7  502.81  4952.6  502.29
  4965.5  501.60  4983.3  501.55  4988.8  497.48  4993.2  494.95  4993.7  494.15
  4999.2  494.15  4999.7  494.95  5006.5  499.00  5012.0  501.05  5029.2  501.06
  5063.9  502.01  5179.4  501.55  5280.6  502.92  5291.1  503.50  5304.1  502.96
  5330.0  503.38  5428.8  503.39  5534.5  503.87  5574.1  504.24  5598.0  504.86
  5629.7  504.77  5777.9  506.52  5854.6  507.73  5926.0  509.38  6027.0  510.86
#Mann=3,-1,0
  4809.2     0.1       0  4993.2    0.07       0  4999.7     0.1       0
Bank Sta=4993.2,4999.7
Exp/Cntr=0.3,0.1

Type RM Length L Ch R = 1,320,195,195,195
BEGIN DESCRIPTION:
Mapping XS 03fb5ee5
END DESCRIPTION:
XS GIS Cut Line= 4
      2043437.87     13524593.89      2043193.28     13524510.18
      2042944.83     13524614.73      2042786.26     13525548.79
#Sta/Elev= 30
  4575.9  502.96  4648.7  503.87  4770.1  502.65  4811.5  501.33  4951.9  500.99
  4960.1  500.25  4973.6  494.46  4983.0  497.07  4983.8  497.29  4989.3  494.63
  4992.0  494.01  4992.5  493.21  4998.1  493.21  4998.6  494.01  5013.0  499.94
  5018.4  499.73  5036.7  501.28  5065.9  502.77  5101.2  503.65  5196.6  504.21
  5449.1  503.81  5591.1  505.19  5613.6  505.91  5662.1  506.04  5674.0  506.67
  5743.3  507.78  5844.7  508.52  6017.1  511.24  6030.7  511.88  6051.4  511.68
#Mann=5,-1,0
  4575.9     0.1       0  4770.1    0.07       0  4983.0     0.1       0
  4992.0    0.07       0  4998.6     0.1       0
Bank Sta=4992,4998.6
Exp/Cntr=0.3,0.1

Type RM Length L Ch R = 1,125,0,0,0
BEGIN DESCRIPTION:
UNT 171 in Lagunillas Cr Wtrshd 1.0
END DESCRIPTION:
XS GIS Cut Line= 4
      2043420.50     13524555.69      2043106.18     13524418.31
      2042814.31     13524378.94      2042582.44     13525430.84
#Sta/Elev= 30
  4577.7  502.86  4613.9  503.48  4649.2  503.14  4666.2  503.88  4671.6  503.11
  4703.8  502.90  4757.6  501.39  4794.1  500.37  4887.7  500.43  4966.1  499.17
  4972.4  498.87  4980.2  497.38  4985.2  492.02  4989.3  491.89  4989.8  491.09
  4995.4  491.09  4995.9  491.89  5002.6  494.37  5012.7  500.53  5022.8  501.04
  5212.4  502.52  5303.4  502.55  5372.3  503.76  5497.9  504.69  5856.3  505.86
  5976.3  507.65  6020.0  507.40  6068.9  508.65  6074.0  508.24  6292.4  509.71
#Mann=5,-1,0
  4577.7     0.1       0  4757.6    0.07       0  4966.1     0.1       0
  4989.3    0.07       0  4995.9     0.1       0
Bank Sta=4989.3,4995.9
Exp/Cntr=0.3,0.1

Chan Stop Cuts=-1