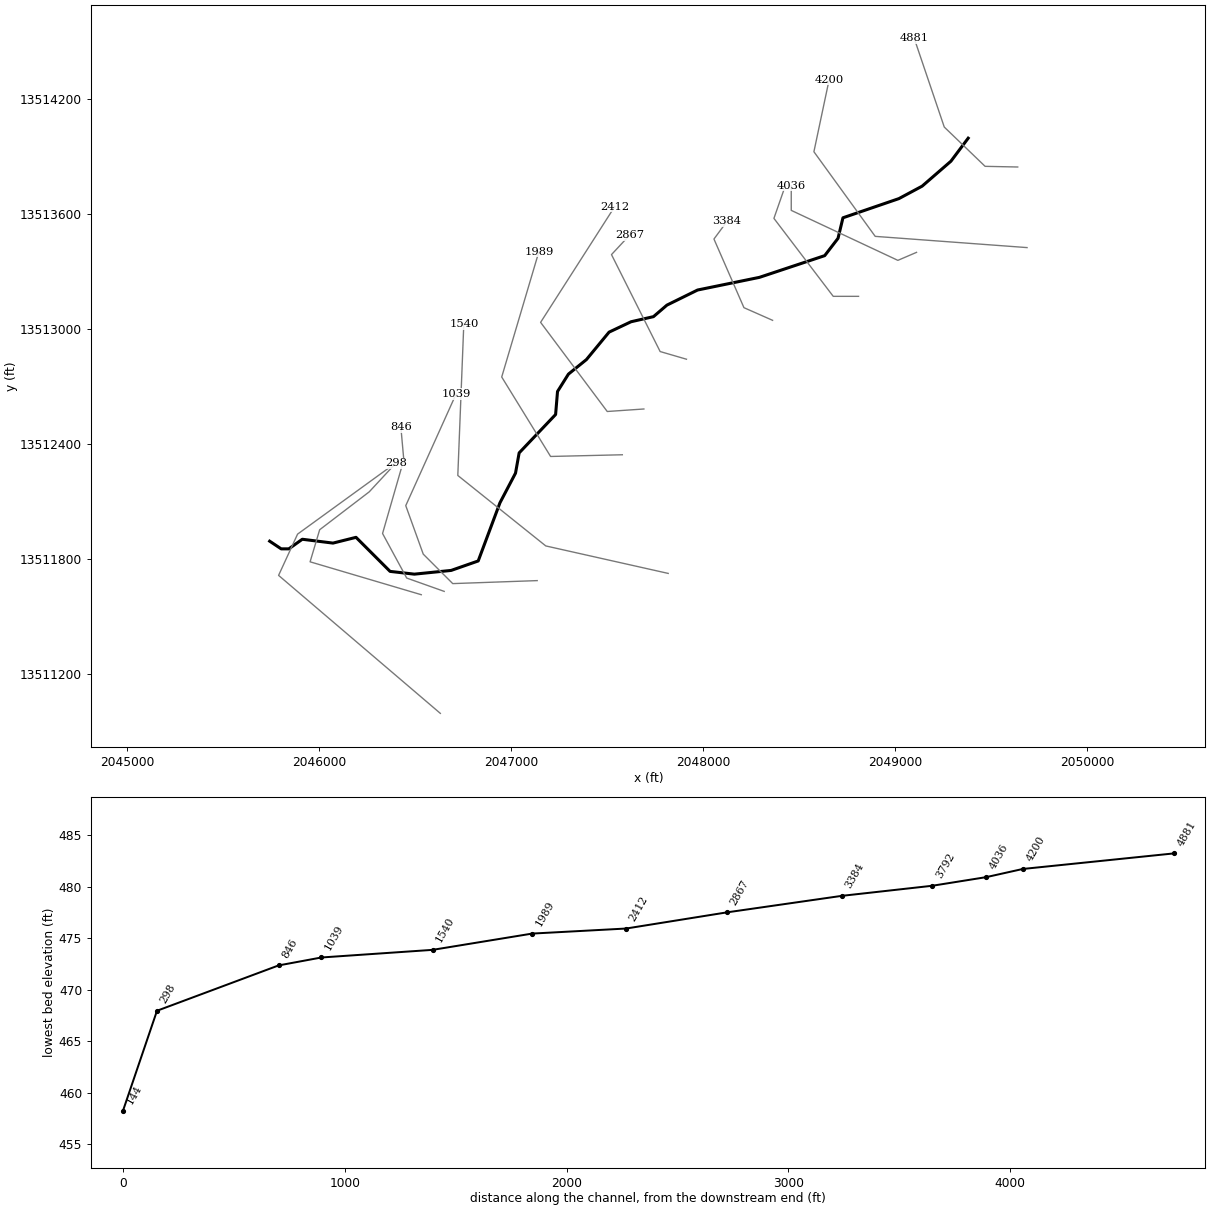
--- UNT 174 in Lagunillas Cr Wtrshd.prj (project) ---

Proj Title=UNT 174 in Lagunillas Cr Wtrshd Base Level Engineering
Current Plan=p01
Default Exp/Contr=0.3,0.1
English Units
Geom File=g01
Flow File=f01
Plan File=p01
BEGIN DESCRIPTION:
UNT 174 in Lagunillas Cr Wtrshd
END DESCRIPTION:

--- UNT 174 in Lagunillas Cr Wtrshd.p01 (plan) ---

Plan Title=Multiple Run
Short Identifier=Multiple
Geom File=g01
Flow File=f01
Subcritical Flow
K Sum by GR= 0
Std Step Tol= 0.01
Critical Tol= 0.01
Num of Std Step Trials= 20
Max Error Tol= 0.3
Flow Tol Ratio= 0.001
Split Flow NTrial= 30
Split Flow Tol= 0.02
Split Flow Ratio= 0.02
Log Output Level= 0
Friction Slope Method= 1
Unsteady Friction Slope Method= 2
Unsteady Bridges Friction Slope Method= 1
Parabolic Critical Depth
Global Vel Dist=  1 , 1 , 1
Global Log Level= 0
CheckData=True
Encroach Param= -1, 0, 0, 0
BEGIN DESCRIPTION:
Multiple Run
END DESCRIPTION:

--- UNT 174 in Lagunillas Cr Wtrshd.f01 (steady flow) ---

Flow Title=Multiple
Number of Profiles=7
Profile Names=10-year,25-year,50-year,1pct_min,100-year,1pct_plu,500-year
River Rch & RM= UNT 174 in Lagun,Reach-1,4881
     168     227     274     165     330     658     485
River Rch & RM= UNT 174 in Lagun,Reach-1,3384
     187     253     306     185     370     737     546
Boundary for River Rch & Prof#=UNT 174 in Lagun,Reach-1,1
Up Type=0
Dn Type=3
Dn Slope=0.005
Boundary for River Rch & Prof#=UNT 174 in Lagun,Reach-1,2
Up Type=0
Dn Type=3
Dn Slope=0.005
Boundary for River Rch & Prof#=UNT 174 in Lagun,Reach-1,3
Up Type=0
Dn Type=3
Dn Slope=0.005
Boundary for River Rch & Prof#=UNT 174 in Lagun,Reach-1,4
Up Type=0
Dn Type=3
Dn Slope=0.005
Boundary for River Rch & Prof#=UNT 174 in Lagun,Reach-1,5
Up Type=0
Dn Type=3
Dn Slope=0.005
Boundary for River Rch & Prof#=UNT 174 in Lagun,Reach-1,6
Up Type=0
Dn Type=3
Dn Slope=0.005
Boundary for River Rch & Prof#=UNT 174 in Lagun,Reach-1,7
Up Type=0
Dn Type=3
Dn Slope=0.005

--- UNT 174 in Lagunillas Cr Wtrshd.g01 (geometry) ---

Geom Title=Existing Conditions

River Reach=UNT 174 in Lagun,Reach-1
Reach XY= 30
      2049380.80     13513994.54      2049290.80     13513874.54
      2049140.80     13513744.54      2049019.84     13513679.65
      2048728.17     13513579.65      2048702.48     13513472.71
      2048633.03     13513382.43      2048292.75     13513269.23
      2047970.53     13513203.26      2047810.80     13513124.54
      2047740.80     13513064.54      2047624.00     13513037.98
      2047509.42     13512983.82      2047391.37     13512840.76
      2047297.62     13512765.07      2047240.80     13512674.54
      2047230.80     13512554.54      2047040.80     13512354.54
      2047021.92     13512249.09      2046940.80     13512094.54
      2046827.48     13511791.46      2046686.50     13511742.15
      2046494.84     13511722.71      2046368.25     13511737.09
      2046190.80     13511914.54      2046070.80     13511884.54
      2045910.80     13511904.54      2045840.80     13511854.54
      2045800.80     13511854.54      2045740.80     13511894.54

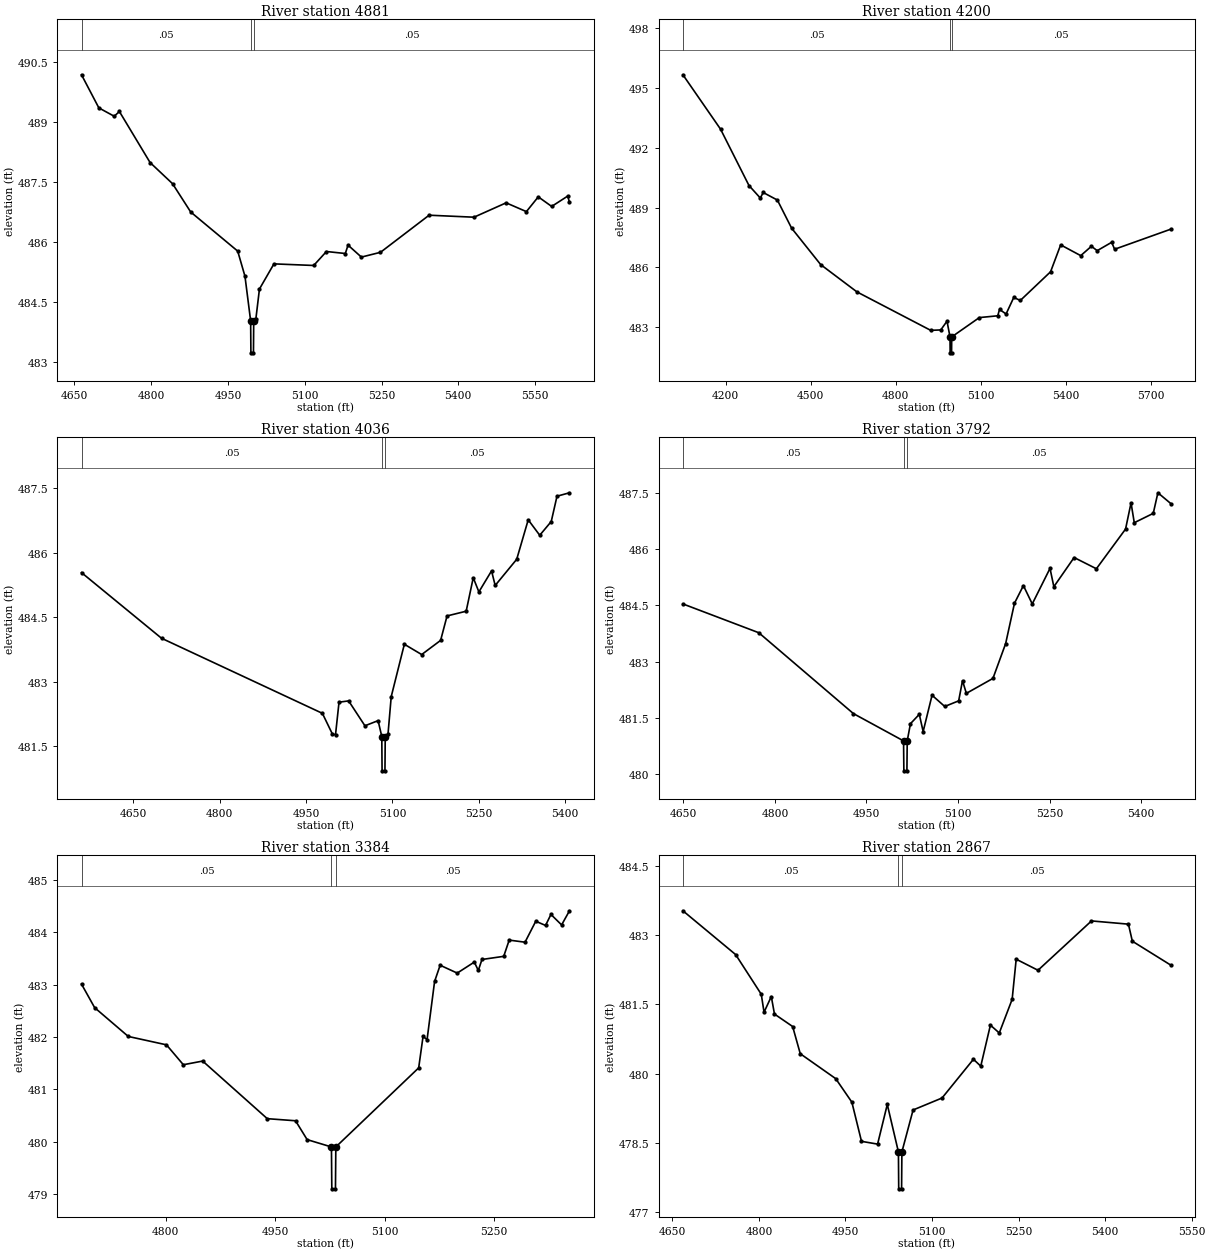
Type RM Length L Ch R = 1,4881,681,681,681
BEGIN DESCRIPTION:
UNT 174 in Lagunillas Cr Wtrshd 2.0
END DESCRIPTION:
XS GIS Cut Line= 4
      2049638.94     13513844.32      2049468.80     13513847.79
      2049256.08     13514052.49      2049099.44     13514514.78
#Sta/Elev= 30
  4663.8  490.19  4697.7  489.36  4727.8  489.15  4737.8  489.27  4797.8  487.99
  4841.7  487.46  4877.2  486.75  4969.0  485.77  4983.2  485.14  4994.3  484.02
  4994.8  483.22  4999.8  483.22  5000.3  484.02  5004.5  484.07  5011.5  484.82
  5039.8  485.45  5117.5  485.41  5142.4  485.76  5179.3  485.71  5184.6  485.92
  5210.7  485.62  5248.0  485.74  5343.0  486.67  5430.7  486.62  5493.5  486.98
  5533.1  486.76  5556.3  487.13  5582.5  486.89  5613.9  487.15  5617.3  486.99
#Mann=3,-1,0
  4663.8    0.05       0  4994.3    0.03       0  5000.3    0.05       0
Bank Sta=4994.3,5000.3
Exp/Cntr=0.3,0.1

Type RM Length L Ch R = 1,4200,164,164,164
BEGIN DESCRIPTION:
Mapping XS 6ad6c2fd
END DESCRIPTION:
XS GIS Cut Line= 4
      2049687.43     13513424.35      2048896.23     13513482.86
      2048576.79     13513923.83      2048656.20     13514299.34
#Sta/Elev= 30
  4048.7  495.67  4181.5  492.94  4281.8  490.11  4321.9  489.48  4331.9  489.76
  4382.0  489.38  4432.2  487.97  4534.8  486.14  4662.7  484.77  4922.9  482.84
  4958.5  482.86  4980.5  483.30  4991.1  482.51  4991.6  481.71  4996.6  481.71
  4997.1  482.51  5094.6  483.48  5159.5  483.57  5165.8  483.89  5188.9  483.66
  5216.0  484.49  5239.2  484.34  5345.9  485.78  5381.5  487.13  5452.3  486.59
  5490.0  487.06  5510.4  486.84  5561.5  487.26  5571.8  486.91  5770.4  487.92
#Mann=3,-1,0
  4048.7    0.05       0  4991.1    0.03       0  4997.1    0.05       0
Bank Sta=4991.1,4997.1
Exp/Cntr=0.3,0.1

Type RM Length L Ch R = 1,4036,244,244,244
BEGIN DESCRIPTION:
Mapping XS 41c340a9
END DESCRIPTION:
XS GIS Cut Line= 4
      2049111.53     13513399.54      2049014.29     13513357.86
      2048458.73     13513618.28      2048458.73     13513746.71
#Sta/Elev= 30
  4559.9  485.54  4698.9  484.01  4978.4  482.26  4995.7  481.78  5001.2  481.76
  5007.3  482.52  5024.0  482.55  5052.3  481.97  5075.2  482.09  5081.6  481.72
  5082.1  480.92  5087.1  480.92  5087.6  481.72  5092.5  481.79  5098.0  482.65
  5120.8  483.87  5150.9  483.63  5183.8  483.96  5195.0  484.53  5228.2  484.64
  5240.5  485.42  5250.3  485.09  5272.3  485.58  5278.6  485.24  5316.0  485.85
  5336.0  486.77  5356.0  486.41  5376.0  486.73  5386.0  487.32  5407.7  487.40
#Mann=3,-1,0
  4559.9    0.05       0  5081.6    0.03       0  5087.6    0.05       0
Bank Sta=5081.6,5087.6
Exp/Cntr=0.3,0.1

Type RM Length L Ch R = 1,3792,408,408,408
BEGIN DESCRIPTION:
Mapping XS 554f4164
END DESCRIPTION:
XS GIS Cut Line= 4
      2048809.44     13513170.36      2048677.48     13513170.36
      2048368.45     13513576.61      2048420.27     13513725.15
#Sta/Elev= 30
  4649.2  484.54  4773.6  483.77  4928.6  481.61  5010.8  480.88  5011.3  480.08
  5016.3  480.08  5016.8  480.88  5022.1  481.34  5036.6  481.59  5042.9  481.13
  5057.5  482.10  5078.3  481.80  5101.1  481.95  5107.4  482.49  5113.7  482.15
  5157.3  482.55  5178.1  483.48  5192.6  484.56  5207.2  485.03  5221.7  484.54
  5250.8  485.49  5257.1  485.00  5290.3  485.78  5326.8  485.48  5374.6  486.54
  5383.6  487.24  5388.9  486.71  5420.0  486.96  5427.6  487.51  5448.9  487.22
#Mann=3,-1,0
  4649.2    0.05       0  5010.8    0.03       0  5016.8    0.05       0
Bank Sta=5010.8,5016.8
Exp/Cntr=0.3,0.1

Type RM Length L Ch R = 1,3384,517,517,517
BEGIN DESCRIPTION:
Mapping XS 7128fdef
END DESCRIPTION:
XS GIS Cut Line= 4
      2048361.51     13513045.36      2048212.20     13513111.33
      2048055.95     13513468.97      2048124.40     13513561.37
#Sta/Elev= 30
  4684.8  483.01  4702.8  482.56  4748.9  482.01  4801.2  481.85  4824.3  481.47
  4850.8  481.54  4939.3  480.44  4978.0  480.40  4993.9  480.04  5027.2  479.90
  5027.7  479.10  5032.7  479.10  5033.2  479.90  5146.7  481.41  5152.7  482.01
  5158.2  481.95  5168.5  483.06  5176.1  483.37  5199.5  483.22  5222.9  483.43
  5228.4  483.27  5233.4  483.48  5263.2  483.54  5270.7  483.85  5292.4  483.81
  5307.1  484.21  5320.5  484.13  5327.9  484.34  5342.5  484.14  5353.3  484.41
#Mann=3,-1,0
  4684.8    0.05       0  5027.2    0.03       0  5033.2    0.05       0
Bank Sta=5027.2,5033.2
Exp/Cntr=0.3,0.1

Type RM Length L Ch R = 1,2867,455,455,455
BEGIN DESCRIPTION:
Mapping XS 13b80a65
END DESCRIPTION:
XS GIS Cut Line= 4
      2047912.72     13512842.73      2047775.54     13512882.67
      2047522.07     13513387.87      2047615.83     13513488.58
#Sta/Elev= 30
  4668.3  483.53  4759.7  482.58  4804.1  481.72  4808.9  481.33  4821.5  481.67
  4827.0  481.29  4858.5  481.02  4871.7  480.43  4933.1  479.89  4961.1  479.38
  4977.8  478.53  5005.7  478.47  5022.5  479.33  5041.8  478.30  5042.3  477.50
  5047.3  477.50  5047.8  478.30  5067.2  479.21  5117.4  479.47  5171.8  480.31
  5184.5  480.16  5201.2  481.05  5216.6  480.88  5238.9  481.61  5245.9  482.48
  5283.7  482.24  5376.4  483.31  5440.4  483.24  5447.2  482.87  5514.0  482.35
#Mann=3,-1,0
  4668.3    0.05       0  5041.8    0.03       0  5047.8    0.05       0
Bank Sta=5041.8,5047.8
Exp/Cntr=0.3,0.1

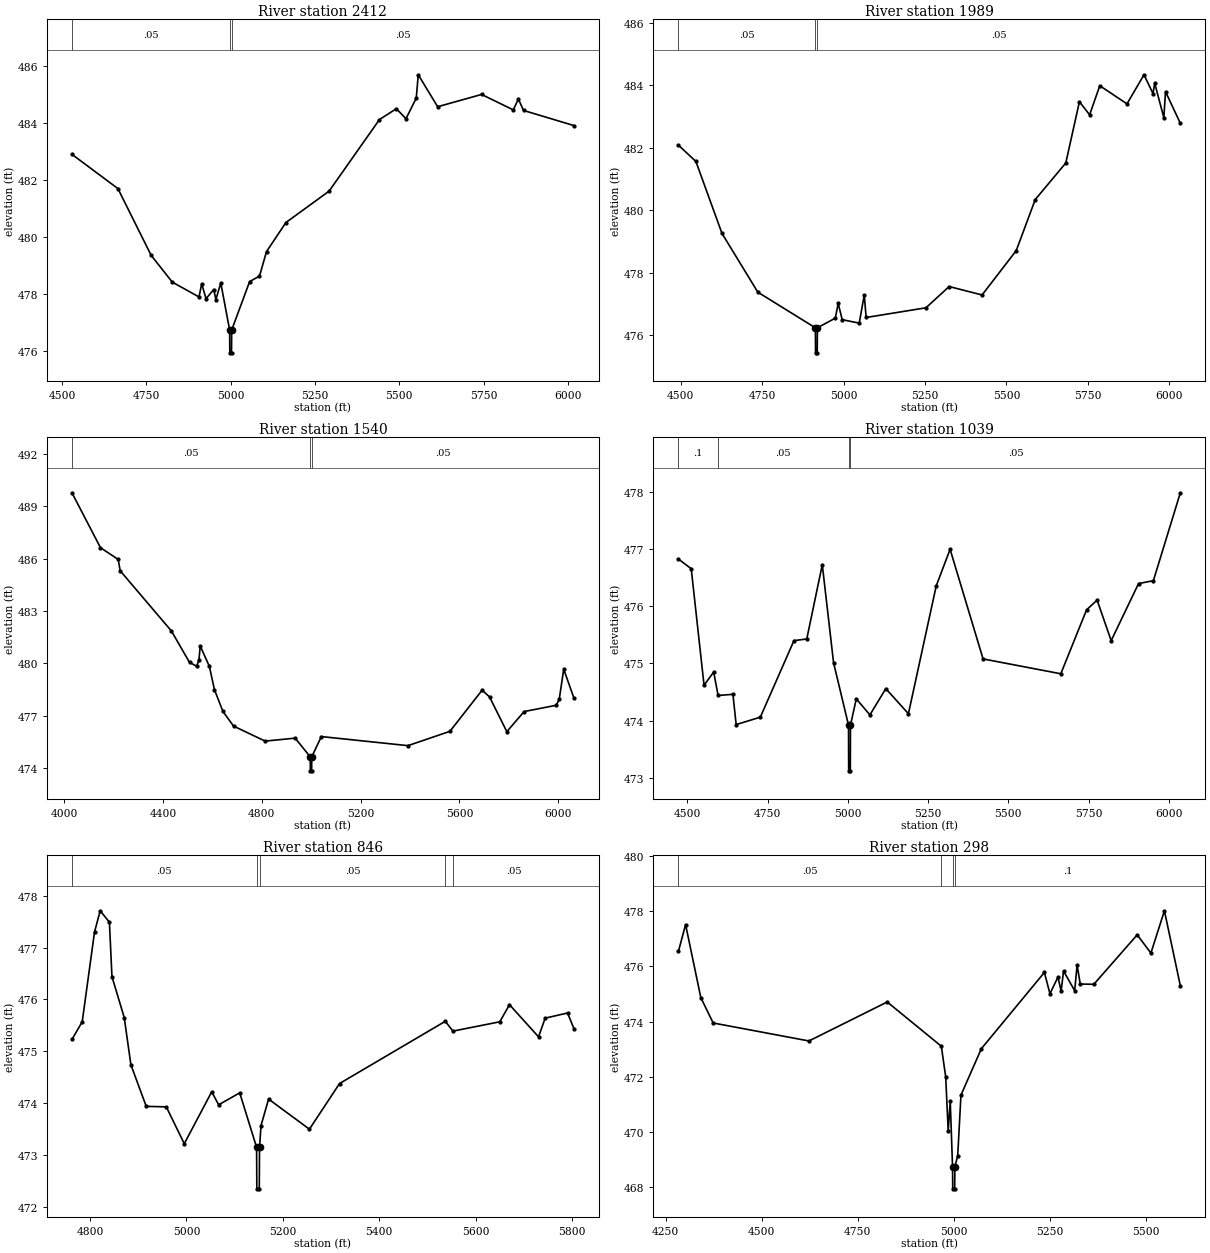
Type RM Length L Ch R = 1,2412,423,423,423
BEGIN DESCRIPTION:
Mapping XS 61206fd3
END DESCRIPTION:
XS GIS Cut Line= 4
      2047690.85     13512583.35      2047499.86     13512570.32
      2047152.63     13513034.73      2047538.93     13513638.06
#Sta/Elev= 30
  4529.8  482.89  4666.0  481.69  4764.5  479.35  4827.2  478.41  4906.4  477.89
  4914.4  478.35  4927.2  477.83  4950.2  478.15  4956.4  477.80  4971.0  478.38
  4997.2  476.73  4997.7  475.93  5002.8  475.93  5003.3  476.73  5056.5  478.43
  5085.7  478.62  5106.5  479.48  5164.1  480.50  5292.0  481.60  5441.3  484.11
  5491.4  484.49  5519.9  484.14  5550.3  484.86  5556.3  485.68  5613.8  484.56
  5744.0  484.99  5837.9  484.45  5853.1  484.83  5868.3  484.43  6017.5  483.90
#Mann=3,-1,0
  4529.8    0.05       0  4997.2    0.03       0  5003.3    0.05       0
Bank Sta=4997.2,5003.3
Exp/Cntr=0.3,0.1

Type RM Length L Ch R = 1,1989,449,449,449
BEGIN DESCRIPTION:
Mapping XS 6edd1928
END DESCRIPTION:
XS GIS Cut Line= 4
      2047578.55     13512344.84      2047204.72     13512335.95
      2046950.00     13512750.00      2047143.42     13513401.85
#Sta/Elev= 30
  4493.4  482.08  4547.0  481.56  4627.0  479.26  4737.0  477.38  4913.7  476.24
  4914.2  475.44  4919.3  475.44  4919.8  476.24  4974.8  476.55  4983.6  477.02
  4996.0  476.50  5048.2  476.39  5063.6  477.29  5069.4  476.57  5252.9  476.88
  5324.1  477.56  5425.1  477.29  5530.0  478.71  5588.2  480.34  5682.0  481.51
  5723.8  483.47  5755.1  483.05  5786.3  483.98  5869.8  483.40  5921.9  484.33
  5949.6  483.73  5954.8  484.06  5982.8  482.96  5988.0  483.79  6033.4  482.78
#Mann=3,-1,0
  4493.4    0.05       0  4913.7    0.03       0  4919.8    0.05       0
Bank Sta=4913.7,4919.8
Exp/Cntr=0.3,0.1

Type RM Length L Ch R = 1,1540,501,501,501
BEGIN DESCRIPTION:
Mapping XS 7917c46a
END DESCRIPTION:
XS GIS Cut Line= 4
      2047817.55     13511726.58      2047179.54     13511869.80
      2046721.21     13512236.99      2046752.46     13513026.01
#Sta/Elev= 30
  4032.1  489.76  4147.5  486.62  4219.2  485.95  4227.3  485.30  4434.4  481.86
  4507.8  480.06  4536.9  479.84  4546.0  480.21  4551.1  481.00  4588.2  479.83
  4608.7  478.50  4642.9  477.26  4685.8  476.42  4813.9  475.56  4935.3  475.73
  4996.3  474.66  4996.8  473.86  5001.9  473.86  5002.4  474.66  5041.2  475.82
  5391.4  475.30  5561.5  476.12  5691.6  478.47  5721.6  478.09  5791.7  476.10
  5861.7  477.25  5991.8  477.61  6003.8  477.96  6021.9  479.67  6062.9  478.03
#Mann=3,-1,0
  4032.1    0.05       0  4996.3    0.03       0  5002.4    0.05       0
Bank Sta=4996.3,5002.4
Exp/Cntr=0.3,0.1

Type RM Length L Ch R = 1,1039,193,193,193
BEGIN DESCRIPTION:
Mapping XS 34066260
END DESCRIPTION:
XS GIS Cut Line= 5
      2047134.84     13511689.07      2046694.75     13511673.44
      2046541.10     13511827.09      2046449.96     13512079.69
      2046712.28     13512661.48
#Sta/Elev= 30
  4471.7  476.83  4511.6  476.66  4551.6  474.62  4581.6  474.85  4595.4  474.44
  4641.6  474.46  4651.7  473.93  4727.0  474.06  4831.8  475.40  4871.8  475.43
  4920.1  476.73  4955.4  475.01  5001.9  473.92  5002.4  473.12  5007.5  473.12
  5008.0  473.92  5026.1  474.38  5068.6  474.10  5118.1  474.56  5188.6  474.12
  5275.3  476.36  5318.5  477.00  5421.3  475.08  5663.6  474.82  5743.9  475.94
  5776.7  476.11  5820.6  475.40  5905.9  476.40  5952.1  476.45  6036.1  477.99
#Mann=4,-1,0
  4471.7     0.1       0  4595.4    0.05       0  5001.9    0.03       0
  5008.0    0.05       0
Bank Sta=5001.9,5008
Exp/Cntr=0.3,0.1

Type RM Length L Ch R = 1,846,548,548,548
BEGIN DESCRIPTION:
Mapping XS 45a0ad9a
END DESCRIPTION:
XS GIS Cut Line= 5
      2046650.24     13511632.94      2046454.95     13511702.38
      2046329.08     13511934.58      2046439.76     13512318.70
      2046424.56     13512487.98
#Sta/Elev= 30
  4762.6  475.23  4783.9  475.57  4809.4  477.30  4821.2  477.71  4840.3  477.49
  4845.6  476.44  4871.1  475.65  4884.9  474.74  4916.7  473.94  4958.3  473.93
  4995.6  473.22  5052.5  474.22  5066.9  473.97  5110.6  474.20  5145.6  473.15
  5146.1  472.35  5151.2  472.35  5151.7  473.15  5154.8  473.57  5170.5  474.08
  5255.2  473.50  5317.7  474.38  5537.1  475.58  5552.8  475.39  5650.1  475.57
  5670.2  475.90  5730.4  475.28  5744.2  475.64  5790.7  475.74  5803.7  475.44
#Mann=5,-1,0
  4762.6    0.05       0  5145.6    0.03       0  5151.7    0.05       0
  5537.1     0.1       0  5552.8    0.05       0
Bank Sta=5145.6,5151.7
Exp/Cntr=0.3,0.1

Type RM Length L Ch R = 1,298,154,154,154
BEGIN DESCRIPTION:
Mapping XS 60364563
END DESCRIPTION:
XS GIS Cut Line= 5
      2046530.92     13511615.56      2045951.47     13511787.01
      2046001.39     13511954.11      2046259.63     13512151.60
      2046397.90     13512300.67
#Sta/Elev= 30
  4283.5  476.54  4302.2  477.51  4341.8  474.87  4374.0  473.95  4623.4  473.30
  4827.3  474.71  4968.2  473.11  4979.6  472.00  4986.1  470.05  4991.4  471.12
  4997.4  468.75  4997.9  467.95  5003.0  467.95  5003.5  468.75  5010.9  469.15
  5019.3  471.34  5072.4  473.02  5236.6  475.78  5251.1  475.01  5271.9  475.61
  5280.2  475.11  5286.5  475.83  5315.5  475.12  5321.8  476.05  5330.0  475.36
  5365.4  475.35  5478.3  477.14  5514.0  476.48  5549.2  478.01  5590.6  475.30
#Mann=4,-1,0
  4283.5    0.05       0  4968.2     0.1       0  4997.4    0.07       0
  5003.5     0.1       0
Bank Sta=4997.4,5003.5
Exp/Cntr=0.3,0.1

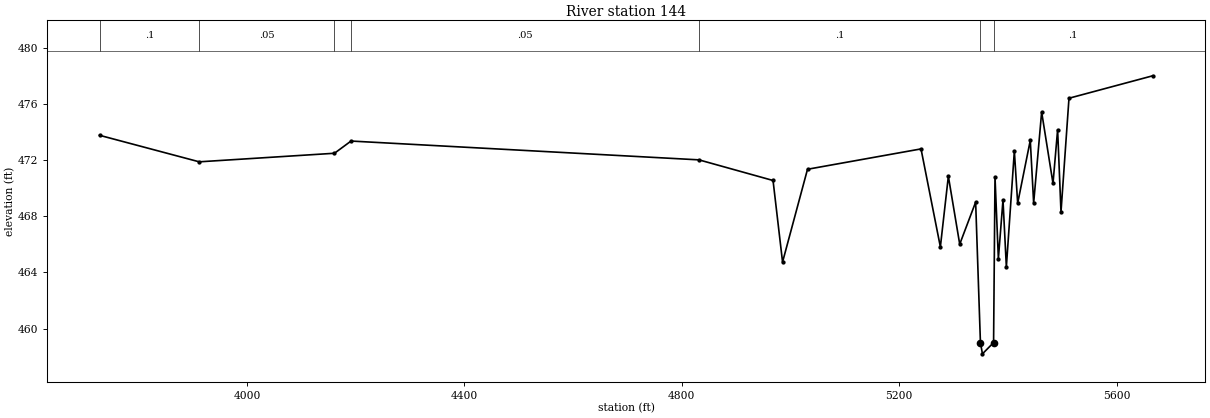
Type RM Length L Ch R = 1,144,0,0,0
BEGIN DESCRIPTION:
UNT 174 in Lagunillas Cr Wtrshd 1.0
END DESCRIPTION:
XS GIS Cut Line= 4
      2046630.19     13510997.24      2045787.32     13511716.31
      2045886.26     13511931.30      2046366.15     13512279.51
#Sta/Elev= 30
  3728.9  473.77  3912.3  471.88  4161.1  472.49  4191.6  473.36  4831.6  472.02
  4967.9  470.55  4985.4  464.74  5031.3  471.35  5240.1  472.80  5275.7  465.82
  5290.4  470.85  5311.3  466.01  5340.6  469.01  5349.4  459.00  5353.1  458.20
  5373.6  459.00  5376.2  470.81  5382.4  464.98  5390.9  469.16  5397.1  464.39
  5411.8  472.65  5417.9  468.93  5441.1  473.41  5447.3  468.94  5462.0  475.43
  5482.9  470.34  5491.4  474.17  5497.6  468.31  5512.3  476.41  5666.4  478.01
#Mann=7,-1,0
  3728.9     0.1       0  3912.3    0.05       0  4161.1     0.1       0
  4191.6    0.05       0  4831.6     0.1       0  5349.4    0.07       0
  5373.6     0.1       0
Bank Sta=5349.4,5373.6
Exp/Cntr=0.3,0.1

Chan Stop Cuts=-1