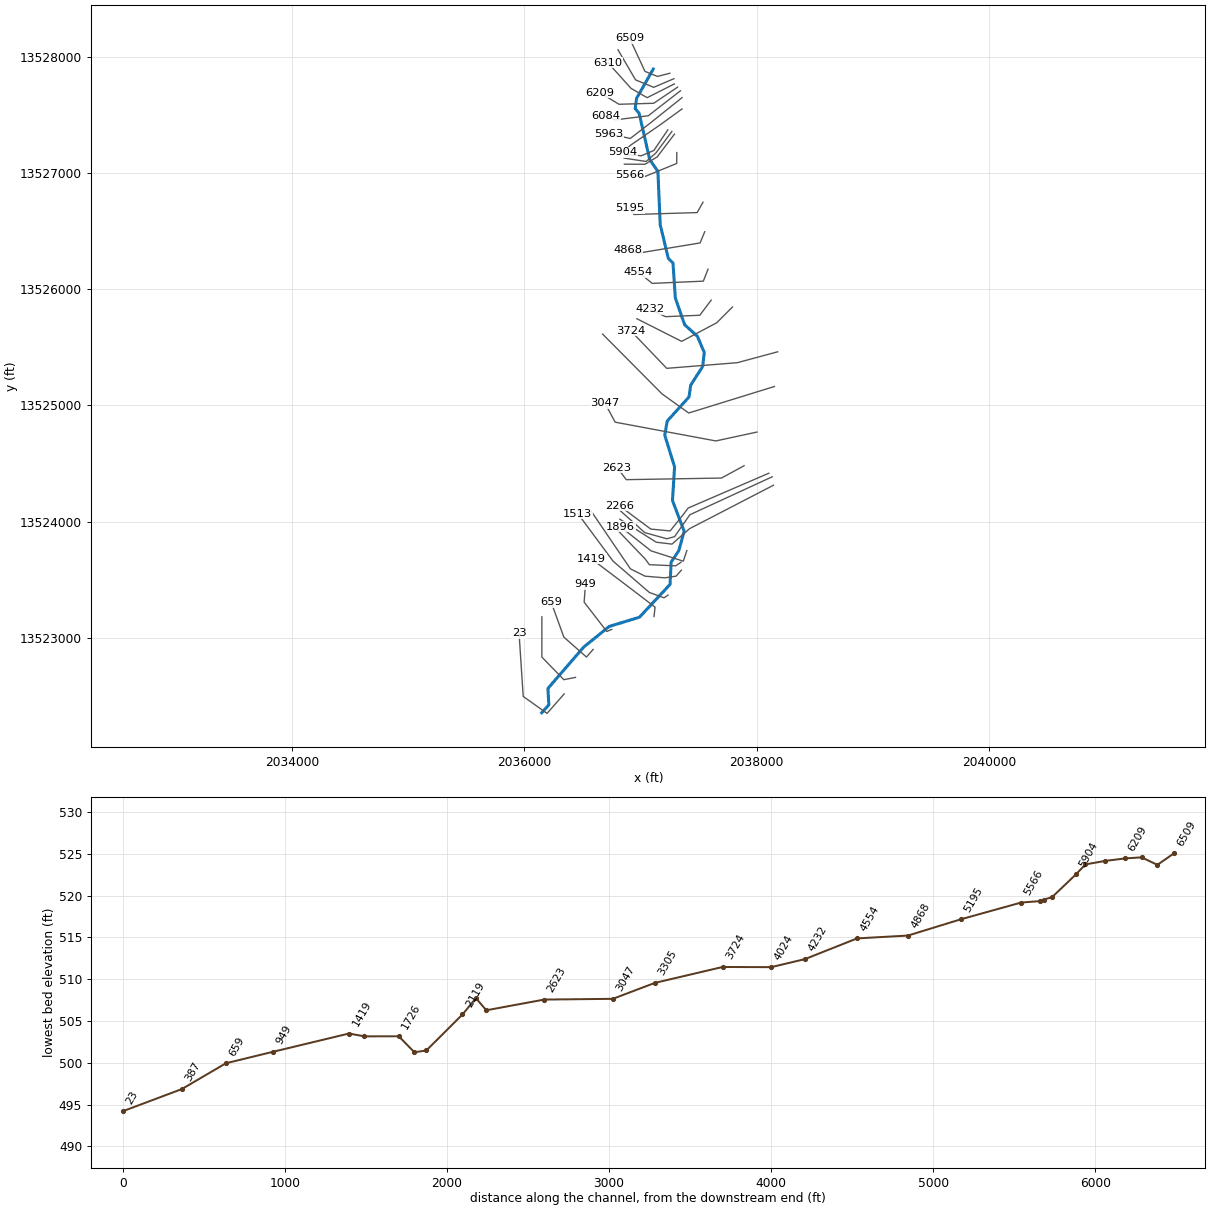
--- UNT 175 in Lagunillas Cr Wtrshd.prj (project) ---

Proj Title=UNT 175 in Lagunillas Cr Wtrshd Base Level Engineering
Current Plan=p01
Default Exp/Contr=0.3,0.1
English Units
Geom File=g01
Flow File=f01
Plan File=p01
BEGIN DESCRIPTION:
UNT 175 in Lagunillas Cr Wtrshd
END DESCRIPTION:

--- UNT 175 in Lagunillas Cr Wtrshd.p01 (plan) ---

Plan Title=Multiple Run
Short Identifier=Multiple
Geom File=g01
Flow File=f01
Subcritical Flow
K Sum by GR= 0
Std Step Tol= 0.01
Critical Tol= 0.01
Num of Std Step Trials= 20
Max Error Tol= 0.3
Flow Tol Ratio= 0.001
Split Flow NTrial= 30
Split Flow Tol= 0.02
Split Flow Ratio= 0.02
Log Output Level= 0
Friction Slope Method= 1
Unsteady Friction Slope Method= 2
Unsteady Bridges Friction Slope Method= 1
Parabolic Critical Depth
Global Vel Dist=  1 , 1 , 1
Global Log Level= 0
CheckData=True
Encroach Param= -1, 0, 0, 0
BEGIN DESCRIPTION:
Multiple Run
END DESCRIPTION:

--- UNT 175 in Lagunillas Cr Wtrshd.f01 (steady flow) ---

Flow Title=Multiple
Number of Profiles=7
Profile Names=10-year,25-year,50-year,1pct_min,100-year,1pct_plu,500-year
River Rch & RM= UNT 175 in Lagun,Reach-1,6509
     171     231     279     169     337     672     497
River Rch & RM= UNT 175 in Lagun,Reach-1,4554
     223     305     373     227     452     903     676
Boundary for River Rch & Prof#=UNT 175 in Lagun,Reach-1,1
Up Type=0
Dn Type=3
Dn Slope=0.005
Boundary for River Rch & Prof#=UNT 175 in Lagun,Reach-1,2
Up Type=0
Dn Type=3
Dn Slope=0.005
Boundary for River Rch & Prof#=UNT 175 in Lagun,Reach-1,3
Up Type=0
Dn Type=3
Dn Slope=0.005
Boundary for River Rch & Prof#=UNT 175 in Lagun,Reach-1,4
Up Type=0
Dn Type=3
Dn Slope=0.005
Boundary for River Rch & Prof#=UNT 175 in Lagun,Reach-1,5
Up Type=0
Dn Type=3
Dn Slope=0.005
Boundary for River Rch & Prof#=UNT 175 in Lagun,Reach-1,6
Up Type=0
Dn Type=3
Dn Slope=0.005
Boundary for River Rch & Prof#=UNT 175 in Lagun,Reach-1,7
Up Type=0
Dn Type=3
Dn Slope=0.005

--- UNT 175 in Lagunillas Cr Wtrshd.g01 (geometry) ---

Geom Title=Existing Conditions

River Reach=UNT 175 in Lagun,Reach-1
Reach XY= 30
      2037110.80     13527894.54      2036967.17     13527642.61
      2036955.19     13527555.11      2036989.57     13527513.45
      2037080.80     13527114.54      2037150.80     13527014.54
      2037170.80     13526554.54      2037240.80     13526264.54
      2037280.80     13526224.54      2037300.80     13525924.54
      2037380.80     13525694.54      2037490.80     13525594.54
      2037550.20     13525454.90      2037535.62     13525334.06
      2037432.84     13525173.65      2037418.95     13525072.95
      2037230.80     13524864.54      2037209.92     13524743.78
      2037294.42     13524470.92      2037276.33     13524180.69
      2037376.59     13523917.67      2037331.01     13523749.70
      2037264.61     13523650.74      2037255.49     13523459.34
      2036991.69     13523176.53      2036732.84     13523097.88
      2036513.56     13522921.32      2036204.43     13522564.13
      2036212.24     13522422.21      2036150.80     13522354.54

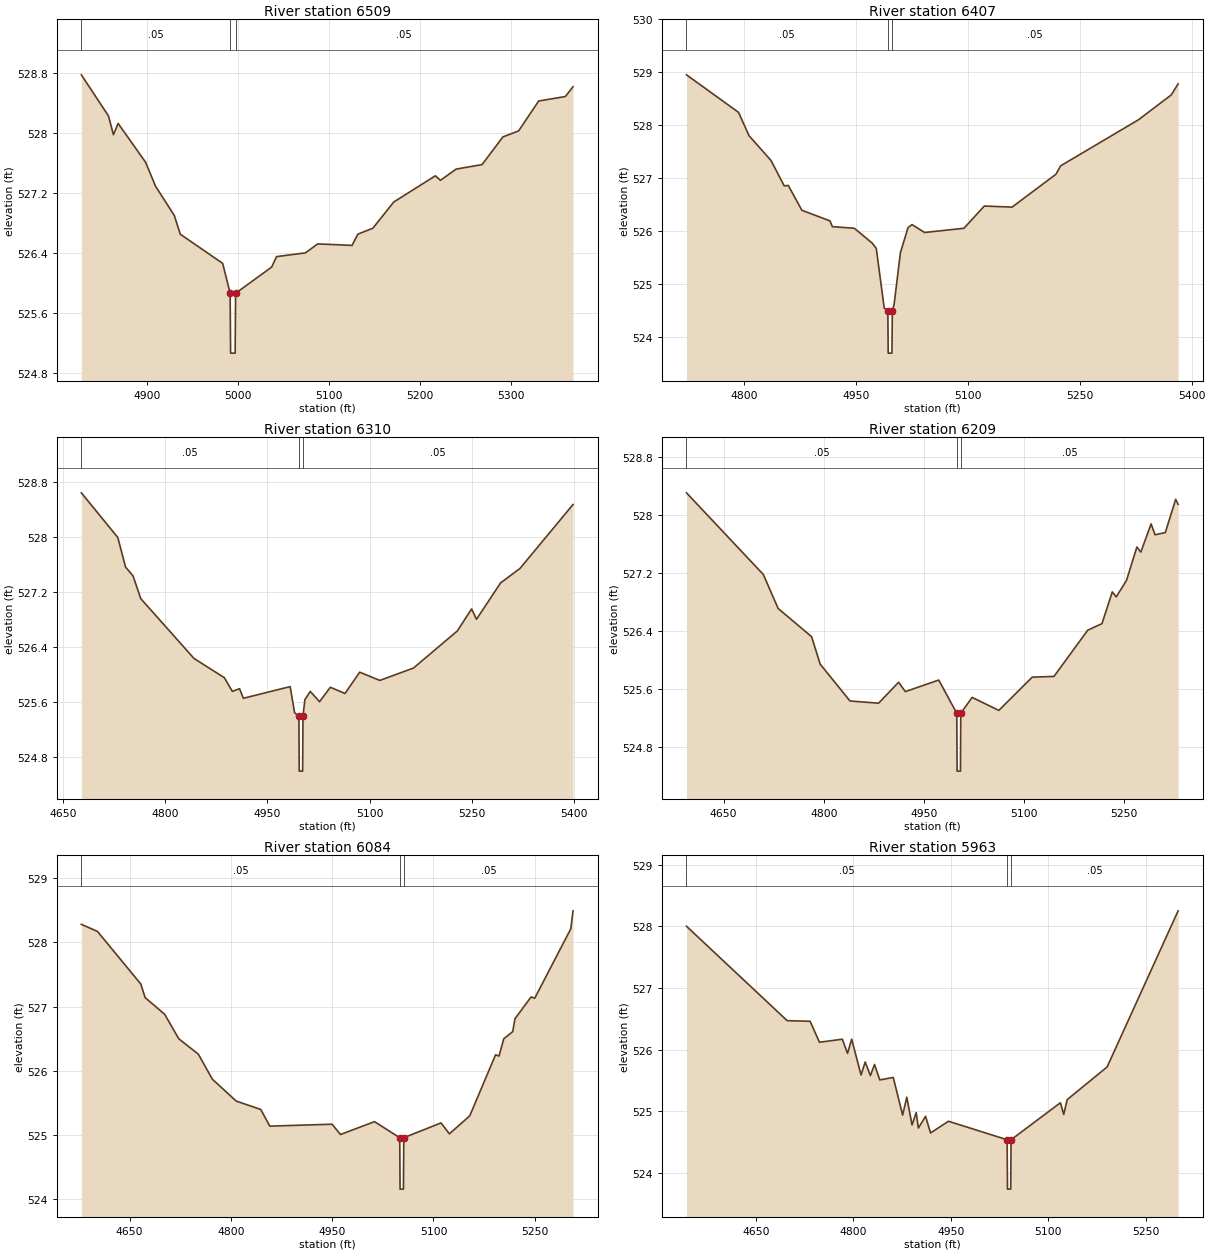
Type RM Length L Ch R = 1,6509,102,102,102
BEGIN DESCRIPTION:
UNT 175 in Lagunillas Cr Wtrshd 10.0
END DESCRIPTION:
XS GIS Cut Line= 4
      2037253.85     13527858.90      2037147.56     13527831.29
      2037039.75     13527874.52      2036907.23     13528159.22
#Sta/Elev= 30
  4828.3  528.78  4858.1  528.23  4863.5  527.98  4868.7  528.13  4898.9  527.61
  4909.8  527.29  4930.4  526.90  4936.9  526.65  4983.5  526.26  4991.7  525.86
  4992.2  525.06  4997.2  525.06  4997.7  525.86  5037.3  526.21  5042.7  526.35
  5074.4  526.40  5087.9  526.52  5125.6  526.50  5132.0  526.65  5148.5  526.73
  5171.4  527.08  5217.1  527.43  5222.7  527.37  5240.0  527.52  5268.4  527.58
  5291.3  527.95  5308.5  528.03  5330.6  528.43  5359.9  528.49  5368.3  528.62
#Mann=3,-1,0
  4828.3    0.05       0  4991.7    0.03       0  4997.7    0.05       0
Bank Sta=4991.7,4997.7
Exp/Cntr=0.3,0.1

Type RM Length L Ch R = 1,6407,97,97,97
BEGIN DESCRIPTION:
Mapping XS 2e324c62
END DESCRIPTION:
XS GIS Cut Line= 4
      2037289.20     13527811.96      2037114.75     13527737.54
      2036958.50     13527801.60      2036807.14     13528060.94
#Sta/Elev= 30
  4723.1  528.95  4792.9  528.24  4806.9  527.80  4836.4  527.33  4854.1  526.85
  4859.5  526.86  4877.7  526.39  4915.3  526.19  4918.6  526.08  4948.0  526.05
  4971.9  525.77  4977.4  525.67  4988.1  524.54  4992.9  524.49  4993.4  523.69
  4998.4  523.69  4998.9  524.49  5001.3  524.61  5009.8  525.59  5019.9  526.06
  5025.3  526.12  5042.2  525.97  5094.9  526.05  5122.2  526.47  5159.4  526.45
  5218.1  527.07  5224.5  527.23  5328.7  528.10  5372.7  528.57  5381.9  528.78
#Mann=3,-1,0
  4723.1    0.05       0  4992.9    0.03       0  4998.9    0.05       0
Bank Sta=4992.9,4998.9
Exp/Cntr=0.3,0.1

Type RM Length L Ch R = 1,6310,101,101,101
BEGIN DESCRIPTION:
Mapping XS 8482e24b
END DESCRIPTION:
XS GIS Cut Line= 4
      2037292.64     13527766.80      2037058.50     13527648.48
      2036919.44     13527728.69      2036720.28     13527950.25
#Sta/Elev= 30
  4677.2  528.64  4730.6  527.99  4742.0  527.56  4753.0  527.43  4764.3  527.10
  4842.3  526.23  4886.8  525.95  4898.6  525.75  4909.1  525.79  4914.7  525.65
  4983.3  525.82  4989.8  525.44  4996.1  525.39  4996.6  524.59  5001.6  524.59
  5002.1  525.39  5004.9  525.63  5012.8  525.75  5026.4  525.60  5042.2  525.81
  5063.7  525.72  5085.3  526.03  5114.7  525.91  5164.1  526.09  5228.4  526.63
  5249.3  526.95  5256.5  526.80  5291.9  527.33  5320.3  527.54  5398.0  528.47
#Mann=3,-1,0
  4677.2    0.05       0  4996.1    0.03       0  5002.1    0.05       0
Bank Sta=4996.1,5002.1
Exp/Cntr=0.3,0.1

Type RM Length L Ch R = 1,6209,125,125,125
BEGIN DESCRIPTION:
Mapping XS 2df87f70
END DESCRIPTION:
XS GIS Cut Line= 4
      2037320.44     13527739.04      2037114.59     13527600.34
      2036815.98     13527591.65      2036654.09     13527690.23
#Sta/Elev= 30
  4594.3  528.31  4709.4  527.18  4731.6  526.71  4781.7  526.32  4794.6  525.94
  4839.3  525.43  4882.1  525.40  4912.1  525.69  4922.1  525.56  4972.2  525.72
  4999.2  525.26  4999.7  524.46  5004.7  524.46  5005.2  525.26  5022.2  525.48
  5062.2  525.30  5112.2  525.76  5144.8  525.77  5195.4  526.41  5216.7  526.50
  5232.2  526.94  5238.1  526.87  5253.5  527.10  5269.0  527.56  5274.9  527.49
  5290.3  527.88  5296.2  527.73  5311.6  527.76  5327.1  528.22  5330.8  528.15
#Mann=3,-1,0
  4594.3    0.05       0  4999.2    0.03       0  5005.2    0.05       0
Bank Sta=4999.2,5005.2
Exp/Cntr=0.3,0.1

Type RM Length L Ch R = 1,6084,121,121,121
BEGIN DESCRIPTION:
Mapping XS 2c6519f3
END DESCRIPTION:
XS GIS Cut Line= 4
      2037344.74     13527707.78      2037068.22     13527492.92
      2036784.20     13527457.51      2036699.47     13527492.28
#Sta/Elev= 30
  4578.6  528.28  4602.4  528.17  4666.7  527.35  4673.0  527.14  4702.0  526.88
  4722.8  526.50  4751.8  526.26  4772.6  525.87  4807.9  525.53  4844.2  525.40
  4857.6  525.14  4949.8  525.17  4962.3  525.01  5012.7  525.21  5050.0  524.96
  5050.5  524.16  5055.5  524.16  5056.0  524.96  5111.2  525.19  5123.5  525.02
  5153.7  525.30  5191.9  526.25  5197.0  526.23  5204.1  526.50  5217.3  526.61
  5220.6  526.81  5244.5  527.15  5249.9  527.13  5303.3  528.21  5306.6  528.49
#Mann=3,-1,0
  4578.6    0.05       0  5050.0    0.03       0  5056.0    0.05       0
Bank Sta=5050,5056
Exp/Cntr=0.3,0.1

Type RM Length L Ch R = 1,5963,59,59,59
BEGIN DESCRIPTION:
Mapping XS 746286e7
END DESCRIPTION:
XS GIS Cut Line= 4
      2037358.65     13527648.77      2037079.68     13527425.73
      2036913.02     13527297.26      2036728.19     13527337.67
#Sta/Elev= 30
  4543.2  528.00  4698.2  526.47  4733.5  526.46  4747.9  526.12  4783.1  526.17
  4791.1  525.94  4797.5  526.17  4811.9  525.59  4818.3  525.80  4826.3  525.58
  4832.7  525.76  4840.7  525.51  4861.5  525.55  4875.9  524.94  4882.3  525.23
  4890.4  524.78  4896.8  524.98  4900.2  524.73  4911.2  524.92  4918.9  524.65
  4946.5  524.84  5036.8  524.54  5037.3  523.74  5042.3  523.74  5042.8  524.54
  5118.8  525.14  5123.9  524.95  5129.2  525.19  5190.7  525.72  5300.0  528.25
#Mann=3,-1,0
  4543.2    0.05       0  5036.8    0.03       0  5042.8    0.05       0
Bank Sta=5036.8,5042.8
Exp/Cntr=0.3,0.1

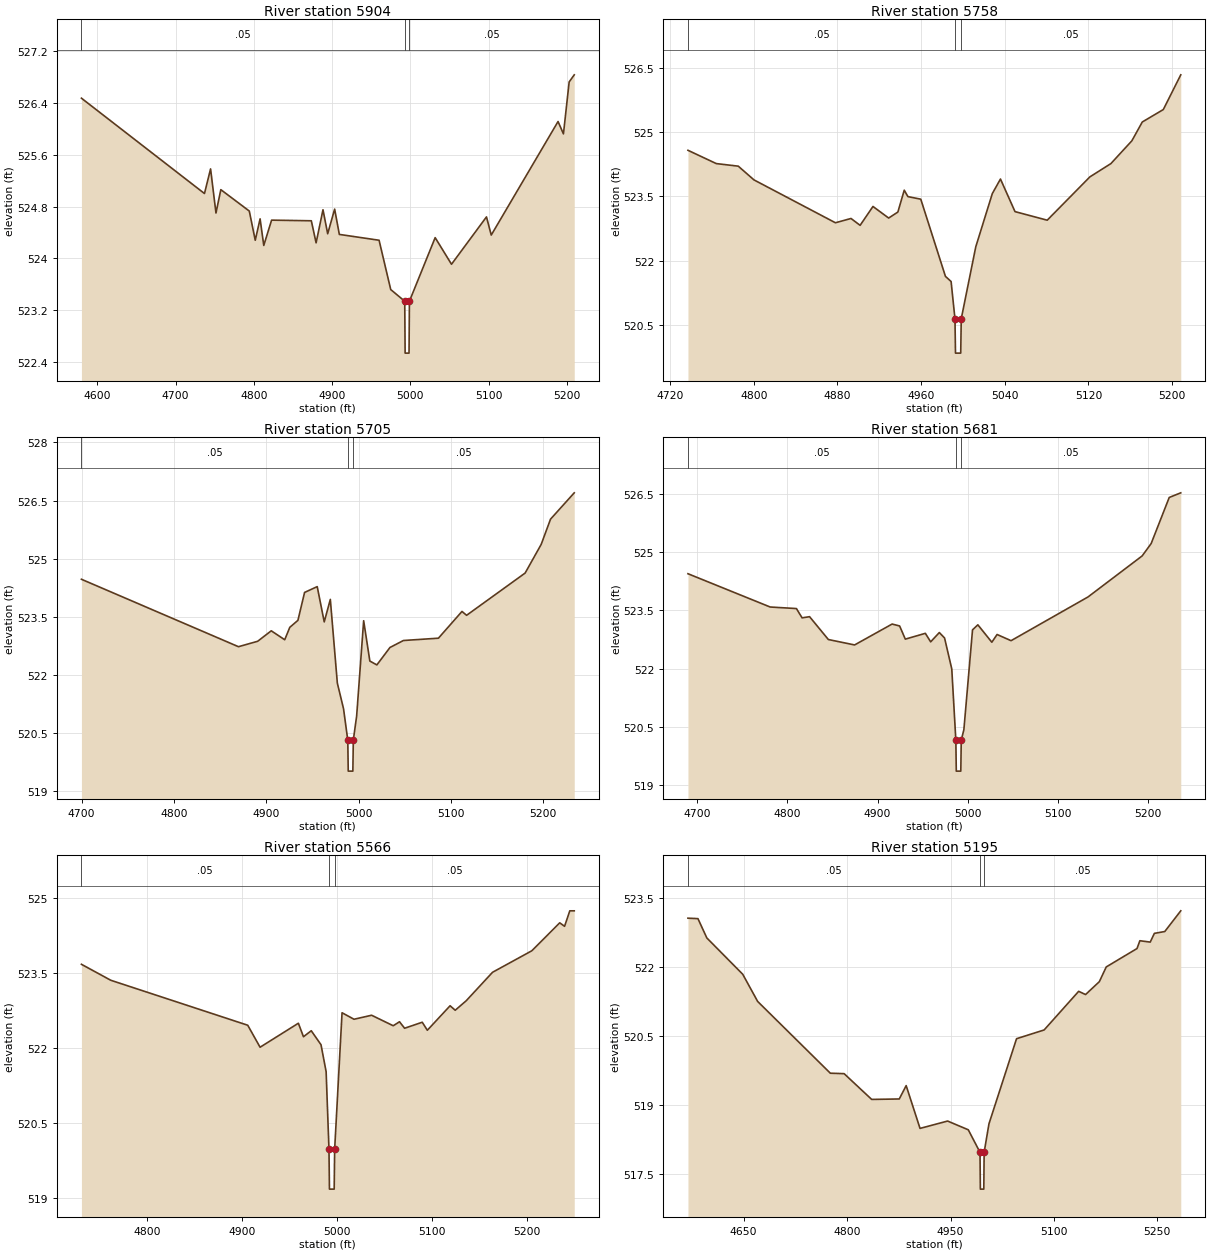
Type RM Length L Ch R = 1,5904,146,146,146
BEGIN DESCRIPTION:
Mapping XS 4c7e7125
END DESCRIPTION:
XS GIS Cut Line= 4
      2037358.60     13527551.51      2037169.96     13527414.45
      2036913.88     13527238.23      2036851.40     13527179.18
#Sta/Elev= 30
  4579.6  526.47  4736.9  525.00  4744.7  525.38  4751.6  524.70  4757.8  525.06
  4794.2  524.73  4801.8  524.28  4808.0  524.61  4812.7  524.20  4822.7  524.59
  4873.5  524.58  4879.6  524.24  4888.4  524.75  4894.4  524.38  4903.3  524.76
  4909.3  524.37  4960.1  524.28  4975.0  523.52  4992.9  523.34  4993.4  522.54
  4998.4  522.54  4998.9  523.34  5031.8  524.32  5052.7  523.91  5097.4  524.64
  5103.5  524.36  5188.9  526.11  5195.8  525.92  5203.1  526.72  5209.6  526.83
#Mann=3,-1,0
  4579.6    0.05       0  4992.9    0.03       0  4998.9    0.05       0
Bank Sta=4992.9,4998.9
Exp/Cntr=0.3,0.1

Type RM Length L Ch R = 1,5758,53,53,53
BEGIN DESCRIPTION:
Mapping XS c92d7de5
END DESCRIPTION:
XS GIS Cut Line= 4
      2037236.12     13527371.18      2037116.05     13527194.44
      2037009.11     13527148.61      2036868.35     13527159.59
#Sta/Elev= 30
  4737.1  524.57  4764.2  524.26  4785.2  524.20  4800.2  523.88  4878.1  522.88
  4893.0  522.98  4901.7  522.82  4914.0  523.26  4929.0  522.99  4937.8  523.13
  4943.9  523.64  4947.4  523.49  4959.7  523.43  4983.3  521.63  4988.7  521.51
  4992.4  520.64  4992.9  519.84  4997.9  519.84  4998.4  520.64  5012.3  522.32
  5028.1  523.56  5035.9  523.90  5049.8  523.14  5080.6  522.94  5121.4  523.95
  5141.5  524.26  5161.5  524.79  5171.5  525.23  5191.6  525.52  5208.3  526.33
#Mann=3,-1,0
  4737.1    0.05       0  4992.4    0.03       0  4998.4    0.05       0
Bank Sta=4992.4,4998.4
Exp/Cntr=0.3,0.1

Type RM Length L Ch R = 1,5705,24,24,24
BEGIN DESCRIPTION:
Mapping XS 292a78f6
END DESCRIPTION:
XS GIS Cut Line= 4
      2037270.86     13527357.30      2037133.41     13527172.22
      2037049.39     13527099.30      2036859.59     13527128.39
#Sta/Elev= 30
  4699.8  524.47  4869.9  522.73  4890.7  522.87  4905.4  523.14  4920.0  522.91
  4925.5  523.23  4934.3  523.41  4941.5  524.13  4955.2  524.28  4962.8  523.37
  4969.4  523.95  4977.0  521.79  4983.7  521.13  4988.3  520.32  4988.8  519.52
  4993.8  519.52  4994.3  520.32  4997.9  520.94  5005.5  523.40  5012.2  522.36
  5019.8  522.26  5034.0  522.71  5048.6  522.89  5086.5  522.95  5112.0  523.64
  5117.0  523.54  5180.4  524.63  5197.8  525.37  5207.9  526.02  5233.6  526.70
#Mann=3,-1,0
  4699.8    0.05       0  4988.3    0.03       0  4994.3    0.05       0
Bank Sta=4988.3,4994.3
Exp/Cntr=0.3,0.1

Type RM Length L Ch R = 1,5681,115,115,115
BEGIN DESCRIPTION:
Mapping XS a77941da
END DESCRIPTION:
XS GIS Cut Line= 4
      2037293.44     13527334.75      2037145.00     13527139.05
      2037040.31     13527075.51      2036862.20     13527076.03
#Sta/Elev= 30
  4689.8  524.45  4780.9  523.59  4810.0  523.55  4816.3  523.31  4824.6  523.34
  4845.4  522.75  4874.5  522.61  4916.1  523.15  4924.4  523.10  4930.7  522.76
  4952.9  522.91  4958.8  522.69  4968.4  522.93  4974.2  522.79  4982.2  521.99
  4986.7  520.15  4987.2  519.35  4992.2  519.35  4992.7  520.15  4995.6  520.42
  5005.2  523.00  5011.1  523.13  5026.6  522.68  5032.4  522.88  5047.9  522.72
  5133.2  523.85  5193.2  524.91  5203.2  525.23  5223.2  526.42  5236.0  526.54
#Mann=3,-1,0
  4689.8    0.05       0  4986.7    0.03       0  4992.7    0.05       0
Bank Sta=4986.7,4992.7
Exp/Cntr=0.3,0.1

Type RM Length L Ch R = 1,5566,371,371,371
BEGIN DESCRIPTION:
Mapping XS c6735d31
END DESCRIPTION:
XS GIS Cut Line= 4
      2037313.49     13527176.02      2037312.62     13527082.23
      2037027.03     13526965.05      2036910.68     13526981.54
#Sta/Elev= 30
  4730.3  523.68  4761.3  523.36  4905.8  522.46  4918.8  522.02  4959.2  522.50
  4964.6  522.23  4972.8  522.35  4983.1  522.07  4988.5  521.53  4991.5  519.98
  4992.0  519.18  4997.0  519.18  4997.5  519.98  5005.3  522.71  5017.9  522.58
  5036.5  522.66  5059.3  522.45  5065.9  522.53  5071.3  522.40  5089.9  522.52
  5095.3  522.36  5119.3  522.85  5124.7  522.76  5136.3  522.95  5164.1  523.52
  5205.5  523.95  5235.0  524.51  5240.1  524.44  5245.6  524.75  5250.3  524.75
#Mann=3,-1,0
  4730.3    0.05       0  4991.5    0.03       0  4997.5    0.05       0
Bank Sta=4991.5,4997.5
Exp/Cntr=0.3,0.1

Type RM Length L Ch R = 1,5195,327,327,327
BEGIN DESCRIPTION:
Mapping XS 46127898
END DESCRIPTION:
XS GIS Cut Line= 4
      2037539.18     13526748.90      2037488.83     13526659.49
      2036944.56     13526643.00      2036907.23     13526699.43
#Sta/Elev= 30
  4569.2  523.07  4583.7  523.06  4596.6  522.64  4648.7  521.85  4670.3  521.26
  4775.7  519.70  4795.7  519.69  4835.7  519.13  4875.7  519.14  4885.7  519.43
  4905.8  518.50  4945.8  518.66  4975.8  518.47  4992.8  517.98  4993.3  517.18
  4998.3  517.18  4998.8  517.98  5005.8  518.60  5045.8  520.45  5085.8  520.64
  5135.9  521.48  5145.9  521.41  5165.9  521.69  5175.9  522.01  5220.5  522.41
  5224.7  522.58  5239.7  522.55  5245.7  522.74  5260.8  522.78  5284.0  523.23
#Mann=3,-1,0
  4569.2    0.05       0  4992.8    0.03       0  4998.8    0.05       0
Bank Sta=4992.8,4998.8
Exp/Cntr=0.3,0.1

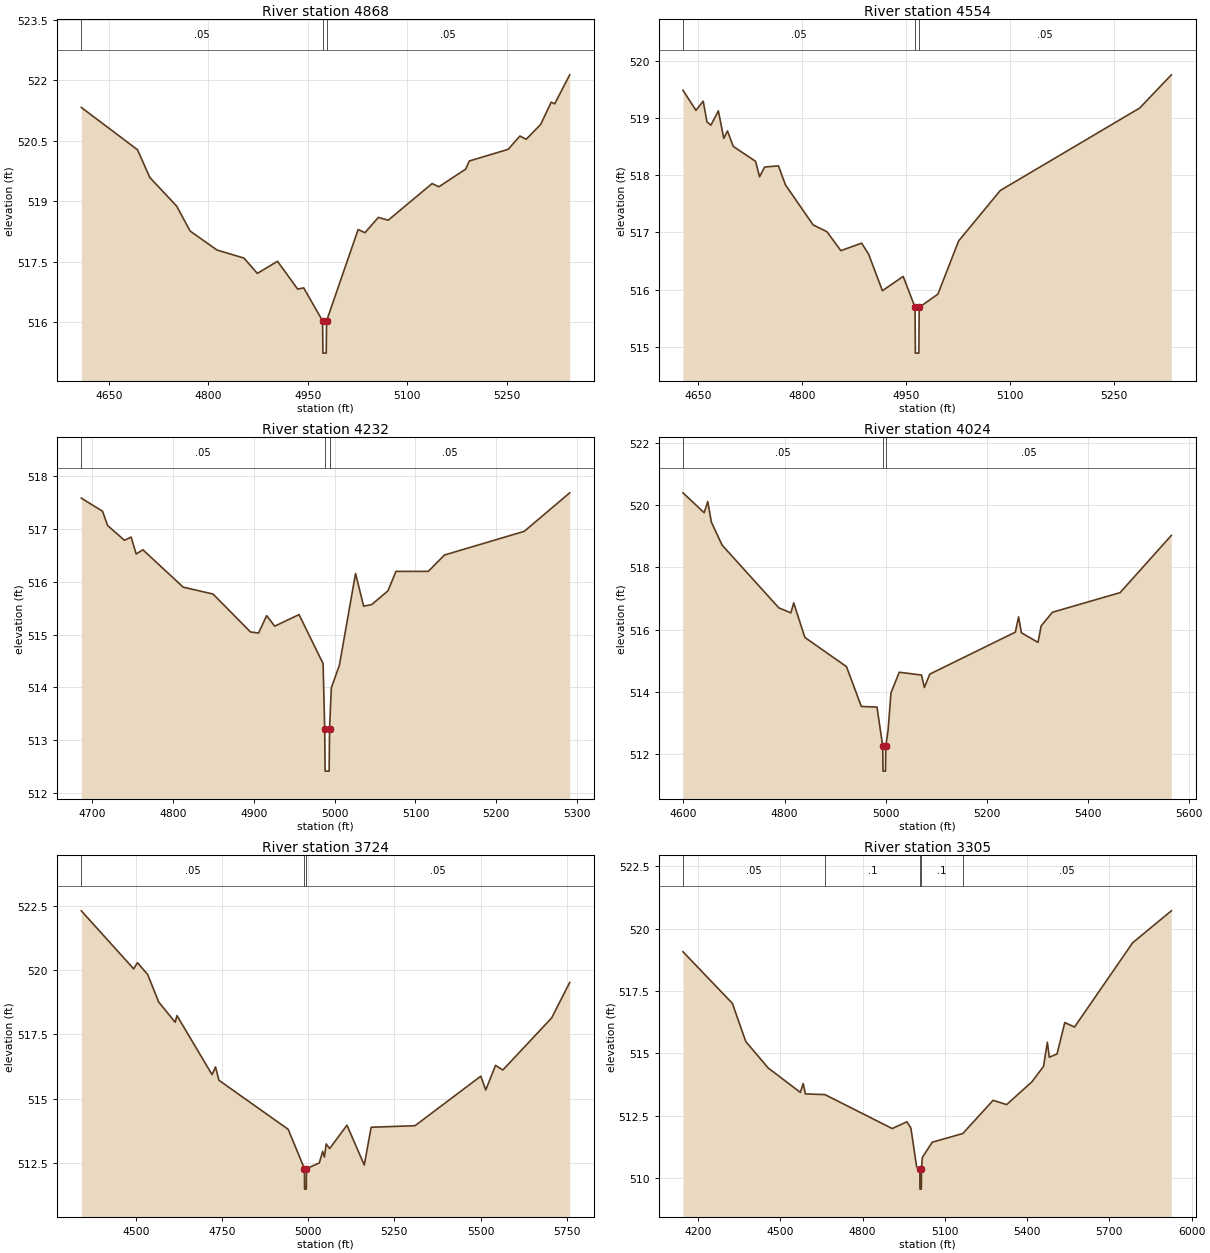
Type RM Length L Ch R = 1,4868,314,314,314
BEGIN DESCRIPTION:
Mapping XS 3a6b9f9c
END DESCRIPTION:
XS GIS Cut Line= 4
      2037553.93     13526494.53      2037514.01     13526398.21
      2036981.89     13526310.53      2036893.31     13526338.32
#Sta/Elev= 30
  4608.7  521.33  4693.4  520.28  4712.0  519.59  4752.5  518.88  4772.8  518.26
  4813.3  517.79  4853.9  517.59  4874.1  517.21  4904.5  517.51  4934.9  516.82
  4944.0  516.85  4972.5  516.03  4973.0  515.23  4978.0  515.23  4978.5  516.03
  5026.1  518.30  5036.3  518.22  5056.6  518.60  5071.4  518.53  5137.6  519.44
  5147.8  519.36  5188.3  519.80  5193.7  520.00  5252.3  520.29  5270.0  520.62
  5279.5  520.54  5301.4  520.91  5317.2  521.46  5322.5  521.42  5345.1  522.14
#Mann=3,-1,0
  4608.7    0.05       0  4972.5    0.03       0  4978.5    0.05       0
Bank Sta=4972.5,4978.5
Exp/Cntr=0.3,0.1

Type RM Length L Ch R = 1,4554,322,322,322
BEGIN DESCRIPTION:
Mapping XS 621cf982
END DESCRIPTION:
XS GIS Cut Line= 4
      2037582.59     13526172.52      2037541.79     13526069.21
      2037101.68     13526050.12      2036982.75     13526147.34
#Sta/Elev= 30
  4627.7  519.48  4646.5  519.13  4656.9  519.29  4662.3  518.93  4668.0  518.87
  4678.8  519.12  4686.7  518.64  4692.0  518.77  4700.3  518.50  4732.5  518.24
  4738.3  517.97  4745.6  518.14  4765.6  518.16  4775.6  517.83  4815.6  517.13
  4835.6  517.01  4855.7  516.68  4885.7  516.81  4895.7  516.62  4915.7  515.98
  4945.7  516.23  4962.8  515.69  4963.3  514.89  4968.3  514.89  4968.8  515.69
  4995.8  515.92  5025.8  516.85  5085.9  517.73  5287.2  519.17  5332.9  519.75
#Mann=3,-1,0
  4627.7    0.05       0  4962.8    0.03       0  4968.8    0.05       0
Bank Sta=4962.8,4968.8
Exp/Cntr=0.3,0.1

Type RM Length L Ch R = 1,4232,208,208,208
BEGIN DESCRIPTION:
Mapping XS 614d39f2
END DESCRIPTION:
XS GIS Cut Line= 4
      2037609.52     13525906.06      2037511.40     13525775.81
      2037216.27     13525763.66      2037084.35     13525827.01
#Sta/Elev= 30
  4686.2  517.59  4712.5  517.34  4718.7  517.07  4739.6  516.79  4747.9  516.85
  4754.1  516.53  4762.4  516.61  4812.4  515.90  4849.3  515.77  4895.7  515.05
  4905.7  515.03  4915.7  515.36  4925.7  515.16  4955.8  515.38  4985.6  514.45
  4987.6  513.21  4988.1  512.41  4993.1  512.41  4993.6  513.21  4995.8  513.99
  5005.8  514.42  5025.8  516.16  5035.8  515.54  5045.8  515.57  5065.9  515.83
  5075.9  516.20  5115.9  516.20  5135.9  516.51  5234.8  516.96  5291.0  517.69
#Mann=3,-1,0
  4686.2    0.05       0  4987.6    0.03       0  4993.6    0.05       0
Bank Sta=4987.6,4993.6
Exp/Cntr=0.3,0.1

Type RM Length L Ch R = 1,4024,300,300,300
BEGIN DESCRIPTION:
Mapping XS ab7f34a6
END DESCRIPTION:
XS GIS Cut Line= 4
      2037792.63     13525846.64      2037657.25     13525711.26
      2037355.15     13525550.98      2036969.90     13525745.90
#Sta/Elev= 30
  4599.1  520.40  4641.0  519.76  4648.1  520.12  4655.2  519.46  4676.4  518.72
  4788.6  516.70  4812.3  516.54  4818.0  516.86  4840.0  515.75  4922.3  514.81
  4951.6  513.53  4982.6  513.51  4993.9  512.25  4994.4  511.45  4999.4  511.45
  4999.9  512.25  5004.6  512.78  5010.2  513.97  5026.6  514.63  5070.5  514.54
  5076.2  514.14  5086.9  514.57  5256.0  515.92  5262.4  516.41  5268.0  515.90
  5300.8  515.59  5307.0  516.12  5329.3  516.56  5463.0  517.19  5564.3  519.03
#Mann=3,-1,0
  4599.1    0.05       0  4993.9    0.03       0  4999.9    0.05       0
Bank Sta=4993.9,4999.9
Exp/Cntr=0.3,0.1

Type RM Length L Ch R = 1,3724,419,419,419
BEGIN DESCRIPTION:
Mapping XS ccd2ce78
END DESCRIPTION:
XS GIS Cut Line= 4
      2038181.57     13525461.26      2037834.33     13525367.51
      2037226.69     13525318.90      2036917.67     13525641.80
#Sta/Elev= 30
  4342.3  522.31  4494.1  520.05  4505.1  520.29  4534.7  519.83  4566.6  518.76
  4614.5  517.97  4619.6  518.23  4721.4  515.93  4731.4  516.23  4741.4  515.71
  4942.1  513.80  4989.2  512.27  4989.7  511.47  4994.7  511.47  4995.2  512.27
  5032.4  512.49  5042.1  512.94  5047.2  512.72  5052.4  513.23  5062.4  513.05
  5112.6  513.96  5162.8  512.41  5182.8  513.88  5309.9  513.94  5500.8  515.87
  5515.0  515.33  5543.3  516.29  5564.7  516.11  5706.2  518.14  5758.5  519.52
#Mann=3,-1,0
  4342.3    0.05       0  4989.2    0.03       0  4995.2    0.05       0
Bank Sta=4989.2,4995.2
Exp/Cntr=0.3,0.1

Type RM Length L Ch R = 1,3305,258,258,258
BEGIN DESCRIPTION:
Mapping XS 95f7db5e
END DESCRIPTION:
XS GIS Cut Line= 4
      2038153.80     13525162.66      2037415.92     13524934.49
      2037186.75     13525098.55      2036674.64     13525614.01
#Sta/Elev= 30
  4145.1  519.08  4325.2  517.01  4374.1  515.48  4455.7  514.42  4573.0  513.44
  4583.5  513.79  4591.4  513.38  4662.8  513.35  4908.0  511.99  4961.5  512.26
  4976.2  512.01  4997.1  510.46  5008.8  510.36  5009.3  509.56  5014.3  509.56
  5014.8  510.36  5018.0  510.83  5053.9  511.44  5165.5  511.79  5275.8  513.12
  5325.3  512.95  5417.2  513.86  5459.7  514.48  5473.8  515.45  5480.9  514.85
  5509.1  514.98  5537.4  516.24  5572.8  516.06  5784.9  519.44  5925.9  520.72
#Mann=5,-1,0
  4145.1    0.05       0  4662.8     0.1       0  5008.8    0.07       0
  5014.8     0.1       0  5165.5    0.05       0
Bank Sta=5008.8,5014.8
Exp/Cntr=0.3,0.1

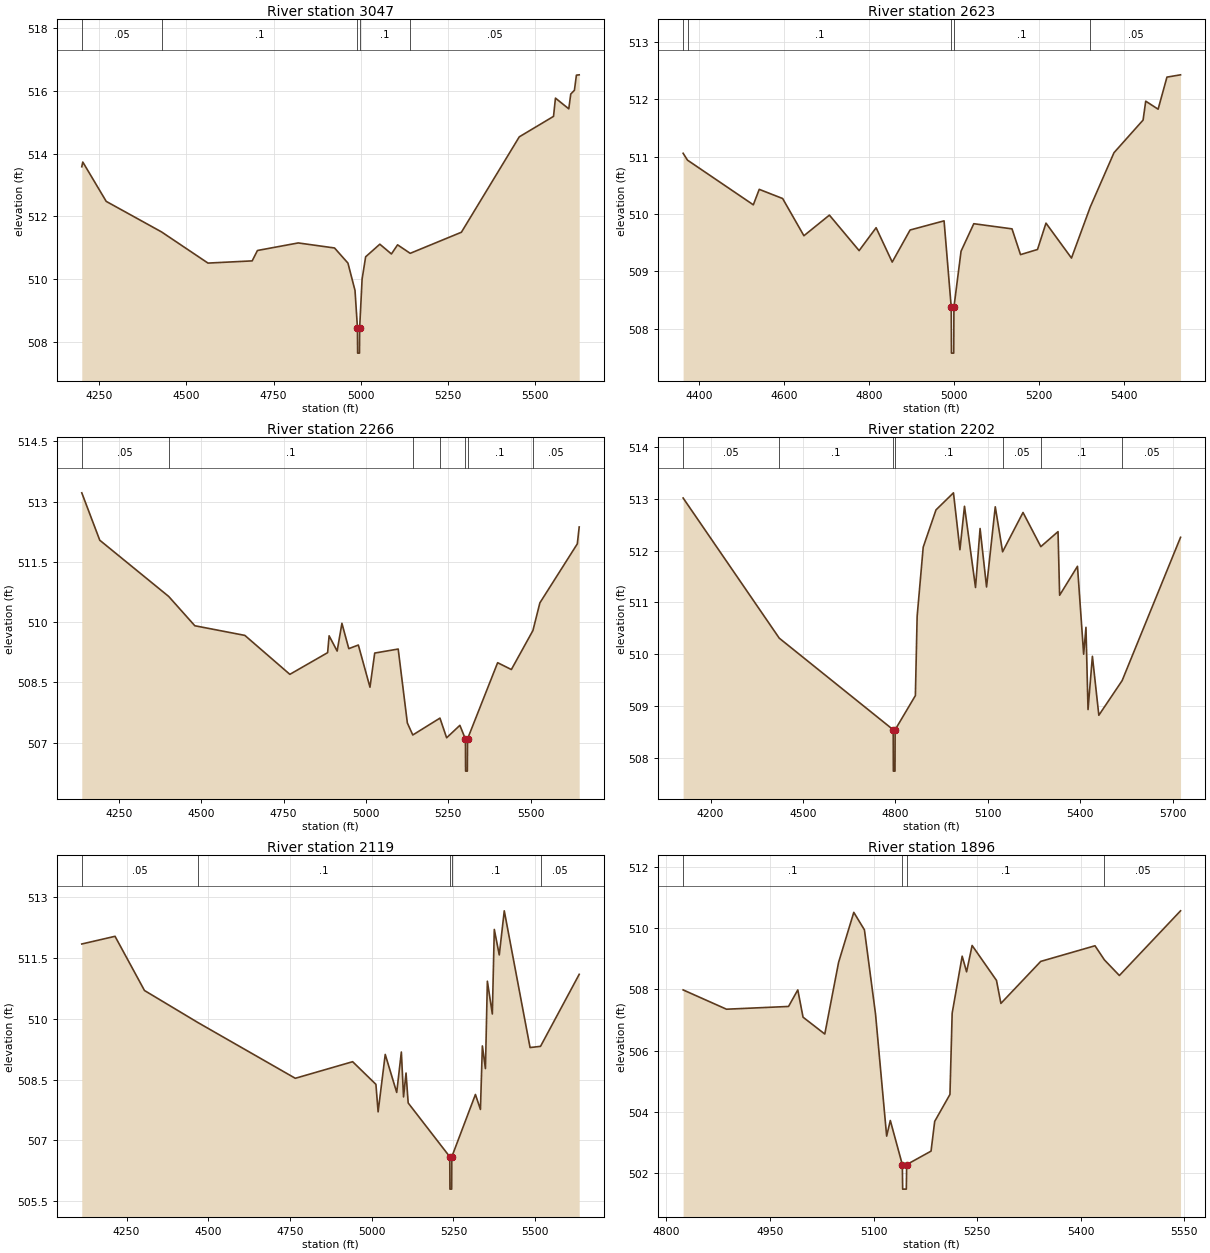
Type RM Length L Ch R = 1,3047,424,424,424
BEGIN DESCRIPTION:
Mapping XS ea2b21c5
END DESCRIPTION:
XS GIS Cut Line= 4
      2038003.52     13524770.48      2037649.31     13524694.09
      2036782.99     13524855.54      2036696.19     13525017.00
#Sta/Elev= 30
  4200.0  513.58  4202.9  513.73  4270.1  512.48  4428.8  511.51  4562.0  510.52
  4688.8  510.59  4703.9  510.92  4821.0  511.16  4925.0  511.00  4963.5  510.52
  4983.8  509.65  4990.8  508.46  4991.3  507.66  4996.6  507.66  4997.1  508.46
  5004.1  510.01  5014.3  510.72  5055.0  511.12  5088.2  510.81  5105.9  511.10
  5142.1  510.83  5289.0  511.50  5455.0  514.53  5553.2  515.18  5558.8  515.76
  5597.0  515.42  5602.7  515.89  5613.2  516.01  5618.9  516.49  5626.9  516.50
#Mann=5,-1,0
  4200.0    0.05       0  4428.8     0.1       0  4990.8    0.07       0
  4997.1     0.1       0  5142.1    0.05       0
Bank Sta=4990.8,4997.1
Exp/Cntr=0.3,0.1

Type RM Length L Ch R = 1,2623,357,357,357
BEGIN DESCRIPTION:
Mapping XS 67678020
END DESCRIPTION:
XS GIS Cut Line= 4
      2037892.38     13524480.55      2037697.92     13524374.64
      2036878.48     13524360.75      2036800.35     13524464.92
#Sta/Elev= 30
  4362.6  511.06  4372.9  510.94  4527.9  510.16  4541.8  510.43  4596.9  510.27
  4647.0  509.62  4707.0  509.98  4777.0  509.36  4817.0  509.76  4854.9  509.16
  4897.0  509.72  4977.0  509.88  4993.9  508.37  4994.4  507.57  4999.7  507.57
  5000.2  508.37  5017.0  509.35  5047.0  509.83  5137.0  509.74  5157.0  509.29
  5197.0  509.38  5217.0  509.84  5277.0  509.23  5321.1  510.12  5377.1  511.07
  5445.6  511.64  5451.8  511.97  5481.0  511.83  5501.8  512.39  5533.8  512.43
#Mann=5,-1,0
  4362.6    0.05       0  4372.9     0.1       0  4993.9    0.07       0
  5000.2     0.1       0  5321.1    0.05       0
Bank Sta=4993.9,5000.2
Exp/Cntr=0.3,0.1

Type RM Length L Ch R = 1,2266,64,64,64
BEGIN DESCRIPTION:
Mapping XS cab2dbb3
END DESCRIPTION:
XS GIS Cut Line= 6
      2038105.14     13524416.11      2037411.75     13524116.74
      2037357.06     13524044.69      2037256.37     13523919.69
      2037089.70     13523935.32      2036819.13     13524136.18
#Sta/Elev= 30
  4137.2  513.22  4191.8  512.04  4401.1  510.64  4480.5  509.91  4632.4  509.67
  4769.1  508.70  4883.8  509.24  4888.3  509.66  4912.7  509.28  4927.2  509.97
  4948.1  509.34  4977.1  509.43  5012.4  508.38  5026.8  509.23  5098.1  509.33
  5125.9  507.49  5142.4  507.19  5224.9  507.61  5245.2  507.12  5285.4  507.43
  5302.3  507.09  5302.8  506.29  5308.1  506.29  5308.6  507.09  5400.1  508.99
  5441.8  508.82  5507.2  509.79  5528.4  510.48  5642.1  511.95  5647.8  512.37
#Mann=7,-1,0
  4137.2    0.05       0  4401.1     0.1       0  5142.4    0.05       0
  5224.9     0.1       0  5302.3    0.07       0  5308.6     0.1       0
  5507.2    0.05       0
Bank Sta=5302.3,5308.6
Exp/Cntr=0.3,0.1

Type RM Length L Ch R = 1,2202,83,83,83
BEGIN DESCRIPTION:
Mapping XS a316e4f9
END DESCRIPTION:
XS GIS Cut Line= 6
      2038134.87     13524385.51      2037425.64     13524058.58
      2037294.56     13523870.21      2037227.72     13523851.98
      2037038.54     13523904.62      2036786.11     13524130.16
#Sta/Elev= 30
  4111.1  513.02  4423.2  510.31  4793.0  508.54  4793.5  507.74  4798.8  507.74
  4799.3  508.54  4865.0  509.20  4870.7  510.73  4890.4  512.07  4931.9  512.79
  4988.6  513.12  5009.6  512.02  5024.4  512.86  5060.2  511.29  5075.0  512.43
  5096.0  511.30  5124.3  512.85  5148.1  511.98  5214.4  512.74  5272.2  512.08
  5328.0  512.37  5333.2  511.14  5391.2  511.70  5411.2  510.00  5418.7  510.52
  5425.4  508.93  5439.6  509.96  5460.5  508.82  5536.1  509.49  5725.7  512.26
#Mann=7,-1,0
  4111.1    0.05       0  4423.2     0.1       0  4793.0    0.07       0
  4799.3     0.1       0  5148.1    0.05       0  5272.2     0.1       0
  5536.1    0.05       0
Bank Sta=4793,4799.3
Exp/Cntr=0.3,0.1

Type RM Length L Ch R = 1,2119,223,223,223
BEGIN DESCRIPTION:
Mapping XS d8b3de55
END DESCRIPTION:
XS GIS Cut Line= 6
      2038145.33     13524312.61      2037424.77     13523939.66
      2037324.95     13523852.85      2037271.99     13523805.98
      2037136.58     13523822.47      2036823.15     13524020.46
#Sta/Elev= 30
  4113.2  511.85  4214.9  512.04  4305.0  510.70  4468.0  509.91  4766.3  508.53
  4941.7  508.94  5012.9  508.38  5019.6  507.70  5041.4  509.12  5076.5  508.18
  5090.7  509.18  5097.4  508.07  5105.0  508.66  5111.6  507.92  5238.8  506.59
  5239.3  505.79  5244.6  505.79  5245.1  506.59  5317.3  508.13  5332.6  507.76
  5338.5  509.33  5347.9  508.77  5353.8  510.93  5369.0  510.12  5375.0  512.21
  5390.2  511.58  5405.5  512.67  5484.4  509.29  5516.4  509.32  5634.7  511.10
#Mann=5,-1,0
  4113.2    0.05       0  4468.0     0.1       0  5238.8    0.07       0
  5245.1     0.1       0  5516.4    0.05       0
Bank Sta=5238.8,5245.1
Exp/Cntr=0.3,0.1

Type RM Length L Ch R = 1,1896,74,74,74
BEGIN DESCRIPTION:
Mapping XS fdd8166a
END DESCRIPTION:
XS GIS Cut Line= 4
      2037399.99     13523749.98      2037369.22     13523659.27
      2037092.31     13523747.82      2036829.92     13523954.46
#Sta/Elev= 30
  4824.2  507.98  4887.0  507.35  4976.9  507.44  4990.3  507.98  4997.9  507.09
  5029.4  506.54  5049.4  508.88  5071.4  510.51  5086.8  509.94  5102.9  507.19
  5119.0  503.21  5124.3  503.72  5141.7  502.28  5142.2  501.48  5147.5  501.48
  5148.0  502.28  5183.3  502.72  5188.6  503.69  5210.7  504.57  5213.9  507.22
  5228.4  509.08  5234.8  508.57  5242.8  509.43  5278.1  508.29  5284.5  507.54
  5342.2  508.91  5420.8  509.42  5434.4  508.96  5456.1  508.45  5544.7  510.56
#Mann=4,-1,0
  4824.2     0.1       0  5141.7    0.07       0  5148.0     0.1       0
  5434.4    0.05       0
Bank Sta=5141.7,5148
Exp/Cntr=0.3,0.1

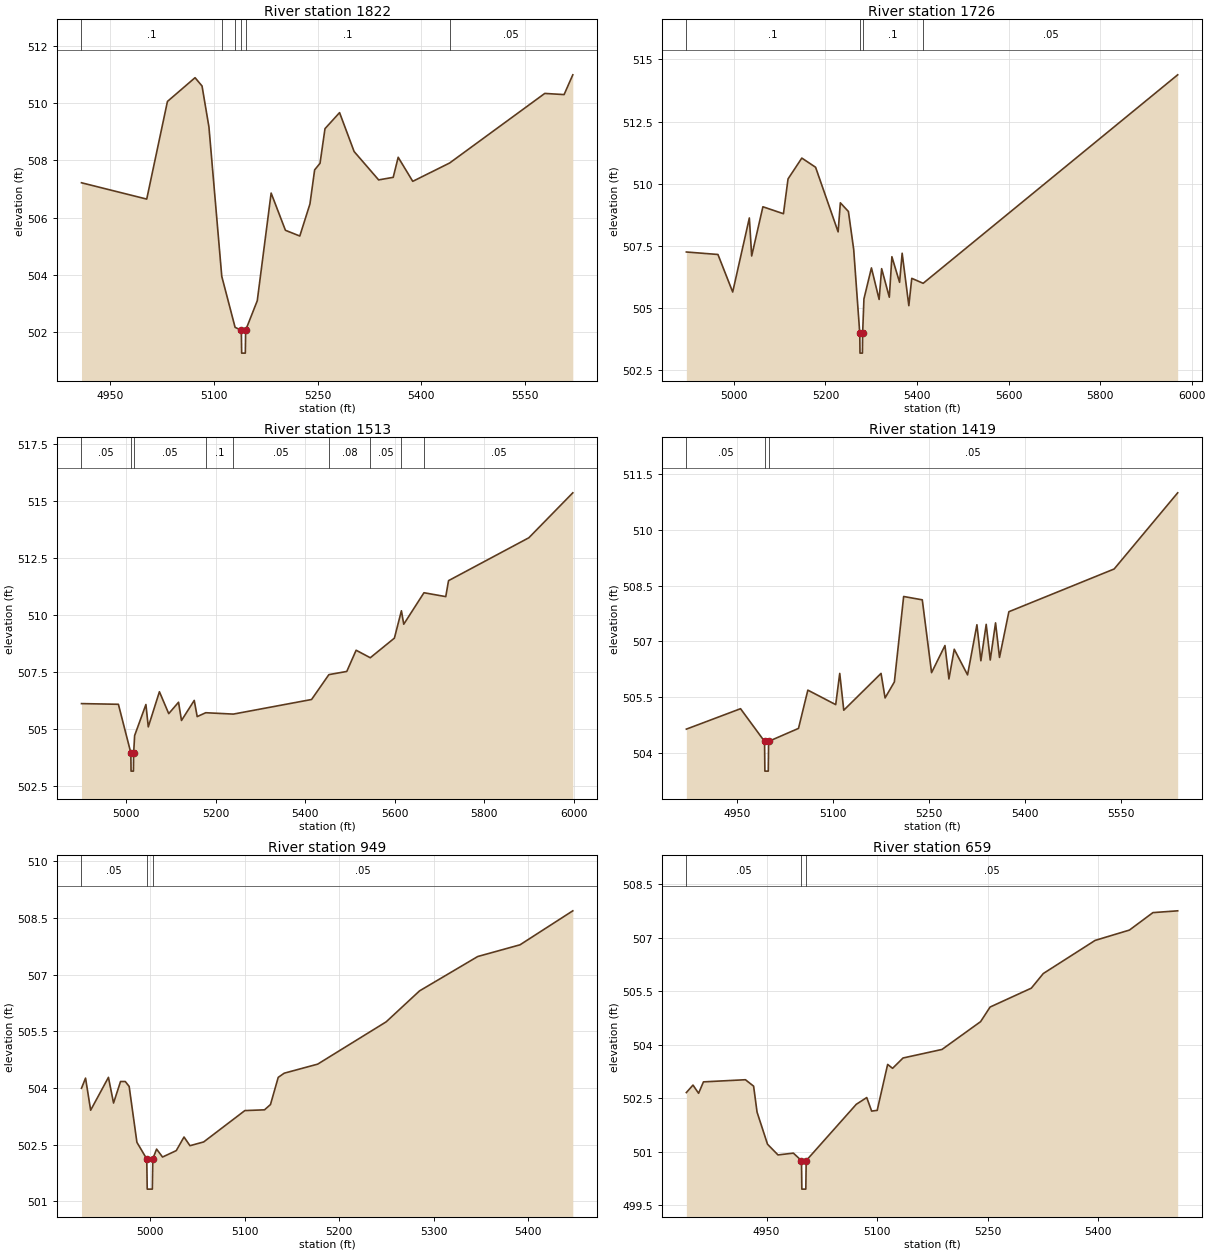
Type RM Length L Ch R = 1,1822,96,96,96
BEGIN DESCRIPTION:
Mapping XS b67585d3
END DESCRIPTION:
XS GIS Cut Line= 5
      2037349.96     13523649.98      2037303.95     13523618.96
      2037077.55     13523628.89      2037041.96     13523677.50
      2036786.47     13523944.08
#Sta/Elev= 30
  4908.1  507.22  5002.6  506.65  5032.6  510.06  5072.6  510.89  5082.7  510.60
  5092.7  509.17  5111.3  503.95  5130.6  502.17  5139.6  502.07  5140.1  501.27
  5145.4  501.27  5145.9  502.07  5162.7  503.10  5182.8  506.86  5203.5  505.56
  5224.3  505.36  5239.0  506.48  5245.8  507.67  5253.6  507.90  5260.8  509.11
  5281.9  509.67  5303.0  508.31  5338.5  507.32  5359.6  507.41  5366.8  508.11
  5387.9  507.27  5441.3  507.91  5579.1  510.34  5607.1  510.30  5619.7  510.99
#Mann=6,-1,0
  4908.1     0.1       0  5111.3    0.05       0  5130.6     0.1       0
  5139.6    0.07       0  5145.9     0.1       0  5441.3    0.05       0
Bank Sta=5139.6,5145.9
Exp/Cntr=0.3,0.1

Type RM Length L Ch R = 1,1726,213,213,213
BEGIN DESCRIPTION:
Mapping XS 4c822707
END DESCRIPTION:
XS GIS Cut Line= 6
      2037352.68     13523581.73      2037306.82     13523530.14
      2037209.40     13523515.81      2037040.34     13523530.14
      2036914.26     13523593.17      2036579.51     13524085.29
#Sta/Elev= 30
  4896.2  507.25  4965.2  507.15  4997.4  505.64  5033.8  508.62  5038.9  507.09
  5063.4  509.07  5108.3  508.79  5118.3  510.19  5148.4  511.03  5178.5  510.66
  5227.7  508.06  5232.6  509.23  5250.2  508.88  5261.7  507.36  5275.0  503.98
  5275.5  503.18  5280.8  503.18  5281.3  503.98  5284.1  505.36  5300.5  506.61
  5317.3  505.34  5322.8  506.58  5339.6  505.43  5345.2  507.06  5362.0  506.03
  5367.6  507.20  5382.2  505.09  5388.6  506.19  5413.5  505.99  5969.5  514.38
#Mann=4,-1,0
  4896.2     0.1       0  5275.0    0.07       0  5281.3     0.1       0
  5413.5    0.05       0
Bank Sta=5275,5281.3
Exp/Cntr=0.3,0.1

Type RM Length L Ch R = 1,1513,94,94,94
BEGIN DESCRIPTION:
Mapping XS 669badd9
END DESCRIPTION:
XS GIS Cut Line= 5
      2037238.07     13523366.83      2037203.67     13523343.89
      2037077.59     13523389.73      2036765.26     13523659.08
      2036461.52     13524068.85
#Sta/Elev= 30
  4900.0  506.13  4982.5  506.10  5010.3  503.97  5010.8  503.17  5016.1  503.17
  5016.6  503.97  5018.8  504.73  5044.0  506.09  5049.3  505.11  5074.2  506.65
  5095.0  505.69  5116.9  506.19  5123.5  505.39  5152.0  506.27  5158.6  505.56
  5177.7  505.73  5239.4  505.67  5414.2  506.31  5452.9  507.40  5492.9  507.54
  5513.8  508.47  5545.4  508.14  5599.3  509.00  5615.0  510.20  5620.2  509.61
  5665.4  510.99  5714.1  510.82  5720.3  511.52  5899.8  513.40  5998.0  515.37
#Mann=9,-1,0
  4900.0    0.05       0  5010.3    0.04       0  5016.6    0.05       0
  5177.7     0.1       0  5239.4    0.05       0  5452.9    0.08       0
  5545.4    0.05       0  5615.0    0.08       0  5665.4    0.05       0
Bank Sta=5010.3,5016.6
Exp/Cntr=0.3,0.1

Type RM Length L Ch R = 1,1419,470,470,470
BEGIN DESCRIPTION:
Mapping XS a9fd7b47
END DESCRIPTION:
XS GIS Cut Line= 4
      2037117.71     13523183.43      2037126.30     13523263.66
      2036836.90     13523484.29      2036579.50     13523678.77
#Sta/Elev= 30
  4871.1  504.64  4955.7  505.19  4993.2  504.31  4993.7  503.51  4999.0  503.51
  4999.5  504.31  5046.2  504.66  5060.8  505.69  5104.3  505.30  5110.6  506.14
  5116.9  505.15  5175.1  506.14  5181.4  505.48  5195.9  505.91  5210.4  508.21
  5239.5  508.12  5254.0  506.16  5274.9  506.89  5281.1  505.99  5289.4  506.79
  5310.2  506.10  5324.8  507.45  5331.0  506.48  5339.3  507.46  5345.6  506.50
  5353.9  507.50  5360.1  506.57  5374.7  507.80  5539.1  508.95  5638.3  511.00
#Mann=3,-1,0
  4871.1    0.05       0  4993.2    0.04       0  4999.5    0.05       0
Bank Sta=4993.2,4999.5
Exp/Cntr=0.3,0.1

Type RM Length L Ch R = 1,949,290,290,290
BEGIN DESCRIPTION:
Mapping XS b4aba66e
END DESCRIPTION:
XS GIS Cut Line= 4
      2036753.78     13523071.67      2036710.82     13523054.49
      2036515.98     13523306.64      2036527.39     13523460.69
#Sta/Elev= 30
  4927.6  503.99  4931.9  504.26  4937.3  503.41  4956.1  504.28  4961.5  503.60
  4968.9  504.17  4973.9  504.17  4978.0  504.04  4986.2  502.56  4996.6  502.12
  4997.1  501.32  5002.5  501.32  5003.0  502.12  5007.0  502.38  5013.3  502.17
  5027.8  502.34  5036.0  502.70  5042.3  502.47  5056.8  502.57  5100.3  503.40
  5121.1  503.42  5127.4  503.56  5135.6  504.28  5141.9  504.39  5177.3  504.63
  5249.7  505.75  5285.0  506.57  5346.5  507.48  5391.2  507.79  5447.0  508.69
#Mann=3,-1,0
  4927.6    0.05       0  4996.6    0.03       0  5003.0    0.05       0
Bank Sta=4996.6,5003
Exp/Cntr=0.3,0.1

Type RM Length L Ch R = 1,659,272,272,272
BEGIN DESCRIPTION:
Mapping XS 6c9709ab
END DESCRIPTION:
XS GIS Cut Line= 4
      2036593.32     13522899.73      2036536.04     13522833.85
      2036341.19     13523005.77      2036232.31     13523306.63
#Sta/Elev= 30
  4841.1  502.66  4850.1  502.87  4857.7  502.64  4864.3  502.96  4921.3  503.02
  4932.4  502.84  4937.1  502.11  4951.3  501.21  4965.5  500.91  4986.4  500.96
  4997.4  500.75  4997.9  499.95  5003.3  499.95  5003.8  500.75  5071.8  502.33
  5086.0  502.52  5092.7  502.14  5100.2  502.16  5114.4  503.45  5121.1  503.34
  5135.3  503.63  5188.2  503.87  5240.6  504.65  5253.5  505.06  5309.5  505.59
  5325.7  506.00  5396.1  506.93  5442.7  507.22  5474.6  507.71  5508.2  507.76
#Mann=3,-1,0
  4841.1    0.05       0  4997.4    0.03       0  5003.8    0.05       0
Bank Sta=4997.4,5003.8
Exp/Cntr=0.3,0.1

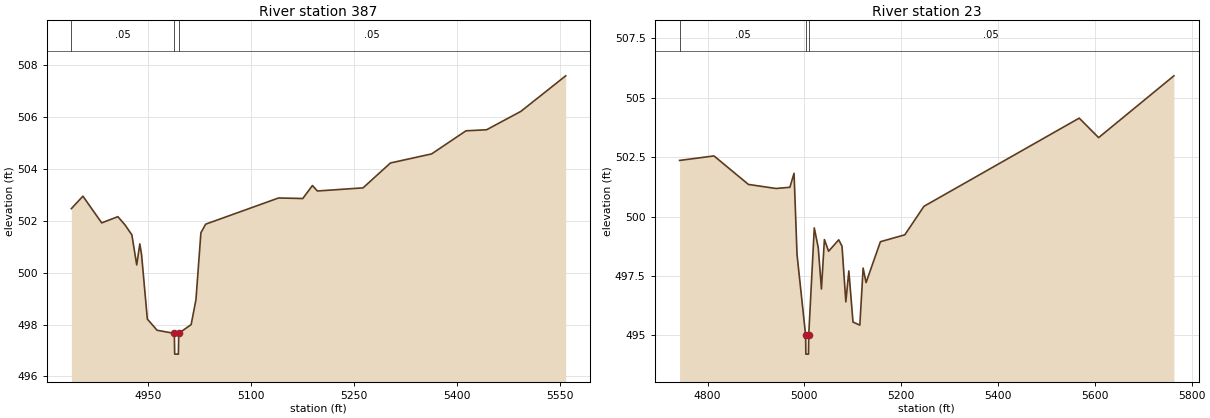
Type RM Length L Ch R = 1,387,364,364,364
BEGIN DESCRIPTION:
Mapping XS e6ab1b8c
END DESCRIPTION:
XS GIS Cut Line= 4
      2036441.43     13522659.06      2036341.19     13522639.01
      2036152.08     13522833.85      2036152.08     13523180.30
#Sta/Elev= 30
  4838.0  502.47  4854.8  502.95  4882.2  501.92  4905.7  502.16  4915.9  501.85
  4926.1  501.46  4933.2  500.30  4937.7  501.11  4940.2  500.71  4948.7  498.21
  4962.9  497.78  4988.0  497.66  4988.5  496.86  4993.9  496.86  4994.4  497.66
  5012.5  498.00  5019.5  498.96  5026.7  501.54  5033.6  501.87  5139.8  502.88
  5175.1  502.86  5189.2  503.36  5196.4  503.15  5262.9  503.27  5302.9  504.23
  5362.9  504.58  5412.9  505.47  5442.9  505.51  5492.9  506.22  5558.2  507.59
#Mann=3,-1,0
  4838.0    0.05       0  4988.0    0.03       0  4994.4    0.05       0
Bank Sta=4988,4994.4
Exp/Cntr=0.3,0.1

Type RM Length L Ch R = 1,23,0,0,0
BEGIN DESCRIPTION:
UNT 175 in Lagunillas Cr Wtrshd 1.0
END DESCRIPTION:
XS GIS Cut Line= 4
      2036344.18     13522516.61      2036196.65     13522349.21
      2035991.53     13522494.91      2035955.75     13523040.21
#Sta/Elev= 30
  4742.1  502.36  4813.2  502.55  4884.4  501.35  4941.3  501.18  4970.0  501.23
  4978.6  501.82  4984.8  498.39  5002.5  495.01  5003.0  494.21  5008.4  494.21
  5008.9  495.01  5020.4  499.52  5028.6  498.69  5035.2  496.95  5041.3  499.03
  5050.0  498.54  5070.9  499.02  5077.7  498.75  5085.6  496.41  5091.8  497.71
  5100.4  495.56  5114.5  495.43  5121.3  497.83  5127.4  497.22  5157.0  498.94
  5207.4  499.23  5247.0  500.43  5567.7  504.14  5607.8  503.32  5763.3  505.92
#Mann=3,-1,0
  4742.1    0.05       0  5002.5    0.03       0  5008.9    0.05       0
Bank Sta=5002.5,5008.9
Exp/Cntr=0.3,0.1

Chan Stop Cuts=-1