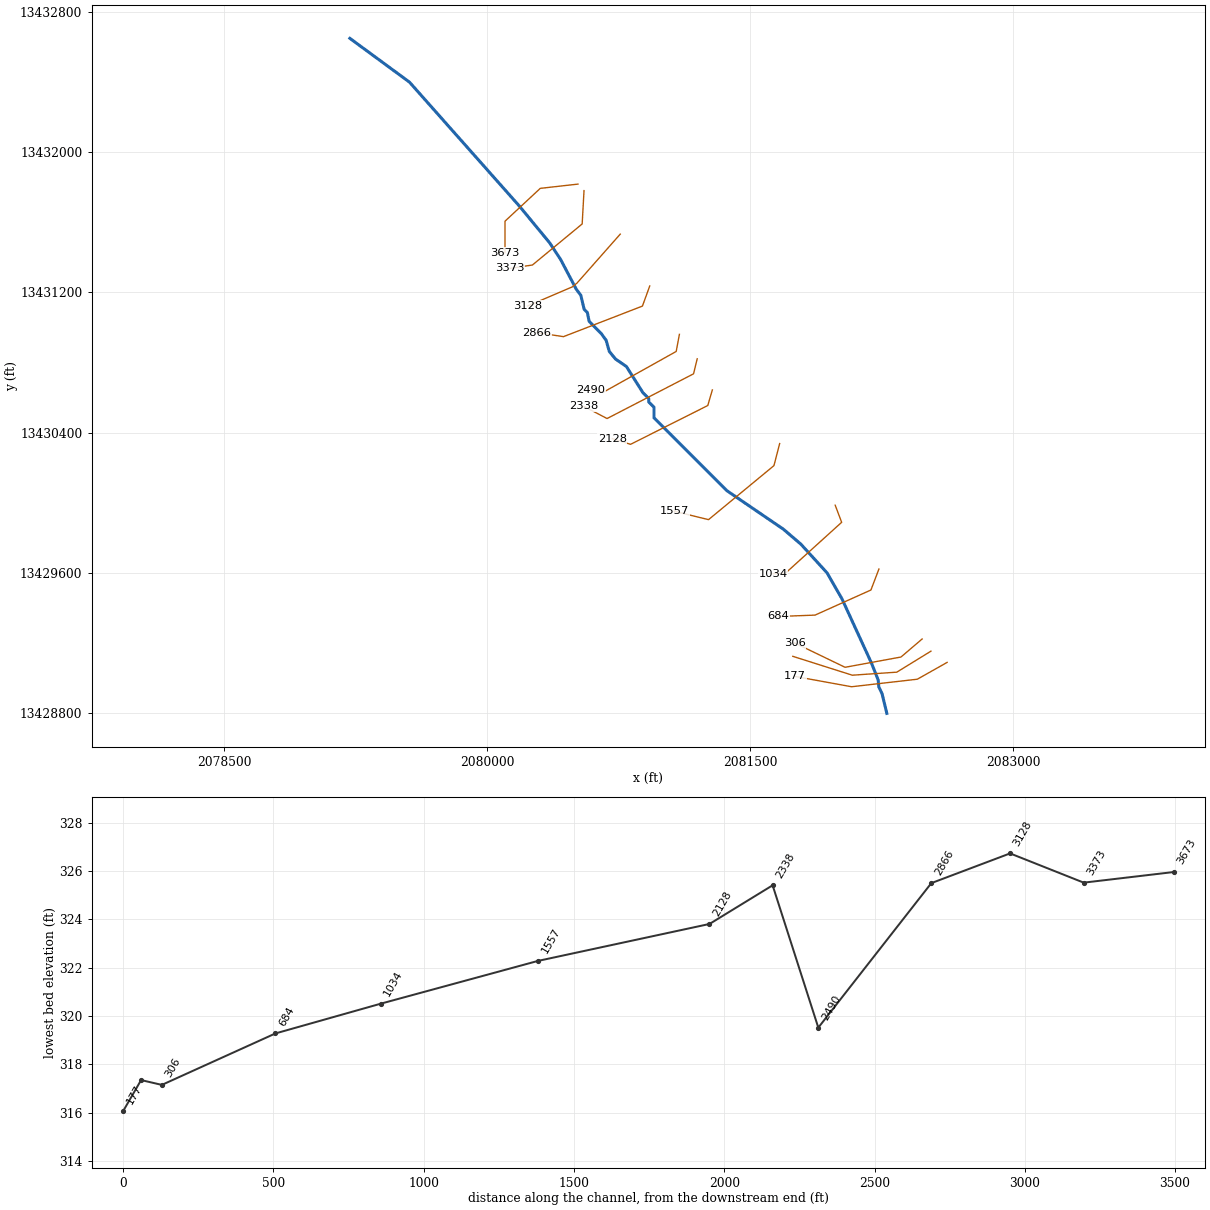
--- UNT 176 in Lagunillas Cr Wtrshd.prj (project) ---

Proj Title=UNT 176 in Lagunillas Cr Wtrshd Base Level Engineering
Current Plan=p01
Default Exp/Contr=0.3,0.1
English Units
Geom File=g01
Flow File=f01
Plan File=p01
BEGIN DESCRIPTION:
UNT 176 in Lagunillas Cr Wtrshd
END DESCRIPTION:

--- UNT 176 in Lagunillas Cr Wtrshd.p01 (plan) ---

Plan Title=Multiple Run
Short Identifier=Multiple
Geom File=g01
Flow File=f01
Subcritical Flow
K Sum by GR= 0
Std Step Tol= 0.01
Critical Tol= 0.01
Num of Std Step Trials= 20
Max Error Tol= 0.3
Flow Tol Ratio= 0.001
Split Flow NTrial= 30
Split Flow Tol= 0.02
Split Flow Ratio= 0.02
Log Output Level= 0
Friction Slope Method= 1
Unsteady Friction Slope Method= 2
Unsteady Bridges Friction Slope Method= 1
Parabolic Critical Depth
Global Vel Dist=  1 , 1 , 1
Global Log Level= 0
CheckData=True
Encroach Param= -1, 0, 0, 0
BEGIN DESCRIPTION:
Multiple Run
END DESCRIPTION:

--- UNT 176 in Lagunillas Cr Wtrshd.f01 (steady flow) ---

Flow Title=Multiple
Number of Profiles=7
Profile Names=10-year,25-year,50-year,1pct_min,100-year,1pct_plu,500-year
River Rch & RM= UNT 176 in Lagun,Reach-1,3673
      41      50      57      32      64     128      82
Boundary for River Rch & Prof#=UNT 176 in Lagun,Reach-1,1
Up Type=0
Dn Type=3
Dn Slope=0.005
Boundary for River Rch & Prof#=UNT 176 in Lagun,Reach-1,2
Up Type=0
Dn Type=3
Dn Slope=0.005
Boundary for River Rch & Prof#=UNT 176 in Lagun,Reach-1,3
Up Type=0
Dn Type=3
Dn Slope=0.005
Boundary for River Rch & Prof#=UNT 176 in Lagun,Reach-1,4
Up Type=0
Dn Type=3
Dn Slope=0.005
Boundary for River Rch & Prof#=UNT 176 in Lagun,Reach-1,5
Up Type=0
Dn Type=3
Dn Slope=0.005
Boundary for River Rch & Prof#=UNT 176 in Lagun,Reach-1,6
Up Type=0
Dn Type=3
Dn Slope=0.005
Boundary for River Rch & Prof#=UNT 176 in Lagun,Reach-1,7
Up Type=0
Dn Type=3
Dn Slope=0.005

--- UNT 176 in Lagunillas Cr Wtrshd.g01 (geometry) ---

Geom Title=Existing Conditions

River Reach=UNT 176 in Lagun,Reach-1
Reach XY= 30
      2079215.60     13432649.37      2079555.88     13432399.37
      2080180.80     13431694.54      2080355.30     13431482.86
      2080418.23     13431387.38      2080507.21     13431218.10
      2080533.25     13431183.38      2080552.51     13431102.82
      2080570.80     13431084.54      2080580.80     13431034.54
      2080650.44     13430964.20      2080677.78     13430926.44
      2080696.01     13430862.64      2080731.16     13430819.67
      2080793.67     13430776.70      2080887.24     13430628.09
      2080920.80     13430594.54      2080920.80     13430574.54
      2080950.80     13430544.54      2080950.80     13430484.54
      2081367.43     13430067.91      2081689.50     13429848.31
      2081788.46     13429763.68      2081938.20     13429599.62
      2082022.83     13429452.48      2082192.10     13429083.99
      2082229.86     13428988.94      2082233.77     13428948.57
      2082252.00     13428910.81      2082279.39     13428797.77

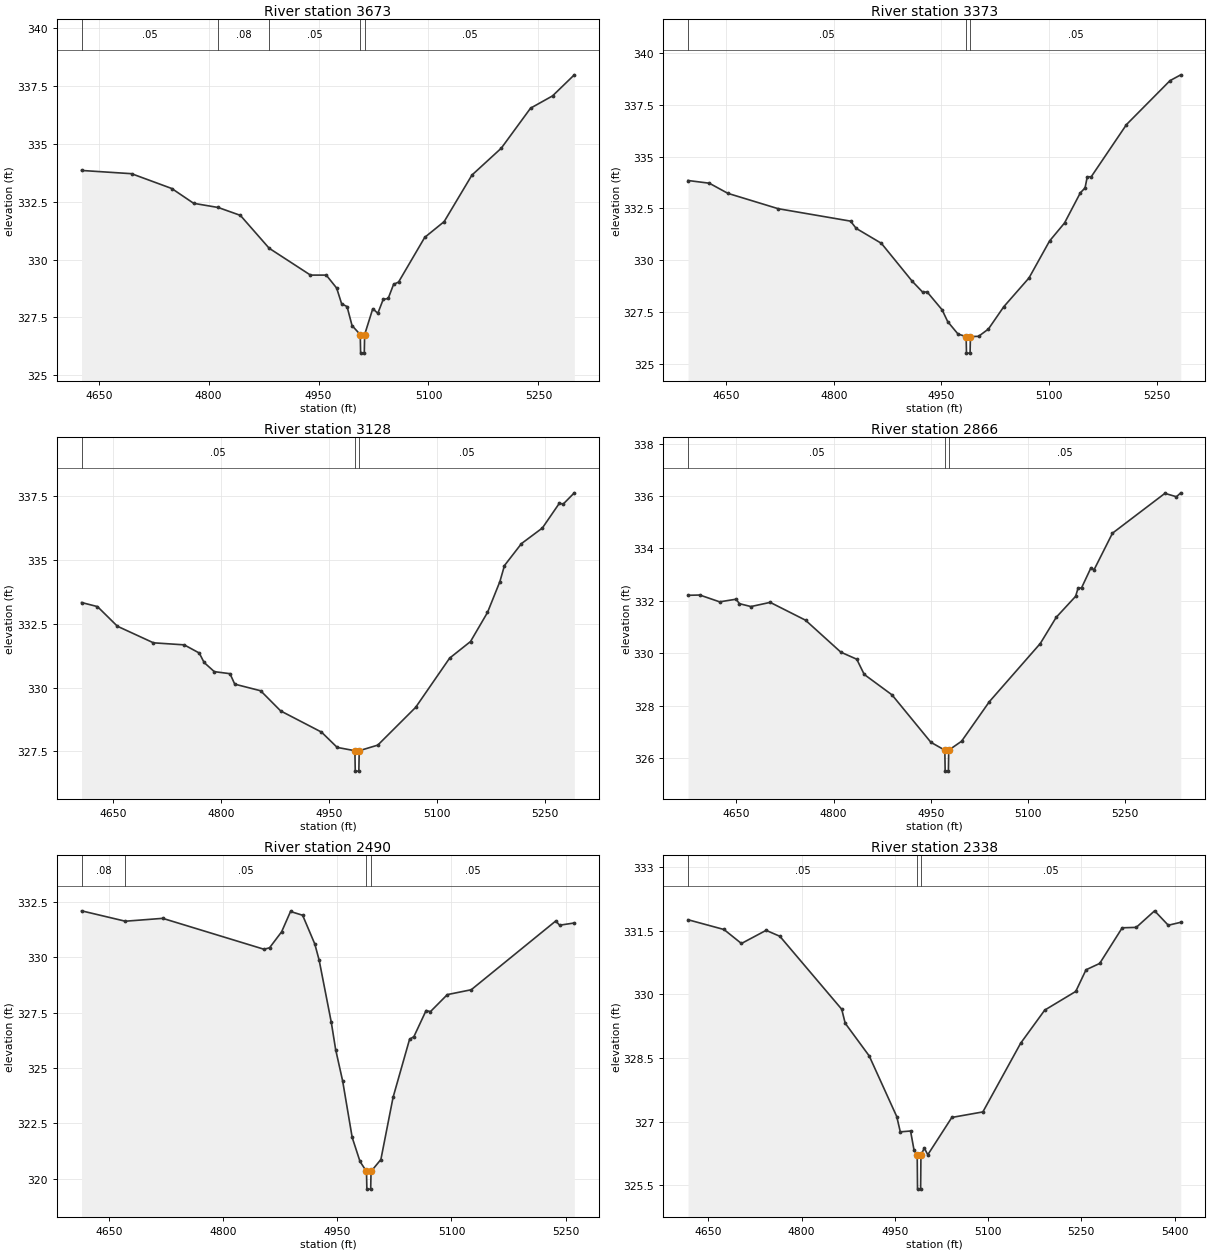
Type RM Length L Ch R = 1,3673,300,300,300
BEGIN DESCRIPTION:
Mapping XS c07e7323
END DESCRIPTION:
XS GIS Cut Line= 4
      2080517.36     13431817.69      2080302.04     13431793.38
      2080100.65     13431605.88      2080100.65     13431425.33
#Sta/Elev= 30
  4626.6  333.85  4694.8  333.71  4749.7  333.07  4779.6  332.43  4813.1  332.25
  4843.3  331.91  4882.6  330.49  4939.0  329.33  4960.5  329.33  4974.7  328.77
  4981.5  328.09  4988.9  327.97  4995.7  327.15  5006.9  326.76  5007.4  325.96
  5012.4  325.96  5012.9  326.76  5024.0  327.88  5030.9  327.68  5038.2  328.28
  5045.0  328.32  5052.4  328.93  5059.2  329.03  5094.9  330.96  5121.4  331.64
  5159.3  333.65  5199.3  334.81  5239.3  336.54  5269.3  337.07  5299.0  337.98
#Mann=5,-1,0
  4626.6    0.05       0  4813.1    0.08       0  4882.6    0.05       0
  5006.9    0.04       0  5012.9    0.05       0
Bank Sta=5006.9,5012.9
Exp/Cntr=0.3,0.1

Type RM Length L Ch R = 1,3373,245,245,245
BEGIN DESCRIPTION:
Mapping XS 6d6452fe
END DESCRIPTION:
XS GIS Cut Line= 4
      2080551.58     13431780.51      2080541.16     13431590.42
      2080257.31     13431356.04      2080130.14     13431336.78
#Sta/Elev= 30
  4596.6  333.85  4626.3  333.72  4652.2  333.23  4722.3  332.49  4823.2  331.89
  4831.1  331.54  4866.2  330.82  4909.2  328.99  4923.6  328.47  4930.1  328.47
  4950.9  327.61  4958.7  327.04  4973.1  326.44  4984.4  326.32  4984.9  325.52
  4989.9  325.52  4990.4  326.32  5001.7  326.33  5015.4  326.68  5036.9  327.76
  5072.1  329.15  5100.7  330.93  5121.6  331.80  5143.7  333.26  5150.2  333.49
  5153.3  334.03  5158.8  334.03  5208.0  336.55  5268.7  338.67  5283.7  338.95
#Mann=3,-1,0
  4596.6    0.05       0  4984.4    0.03       0  4990.4    0.05       0
Bank Sta=4984.4,4990.4
Exp/Cntr=0.3,0.1

Type RM Length L Ch R = 1,3128,262,262,262
BEGIN DESCRIPTION:
Mapping XS afc2aea0
END DESCRIPTION:
XS GIS Cut Line= 4
      2080758.40     13431532.34      2080513.15     13431254.54
      2080486.02     13431231.75      2080229.98     13431122.17
#Sta/Elev= 30
  4606.7  333.34  4628.8  333.18  4656.5  332.41  4706.6  331.76  4749.3  331.68
  4770.2  331.36  4776.9  330.99  4791.1  330.63  4812.9  330.55  4819.5  330.14
  4855.5  329.88  4883.3  329.09  4940.0  328.26  4961.8  327.66  4986.4  327.53
  4986.9  326.73  4991.9  326.73  4992.4  327.53  5018.2  327.75  5070.8  329.23
  5118.0  331.16  5147.0  331.81  5170.6  332.95  5187.8  334.16  5194.2  334.79
  5217.8  335.65  5246.8  336.26  5270.4  337.23  5275.8  337.20  5291.2  337.64
#Mann=3,-1,0
  4606.7    0.05       0  4986.4    0.03       0  4992.4    0.05       0
Bank Sta=4986.4,4992.4
Exp/Cntr=0.3,0.1

Type RM Length L Ch R = 1,2866,376,376,376
BEGIN DESCRIPTION:
Mapping XS 9732c500
END DESCRIPTION:
XS GIS Cut Line= 4
      2080926.57     13431236.23      2080884.91     13431121.67
      2080434.39     13430947.19      2080280.79     13430970.62
#Sta/Elev= 30
  4575.5  332.21  4593.7  332.22  4624.3  331.96  4649.6  332.06  4654.9  331.89
  4672.6  331.78  4702.3  331.94  4756.8  331.26  4811.3  330.04  4835.9  329.77
  4847.4  329.19  4890.3  328.41  4950.3  326.60  4971.8  326.30  4972.3  325.50
  4977.3  325.50  4977.8  326.30  4997.6  326.64  5040.5  328.15  5119.1  330.37
  5143.7  331.37  5173.6  332.17  5177.5  332.49  5182.7  332.49  5197.1  333.25
  5202.2  333.19  5230.5  334.58  5311.4  336.10  5329.2  335.97  5335.9  336.12
#Mann=3,-1,0
  4575.5    0.05       0  4971.8    0.03       0  4977.8    0.05       0
Bank Sta=4971.8,4977.8
Exp/Cntr=0.3,0.1

Type RM Length L Ch R = 1,2490,152,152,152
BEGIN DESCRIPTION:
Mapping XS f9481e00
END DESCRIPTION:
XS GIS Cut Line= 4
      2081095.85     13430960.47      2081077.62     13430862.81
      2080660.95     13430629.74      2080591.89     13430644.07
#Sta/Elev= 30
  4614.1  332.11  4671.6  331.64  4720.7  331.77  4853.9  330.37  4861.1  330.44
  4876.9  331.16  4888.6  332.08  4904.5  331.91  4920.5  330.61  4926.2  329.88
  4942.2  327.06  4947.9  325.83  4957.1  324.41  4969.6  321.86  4979.9  320.77
  4988.4  320.32  4988.9  319.52  4993.9  319.52  4994.4  320.32  5007.3  320.86
  5023.3  323.67  5045.0  326.30  5050.7  326.42  5066.7  327.60  5072.4  327.55
  5094.6  328.32  5126.0  328.54  5237.0  331.65  5242.1  331.46  5261.4  331.56
#Mann=4,-1,0
  4614.1    0.08       0  4671.6    0.05       0  4988.4    0.03       0
  4994.4    0.05       0
Bank Sta=4988.4,4994.4
Exp/Cntr=0.3,0.1

Type RM Length L Ch R = 1,2338,210,210,210
BEGIN DESCRIPTION:
Mapping XS ab10ee6f
END DESCRIPTION:
XS GIS Cut Line= 4
      2081197.41     13430821.13      2081176.58     13430735.21
      2080683.09     13430480.00      2080551.58     13430549.01
#Sta/Elev= 30
  4617.4  331.76  4675.2  331.53  4703.3  331.20  4743.0  331.51  4765.1  331.37
  4864.6  329.65  4870.2  329.32  4908.8  328.55  4953.1  327.12  4958.8  326.76
  4975.3  326.78  4980.9  326.33  4986.0  326.21  4986.5  325.41  4991.5  325.41
  4992.0  326.21  4997.4  326.38  5003.0  326.22  5041.7  327.10  5091.6  327.23
  5152.4  328.85  5191.1  329.63  5241.0  330.07  5257.5  330.58  5279.5  330.73
  5315.7  331.57  5338.3  331.58  5367.8  331.97  5389.8  331.63  5409.9  331.70
#Mann=3,-1,0
  4617.4    0.05       0  4986.0    0.03       0  4992.0    0.05       0
Bank Sta=4986,4992
Exp/Cntr=0.3,0.1

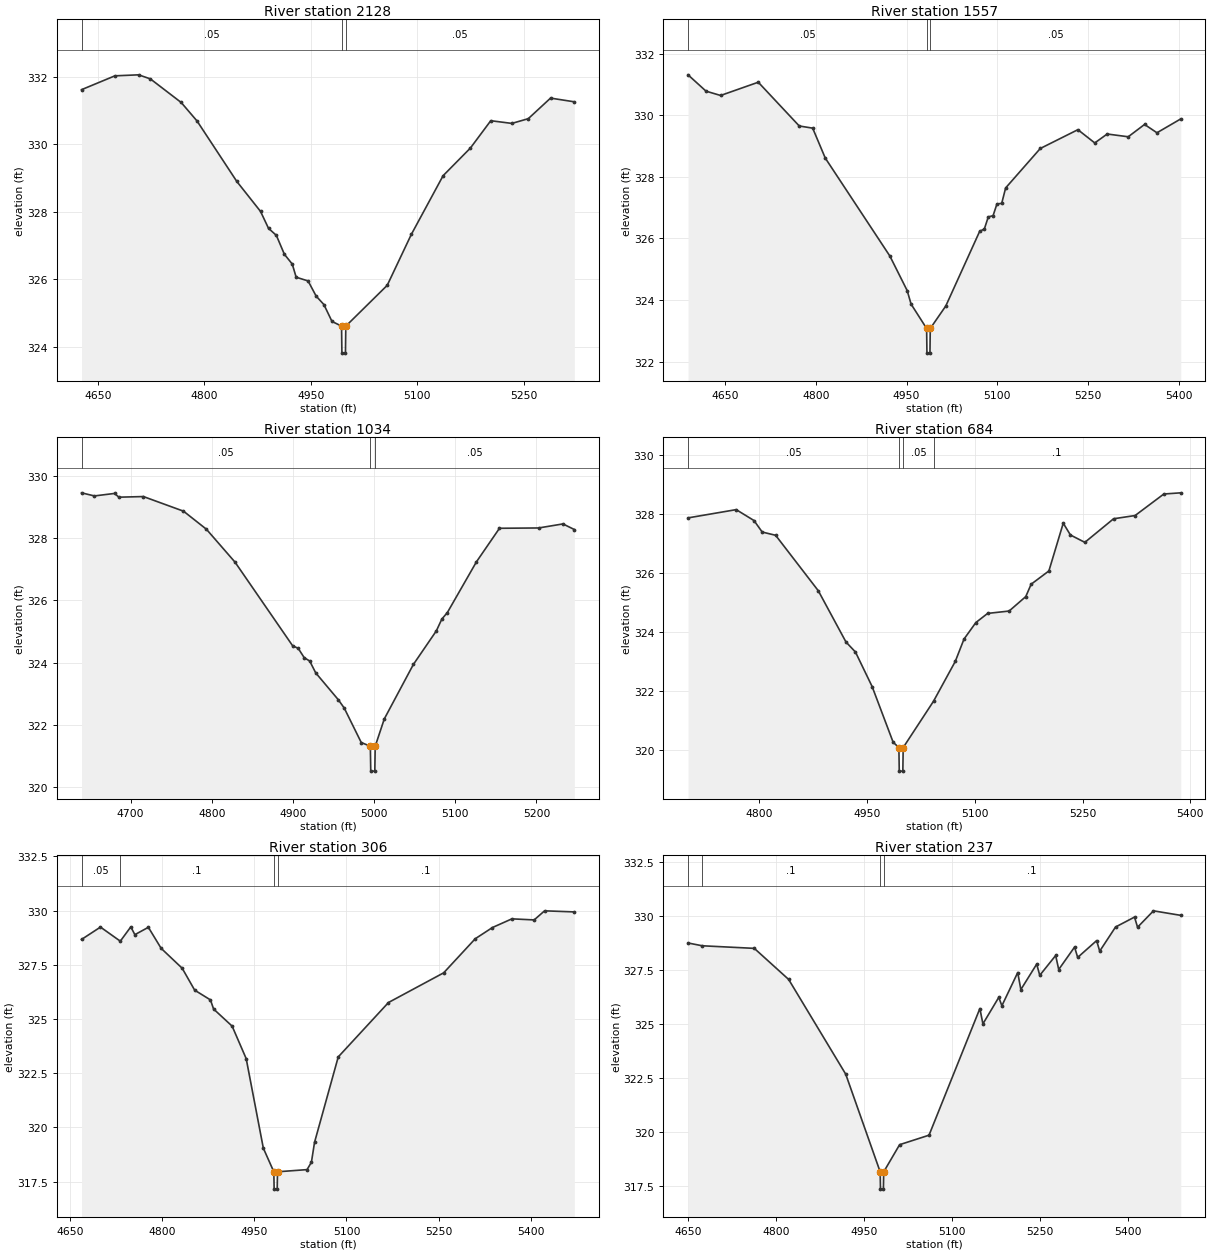
Type RM Length L Ch R = 1,2128,571,571,571
BEGIN DESCRIPTION:
Mapping XS 45ba5eed
END DESCRIPTION:
XS GIS Cut Line= 4
      2081283.77     13430643.15      2081257.74     13430554.22
      2080817.20     13430332.86      2080713.06     13430365.41
#Sta/Elev= 30
  4626.8  331.62  4673.8  332.03  4707.2  332.06  4723.8  331.94  4767.3  331.24
  4789.7  330.69  4845.7  328.90  4879.2  328.01  4890.4  327.51  4901.5  327.30
  4912.8  326.74  4923.9  326.45  4929.4  326.06  4946.2  325.95  4957.6  325.50
  4968.5  325.25  4979.9  324.75  4993.4  324.61  4993.9  323.81  4998.9  323.81
  4999.4  324.61  5057.8  325.82  5091.8  327.33  5136.6  329.07  5175.1  329.89
  5203.8  330.70  5233.5  330.62  5256.7  330.76  5288.1  331.37  5321.6  331.26
#Mann=3,-1,0
  4626.8    0.05       0  4993.4    0.03       0  4999.4    0.05       0
Bank Sta=4993.4,4999.4
Exp/Cntr=0.3,0.1

Type RM Length L Ch R = 1,1557,523,523,523
BEGIN DESCRIPTION:
Mapping XS ca8a3249
END DESCRIPTION:
XS GIS Cut Line= 4
      2081667.89     13430337.20      2081635.34     13430211.34
      2081262.08     13429903.18      2081066.77     13429950.92
#Sta/Elev= 30
  4588.5  331.31  4618.3  330.78  4642.4  330.64  4704.7  331.07  4772.5  329.65
  4794.7  329.58  4815.5  328.61  4922.4  325.43  4951.0  324.31  4957.5  323.87
  4983.2  323.08  4983.7  322.28  4988.7  322.28  4989.2  323.08  5014.9  323.81
  5070.9  326.23  5078.7  326.31  5085.2  326.70  5093.1  326.74  5099.5  327.12
  5107.4  327.14  5113.9  327.64  5171.2  328.92  5233.4  329.53  5261.3  329.10
  5281.9  329.39  5316.7  329.30  5343.7  329.70  5364.2  329.43  5403.6  329.88
#Mann=3,-1,0
  4588.5    0.05       0  4983.2    0.03       0  4989.2    0.05       0
Bank Sta=4983.2,4989.2
Exp/Cntr=0.3,0.1

Type RM Length L Ch R = 1,1034,350,350,350
BEGIN DESCRIPTION:
Mapping XS 9dec8fff
END DESCRIPTION:
XS GIS Cut Line= 4
      2081984.74     13429985.63      2082021.63     13429887.99
      2081700.45     13429597.19      2081631.02     13429595.02
#Sta/Elev= 30
  4639.6  329.46  4655.4  329.36  4680.2  329.44  4685.6  329.32  4715.8  329.34
  4765.2  328.87  4793.4  328.29  4828.7  327.23  4899.7  324.54  4906.5  324.46
  4913.9  324.16  4920.7  324.05  4928.1  323.67  4955.8  322.81  4963.2  322.54
  4984.2  321.43  4995.4  321.31  4995.9  320.51  5000.9  320.51  5001.4  321.31
  5012.6  322.19  5048.4  323.94  5076.7  325.02  5083.5  325.40  5090.3  325.61
  5126.1  327.24  5154.5  328.32  5202.7  328.33  5232.7  328.46  5246.7  328.28
#Mann=3,-1,0
  4639.6    0.05       0  4995.4    0.03       0  5001.4    0.05       0
Bank Sta=4995.4,5001.4
Exp/Cntr=0.3,0.1

Type RM Length L Ch R = 1,684,378,378,378
BEGIN DESCRIPTION:
Mapping XS a3b66c39
END DESCRIPTION:
XS GIS Cut Line= 4
      2082234.33     13429621.51      2082188.73     13429501.70
      2081869.72     13429358.47      2081661.45     13429350.68
#Sta/Elev= 30
  4700.5  327.87  4767.6  328.15  4792.4  327.78  4803.8  327.39  4822.5  327.28
  4881.9  325.40  4920.5  323.66  4933.7  323.32  4956.9  322.15  4986.2  320.26
  4994.2  320.08  4994.7  319.28  4999.7  319.28  5000.2  320.08  5042.4  321.65
  5072.7  323.00  5084.9  323.76  5101.4  324.32  5117.8  324.63  5147.7  324.71
  5170.9  325.20  5178.4  325.62  5203.1  326.07  5223.1  327.69  5233.1  327.29
  5253.2  327.04  5293.2  327.84  5323.2  327.95  5363.2  328.68  5386.8  328.72
#Mann=4,-1,0
  4700.5    0.05       0  4994.2    0.03       0  5000.2    0.05       0
  5042.4     0.1       0
Bank Sta=4994.2,5000.2
Exp/Cntr=0.3,0.1

Type RM Length L Ch R = 1,306,69,69,69
BEGIN DESCRIPTION:
Mapping XS 020530c6
END DESCRIPTION:
XS GIS Cut Line= 4
      2082480.87     13429222.21      2082360.17     13429119.32
      2082041.16     13429060.73      2081753.47     13429199.61
#Sta/Elev= 30
  4668.6  328.67  4699.4  329.24  4731.7  328.59  4748.8  329.25  4755.4  328.89
  4777.4  329.23  4798.2  328.26  4832.5  327.34  4852.8  326.33  4878.5  325.88
  4883.6  325.46  4913.8  324.67  4936.7  323.17  4964.6  319.04  4981.7  317.95
  4982.2  317.15  4987.2  317.15  4987.7  317.95  5035.8  318.05  5042.9  318.39
  5048.0  319.31  5086.6  323.25  5168.4  325.76  5258.3  327.13  5309.6  328.70
  5337.7  329.22  5369.4  329.62  5405.6  329.57  5422.6  329.99  5471.0  329.94
#Mann=4,-1,0
  4668.6    0.05       0  4731.7     0.1       0  4981.7    0.07       0
  4987.7     0.1       0
Bank Sta=4981.7,4987.7
Exp/Cntr=0.3,0.1

Type RM Length L Ch R = 1,237,60,60,60
BEGIN DESCRIPTION:
Mapping XS c5d7c6db
END DESCRIPTION:
XS GIS Cut Line= 4
      2082531.20     13429152.75      2082336.30     13429032.95
      2082082.39     13429015.59      2081743.03     13429123.24
#Sta/Elev= 30
  4650.3  328.76  4674.5  328.63  4763.2  328.51  4821.7  327.07  4918.9  322.68
  4977.6  318.15  4978.1  317.35  4983.1  317.35  4983.6  318.15  5010.7  319.41
  5060.8  319.85  5147.4  325.72  5152.6  325.01  5179.6  326.24  5184.9  325.85
  5211.9  327.39  5217.2  326.60  5244.2  327.78  5249.4  327.26  5276.5  328.18
  5281.7  327.53  5308.7  328.57  5314.0  328.09  5346.3  328.87  5351.5  328.38
  5378.5  329.50  5410.8  329.96  5416.0  329.49  5443.1  330.25  5489.6  330.04
#Mann=4,-1,0
  4650.3    0.05       0  4674.5     0.1       0  4977.6    0.07       0
  4983.6     0.1       0
Bank Sta=4977.6,4983.6
Exp/Cntr=0.3,0.1

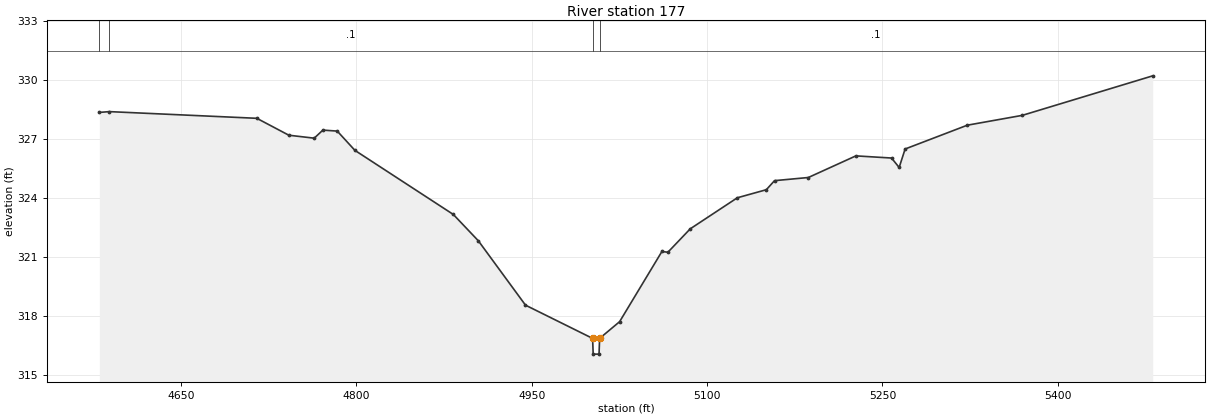
Type RM Length L Ch R = 1,177,0,0,0
BEGIN DESCRIPTION:
UNT 176 in Lagunillas Cr Wtrshd 2.0
END DESCRIPTION:
XS GIS Cut Line= 4
      2082623.23     13429088.53      2082453.38     13428992.70
      2082078.38     13428949.73      2081755.18     13429008.66
#Sta/Elev= 30
  4580.2  328.35  4588.8  328.39  4714.9  328.05  4742.3  327.19  4764.0  327.04
  4771.4  327.45  4783.7  327.40  4798.8  326.42  4883.0  323.16  4904.4  321.82
  4944.7  318.55  5002.1  316.86  5002.6  316.06  5007.6  316.06  5008.1  316.86
  5025.2  317.71  5061.4  321.28  5066.5  321.24  5085.6  322.43  5125.9  324.01
  5150.7  324.42  5157.7  324.88  5186.6  325.04  5227.3  326.14  5257.8  326.03
  5264.3  325.55  5269.4  326.49  5322.6  327.70  5369.6  328.20  5481.2  330.21
#Mann=4,-1,0
  4580.2    0.05       0  4588.8     0.1       0  5002.1    0.07       0
  5008.1     0.1       0
Bank Sta=5002.1,5008.1
Exp/Cntr=0.3,0.1

Chan Stop Cuts=-1