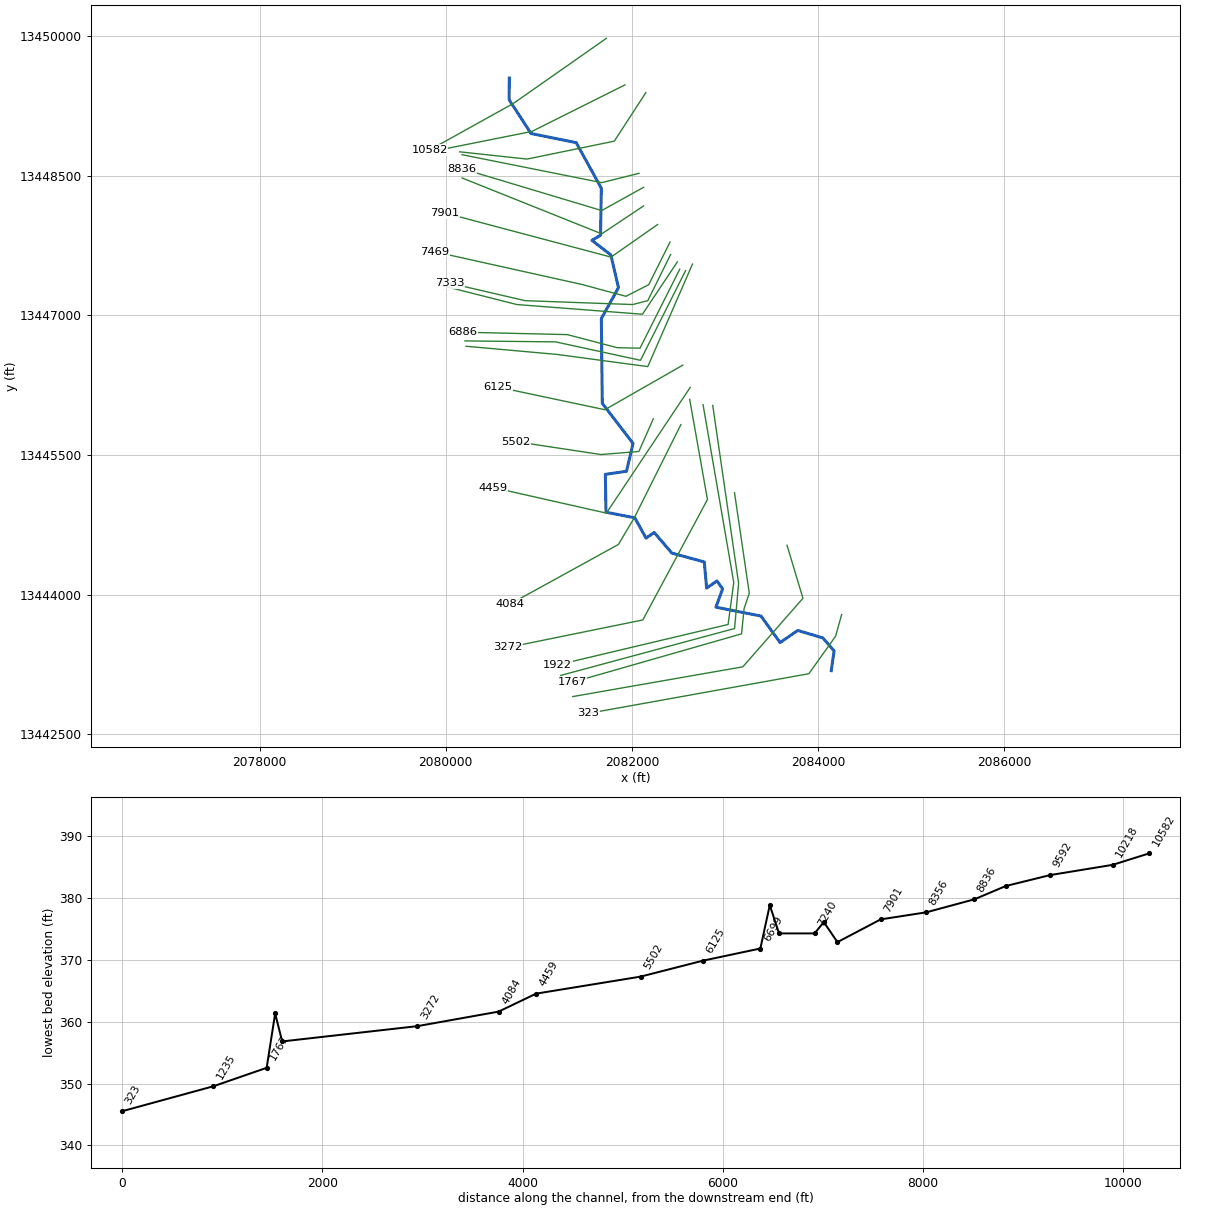
--- UNT 177 SanMiguel Cr Watershed.prj (project) ---

Proj Title=UNT 177 SanMiguel Cr Watershed Base Level Engineering
Current Plan=p01
Default Exp/Contr=0.3,0.1
English Units
Geom File=g01
Flow File=f01
Plan File=p01
Y Axis Title=Elevation
X Axis Title(PF)=Main Channel Distance
X Axis Title(XS)=Station
BEGIN DESCRIPTION:
UNT 177 SanMiguel Cr Watershed
END DESCRIPTION:
DSS Export Rating Curves= 0
DSS Export Rating Curve Sorted= 0
DSS Export Volume Flow Curves= 0
DXF OffsetX= 0
DXF OffsetY= 0
DXF ScaleX= 1
DXF ScaleY= 10

--- UNT 177 SanMiguel Cr Watershed.p01 (plan) ---

Plan Title=Multiple Run
Short Identifier=Multiple
Geom File=g01
Flow File=f01
Subcritical Flow
K Sum by GR= 0
Std Step Tol= 0.01
Critical Tol= 0.01
Num of Std Step Trials= 20
Max Error Tol= 0.3
Flow Tol Ratio= 0.001
Split Flow NTrial= 30
Split Flow Tol= 0.02
Split Flow Ratio= 0.02
Log Output Level= 0
Friction Slope Method= 1
Unsteady Friction Slope Method= 2
Unsteady Bridges Friction Slope Method= 1
Parabolic Critical Depth
Global Vel Dist=  1 , 1 , 1
Global Log Level= 0
CheckData=True
Encroach Param= -1, 0, 0, 0
BEGIN DESCRIPTION:
Multiple Run
END DESCRIPTION:

--- UNT 177 SanMiguel Cr Watershed.f01 (steady flow) ---

Flow Title=Multiple
Number of Profiles=7
Profile Names=10-year,25-year,50-year,1pct_min,100-year,1pct_plu,500-year
River Rch & RM= UNT 177 SanMigue,Reach-1,10582
     201     274     334     203     405     808     604
River Rch & RM= UNT 177 SanMigue,Reach-1,7333
     228     313     383     233     466     929     699
River Rch & RM= UNT 177 SanMigue,Reach-1,4459
     248     341     418     255     509    1015     767
River Rch & RM= UNT 177 SanMigue,Reach-1,323
     272     377     463     284     567    1131     861
Boundary for River Rch & Prof#=UNT 177 SanMigue,Reach-1,1
Up Type=0
Dn Type=3
Dn Slope=0.005
Boundary for River Rch & Prof#=UNT 177 SanMigue,Reach-1,2
Up Type=0
Dn Type=3
Dn Slope=0.005
Boundary for River Rch & Prof#=UNT 177 SanMigue,Reach-1,3
Up Type=0
Dn Type=3
Dn Slope=0.005
Boundary for River Rch & Prof#=UNT 177 SanMigue,Reach-1,4
Up Type=0
Dn Type=3
Dn Slope=0.005
Boundary for River Rch & Prof#=UNT 177 SanMigue,Reach-1,5
Up Type=0
Dn Type=3
Dn Slope=0.005
Boundary for River Rch & Prof#=UNT 177 SanMigue,Reach-1,6
Up Type=0
Dn Type=3
Dn Slope=0.005
Boundary for River Rch & Prof#=UNT 177 SanMigue,Reach-1,7
Up Type=0
Dn Type=3
Dn Slope=0.005

--- UNT 177 SanMiguel Cr Watershed.g01 (geometry) ---

Geom Title=Existing Conditions
Program Version=5.05

River Reach=UNT 177 SanMigue,Reach-1
Reach XY= 30
      2080681.62     13449549.35       2080680.8     13449314.54
      2080915.65     13448952.54       2081400.8     13448854.54
       2081670.8     13448364.54      2081662.01     13447859.99
      2081569.65     13447805.13      2081773.12     13447648.19
       2081854.8     13447296.93       2081670.8     13446964.54
       2081680.8     13446054.54      2082011.66     13445623.04
       2081940.8     13445324.54      2081713.74      13445291.1
       2081720.8     13444884.54       2082030.8     13444824.54
      2082150.62     13444606.39      2082238.81     13444666.81
       2082428.4     13444445.28      2082776.31     13444350.83
      2082802.01     13444069.58      2082913.12     13444146.67
      2082973.54     13444061.25      2082901.31     13443864.72
      2083386.24      13443769.1       2083590.8     13443484.54
       2083780.8     13443614.54       2084050.8     13443534.54
       2084170.8     13443394.54      2084140.66     13443182.88

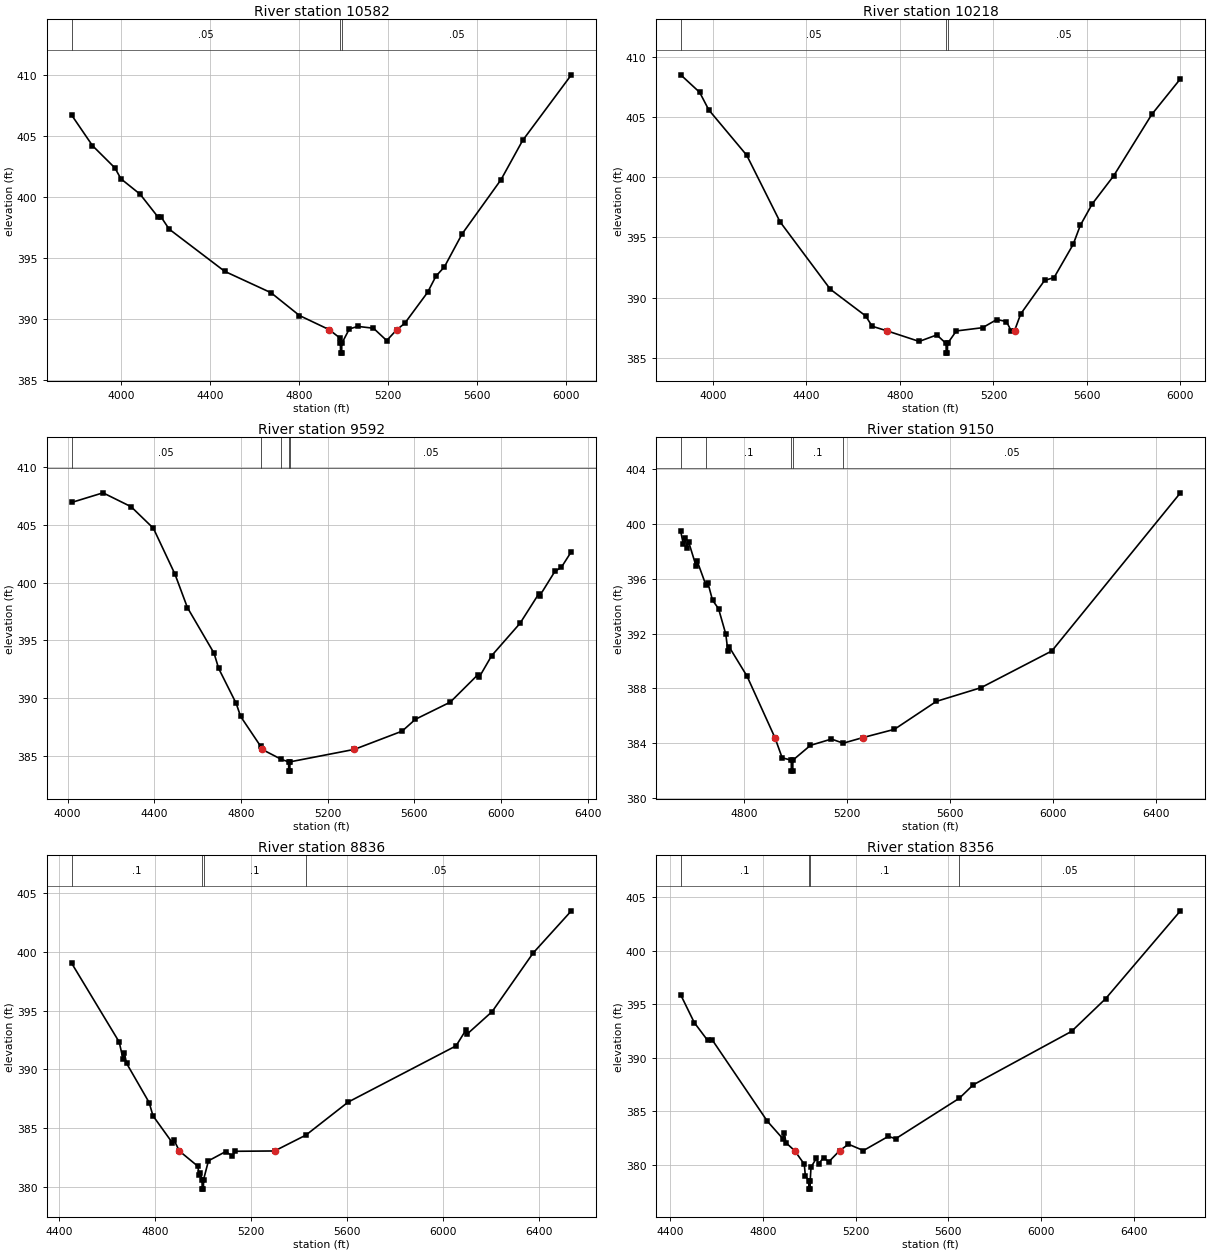
Type RM Length L Ch R = 1 ,10582   ,364,364,364
BEGIN DESCRIPTION:
UNT 177 SanMiguel Cr Watershed 23.0
END DESCRIPTION:
XS GIS Cut Line= 3
      2081725.01     13449975.01        2080725.       13449275.
      2079825.03     13448775.02
#Sta/Elev= 30
  3775.9  406.74  3869.6  404.24  3970.8  402.41  3997.8  401.52  4084.1  400.26
  4164.3   398.4  4178.7  398.39  4214.9   397.4  4465.1  393.94  4673.5  392.19
  4801.7  390.32 4935.23 389.166  4983.1  388.49  4986.1  388.04  4986.6  387.24
  4991.8  387.24  4992.3  388.04  5026.3  389.22  5064.1  389.43    5135  389.28
  5194.5  388.27 5240.42389.1663  5275.7  389.68  5378.7  392.22  5416.4  393.55
  5454.2   394.3  5534.2  397.01  5709.3  401.45  5806.5  404.66  6026.1  410.04
#Mann= 3 ,-1 , 0
  3775.9     .05       0  4986.1    .035       0  4992.3     .05       0
Bank Sta=4935.23,5240.42
XS Rating Curve= 0 ,0
Exp/Cntr=0.3,0.1

Type RM Length L Ch R = 1 ,10218   ,626,626,626
BEGIN DESCRIPTION:
UNT 177 SanMiguel Cr Watershed 22.0
END DESCRIPTION:
XS GIS Cut Line= 3
      2081924.96     13449474.98        2080925.       13448975.
      2079924.99       13448775.
#Sta/Elev= 30
    3862  408.48    3943  407.03  3982.1  405.57  4144.3  401.81  4286.8  396.29
    4502  390.69    4653  388.48  4680.9  387.62 4743.14387.2475  4882.2  386.36
  4957.6   386.9  4997.3  386.19  4997.8  385.39    5003  385.39  5003.5  386.19
  5041.2  387.23  5153.4   387.5  5214.5  388.18  5255.3  388.01  5275.7  387.25
 5290.08387.2476  5316.5  388.64  5418.5  391.42  5459.3  391.66  5540.9  394.41
  5571.5  395.99  5622.5  397.77  5714.2   400.1  5877.4   405.2  5999.8  408.15
#Mann= 3 ,-1 , 0
    3862     .05       0  4997.3    .035       0  5003.5     .05       0
Bank Sta=4743.14,5290.08
XS Rating Curve= 0 ,0
Exp/Cntr=0.3,0.1

Type RM Length L Ch R = 1 ,9592    ,442,442,442
BEGIN DESCRIPTION:
UNT 177 SanMiguel Cr Watershed 21.0
END DESCRIPTION:
XS GIS Cut Line= 4
      2082148.71     13449391.49      2081810.15     13448870.63
      2080872.65     13448677.92      2080149.37     13448755.98
#Sta/Elev= 30
  4018.5  406.91  4163.2  407.74    4293  406.54  4395.7  404.68  4495.3  400.72
  4552.6  397.84  4675.6   393.9  4696.8  392.59  4777.7  389.57  4798.1  388.45
    4891  385.86 4896.93385.6067  4986.7  384.74  5019.6  384.53  5020.1  383.73
  5025.3  383.73  5025.8  384.53 5323.09385.6068  5543.4  387.18  5604.5   388.2
  5765.4  389.68  5893.5  392.06  5898.5  391.82  5956.5  393.69  6087.3  396.48
  6174.1  399.03  6179.1  398.88  6248.2  400.96  6278.4  401.32  6324.3  402.67
#Mann= 5 ,-1 , 0
  4018.5     .05       0    4891      .1       0  4986.7     .05       0
  5019.6    .035       0  5025.8     .05       0
Bank Sta=4896.93,5323.09
XS Rating Curve= 0 ,0
Exp/Cntr=0.3,0.1

Type RM Length L Ch R = 1 ,9150    ,314,314,314
BEGIN DESCRIPTION:
UNT 177 SanMiguel Cr Watershed 20.0
END DESCRIPTION:
XS GIS Cut Line= 3
      2082075.01       13448525.        2081675.       13448425.
      2080175.03     13448724.99
#Sta/Elev= 30
  4552.8  399.46  4563.1  398.51  4570.8  398.97    4576  398.28  4583.7  398.68
  4612.1  396.95  4617.2  397.27  4651.1  395.52  4658.5  395.69  4676.5  394.43
  4699.7  393.82    4728  391.96  4735.8  390.76  4740.9  391.03  4810.5  388.89
 4918.88384.4066  4947.1  382.93  4982.4  382.76  4982.9  381.96  4988.2  381.96
  4988.7  382.76  5056.9  383.84  5138.5   384.3  5184.3     384 5260.61384.4063
  5383.2  385.01  5546.4  387.05  5719.8  388.05  5995.1  390.73  6494.8  402.27
#Mann= 5 ,-1 , 0
  4552.8     .05       0  4651.1      .1       0  4982.4     .07       0
  4988.7      .1       0  5184.3     .05       0
Bank Sta=4918.88,5260.61
XS Rating Curve= 0 ,0
Exp/Cntr=0.3,0.1

Type RM Length L Ch R = 1 ,8836    ,480,480,480
BEGIN DESCRIPTION:
UNT 177 SanMiguel Cr Watershed 19.0
END DESCRIPTION:
XS GIS Cut Line= 3
      2082124.99     13448374.99        2081675.       13448125.
      2080175.01       13448575.
#Sta/Elev= 30
    4452  399.03  4649.9  392.33  4665.9  390.89  4671.6  391.37  4680.8  390.51
  4774.6  387.18  4790.6  386.05  4871.8  383.74  4877.5  384.02 4900.27383.0574
  4977.2  381.76  4983.3  380.99  4988.5  381.22  4994.9  380.61  4995.4  379.81
  5000.7  379.81  5001.2  380.61  5021.6  382.22  5092.9     383  5120.8  382.64
  5133.8  383.03    5297383.0573  5427.7  384.41  5603.6  387.22  6052.6     392
  6093.5  393.34  6098.7     393  6203.1  394.92  6373.6   399.9  6532.8  403.49
#Mann= 4 ,-1 , 0
    4452      .1       0  4994.9     .07       0  5001.2      .1       0
  5427.7     .05       0
Bank Sta=4900.27,5297
XS Rating Curve= 0 ,0
Exp/Cntr=0.3,0.1

Type RM Length L Ch R = 1 ,8356    ,455,455,455
BEGIN DESCRIPTION:
UNT 177 SanMiguel Cr Watershed 18.0
END DESCRIPTION:
XS GIS Cut Line= 3
      2082124.98     13448174.99        2081675.       13447875.
      2080174.96     13448475.02
#Sta/Elev= 30
  4445.2  395.89  4503.8  393.29  4560.9  391.64  4581.9  391.65  4819.2  384.06
  4885.4  382.44  4891.4  382.93  4900.4  382.03 4937.16 381.302  4978.5  380.04
    4983  378.95  4997.7  378.51  4998.2  377.71  5003.5  377.71    5004  378.51
  5007.5  379.76  5030.4  380.59  5039.9  380.07  5061.4  380.65  5084.3  380.27
 5130.58381.3019  5169.1  381.91  5233.7  381.32  5341.4  382.65  5372.4  382.42
  5647.3  386.21  5707.6  387.47  6131.7  392.47  6278.4  395.52  6601.6  403.75
#Mann= 4 ,-1 , 0
  4445.2      .1       0  4997.7     .07       0    5004      .1       0
  5647.3     .05       0
Bank Sta=4937.16,5130.58
XS Rating Curve= 0 ,0
Exp/Cntr=0.3,0.1

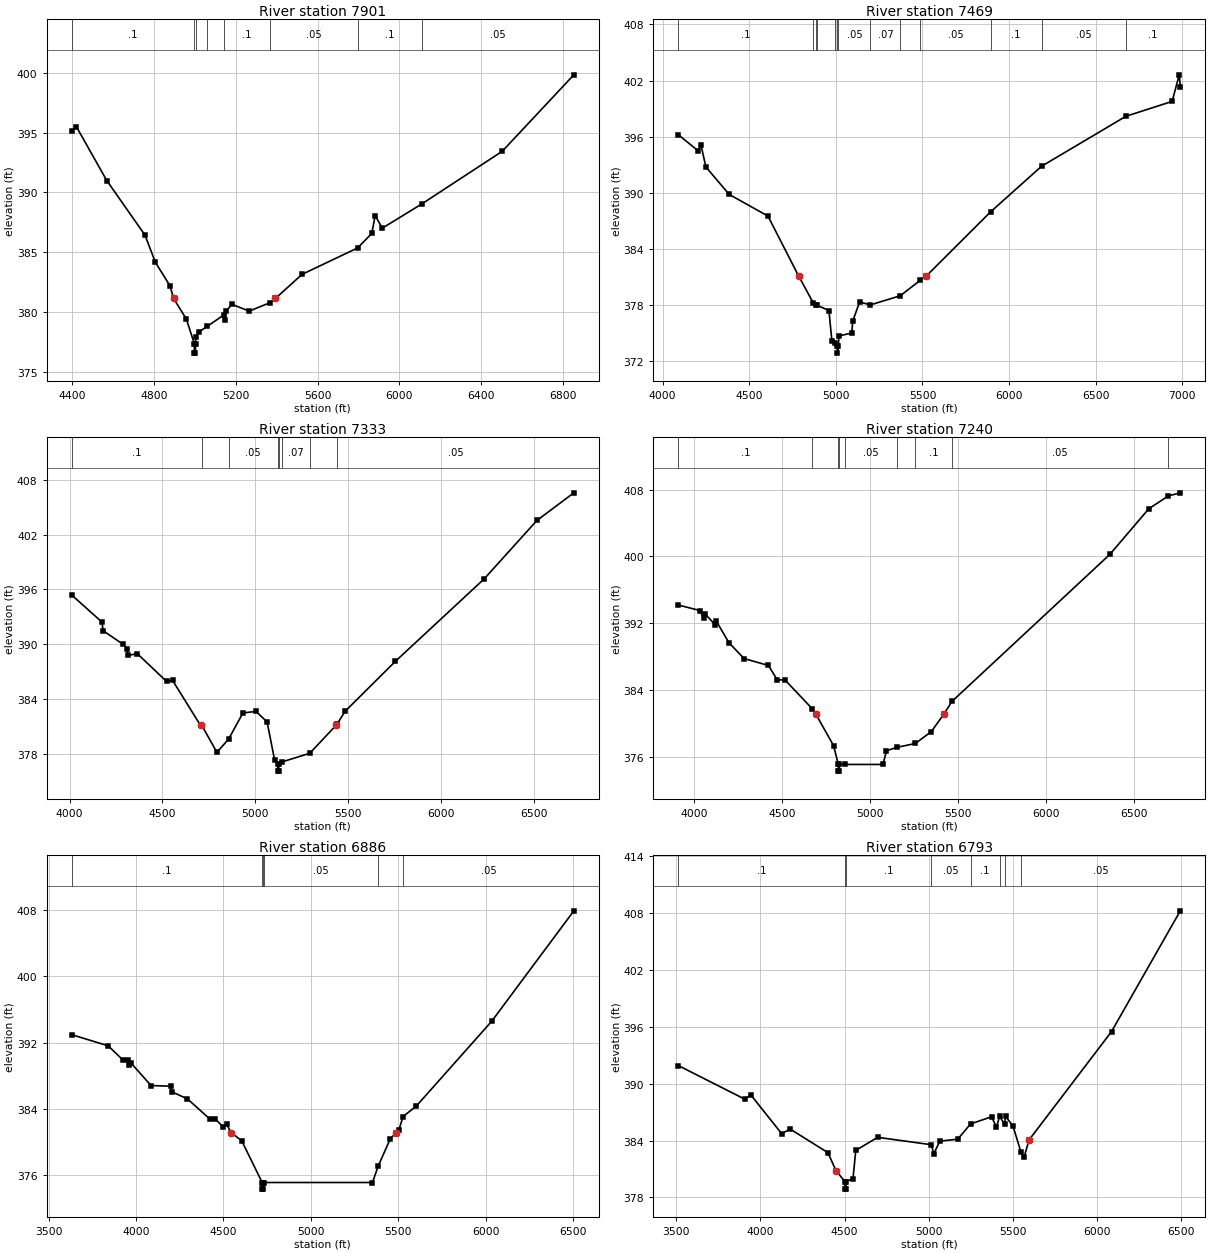
Type RM Length L Ch R = 1 ,7901    ,432,432,432
BEGIN DESCRIPTION:
UNT 177 SanMiguel Cr Watershed 17.0
END DESCRIPTION:
XS GIS Cut Line= 3
        2082275.       13447975.        2081775.       13447625.
      2079988.65     13448099.42
#Sta/Elev= 30
  4396.6  395.09  4418.8   395.5  4567.9  390.99  4755.4  386.42  4805.9  384.16
  4877.4   382.2 4895.29381.1382  4957.7  379.42  4996.4  377.37  4996.9  376.57
  5002.2  376.57  5002.7  377.37  5003.9  377.95  5017.3  378.32  5060.5  378.81
  5140.3  379.75  5144.9  379.36  5151.8  380.05  5179.9  380.65  5265.6  380.08
  5368.4  380.79 5393.88381.1384  5524.3  383.15  5796.7  385.36  5865.7  386.57
  5882.4  388.06  5917.3  387.01  6110.4  389.03  6504.4  393.43  6855.2  399.82
#Mann= 8 ,-1 , 0
  4396.6      .1       0  4996.4     .07       0  5002.7      .1       0
  5060.5     .07       0  5140.3      .1       0  5368.4     .05       0
  5796.7      .1       0  6110.4     .05       0
Bank Sta=4895.29,5393.88
XS Rating Curve= 0 ,0
Exp/Cntr=0.3,0.1

Type RM Length L Ch R = 1 ,7469    ,136,136,136
BEGIN DESCRIPTION:
UNT 177 SanMiguel Cr Watershed 16.0
END DESCRIPTION:
XS GIS Cut Line= 6
       2082409.1     13447787.29      2082179.94     13447328.97
      2081935.15     13447203.97      2081700.78     13447266.47
      2081471.61     13447328.97      2079878.94     13447682.89
#Sta/Elev= 30
    4090  396.23  4204.9   394.5  4221.6  395.11  4249.6  392.78  4383.8  389.85
    4608  387.53 4784.93 381.137  4870.9  378.21  4886.7  378.01  4891.4     378
  4960.2  377.44    4977  374.21  4993.9  373.95  5008.8  373.69  5009.3  372.89
  5015.1  373.69  5017.1  374.72  5092.2  375.04  5097.4   376.3  5137.3  378.36
  5199.1  378.04  5372.2  379.02  5486.9  380.66  5522.8381.1368  5894.5     388
  6187.6  392.85  6674.6  398.19  6941.7  399.78  6982.7  402.62  6988.9  401.37
#Mann= 13 ,-1 , 0
    4090      .1       0  4870.9     .07       0  4886.7      .1       0
  4891.4     .07       0  4993.9     .05       0  5008.8    .035       0
  5015.1     .05       0  5199.1     .07       0  5372.2      .1       0
  5486.9     .05       0  5894.5      .1       0  6187.6     .05       0
  6674.6      .1       0
Bank Sta=4784.93,5522.8
XS Rating Curve= 0 ,0
Exp/Cntr=0.3,0.1

Type RM Length L Ch R = 1 ,7333    ,93,93,93
BEGIN DESCRIPTION:
UNT 177 SanMiguel Cr Watershed 15.0
END DESCRIPTION:
XS GIS Cut Line= 5
      2082414.32     13447651.88      2082169.53     13447157.09
      2082008.07     13447115.42      2080851.82     13447157.09
      2080044.49      13447344.6
#Sta/Elev= 30
  4012.1  395.38    4175  392.42  4180.6  391.49  4287.2  390.01  4309.6  389.51
  4315.2  388.79  4365.7  388.96  4522.7  385.94  4555.3  386.04  4705.6381.1359
  4715.9  381.01    4794  378.18  4857.1  379.64  4934.1  382.49  5004.1  382.66
  5064.2  381.52  5104.2   377.4  5121.1  376.93  5121.6  376.13  5126.9  376.13
  5127.4  376.93  5143.3  377.13    5294  378.08 5435.77381.1355  5442.5  381.31
  5484.4  382.67  5754.6  388.12  6233.7  397.15  6517.8  403.54  6716.7  406.56
#Mann= 8 ,-1 , 0
  4012.1      .1       0  4715.9     .07       0  4857.1     .05       0
  5121.1    .035       0  5127.4     .05       0  5143.3     .07       0
    5294      .1       0  5442.5     .05       0
Bank Sta=4705.6,5435.77
XS Rating Curve= 0 ,0
Exp/Cntr=0.3,0.1

Type RM Length L Ch R = 1 ,7240    ,354,354,354
BEGIN DESCRIPTION:
UNT 177 SanMiguel Cr Watershed 14.0
END DESCRIPTION:
XS GIS Cut Line= 4
      2082487.21     13447573.72      2082112.23     13447011.26
      2080763.28     13447115.42      2079961.17     13447318.56
#Sta/Elev= 30
  3907.7  394.19  4030.6  393.53  4051.6  392.58  4060.7  393.12  4117.7  391.82
  4123.8  392.28  4195.9  389.68    4283  387.77  4421.2  386.95    4471  385.22
  4514.4  385.23  4670.5  381.76 4690.24381.1355  4791.5  377.35  4818.4   375.1
  4818.9   374.3  4824.3   374.3  4824.8   375.1  4855.3   375.1  5072.4   375.1
  5092.4  376.73  5149.7  377.14    5257  377.61  5347.4  379.03 5419.34381.1357
  5464.6  382.64  6362.8  400.24  6584.8  405.71    6696  407.25  6764.1  407.62
#Mann= 9 ,-1 , 0
  3907.7      .1       0  4670.5     .07       0  4818.4    .035       0
  4824.8     .07       0  4855.3     .05       0  5149.7     .07       0
    5257      .1       0  5464.6     .05       0    6696      .1       0
Bank Sta=4690.24,5419.34
XS Rating Curve= 0 ,0
Exp/Cntr=0.3,0.1

Type RM Length L Ch R = 1 ,6886    ,93,93,93
BEGIN DESCRIPTION:
UNT 177 SanMiguel Cr Watershed 13.0
END DESCRIPTION:
XS GIS Cut Line= 5
      2082513.27     13447495.62      2082086.19     13446646.67
       2081841.4     13446651.88      2081304.94     13446792.51
      2080185.19     13446818.55
#Sta/Elev= 30
    3633  392.95  3840.7  391.61  3924.3  389.92  3952.3  389.93  3958.3   389.3
    3969  389.59  4086.2  386.81  4197.8  386.73  4204.6  386.06  4294.1   385.2
    4421  382.79  4450.9  382.82  4495.6  381.86    4518  382.15  4543.7381.1355
  4604.5  380.13  4721.3   375.1  4721.8   374.3  4727.3   374.3  4727.8   375.1
  4730.8   375.1  5351.7   375.1  5384.5  377.08  5452.7  380.34 5486.22381.1356
  5502.7  381.42  5526.4  383.06  5602.7  384.34  6032.9  394.56  6502.8  407.91
#Mann= 6 ,-1 , 0
    3633      .1       0  4721.3    .033       0  4727.8      .1       0
  4730.8     .05       0  5384.5      .1       0  5526.4     .05       0
Bank Sta=4543.7,5486.22
XS Rating Curve= 0 ,0
Exp/Cntr=0.3,0.1

Type RM Length L Ch R = 1 ,6793    ,94,94,94
BEGIN DESCRIPTION:
UNT 177 SanMiguel Cr Watershed 12.0
END DESCRIPTION:
XS GIS Cut Line= 4
      2082575.79     13447480.03       2082091.4     13446516.47
      2081179.94     13446714.38      2080205.96      13446724.8
#Sta/Elev= 30
  3510.9  391.92  3908.3  388.35  3941.5  388.84  4125.7  384.73  4176.9  385.21
  4400.7  382.72 4448.72380.8253    4502  379.67  4502.5  378.87    4508  378.87
  4508.5  379.67  4549.9  379.97  4566.6  382.96  4696.7  384.34  5015.1  383.56
  5030.5  382.61  5066.6  383.94  5172.8  384.14  5248.7  385.75  5373.6  386.51
  5403.2  385.42  5421.9  386.55  5451.2  385.71  5457.4  386.55  5501.5  385.52
  5548.4  382.79    5567  382.24    5597  384.07    6087   395.5  6496.1  408.25
#Mann= 8 ,-1 , 0
  3510.9      .1       0    4502     .07       0  4508.5      .1       0
  5015.1     .05       0  5248.7      .1       0  5421.9     .05       0
  5451.2      .1       0  5548.4     .05       0
Bank Sta=4448.72,5597
XS Rating Curve= 0 ,0
Exp/Cntr=0.3,0.1

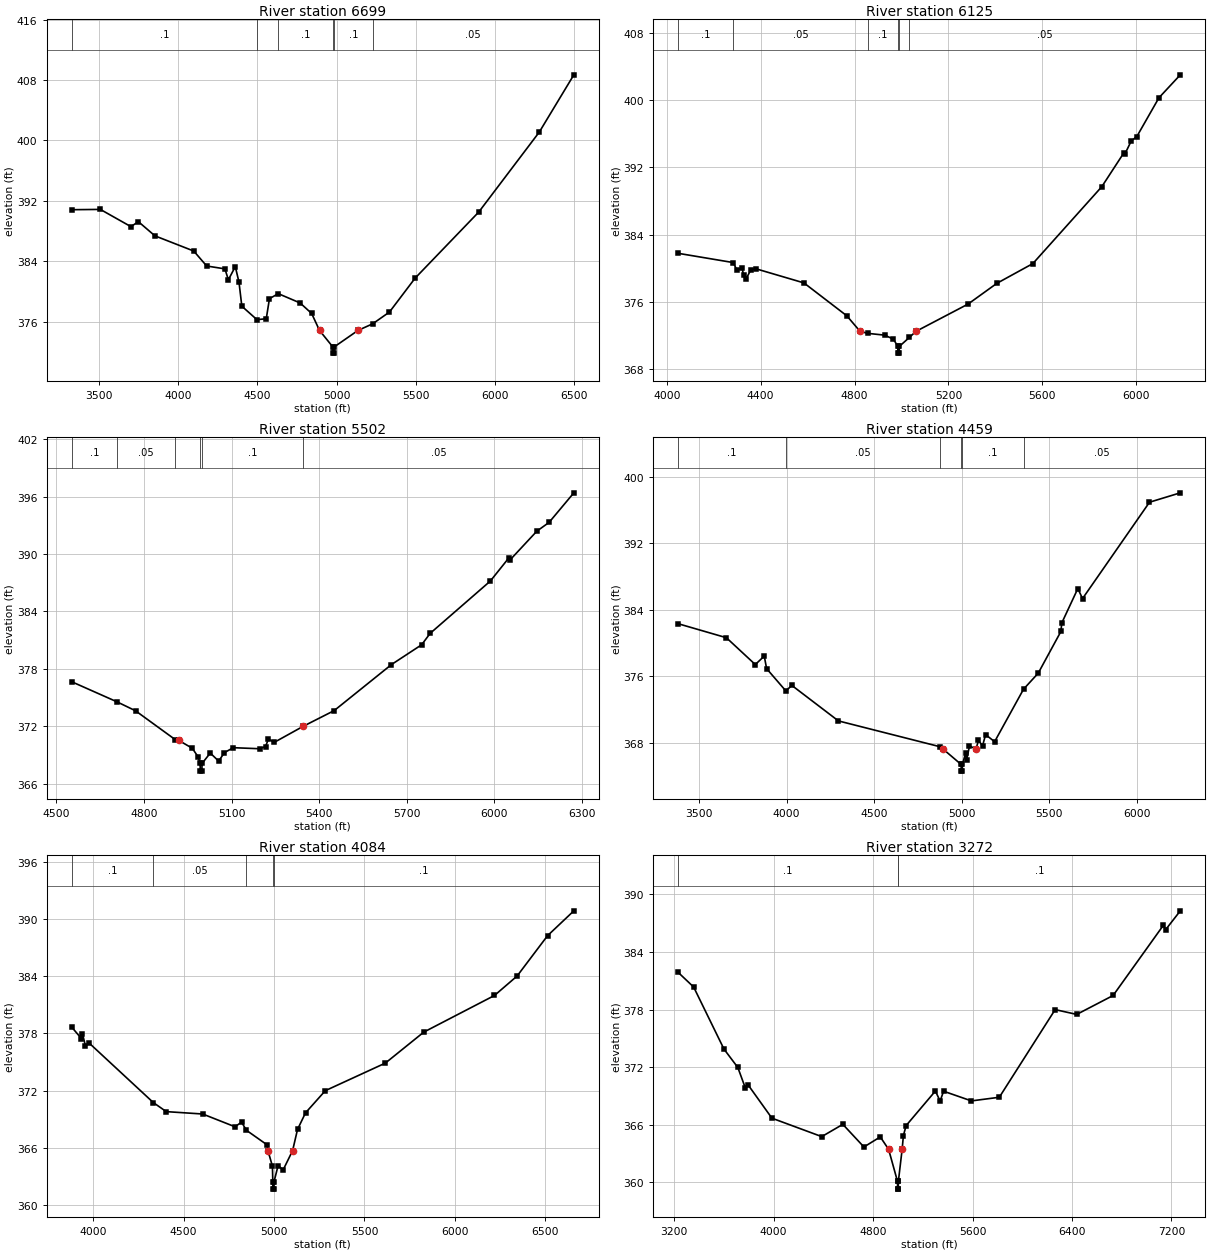
Type RM Length L Ch R = 1 ,6699    ,574,574,574
BEGIN DESCRIPTION:
UNT 177 SanMiguel Cr Watershed 11.0
END DESCRIPTION:
XS GIS Cut Line= 4
      2082649.99     13447549.97      2082169.53     13446448.76
      2081200.78     13446578.97      2080218.17     13446667.35
#Sta/Elev= 30
  3330.8  390.84    3511  390.88  3703.8   388.6  3750.6  389.26  3855.2  387.38
  4099.9  385.37  4181.4  383.39  4296.3  383.01  4318.2  381.57  4361.8  383.31
  4385.1  381.25    4403  378.07  4498.3  376.29    4557  376.41  4577.2  379.07
  4632.9  379.73  4770.4   378.5  4843.2  377.11 4892.75374.8647  4977.5  372.66
    4978  371.86  4983.5  371.86    4984  372.66 5135.37374.8647    5228  375.74
  5333.9   377.3  5495.4  381.78  5897.1  390.54  6278.6  401.12  6496.3  408.69
#Mann= 6 ,-1 , 0
  3330.8      .1       0  4498.3     .05       0  4632.9      .1       0
  4977.5     .07       0    4984      .1       0    5228     .05       0
Bank Sta=4892.75,5135.37
XS Rating Curve= 0 ,0
Exp/Cntr=0.3,0.1

Type RM Length L Ch R = 1 ,6125    ,623,623,623
BEGIN DESCRIPTION:
UNT 177 SanMiguel Cr Watershed 10.0
END DESCRIPTION:
XS GIS Cut Line= 3
      2082546.49     13446464.74      2081708.44     13445985.62
      2080560.55     13446228.79
#Sta/Elev= 30
  4048.9  381.77  4283.3  380.67  4299.2  379.74  4320.8  380.06  4327.1  379.16
  4336.7  378.67  4358.3  379.81  4379.9  379.93  4584.3  378.25  4767.1  374.33
 4823.74372.4729  4857.2  372.24  4928.3  372.03  4965.7  371.55  4984.1  370.69
  4984.6  369.89  4990.1  369.89  4990.6  370.69  5033.6  371.76 5061.09372.4729
  5283.5  375.73  5406.2   378.2  5559.5  380.55  5853.3  389.71  5947.5  393.75
  5952.6  393.65  5978.6  395.15  6002.3  395.67  6096.6  400.29  6187.6  403.02
#Mann= 6 ,-1 , 0
  4048.9      .1       0  4283.3     .05       0  4857.2      .1       0
  4984.1     .07       0  4990.6      .1       0  5033.6     .05       0
Bank Sta=4823.74,5061.09
XS Rating Curve= 0 ,0
Exp/Cntr=0.3,0.1

Type RM Length L Ch R = 1 ,5502    ,1043,1043,1043
BEGIN DESCRIPTION:
UNT 177 SanMiguel Cr Watershed 9.0
END DESCRIPTION:
XS GIS Cut Line= 4
      2082229.09     13445888.01      2082073.73     13445536.89
      2081665.12      13445504.4      2080749.64     13445643.24
#Sta/Elev= 30
  4552.7  376.65  4707.1  374.56    4771  373.62  4906.8  370.61 4919.12370.5247
  4965.5   369.7  4985.5   368.8  4992.3  368.11  4992.8  367.31  4998.4  367.31
  4998.9  368.11  5027.1   369.2  5055.8  368.36  5075.8  369.25  5105.9  369.76
  5196.2  369.65  5216.3  369.88  5226.3  370.66  5246.4  370.32  5345.8     372
  5451.7  373.64  5647.8  378.45  5751.2  380.52  5780.3  381.71  5986.5  387.18
  6050.2  389.61  6055.3  389.43  6145.7  392.39  6187.7  393.31  6272.5   396.4
#Mann= 6 ,-1 , 0
  4552.7      .1       0  4707.1     .05       0  4906.8      .1       0
  4992.3     .07       0  4998.9      .1       0  5345.8     .05       0
Bank Sta=4919.12,5345.8
XS Rating Curve= 0 ,0
Exp/Cntr=0.3,0.1

Type RM Length L Ch R = 1 ,4459    ,375,375,375
BEGIN DESCRIPTION:
UNT 177 SanMiguel Cr Watershed 8.0
END DESCRIPTION:
XS GIS Cut Line= 3
      2082625.03     13446225.04        2081725.       13444875.
      2080510.32     13445149.21
#Sta/Elev= 30
  3381.3  382.29  3656.3  380.61  3821.5  377.38  3872.6   378.4  3886.1  376.89
  3995.9  374.21  4030.3  374.87  4296.3   370.6  4875.8   367.5 4893.64367.2201
  4997.4  365.36  4997.9  364.56  5003.7  364.56  5004.2  365.36  5022.9  366.74
    5028  365.85  5044.9  367.59 5082.37367.2198  5096.1  368.25  5119.6  367.62
  5137.1  368.95  5188.4   368.1  5353.7  374.42  5437.4  376.34    5567  381.36
  5572.2  382.39  5663.7  386.52  5690.7  385.32  6073.1  396.91  6249.1  398.04
#Mann= 6 ,-1 , 0
  3381.3      .1       0  3995.9     .05       0  4875.8      .1       0
  4997.4     .07       0  5004.2      .1       0  5353.7     .05       0
Bank Sta=4893.64,5082.37
XS Rating Curve= 0 ,0
Exp/Cntr=0.3,0.1

Type RM Length L Ch R = 1 ,4084    ,812,812,812
BEGIN DESCRIPTION:
UNT 177 SanMiguel Cr Watershed 7.0
END DESCRIPTION:
XS GIS Cut Line= 4
      2082525.01     13445825.02        2082025.       13444825.
      2081853.89     13444538.14      2080693.34      13443899.6
#Sta/Elev= 30
  3881.4  378.66  3934.5  377.47  3940.1  377.99  3956.9  376.71  3979.3  376.96
  4332.5  370.74  4404.1  369.79  4605.4  369.54  4784.2   368.2  4820.6  368.69
  4846.6  367.84  4963.1  366.28  4966.4365.6908  4991.1  364.06  4993.3  362.45
  4993.8  361.65  4999.6  361.65  5000.1  362.45  5022.7  364.13  5050.1  363.66
 5102.63365.6917  5129.9  367.92  5174.1  369.66  5283.6  371.99  5615.9  374.89
  5828.1  378.14  6219.2  381.99  6344.2  384.03  6512.8  388.27  6658.1  390.88
#Mann= 5 ,-1 , 0
  3881.4      .1       0  4332.5     .05       0  4846.6      .1       0
  4993.3     .07       0  5000.1      .1       0
Bank Sta=4966.4,5102.63
XS Rating Curve= 0 ,0
Exp/Cntr=0.3,0.1

Type RM Length L Ch R = 1 ,3272    ,1350,1350,1350
BEGIN DESCRIPTION:
UNT 177 SanMiguel Cr Watershed 6.0
END DESCRIPTION:
XS GIS Cut Line= 4
      2082619.71     13446097.15      2082810.69     13445020.74
      2082116.24     13443727.33      2080668.31     13443432.55
#Sta/Elev= 30
  3232.3  381.87  3356.4  380.35  3600.1  373.89  3711.8  371.97  3772.8  369.81
  3793.1  370.18    3986  366.69  4386.8  364.77  4556.4  366.05  4726.1  363.69
  4857.6  364.74 4924.56363.4488  4996.3   360.1  4996.8   359.3  5002.6   359.3
  5003.1   360.1 5033.45363.4493  5043.6  364.88  5065.5  365.92  5300.9  369.52
  5339.1  368.47  5366.7   369.5  5590.8  368.49  5815.2  368.87  6264.3     378
  6437.8   377.5  6730.6  379.47  7135.2  386.79  7152.1  386.31  7271.2  388.29
#Mann= 3 ,-1 , 0
  3232.3      .1       0  4996.3     .07       0  5003.1      .1       0
Bank Sta=4924.56,5033.45
XS Rating Curve= 0 ,0
Exp/Cntr=0.3,0.1

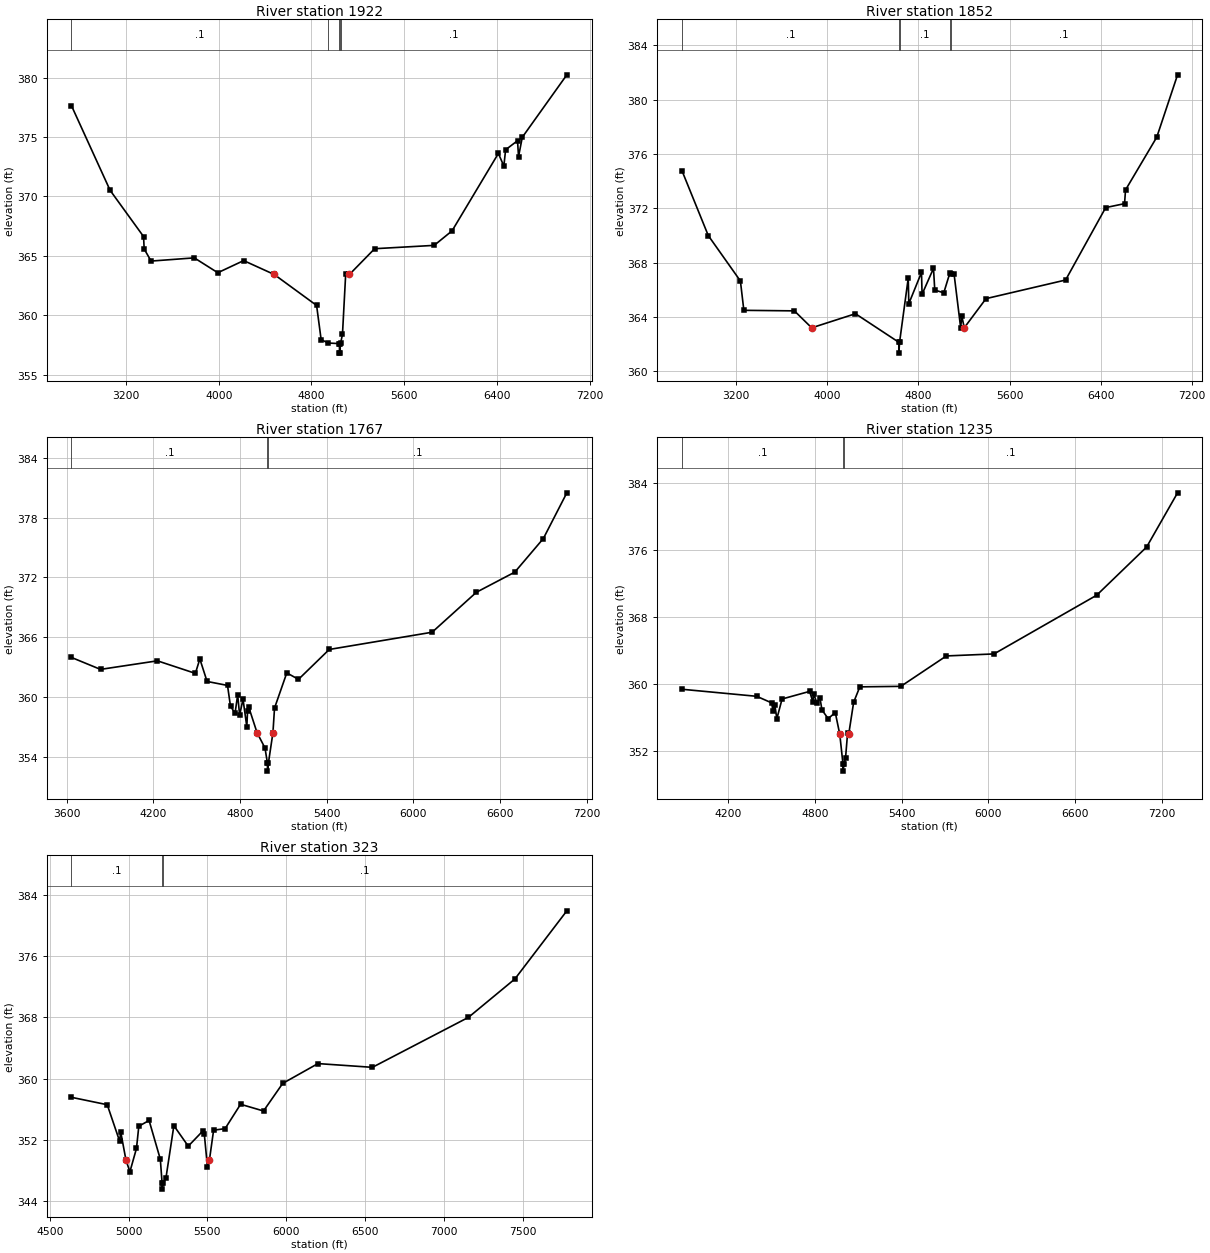
Type RM Length L Ch R = 1 ,1922    ,70,70,70
BEGIN DESCRIPTION:
UNT 177 SanMiguel Cr Watershed 5.0
END DESCRIPTION:
XS GIS Cut Line= 4
      2082763.38     13446039.83      2083093.24     13444130.11
      2083032.48     13443678.72      2081200.86     13443244.69
#Sta/Elev= 30
  2728.5  377.64  3062.2  370.52  3351.1  366.63  3356.2  365.59    3416  364.57
  3788.8  364.84  3991.8  363.59    4215  364.61 4478.84363.4419  4844.5  360.84
  4883.6  357.97  4943.4  357.68  5041.6  357.63  5042.1  356.83  5047.9  356.83
  5048.4  357.63  5051.9  357.66  5067.9  358.43  5095.4  363.45 5127.71363.4418
  5345.5  365.61  5859.3  365.89  6013.5  367.11  6413.3  373.62  6460.7  372.56
  6475.9  373.93  6578.7  374.69  6587.4  373.35  6619.8  374.98  7004.3  380.23
#Mann= 5 ,-1 , 0
  2728.5      .1       0  4943.4     .05       0  5041.6    .033       0
  5048.4     .05       0  5051.9      .1       0
Bank Sta=4478.84,5127.71
XS Rating Curve= 0 ,0
Exp/Cntr=0.3,0.1

Type RM Length L Ch R = 1 ,1852    ,85,85,85
BEGIN DESCRIPTION:
UNT 177 SanMiguel Cr Watershed 4.0
END DESCRIPTION:
XS GIS Cut Line= 4
      2082867.54     13446031.16      2083145.32     13444121.43
      2083101.92     13443635.32      2081235.61     13443131.85
#Sta/Elev= 30
  2724.9  374.74  2954.4     370  3236.4  366.66  3266.7   364.5  3710.4  364.46
 3862.59363.2125  4246.9  364.25  4627.5  362.15    4628  361.35  4634.3  362.15
  4710.5  366.87  4715.5  364.99  4826.9  367.29    4832  365.68  4932.3  367.59
  4943.4  365.99  5022.6  365.79  5076.4  367.26  5082.8   367.2    5113  367.17
  5170.7  363.23    5181  364.08 5202.29363.2126  5393.5  365.36  6092.5  366.73
  6444.6  372.06  6610.3  372.35  6618.8  373.36  6893.1  377.24  7075.8  381.83
#Mann= 5 ,-1 , 0
  2724.9      .1       0  4627.5     .07       0  4634.3      .1       0
  5076.4     .05       0  5082.8      .1       0
Bank Sta=3862.59,5202.29
XS Rating Curve= 0 ,0
Exp/Cntr=0.3,0.1

Type RM Length L Ch R = 1 ,1767    ,532,532,532
BEGIN DESCRIPTION:
UNT 177 SanMiguel Cr Watershed 3.0
END DESCRIPTION:
XS GIS Cut Line= 5
      2083101.37     13445093.71      2083259.91     13444015.53
      2083204.35     13443848.86      2083176.57     13443578.03
       2081358.6     13443057.62
#Sta/Elev= 30
  3632.9  363.97  3834.2  362.77  4227.9  363.63  4490.7  362.37  4521.6  363.82
  4571.6  361.56  4713.1  361.16  4733.8  359.06  4765.4  358.38  4783.4  360.21
    4797  358.17  4820.3  359.79  4846.7  357.01  4851.9  358.61  4860.3  358.97
 4917.52356.4177  4972.6  354.88  4989.3  353.36  4989.8  352.56  4996.1  353.36
  5027.5356.4166  5038.5  358.89  5123.4  362.42  5204.2  361.77  5417.2  364.77
  6129.2   366.5  6435.6  370.51  6701.3  372.53  6898.9   375.9  7061.6  380.49
#Mann= 3 ,-1 , 0
  3632.9      .1       0  4989.3     .07       0  4996.1      .1       0
Bank Sta=4917.52,5027.5
XS Rating Curve= 0 ,0
Exp/Cntr=0.3,0.1

Type RM Length L Ch R = 1 ,1235    ,912,912,912
BEGIN DESCRIPTION:
UNT 177 SanMiguel Cr Watershed 2.0
END DESCRIPTION:
XS GIS Cut Line= 4
      2083665.62     13444529.41       2083836.3     13443959.97
      2083190.46     13443223.86      2081364.12     13442904.43
#Sta/Elev= 30
  3880.5  359.35  4396.6  358.51  4500.6  357.72  4508.2  356.74  4521.5  357.49
  4535.7  355.83  4571.8  358.19  4762.5   359.1  4784.3  357.89    4791  358.73
  4812.8  357.76  4833.7  358.33  4847.9  356.88  4890.6  355.85    4940  356.57
 4971.22353.9596  4993.5  350.38    4994  349.58  5000.3  350.38  5011.1  351.17
  5025.4  354.18 5032.74353.9594  5067.1   357.8  5109.8  359.64  5393.6   359.7
  5708.7  363.33  6038.4  363.57  6748.8  370.58  7094.2  376.33  7308.3   382.8
#Mann= 3 ,-1 , 0
  3880.5      .1       0  4993.5     .07       0  5000.3      .1       0
Bank Sta=4971.22,5032.74
XS Rating Curve= 0 ,0
Exp/Cntr=0.3,0.1

Type RM Length L Ch R = 1 ,323     ,0,0,0
BEGIN DESCRIPTION:
UNT 177 SanMiguel Cr Watershed 1.0
END DESCRIPTION:
XS GIS Cut Line= 4
      2084252.27     13443785.33      2084187.17     13443553.14
        2083900.       13443150.      2081530.72     13442723.86
#Sta/Elev= 30
  4637.8  357.55  4864.9  356.58  4943.6  351.81  4950.3  353.05 4983.82349.3344
  5008.8  347.81  5050.5  350.87  5065.3  353.77  5130.5  354.52  5201.8  349.45
    5213  346.34  5213.5  345.54    5220  346.34  5237.4  346.99  5287.8  353.84
    5379  351.16  5470.4  353.12  5480.6   352.8  5500.9  348.43 5513.22349.3345
  5539.9  353.25  5612.7  353.45    5711  356.64  5856.5  355.76  5978.4  359.37
    6202  361.96  6547.4  361.47  7157.1  368.01  7451.7  373.03  7781.2  381.94
#Mann= 3 ,-1 , 0
  4637.8      .1       0    5213     .07       0    5220      .1       0
Bank Sta=4983.82,5513.22
XS Rating Curve= 0 ,0
Exp/Cntr=0.3,0.1
LCMann Table=0

Chan Stop Cuts=-1
Use User Specified Reach Order=0
Composite Channel Slope=5