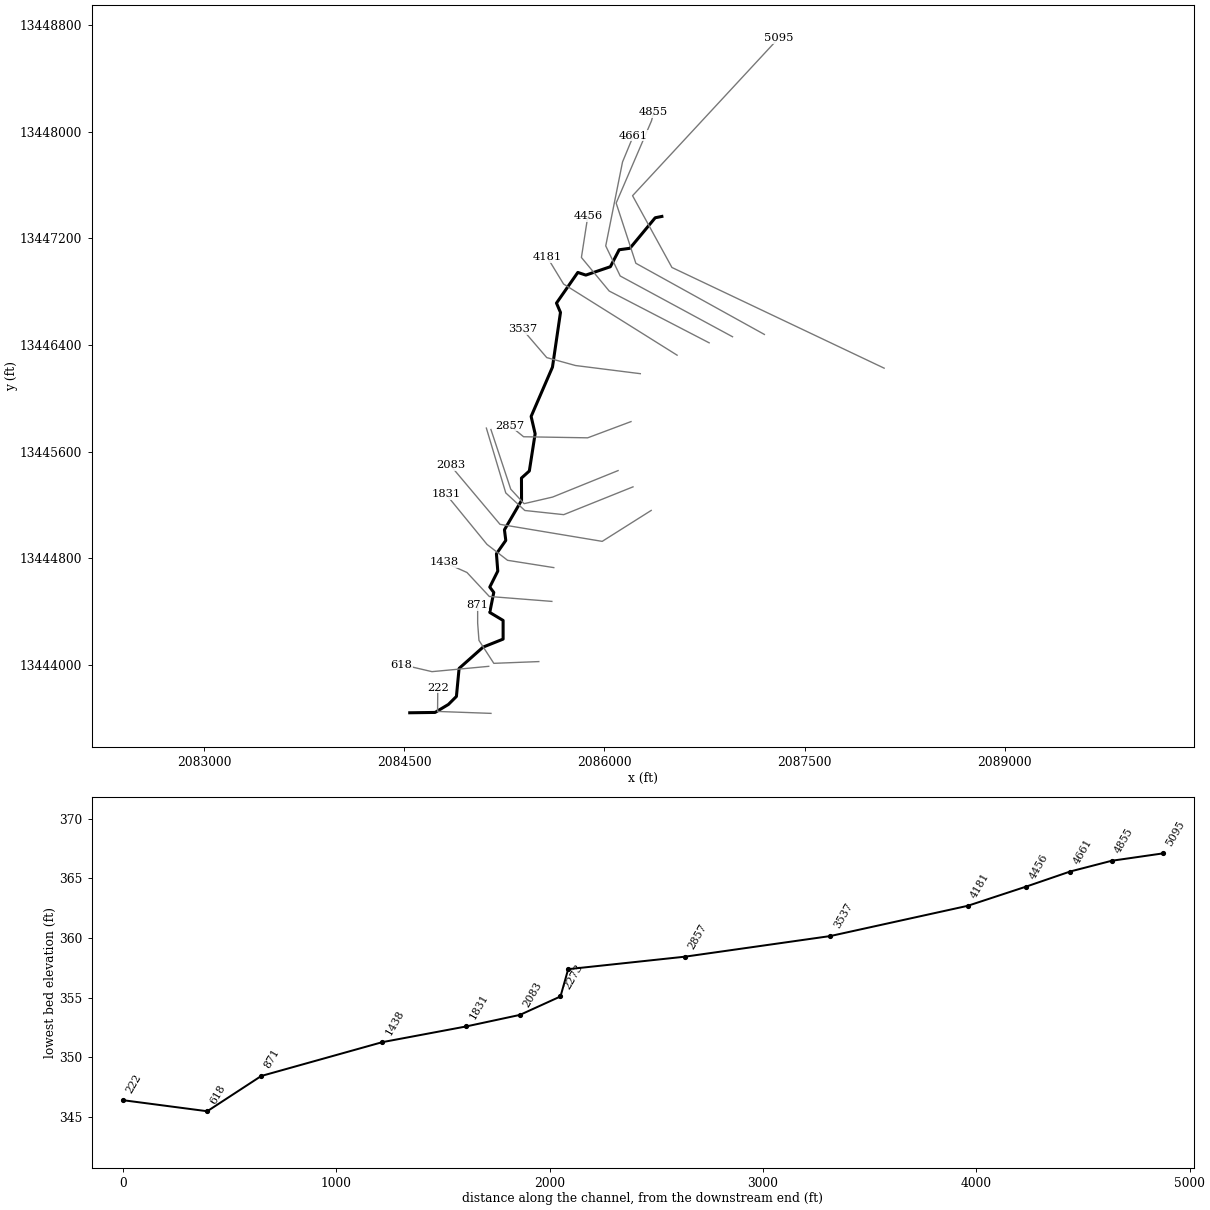
--- UNT 178 SanMiguel Cr Watershed.prj (project) ---

Proj Title=UNT 178 SanMiguel Cr Watershed Base Level Engineering
Current Plan=p01
Default Exp/Contr=0.3,0.1
English Units
Geom File=g01
Flow File=f01
Plan File=p01
Y Axis Title=Elevation
X Axis Title(PF)=Main Channel Distance
X Axis Title(XS)=Station
BEGIN DESCRIPTION:
UNT 178 SanMiguel Cr Watershed
END DESCRIPTION:
DSS Export Rating Curves= 0
DSS Export Rating Curve Sorted= 0
DSS Export Volume Flow Curves= 0
DXF OffsetX= 0
DXF OffsetY= 0
DXF ScaleX= 1
DXF ScaleY= 10

--- UNT 178 SanMiguel Cr Watershed.p01 (plan) ---

Plan Title=Multiple Run
Short Identifier=Multiple
Geom File=g01
Flow File=f01
Subcritical Flow
K Sum by GR= 0
Std Step Tol= 0.01
Critical Tol= 0.01
Num of Std Step Trials= 20
Max Error Tol= 0.3
Flow Tol Ratio= 0.001
Split Flow NTrial= 30
Split Flow Tol= 0.02
Split Flow Ratio= 0.02
Log Output Level= 0
Friction Slope Method= 1
Unsteady Friction Slope Method= 2
Unsteady Bridges Friction Slope Method= 1
Parabolic Critical Depth
Global Vel Dist=  1 , 1 , 1
Global Log Level= 0
CheckData=True
Encroach Param= -1, 0, 0, 0
BEGIN DESCRIPTION:
Multiple Run
END DESCRIPTION:

--- UNT 178 SanMiguel Cr Watershed.f01 (steady flow) ---

Flow Title=Multiple
Program Version=5.05
Number of Profiles= 7
Profile Names=10-year,25-year,50-year,1pct_min,100-year,1pct_plu,500-year
River Rch & RM=UNT 178 SanMigue,Reach-1         ,5095
     130     174     209     126     251     501     366
River Rch & RM=UNT 178 SanMigue,Reach-1         ,871
     204     280     342     209     417     832     628
Boundary for River Rch & Prof#=UNT 178 SanMigue,Reach-1         , 1
Up Type= 0
Dn Type= 3
Dn Slope=0.005
Boundary for River Rch & Prof#=UNT 178 SanMigue,Reach-1         , 2
Up Type= 0
Dn Type= 3
Dn Slope=0.005
Boundary for River Rch & Prof#=UNT 178 SanMigue,Reach-1         , 3
Up Type= 0
Dn Type= 3
Dn Slope=0.005
Boundary for River Rch & Prof#=UNT 178 SanMigue,Reach-1         , 4
Up Type= 0
Dn Type= 3
Dn Slope=0.005
Boundary for River Rch & Prof#=UNT 178 SanMigue,Reach-1         , 5
Up Type= 0
Dn Type= 3
Dn Slope=0.005
Boundary for River Rch & Prof#=UNT 178 SanMigue,Reach-1         , 6
Up Type= 0
Dn Type= 3
Dn Slope=0.005
Boundary for River Rch & Prof#=UNT 178 SanMigue,Reach-1         , 7
Up Type= 0
Dn Type= 3
Dn Slope=0.005
DSS Import GetInterval= 0
DSS Import GetPeak= 0
DSS Import FillOption= 0

--- UNT 178 SanMiguel Cr Watershed.g01 (geometry) ---

Geom Title=Existing Conditions
Program Version=5.05

River Reach=UNT 178 SanMigue,Reach-1
Reach XY= 30
       2086430.8     13447364.54       2086380.8     13447354.54
      2086191.54     13447125.66       2086110.8     13447114.54
       2086044.8     13446987.38       2085860.8     13446924.54
       2085800.8     13446944.54       2085640.8     13446714.54
       2085670.8     13446644.54       2085610.8     13446234.54
       2085450.8     13445864.54       2085480.8     13445734.54
      2085437.37     13445455.52      2085378.35     13445402.14
        2085379.      13445234.6       2085250.8     13445014.54
       2085260.8     13444934.54       2085190.8     13444834.54
       2085200.8     13444704.54       2085140.8     13444584.54
       2085170.8     13444544.54       2085140.8     13444394.54
       2085240.8     13444334.54       2085240.8     13444194.54
       2085090.8     13444134.54       2084910.8     13443974.54
       2084890.8     13443764.54       2084830.8     13443704.54
       2084730.8     13443644.54      2084540.89     13443642.01

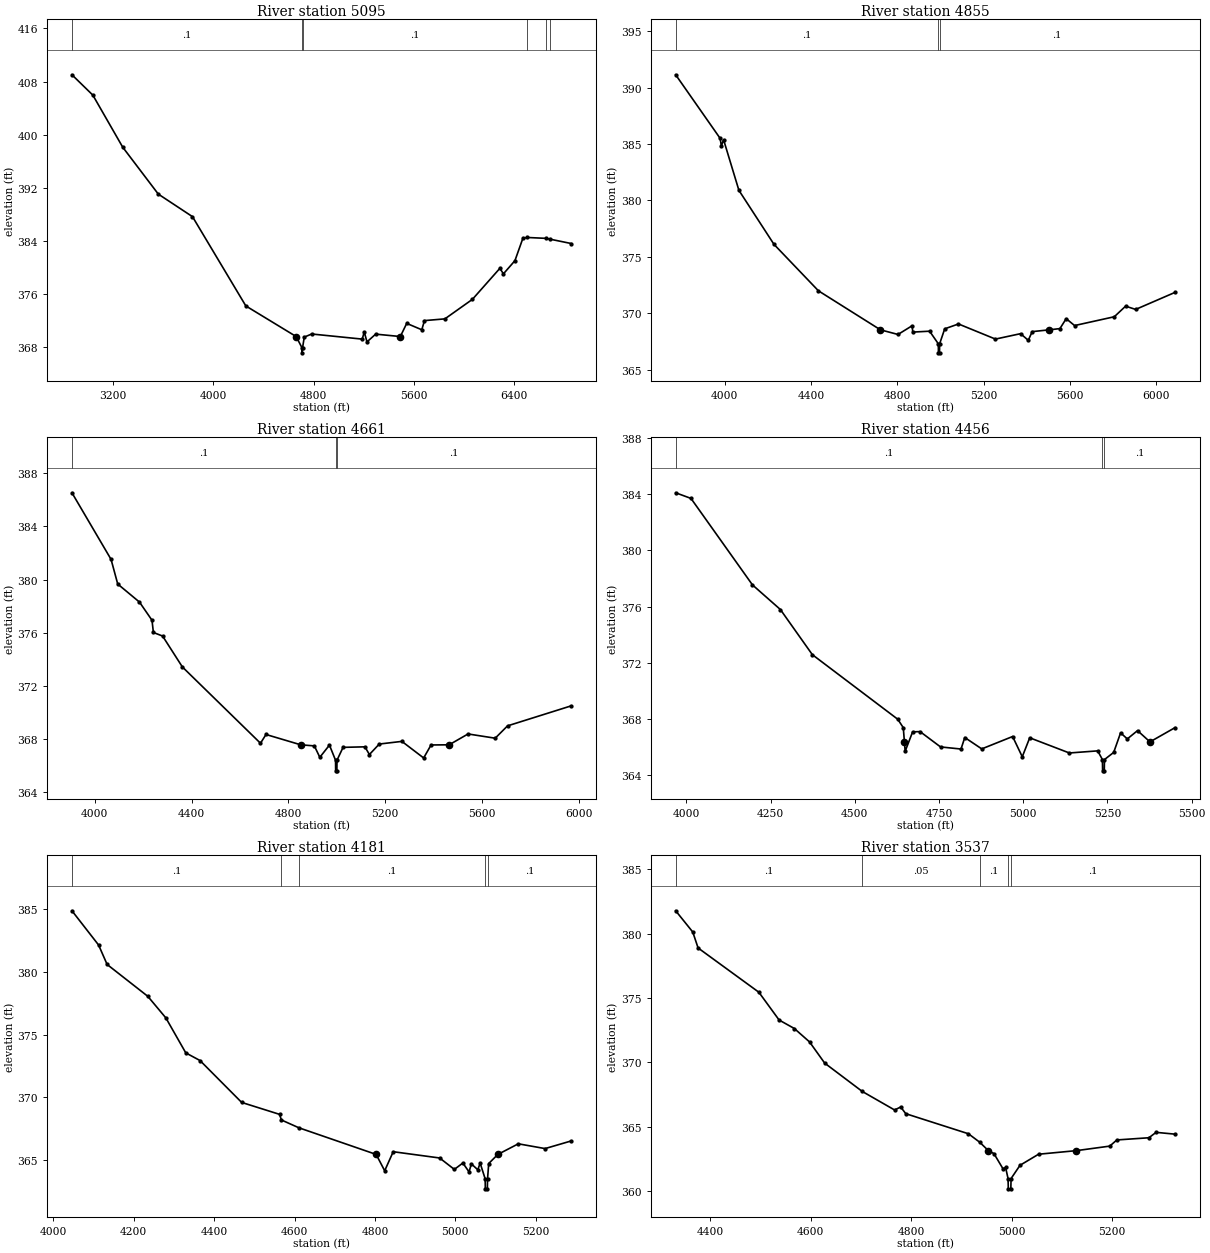
Type RM Length L Ch R = 1 ,5095    ,240,240,240
BEGIN DESCRIPTION:
UNT 178 SanMiguel Cr Watershed 13.0
END DESCRIPTION:
XS GIS Cut Line= 4
       2088096.8     13446226.58      2086506.26     13446981.75
      2086211.12     13447519.95      2087304.62     13448700.24
#Sta/Elev= 30
  2872.3  409.02  3039.1  405.95  3277.5   398.1  3561.3  391.03    3834  387.63
  4259.7  374.17 4660.99369.5587  4706.6   367.9  4707.1   367.1  4712.6   367.9
  4725.7  369.47    4785  369.94  5188.3  369.17  5204.4  370.25  5226.2  368.75
  5295.4  369.92 5492.21369.5588  5543.1  371.54  5663.3  370.58  5684.9  371.96
  5847.6  372.22    6067  375.16  6286.4  379.84  6314.7  379.01  6406.6     381
  6470.1  384.38  6506.3  384.49  6654.2  384.36    6683  384.25  6855.8  383.58
#Mann= 6 ,-1 , 0
  2872.3      .1       0  4706.6     .07       0  4712.6      .1       0
  6506.3     .08       0  6654.2     .05       0    6683     .08       0
Bank Sta=4660.99,5492.21
XS Rating Curve= 0 ,0
Exp/Cntr=0.3,0.1

Type RM Length L Ch R = 1 ,4855    ,194,194,194
BEGIN DESCRIPTION:
UNT 178 SanMiguel Cr Watershed 12.0
END DESCRIPTION:
XS GIS Cut Line= 5
       2087199.2     13446479.51       2086235.7     13447013.34
      2086088.13     13447464.73      2086352.89     13448081.05
      2086370.13     13448145.71
#Sta/Elev= 30
  3773.3  391.14  3979.4   385.5  3985.1  384.82  3995.3  385.38  4066.4  380.89
    4229   376.1    4435  371.98 4722.33368.5202  4803.7  368.11  4868.9  368.88
  4872.3  368.32  4950.2   368.4  4990.6  367.28  4991.1  366.48  4996.1  366.48
  4996.6  367.28  5020.2  368.61    5084  369.04  5255.3   367.7  5371.8  368.18
  5407.5  367.59  5425.6  368.36 5504.41368.5203  5554.2  368.63  5583.2  369.51
  5622.1   368.9  5806.1  369.68  5858.6  370.62  5905.1  370.33  6087.4  371.84
#Mann= 3 ,-1 , 0
  3773.3      .1       0  4990.6     .07       0  4996.6      .1       0
Bank Sta=4722.33,5504.41
XS Rating Curve= 0 ,0
Exp/Cntr=0.3,0.1

Type RM Length L Ch R = 1 ,4661    ,205,205,205
BEGIN DESCRIPTION:
UNT 178 SanMiguel Cr Watershed 11.0
END DESCRIPTION:
XS GIS Cut Line= 5
      2086960.56     13446462.11      2086118.51     13446917.85
      2086010.01     13447143.55      2086135.87     13447772.89
       2086217.8     13447971.24
#Sta/Elev= 30
  3905.2  386.54  4066.9  381.52  4094.5  379.66  4184.4   378.3  4236.2  376.93
  4241.9  376.01    4280  375.74  4361.8  373.41  4684.7  367.66  4707.5  368.32
 4851.19367.5422  4907.4  367.46    4930   366.6  4969.8  367.52    4995  366.38
  4995.5  365.58  5000.5  365.58    5001  366.38  5026.1  367.35  5116.4  367.39
    5135  366.81  5175.8   367.6  5269.3   367.8  5359.3  366.55  5389.9  367.53
 5464.63367.5427  5542.9  368.36  5655.1  368.04  5706.1  368.97  5969.5  370.48
#Mann= 3 ,-1 , 0
  3905.2      .1       0    4995     .07       0    5001      .1       0
Bank Sta=4851.19,5464.63
XS Rating Curve= 0 ,0
Exp/Cntr=0.3,0.1

Type RM Length L Ch R = 1 ,4456    ,275,275,275
BEGIN DESCRIPTION:
UNT 178 SanMiguel Cr Watershed 10.0
END DESCRIPTION:
XS GIS Cut Line= 4
      2086785.26     13446416.53      2086036.05     13446805.01
      2085827.71     13447056.74      2085875.45     13447364.86
#Sta/Elev= 30
    3968  384.09  4013.4  383.69    4196  377.54  4278.9  375.79  4373.8  372.58
  4627.3  367.99  4643.8  367.39 4647.17 366.379  4649.4  365.71  4671.5  367.09
  4693.6  367.11  4754.4  366.02  4815.2  365.87  4826.4  366.69  4876.8  365.88
  4968.4  366.76  4997.1  365.32  5019.2  366.67  5136.9  365.59    5221  365.74
  5235.1  365.12  5235.6  364.32  5240.6  364.32  5241.1  365.12  5268.5  365.63
    5289  367.02    5309  366.59  5339.3  367.18 5376.26366.3784  5450.5  367.39
#Mann= 3 ,-1 , 0
    3968      .1       0  5235.1     .07       0  5241.1      .1       0
Bank Sta=4647.17,5376.26
XS Rating Curve= 0 ,0
Exp/Cntr=0.3,0.1

Type RM Length L Ch R = 1 ,4181    ,644,644,644
BEGIN DESCRIPTION:
UNT 178 SanMiguel Cr Watershed 9.0
END DESCRIPTION:
XS GIS Cut Line= 3
      2086544.89     13446323.96      2085693.78     13446857.73
      2085570.47     13447060.67
#Sta/Elev= 30
  4046.3  384.87  4112.6  382.14  4133.8  380.59    4235  378.05  4279.9  376.33
  4329.5  373.54  4364.9  372.93  4468.5  369.59  4562.7  368.64  4567.4  368.19
  4610.7  367.57  4803.1365.4439  4824.3  364.14  4845.5  365.66    4961  365.16
  4997.6  364.25  5018.8  364.76  5034.1  364.05    5040  364.69  5055.9  364.22
  5061.8  364.75  5074.2   363.5  5074.7   362.7  5079.7   362.7  5080.2   363.5
  5083.1  364.72 5105.84365.4443  5156.7  366.29  5223.3  365.91  5288.4  366.52
#Mann= 5 ,-1 , 0
  4046.3      .1       0  4567.4     .05       0  4610.7      .1       0
  5074.2     .07       0  5080.2      .1       0
Bank Sta=4803.1,5105.84
XS Rating Curve= 0 ,0
Exp/Cntr=0.3,0.1

Type RM Length L Ch R = 1 ,3537    ,680,680,680
BEGIN DESCRIPTION:
UNT 178 SanMiguel Cr Watershed 8.0
END DESCRIPTION:
XS GIS Cut Line= 4
      2086269.21     13446185.18       2085783.5     13446246.39
      2085567.85     13446305.84      2085385.34     13446518.39
#Sta/Elev= 30
  4331.3  381.77  4365.3  380.12  4375.9  378.88  4496.8  375.44  4537.1  373.28
  4567.4  372.62  4597.6  371.58  4627.8  369.93  4702.5  367.73  4766.8  366.29
    4779  366.52  4789.1     366  4913.8  364.44  4936.3  363.78 4953.43363.1291
  4964.5   362.9  4982.5  361.72  4987.7  361.82  4992.6  360.96  4993.1  360.16
  4998.1  360.16  4998.6  360.96  5016.4  361.99  5053.3  362.85 5128.64363.1291
  5194.9  363.48  5209.1  363.96  5272.8  364.13  5287.1  364.55  5324.7  364.41
#Mann= 5 ,-1 , 0
  4331.3      .1       0  4702.5     .05       0  4936.3      .1       0
  4992.6     .07       0  4998.6      .1       0
Bank Sta=4953.43,5128.64
XS Rating Curve= 0 ,0
Exp/Cntr=0.3,0.1

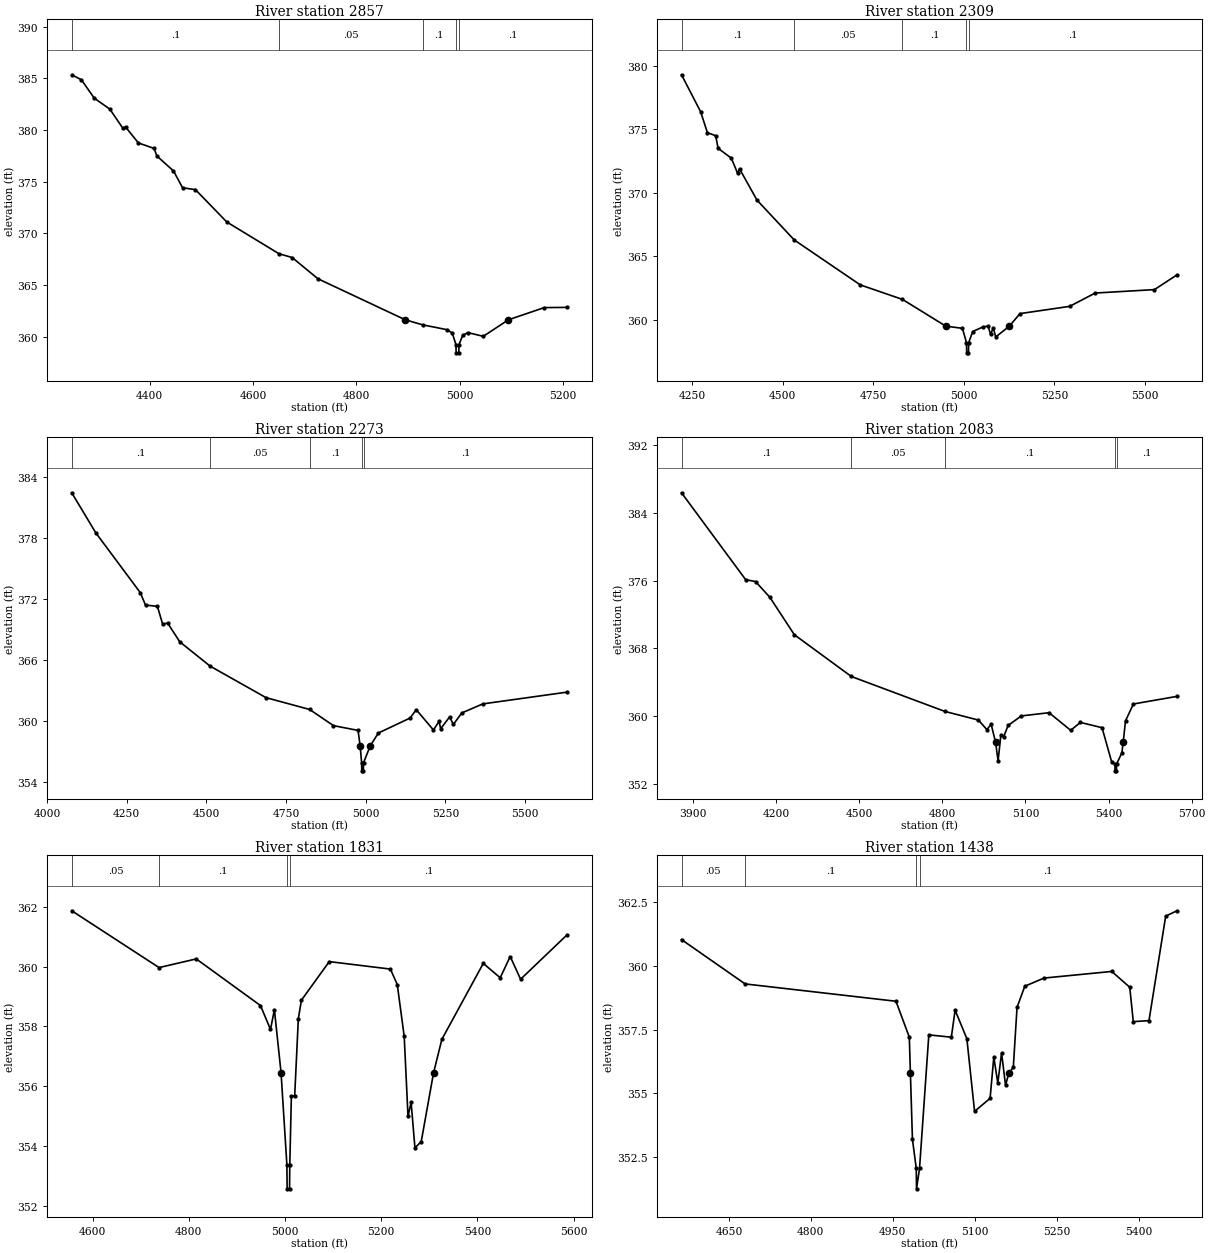
Type RM Length L Ch R = 1 ,2857    ,548,548,548
BEGIN DESCRIPTION:
UNT 178 SanMiguel Cr Watershed 7.0
END DESCRIPTION:
XS GIS Cut Line= 4
      2086199.41     13445825.79      2085874.59     13445704.13
      2085394.28     13445712.14      2085292.22     13445795.33
#Sta/Elev= 30
  4249.3  385.35  4267.9  384.87  4292.8  383.09  4323.1  382.02  4348.1  380.18
  4353.4   380.3  4378.3  378.75  4408.6  378.22  4414.2  377.48  4446.2  376.04
  4463.8  374.41  4488.7  374.23  4549.3   371.1  4650.5  368.02  4675.8  367.66
  4725.8   365.6 4894.67361.6317  4928.5  361.14  4975.8  360.67  4985.8  360.34
  4992.8  359.23  4993.3  358.43  4998.3  358.43  4998.8  359.23  5005.8  360.11
  5015.8  360.39  5045.8  360.03 5094.49361.6315  5163.8  362.81  5208.2  362.83
#Mann= 5 ,-1 , 0
  4249.3      .1       0  4650.5     .05       0  4928.5      .1       0
  4992.8     .07       0  4998.8      .1       0
Bank Sta=4894.67,5094.49
XS Rating Curve= 0 ,0
Exp/Cntr=0.3,0.1

Type RM Length L Ch R = 1 ,2309    ,36,36,36
BEGIN DESCRIPTION:
UNT 178 SanMiguel Cr Watershed 6.0
END DESCRIPTION:
XS GIS Cut Line= 5
      2086102.52     13445458.37      2085611.91     13445259.83
      2085398.06     13445210.28      2085297.99      13445319.2
      2085149.56     13445766.22
#Sta/Elev= 30
  4220.6  379.28  4273.4  376.37  4292.1  374.72    4315  374.48  4321.6  373.49
  4358.2  372.71  4375.3  371.53  4380.7  371.88  4428.9  369.41  4531.8  366.27
  4714.2  362.73  4830.5  361.59 4949.98359.4849  4996.1  359.31  5007.3  358.18
  5007.8  357.38  5012.8  357.38  5013.3  358.18  5024.5  359.06  5052.8  359.42
    5067  359.49  5073.8  358.83  5081.2  359.35    5088  358.63 5125.74359.4848
    5155  360.47    5292  361.04  5362.6  362.09  5526.2  362.36  5588.3  363.52
#Mann= 5 ,-1 , 0
  4220.6      .1       0  4531.8     .05       0  4830.5      .1       0
  5007.3     .07       0  5013.3      .1       0
Bank Sta=4949.98,5125.74
XS Rating Curve= 0 ,0
Exp/Cntr=0.3,0.1

Type RM Length L Ch R = 1 ,2273    ,190,190,190
BEGIN DESCRIPTION:
UNT 178 SanMiguel Cr Watershed 5.0
END DESCRIPTION:
XS GIS Cut Line= 5
      2086214.36     13445336.35      2085695.24     13445127.89
      2085403.57     13445159.14      2085260.66     13445290.99
      2085115.26     13445777.12
#Sta/Elev= 30
  4077.7  382.46  4153.1  378.52  4292.5  372.64  4309.1  371.41  4346.4  371.28
  4362.8  369.54  4378.7  369.63  4416.6  367.79  4512.2  365.39  4687.6  362.29
  4824.2  361.13  4898.8  359.54    4976  359.07 4982.57357.5561  4987.2  355.89
  4987.7  355.09  4992.7  355.09  4993.2  355.89 5014.41357.5555  5039.6  358.81
  5139.5  360.29  5158.6  361.11  5212.6  359.11  5230.1  359.96  5235.3  359.23
  5263.2   360.4  5275.2  359.66  5301.5  360.79  5367.7  361.68  5632.3  362.84
#Mann= 5 ,-1 , 0
  4077.7      .1       0  4512.2     .05       0  4824.2      .1       0
  4987.2     .07       0  4993.2      .1       0
Bank Sta=4982.57,5014.41
XS Rating Curve= 0 ,0
Exp/Cntr=0.3,0.1

Type RM Length L Ch R = 1 ,2083    ,252,252,252
BEGIN DESCRIPTION:
UNT 178 SanMiguel Cr Watershed 4.0
END DESCRIPTION:
XS GIS Cut Line= 4
      2086350.84     13445159.56      2085983.55     13444927.58
      2085217.65     13445055.24      2084846.16     13445497.16
#Sta/Elev= 30
  3858.8   386.4  4090.4  376.13    4126  375.91  4177.7  374.05  4265.9  369.63
  4471.8  364.69  4809.5  360.56  4930.4  359.54  4960.8  358.42  4976.5  359.03
 4992.48 356.899  5001.4   354.7  5011.5   357.8  5021.7  357.56  5037.4   358.9
  5085.3  360.03  5185.4  360.41  5263.4  358.33  5298.6  359.26  5376.6  358.64
  5411.7  354.55    5423  354.34  5423.5  353.54  5428.5  353.54    5429  354.34
  5448.1  355.66 5452.94356.8993  5461.3  359.45  5489.8  361.44    5647  362.34
#Mann= 5 ,-1 , 0
  3858.8      .1       0  4471.8     .05       0  4809.5      .1       0
    5423     .07       0    5429      .1       0
Bank Sta=4992.48,5452.94
XS Rating Curve= 0 ,0
Exp/Cntr=0.3,0.1

Type RM Length L Ch R = 1 ,1831    ,393,393,393
BEGIN DESCRIPTION:
UNT 178 SanMiguel Cr Watershed 3.0
END DESCRIPTION:
XS GIS Cut Line= 4
      2085620.61     13444730.71      2085274.12     13444785.51
      2085120.04     13444904.87      2084813.66     13445280.08
#Sta/Elev= 30
  4556.5  361.87    4738  359.97  4815.3  360.26  4948.9   358.7  4969.7   357.9
  4977.8  358.56 4991.65356.4572  5003.8  353.37  5004.3  352.57  5009.3  352.57
  5009.8  353.37  5013.1  355.66    5020  355.68  5027.6  358.26    5034  358.88
  5091.9  360.17    5219  359.92  5233.3   359.4  5247.7  357.67  5255.6     355
  5262.1  355.46    5270  353.94  5283.1  354.15  5308.8356.4574    5326  357.57
  5412.1  360.11  5447.3  359.63  5468.1  360.34  5489.7  359.58  5586.6  361.07
#Mann= 4 ,-1 , 0
  4556.5     .05       0    4738      .1       0  5003.8     .07       0
  5009.8      .1       0
Bank Sta=4991.65,5308.8
XS Rating Curve= 0 ,0
Exp/Cntr=0.3,0.1

Type RM Length L Ch R = 1 ,1438    ,567,567,567
BEGIN DESCRIPTION:
UNT 178 SanMiguel Cr Watershed 2.0
END DESCRIPTION:
XS GIS Cut Line= 4
      2085606.15     13444477.35       2085137.4     13444514.25
      2084969.86      13444694.2      2084796.21     13444772.35
#Sta/Elev= 30
  4563.3  361.03  4679.7  359.29  4955.7  358.61  4980.1   357.2 4982.13355.7755
  4985.8   353.2  4992.8  352.05  4993.3  351.25  4998.8  352.05  5015.8  357.29
    5057   357.2  5063.9  358.26  5085.4  357.14  5099.5  354.29  5127.9   354.8
  5134.7  356.42    5142   355.4  5148.9  356.58  5156.2  355.31 5161.99355.7783
  5170.4  356.02  5177.2  358.37  5191.4   359.2  5226.6  359.52  5350.5  359.78
  5383.4  359.16  5389.9  357.81  5418.6  357.85  5449.2  361.95  5469.8  362.16
#Mann= 4 ,-1 , 0
  4563.3     .05       0  4679.7      .1       0  4992.8     .07       0
  4998.8      .1       0
Bank Sta=4982.13,5161.99
XS Rating Curve= 0 ,0
Exp/Cntr=0.3,0.1

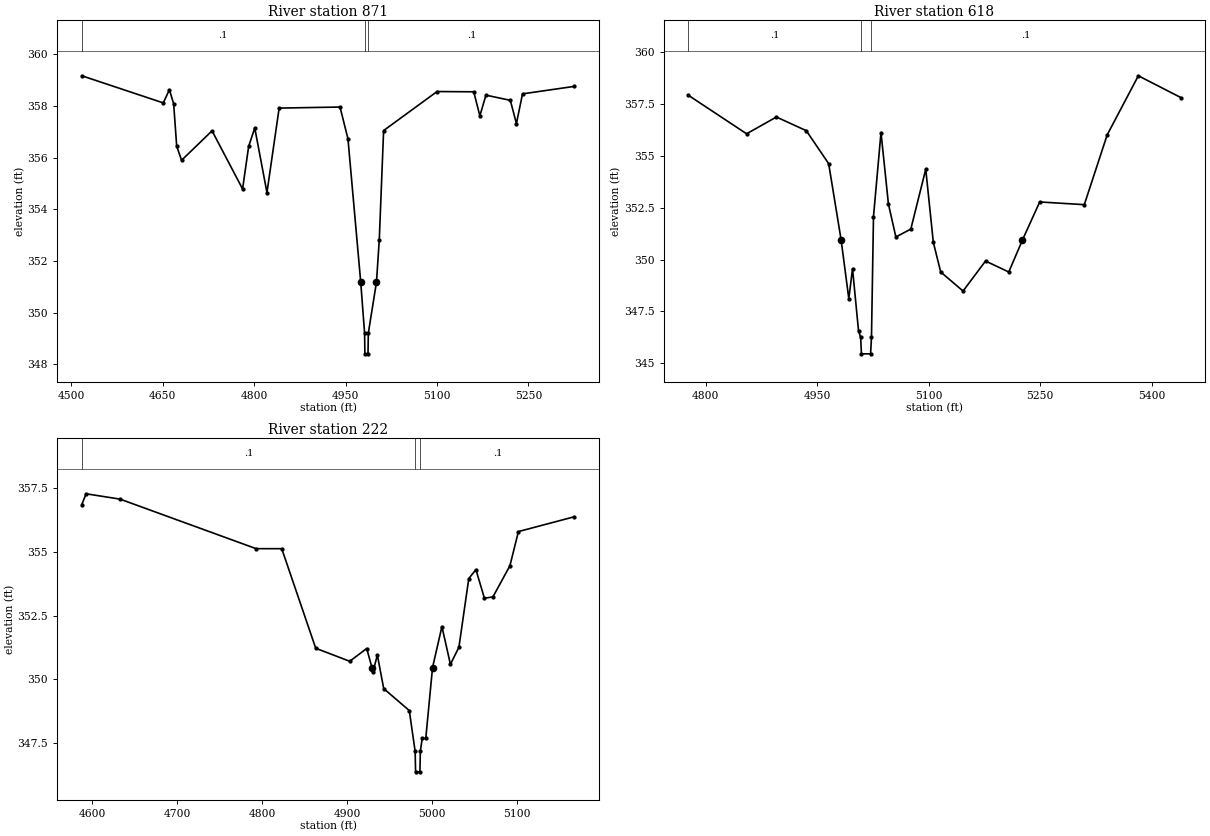
Type RM Length L Ch R = 1 ,871     ,253,253,253
BEGIN DESCRIPTION:
UNT 178 SanMiguel Cr Watershed 1.0
END DESCRIPTION:
XS GIS Cut Line= 5
      2085508.46     13444025.96      2085171.15     13444012.77
      2085059.81     13444184.84        2085050.     13444314.59
        2085050.     13444449.96
#Sta/Elev= 30
  4517.4  359.17    4651  358.12    4661  358.63    4668  358.09    4673  356.45
    4681   355.9    4731  357.04  4781.1  354.79  4791.1  356.44  4801.1  357.15
  4821.1  354.65  4841.1  357.92    4941  357.96    4954  356.73 4974.93351.1877
  4981.3  349.21  4981.8  348.41  4986.9  348.41  4987.4  349.21 5000.81351.1885
  5005.4  352.83  5012.5  357.05  5100.2  358.56  5160.4  358.55  5170.4  357.62
  5180.4  358.42  5220.4  358.22  5230.4  357.32  5240.4  358.47  5325.4  358.76
#Mann= 3 ,-1 , 0
  4517.4      .1       0  4981.3     .07       0  4987.4      .1       0
Bank Sta=4974.93,5000.81
XS Rating Curve= 0 ,0
Exp/Cntr=0.3,0.1

Type RM Length L Ch R = 1 ,618     ,396,396,396
BEGIN DESCRIPTION:
Mapping XS 111f2ca5
END DESCRIPTION:
XS GIS Cut Line= 3
      2085133.02     13443990.35      2084707.71     13443950.43
      2084478.57     13444003.98
#Sta/Elev= 30
  4776.8  357.93  4855.2  356.07  4895.3  356.88  4935.5  356.22  4965.6  354.63
 4982.38350.9445  4992.7  348.11  4997.7  349.56  5005.8  346.55  5008.6  346.25
  5009.7  345.45    5022  345.45  5023.2  346.25  5025.9  352.07    5036  356.13
    5046  352.68    5056  351.09  5076.1  351.47  5096.2  354.36  5106.4  350.83
  5116.3   349.4  5146.4  348.48  5176.6  349.93  5207.9   349.4 5226.28350.9438
  5249.5  352.78  5309.5  352.65  5340.3  356.02  5382.2  358.87  5439.3  357.82
#Mann= 3 ,-1 , 0
  4776.8      .1       0  5008.6     .07       0  5023.2      .1       0
Bank Sta=4982.38,5226.28
XS Rating Curve= 0 ,0
Exp/Cntr=0.3,0.1

Type RM Length L Ch R = 1 ,222     ,0,0,0
BEGIN DESCRIPTION:
double MACHO CREEK 200.0
END DESCRIPTION:
XS GIS Cut Line= 3
      2085150.01     13443637.51      2084749.55     13443652.01
      2084751.11     13443830.79
#Sta/Elev= 30
  4587.9  356.85  4592.9  357.27  4632.9  357.06    4793  355.12  4823.1  355.12
  4863.1  351.22  4903.1  350.71  4923.1  351.21 4929.25350.4638  4930.6   350.3
  4935.6  350.96  4943.1  349.64  4973.2  348.78  4980.1  347.18  4980.6  346.38
  4985.7  346.38  4986.2  347.18  4988.4  347.69  4992.6  347.69 5000.55350.4636
  5011.6  352.07  5021.6  350.59  5031.6  351.26  5043.2  353.95  5051.6   354.3
  5061.6  353.18  5071.6  353.23  5091.6  354.45  5101.6  355.79  5167.4  356.37
#Mann= 3 ,-1 , 0
  4587.9      .1       0  4980.1     .07       0  4986.2      .1       0
Bank Sta=4929.25,5000.55
XS Rating Curve= 0 ,0
Exp/Cntr=0.3,0.1
LCMann Table=0

Chan Stop Cuts=-1
Use User Specified Reach Order=0
Composite Channel Slope=5