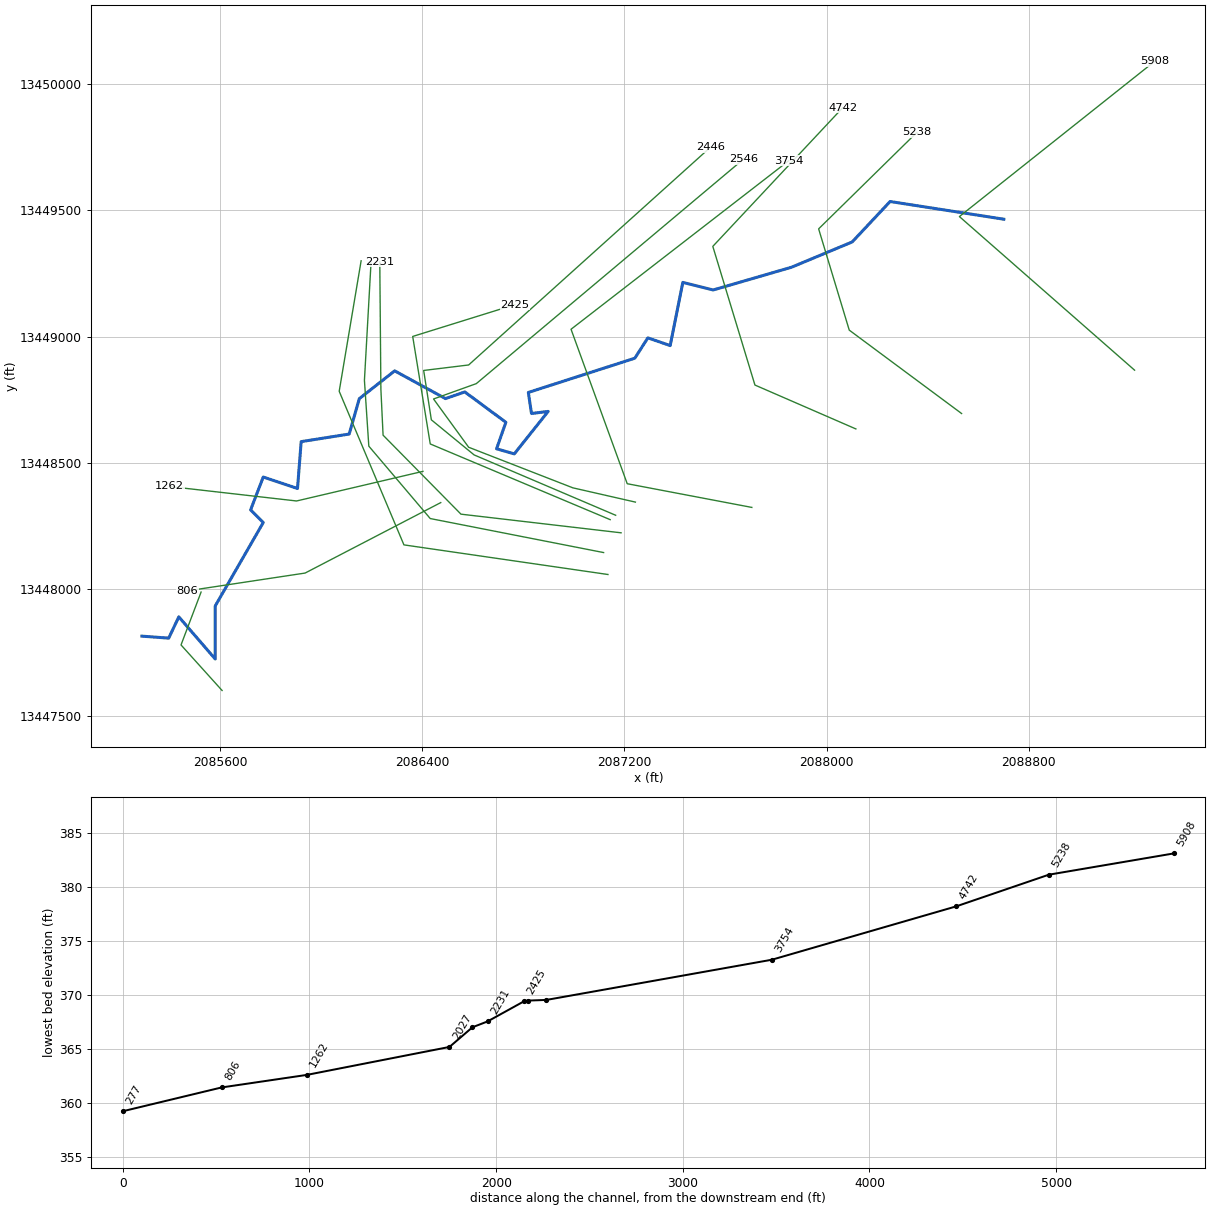
--- UNT 179 SanMiguel Cr Watershed.prj (project) ---

Proj Title=UNT 179 SanMiguel Cr Watershed Base Level Engineering
Current Plan=p01
Default Exp/Contr=0.3,0.1
English Units
Geom File=g01
Flow File=f01
Plan File=p01
Y Axis Title=Elevation
X Axis Title(PF)=Main Channel Distance
X Axis Title(XS)=Station
BEGIN DESCRIPTION:
UNT 179 SanMiguel Cr Watershed
END DESCRIPTION:
DSS Export Rating Curves= 0
DSS Export Rating Curve Sorted= 0
DSS Export Volume Flow Curves= 0
DXF OffsetX= 0
DXF OffsetY= 0
DXF ScaleX= 1
DXF ScaleY= 10

--- UNT 179 SanMiguel Cr Watershed.p01 (plan) ---

Plan Title=Multiple Run
Short Identifier=Multiple
Geom File=g01
Flow File=f01
Subcritical Flow
K Sum by GR= 0
Std Step Tol= 0.01
Critical Tol= 0.01
Num of Std Step Trials= 20
Max Error Tol= 0.3
Flow Tol Ratio= 0.001
Split Flow NTrial= 30
Split Flow Tol= 0.02
Split Flow Ratio= 0.02
Log Output Level= 0
Friction Slope Method= 1
Unsteady Friction Slope Method= 2
Unsteady Bridges Friction Slope Method= 1
Parabolic Critical Depth
Global Vel Dist=  1 , 1 , 1
Global Log Level= 0
CheckData=True
Encroach Param= -1, 0, 0, 0
BEGIN DESCRIPTION:
Multiple Run
END DESCRIPTION:

--- UNT 179 SanMiguel Cr Watershed.f01 (steady flow) ---

Flow Title=Multiple
Number of Profiles=7
Profile Names=10-year,25-year,50-year,1pct_min,100-year,1pct_plu,500-year
River Rch & RM= UNT 179 SanMigue,Reach-1,5908
     178     243     297     181     360     719     540
River Rch & RM= UNT 179 SanMigue,Reach-1,5238
     188     257     314     191     382     761     572
Boundary for River Rch & Prof#=UNT 179 SanMigue,Reach-1,1
Up Type=0
Dn Type=3
Dn Slope=0.005
Boundary for River Rch & Prof#=UNT 179 SanMigue,Reach-1,2
Up Type=0
Dn Type=3
Dn Slope=0.005
Boundary for River Rch & Prof#=UNT 179 SanMigue,Reach-1,3
Up Type=0
Dn Type=3
Dn Slope=0.005
Boundary for River Rch & Prof#=UNT 179 SanMigue,Reach-1,4
Up Type=0
Dn Type=3
Dn Slope=0.005
Boundary for River Rch & Prof#=UNT 179 SanMigue,Reach-1,5
Up Type=0
Dn Type=3
Dn Slope=0.005
Boundary for River Rch & Prof#=UNT 179 SanMigue,Reach-1,6
Up Type=0
Dn Type=3
Dn Slope=0.005
Boundary for River Rch & Prof#=UNT 179 SanMigue,Reach-1,7
Up Type=0
Dn Type=3
Dn Slope=0.005

--- UNT 179 SanMiguel Cr Watershed.g01 (geometry) ---

Geom Title=Existing Conditions
Program Version=5.05

River Reach=UNT 179 SanMigue,Reach-1
Reach XY= 30
       2088700.8     13449464.54       2088250.8     13449534.54
       2088100.8     13449374.54       2087860.8     13449274.54
       2087550.8     13449184.54       2087430.8     13449214.54
       2087380.8     13448964.54      2087292.46     13448995.11
       2087240.8     13448914.54      2086819.54     13448779.14
      2086832.04     13448695.81      2086898.02     13448704.14
      2086763.99     13448536.09      2086693.85     13448556.23
      2086730.65     13448661.09      2086568.15     13448781.23
      2086491.77     13448754.84       2086290.8     13448864.54
       2086150.8     13448754.54       2086110.8     13448614.54
       2085920.8     13448584.54      2085906.31     13448399.12
       2085770.8     13448444.54       2085720.8     13448314.54
       2085770.8     13448264.54       2085580.8     13447934.54
       2085580.8     13447724.54       2085436.7     13447891.31
      2085396.77      13447807.1       2085290.8     13447814.92

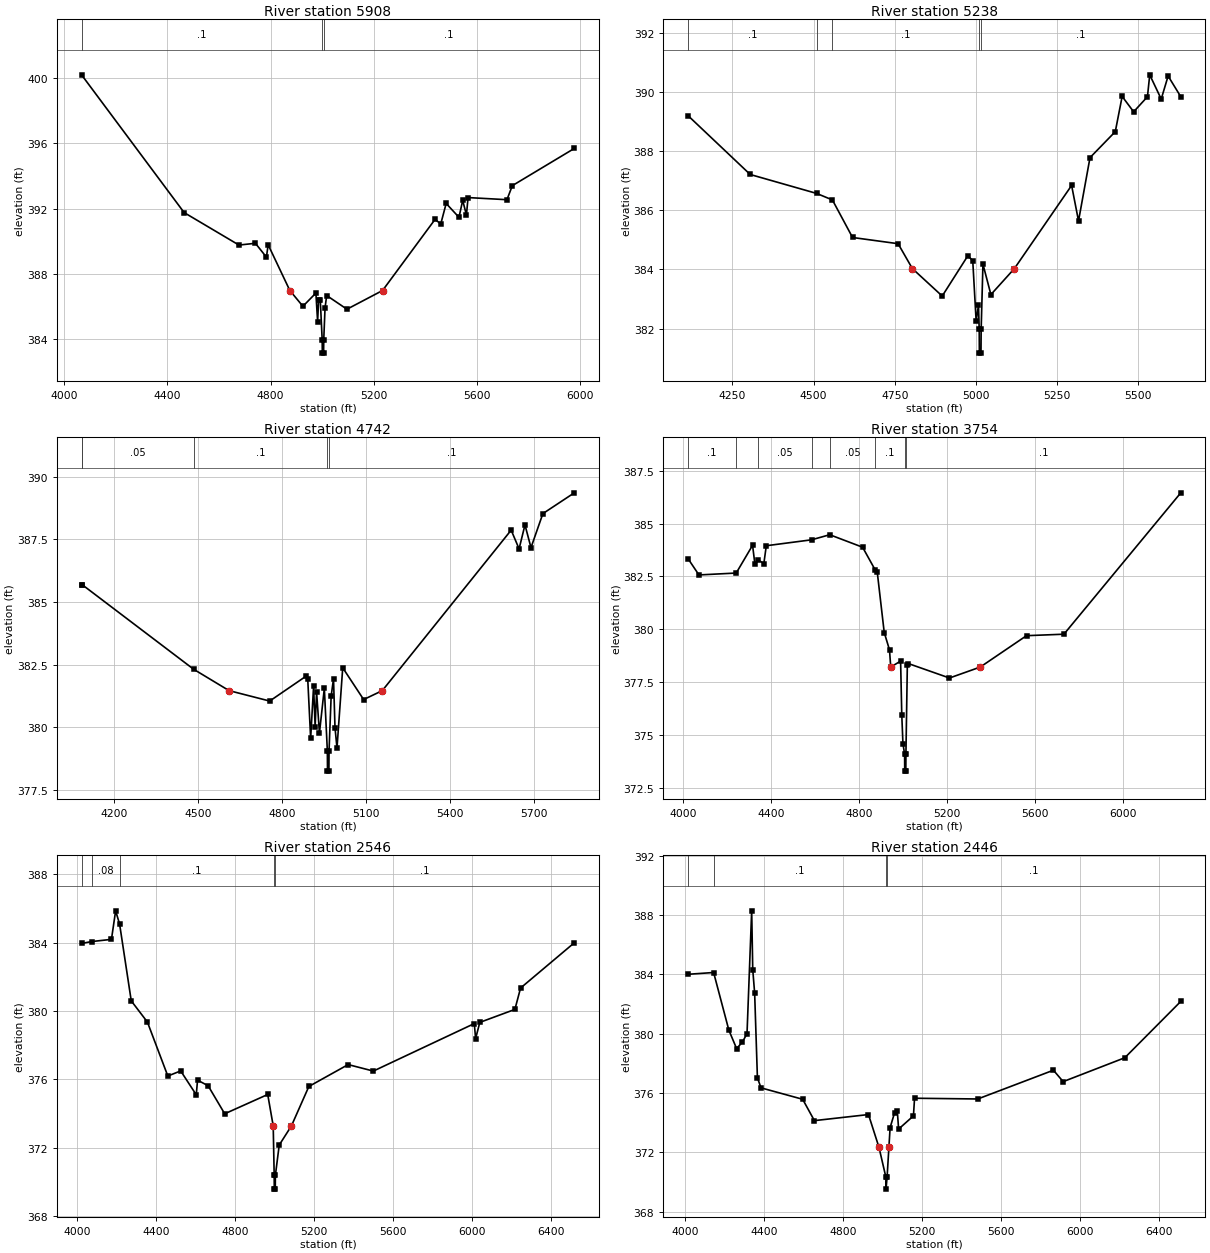
Type RM Length L Ch R = 1 ,5908    ,670,670,670
BEGIN DESCRIPTION:
UNT 179 SanMiguel Cr Watershed 12.0
END DESCRIPTION:
XS GIS Cut Line= 3
       2089218.1     13448867.29        2088525.       13449475.
      2089297.98     13450089.56
#Sta/Elev= 30
  4067.3  400.19  4464.8  391.75  4677.3  389.76  4740.9  389.87  4783.6  389.02
  4790.3  389.78 4874.37386.9768    4925  386.01  4975.3  386.82    4982  385.07
  4985.8   386.4  4992.3   386.4  4999.7  383.94  5000.2  383.14  5005.2  383.14
  5005.7  383.94  5010.7   385.9  5017.1  386.67  5095.6  385.83 5233.65386.9767
  5436.8  391.33  5459.2  391.06  5480.1  392.31  5529.7  391.46  5544.1   392.5
  5558.6   391.6  5564.9  392.67  5715.6  392.54  5736.4   393.4  5976.6  395.68
#Mann= 3 ,-1 , 0
  4067.3      .1       0  4999.7     .07       0  5005.7      .1       0
Bank Sta=4874.37,5233.65
XS Rating Curve= 0 ,0
Exp/Cntr=0.3,0.1

Type RM Length L Ch R = 1 ,5238    ,496,496,496
BEGIN DESCRIPTION:
UNT 179 SanMiguel Cr Watershed 11.0
END DESCRIPTION:
XS GIS Cut Line= 4
      2088533.67     13448695.81      2088089.22     13449025.68
      2087968.08     13449426.33      2088356.94     13449808.25
#Sta/Elev= 30
  4113.4   389.2  4304.9  387.21  4509.3  386.57  4557.9  386.35    4620  385.08
  4760.2  384.87 4804.07384.0293    4896   383.1  4974.8  384.46    4990   384.3
  5000.5  382.25  5007.7  382.79  5009.9  381.97  5010.4  381.17  5015.4  381.17
  5015.9  381.97  5021.4  384.18  5045.9  383.15 5118.27384.0293  5294.4  386.84
  5315.7  385.64    5351  387.78  5428.9  388.66    5450  389.85  5485.4  389.33
  5527.9  389.84  5534.9  390.58  5570.3  389.76  5591.5  390.54  5630.5  389.84
#Mann= 5 ,-1 , 0
  4113.4      .1       0  4509.3     .05       0  4557.9      .1       0
  5009.9     .07       0  5015.9      .1       0
Bank Sta=4804.07,5118.27
XS Rating Curve= 0 ,0
Exp/Cntr=0.3,0.1

Type RM Length L Ch R = 1 ,4742    ,988,988,988
BEGIN DESCRIPTION:
UNT 179 SanMiguel Cr Watershed 10.0
END DESCRIPTION:
XS GIS Cut Line= 4
       2088115.4     13448634.82      2087716.07     13448808.44
      2087549.41     13449357.05      2088063.29     13449905.66
#Sta/Elev= 30
  4082.5  385.69  4085.8  385.68    4483  382.31 4609.54381.4565  4754.7  381.04
  4884.1  382.03  4890.6  381.92    4901  379.55  4911.5  381.63    4917  380.02
  4922.2  381.41  4932.4  379.76  4949.9  381.55  4960.7  379.04  4961.2  378.24
  4966.2  378.24  4966.7  379.04  4974.2  381.23  4982.7  381.93    4988  379.98
  4995.1  379.16  5015.6  382.37  5090.3   381.1    5157381.4565  5617.4  387.87
  5645.7  387.12  5666.7  388.08  5688.2  387.17  5730.7  388.53    5843  389.36
#Mann= 5 ,-1 , 0
  4082.5      .1       0  4085.8     .05       0    4483      .1       0
  4960.7     .07       0  4966.7      .1       0
Bank Sta=4609.54,5157
XS Rating Curve= 0 ,0
Exp/Cntr=0.3,0.1

Type RM Length L Ch R = 1 ,3754    ,1208,1208,1208
BEGIN DESCRIPTION:
UNT 179 SanMiguel Cr Watershed 9.0
END DESCRIPTION:
XS GIS Cut Line= 4
      2087703.82     13448324.29      2087210.75     13448418.04
      2086988.53     13449029.15      2087849.66     13449695.83
#Sta/Elev= 30
    4023  383.34  4072.7  382.57  4242.2  382.66  4316.6  383.97  4327.2  383.08
  4342.9  383.27  4367.9  383.11    4379  383.95  4584.9  384.23  4667.6  384.47
    4817  383.88  4875.2  382.79  4883.5  382.72  4915.4  379.85  4939.4  379.03
 4944.94378.2165  4989.9   378.5  4995.2  375.96  5000.5   374.6  5008.1   374.1
  5008.6   373.3  5013.6   373.3  5014.1   374.1  5020.5   378.3  5025.8  378.38
  5212.1   377.7 5352.12378.2172  5562.5   379.7  5732.7  379.77  6264.2  386.45
#Mann= 8 ,-1 , 0
    4023      .1       0  4242.2     .08       0  4342.9     .05       0
  4584.9     .08       0  4667.6     .05       0  4875.2      .1       0
  5008.1     .07       0  5014.1      .1       0
Bank Sta=4944.94,5352.12
XS Rating Curve= 0 ,0
Exp/Cntr=0.3,0.1

Type RM Length L Ch R = 1 ,2546    ,100,100,100
BEGIN DESCRIPTION:
UNT 179 SanMiguel Cr Watershed 8.0
END DESCRIPTION:
XS GIS Cut Line= 6
      2087243.17     13448345.31      2086995.73     13448401.74
       2086583.4     13448562.33      2086444.51     13448753.31
      2086613.78     13448814.07      2087671.38     13449702.62
#Sta/Elev= 30
  4022.8  383.96  4073.4  384.07  4174.2   384.2  4195.3  385.87  4215.5  385.09
  4274.4   380.6  4356.2  379.36  4459.6   376.2  4524.7   376.5  4603.6   375.1
  4610.1  375.96  4663.7  375.63  4747.6  373.99  4965.4  375.12  4993.2373.2807
  4998.1  370.38  4998.6  369.58  5003.6  369.58  5004.1  370.38  5023.6  372.16
 5085.52373.2837  5173.7  375.59  5372.7  376.87  5500.2  376.49  6011.3  379.27
  6017.9  378.39  6039.2  379.34  6216.9   380.1  6245.5  381.35  6517.7     384
#Mann= 5 ,-1 , 0
  4022.8     .05       0  4073.4     .08       0  4215.5      .1       0
  4998.1     .07       0  5004.1      .1       0
Bank Sta=4993.2,5085.52
XS Rating Curve= 0 ,0
Exp/Cntr=0.3,0.1

Type RM Length L Ch R = 1 ,2446    ,21,21,21
BEGIN DESCRIPTION:
UNT 179 SanMiguel Cr Watershed 7.0
END DESCRIPTION:
XS GIS Cut Line= 6
      2087165.03     13448293.22       2086605.1     13448531.95
      2086435.83     13448670.84      2086405.45     13448866.15
       2086583.4     13448887.86      2087540.41      13449749.6
#Sta/Elev= 30
  4016.8  384.01  4146.3  384.13  4223.4  380.24  4262.5     379  4291.5  379.43
  4315.2  380.01  4338.8  388.29  4344.2  384.32  4353.8  382.74  4367.8  377.03
    4386  376.35  4596.7  375.58    4656  374.14  4929.6  374.55  4982.8372.3333
  5017.7  370.32  5018.2  369.52  5023.7  370.32 5032.84372.3329    5039  373.67
  5061.8  374.68  5075.4  374.78    5082  373.57    5157  374.46  5162.6  375.65
  5482.3   375.6    5865  377.54  5914.3  376.77    6226  378.38  6509.2  382.18
#Mann= 4 ,-1 , 0
  4016.8     .08       0  4146.3      .1       0  5017.7     .07       0
  5023.7      .1       0
Bank Sta=4982.8,5032.84
XS Rating Curve= 0 ,0
Exp/Cntr=0.3,0.1

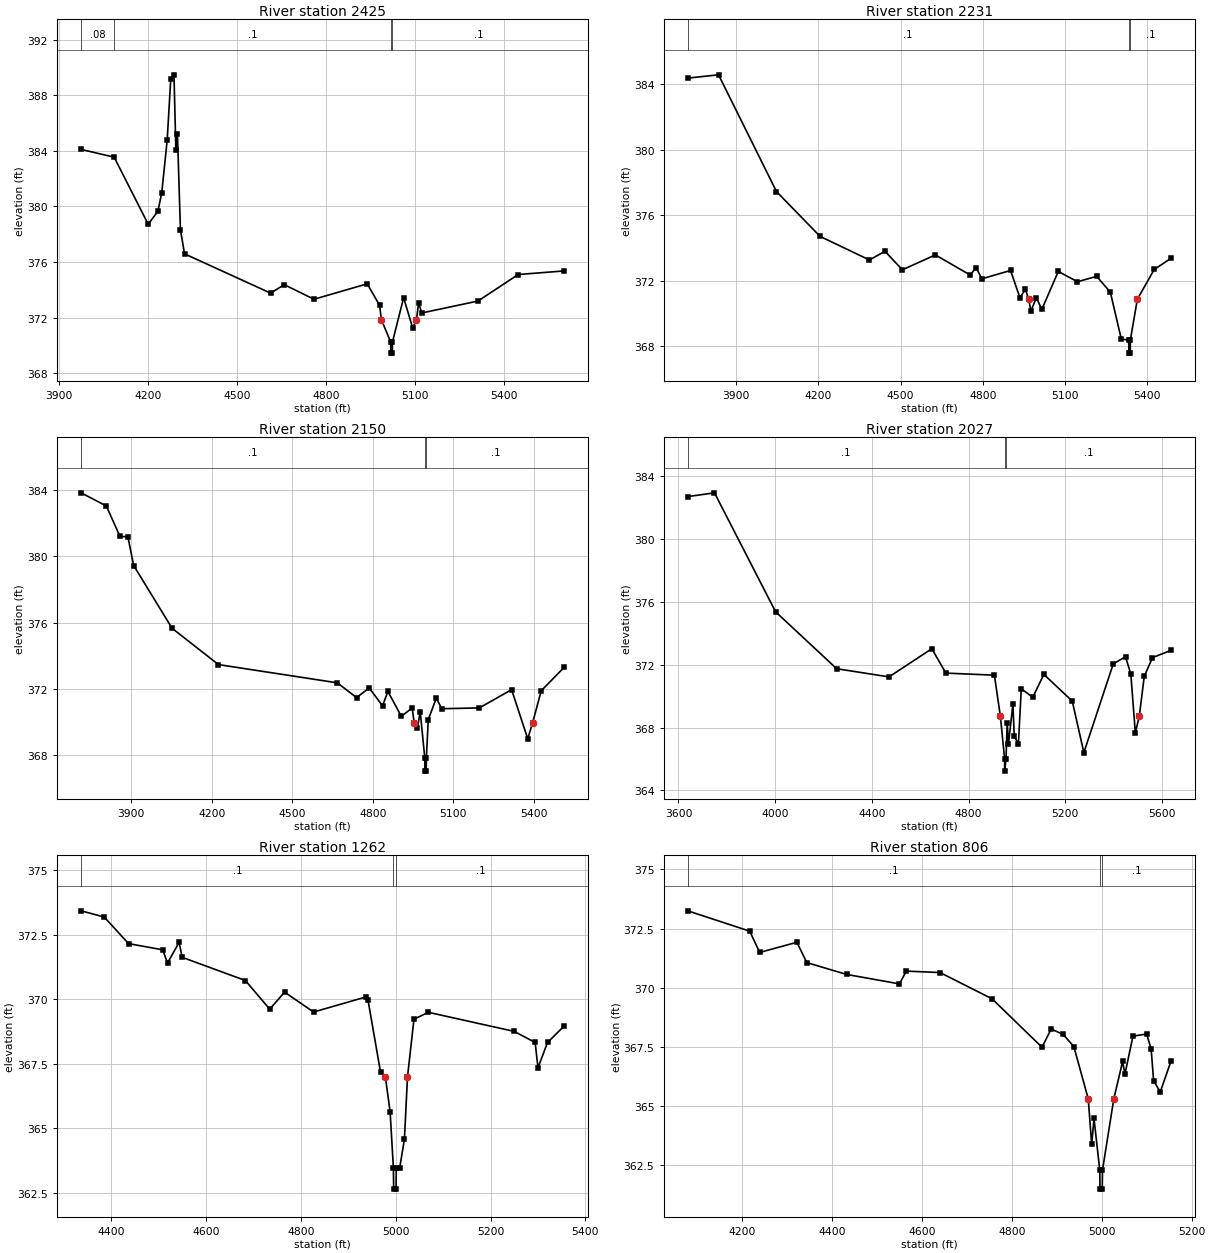
Type RM Length L Ch R = 1 ,2425    ,194,194,194
BEGIN DESCRIPTION:
UNT 179 SanMiguel Cr Watershed 6.0
END DESCRIPTION:
XS GIS Cut Line= 4
      2087143.28     13448275.88      2086431.49     13448575.36
      2086362.05      13449000.7      2086766.52     13449126.57
#Sta/Elev= 30
  3975.3  384.11  4086.7  383.55  4201.3  378.72  4233.8  379.65  4246.9  380.98
  4265.2  384.77  4277.2  389.17  4288.1  389.48  4294.4   384.1  4299.8  385.19
  4309.8  378.33  4323.6  376.59  4613.5  373.76  4659.3  374.37  4759.6  373.32
  4938.8  374.43  4980.2  372.89 4986.64371.8379  5017.7  370.24  5018.2  369.44
  5023.2  369.44  5023.7  370.24  5061.3  373.43  5091.7  371.26 5104.48371.8385
  5111.9  373.08  5122.1  372.33  5311.6  373.19    5447   375.1  5602.1  375.36
#Mann= 4 ,-1 , 0
  3975.3     .08       0  4086.7      .1       0  5017.7     .07       0
  5023.7      .1       0
Bank Sta=4986.64,5104.48
XS Rating Curve= 0 ,0
Exp/Cntr=0.3,0.1

Type RM Length L Ch R = 1 ,2231    ,81,81,81
BEGIN DESCRIPTION:
UNT 179 SanMiguel Cr Watershed 5.0
END DESCRIPTION:
XS GIS Cut Line= 5
      2087186.66      13448223.8      2086553.02     13448297.58
      2086244.86     13448610.08      2086236.18     13448792.37
      2086231.84     13449295.85
#Sta/Elev= 30
  3723.3  384.39  3835.7  384.59  4047.1  377.46  4206.2  374.72  4386.2  373.28
  4442.8  373.81  4506.5  372.68  4626.7  373.59    4754  372.36  4775.2  372.82
  4796.4  372.13  4901.2  372.64  4935.2  370.97  4955.2  371.48 4967.42370.8813
  4975.2  370.15  4995.2  370.98  5015.2  370.26  5075.2  372.58  5145.2  371.95
  5215.2  372.28  5265.2  371.31  5305.2  368.44  5332.2  368.39  5332.7  367.59
  5337.7  367.59  5338.2  368.39 5363.61370.8807  5425.2   372.7  5486.1  373.38
#Mann= 3 ,-1 , 0
  3723.3      .1       0  5332.2     .07       0  5338.2      .1       0
Bank Sta=4967.42,5363.61
XS Rating Curve= 0 ,0
Exp/Cntr=0.3,0.1

Type RM Length L Ch R = 1 ,2150    ,123,123,123
BEGIN DESCRIPTION:
UNT 179 SanMiguel Cr Watershed 4.0
END DESCRIPTION:
XS GIS Cut Line= 5
      2087117.26     13448145.67      2086431.49     13448280.22
      2086188.44     13448566.67      2086171.08     13448827.09
      2086197.07     13449290.74
#Sta/Elev= 30
  3713.6  383.82  3807.6  383.03  3858.6  381.19    3888  381.17  3909.5  379.44
  4052.5  375.66  4225.4  373.47  4668.3  372.37  4739.7  371.48  4786.9  372.06
  4836.6  370.99  4856.6  371.85  4906.7  370.35  4946.8  370.86 4954.44369.9738
  4966.8  369.66  4976.9  370.64  4993.9  367.85  4994.4  367.05  4999.4  367.05
  4999.9  367.85  5006.9  370.15    5037  371.45    5057  370.81  5197.3  370.86
  5317.4  371.96  5377.5     369 5395.84369.9728  5427.6  371.89  5513.5  373.31
#Mann= 3 ,-1 , 0
  3713.6      .1       0  4993.9     .07       0  4999.9      .1       0
Bank Sta=4954.44,5395.84
XS Rating Curve= 0 ,0
Exp/Cntr=0.3,0.1

Type RM Length L Ch R = 1 ,2027    ,765,765,765
BEGIN DESCRIPTION:
UNT 179 SanMiguel Cr Watershed 3.0
END DESCRIPTION:
XS GIS Cut Line= 4
      2087134.59     13448058.87      2086327.33     13448176.05
      2086071.25     13448783.69      2086158.04     13449300.12
#Sta/Elev= 30
  3638.4  382.68  3749.1  382.92  4001.8  375.36  4254.4  371.74  4471.1  371.22
  4648.1  373.01  4706.4  371.46    4907  371.33 4931.72368.7146  4949.2  366.03
  4949.7  365.23  4955.2  366.03  4959.9  368.31  4965.3  366.98  4983.6  369.49
  4989.1  367.46  5006.4  366.96  5018.2  370.47  5065.7  369.92  5111.5  371.38
  5229.1  369.68  5277.1  366.41  5398.8  372.05  5449.5   372.5  5471.4  371.39
    5490  367.67 5506.41368.7158  5526.9  371.25    5561  372.45  5637.2   372.9
#Mann= 3 ,-1 , 0
  3638.4      .1       0  4949.2     .07       0  4955.2      .1       0
Bank Sta=4931.72,5506.41
XS Rating Curve= 0 ,0
Exp/Cntr=0.3,0.1

Type RM Length L Ch R = 1 ,1262    ,456,456,456
BEGIN DESCRIPTION:
Mapping XS f968acb7
END DESCRIPTION:
XS GIS Cut Line= 3
      2086402.55     13448466.94      2085902.58     13448349.76
      2085399.95     13448407.05
#Sta/Elev= 30
    4336  373.42  4384.8  373.18  4436.2  372.15  4508.1  371.91  4518.4   371.4
  4542.9   372.2  4549.2  371.62  4682.7  370.72    4734  369.61  4765.4  370.27
  4826.5   369.5  4936.3  370.08  4941.3  369.97  4967.9  367.16 4978.02366.9838
    4988  365.64    4995  363.44  4995.5  362.64  5000.5  362.64    5001  363.44
  5008.1  363.45  5018.2  364.57 5024.67366.9854  5038.3  369.22  5068.5  369.49
  5249.7  368.75    5294  368.32    5300  367.34  5320.1  368.32  5355.4  368.96
#Mann= 3 ,-1 , 0
    4336      .1       0    4995     .07       0    5001      .1       0
Bank Sta=4978.02,5024.67
XS Rating Curve= 0 ,0
Exp/Cntr=0.3,0.1

Type RM Length L Ch R = 1 ,806     ,529,529,529
BEGIN DESCRIPTION:
Mapping XS 4664b8f9
END DESCRIPTION:
XS GIS Cut Line= 3
      2086472.92     13448343.27      2085936.43      13448064.6
      2085471.56     13447994.29
#Sta/Elev= 30
    4079  373.25  4216.9  372.39    4239  371.49  4321.8  371.92  4343.9  371.06
  4432.4  370.56  4549.9  370.16  4565.1   370.7  4640.1  370.64  4755.8  369.53
    4867  367.48  4887.3  368.25  4913.7  368.03  4937.8  367.51 4969.85365.2949
  4977.5  363.37  4982.6  364.47  4995.5  362.28    4996  361.48    5001  361.48
  5001.5  362.28 5026.66365.2941  5046.3  366.88  5051.4  366.34  5069.3  367.95
  5099.7  368.04  5109.8   367.4  5115.2  366.07    5130  365.59  5153.7  366.88
#Mann= 3 ,-1 , 0
    4079      .1       0  4995.5     .07       0  5001.5      .1       0
Bank Sta=4969.85,5026.66
XS Rating Curve= 0 ,0
Exp/Cntr=0.3,0.1

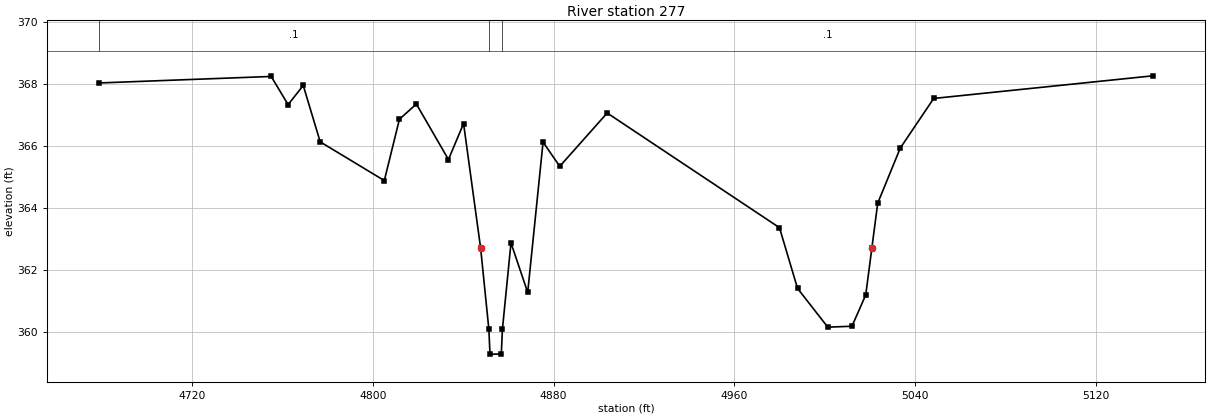
Type RM Length L Ch R = 1 ,277     ,0,0,0
BEGIN DESCRIPTION:
UNT 179 SanMiguel Cr Watershed 1.0
END DESCRIPTION:
XS GIS Cut Line= 3
      2085607.88     13447600.01      2085445.42     13447780.17
      2085524.89     13447989.49
#Sta/Elev= 30
  4678.8  368.03  4754.9  368.24  4762.4  367.33  4769.1  367.95  4776.6  366.13
    4805  364.88  4811.7  366.86  4819.2  367.35  4833.4  365.56  4840.1  366.72
 4847.66362.6973  4851.3  360.08  4851.8  359.28  4856.8  359.28  4857.3  360.08
  4861.1  362.87  4868.5  361.27  4875.3  366.12  4882.7  365.34  4903.7  367.06
    4980  363.36    4988   361.4  5001.4  360.15  5012.1  360.18  5018.2  361.19
 5020.91362.7036  5023.5  364.15  5033.5  365.93  5048.3  367.53  5145.3  368.26
#Mann= 3 ,-1 , 0
  4678.8      .1       0  4851.3     .07       0  4857.3      .1       0
Bank Sta=4847.66,5020.91
XS Rating Curve= 0 ,0
Exp/Cntr=0.3,0.1
LCMann Table=0

Chan Stop Cuts=-1
Use User Specified Reach Order=0
Composite Channel Slope=5