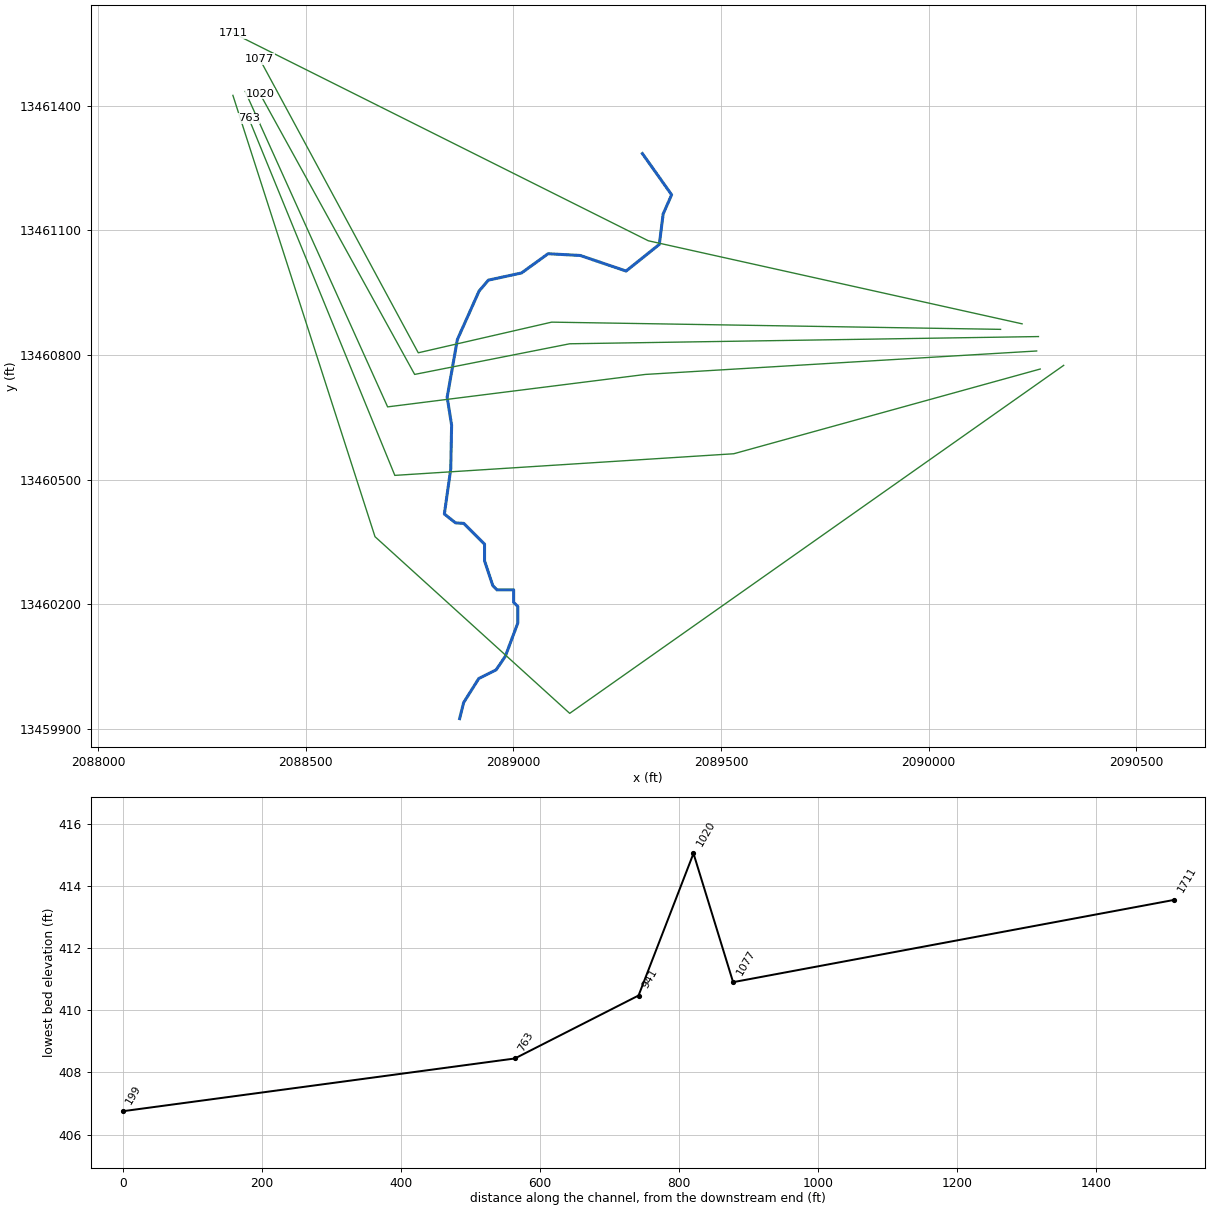
--- UNT 180 SanMiguel Cr Watershed.prj (project) ---

Proj Title=UNT 180 SanMiguel Cr Watershed Base Level Engineering
Current Plan=p01
Default Exp/Contr=0.3,0.1
English Units
Geom File=g01
Flow File=f01
Plan File=p01
Y Axis Title=Elevation
X Axis Title(PF)=Main Channel Distance
X Axis Title(XS)=Station
BEGIN DESCRIPTION:
UNT 180 SanMiguel Cr Watershed
END DESCRIPTION:
DSS Export Rating Curves= 0
DSS Export Rating Curve Sorted= 0
DSS Export Volume Flow Curves= 0
DXF OffsetX= 0
DXF OffsetY= 0
DXF ScaleX= 1
DXF ScaleY= 10

--- UNT 180 SanMiguel Cr Watershed.p01 (plan) ---

Plan Title=Multiple Run
Short Identifier=Multiple
Geom File=g01
Flow File=f01
Subcritical Flow
K Sum by GR= 0
Std Step Tol= 0.01
Critical Tol= 0.01
Num of Std Step Trials= 20
Max Error Tol= 0.3
Flow Tol Ratio= 0.001
Split Flow NTrial= 30
Split Flow Tol= 0.02
Split Flow Ratio= 0.02
Log Output Level= 0
Friction Slope Method= 1
Unsteady Friction Slope Method= 2
Unsteady Bridges Friction Slope Method= 1
Parabolic Critical Depth
Global Vel Dist=  1 , 1 , 1
Global Log Level= 0
CheckData=True
Encroach Param= -1, 0, 0, 0
BEGIN DESCRIPTION:
Multiple Run
END DESCRIPTION:

--- UNT 180 SanMiguel Cr Watershed.f01 (steady flow) ---

Flow Title=Multiple
Number of Profiles=7
Profile Names=10-year,25-year,50-year,1pct_min,100-year,1pct_plu,500-year
River Rch & RM= UNT 180 SanMigue,Reach-1,1711
     183     249     303     184     368     734     550
Boundary for River Rch & Prof#=UNT 180 SanMigue,Reach-1,1
Up Type=0
Dn Type=3
Dn Slope=0.005
Boundary for River Rch & Prof#=UNT 180 SanMigue,Reach-1,2
Up Type=0
Dn Type=3
Dn Slope=0.005
Boundary for River Rch & Prof#=UNT 180 SanMigue,Reach-1,3
Up Type=0
Dn Type=3
Dn Slope=0.005
Boundary for River Rch & Prof#=UNT 180 SanMigue,Reach-1,4
Up Type=0
Dn Type=3
Dn Slope=0.005
Boundary for River Rch & Prof#=UNT 180 SanMigue,Reach-1,5
Up Type=0
Dn Type=3
Dn Slope=0.005
Boundary for River Rch & Prof#=UNT 180 SanMigue,Reach-1,6
Up Type=0
Dn Type=3
Dn Slope=0.005
Boundary for River Rch & Prof#=UNT 180 SanMigue,Reach-1,7
Up Type=0
Dn Type=3
Dn Slope=0.005

--- UNT 180 SanMiguel Cr Watershed.g01 (geometry) ---

Geom Title=Existing Conditions
Program Version=5.05

River Reach=UNT 180 SanMigue,Reach-1
Reach XY= 30
       2089310.8     13461284.91      2089381.19     13461185.69
       2089360.8     13461139.54       2089351.5     13461066.16
      2089271.55     13461002.09      2089161.14     13461039.59
      2089083.79     13461043.76      2089019.73     13460997.41
      2088940.04     13460980.22      2088917.65     13460953.92
       2088865.3     13460836.99      2088840.82     13460698.45
       2088851.5       13460631.      2088849.42     13460525.53
      2088834.05      13460417.2      2088860.88     13460395.84
       2088880.8     13460394.54       2088930.8     13460344.54
       2088930.8     13460304.54       2088950.8     13460244.54
       2088960.8     13460234.54       2089000.8     13460234.54
       2089000.8     13460204.54       2089010.8     13460194.54
       2089010.8     13460154.54       2088980.8     13460074.54
      2088958.62     13460041.93      2088916.95     13460021.09
      2088880.49     13459963.28       2088870.8     13459924.54

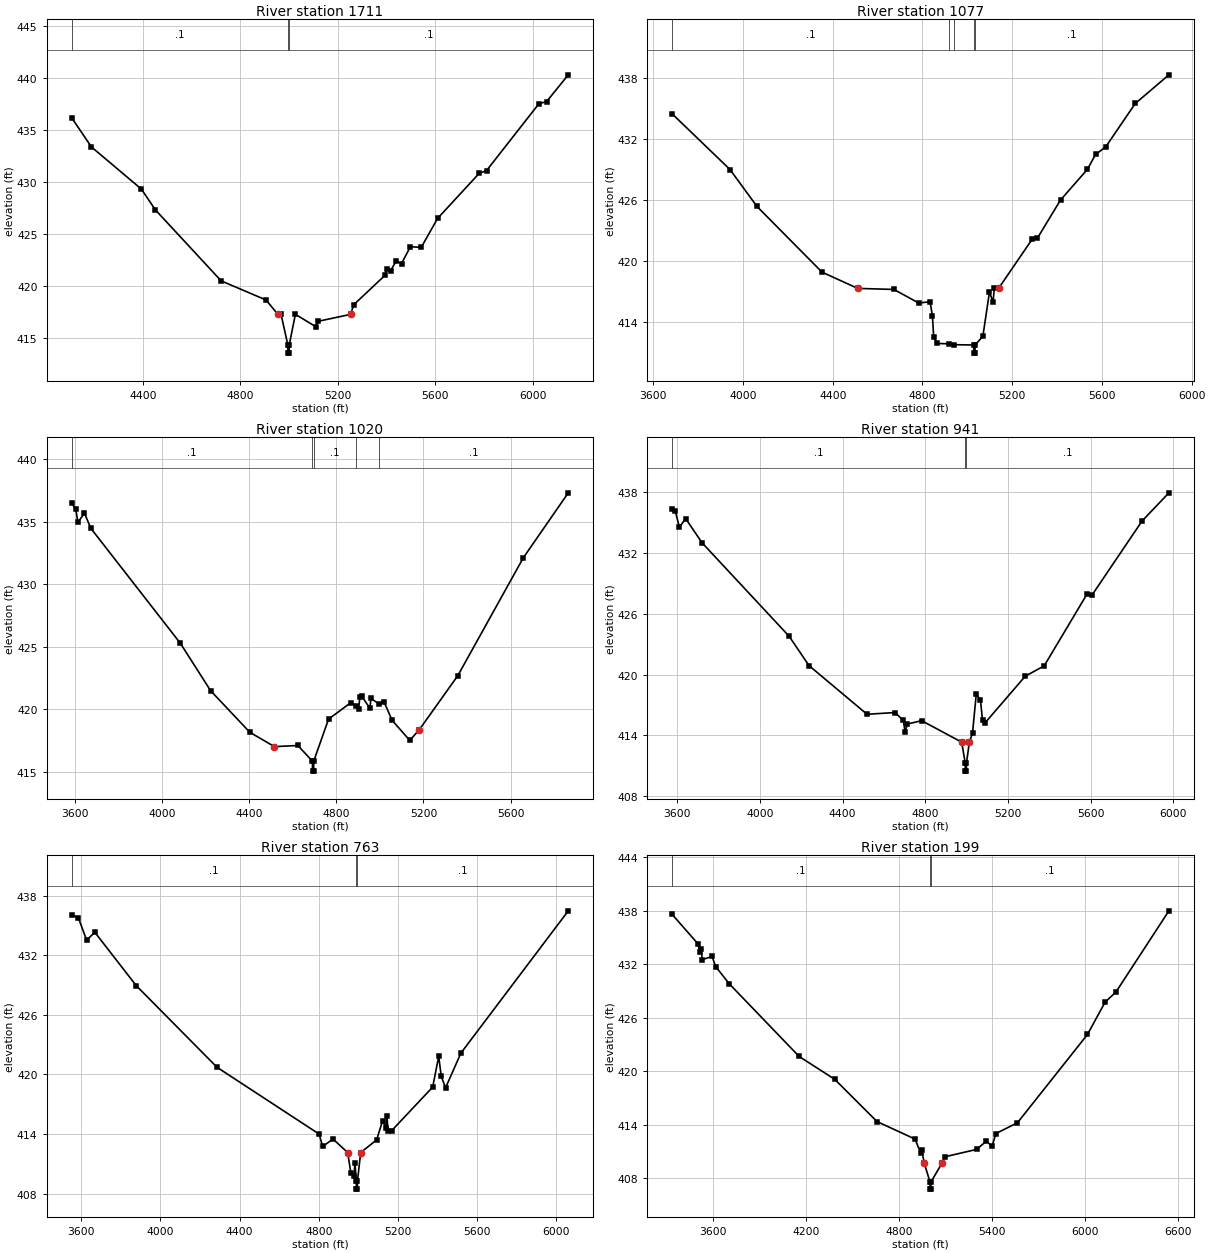
Type RM Length L Ch R = 1 ,1711    ,634,634,634
BEGIN DESCRIPTION:
UNT 180 SanMiguel Cr Watershed 6.0
END DESCRIPTION:
XS GIS Cut Line= 3
      2090224.95     13460875.01        2089325.       13461075.
      2088325.04     13461574.98
#Sta/Elev= 30
  4106.8  436.19  4188.7  433.36  4393.6  429.32  4451.2  427.32  4721.4   420.5
  4905.8  418.66 4954.52417.2818  4967.2  417.29    4995  414.36  4995.5  413.56
  5000.5  413.56    5001  414.36  5026.1  417.29  5109.8   416.1  5118.1  416.61
 5252.67417.2816  5266.3  418.22  5394.9  421.05  5400.5  421.62  5417.2  421.47
  5439.6   422.4  5461.9  422.16  5498.3  423.78    5543  423.72  5610.1   426.5
  5780.6  430.82  5811.3   431.1  6026.6  437.53  6057.3  437.71  6146.7  440.29
#Mann= 3 ,-1 , 0
  4106.8      .1       0    4995     .07       0    5001      .1       0
Bank Sta=4954.52,5252.67
XS Rating Curve= 0 ,0
Exp/Cntr=0.3,0.1

Type RM Length L Ch R = 1 ,1077    ,57,57,57
BEGIN DESCRIPTION:
UNT 180 SanMiguel Cr Watershed 5.0
END DESCRIPTION:
XS GIS Cut Line= 4
      2090173.14     13460861.72      2089092.41     13460879.08
      2088771.23     13460805.29      2088389.28     13461512.75
#Sta/Elev= 30
  3684.2  434.47  3942.4  428.98  4062.4  425.35  4352.4  418.88 4511.64417.2821
  4672.5  417.18  4782.9  415.85  4834.2  415.96  4844.5  414.57    4850   412.5
    4865  411.86  4918.5  411.83  4942.5  411.74  5028.6  411.71  5029.1  410.91
  5034.1  410.91  5034.6  411.71  5069.3  412.57  5098.6  416.91  5114.8  415.95
  5120.5  417.37  5139.2417.2821  5289.9  422.15  5311.8  422.21  5415.6  425.99
  5535.5  429.01  5571.6  430.47    5617  431.22  5748.7  435.49  5898.6  438.31
#Mann= 5 ,-1 , 0
  3684.2      .1       0  4918.5     .05       0  4942.5      .1       0
  5028.6     .07       0  5034.6      .1       0
Bank Sta=4511.64,5139.2
XS Rating Curve= 0 ,0
Exp/Cntr=0.3,0.1

Type RM Length L Ch R = 1 ,1020    ,79,79,79
BEGIN DESCRIPTION:
UNT 180 SanMiguel Cr Watershed 4.0
END DESCRIPTION:
XS GIS Cut Line= 4
      2090264.29     13460844.35      2089135.81     13460826.99
      2088762.54     13460753.21      2088389.74     13461429.46
#Sta/Elev= 30
  3583.8   436.5  3603.1  436.05  3613.1  434.96  3643.1  435.69  3673.1  434.47
  4083.1   425.3  4223.2  421.48  4403.2  418.16 4515.81417.0195  4623.2  417.11
  4690.2  415.86  4690.7  415.06  4695.7  415.06  4696.2  415.86  4764.2  419.22
  4866.1  420.53  4892.3  420.29  4902.5  420.03  4907.6  420.95  4917.1  421.04
  4953.8  420.09  4958.9  420.87  4997.6  420.42    5019   420.6  5056.3  419.12
  5137.3  417.52  5180.8  418.37  5357.6  422.69  5658.8  432.13  5865.1  437.32
#Mann= 5 ,-1 , 0
  3583.8      .1       0  4690.2     .07       0  4696.2      .1       0
  4892.3     .05       0  4997.6      .1       0
Bank Sta=4515.81,5180.8
XS Rating Curve= 0 ,0
Exp/Cntr=0.3,0.1

Type RM Length L Ch R = 1 ,941     ,178,178,178
BEGIN DESCRIPTION:
UNT 180 SanMiguel Cr Watershed 3.0
END DESCRIPTION:
XS GIS Cut Line= 4
      2090259.99     13460809.64       2089318.1     13460753.21
      2088697.44     13460675.08      2088354.55     13461434.64
#Sta/Elev= 30
  3575.7  436.38  3590.7  436.17  3610.7  434.54  3640.8   435.4  3720.9     433
  4141.7  423.78  4237.7  420.89  4518.3  416.09  4653.4  416.26  4693.7  415.49
  4701.9  414.38  4713.9  415.13  4782.3  415.46 4976.01413.3384  4993.1  411.28
  4993.6  410.48  4998.6  410.48  4999.1  411.28 5013.25413.3389  5028.4  414.24
  5046.5  418.08  5066.7  417.52  5076.7  415.51  5086.8  415.19  5283.2  419.84
  5375.1  420.87  5583.6     428  5605.7  427.83  5847.9  435.15  5978.2  437.94
#Mann= 3 ,-1 , 0
  3575.7      .1       0  4993.1     .07       0  4999.1      .1       0
Bank Sta=4976.01,5013.25
XS Rating Curve= 0 ,0
Exp/Cntr=0.3,0.1

Type RM Length L Ch R = 1 ,763     ,564,564,564
BEGIN DESCRIPTION:
UNT 180 SanMiguel Cr Watershed 2.0
END DESCRIPTION:
XS GIS Cut Line= 4
       2090268.6     13460766.22      2089530.77     13460562.24
       2088714.8     13460510.15      2088363.25     13461369.49
#Sta/Elev= 30
  3550.1  436.09    3585  435.77  3626.5  433.53    3668  434.32  3877.2  428.95
  4285.9  420.72  4802.4  413.99  4819.5  412.75  4872.5  413.49 4946.23412.1388
  4962.7  410.06  4978.2   409.8  4983.2  411.08  4989.8  409.25  4990.3  408.45
  4995.3  408.45  4995.8  409.25 5012.07412.1379    5093  413.41    5123  415.36
  5138.6  414.59  5144.9  415.81  5150.3  414.26  5168.9  414.34  5376.2  418.73
  5406.6  421.83  5419.4   419.8  5441.4  418.66  5518.8  422.15  6061.7  436.48
#Mann= 3 ,-1 , 0
  3550.1      .1       0  4989.8     .07       0  4995.8      .1       0
Bank Sta=4946.23,5012.07
XS Rating Curve= 0 ,0
Exp/Cntr=0.3,0.1

Type RM Length L Ch R = 1 ,199     ,0,0,0
BEGIN DESCRIPTION:
UNT 180 SanMiguel Cr Watershed 1.0
END DESCRIPTION:
XS GIS Cut Line= 4
      2090325.02     13460775.02      2089135.81     13459937.24
      2088667.06     13460362.58      2088324.99     13461425.02
#Sta/Elev= 30
    3336  437.61  3501.1  434.33  3515.9  433.37    3522   433.7  3530.7  432.53
  3593.4  432.89  3616.9  431.75    3703  429.84  4155.1  421.65  4384.2  419.09
  4657.1  414.34  4902.8  412.37  4938.6  410.81  4945.3  411.11 4962.26409.6441
  4999.1  407.55  4999.6  406.75  5004.6  406.75  5005.1  407.55 5075.46409.6443
    5094  410.38  5299.5  411.21    5363  412.15  5398.8  411.55  5423.7  412.99
  5562.8   414.2  6014.5  424.12  6128.4  427.76  6197.8  428.88  6539.8  438.01
#Mann= 3 ,-1 , 0
    3336      .1       0  4999.1     .07       0  5005.1      .1       0
Bank Sta=4962.26,5075.46
XS Rating Curve= 0 ,0
Exp/Cntr=0.3,0.1
LCMann Table=0

Chan Stop Cuts=-1
Use User Specified Reach Order=0
Composite Channel Slope=5