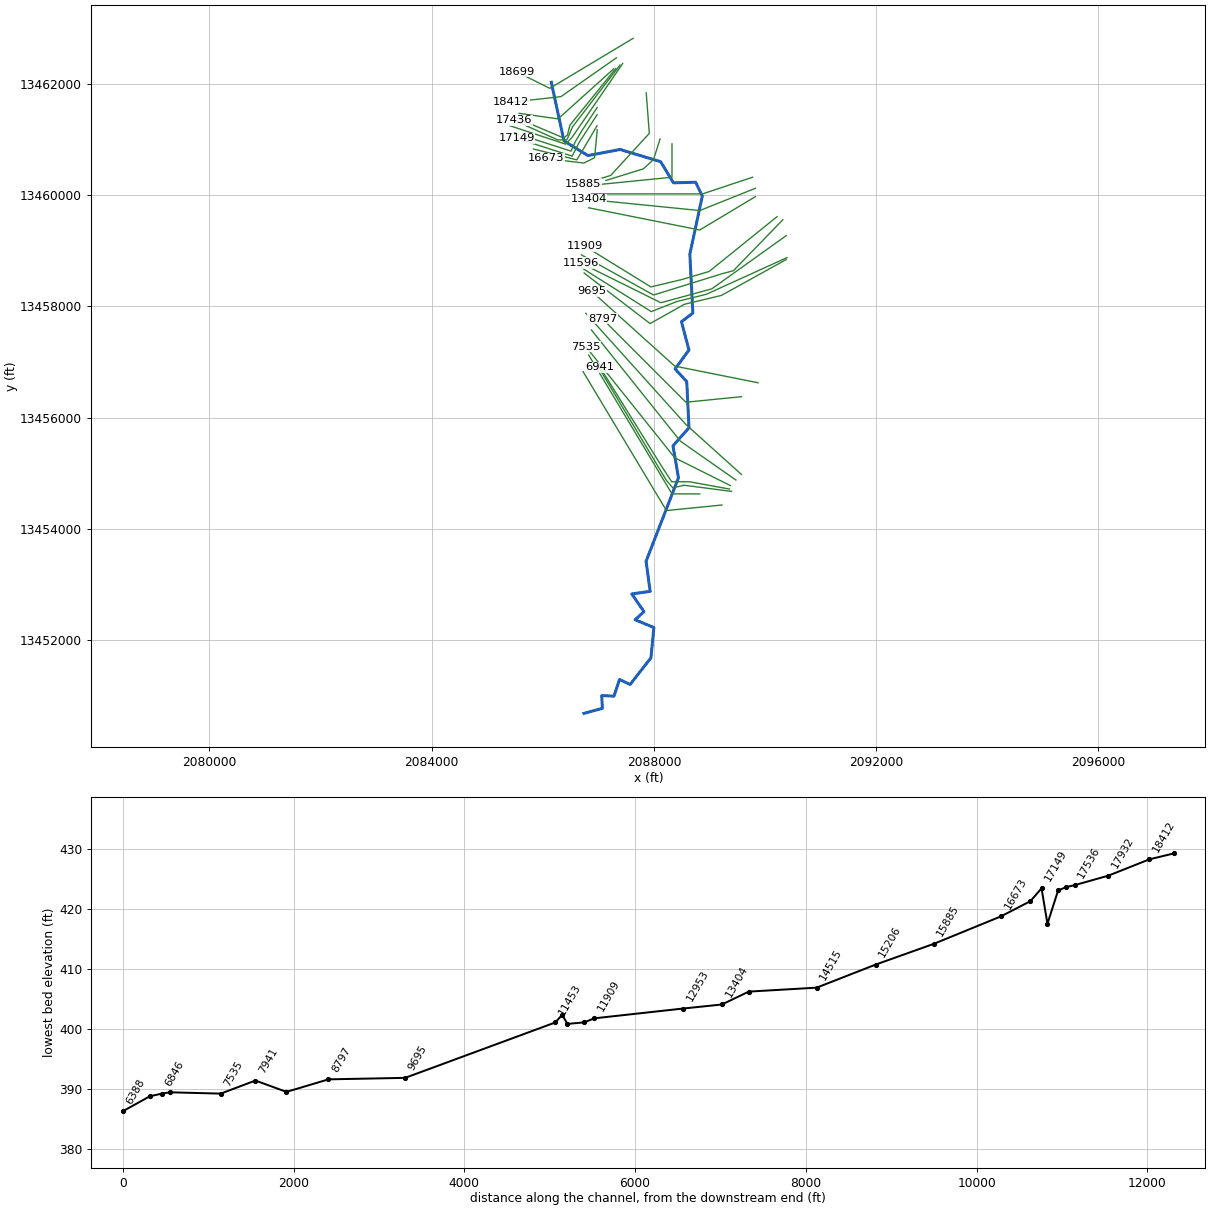
--- UNT 181 SanMiguel Cr Watershed.prj (project) ---

Proj Title=UNT 181 SanMiguel Cr Watershed Base Level Engineering
Current Plan=p01
Default Exp/Contr=0.3,0.1
English Units
Geom File=g01
Flow File=f01
Plan File=p01
Y Axis Title=Elevation
X Axis Title(PF)=Main Channel Distance
X Axis Title(XS)=Station
BEGIN DESCRIPTION:
UNT 181 SanMiguel Cr Watershed
END DESCRIPTION:
DSS Export Rating Curves= 0
DSS Export Rating Curve Sorted= 0
DSS Export Volume Flow Curves= 0
DXF OffsetX= 0
DXF OffsetY= 0
DXF ScaleX= 1
DXF ScaleY= 10

--- UNT 181 SanMiguel Cr Watershed.p01 (plan) ---

Plan Title=Multiple Run
Short Identifier=Multiple
Geom File=g01
Flow File=f01
Subcritical Flow
K Sum by GR= 0
Std Step Tol= 0.01
Critical Tol= 0.01
Num of Std Step Trials= 20
Max Error Tol= 0.3
Flow Tol Ratio= 0.001
Split Flow NTrial= 30
Split Flow Tol= 0.02
Split Flow Ratio= 0.02
Log Output Level= 0
Friction Slope Method= 1
Unsteady Friction Slope Method= 2
Unsteady Bridges Friction Slope Method= 1
Parabolic Critical Depth
Global Vel Dist=  1 , 1 , 1
Global Log Level= 0
CheckData=True
Encroach Param= -1, 0, 0, 0
BEGIN DESCRIPTION:
Multiple Run
END DESCRIPTION:

--- UNT 181 SanMiguel Cr Watershed.f01 (steady flow) ---

Flow Title=Multiple
Number of Profiles=7
Profile Names=10-year,25-year,50-year,1pct_min,100-year,1pct_plu,500-year
River Rch & RM= UNT 181 SanMigue,Reach-1,18699
     166     224     271     163     326     651     480
River Rch & RM= UNT 181 SanMigue,Reach-1,15885
     179     242     294     178     354     707     524
River Rch & RM= UNT 181 SanMigue,Reach-1,13404
     306     427     528     325     648    1294     994
River Rch & RM= UNT 181 SanMigue,Reach-1,9695
     376     530     659     408     815    1626    1263
River Rch & RM= UNT 181 SanMigue,Reach-1,7941
     400     564     703     435     869    1733    1349
River Rch & RM= UNT 181 SanMigue,Reach-1,4242
     444     630     787     489     976    1948    1526
River Rch & RM= UNT 181 SanMigue,Reach-1,2342
     461     653     816     507    1012    2019    1581
Boundary for River Rch & Prof#=UNT 181 SanMigue,Reach-1,1
Up Type=0
Dn Type=3
Dn Slope=0.005
Boundary for River Rch & Prof#=UNT 181 SanMigue,Reach-1,2
Up Type=0
Dn Type=3
Dn Slope=0.005
Boundary for River Rch & Prof#=UNT 181 SanMigue,Reach-1,3
Up Type=0
Dn Type=3
Dn Slope=0.005
Boundary for River Rch & Prof#=UNT 181 SanMigue,Reach-1,4
Up Type=0
Dn Type=3
Dn Slope=0.005
Boundary for River Rch & Prof#=UNT 181 SanMigue,Reach-1,5
Up Type=0
Dn Type=3
Dn Slope=0.005
Boundary for River Rch & Prof#=UNT 181 SanMigue,Reach-1,6
Up Type=0
Dn Type=3
Dn Slope=0.005
Boundary for River Rch & Prof#=UNT 181 SanMigue,Reach-1,7
Up Type=0
Dn Type=3
Dn Slope=0.005

--- UNT 181 SanMiguel Cr Watershed.g01 (geometry) ---

Geom Title=Existing Conditions
Program Version=5.05

River Reach=UNT 181 SanMigue,Reach-1
Reach XY= 30
      2086152.37     13462034.63      2086379.97     13460980.47
       2086810.8     13460714.54       2087390.8     13460824.54
       2088120.8     13460604.54       2088350.8     13460224.54
       2088750.8     13460234.54       2088870.8     13459984.54
      2088646.23     13458941.22      2088700.36      13457880.4
       2088495.5     13457724.15       2088630.8     13457214.54
       2088380.8     13456874.54       2088590.8     13456644.54
       2088630.8     13455814.54      2088343.01      13455490.7
       2088441.4     13454914.17      2087858.24     13453412.19
      2087932.52     13452870.75       2087600.8     13452824.54
      2087821.21     13452505.68      2087660.49     13452359.96
      2087999.16     13452220.09      2087945.92     13451674.45
       2087570.8     13451194.54       2087380.8     13451284.54
       2087280.8     13450984.54       2087060.8     13450994.54
       2087070.8     13450764.54       2086740.8     13450674.54

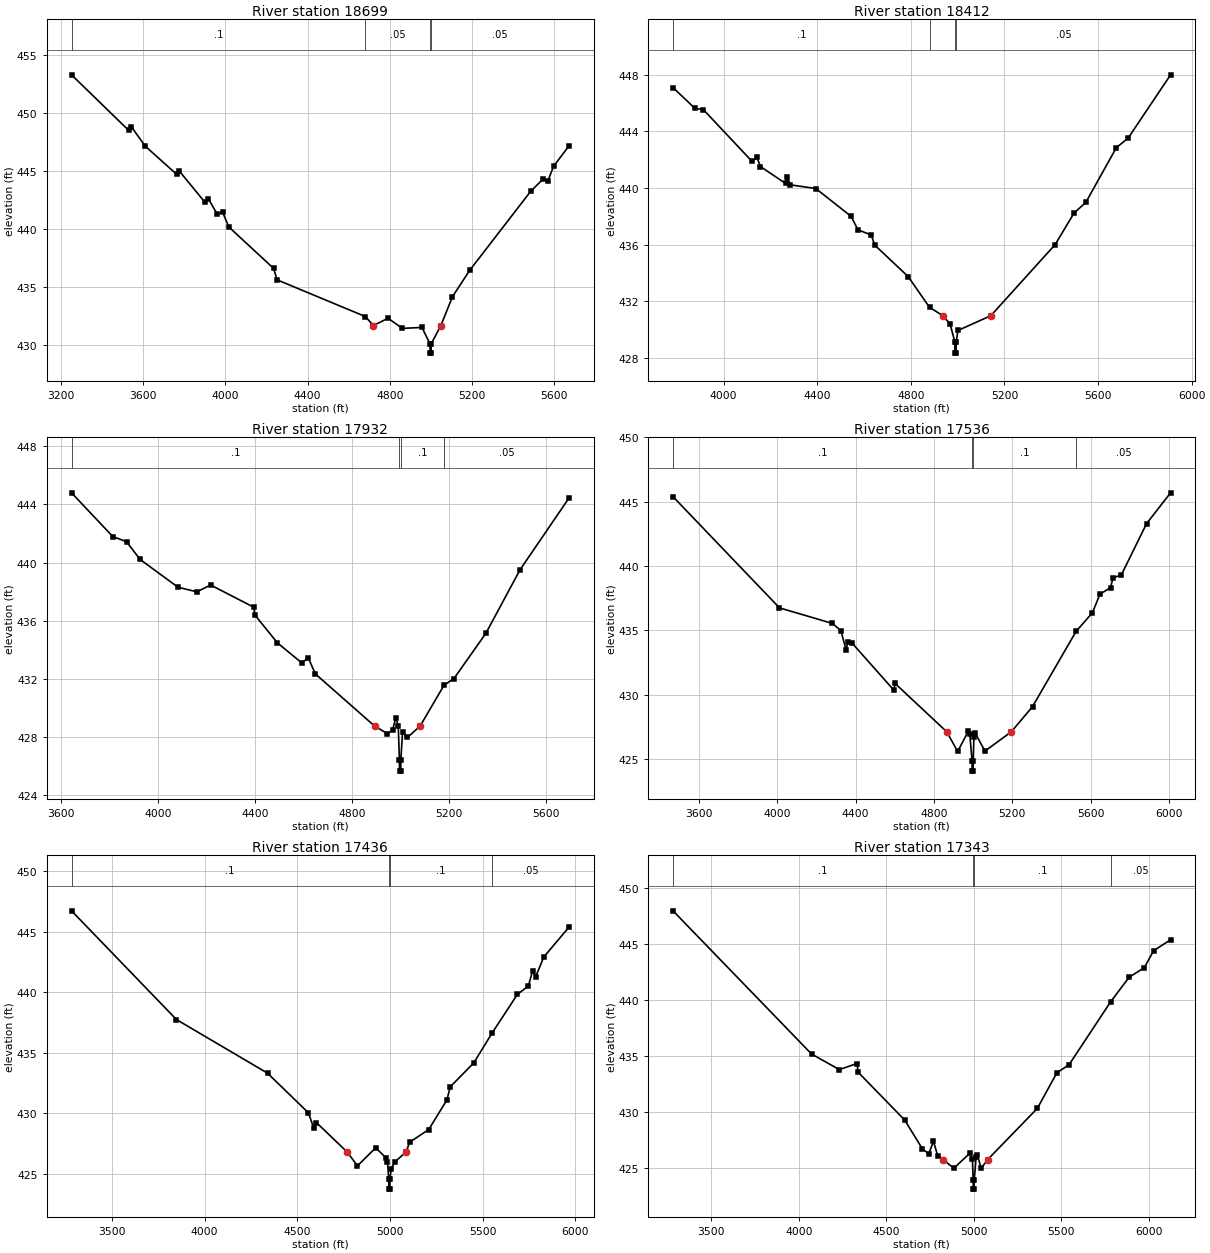
Type RM Length L Ch R = 1 ,18699   ,287,287,287
BEGIN DESCRIPTION:
UNT 181 SanMiguel Cr Watershed 43.0
END DESCRIPTION:
XS GIS Cut Line= 3
      2087625.03     13462825.02        2086125.       13461925.
      2085525.03     13462224.98
#Sta/Elev= 30
    3252  453.28    3530   448.5  3543.6   448.8  3609.7  447.16  3763.2  444.72
  3776.8  444.99  3901.2  442.31  3916.8  442.64  3959.5  441.33  3986.7  441.46
  4017.8  440.18  4235.5  436.62  4251.1  435.65  4680.7  432.49 4720.48431.7148
  4791.4  432.34  4861.4  431.47  4956.6  431.55  4995.4  430.14  4995.9  429.34
  5000.9  429.34  5001.4  430.14 5048.65431.7146  5104.7  434.19  5188.6  436.46
  5484.9  443.25  5546.4  444.33  5568.7  444.14  5596.7  445.41  5672.1  447.18
#Mann= 4 ,-1 , 0
    3252      .1       0  4680.7     .05       0  4995.4     .03       0
  5001.4     .05       0
Bank Sta=4720.48,5048.65
XS Rating Curve= 0 ,0
Exp/Cntr=0.3,0.1

Type RM Length L Ch R = 1 ,18412   ,480,480,480
BEGIN DESCRIPTION:
UNT 181 SanMiguel Cr Watershed 42.0
END DESCRIPTION:
XS GIS Cut Line= 3
      2087325.01     13462475.01        2086325.       13461775.
      2085425.01       13461675.
#Sta/Elev= 30
  3783.6  447.08  3877.3  445.61  3913.1  445.53  4121.5  441.87  4142.4  442.15
  4157.2  441.51  4264.5  440.32  4271.9  440.78  4285.4  440.22  4393.9  439.96
  4544.3     438    4574  437.05  4630.7  436.68  4645.5  435.97  4788.5  433.75
  4879.8  431.58 4936.73430.9897  4967.7   430.4  4987.8  429.15  4988.3  428.35
  4993.3  428.35  4993.8  429.15  5001.2  429.95 5141.74430.9897  5416.8  436.01
  5497.3  438.23  5547.6  438.98  5678.4  442.85  5728.7  443.52  5909.8  447.98
#Mann= 4 ,-1 , 0
  3783.6      .1       0  4879.8     .05       0  4987.8     .03       0
  4993.8     .05       0
Bank Sta=4936.73,5141.74
XS Rating Curve= 0 ,0
Exp/Cntr=0.3,0.1

Type RM Length L Ch R = 1 ,17932   ,396,396,396
BEGIN DESCRIPTION:
UNT 181 SanMiguel Cr Watershed 41.0
END DESCRIPTION:
XS GIS Cut Line= 3
      2087274.97     13462274.97        2086275.       13461375.
      2085575.03       13461475.
#Sta/Elev= 30
  3642.5   444.8  3812.5  441.79  3869.3  441.43  3925.4  440.21  4081.6   438.3
  4159.3  437.98  4216.1  438.45  4393.2  436.93    4400  436.36  4491.9  434.46
  4591.3   433.1  4619.7  433.41  4648.1  432.33 4892.45428.7357  4945.6  428.21
  4966.5  428.45  4980.7  429.32  4990.4  428.72  4994.9  426.43  4995.4  425.63
  5000.4  425.63  5000.9  426.43    5008  428.33  5028.2  427.95  5080.6428.7357
  5179.1  431.55  5220.2  432.01  5351.5  435.12  5492.9  439.51  5694.9  444.45
#Mann= 4 ,-1 , 0
  3642.5      .1       0  4994.9     .07       0  5000.9      .1       0
  5179.1     .05       0
Bank Sta=4892.45,5080.6
XS Rating Curve= 0 ,0
Exp/Cntr=0.3,0.1

Type RM Length L Ch R = 1 ,17536   ,100,100,100
BEGIN DESCRIPTION:
UNT 181 SanMiguel Cr Watershed 40.0
END DESCRIPTION:
XS GIS Cut Line= 5
      2087312.72     13462281.29      2086486.31     13461260.43
      2086444.64     13461086.82       2086375.2     13461031.26
      2085493.22     13461406.28
#Sta/Elev= 30
  3468.1  445.39  4011.5  436.74  4281.6  435.53  4324.8  434.97    4352  433.43
    4360  434.12  4380.8  434.02    4595  430.34  4601.4  430.86 4865.03427.1015
  4920.8  425.57  4974.9  427.13  4982.9  426.89  4994.3  424.84  4994.8  424.04
  4999.8  424.04  5000.3  424.84  5003.7  426.66  5010.8  426.99  5060.1   425.6
 5194.79427.1016    5303  429.06  5525.2  434.91  5608.4  436.36  5646.9   437.8
  5701.2  438.32  5713.9  439.09  5755.5  439.28  5884.8  443.29  6007.4  445.69
#Mann= 4 ,-1 , 0
  3468.1      .1       0  4994.3     .07       0  5000.3      .1       0
  5525.2     .05       0
Bank Sta=4865.03,5194.79
XS Rating Curve= 0 ,0
Exp/Cntr=0.3,0.1

Type RM Length L Ch R = 1 ,17436   ,93,93,93
BEGIN DESCRIPTION:
UNT 181 SanMiguel Cr Watershed 39.0
END DESCRIPTION:
XS GIS Cut Line= 6
      2087389.06     13462343.73      2086534.92     13461232.65
      2086451.59     13461038.21      2086430.75     13460996.54
      2086271.03     13460996.54      2085480.44     13461350.22
#Sta/Elev= 30
  3281.6  446.73  3847.6  437.74  4339.5   433.3  4560.1  430.02  4589.1  428.75
  4603.6  429.21 4769.53426.7762  4824.9  425.64  4923.3  427.13  4976.9  426.32
  4986.9  425.93  4993.9  424.51  4994.4  423.71  4999.4  423.71  4999.9  424.51
  5006.9  425.38  5026.9  425.97 5087.52426.7761  5105.7  427.58  5209.5  428.64
  5307.7  431.09  5325.5  432.17  5452.4  434.15  5551.4  436.62  5688.1  439.82
  5747.2  440.51  5770.4  441.78  5786.7  441.28  5830.5  442.91    5967  445.39
#Mann= 4 ,-1 , 0
  3281.6      .1       0  4993.9     .07       0  4999.9      .1       0
  5551.4     .05       0
Bank Sta=4769.53,5087.52
XS Rating Curve= 0 ,0
Exp/Cntr=0.3,0.1

Type RM Length L Ch R = 1 ,17343   ,125,125,125
BEGIN DESCRIPTION:
UNT 181 SanMiguel Cr Watershed 38.0
END DESCRIPTION:
XS GIS Cut Line= 4
      2087437.71     13462371.56      2086527.97     13461045.15
      2086409.92     13460920.15        2085403.     13461253.47
#Sta/Elev= 30
  3282.3  447.93  4073.1  435.19  4231.5   433.8    4333  434.34  4339.1  433.57
  4605.1  429.31  4706.6  426.74  4742.5   426.3  4769.6  427.41  4793.3  426.15
 4823.72425.7945    4886  425.02  4977.7  426.36  4991.9  425.87  4996.2  423.96
  4996.7  423.16  5001.7  423.16  5002.2  423.96  5013.3  426.04  5020.2  426.21
  5041.7  425.01 5079.17425.7945  5362.8  430.35  5474.6  433.53  5543.3  434.22
  5781.4  439.84  5886.8  442.02  5973.7  442.87  6026.4  444.38  6123.3  445.35
#Mann= 4 ,-1 , 0
  3282.3      .1       0  4996.2     .07       0  5002.2      .1       0
  5781.4     .05       0
Bank Sta=4823.72,5079.17
XS Rating Curve= 0 ,0
Exp/Cntr=0.3,0.1

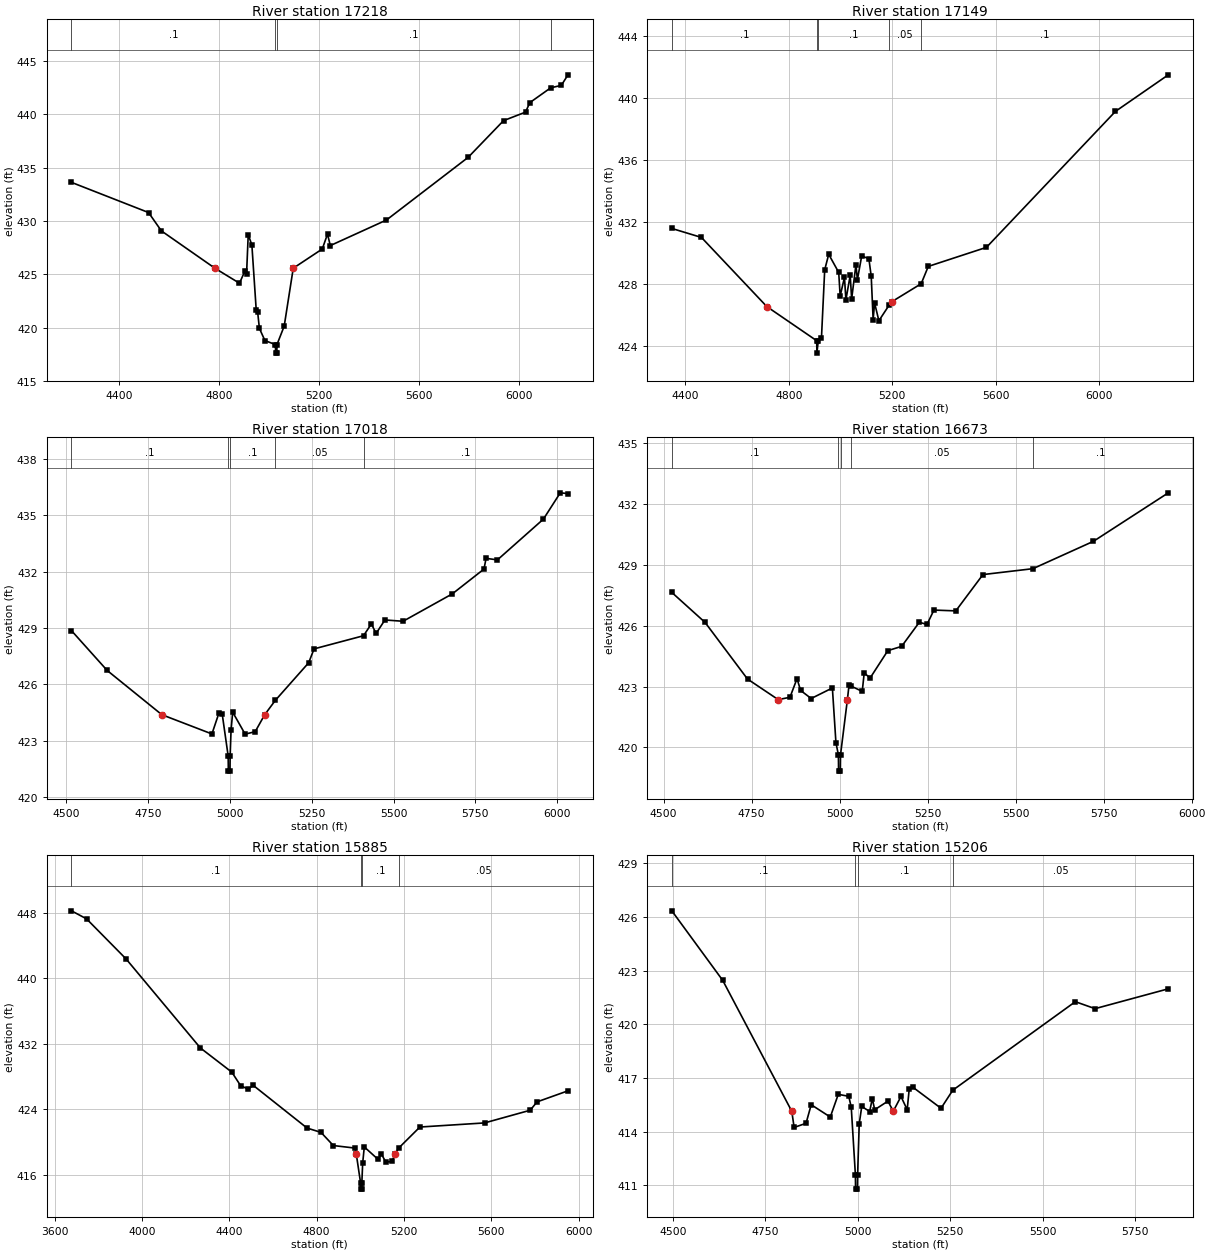
Type RM Length L Ch R = 1 ,17218   ,69,69,69
BEGIN DESCRIPTION:
UNT 181 SanMiguel Cr Watershed 37.0
END DESCRIPTION:
XS GIS Cut Line= 5
      2086977.95     13461579.58      2086708.53     13461170.15
      2086590.47     13460975.71      2086507.14     13460795.15
      2085489.62     13461122.38
#Sta/Elev= 30
  4210.4  433.62  4518.5  430.79  4569.8  429.07 4783.83425.5664    4882  424.16
  4904.6  425.34  4910.5  425.05  4917.1  428.72  4931.7  427.74  4949.1  421.63
  4954.7  421.46  4961.8  419.92  4983.8  418.78    5026   418.4  5026.5   417.6
  5031.5   417.6    5032   418.4  5060.9  420.13 5097.15425.5667  5213.2  427.37
  5234.1  428.77  5245.3  427.69  5469.9  430.09  5796.1  435.96  5937.9  439.41
  6025.9  440.21    6043   441.1  6126.5  442.49    6169  442.72  6195.7  443.71
#Mann= 4 ,-1 , 0
  4210.4      .1       0    5026     .07       0    5032      .1       0
  6126.5     .05       0
Bank Sta=4783.83,5097.15
XS Rating Curve= 0 ,0
Exp/Cntr=0.3,0.1

Type RM Length L Ch R = 1 ,17149   ,131,131,131
BEGIN DESCRIPTION:
UNT 181 SanMiguel Cr Watershed 36.0
END DESCRIPTION:
XS GIS Cut Line= 4
      2086977.93     13461451.08      2086659.92     13460961.82
      2086527.97     13460704.87      2085530.41     13461024.86
#Sta/Elev= 30
  4347.3  431.56  4461.9  430.98  4714.4  426.52  4907.7  424.31  4908.2  423.51
  4913.7  424.31  4925.9  424.47  4938.5  428.89    4954  429.89  4992.7  428.72
  4998.3   427.2  5014.9   428.4  5020.5  426.96  5037.1  428.53  5042.7  427.01
  5059.3  429.22  5064.9  428.25  5081.5  429.78  5109.3  429.61  5118.4  428.47
  5125.8  425.68  5131.4  426.75    5148   425.6  5186.9  426.59    5198  426.83
  5311.5  427.99  5339.1  429.11    5564  430.34  6062.9  439.12  6267.3  441.48
#Mann= 5 ,-1 , 0
  4347.3      .1       0  4907.7     .07       0  4913.7      .1       0
  5186.9     .05       0  5311.5      .1       0
Bank Sta=4714.4,5198
XS Rating Curve= 0 ,0
Exp/Cntr=0.3,0.1

Type RM Length L Ch R = 1 ,17018   ,345,345,345
BEGIN DESCRIPTION:
UNT 181 SanMiguel Cr Watershed 35.0
END DESCRIPTION:
XS GIS Cut Line= 4
       2086976.6     13461251.93        2086725.       13460825.
      2086610.73     13460637.81      2085832.12     13460832.68
#Sta/Elev= 30
  4515.6  428.85  4624.7  426.73 4791.69424.3755  4944.8  423.35  4966.2  424.46
  4976.1  424.43  4994.5  422.17    4995  421.37    5000  421.37  5000.5  422.17
  5003.3  423.56  5008.3  424.51  5046.3  423.34    5077  423.47 5106.15424.3756
  5138.7  425.14  5240.5  427.14    5257  427.88  5408.1  428.58  5432.2  429.21
  5446.6   428.7  5473.5  429.42    5529  429.35  5679.6  430.81  5776.3  432.13
  5782.7   432.7  5817.5  432.62    5958  434.79  6009.5  436.19  6033.1  436.15
#Mann= 5 ,-1 , 0
  4515.6      .1       0  4994.5     .07       0  5000.5      .1       0
  5138.7     .05       0  5408.1      .1       0
Bank Sta=4791.69,5106.15
XS Rating Curve= 0 ,0
Exp/Cntr=0.3,0.1

Type RM Length L Ch R = 1 ,16673   ,788,788,788
BEGIN DESCRIPTION:
UNT 181 SanMiguel Cr Watershed 34.0
END DESCRIPTION:
XS GIS Cut Line= 4
      2086980.09     13461179.03      2086931.48     13460676.22
      2086738.77     13460580.08      2086053.83     13460662.55
#Sta/Elev= 30
  4523.3  427.64  4617.8  426.16  4738.3  423.37 4825.52422.3554  4858.9  422.47
    4879  423.39    4889  422.81  4919.2  422.41  4979.4  422.93  4989.5  420.23
  4996.5  419.63    4997  418.83    5002  418.83  5002.5  419.63 5022.06422.3549
  5026.6  423.06  5032.8  423.02  5064.2  422.76  5069.8  423.67  5086.6  423.42
  5136.9  424.77  5176.1  424.98  5226.4  426.17  5248.2  426.06  5267.8  426.77
    5330  426.73  5407.1  428.52    5549  428.81    5721  430.16  5933.7  432.55
#Mann= 5 ,-1 , 0
  4523.3      .1       0  4996.5     .07       0  5002.5      .1       0
  5032.8     .05       0    5549      .1       0
Bank Sta=4825.52,5022.06
XS Rating Curve= 0 ,0
Exp/Cntr=0.3,0.1

Type RM Length L Ch R = 1 ,15885   ,679,679,679
BEGIN DESCRIPTION:
UNT 181 SanMiguel Cr Watershed 33.0
END DESCRIPTION:
XS GIS Cut Line= 4
       2087861.3     13461843.81      2087916.86      13461114.6
      2087222.42     13460357.65      2086729.69     13460204.98
#Sta/Elev= 30
  3676.9  448.21  3745.9  447.23  3927.2  442.33  4267.4  431.47  4411.3  428.52
  4451.6  426.87  4487.3  426.43  4508.3  426.93  4756.2  421.69  4819.7  421.17
  4876.4  419.56  4975.7  419.25 4981.26418.5632    5001  415.04  5001.5  414.24
  5006.5  414.24    5007  415.04  5010.8  417.42  5018.2  419.39  5081.7  417.86
  5095.9  418.55  5116.9  417.54  5145.2  417.62 5159.33418.5632  5176.8  419.28
  5272.9  421.82  5568.9  422.32  5778.2  423.87  5809.6  424.89  5951.3  426.24
#Mann= 4 ,-1 , 0
  3676.9      .1       0    5001     .07       0    5007      .1       0
  5176.8     .05       0
Bank Sta=4981.26,5159.33
XS Rating Curve= 0 ,0
Exp/Cntr=0.3,0.1

Type RM Length L Ch R = 1 ,15206   ,691,691,691
BEGIN DESCRIPTION:
UNT 181 SanMiguel Cr Watershed 32.0
END DESCRIPTION:
XS GIS Cut Line= 5
      2088110.96     13461014.09      2087992.45     13460642.96
      2087810.16     13460476.29      2087190.37     13460283.58
      2087135.68     13460266.66
#Sta/Elev= 30
  4497.1  426.35  4634.8  422.46 4821.55415.1425  4827.9  414.24  4860.1  414.47
  4874.1  415.51  4925.7  414.82  4947.3  416.09  4975.7  415.98  4982.4  415.37
  4993.6  411.59  4994.1  410.79  4999.1  410.79  4999.6  411.59    5004  414.45
  5010.8  415.41  5032.3  415.13  5039.2  415.85  5045.9  415.23  5081.7  415.71
    5096415.1425  5116.9  415.97  5133.7  415.23  5139.1  416.37  5149.6  416.48
  5225.2  415.31    5257  416.32  5588.5  421.27  5641.8  420.88    5840  421.99
#Mann= 4 ,-1 , 0
  4497.1      .1       0  4993.6     .07       0  4999.6      .1       0
    5257     .05       0
Bank Sta=4821.55,5096
XS Rating Curve= 0 ,0
Exp/Cntr=0.3,0.1

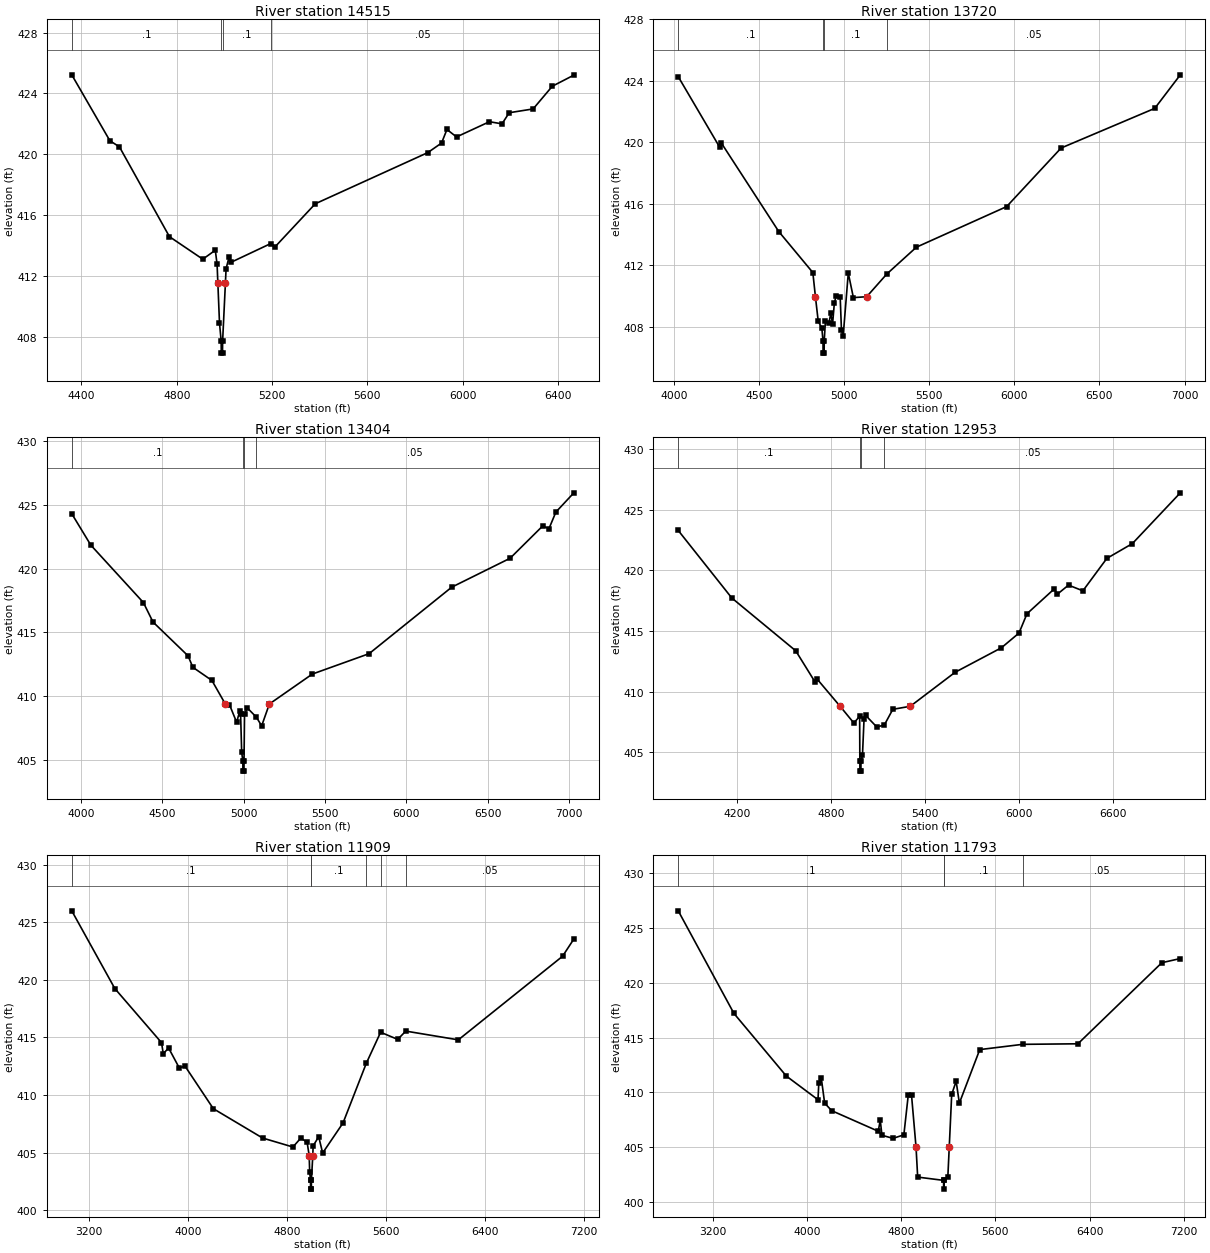
Type RM Length L Ch R = 1 ,14515   ,795,795,795
BEGIN DESCRIPTION:
UNT 181 SanMiguel Cr Watershed 31.0
END DESCRIPTION:
XS GIS Cut Line= 3
        2088325.     13460924.99        2088325.       13460325.
      2086824.98       13460175.
#Sta/Elev= 30
  4359.2  425.22  4519.2  420.89  4559.2  420.49  4769.2  414.59  4909.2  413.11
  4961.7   413.7  4969.2  412.77 4972.45411.5311  4979.3  408.92  4986.3  407.74
  4986.8  406.94  4991.9  406.94  4992.4  407.74  5004.1411.5318  5006.9  412.48
  5019.5  413.25  5029.5  412.92  5194.9  414.14    5213  413.93  5381.3  416.75
  5853.6  420.11  5911.4  420.74    5934  421.63  5974.2  421.14  6112.4  422.14
  6165.2     422  6195.3  422.73  6295.8  422.98  6376.2  424.47  6466.7   425.2
#Mann= 4 ,-1 , 0
  4359.2      .1       0  4986.3     .07       0  4992.4      .1       0
  5194.9     .05       0
Bank Sta=4972.45,5004.1
XS Rating Curve= 0 ,0
Exp/Cntr=0.3,0.1

Type RM Length L Ch R = 1 ,13720   ,316,316,316
BEGIN DESCRIPTION:
UNT 181 SanMiguel Cr Watershed 30.0
END DESCRIPTION:
XS GIS Cut Line= 3
      2089774.96     13460324.99        2088875.       13460025.
      2086875.04       13460025.
#Sta/Elev= 30
  4026.7  424.26  4269.1  419.69  4279.6  419.95  4616.9  414.19  4817.2  411.52
 4832.38409.9493  4848.8  408.35  4869.9  407.92  4876.9  407.08  4877.4  406.28
  4883.5  406.28  4884.1  407.08    4891  408.35  4912.1  408.26  4922.6  408.86
  4933.2  408.19  4943.7  409.56  4954.3     410  4977.8  409.94  4985.3  407.76
  4995.3  407.39  5025.3  411.49  5055.3  409.89 5133.41409.9492  5251.1  411.42
  5425.3  413.17  5955.3  415.81  6275.3  419.62  6825.3   422.2  6975.3  424.38
#Mann= 4 ,-1 , 0
  4026.7      .1       0  4876.9     .07       0  4884.1      .1       0
  5251.1     .05       0
Bank Sta=4832.38,5133.41
XS Rating Curve= 0 ,0
Exp/Cntr=0.3,0.1

Type RM Length L Ch R = 1 ,13404   ,451,451,451
BEGIN DESCRIPTION:
UNT 181 SanMiguel Cr Watershed 29.0
END DESCRIPTION:
XS GIS Cut Line= 3
      2089824.99       13460125.        2088825.       13459725.
        2086825.       13459925.
#Sta/Elev= 30
  3942.6  424.31  4059.7  421.85  4382.8  417.35  4442.1  415.82  4657.5  413.17
  4687.1  412.27  4804.2  411.24  4886.6409.3943  4911.9  409.35  4956.3  407.96
  4975.2  408.83  4980.6   408.6  4987.3   405.6  4994.5  404.93    4995  404.13
  5001.1  404.13  5001.7  404.93  5004.8   408.6  5022.1  409.08  5077.7  408.36
  5110.1  407.68  5157.6409.3941  5421.6  411.74  5770.9  413.34  6278.4  418.55
  6637.7  420.82  6838.7  423.36  6876.3  423.13  6919.1  424.44  7029.6  425.95
#Mann= 4 ,-1 , 0
  3942.6      .1       0  4994.5     .07       0  5001.7      .1       0
  5077.7     .05       0
Bank Sta=4886.6,5157.6
XS Rating Curve= 0 ,0
Exp/Cntr=0.3,0.1

Type RM Length L Ch R = 1 ,12953   ,1044,1044,1044
BEGIN DESCRIPTION:
UNT 181 SanMiguel Cr Watershed 28.0
END DESCRIPTION:
XS GIS Cut Line= 3
      2089824.97     13459974.98        2088825.       13459375.
      2086824.96     13459775.01
#Sta/Elev= 30
  3825.6  423.28  4167.6  417.72  4575.8  413.37  4700.2  410.78  4713.8  411.02
 4859.31408.7993    4947  407.42    4984  407.98  4985.2  404.26  4985.7  403.46
  4991.9  403.46  4992.5  404.26    5002  404.77  5012.1  407.78  5022.3  408.05
  5093.7  407.09    5142  407.27  5195.7  408.55 5307.21408.7993  5593.4   411.6
  5889.2  413.62  6001.4  414.83  6052.3  416.42  6225.7  418.46  6246.1  418.03
  6317.5  418.78  6409.3  418.31  6562.3  420.98  6725.4   422.2  7031.4  426.38
#Mann= 4 ,-1 , 0
  3825.6      .1       0  4985.2     .07       0  4992.5      .1       0
    5142     .05       0
Bank Sta=4859.31,5307.21
XS Rating Curve= 0 ,0
Exp/Cntr=0.3,0.1

Type RM Length L Ch R = 1 ,11909   ,116,116,116
BEGIN DESCRIPTION:
UNT 181 SanMiguel Cr Watershed 27.0
END DESCRIPTION:
XS GIS Cut Line= 5
       2090215.5     13459614.62      2088993.25     13458628.48
       2088500.2     13458482.65      2087944.64     13458350.71
      2086750.19     13459086.82
#Sta/Elev= 30
  3061.4     426  3409.3  419.25  3786.7  414.55  3801.1  413.59  3844.3  414.08
    3929  412.38  3978.6  412.48  4205.7  408.81    4604  406.26    4849  405.48
  4912.7  406.25  4963.7   405.9 4980.76404.7279  4984.6  403.27  4991.3  402.62
  4991.9  401.82  4998.2  401.82  4998.7  402.62 5009.76404.7266  5012.5  405.58
  5057.6  406.37  5089.5  404.96  5254.2  407.57  5442.2  412.75  5558.1  415.45
  5696.1  414.83  5761.5  415.55  6186.4  414.79  7028.6  422.05  7120.1  423.55
#Mann= 6 ,-1 , 0
  3061.4      .1       0  4991.3     .07       0  4998.7      .1       0
  5442.2     .05       0  5558.1      .1       0  5761.5     .05       0
Bank Sta=4980.76,5009.76
XS Rating Curve= 0 ,0
Exp/Cntr=0.3,0.1

Type RM Length L Ch R = 1 ,11793   ,197,197,197
BEGIN DESCRIPTION:
UNT 181 SanMiguel Cr Watershed 26.0
END DESCRIPTION:
XS GIS Cut Line= 5
      2090319.66     13459559.07      2089430.75     13458642.37
      2089222.42     13458586.82      2087993.25     13458204.87
      2086694.64      13458927.1
#Sta/Elev= 30
  2905.5  426.58  3378.4  417.21    3824  411.48  4092.8  409.32  4099.7  410.83
    4121  411.29  4149.3  409.01  4209.1  408.32  4604.8  406.44  4621.8  407.45
  4636.2  406.07  4730.4  405.79  4822.4  406.11  4860.2  409.79  4887.5  409.74
 4925.86404.9796  4939.8  402.25  5159.9  401.95  5160.5  401.15  5167.4  401.95
  5196.2   402.3 5207.96404.9799  5228.8  409.81  5266.6  411.01  5293.9  409.01
  5467.2   413.9  5831.3  414.38  6301.1  414.43  7014.3  421.84  7171.1  422.22
#Mann= 4 ,-1 , 0
  2905.5      .1       0  5159.9     .07       0  5167.4      .1       0
  5831.3     .05       0
Bank Sta=4925.86,5207.96
XS Rating Curve= 0 ,0
Exp/Cntr=0.3,0.1

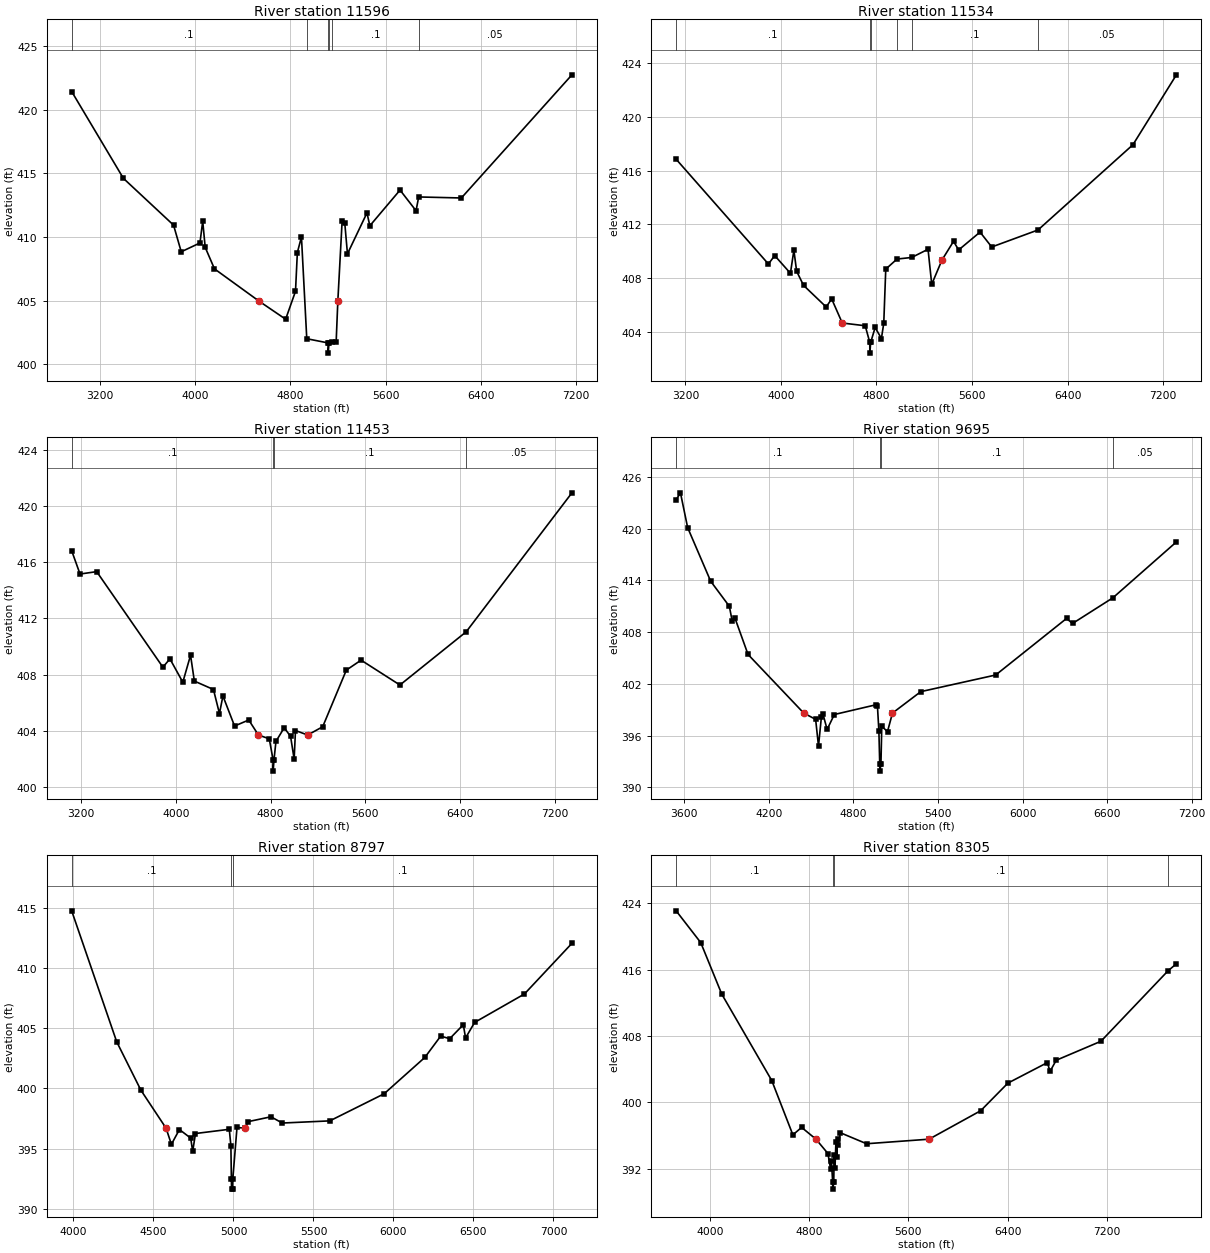
Type RM Length L Ch R = 1 ,11596   ,62,62,62
BEGIN DESCRIPTION:
UNT 181 SanMiguel Cr Watershed 25.0
END DESCRIPTION:
XS GIS Cut Line= 4
      2090382.15     13459274.32      2089041.86     13458315.98
       2088125.2     13458065.98      2086682.05     13458780.62
#Sta/Elev= 30
  2959.7  421.41  3394.8   414.6  3816.7  410.93  3881.3  408.84  4038.6  409.53
    4062  411.24  4082.8  409.19  4160.9   407.5 4535.88404.9677  4759.6  403.55
  4842.5  405.74  4858.1  408.78  4892.6     410  4937.3  402.02  5116.9  401.69
  5117.5  400.89  5124.4  401.69  5153.5  401.79  5184.6  401.79 5198.58404.9656
  5234.7  411.25  5257.1  411.08  5279.6  408.68  5443.7  411.89  5467.9  410.88
  5721.9  413.68  5856.5  412.06  5878.8  413.14  6237.7  413.06  7167.9  422.72
#Mann= 6 ,-1 , 0
  2959.7      .1       0  4937.3     .05       0  5116.9    .033       0
  5124.4     .05       0  5153.5      .1       0  5878.8     .05       0
Bank Sta=4535.88,5198.58
XS Rating Curve= 0 ,0
Exp/Cntr=0.3,0.1

Type RM Length L Ch R = 1 ,11534   ,81,81,81
BEGIN DESCRIPTION:
UNT 181 SanMiguel Cr Watershed 24.0
END DESCRIPTION:
XS GIS Cut Line= 5
      2090396.06      13458878.5      2088944.64     13458218.76
      2088409.92     13458086.82      2087951.59     13457906.26
      2086639.58     13458732.34
#Sta/Elev= 30
  3122.7  416.85  3895.3  409.04  3947.7  409.67  4079.5  408.35  4108.4  410.07
  4131.5   408.5  4189.4  407.45  4378.7  405.84  4424.8  406.44 4513.56 404.644
  4705.6  404.44  4743.8   403.2  4744.4   402.4  4751.3   403.2  4788.8  404.31
  4841.2  403.49  4860.9  404.63  4877.6  408.66  4971.6  409.41  5094.8  409.53
  5231.6  410.14  5262.5  407.53  5348.3  409.34  5444.9  410.73    5488  410.09
  5666.9  411.42  5764.8  410.31  6152.6  411.58  6946.9  417.93  7310.8  423.14
#Mann= 6 ,-1 , 0
  3122.7      .1       0  4743.8    .033       0  4751.3      .1       0
  4971.6     .05       0  5094.8      .1       0  6152.6     .05       0
Bank Sta=4513.56,5348.3
XS Rating Curve= 0 ,0
Exp/Cntr=0.3,0.1

Type RM Length L Ch R = 1 ,11453   ,1758,1758,1758
BEGIN DESCRIPTION:
UNT 181 SanMiguel Cr Watershed 23.0
END DESCRIPTION:
XS GIS Cut Line= 5
      2090382.14     13458843.76      2089215.47     13458197.93
      2088548.81     13458038.21      2087930.75     13457690.98
      2086743.69     13458600.37
#Sta/Elev= 30
  3120.2  416.82  3190.6  415.16  3331.4  415.33  3890.2  408.53  3949.7  409.12
  4058.5  407.46  4123.8  409.38  4155.8  407.54  4317.1  406.94  4367.7  405.23
  4397.1  406.48  4495.3  404.34    4615  404.77 4696.72403.7007  4788.3  403.43
  4820.6  401.93  4821.2  401.13  4828.1  401.93  4844.9  403.25  4914.4  404.22
  4968.3   403.6  4998.4  401.98  5009.5  404.02 5112.72403.7007  5239.4  404.29
  5438.9  408.32  5563.3  409.03  5891.4  407.26    6451  411.05  7343.5  420.94
#Mann= 4 ,-1 , 0
  3120.2      .1       0  4820.6     .07       0  4828.1      .1       0
    6451     .05       0
Bank Sta=4696.72,5112.72
XS Rating Curve= 0 ,0
Exp/Cntr=0.3,0.1

Type RM Length L Ch R = 1 ,9695    ,898,898,898
BEGIN DESCRIPTION:
UNT 181 SanMiguel Cr Watershed 22.0
END DESCRIPTION:
XS GIS Cut Line= 3
        2089875.       13456625.        2088375.       13456925.
      2086874.96     13458275.03
#Sta/Elev= 30
  3543.6  423.34  3574.2  424.14  3625.2  420.11  3788.4   413.9  3920.9  410.99
  3941.3  409.27  3961.7  409.58  4053.5  405.41 4448.54398.6161  4532.8  397.89
  4553.2   394.8  4573.6  398.14  4583.8  398.56  4614.4  396.72  4665.4  398.45
  4961.1  399.58  4971.3  399.41  4981.5  396.53  4987.5  392.69  4988.2  391.89
    4996  392.69  5001.9  397.07  5042.7  396.48 5077.79 398.616  5278.5   401.1
  5809.9  403.03  6312.2  409.58  6354.8     409  6641.5  411.98  7091.4  418.45
#Mann= 4 ,-1 , 0
  3543.6      .1       0  4987.5     .07       0    4996      .1       0
  6641.5     .05       0
Bank Sta=4448.54,5077.79
XS Rating Curve= 0 ,0
Exp/Cntr=0.3,0.1

Type RM Length L Ch R = 1 ,8797    ,492,492,492
BEGIN DESCRIPTION:
UNT 181 SanMiguel Cr Watershed 21.0
END DESCRIPTION:
XS GIS Cut Line= 3
      2089574.97       13456375.        2088575.       13456275.
      2087074.98     13457775.02
#Sta/Elev= 30
  3989.1  414.76  4270.5  403.88  4421.2  399.87 4579.26396.6973  4612.2  395.36
  4662.4  396.59  4732.8  395.88  4745.3  394.78  4762.9  396.26    4974  396.61
    4984  395.26  4987.3  392.44    4988  391.64    4995  391.64  4995.8  392.44
  5022.3  396.77 5070.48396.6974  5093.1  397.25  5234.5  397.65  5305.2  397.13
  5602.2  397.31  5941.6  399.56  6196.1  402.58  6295.1  404.35  6351.7  404.14
  6436.6   405.3  6450.7   404.2  6507.3  405.49  6818.4  407.85  7115.4  412.06
#Mann= 3 ,-1 , 0
  3989.1      .1       0  4987.3     .07       0  4995.8      .1       0
Bank Sta=4579.26,5070.48
XS Rating Curve= 0 ,0
Exp/Cntr=0.3,0.1

Type RM Length L Ch R = 1 ,8305    ,364,364,364
BEGIN DESCRIPTION:
UNT 181 SanMiguel Cr Watershed 20.0
END DESCRIPTION:
XS GIS Cut Line= 3
      2089575.02     13454974.98        2088575.       13455875.
      2086775.01     13457874.99
#Sta/Elev= 30
  3726.4  423.09  3924.9  419.26  4094.5  413.05  4498.1  402.63  4668.2  396.09
  4738.8  396.99 4854.53395.5687  4951.1  393.84  4972.8  391.94  4979.5  392.96
  4989.3  390.35  4990.1  389.55    4998  390.35  5001.2  393.72  5007.9  392.09
  5015.4  395.17  5022.1  393.42  5029.6  395.65  5036.3  394.92  5050.5  396.35
  5262.8  395.02 5766.87395.5688  6183.6     399  6403.3  402.33  6721.7   404.8
  6742.7  403.73  6792.7  405.08  7153.7  407.37  7694.4  415.85  7762.5  416.71
#Mann= 4 ,-1 , 0
  3726.4      .1       0  4989.3     .07       0    4998      .1       0
  7694.4     .05       0
Bank Sta=4854.53,5766.87
XS Rating Curve= 0 ,0
Exp/Cntr=0.3,0.1

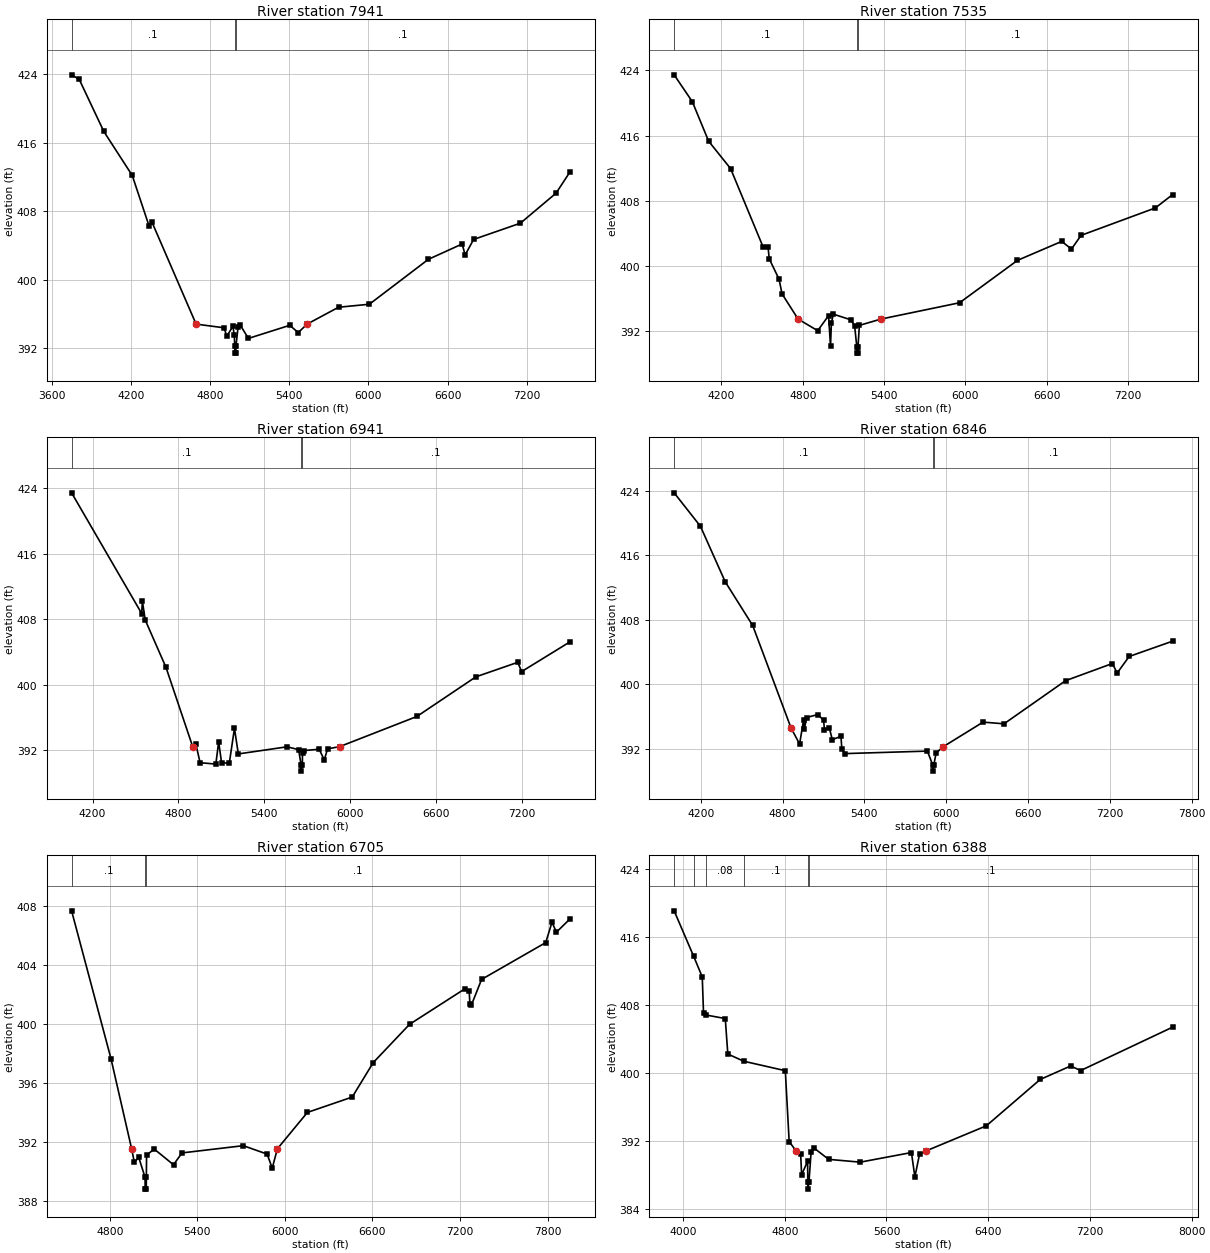
Type RM Length L Ch R = 1 ,7941    ,406,406,406
BEGIN DESCRIPTION:
UNT 181 SanMiguel Cr Watershed 19.0
END DESCRIPTION:
XS GIS Cut Line= 3
      2089475.02     13454874.99        2088475.       13455575.
      2086875.02     13457574.98
#Sta/Elev= 30
  3748.2  423.95  3806.2  423.42  3992.4  417.34  4208.2   412.2  4336.3  406.28
  4358.6  406.72 4692.73394.8294  4904.8   394.4  4925.7  393.42  4972.1  394.58
  4982.5  393.53  4985.9  392.24  4986.8  391.44  4994.2  391.44    4995  392.24
  5011.3  394.51  5025.7  394.76  5089.7  393.16  5403.5  394.69  5467.5  393.84
  5534.8394.8294  5773.3   396.8    6007  397.15  6455.2   402.4  6711.3  404.19
  6733.7   402.9  6797.8  404.72  7153.1  406.62  7423.7  410.13  7530.1  412.63
#Mann= 3 ,-1 , 0
  3748.2      .1       0  4985.9     .07       0    4995      .1       0
Bank Sta=4692.73,5534.8
XS Rating Curve= 0 ,0
Exp/Cntr=0.3,0.1

Type RM Length L Ch R = 1 ,7535    ,594,594,594
BEGIN DESCRIPTION:
UNT 181 SanMiguel Cr Watershed 18.0
END DESCRIPTION:
XS GIS Cut Line= 3
      2089375.04     13454774.98        2088375.       13455275.
      2086775.02     13457274.98
#Sta/Elev= 30
  3850.8  423.46    3985  420.16  4105.2  415.31  4267.3  411.94  4507.7  402.29
    4544  402.29  4552.4  400.86  4625.1  398.34  4647.4  396.53 4765.83393.4409
  4910.2  392.02  4990.5  393.86  5004.9  390.11  5011.3  392.96  5025.7  394.05
  5153.8  393.36  5182.6  392.65  5198.8  390.06  5199.7  389.26  5207.1  389.26
  5207.9  390.06  5217.8  392.67 5376.12393.4411  5957.4  395.45  6384.8  400.66
  6711.3  402.99  6783.4  402.05  6853.8  403.73  7402.1   407.1  7530.1  408.75
#Mann= 3 ,-1 , 0
  3850.8      .1       0  5198.8     .07       0  5207.9      .1       0
Bank Sta=4765.83,5376.12
XS Rating Curve= 0 ,0
Exp/Cntr=0.3,0.1

Type RM Length L Ch R = 1 ,6941    ,95,95,95
BEGIN DESCRIPTION:
UNT 181 SanMiguel Cr Watershed 17.0
END DESCRIPTION:
XS GIS Cut Line= 5
       2089361.3     13454711.82      2088639.09     13454843.76
      2088319.64     13454843.76      2088139.09     13455121.54
        2087029.     13456904.61
#Sta/Elev= 30
  4053.7  423.45  4543.7  408.72  4548.7  410.22  4568.4  407.93  4713.5  402.15
 4900.37392.4668    4922  392.82    4952  390.51    5062  390.34    5082  393.05
    5102  390.53  5156.1  390.42  5192.3   394.7  5219.4  391.58  5560.5  392.45
    5641   392.1  5657.7  390.28  5658.6  389.48  5666.8  390.28  5668.2  391.71
  5677.6  391.99  5784.3  392.15  5820.4  390.86  5843.2   392.2  5927.4392.4668
  6467.5  396.15  6880.3  400.99    7173  402.76  7200.1  401.63    7539  405.27
#Mann= 3 ,-1 , 0
  4053.7      .1       0  5657.7     .07       0  5666.8      .1       0
Bank Sta=4900.37,5927.4
XS Rating Curve= 0 ,0
Exp/Cntr=0.3,0.1

Type RM Length L Ch R = 1 ,6846    ,141,141,141
BEGIN DESCRIPTION:
UNT 181 SanMiguel Cr Watershed 16.0
END DESCRIPTION:
XS GIS Cut Line= 5
      2089396.06     13454670.15      2088541.86     13454781.26
      2088340.47     13454732.65      2088222.42     13454871.54
      2086986.31     13456934.04
#Sta/Elev= 30
  4005.3  423.73    4198  419.59  4379.5  412.72  4581.2   407.3  4862.6   394.6
  4925.2  392.62  4954.1  395.56  4959.3  394.42  4976.6   395.9  5058.9  396.27
  5101.1  395.56  5107.6  394.38  5142.7  394.65  5164.8  393.17  5228.4  393.56
    5235  392.02  5255.1  391.43  5862.2  391.74  5900.5  390.06  5901.3  389.26
  5909.6  390.06  5926.4  391.51 5979.85392.3005  6270.5  395.33  6424.1  395.12
  6875.1  400.46  7218.8  402.59  7253.8  401.41  7341.7  403.46  7660.7  405.36
#Mann= 3 ,-1 , 0
  4005.3      .1       0  5900.5     .07       0  5909.6      .1       0
Bank Sta=4862.6,5979.85
XS Rating Curve= 0 ,0
Exp/Cntr=0.3,0.1

Type RM Length L Ch R = 1 ,6705    ,317,317,317
BEGIN DESCRIPTION:
UNT 181 SanMiguel Cr Watershed 15.0
END DESCRIPTION:
XS GIS Cut Line= 3
      2088824.96       13454625.        2088325.       13454625.
      2086825.02     13457124.97
#Sta/Elev= 30
    4539  407.65    4809  397.64 4950.16 391.553    4969  390.63    4999  390.97
  5042.2  389.62    5043  388.82  5050.4  388.82  5051.3  389.62  5052.6  391.12
    5105  391.53  5237.2  390.47  5295.5  391.27  5715.3  391.76  5878.6  391.19
  5913.6  390.24 5949.09 391.553  6154.6  394.01  6461.7  395.05  6605.5  397.38
  6854.3  399.97  7231.4  402.36  7262.5  402.24  7268.3  401.34    7278  401.27
    7348  403.01  7787.3   405.5    7830  406.87  7861.1  406.21  7954.4  407.11
#Mann= 3 ,-1 , 0
    4539      .1       0  5042.2     .07       0  5051.3      .1       0
Bank Sta=4950.16,5949.09
XS Rating Curve= 0 ,0
Exp/Cntr=0.3,0.1

Type RM Length L Ch R = 1 ,6388    ,452,452,452
BEGIN DESCRIPTION:
UNT 181 SanMiguel Cr Watershed 14.0
END DESCRIPTION:
XS GIS Cut Line= 3
        2089225.       13454425.        2088225.       13454325.
      2086724.98     13456825.03
#Sta/Elev= 30
  3930.1  419.03    4084  413.67  4151.2  411.26  4161.2  406.97  4182.5  406.78
  4332.1  406.37  4352.2   402.2  4477.9  401.35  4804.4  400.24  4834.6  391.91
 4889.43390.8047    4925  390.45  4932.6  387.99  4979.8  389.62    4981  387.12
  4981.9  386.32  4990.2  387.12    5007  390.64  5028.4  391.17    5145  389.82
  5393.8  389.49  5796.1  390.62  5823.3  387.76  5860.3  390.46 5910.27390.8048
  6385.1  393.76  6808.8  399.21  7047.8  400.79  7127.5  400.26  7850.6  405.36
#Mann= 6 ,-1 , 0
  3930.1      .1       0    4084     .05       0  4182.5     .08       0
  4477.9      .1       0    4981     .07       0  4990.2      .1       0
Bank Sta=4889.43,5910.27
XS Rating Curve= 0 ,0
Exp/Cntr=0.3,0.1