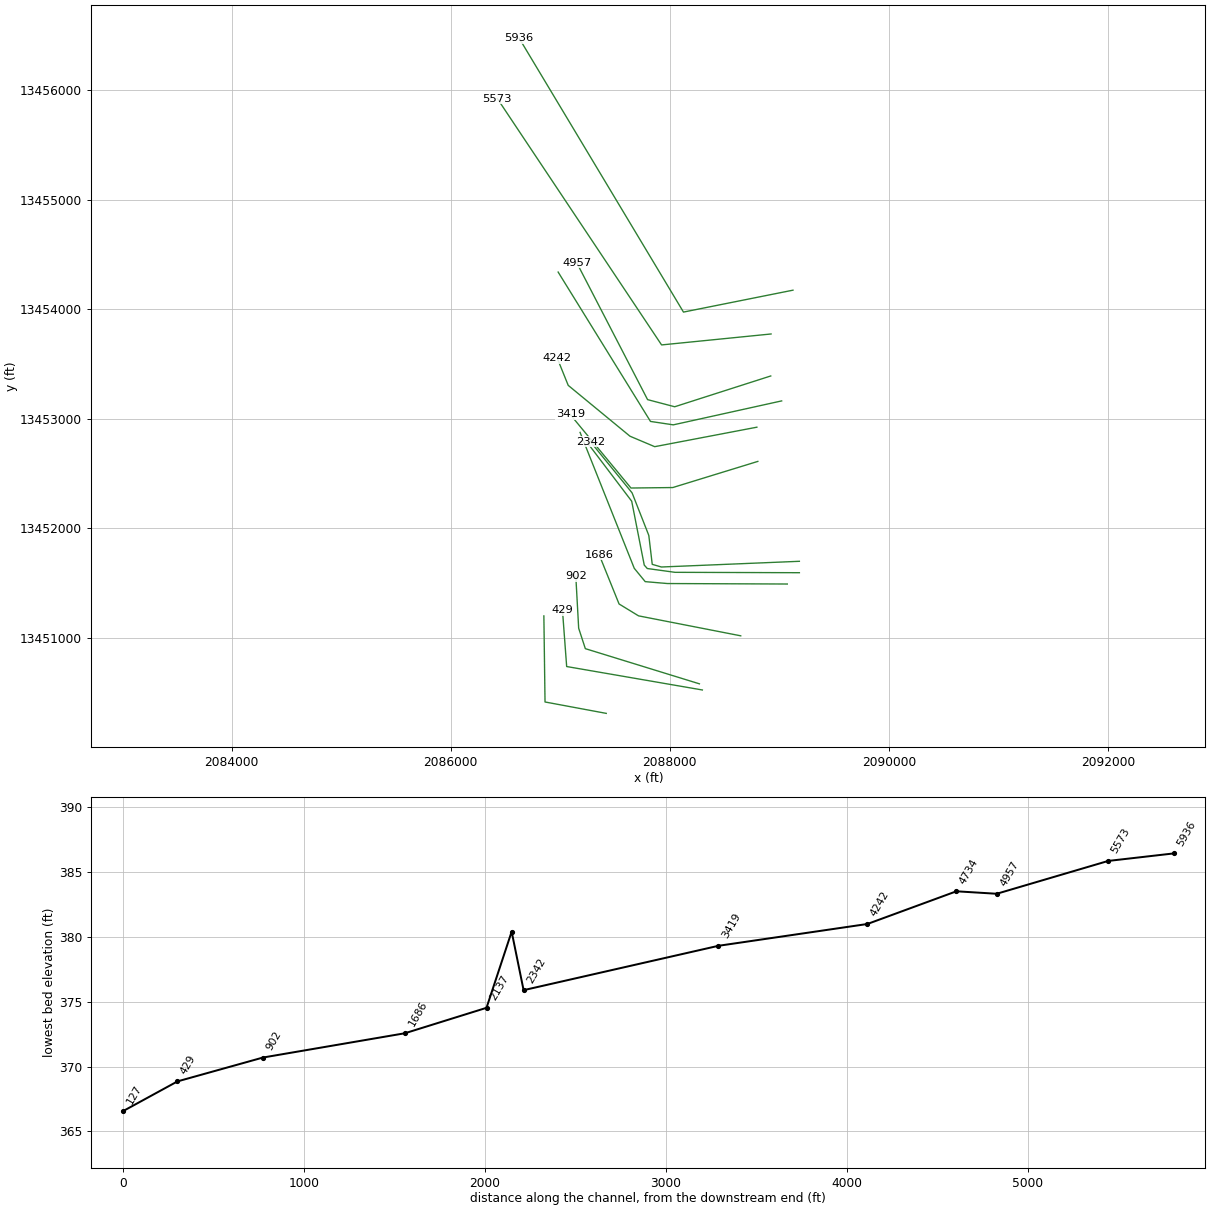
HEC-RAS study UNT 181 SanMiguel Cr Watershed.prj: UNT 181 SanMiguel Cr Watershed Base Level Engineering

--- UNT 181 SanMiguel Cr Watershed.g01 (geometry) --- (continued)

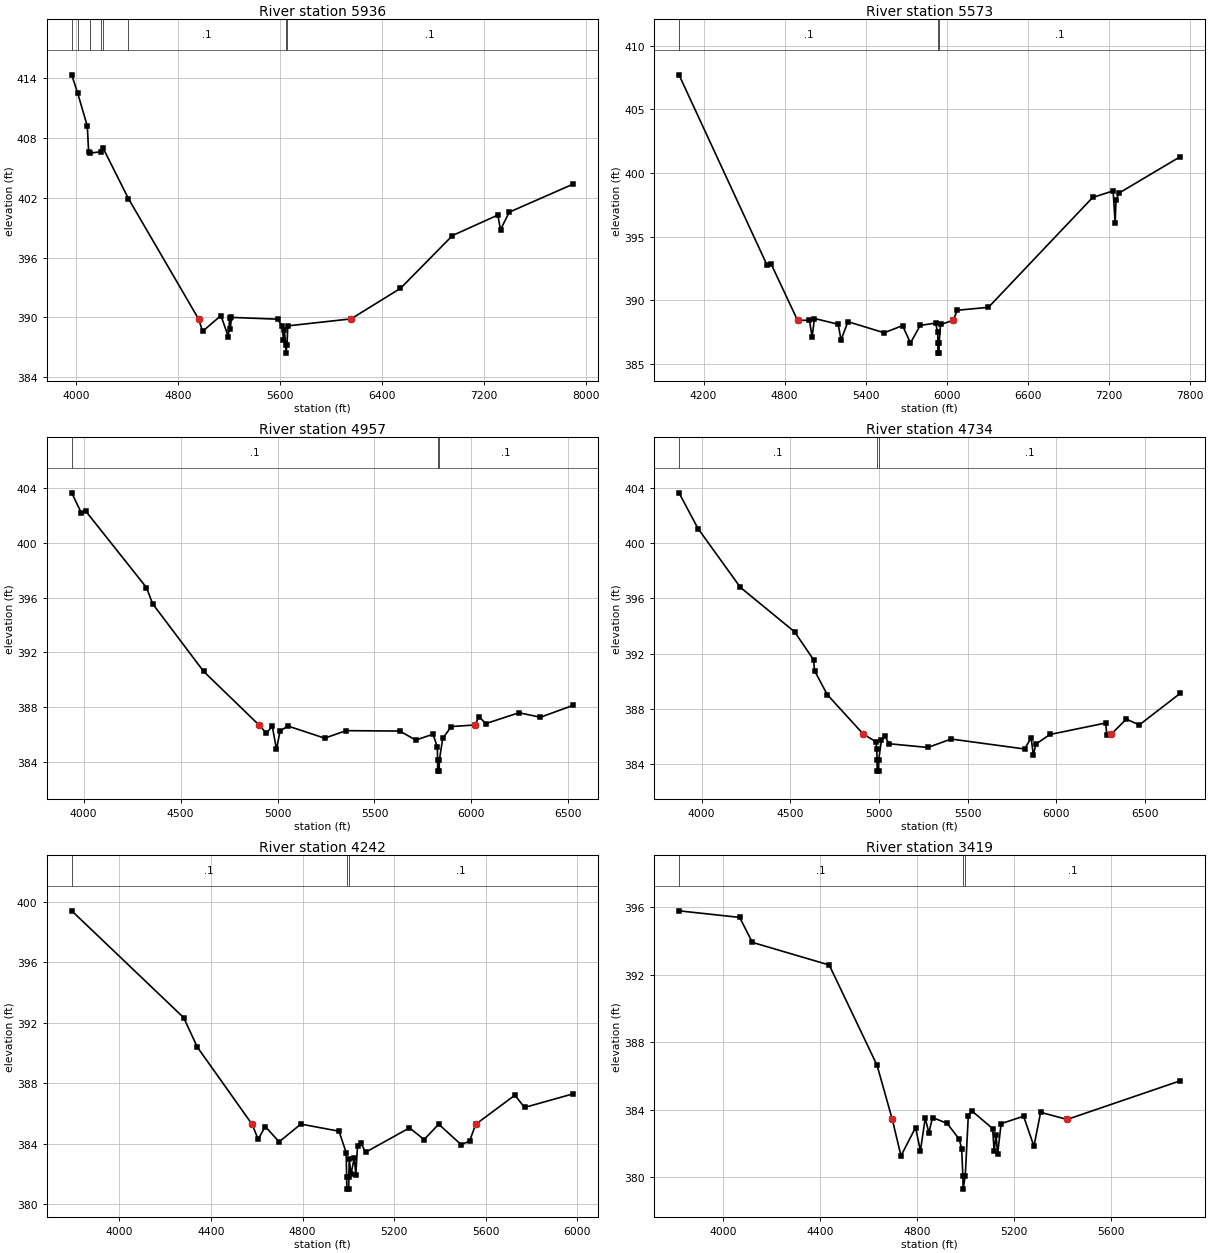
Type RM Length L Ch R = 1 ,5936    ,363,363,363
BEGIN DESCRIPTION:
UNT 181 SanMiguel Cr Watershed 13.0
END DESCRIPTION:
XS GIS Cut Line= 3
      2089124.98       13454175.        2088125.       13453975.
      2086624.98     13456475.03
#Sta/Elev= 30
  3963.8  414.31  4010.3  412.48  4086.2  409.17  4096.4  406.55  4109.9  406.47
  4195.6  406.61  4209.6  406.98  4408.8  401.91 4958.85389.8618  4991.4  388.62
  5135.2  390.19  5193.5  388.04  5203.2  389.96    5209  388.83  5216.8  390.01
  5580.3  389.83  5617.2  389.11    5625  387.71  5632.8  388.71  5643.7  387.23
  5644.6  386.43  5652.9  387.23    5660  389.16 6156.47 389.862  6544.3  392.92
  6952.5  398.21  7308.2  400.26  7329.6  398.79  7397.6  400.55  7899.1  403.36
#Mann= 8 ,-1 , 0
  3963.8      .1       0  4010.3     .08       0  4109.9     .05       0
  4195.6      .1       0  4209.6     .05       0  4408.8      .1       0
  5643.7     .07       0  5652.9      .1       0
Bank Sta=4958.85,6156.47
XS Rating Curve= 0 ,0
Exp/Cntr=0.3,0.1

Type RM Length L Ch R = 1 ,5573    ,616,616,616
BEGIN DESCRIPTION:
UNT 181 SanMiguel Cr Watershed 12.0
END DESCRIPTION:
XS GIS Cut Line= 3
      2088925.04       13453775.        2087925.       13453675.
      2086424.99     13455925.01
#Sta/Elev= 30
  4018.6  407.72  4669.4  392.78    4702  392.82 4895.79388.4277  4983.4  388.43
  5003.5  387.14  5021.1  388.57  5196.4  388.12  5217.4  386.88  5268.5  388.32
  5535.9  387.45  5672.6  388.01  5731.2  386.65  5803.3  388.03  5917.5  388.21
  5932.5  387.48  5933.9  386.65  5934.8  385.85  5942.3  385.85  5943.1  386.65
  5953.6   388.1 6048.24388.4276  6076.7  389.22  6308.1  389.45  7078.8  398.08
  7230.5   398.6  7245.5  396.06  7251.6  397.85  7272.6  398.42  7727.8  401.29
#Mann= 3 ,-1 , 0
  4018.6      .1       0  5933.9     .07       0  5943.1      .1       0
Bank Sta=4895.79,6048.24
XS Rating Curve= 0 ,0
Exp/Cntr=0.3,0.1

Type RM Length L Ch R = 1 ,4957    ,223,223,223
BEGIN DESCRIPTION:
UNT 181 SanMiguel Cr Watershed 11.0
END DESCRIPTION:
XS GIS Cut Line= 4
      2088922.03     13453391.49       2088044.6     13453110.31
       2087797.2     13453175.42      2087150.49     13454425.43
#Sta/Elev= 30
  3939.2  403.67  3988.6   402.2  4012.2  402.32  4324.6  396.74  4356.1  395.56
  4618.6  390.62  4904.5386.6943    4943  386.09    4973  386.61  4994.6  384.92
  5013.3  386.25  5053.6  386.62  5243.2  385.73  5353.9  386.28  5630.4  386.25
  5712.7  385.59  5801.9  386.02  5824.1  385.08  5825.1  384.12  5825.9  383.32
  5833.4  383.32  5834.3  384.12  5851.8  385.72  5896.1  386.58 6017.86386.6945
  6039.2  387.31  6073.2  386.79  6244.7  387.59  6355.4  387.26  6523.8  388.13
#Mann= 3 ,-1 , 0
  3939.2      .1       0  5825.1     .07       0  5834.3      .1       0
Bank Sta=4904.5,6017.86
XS Rating Curve= 0 ,0
Exp/Cntr=0.3,0.1

Type RM Length L Ch R = 1 ,4734    ,492,492,492
BEGIN DESCRIPTION:
UNT 181 SanMiguel Cr Watershed 10.0
END DESCRIPTION:
XS GIS Cut Line= 4
       2089021.7     13453163.79       2088032.1     13452945.04
      2087823.76     13452976.29      2086980.29     13454340.42
#Sta/Elev= 30
  3872.2  403.63  3979.4  401.05  4218.1   396.8  4524.3  393.58  4631.4  391.56
  4636.9  390.77  4708.6  389.04 4911.67386.1856  4982.7  385.64  4987.8  385.09
  4989.3  384.31  4990.2  383.51  4997.7  383.51  4998.6  384.31  5014.2  385.76
  5034.4  386.02  5056.9  385.49  5275.9  385.22  5407.1  385.83    5822  385.11
  5858.6  385.93  5870.8  384.68  5885.8  385.47    5965  386.16  6279.4  386.99
  6285.3  386.11 6310.82386.1855  6395.3  387.27  6468.6  386.85  6700.2  389.14
#Mann= 3 ,-1 , 0
  3872.2      .1       0  4989.3     .07       0  4998.6      .1       0
Bank Sta=4911.67,6310.82
XS Rating Curve= 0 ,0
Exp/Cntr=0.3,0.1

Type RM Length L Ch R = 1 ,4242    ,823,823,823
BEGIN DESCRIPTION:
UNT 181 SanMiguel Cr Watershed 9.0
END DESCRIPTION:
XS GIS Cut Line= 5
      2088795.46     13452923.68      2087862.31     13452745.73
      2087636.61     13452841.22      2087072.38     13453305.63
      2086973.14     13453551.55
#Sta/Elev= 30
  3791.5  399.39  4280.6  392.33  4340.8  390.37 4579.77385.2749  4606.4  384.28
  4636.9  385.13    4698  384.12  4792.8  385.29  4959.4  384.82  4990.8  383.41
  4992.8  381.79  4993.7  380.99  5001.7  380.99  5002.7  381.79  5004.2  382.95
  5012.1  381.98  5026.4  383.08  5032.9  381.92  5040.4  383.83  5053.7  384.07
  5075.9  383.43  5267.5  385.04  5331.3  384.27  5395.2  385.28  5494.2  383.92
  5530.7  384.18 5556.86385.2748  5728.2   387.2  5770.6  386.39  5982.5  387.29
#Mann= 3 ,-1 , 0
  3791.5      .1       0  4992.8     .07       0  5002.7      .1       0
Bank Sta=4579.77,5556.86
XS Rating Curve= 0 ,0
Exp/Cntr=0.3,0.1

Type RM Length L Ch R = 1 ,3419    ,1077,1077,1077
BEGIN DESCRIPTION:
UNT 181 SanMiguel Cr Watershed 8.0
END DESCRIPTION:
XS GIS Cut Line= 4
       2088804.1     13452611.17      2088027.24     13452372.47
      2087645.29     13452368.13      2087090.22     13453040.28
#Sta/Elev= 30
  3819.5   395.8  4069.6  395.41  4121.9  393.93  4438.7  392.59  4635.8  386.65
 4698.61383.4395  4734.5  381.28  4794.5  382.96  4814.5  381.58  4834.5  383.51
  4849.4  382.65  4864.5  383.55  4924.5  383.21  4974.5  382.27  4984.5  381.71
  4989.5  380.11  4990.5  379.31  4999.5  380.11  5011.8  383.63    5026  383.95
  5112.1   382.9  5118.5  381.56  5126.4  382.52  5132.9  381.41  5147.2  383.19
  5239.7  383.63  5282.5  381.85    5310  383.86 5419.27383.4394  5885.9  385.73
#Mann= 3 ,-1 , 0
  3819.5      .1       0  4989.5     .07       0  4999.5      .1       0
Bank Sta=4698.61,5419.27
XS Rating Curve= 0 ,0
Exp/Cntr=0.3,0.1

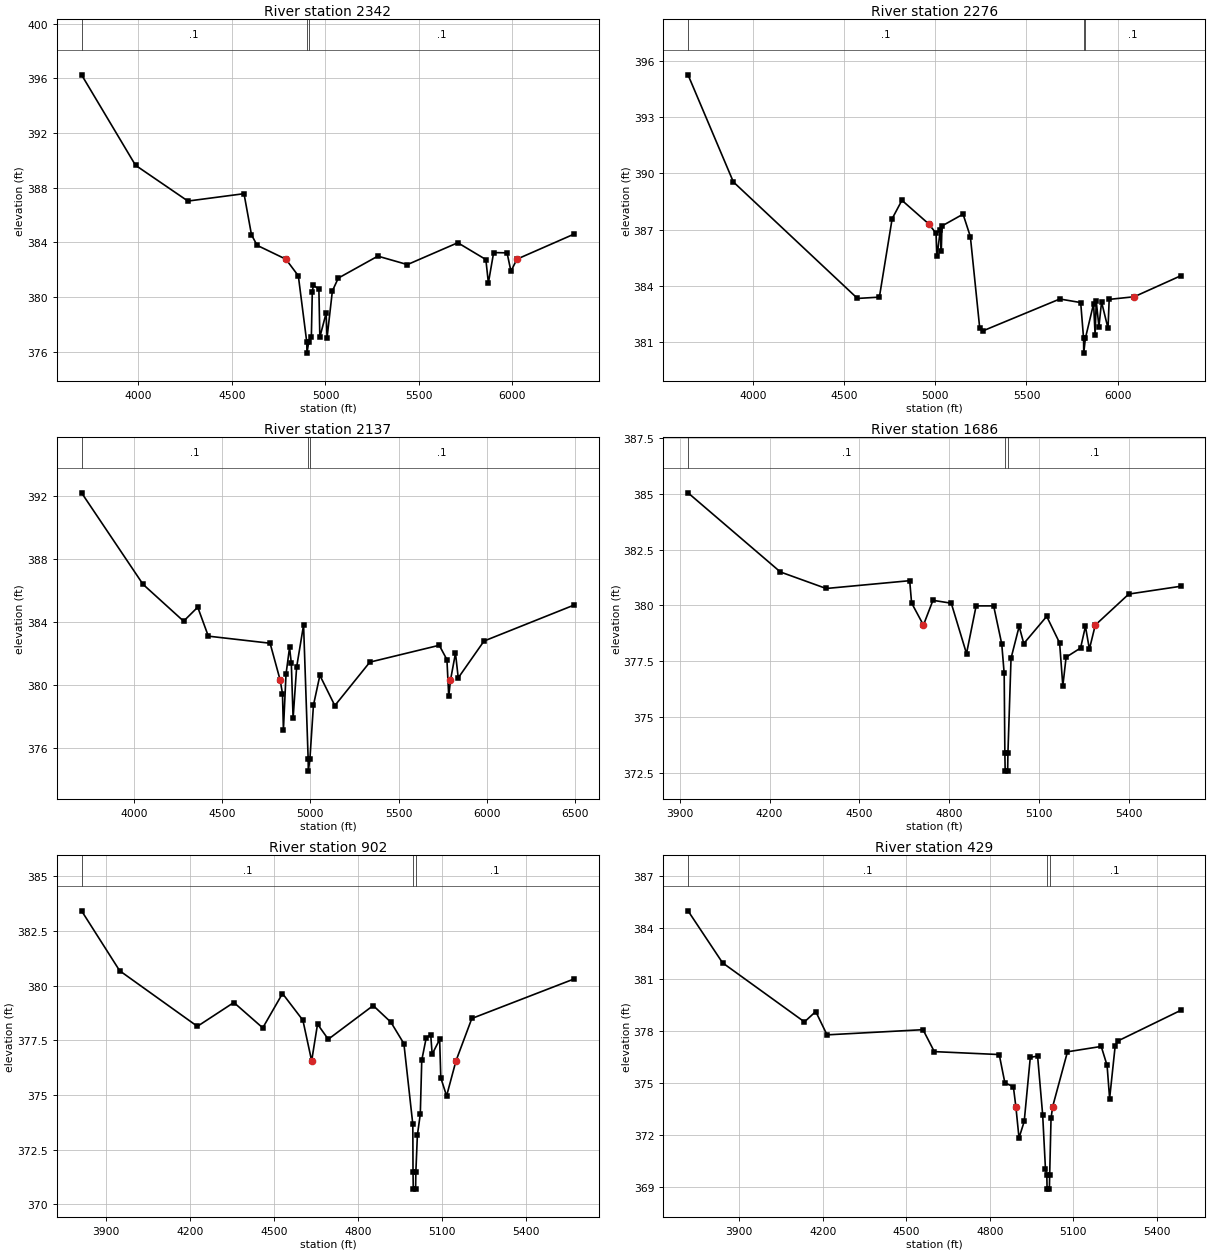
Type RM Length L Ch R = 1 ,2342    ,66,66,66
BEGIN DESCRIPTION:
UNT 181 SanMiguel Cr Watershed 7.0
END DESCRIPTION:
XS GIS Cut Line= 6
       2089183.5     13451698.86      2087923.07     13451646.77
      2087839.74     13451671.08      2087808.49     13451934.97
      2087655.71     13452323.86      2087274.82     13452791.31
#Sta/Elev= 30
  3695.5  396.26  3984.1  389.64  4264.3  387.02  4564.4  387.56  4604.4  384.55
  4634.5  383.78 4788.22 382.767  4854.9  381.55  4900.1  376.69    4901  375.89
  4910.3  376.69  4924.6   377.1  4929.6   380.4  4935.4  380.84  4964.8  380.59
    4970  377.06  5003.5  378.81  5008.7  377.03    5037  380.44  5068.5  381.38
  5280.1  382.99  5438.3  382.37  5707.8  383.97  5857.9  382.74  5871.4  381.03
  5899.5  383.25  5971.3  383.23  5992.1  381.88 6023.96382.7673    6331  384.61
#Mann= 3 ,-1 , 0
  3695.5      .1       0  4900.1     .07       0  4910.3      .1       0
Bank Sta=4788.22,6023.96
XS Rating Curve= 0 ,0
Exp/Cntr=0.3,0.1

Type RM Length L Ch R = 1 ,2276    ,139,139,139
BEGIN DESCRIPTION:
UNT 181 SanMiguel Cr Watershed 6.0
END DESCRIPTION:
XS GIS Cut Line= 6
      2089183.53     13451594.69      2088048.07     13451598.16
       2087794.6     13451632.88      2087766.82     13451664.13
      2087652.24     13452247.47      2087249.72     13452778.37
#Sta/Elev= 30
  3645.5  395.26    3894  389.54    4574  383.32    4694  383.39    4764  387.58
  4817.5  388.56  4964.3   387.3  5004.4   386.8  5009.9  385.56  5027.8  386.98
  5033.3  385.87  5036.9  387.19  5152.5  387.82  5192.5  386.62  5243.5  381.76
  5264.1   381.6  5682.6  383.29    5797   383.1  5812.7   381.2  5813.7   380.4
  5822.9   381.2  5867.7  383.04    5876  381.38  5882.3  383.16  5896.9  381.82
  5911.4  383.13  5946.8  381.72  5953.1  383.27  6090.2  383.41  6345.4  384.53
#Mann= 3 ,-1 , 0
  3645.5      .1       0  5812.7     .07       0  5822.9      .1       0
Bank Sta=4964.3,6090.2
XS Rating Curve= 0 ,0
Exp/Cntr=0.3,0.1

Type RM Length L Ch R = 1 ,2137    ,451,451,451
BEGIN DESCRIPTION:
UNT 181 SanMiguel Cr Watershed 5.0
END DESCRIPTION:
XS GIS Cut Line= 5
      2089073.29     13451491.39      2087979.49     13451495.73
       2087775.5     13451513.09      2087675.67     13451634.62
      2087180.88     13452875.93
#Sta/Elev= 30
  3703.7   392.2    4052  386.39    4282  384.05    4362  384.94    4422   383.1
    4772  382.65 4829.22380.3031  4842.2  379.45  4847.5  377.15  4862.2  380.68
  4882.3  382.38  4892.3  381.38  4902.4  377.88  4922.4  381.13  4961.7  383.81
  4987.6  375.33  4988.6  374.53  4997.8  375.33  5017.6  378.71  5054.1  380.61
  5138.8  378.69  5337.2  381.45  5730.5  382.52    5774  381.61  5784.3  379.27
  5794.1380.3034  5822.5  382.02  5838.1  380.45  5984.2  382.79  6495.8  385.08
#Mann= 3 ,-1 , 0
  3703.7      .1       0  4987.6     .07       0  4997.8      .1       0
Bank Sta=4829.22,5794.1
XS Rating Curve= 0 ,0
Exp/Cntr=0.3,0.1

Type RM Length L Ch R = 1 ,1686    ,784,784,784
BEGIN DESCRIPTION:
UNT 181 SanMiguel Cr Watershed 4.0
END DESCRIPTION:
XS GIS Cut Line= 4
      2088647.86     13451018.31      2087714.74     13451200.59
      2087536.79      13451309.1       2087354.6     13451760.21
#Sta/Elev= 30
  3927.5  385.05  4236.1   381.5  4388.9  380.76  4667.8  381.11  4674.2  380.11
 4713.73379.1186  4745.5  380.23  4806.7   380.1  4857.6  377.84  4889.7  379.98
  4948.2  379.98  4975.3  378.27  4983.4  376.95  4985.7  373.37  4986.7  372.57
    4995  372.57  4995.9  373.37  5006.3  377.63  5033.4  379.06  5048.9  378.29
  5125.4  379.51  5168.5  378.32  5179.3  376.39  5190.2  377.68  5238.5  378.09
  5254.8  379.06    5268  378.04 5287.66379.1185  5399.5  380.51  5573.2  380.86
#Mann= 3 ,-1 , 0
  3927.5      .1       0  4985.7     .07       0  4995.9      .1       0
Bank Sta=4713.73,5287.66
XS Rating Curve= 0 ,0
Exp/Cntr=0.3,0.1

Type RM Length L Ch R = 1 ,902     ,473,473,473
BEGIN DESCRIPTION:
UNT 181 SanMiguel Cr Watershed 3.0
END DESCRIPTION:
XS GIS Cut Line= 4
      2088270.28     13450579.93      2087228.63     13450901.11
      2087167.86     13451087.74      2087141.84     13451560.41
#Sta/Elev= 30
  3811.7  383.42  3947.9  380.68  4225.3  378.14  4355.6  379.23  4458.8  378.07
  4529.3  379.64  4602.1  378.42  4633.4376.5629  4654.4  378.24  4692.7  377.55
  4853.2  379.09  4916.4  378.33  4962.8  377.35  4994.7  373.66  4995.4   371.5
  4996.3   370.7  5004.6   370.7  5005.6   371.5    5011  373.17  5021.4  374.13
  5026.6  376.59  5042.6  377.62  5058.6  377.75  5063.8  376.87  5090.5  377.54
  5094.6  375.79  5115.3  374.96 5148.85376.5628  5205.4   378.5  5571.4  380.31
#Mann= 3 ,-1 , 0
  3811.7      .1       0  4995.4     .07       0  5005.6      .1       0
Bank Sta=4633.4,5148.85
XS Rating Curve= 0 ,0
Exp/Cntr=0.3,0.1

Type RM Length L Ch R = 1 ,429     ,302,302,302
BEGIN DESCRIPTION:
UNT 181 SanMiguel Cr Watershed 2.0
END DESCRIPTION:
XS GIS Cut Line= 3
       2088297.4     13450523.72       2087058.2     13450737.76
        2087020.     13451250.09
#Sta/Elev= 30
  3715.6  384.97  3839.8  381.96  4134.1  378.54  4174.7  379.14  4215.3  377.79
  4560.3  378.09  4600.9  376.82  4834.3  376.65  4854.6  375.01  4885.1  374.79
 4894.15373.6252  4905.4  371.82  4924.1  372.78    4946  376.49  4972.2  376.56
  4990.4  373.17  5000.5  370.02  5005.4  369.66  5006.3  368.86  5014.6  368.86
  5015.6  369.66  5020.5  372.95 5026.17373.6247  5079.6  376.81    5201  377.12
    5222  376.02  5231.1   374.1  5251.2  377.17  5261.2  377.44  5486.9  379.21
#Mann= 3 ,-1 , 0
  3715.6      .1       0  5005.4     .07       0  5015.6      .1       0
Bank Sta=4894.15,5026.17
XS Rating Curve= 0 ,0
Exp/Cntr=0.3,0.1

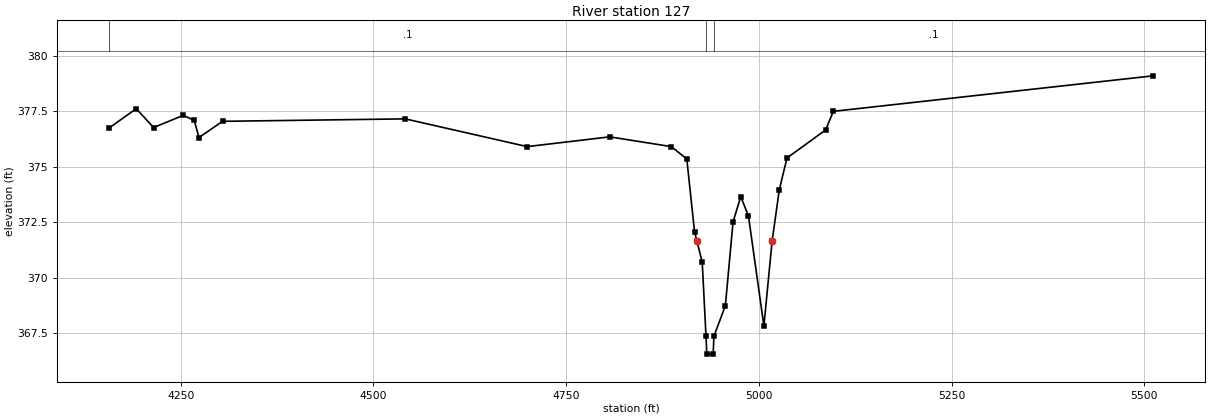
Type RM Length L Ch R = 1 ,127     ,0,0,0
BEGIN DESCRIPTION:
UNT 181 SanMiguel Cr Watershed 1.0
END DESCRIPTION:
XS GIS Cut Line= 3
       2087419.6     13450309.97      2086860.57     13450414.13
        2086850.     13451200.01
#Sta/Elev= 30
    4157  376.75  4192.2  377.62  4214.7  376.77  4253.2  377.32  4267.4  377.09
  4273.6  376.32  4304.1  377.05  4541.2  377.16  4699.4  375.91  4806.5  376.35
  4886.5  375.91  4906.5  375.35  4916.5  372.08 4919.59371.6536  4926.5   370.7
  4931.4  367.36  4932.4  366.56  4940.7  366.56  4941.6  367.36  4956.5  368.74
  4966.5  372.52  4976.5  373.66  4986.5  372.78  5006.5  367.83 5017.16371.6537
  5026.5  373.97  5036.5   375.4  5086.6  376.66  5096.6   377.5  5511.6   379.1
#Mann= 3 ,-1 , 0
    4157      .1       0  4931.4     .07       0  4941.6      .1       0
Bank Sta=4919.59,5017.16
XS Rating Curve= 0 ,0
Exp/Cntr=0.3,0.1
LCMann Table=0

Chan Stop Cuts=-1
Use User Specified Reach Order=0
Composite Channel Slope=5