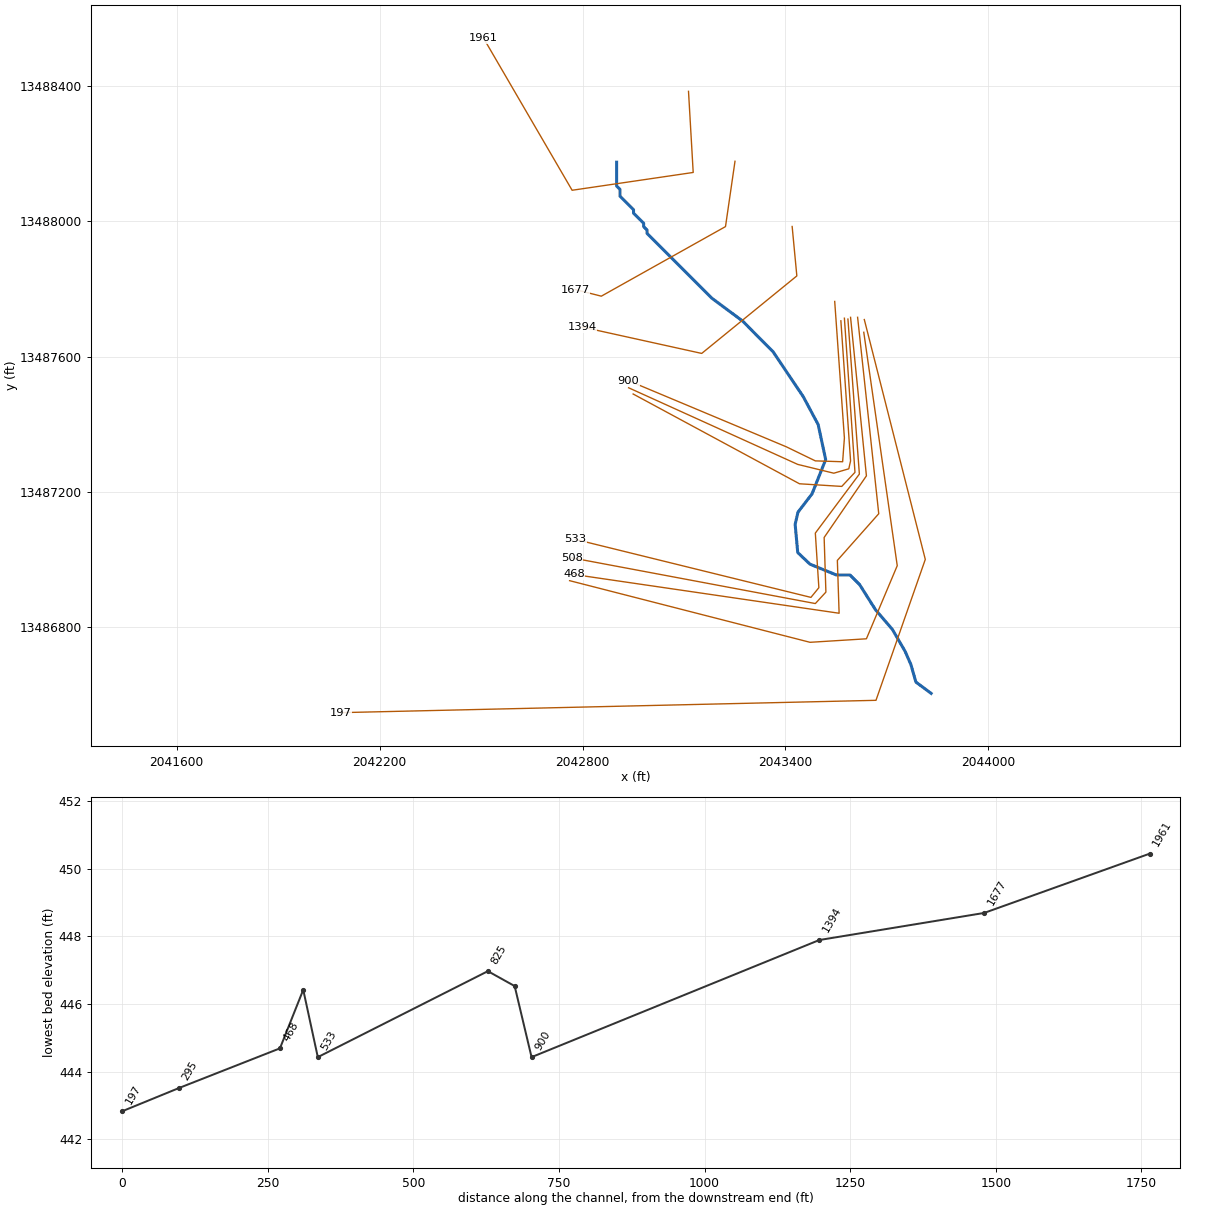
--- UNT 182 SanMiguel Cr Watershed.prj (project) ---

Proj Title=UNT 182 SanMiguel Cr Watershed Base Level Engineering
Current Plan=p01
Default Exp/Contr=0.3,0.1
English Units
Geom File=g01
Flow File=f01
Plan File=p01
Y Axis Title=Elevation
X Axis Title(PF)=Main Channel Distance
X Axis Title(XS)=Station
BEGIN DESCRIPTION:
UNT 182 SanMiguel Cr Watershed
END DESCRIPTION:
DSS Export Rating Curves= 0
DSS Export Rating Curve Sorted= 0
DSS Export Volume Flow Curves= 0
DXF OffsetX= 0
DXF OffsetY= 0
DXF ScaleX= 1
DXF ScaleY= 10

--- UNT 182 SanMiguel Cr Watershed.p01 (plan) ---

Plan Title=Multiple Run
Short Identifier=Multiple
Geom File=g01
Flow File=f01
Subcritical Flow
K Sum by GR= 0
Std Step Tol= 0.01
Critical Tol= 0.01
Num of Std Step Trials= 20
Max Error Tol= 0.3
Flow Tol Ratio= 0.001
Split Flow NTrial= 30
Split Flow Tol= 0.02
Split Flow Ratio= 0.02
Log Output Level= 0
Friction Slope Method= 1
Unsteady Friction Slope Method= 2
Unsteady Bridges Friction Slope Method= 1
Parabolic Critical Depth
Global Vel Dist=  1 , 1 , 1
Global Log Level= 0
CheckData=True
Encroach Param= -1, 0, 0, 0
BEGIN DESCRIPTION:
Multiple Run
END DESCRIPTION:

--- UNT 182 SanMiguel Cr Watershed.f01 (steady flow) ---

Flow Title=Multiple
Number of Profiles=7
Profile Names=10-year,25-year,50-year,1pct_min,100-year,1pct_plu,500-year
River Rch & RM= UNT 182 SanMigue,Reach-1,1961
     147     197     237     143     285     568     416
River Rch & RM= UNT 182 SanMigue,Reach-1,533
     168     226     274     165     330     659     486
Boundary for River Rch & Prof#=UNT 182 SanMigue,Reach-1,1
Up Type=0
Dn Type=3
Dn Slope=0.005
Boundary for River Rch & Prof#=UNT 182 SanMigue,Reach-1,2
Up Type=0
Dn Type=3
Dn Slope=0.005
Boundary for River Rch & Prof#=UNT 182 SanMigue,Reach-1,3
Up Type=0
Dn Type=3
Dn Slope=0.005
Boundary for River Rch & Prof#=UNT 182 SanMigue,Reach-1,4
Up Type=0
Dn Type=3
Dn Slope=0.005
Boundary for River Rch & Prof#=UNT 182 SanMigue,Reach-1,5
Up Type=0
Dn Type=3
Dn Slope=0.005
Boundary for River Rch & Prof#=UNT 182 SanMigue,Reach-1,6
Up Type=0
Dn Type=3
Dn Slope=0.005
Boundary for River Rch & Prof#=UNT 182 SanMigue,Reach-1,7
Up Type=0
Dn Type=3
Dn Slope=0.005

--- UNT 182 SanMiguel Cr Watershed.g01 (geometry) ---

Geom Title=Existing Conditions
Program Version=5.05

River Reach=UNT 182 SanMigue,Reach-1
Reach XY= 30
       2042900.8     13488175.08       2042900.8     13488104.54
       2042910.8     13488094.54       2042910.8     13488074.54
       2042950.8     13488034.54       2042950.8     13488024.54
       2042980.8     13487994.54       2042980.8     13487984.54
       2042990.8     13487974.54       2042990.8     13487964.54
      2043182.25     13487773.08      2043273.13     13487705.63
      2043363.41     13487614.66      2043452.99     13487481.33
      2043496.74     13487399.38      2043518.97     13487295.91
      2043478.69     13487194.52      2043437.02     13487140.35
      2043428.69     13487104.24      2043436.33     13487020.91
      2043472.49     13486986.62       2043550.8     13486954.54
       2043590.8     13486954.54      2043619.42     13486925.91
      2043666.24      13486851.9      2043716.24     13486793.57
      2043753.74     13486728.98       2043771.1      13486689.4
      2043785.69     13486638.01       2043830.8     13486604.54

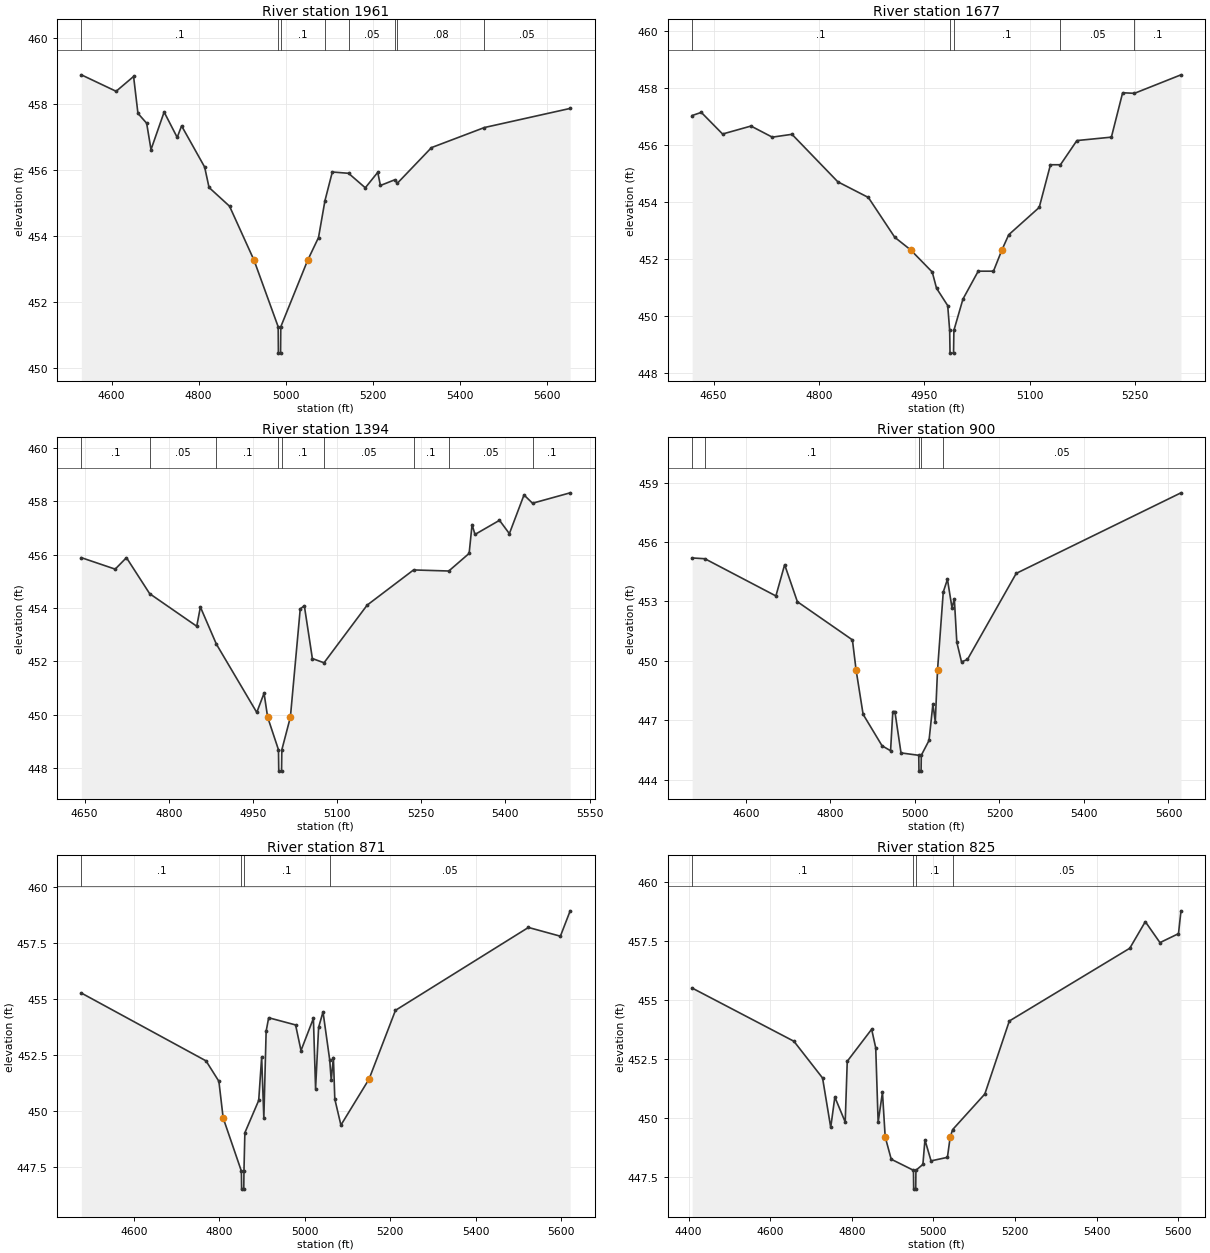
Type RM Length L Ch R = 1 ,1961    ,284,284,284
BEGIN DESCRIPTION:
UNT 182 SanMiguel Cr Watershed 11.0
END DESCRIPTION:
XS GIS Cut Line= 4
      2043113.37     13488384.67      2043127.26     13488144.77
      2042769.24     13488092.13      2042507.62     13488541.44
#Sta/Elev= 30
  4530.8  458.89  4610.6  458.39  4650.7  458.84  4660.7  457.72  4680.7  457.42
  4690.7  456.62  4720.8  457.76  4750.8  456.99  4760.9  457.34  4813.8  456.09
  4823.9  455.47    4871   454.9  4927.3453.2574  4982.6  451.24  4983.1  450.44
  4988.1  450.44  4988.6  451.24 5050.22453.2575  5075.2  453.95    5090  455.07
  5106.9  455.94  5144.2   455.9  5182.6  455.46  5211.2  455.93  5217.3  455.53
  5249.7   455.7  5256.3   455.6  5334.5  456.68  5456.1  457.29  5652.9  457.87
#Mann= 8 ,-1 , 0
  4530.8      .1       0  4982.6     .07       0  4988.6      .1       0
    5090     .08       0  5144.2     .05       0  5249.7      .1       0
  5256.3     .08       0  5456.1     .05       0
Bank Sta=4927.3,5050.22
XS Rating Curve= 0 ,0
Exp/Cntr=0.3,0.1

Type RM Length L Ch R = 1 ,1677    ,283,283,283
BEGIN DESCRIPTION:
UNT 182 SanMiguel Cr Watershed 10.0
END DESCRIPTION:
XS GIS Cut Line= 4
      2043250.84     13488177.85      2043222.75      13487984.7
      2042855.56     13487778.97      2042778.58     13487798.52
#Sta/Elev= 30
  4619.6  457.04  4632.6  457.15  4662.9  456.39  4703.3  456.67  4733.6  456.28
  4761.6  456.38  4826.9  454.71  4870.3  454.16  4907.9  452.76 4930.38452.3201
  4961.2  451.54  4967.3  450.97  4983.2  450.36    4986  449.49  4986.5  448.69
  4991.5  448.69    4992  449.49  5004.9  450.59  5026.6  451.57  5048.3  451.57
 5060.39452.3199    5070  452.85  5113.4  453.81  5129.4  455.31  5143.6  455.31
    5167  456.16  5216.1  456.28  5232.1  457.84  5248.9  457.82  5315.1  458.47
#Mann= 5 ,-1 , 0
  4619.6      .1       0    4986     .07       0    4992      .1       0
  5143.6     .05       0  5248.9      .1       0
Bank Sta=4930.38,5060.39
XS Rating Curve= 0 ,0
Exp/Cntr=0.3,0.1

Type RM Length L Ch R = 1 ,1394    ,494,494,494
BEGIN DESCRIPTION:
UNT 182 SanMiguel Cr Watershed 9.0
END DESCRIPTION:
XS GIS Cut Line= 4
      2043419.84     13487985.01      2043433.68     13487838.87
      2043152.43      13487609.7      2042799.12     13487687.64
#Sta/Elev= 30
  4644.1  455.89  4704.4  455.46  4724.5  455.89  4765.9  454.54  4849.8  453.32
  4856.3  454.04  4884.8  452.65  4956.8  450.09  4969.8  450.81 4976.18449.9136
  4995.5  448.69    4996  447.89    5001  447.89  5001.5  448.69 5016.73449.9141
  5034.3  453.97  5041.6  454.09  5055.9  452.11  5076.7  451.95  5153.5  454.11
  5236.3  455.43  5299.1  455.39  5335.4  456.05  5340.6  457.13  5345.8  456.76
  5389.5  457.29  5407.1  456.79  5433.2  458.24  5448.4  457.93  5515.5  458.32
#Mann= 9 ,-1 , 0
  4644.1      .1       0  4765.9     .05       0  4884.8      .1       0
  4995.5     .07       0  5001.5      .1       0  5076.7     .05       0
  5236.3      .1       0  5299.1     .05       0  5448.4      .1       0
Bank Sta=4976.18,5016.73
XS Rating Curve= 0 ,0
Exp/Cntr=0.3,0.1

Type RM Length L Ch R = 1 ,900     ,29,29,29
BEGIN DESCRIPTION:
UNT 182 SanMiguel Cr Watershed 8.0
END DESCRIPTION:
XS GIS Cut Line= 6
      2043545.66     13487763.39      2043574.31      13487359.7
       2043569.1     13487289.39      2043488.37     13487291.99
      2043402.43     13487333.66      2042936.29     13487528.97
#Sta/Elev= 30
  4472.7   455.2  4502.8  455.16  4670.9  453.28  4691.6  454.86  4721.7  452.99
    4852  451.06 4860.67449.5406  4877.3   447.3  4922.2  445.71  4942.3  445.46
  4947.6  447.44  4952.5  447.44    4967  445.35    5009  445.23  5009.5  444.43
  5014.5  444.43    5015  445.23  5033.3  445.98  5042.5  447.82  5048.1  446.92
 5053.44449.5414    5067  453.48  5076.9  454.12  5087.7  452.68  5093.2  453.13
  5099.1  450.94  5110.2  449.95  5124.2  450.07  5239.7  454.42  5629.6  458.49
#Mann= 5 ,-1 , 0
  4472.7     .05       0  4502.8      .1       0    5009     .07       0
    5015      .1       0    5067     .05       0
Bank Sta=4860.67,5053.44
XS Rating Curve= 0 ,0
Exp/Cntr=0.3,0.1

Type RM Length L Ch R = 1 ,871     ,46,46,46
BEGIN DESCRIPTION:
UNT 182 SanMiguel Cr Watershed 7.0
END DESCRIPTION:
XS GIS Cut Line= 6
      2043563.89     13487706.09      2043592.54     13487291.99
      2043587.33     13487268.55      2043543.06     13487255.53
      2043436.29     13487281.57      2042936.27     13487508.15
#Sta/Elev= 30
  4477.1  455.26  4768.9  452.24    4799  451.33    4809   449.7  4851.7  447.33
  4852.2  446.53  4857.2  446.53  4857.7  447.33  4859.8  449.04  4892.2  450.48
  4899.1  452.41  4904.2  449.69  4909.6  453.56  4915.5  454.16  4978.5  453.84
  4991.2   452.7  5020.2  454.13  5025.3     451  5032.4  453.73  5042.7  454.42
  5058.4  452.28  5061.9  451.38    5067  452.39  5070.3  450.54  5084.6  449.38
  5150.5  451.43  5212.3  454.49  5523.5  458.18  5598.3  457.79  5621.2  458.92
#Mann= 4 ,-1 , 0
  4477.1      .1       0  4851.7     .07       0  4857.7      .1       0
  5058.4     .05       0
Bank Sta=4809,5150.5
XS Rating Curve= 0 ,0
Exp/Cntr=0.3,0.1

Type RM Length L Ch R = 1 ,825     ,292,292,292
BEGIN DESCRIPTION:
UNT 182 SanMiguel Cr Watershed 6.0
END DESCRIPTION:
XS GIS Cut Line= 5
      2043574.31     13487713.83      2043605.56     13487258.14
       2043566.5     13487216.47       2043441.5     13487224.28
      2042949.67     13487489.71
#Sta/Elev= 30
  4408.8  455.51  4658.2  453.25  4728.4  451.69  4748.4  449.59  4758.5  450.88
  4783.9  449.82  4788.9   452.4  4848.7  453.76  4858.7  452.97  4864.6  449.81
  4875.2  451.08 4881.87449.1886  4896.7  448.24  4951.2  447.77  4951.7  446.97
  4956.7  446.97  4957.2  447.77  4974.3  448.02  4979.3  449.06  4994.3  448.17
  5034.4  448.32 5041.25449.1891  5047.3   449.5  5126.1  451.01  5186.1  454.11
  5481.3   457.2  5519.4  458.33  5555.3  457.44  5600.7  457.82  5606.8  458.79
#Mann= 4 ,-1 , 0
  4408.8      .1       0  4951.2     .07       0  4957.2      .1       0
  5047.3     .05       0
Bank Sta=4881.87,5041.25
XS Rating Curve= 0 ,0
Exp/Cntr=0.3,0.1

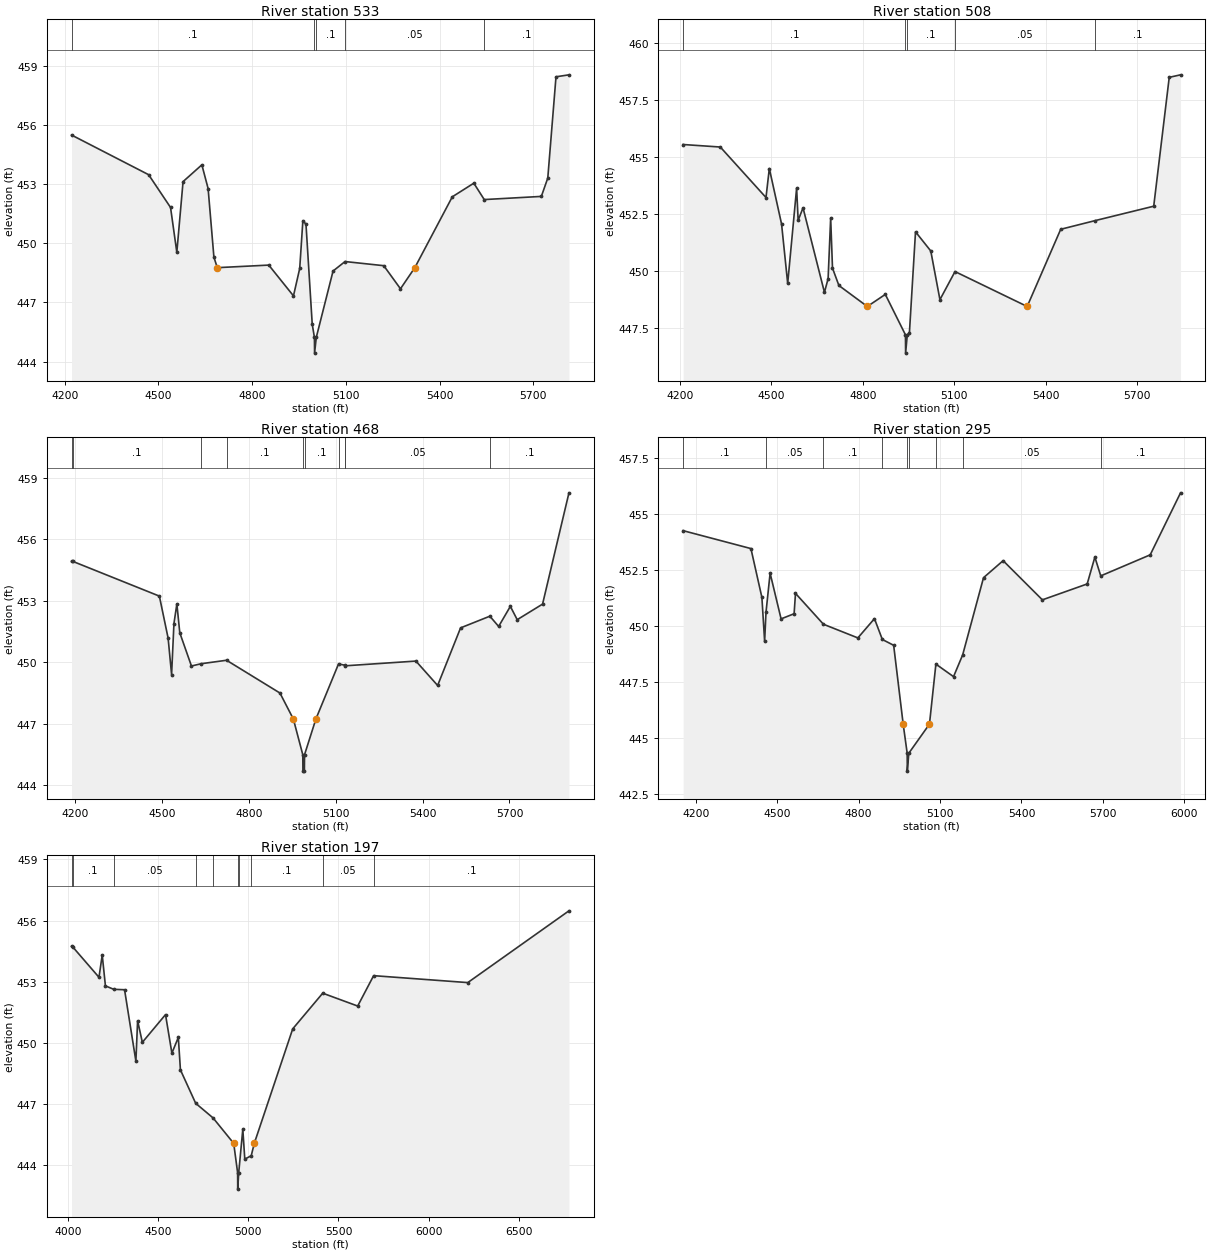
Type RM Length L Ch R = 1 ,533     ,25,25,25
BEGIN DESCRIPTION:
UNT 182 SanMiguel Cr Watershed 5.0
END DESCRIPTION:
XS GIS Cut Line= 6
      2043584.73     13487711.26      2043618.58     13487252.93
      2043488.37     13487078.45      2043498.79     13486916.99
      2043475.35     13486888.35      2042779.14      13487059.8
#Sta/Elev= 30
  4221.5  455.48  4468.4  453.47  4538.6  451.81  4558.7  449.54  4578.7  453.12
  4638.9  453.97  4658.9  452.77  4677.5  449.29 4688.33448.7598  4853.2  448.89
  4932.3  447.33  4952.3  448.72  4962.4  451.14  4972.4  450.96  4992.4  445.89
  4999.4  445.23  4999.9  444.43  5005.4  445.23  5059.1  448.59  5097.5  449.07
  5221.5  448.86    5275  447.69 5320.93448.7595    5441  452.35  5509.9  453.04
  5543.3  452.21  5726.2  452.37  5746.8   453.3  5773.1  458.43  5814.6  458.53
#Mann= 5 ,-1 , 0
  4221.5      .1       0  4999.4     .07       0  5005.4      .1       0
  5097.5     .05       0  5543.3      .1       0
Bank Sta=4688.33,5320.93
XS Rating Curve= 0 ,0
Exp/Cntr=0.3,0.1

Type RM Length L Ch R = 1 ,508     ,40,40,40
BEGIN DESCRIPTION:
UNT 182 SanMiguel Cr Watershed 4.0
END DESCRIPTION:
XS GIS Cut Line= 6
      2043592.54     13487716.43      2043639.41     13487247.72
      2043514.41     13487065.43      2043519.62     13486903.97
      2043488.37     13486870.12      2042768.54     13487005.25
#Sta/Elev= 30
  4210.6  455.55  4332.6  455.44  4482.5  453.23  4493.4   454.5  4533.6  452.07
  4553.7  449.47    4583  453.64    4588  452.23    4604  452.78  4674.3  449.08
  4686.3  449.68  4694.7  452.33  4700.7  450.14  4721.7  449.38 4814.94448.4614
    4874  448.99  4940.1  447.22  4940.6  446.42  4946.1  447.22  4953.1  447.31
  4973.1  451.73  5023.2  450.89  5053.2  448.76  5102.7  449.99 5339.46448.4616
  5449.5  451.84  5562.5  452.22  5754.7  452.85  5805.6  458.49  5842.7   458.6
#Mann= 5 ,-1 , 0
  4210.6      .1       0  4940.1     .07       0  4946.1      .1       0
  5102.7     .05       0  5562.5      .1       0
Bank Sta=4814.94,5339.46
XS Rating Curve= 0 ,0
Exp/Cntr=0.3,0.1

Type RM Length L Ch R = 1 ,468     ,173,173,173
BEGIN DESCRIPTION:
UNT 182 SanMiguel Cr Watershed 3.0
END DESCRIPTION:
XS GIS Cut Line= 5
      2043613.37     13487716.51      2043675.87     13487135.74
      2043553.48     13486997.72      2043558.68     13486841.47
      2042774.84     13486956.05
#Sta/Elev= 30
  4188.2  454.92  4193.4  454.92  4491.4  453.23  4521.6  451.18  4533.6   449.4
  4541.7  451.89  4551.8  452.85  4561.9  451.44  4602.1  449.82  4635.3  449.93
  4723.3   450.1  4907.7   448.5 4953.99447.2298  4986.5  445.49    4987  444.69
    4992  444.69  4992.5  445.49 5031.62447.2292  5109.9  449.92  5131.4  449.86
  5133.7  449.83    5377  450.06    5452  448.87  5531.2  451.68  5632.2  452.25
  5662.6  451.75    5703  452.73  5726.7  452.08  5814.2  452.84  5905.3  458.27
#Mann= 10 ,-1 , 0
  4188.2     .05       0  4193.4      .1       0  4635.3     .05       0
  4723.3      .1       0  4986.5     .07       0  4992.5      .1       0
  5109.9     .08       0  5131.4      .1       0  5133.7     .05       0
  5632.2      .1       0
Bank Sta=4953.99,5031.62
XS Rating Curve= 0 ,0
Exp/Cntr=0.3,0.1

Type RM Length L Ch R = 1 ,295     ,98,98,98
BEGIN DESCRIPTION:
UNT 182 SanMiguel Cr Watershed 2.0
END DESCRIPTION:
XS GIS Cut Line= 5
      2043631.59     13487672.25      2043730.56      13486982.1
      2043639.41     13486765.95      2043472.75     13486755.53
      2042761.82     13486937.82
#Sta/Elev= 30
  4153.5  454.26  4403.3  453.46  4443.7  451.28  4453.8  449.31  4458.8  450.61
    4474  452.36  4514.4  450.32  4562.4  450.55  4567.5  451.46  4670.5  450.08
  4797.3  449.47  4858.4  450.33  4887.5   449.4  4929.2  449.14 4964.26445.6194
    4979  444.32  4979.5  443.52    4985  444.32 5061.11445.6195  5084.8   448.3
  5149.8  447.74  5183.4  448.71  5260.3  452.16  5332.5  452.92  5477.1  451.17
  5642.2  451.88  5670.5  453.08  5692.2  452.24  5874.4  453.18  5986.2  455.95
#Mann= 9 ,-1 , 0
  4153.5      .1       0  4458.8     .05       0  4670.5      .1       0
  4887.5     .05       0    4979     .04       0    4985     .05       0
  5084.8     .08       0  5183.4     .05       0  5692.2      .1       0
Bank Sta=4964.26,5061.11
XS Rating Curve= 0 ,0
Exp/Cntr=0.3,0.1

Type RM Length L Ch R = 1 ,197     ,0,0,0
BEGIN DESCRIPTION:
UNT 182 SanMiguel Cr Watershed 1.0
END DESCRIPTION:
XS GIS Cut Line= 4
      2043633.16     13487709.87       2043813.5     13487000.67
      2043667.67     13486584.01      2042084.31     13486547.55
#Sta/Elev= 30
  4020.6  454.74  4026.2  454.72  4172.7  453.22  4190.7  454.31  4208.4   452.8
  4254.4  452.63  4314.5  452.61  4377.3  449.11  4386.8  451.09  4413.1  450.03
  4541.5  451.39  4576.8   449.5  4612.5  450.27  4624.1  448.68  4708.7  447.04
  4805.3  446.32 4919.43445.0751  4941.2  443.63  4941.7  442.83  4947.2  443.63
  4969.9  445.77  4980.9   444.3  5016.6  444.47 5033.52 445.075  5246.5  450.69
  5412.8  452.44  5606.6  451.81    5695   453.3  6216.8  452.96  6777.6  456.48
#Mann= 10 ,-1 , 0
  4020.6     .05       0  4026.2      .1       0  4254.4     .05       0
  4708.7      .1       0  4805.3     .05       0  4941.2     .04       0
  4947.2     .05       0  5016.6      .1       0  5412.8     .05       0
    5695      .1       0
Bank Sta=4919.43,5033.52
XS Rating Curve= 0 ,0
Exp/Cntr=0.3,0.1
LCMann Table=0

Chan Stop Cuts=-1
Use User Specified Reach Order=0
Composite Channel Slope=5