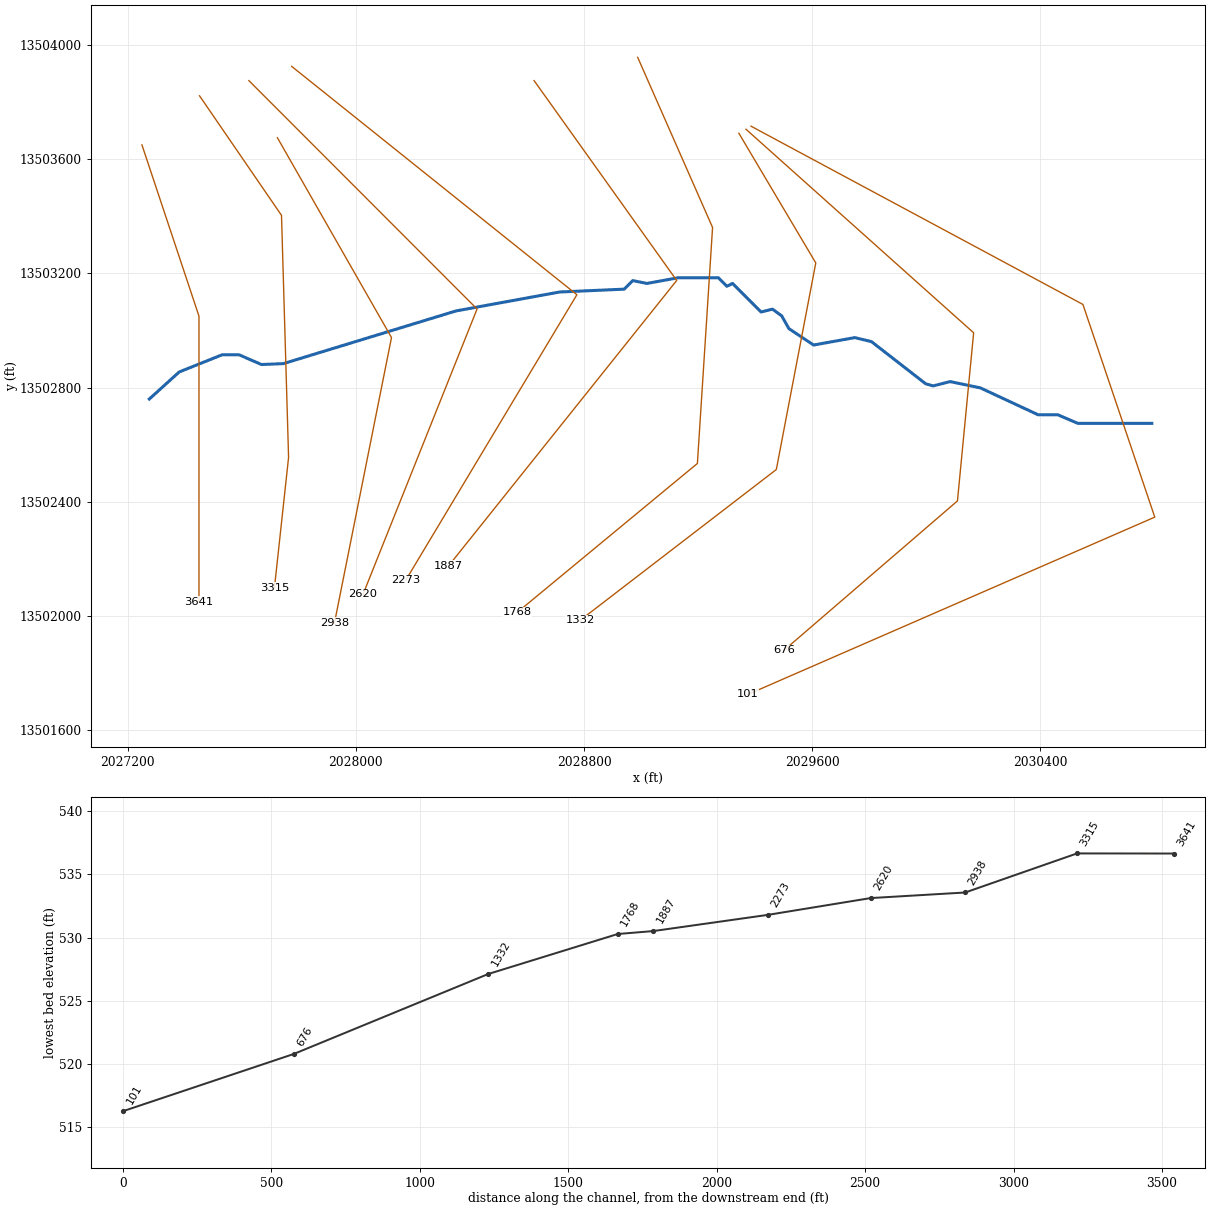
--- UNT 183 SanMiguel CrWatershed.prj (project) ---

Proj Title=UNT 183 SanMiguel CrWatershed Base Level Engineering
Current Plan=p01
Default Exp/Contr=0.3,0.1
English Units
Geom File=g01
Flow File=f01
Plan File=p01
Y Axis Title=Elevation
X Axis Title(PF)=Main Channel Distance
X Axis Title(XS)=Station
BEGIN DESCRIPTION:
UNT 183 SanMiguel CrWatershed
END DESCRIPTION:
DSS Export Rating Curves= 0
DSS Export Rating Curve Sorted= 0
DSS Export Volume Flow Curves= 0
DXF OffsetX= 0
DXF OffsetY= 0
DXF ScaleX= 1
DXF ScaleY= 10

--- UNT 183 SanMiguel CrWatershed.p01 (plan) ---

Plan Title=Multiple Run
Short Identifier=Multiple
Geom File=g01
Flow File=f01
Subcritical Flow
K Sum by GR= 0
Std Step Tol= 0.01
Critical Tol= 0.01
Num of Std Step Trials= 20
Max Error Tol= 0.3
Flow Tol Ratio= 0.001
Split Flow NTrial= 30
Split Flow Tol= 0.02
Split Flow Ratio= 0.02
Log Output Level= 0
Friction Slope Method= 1
Unsteady Friction Slope Method= 2
Unsteady Bridges Friction Slope Method= 1
Parabolic Critical Depth
Global Vel Dist=  1 , 1 , 1
Global Log Level= 0
CheckData=True
Encroach Param= -1, 0, 0, 0
BEGIN DESCRIPTION:
Multiple Run
END DESCRIPTION:

--- UNT 183 SanMiguel CrWatershed.f01 (steady flow) ---

Flow Title=Multiple
Number of Profiles=7
Profile Names=10-year,25-year,50-year,1pct_min,100-year,1pct_plu,500-year
River Rch & RM= UNT 183 SanMigue,Reach-1,3641
     218     301     369     226     450     898     681
Boundary for River Rch & Prof#=UNT 183 SanMigue,Reach-1,1
Up Type=0
Dn Type=3
Dn Slope=0.005
Boundary for River Rch & Prof#=UNT 183 SanMigue,Reach-1,2
Up Type=0
Dn Type=3
Dn Slope=0.005
Boundary for River Rch & Prof#=UNT 183 SanMigue,Reach-1,3
Up Type=0
Dn Type=3
Dn Slope=0.005
Boundary for River Rch & Prof#=UNT 183 SanMigue,Reach-1,4
Up Type=0
Dn Type=3
Dn Slope=0.005
Boundary for River Rch & Prof#=UNT 183 SanMigue,Reach-1,5
Up Type=0
Dn Type=3
Dn Slope=0.005
Boundary for River Rch & Prof#=UNT 183 SanMigue,Reach-1,6
Up Type=0
Dn Type=3
Dn Slope=0.005
Boundary for River Rch & Prof#=UNT 183 SanMigue,Reach-1,7
Up Type=0
Dn Type=3
Dn Slope=0.005

--- UNT 183 SanMiguel CrWatershed.g01 (geometry) ---

Geom Title=Existing Conditions
Program Version=5.05

River Reach=UNT 183 SanMigue,Reach-1
Reach XY= 30
      2027275.95     13502759.69       2027380.8     13502854.54
       2027530.8     13502914.54       2027590.8     13502914.54
      2027668.96      13502880.5      2027746.03     13502883.66
      2028351.22     13503068.26      2028714.24     13503134.54
       2028940.8     13503144.54       2028970.8     13503174.54
       2029020.8     13503164.54       2029130.8     13503184.54
       2029270.8     13503184.54       2029300.8     13503154.54
       2029320.8     13503164.54       2029420.8     13503064.54
       2029460.8     13503074.54      2029493.24     13503050.76
      2029518.19     13503006.27        2029605.     13502948.76
      2029749.31     13502974.81      2029807.91      13502960.7
      2029997.79     13502813.13      2030023.84     13502805.54
      2030083.52     13502820.73      2030189.57     13502798.67
      2030391.98     13502704.54       2030460.8     13502704.54
       2030530.8     13502674.54       2030790.8     13502674.54

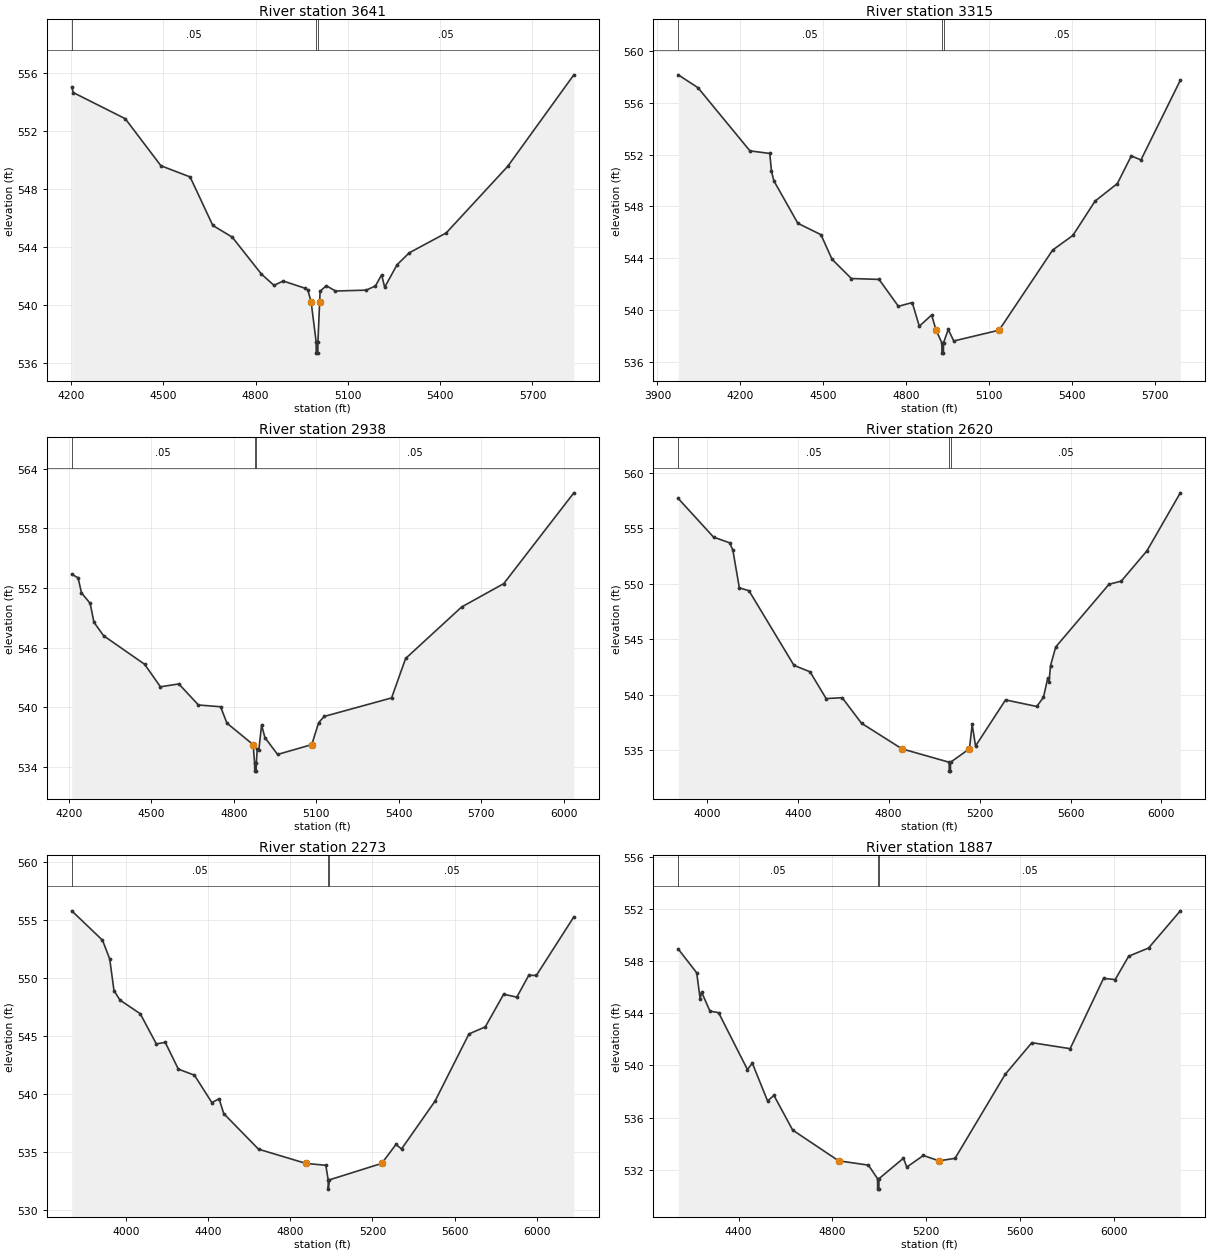
Type RM Length L Ch R = 1 ,3641    ,326,326,326
BEGIN DESCRIPTION:
UNT 183 SanMiguel CrWatershed 10.0
END DESCRIPTION:
XS GIS Cut Line= 3
      2027250.01     13503649.98        2027450.       13503050.
        2027450.     13502050.04
#Sta/Elev= 30
  4202.1     555  4207.4  554.64    4376  552.84    4492  549.59  4586.8  548.82
  4660.6  545.47  4723.9  544.66  4818.7  542.11  4859.5  541.33  4889.5  541.63
  4959.5  541.14  4969.5  541.01  4980.4 540.179  4996.5  537.45    4997  536.65
    5002  536.65  5002.5  537.45    5008540.1764  5009.5  540.92  5029.5  541.31
  5059.5  540.94  5159.5     541  5189.5  541.29  5209.5  542.06  5219.5   541.2
  5259.5  542.75  5299.5  543.58  5419.5  544.95  5619.5  549.55  5834.5  555.87
#Mann= 3 ,-1 , 0
  4202.1     .05       0  4996.5     .03       0  5002.5     .05       0
Bank Sta=4980.4,5008
XS Rating Curve= 0 ,0
Exp/Cntr=0.3,0.1

Type RM Length L Ch R = 1 ,3315    ,377,377,377
BEGIN DESCRIPTION:
UNT 183 SanMiguel CrWatershed 9.0
END DESCRIPTION:
XS GIS Cut Line= 4
      2027451.95     13503821.84      2027739.34     13503403.17
      2027764.17     13502555.24      2027714.63     13502098.74
#Sta/Elev= 30
  3975.4  558.18  4046.5  557.19  4234.7   552.3  4306.4   552.1  4312.5  550.73
  4321.3  549.98  4407.9   546.7  4491.4  545.82  4531.4  543.92  4601.4  542.43
  4701.5  542.36  4771.5  540.28  4821.5  540.57    4847  538.74  4891.6  539.61
 4907.58538.4352  4928.5  537.46    4929  536.66  4934.1  536.66  4934.6  537.46
  4951.6  538.49  4971.6   537.6 5135.48538.4351  5329.1  544.63  5402.2  545.76
  5482.6  548.42  5563.1  549.77  5613.4  551.91  5648.4   551.6  5790.7  557.76
#Mann= 3 ,-1 , 0
  3975.4     .05       0  4928.5     .03       0  4934.6     .05       0
Bank Sta=4907.58,5135.48
XS Rating Curve= 0 ,0
Exp/Cntr=0.3,0.1

Type RM Length L Ch R = 1 ,2938    ,318,318,318
BEGIN DESCRIPTION:
UNT 183 SanMiguel CrWatershed 8.0
END DESCRIPTION:
XS GIS Cut Line= 3
        2027725.     13503674.99        2028125.       13502975.
        2027925.     13501975.02
#Sta/Elev= 30
  4211.1  553.38  4234.1  553.04  4246.4  551.52    4278  550.46  4291.7  548.56
    4327   547.2    4476  544.33  4533.6  542.06  4600.5  542.35  4671.8  540.23
  4752.4  540.05  4775.4   538.4 4870.66536.2401  4876.1  534.37  4876.6  533.57
  4881.7  533.57  4882.2  534.37  4885.6  535.77  4891.3  535.66  4901.4  538.21
  4913.7  536.94  4959.7  535.25 5083.92 536.241  5109.1  538.46  5129.5  539.08
  5374.2  540.94  5425.2  544.91  5629.2   550.1  5782.2  552.45  6037.1  561.59
#Mann= 3 ,-1 , 0
  4211.1     .05       0  4876.1     .03       0  4882.2     .05       0
Bank Sta=4870.66,5083.92
XS Rating Curve= 0 ,0
Exp/Cntr=0.3,0.1

Type RM Length L Ch R = 1 ,2620    ,347,347,347
BEGIN DESCRIPTION:
UNT 183 SanMiguel CrWatershed 7.0
END DESCRIPTION:
XS GIS Cut Line= 3
        2027625.       13503875.        2028425.       13503075.
        2028025.       13502075.
#Sta/Elev= 30
  3874.4  557.67    4030  554.19  4100.7  553.68  4114.8  553.01  4143.1  549.63
  4185.5  549.37  4383.5  542.65  4454.2  542.07  4524.9  539.66  4595.6  539.74
  4680.5  537.44 4858.34535.1369    5066  533.93  5066.5  533.13  5071.6  533.13
  5072.1  533.93 5155.28535.1369  5167.3  537.33  5182.1  535.39  5314.1  539.54
  5451.4  538.95    5481  539.78  5499.9  541.52  5505.2  541.13    5512  542.63
  5534.9  544.31  5769.1  549.95    5823  550.23  5936.1  552.96  6082.8  558.18
#Mann= 3 ,-1 , 0
  3874.4     .05       0    5066     .03       0  5072.1     .05       0
Bank Sta=4858.34,5155.28
XS Rating Curve= 0 ,0
Exp/Cntr=0.3,0.1

Type RM Length L Ch R = 1 ,2273    ,386,386,386
BEGIN DESCRIPTION:
UNT 183 SanMiguel CrWatershed 6.0
END DESCRIPTION:
XS GIS Cut Line= 3
      2027774.97     13503925.03        2028775.       13503125.
      2028174.98     13502124.96
#Sta/Elev= 30
  3734.6  555.76  3884.3  553.23  3919.5  551.62  3940.3   548.9  3969.2  548.08
  4068.4   546.9  4146.8   544.3  4190.1  544.44  4254.1  542.13  4332.5  541.61
  4417.4  539.25  4452.6  539.58    4475  538.31  4644.7  535.24 4875.27534.0169
  4972.8  533.85  4984.2   532.6  4984.7   531.8  4990.3   532.6 5245.41 534.017
  5314.6  535.65  5341.8  535.26  5505.1  539.38  5670.3  545.16    5750  545.77
  5839.4  548.58  5903.5  548.33  5961.8  550.21  5998.8   550.2  6181.5  555.24
#Mann= 3 ,-1 , 0
  3734.6     .05       0  4984.2     .03       0  4990.3     .05       0
Bank Sta=4875.27,5245.41
XS Rating Curve= 0 ,0
Exp/Cntr=0.3,0.1

Type RM Length L Ch R = 1 ,1887    ,119,119,119
BEGIN DESCRIPTION:
UNT 183 SanMiguel CrWatershed 5.0
END DESCRIPTION:
XS GIS Cut Line= 3
      2028624.97     13503875.04        2029125.       13503175.
        2028325.       13502175.
#Sta/Elev= 30
  4142.4  548.93  4221.1  547.11  4235.8  545.12    4242  545.63  4277.6  544.17
  4314.5  544.05  4437.4  539.69  4458.3  540.18  4523.4  537.28  4550.4  537.71
  4630.3  535.05  4826.3532.6908  4953.5  532.36  4992.3  531.32  4992.8  530.52
  4997.9  530.52  4998.4  531.32  5102.7  532.89  5117.1  532.21  5187.6   533.1
 5254.04532.6909  5322.8  532.88  5536.5  539.32  5650.2  541.75  5813.5  541.29
  5955.9  546.68  6005.6  546.59  6063.2  548.38    6148  549.01  6283.3  551.86
#Mann= 3 ,-1 , 0
  4142.4     .05       0  4992.3     .03       0  4998.4     .05       0
Bank Sta=4826.3,5254.04
XS Rating Curve= 0 ,0
Exp/Cntr=0.3,0.1

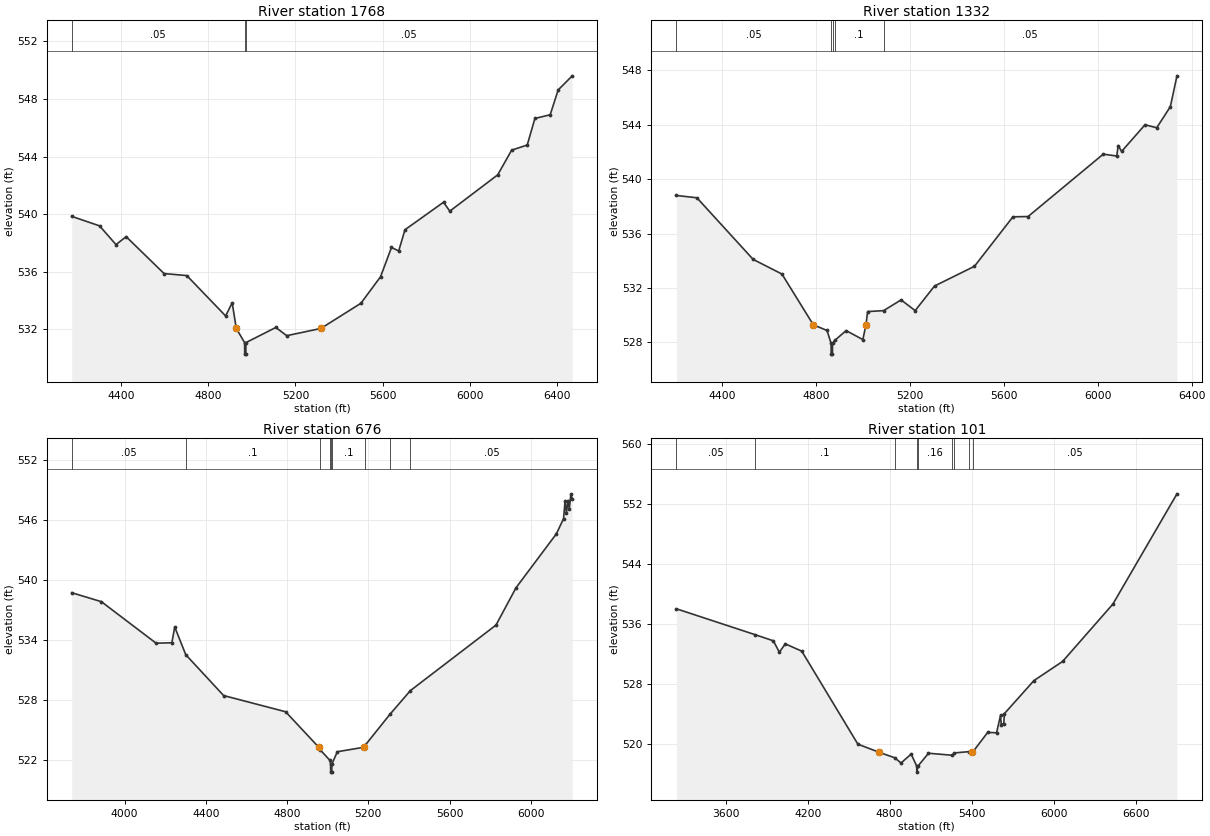
Type RM Length L Ch R = 1 ,1768    ,436,436,436
BEGIN DESCRIPTION:
UNT 183 SanMiguel CrWatershed 4.0
END DESCRIPTION:
XS GIS Cut Line= 4
      2028988.18     13503956.62      2029250.72      13503360.6
       2029197.5     13502533.95      2028565.95      13502012.4
#Sta/Elev= 30
  4172.3  539.85  4300.3  539.19  4375.7  537.89  4422.4  538.44  4596.6  535.88
  4700.9  535.74  4879.3  532.94  4909.4  533.85 4928.29 532.071  4966.4  531.09
  4966.9  530.29    4972  530.29  4972.5  531.09  5109.8  532.14  5159.9  531.57
 5316.72532.0712  5500.6  533.82  5590.8  535.66  5640.9  537.69  5674.2  537.45
  5702.9  538.92  5880.1  540.83  5908.7  540.21  6128.9  542.73  6192.7  544.44
  6264.4   544.8  6299.6  546.64  6369.9   546.9  6406.4  548.62    6471   549.6
#Mann= 3 ,-1 , 0
  4172.3     .05       0  4966.4     .03       0  4972.5     .05       0
Bank Sta=4928.29,5316.72
XS Rating Curve= 0 ,0
Exp/Cntr=0.3,0.1

Type RM Length L Ch R = 1 ,1332    ,656,656,656
BEGIN DESCRIPTION:
UNT 183 SanMiguel CrWatershed 3.0
END DESCRIPTION:
XS GIS Cut Line= 4
      2029342.95     13503690.56      2029612.59     13503236.43
      2029474.23     13502512.67      2028785.93     13501984.02
#Sta/Elev= 30
  4204.6   538.8  4291.7  538.63  4531.3   534.1  4654.1  533.02 4787.81529.2861
  4846.2  528.87  4863.5  527.93    4864  527.13  4869.2  527.13  4869.7  527.93
  4879.3  528.14  4927.6  528.86  4998.9   528.2 5012.23529.2858  5019.3  530.26
  5087.5  530.33  5161.8  531.12  5221.8  530.33  5304.3  532.14  5474.5  533.59
  5638.5  537.23  5702.9  537.25  6023.4  541.84  6080.8   541.7  6087.1  542.47
  6101.6  542.04  6201.3     544  6251.2  543.78  6309.2  545.33  6337.5   547.6
#Mann= 5 ,-1 , 0
  4204.6     .05       0  4863.5     .07       0  4869.7     .05       0
  4879.3      .1       0  5087.5     .05       0
Bank Sta=4787.81,5012.23
XS Rating Curve= 0 ,0
Exp/Cntr=0.3,0.1

Type RM Length L Ch R = 1 ,676     ,575,575,575
BEGIN DESCRIPTION:
UNT 183 SanMiguel CrWatershed 2.0
END DESCRIPTION:
XS GIS Cut Line= 4
      2029367.83     13503704.71      2030166.06     13502991.62
      2030109.29     13502402.68      2029500.93     13501879.21
#Sta/Elev= 30
  3739.4  538.75  3885.7  537.85  4154.9   533.7  4232.6  533.74  4246.8  535.32
    4301  532.55  4487.6  528.46  4792.7  526.84 4955.59523.2966  4964.4     523
  5011.3  521.97  5014.2   521.6  5014.7   520.8    5020   520.8  5020.5   521.6
  5047.5  522.84 5180.48523.2968  5185.4  523.51  5305.9  526.57  5407.4  528.96
  5828.7  535.51  5927.5  539.25  6126.1  544.64  6161.2  546.15  6168.9  547.92
  6175.5  546.74  6183.2  547.97  6189.7  547.15  6197.4  548.64    6204  548.15
#Mann= 9 ,-1 , 0
  3739.4     .05       0    4301      .1       0  4964.4     .16       0
  5011.3      .1       0  5014.2     .07       0  5020.5      .1       0
  5185.4     .16       0  5305.9      .1       0  5407.4     .05       0
Bank Sta=4955.59,5180.48
XS Rating Curve= 0 ,0
Exp/Cntr=0.3,0.1

Type RM Length L Ch R = 1 ,101     ,0,0,0
BEGIN DESCRIPTION:
UNT 183 SanMiguel CrWatershed 1.0
END DESCRIPTION:
XS GIS Cut Line= 4
      2029385.55     13503715.38      2030549.22     13503090.96
      2030801.12     13502345.92      2029375.02     13501725.01
#Sta/Elev= 30
  3239.8  538.07    3815  534.62  3948.8   533.8  3992.6  532.28  4036.5  533.39
  4156.7  532.42  4567.4  520.01 4723.91518.9199  4836.3   518.2  4883.4   517.5
  4957.3  518.69  4997.9  517.08  4998.7  516.28  5006.9  517.08    5084   518.8
  5258.3  518.53  5272.4  518.84  5383.1  519.02  5399.2  518.92  5411.6  519.05
  5517.3  521.58  5582.2  521.53    5611  523.84  5616.5  522.63  5634.5  522.76
  5639.9  524.09  5855.3  528.49  6065.5  531.05  6433.3   538.7  6902.3  553.41
#Mann= 9 ,-1 , 0
  3239.8     .05       0    3815      .1       0  4836.3     .16       0
  4997.9     .07       0  5006.9     .16       0  5258.3      .1       0
  5272.4     .05       0  5383.1      .1       0  5411.6     .05       0
Bank Sta=4723.91,5399.2
XS Rating Curve= 0 ,0
Exp/Cntr=0.3,0.1
LCMann Table=0

Chan Stop Cuts=-1
Use User Specified Reach Order=0
Composite Channel Slope=5