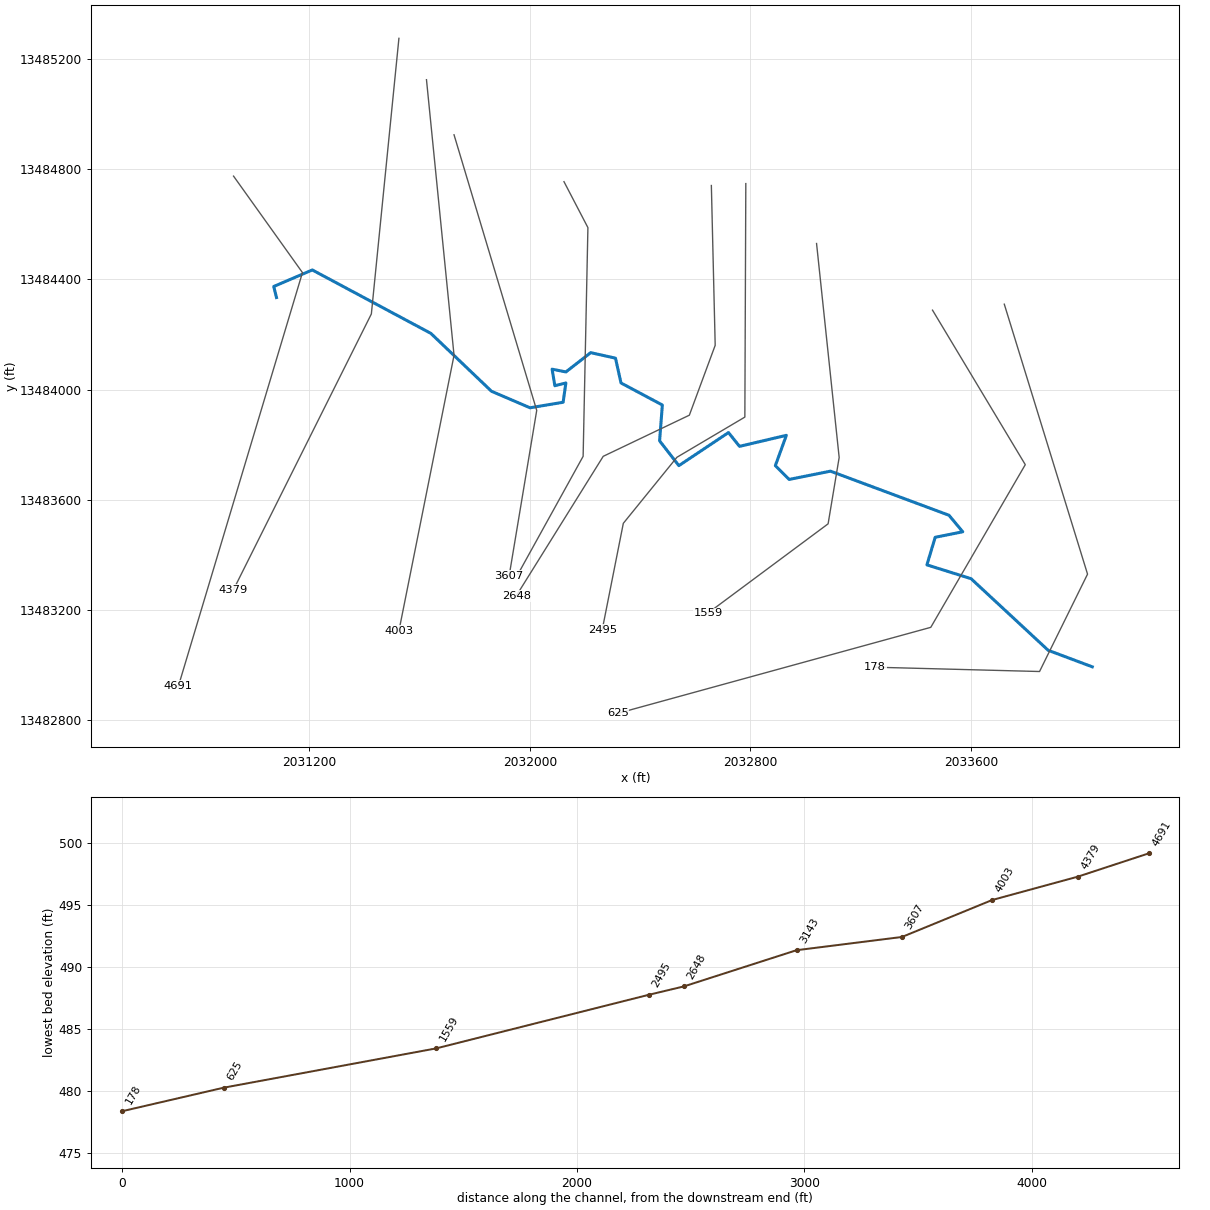
--- UNT 184 SanMiguel Cr Watershed.prj (project) ---

Proj Title=UNT 184 SanMiguel Cr Watershed Base Level Engineering
Current Plan=p01
Default Exp/Contr=0.3,0.1
English Units
Geom File=g01
Flow File=f01
Plan File=p01
Y Axis Title=Elevation
X Axis Title(PF)=Main Channel Distance
X Axis Title(XS)=Station
BEGIN DESCRIPTION:
UNT 184 SanMiguel Cr Watershed
END DESCRIPTION:
DSS Export Rating Curves= 0
DSS Export Rating Curve Sorted= 0
DSS Export Volume Flow Curves= 0
DXF OffsetX= 0
DXF OffsetY= 0
DXF ScaleX= 1
DXF ScaleY= 10

--- UNT 184 SanMiguel Cr Watershed.p01 (plan) ---

Plan Title=Multiple Run
Short Identifier=Multiple
Geom File=g01
Flow File=f01
Subcritical Flow
K Sum by GR= 0
Std Step Tol= 0.01
Critical Tol= 0.01
Num of Std Step Trials= 20
Max Error Tol= 0.3
Flow Tol Ratio= 0.001
Split Flow NTrial= 30
Split Flow Tol= 0.02
Split Flow Ratio= 0.02
Log Output Level= 0
Friction Slope Method= 1
Unsteady Friction Slope Method= 2
Unsteady Bridges Friction Slope Method= 1
Parabolic Critical Depth
Global Vel Dist=  1 , 1 , 1
Global Log Level= 0
CheckData=True
Encroach Param= -1, 0, 0, 0
BEGIN DESCRIPTION:
Multiple Run
END DESCRIPTION:

--- UNT 184 SanMiguel Cr Watershed.f01 (steady flow) ---

Flow Title=Multiple
Number of Profiles=7
Profile Names=10-year,25-year,50-year,1pct_min,100-year,1pct_plu,500-year
River Rch & RM= UNT 184 SanMigue,Reach-1,4691
     239     331     407     250     499     996     761
Boundary for River Rch & Prof#=UNT 184 SanMigue,Reach-1,1
Up Type=0
Dn Type=3
Dn Slope=0.005
Boundary for River Rch & Prof#=UNT 184 SanMigue,Reach-1,2
Up Type=0
Dn Type=3
Dn Slope=0.005
Boundary for River Rch & Prof#=UNT 184 SanMigue,Reach-1,3
Up Type=0
Dn Type=3
Dn Slope=0.005
Boundary for River Rch & Prof#=UNT 184 SanMigue,Reach-1,4
Up Type=0
Dn Type=3
Dn Slope=0.005
Boundary for River Rch & Prof#=UNT 184 SanMigue,Reach-1,5
Up Type=0
Dn Type=3
Dn Slope=0.005
Boundary for River Rch & Prof#=UNT 184 SanMigue,Reach-1,6
Up Type=0
Dn Type=3
Dn Slope=0.005
Boundary for River Rch & Prof#=UNT 184 SanMigue,Reach-1,7
Up Type=0
Dn Type=3
Dn Slope=0.005

--- UNT 184 SanMiguel Cr Watershed.g01 (geometry) ---

Geom Title=Existing Conditions
Program Version=5.05

River Reach=UNT 184 SanMigue,Reach-1
Reach XY= 30
       2031080.8     13484334.54       2031070.8     13484374.54
       2031210.8     13484434.54       2031640.8     13484204.54
       2031860.8     13483994.54       2032000.8     13483934.54
       2032120.8     13483954.54       2032130.8     13484024.54
       2032090.8     13484014.54       2032080.8     13484074.54
       2032130.8     13484064.54       2032220.8     13484134.54
       2032310.8     13484114.54       2032330.8     13484024.54
       2032480.8     13483944.54       2032470.8     13483814.54
       2032540.8     13483724.54       2032720.8     13483844.54
       2032760.8     13483794.54       2032930.8     13483834.54
       2032890.8     13483724.54       2032940.8     13483674.54
       2033090.8     13483704.54       2033520.8     13483544.54
       2033570.8     13483484.54       2033470.8     13483464.54
       2033440.8     13483364.54       2033600.8     13483314.54
       2033880.8     13483054.54       2034040.8     13482994.54

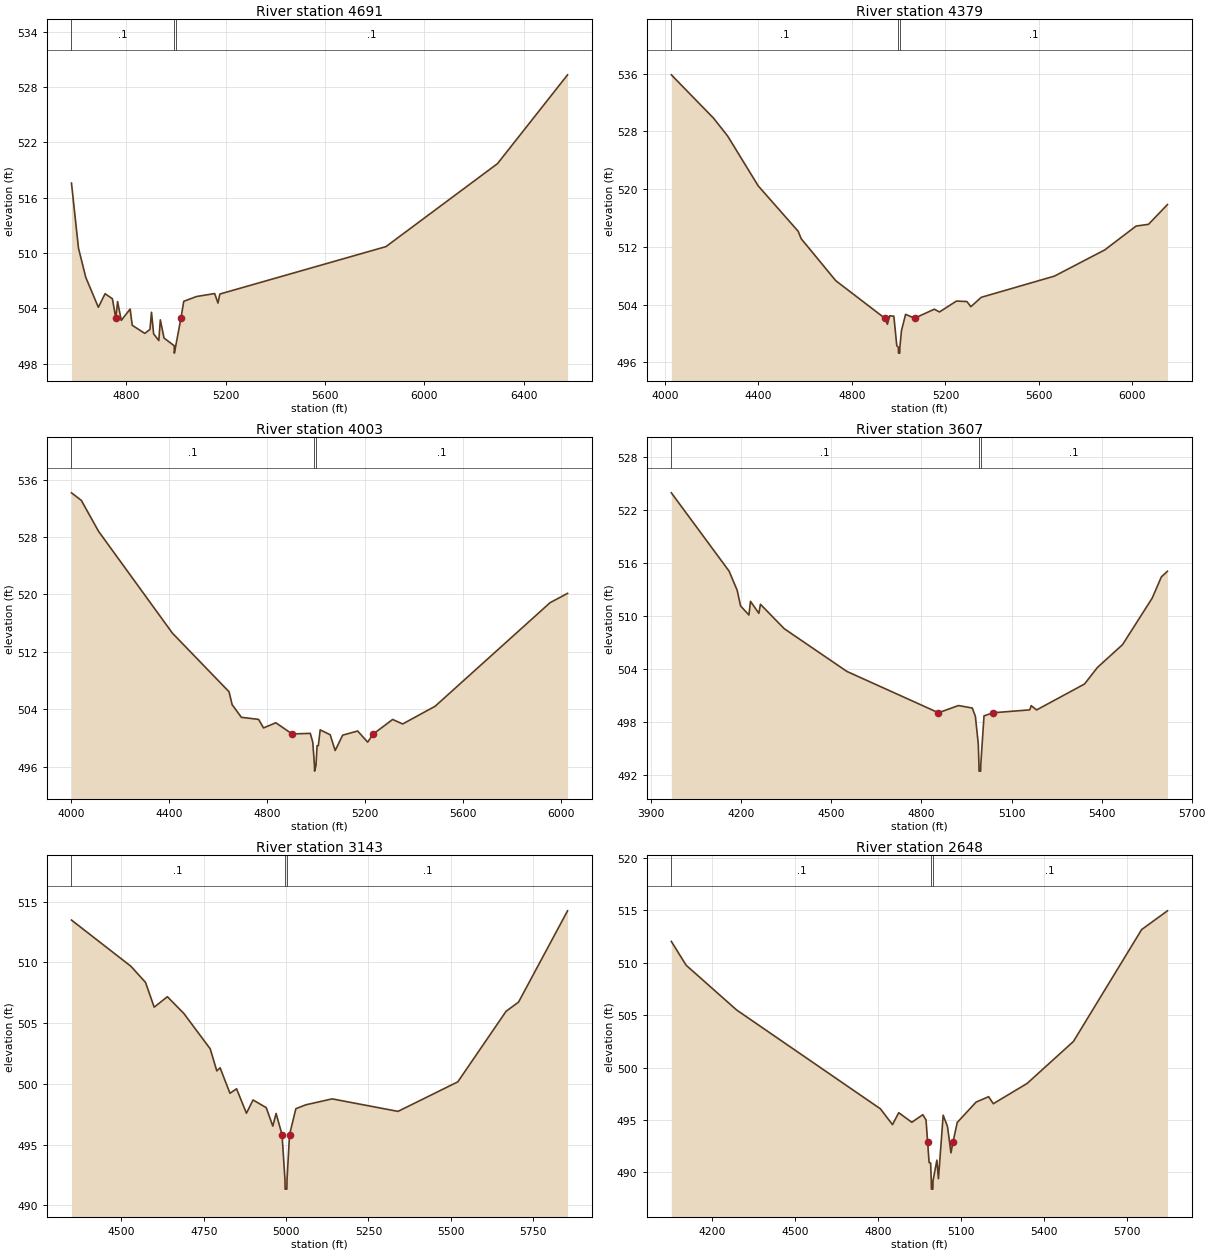
Type RM Length L Ch R = 1 ,4691    ,312,312,312
BEGIN DESCRIPTION:
UNT 184 SanMiguel Cr Watershed 10.0
END DESCRIPTION:
XS GIS Cut Line= 3
      2030924.98     13484775.03        2031175.       13484425.
        2030725.       13482925.
#Sta/Elev= 30
  4579.7  517.58    4608  510.51  4637.5  507.34  4687.9  504.11  4714.9  505.58
  4744.4  505.04  4758.2502.9221  4765.3  504.73    4780  502.69  4815.7  503.92
  4824.3  502.16  4874.7  501.28  4895.6  501.71  4901.7  503.57  4910.3  501.23
  4931.2   500.5  4937.3  502.75  4952.1  500.78  4993.2  499.94  4993.7  499.14
  4999.4  499.94 5020.18502.9218  5031.6  504.76  5082.9  505.28    5156   505.6
  5169.1  504.57  5176.9  505.55  5845.1  510.69    6294  519.69  6575.9  529.32
#Mann= 3 ,-1 , 0
  4579.7      .1       0  4993.2     .07       0  4999.4      .1       0
Bank Sta=4758.2,5020.18
XS Rating Curve= 0 ,0
Exp/Cntr=0.3,0.1

Type RM Length L Ch R = 1 ,4379    ,376,376,376
BEGIN DESCRIPTION:
UNT 184 SanMiguel Cr Watershed 9.0
END DESCRIPTION:
XS GIS Cut Line= 3
        2031525.       13485275.        2031425.       13484275.
      2030925.01     13483275.02
#Sta/Elev= 30
  4027.3  535.85  4208.2  529.83  4268.5  527.35  4399.1  520.45    4570  514.16
  4582.6  513.14  4730.8  507.31 4940.66502.1018  4951.9  501.26  4961.9  502.44
  4979.5  502.38  4992.1  498.29    4999  498.06  4999.5  497.26  5004.7  497.26
  5005.2  498.06  5012.2   500.4  5029.8  502.64 5068.22502.1018  5152.5  503.35
  5174.8  502.97  5247.5  504.48  5292.2  504.41    5309   503.7  5353.7     505
  5666.8  507.94    5882  511.57  6016.2  514.88  6069.3  515.12  6150.3  517.86
#Mann= 3 ,-1 , 0
  4027.3      .1       0    4999     .07       0  5005.2      .1       0
Bank Sta=4940.66,5068.22
XS Rating Curve= 0 ,0
Exp/Cntr=0.3,0.1

Type RM Length L Ch R = 1 ,4003    ,396,396,396
BEGIN DESCRIPTION:
UNT 184 SanMiguel Cr Watershed 8.0
END DESCRIPTION:
XS GIS Cut Line= 3
        2031625.     13485124.97        2031725.       13484125.
      2031524.99     13483124.96
#Sta/Elev= 30
    4001  534.16  4041.2  533.11  4111.5   528.8    4413  514.61  4644.2  506.44
  4656.7  504.65  4694.4  502.88  4764.8  502.59  4784.9   501.4  4835.1  502.12
 4901.54500.5621  4975.8  500.64  4985.9  499.42  4992.8  496.18  4993.3  495.38
    4999  496.18  5003.4  498.92  5008.5  498.92  5016.2  501.13  5056.9  500.45
  5077.3  498.25  5107.9  500.39  5169.1  500.97  5209.9  499.42 5233.16500.5623
  5311.9  502.58  5352.7  501.95  5485.3  504.42  5954.4  518.85  6025.8  520.15
#Mann= 3 ,-1 , 0
    4001      .1       0  4992.8     .07       0    4999      .1       0
Bank Sta=4901.54,5233.16
XS Rating Curve= 0 ,0
Exp/Cntr=0.3,0.1

Type RM Length L Ch R = 1 ,3607    ,464,464,464
BEGIN DESCRIPTION:
UNT 184 SanMiguel Cr Watershed 7.0
END DESCRIPTION:
XS GIS Cut Line= 3
        2031725.       13484925.        2032025.       13483925.
        2031925.     13483325.01
#Sta/Elev= 30
    3967  523.97  4159.3  515.09  4186.2  512.92  4197.6  511.14  4225.4  510.11
  4230.6  511.66  4258.5   510.3  4263.7  511.33  4342.9  508.56  4551.7  503.71
 4856.66499.0211  4923.2  499.84  4969.3  499.56  4979.7  498.61  4989.3  495.49
  4991.4   493.2  4991.9   492.4  4997.2   492.4  4997.7   493.2  5008.4  498.67
 5039.02499.0212  5160.6  499.35  5165.6  499.83  5183.4  499.34  5343.1  502.28
  5386.1  504.16  5469.8  506.75  5568.6  512.03    5599  514.43  5619.3  515.07
#Mann= 3 ,-1 , 0
    3967      .1       0  4991.4     .07       0  4997.7      .1       0
Bank Sta=4856.66,5039.02
XS Rating Curve= 0 ,0
Exp/Cntr=0.3,0.1

Type RM Length L Ch R = 1 ,3143    ,495,495,495
BEGIN DESCRIPTION:
UNT 184 SanMiguel Cr Watershed 6.0
END DESCRIPTION:
XS GIS Cut Line= 4
      2032123.94     13484754.89      2032210.74     13484588.23
      2032193.38     13483758.37      2031957.25     13483331.24
#Sta/Elev= 30
  4348.3  513.48  4528.6  509.68  4573.1  508.35  4599.4  506.31  4639.5  507.17
  4689.5  505.79  4769.5  502.88  4789.5  501.06  4799.5  501.32  4829.5  499.22
  4849.5  499.59  4879.5  497.58  4899.5  498.67  4939.5  498.04  4959.5  496.52
  4969.5  497.56 4987.51495.8147  4996.4  492.13  4996.9  491.33  5002.2  491.33
  5002.7  492.13 5010.33495.8153  5029.5  497.95  5059.6  498.27  5139.6  498.76
  5339.6  497.73  5521.1  500.16  5667.7  505.97  5705.6  506.73  5854.3  514.24
#Mann= 3 ,-1 , 0
  4348.3      .1       0  4996.4     .07       0  5002.7      .1       0
Bank Sta=4987.51,5010.33
XS Rating Curve= 0 ,0
Exp/Cntr=0.3,0.1

Type RM Length L Ch R = 1 ,2648    ,153,153,153
BEGIN DESCRIPTION:
UNT 184 SanMiguel Cr Watershed 5.0
END DESCRIPTION:
XS GIS Cut Line= 5
      2032658.66       13484741.      2032672.55     13484161.15
       2032578.8     13483907.67       2032266.3     13483758.37
      2031950.31     13483251.39
#Sta/Elev= 30
  4052.2  512.04  4105.7  509.77  4288.3   505.5  4808.3  496.07    4852  494.56
  4874.4   495.7  4921.8  494.79  4961.6  495.51  4973.2  495.01 4979.01 492.885
  4984.3  490.95  4989.8   490.9  4992.2  489.21  4992.7  488.41    4998  488.41
  4998.5  489.21  5012.5  491.18  5018.1  489.41  5035.2  495.46  5050.8  494.39
  5063.4  491.87  5070.6492.8856  5086.1  494.77  5154.1  496.71  5199.5  497.23
  5216.6  496.56  5338.7  498.49  5506.3   502.5  5752.9  513.17  5846.2  514.96
#Mann= 3 ,-1 , 0
  4052.2      .1       0  4992.2     .07       0  4998.5      .1       0
Bank Sta=4979.01,5070.6
XS Rating Curve= 0 ,0
Exp/Cntr=0.3,0.1

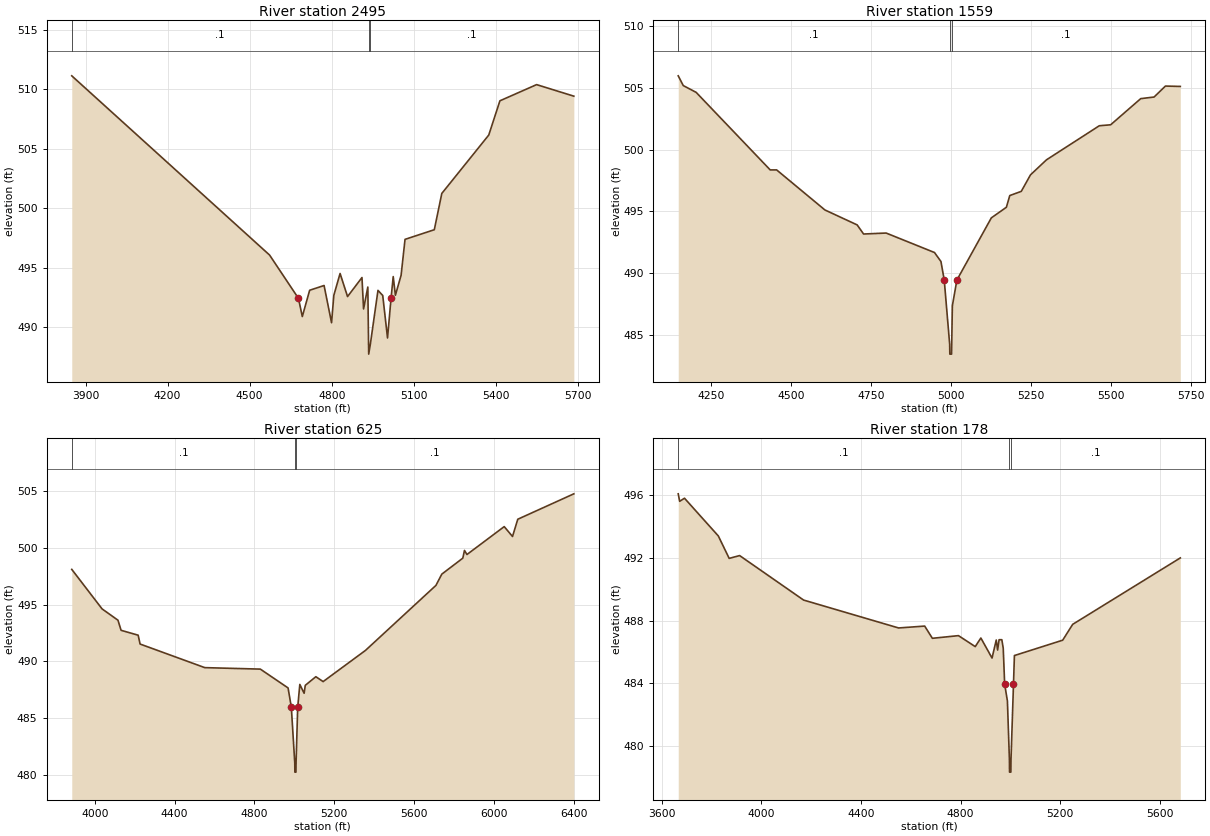
Type RM Length L Ch R = 1 ,2495    ,936,936,936
BEGIN DESCRIPTION:
UNT 184 SanMiguel Cr Watershed 4.0
END DESCRIPTION:
XS GIS Cut Line= 5
      2032783.66     13484747.98      2032780.19     13483900.73
      2032533.66      13483754.9      2032339.22     13483515.31
      2032262.84     13483129.96
#Sta/Elev= 30
  3849.8  511.14  4572.8  496.07 4678.36492.4283  4692.4   490.9  4719.3  493.11
    4772  493.51  4799.3  490.38  4807.7  492.69  4830.5  494.52  4857.8  492.58
  4910.5  494.18  4916.3  491.54  4931.9  493.38  4934.6  488.54  4935.1  487.74
  4940.9  488.54    4969   493.1  4986.4  492.67  5003.9   489.1 5016.78492.4287
  5024.7  494.26  5032.7  492.69  5053.5  494.37  5067.9  497.39  5174.9   498.2
  5202.3  501.25  5373.9  506.16  5414.7  509.04  5548.8   510.4  5684.9  509.43
#Mann= 3 ,-1 , 0
  3849.8      .1       0  4934.6     .07       0  4940.9      .1       0
Bank Sta=4678.36,5016.78
XS Rating Curve= 0 ,0
Exp/Cntr=0.3,0.1

Type RM Length L Ch R = 1 ,1559    ,934,934,934
BEGIN DESCRIPTION:
UNT 184 SanMiguel Cr Watershed 3.0
END DESCRIPTION:
XS GIS Cut Line= 4
      2033040.36     13484530.57      2033122.38      13483754.1
      2033082.28     13483513.48      2032646.37     13483189.57
#Sta/Elev= 30
  4148.7  505.98  4164.4  505.19  4204.6  504.64  4435.9  498.35    4456  498.35
  4606.8   495.1  4707.4  493.89  4727.5  493.15  4797.9  493.23  4948.9  491.65
  4969.1  490.92 4979.34489.4185  4996.3  484.21  4996.8  483.41  5002.2  483.41
  5002.7  484.21  5004.7  487.33 5018.85489.4181  5126.4  494.46  5173.4  495.32
    5184  496.27  5219.9  496.61  5248.7  497.95  5298.7  499.17  5463.5  501.93
    5499  502.01  5592.9  504.13  5634.6  504.26    5670  505.15  5716.5  505.12
#Mann= 3 ,-1 , 0
  4148.7      .1       0  4996.3     .07       0  5002.7      .1       0
Bank Sta=4979.34,5018.85
XS Rating Curve= 0 ,0
Exp/Cntr=0.3,0.1

Type RM Length L Ch R = 1 ,625     ,447,447,447
BEGIN DESCRIPTION:
UNT 184 SanMiguel Cr Watershed 2.0
END DESCRIPTION:
XS GIS Cut Line= 4
      2033461.08     13484288.75      2033797.67     13483728.16
      2033454.79     13483137.88      2032318.81      13482825.7
#Sta/Elev= 30
  3884.9  498.11  4036.6  494.63  4116.3  493.63  4131.9  492.74  4217.4  492.31
  4227.1  491.53  4551.1  489.45  4829.3  489.32  4968.3  487.66  4984.6485.9515
  5001.8  481.04  5002.3  480.24  5007.7  480.24  5008.2  481.04 5016.43485.9523
  5027.1  487.97  5048.6  487.19  5054.4  487.89  5107.4  488.65  5143.8  488.22
    5356  490.97  5708.9   496.7  5738.1  497.69  5843.4   499.1  5851.8  499.78
  5864.2  499.42  6050.8  501.88  6092.3  501.01  6118.7  502.53  6399.5  504.77
#Mann= 3 ,-1 , 0
  3884.9      .1       0  5001.8     .07       0  5008.2      .1       0
Bank Sta=4984.6,5016.43
XS Rating Curve= 0 ,0
Exp/Cntr=0.3,0.1

Type RM Length L Ch R = 1 ,178     ,0,0,0
BEGIN DESCRIPTION:
UNT 184 SanMiguel Cr Watershed 1.0
END DESCRIPTION:
XS GIS Cut Line= 4
       2033721.5     13484310.46      2034023.59     13483330.87
      2033849.41     13482977.58      2033253.01     13482993.21
#Sta/Elev= 30
  3666.8   496.1  3672.5  495.62  3691.9  495.82  3827.8  493.41  3871.3  491.98
  3913.2  492.16  4170.1  489.32  4551.5  487.54  4656.2  487.66  4687.1  486.88
  4791.8  487.05  4859.2  486.35  4881.7   486.9  4926.6  485.62  4943.5  486.77
    4949  486.13  4954.9  486.79  4965.9  486.79  4971.5  486.25 4977.27483.9532
  4988.3  482.88  4996.3  479.14  4996.8  478.34  5002.2  478.34  5002.7  479.14
 5012.68483.9521  5016.4  485.78  5210.2  486.76  5250.3  487.77  5682.4  492.01
#Mann= 3 ,-1 , 0
  3666.8      .1       0  4996.3     .07       0  5002.7      .1       0
Bank Sta=4977.27,5012.68
XS Rating Curve= 0 ,0
Exp/Cntr=0.3,0.1
LCMann Table=0

Chan Stop Cuts=-1
Use User Specified Reach Order=0
Composite Channel Slope=5