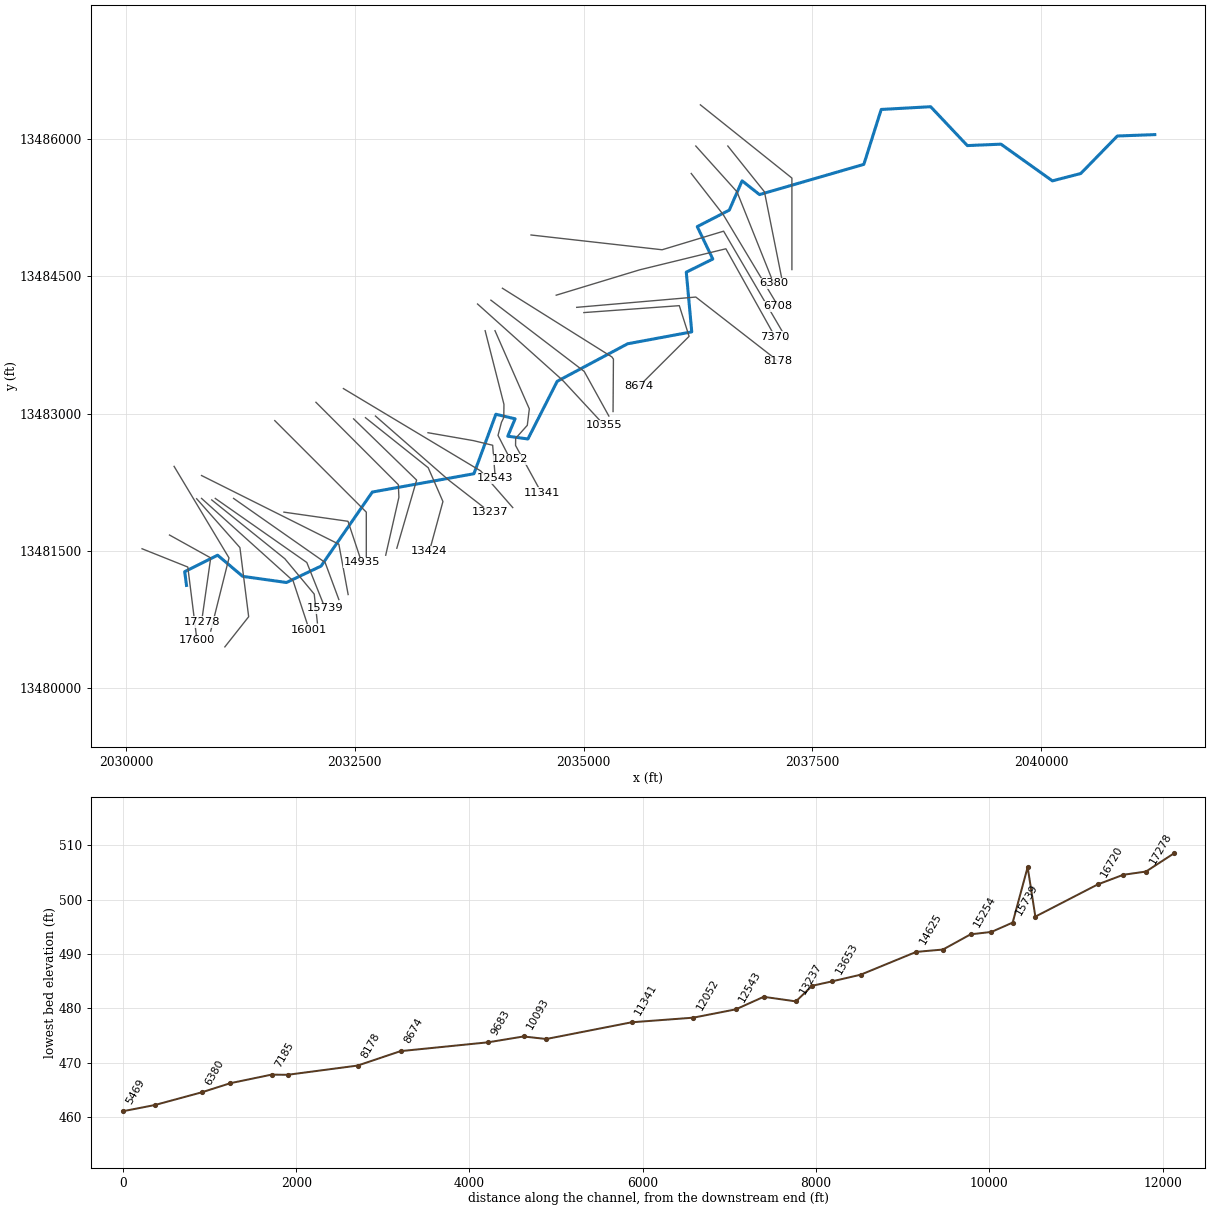
--- UNT 185 SanMiguel Cr Watershed.prj (project) ---

Proj Title=UNT 185 SanMiguel Cr Watershed Base Level Engineering
Current Plan=p01
Default Exp/Contr=0.3,0.1
English Units
Geom File=g01
Flow File=f01
Plan File=p01
Y Axis Title=Elevation
X Axis Title(PF)=Main Channel Distance
X Axis Title(XS)=Station
BEGIN DESCRIPTION:
UNT 185 SanMiguel Cr Watershed
END DESCRIPTION:
DSS Export Rating Curves= 0
DSS Export Rating Curve Sorted= 0
DSS Export Volume Flow Curves= 0
DXF OffsetX= 0
DXF OffsetY= 0
DXF ScaleX= 1
DXF ScaleY= 10

--- UNT 185 SanMiguel Cr Watershed.p01 (plan) ---

Plan Title=Multiple Run
Short Identifier=Multiple
Geom File=g01
Flow File=f01
Subcritical Flow
K Sum by GR= 0
Std Step Tol= 0.01
Critical Tol= 0.01
Num of Std Step Trials= 20
Max Error Tol= 0.3
Flow Tol Ratio= 0.001
Split Flow NTrial= 30
Split Flow Tol= 0.02
Split Flow Ratio= 0.02
Log Output Level= 0
Friction Slope Method= 1
Unsteady Friction Slope Method= 2
Unsteady Bridges Friction Slope Method= 1
Parabolic Critical Depth
Global Vel Dist=  1 , 1 , 1
Global Log Level= 0
CheckData=True
Encroach Param= -1, 0, 0, 0
BEGIN DESCRIPTION:
Multiple Run
END DESCRIPTION:

--- UNT 185 SanMiguel Cr Watershed.f01 (steady flow) ---

Flow Title=Multiple
Number of Profiles=7
Profile Names=10-year,25-year,50-year,1pct_min,100-year,1pct_plu,500-year
River Rch & RM= UNT 185 SanMigue,Reach-1,17600
     130     174     210     126     252     502     367
River Rch & RM= UNT 185 SanMigue,Reach-1,13237
     246     342     422     260     518    1033     792
River Rch & RM= UNT 185 SanMigue,Reach-1,12052
     411     586     735     459     915    1827    1443
River Rch & RM= UNT 185 SanMigue,Reach-1,8178
     479     685     860     538    1073    2141    1696
Boundary for River Rch & Prof#=UNT 185 SanMigue,Reach-1,1
Up Type=0
Dn Type=3
Dn Slope=0.005
Boundary for River Rch & Prof#=UNT 185 SanMigue,Reach-1,2
Up Type=0
Dn Type=3
Dn Slope=0.005
Boundary for River Rch & Prof#=UNT 185 SanMigue,Reach-1,3
Up Type=0
Dn Type=3
Dn Slope=0.005
Boundary for River Rch & Prof#=UNT 185 SanMigue,Reach-1,4
Up Type=0
Dn Type=3
Dn Slope=0.005
Boundary for River Rch & Prof#=UNT 185 SanMigue,Reach-1,5
Up Type=0
Dn Type=3
Dn Slope=0.005
Boundary for River Rch & Prof#=UNT 185 SanMigue,Reach-1,6
Up Type=0
Dn Type=3
Dn Slope=0.005
Boundary for River Rch & Prof#=UNT 185 SanMigue,Reach-1,7
Up Type=0
Dn Type=3
Dn Slope=0.005

--- UNT 185 SanMiguel Cr Watershed.g01 (geometry) ---

Geom Title=Existing Conditions
Program Version=5.05

River Reach=UNT 185 SanMigue,Reach-1
Reach XY= 30
       2030660.8     13481124.54       2030640.8     13481274.54
       2031000.8     13481454.54       2031274.1     13481223.48
      2031752.62     13481156.21      2032130.22     13481335.24
       2032690.8     13482144.54       2033800.8     13482344.54
       2034040.8     13482994.54       2034250.8     13482944.54
       2034170.8     13482754.54       2034390.8     13482724.54
       2034710.8     13483354.54       2035480.8     13483764.54
       2036180.8     13483894.54      2036121.12     13484546.67
       2036410.7     13484690.42       2036240.8     13485044.54
       2036590.8     13485224.54       2036730.8     13485544.54
       2036920.8     13485394.54       2038060.8     13485724.54
       2038250.8     13486324.54       2038790.8     13486354.54
      2039191.65     13485929.79      2039558.84     13485945.41
       2040120.8     13485544.54       2040430.8     13485624.54
       2040830.8     13486034.54      2041239.61     13486049.71

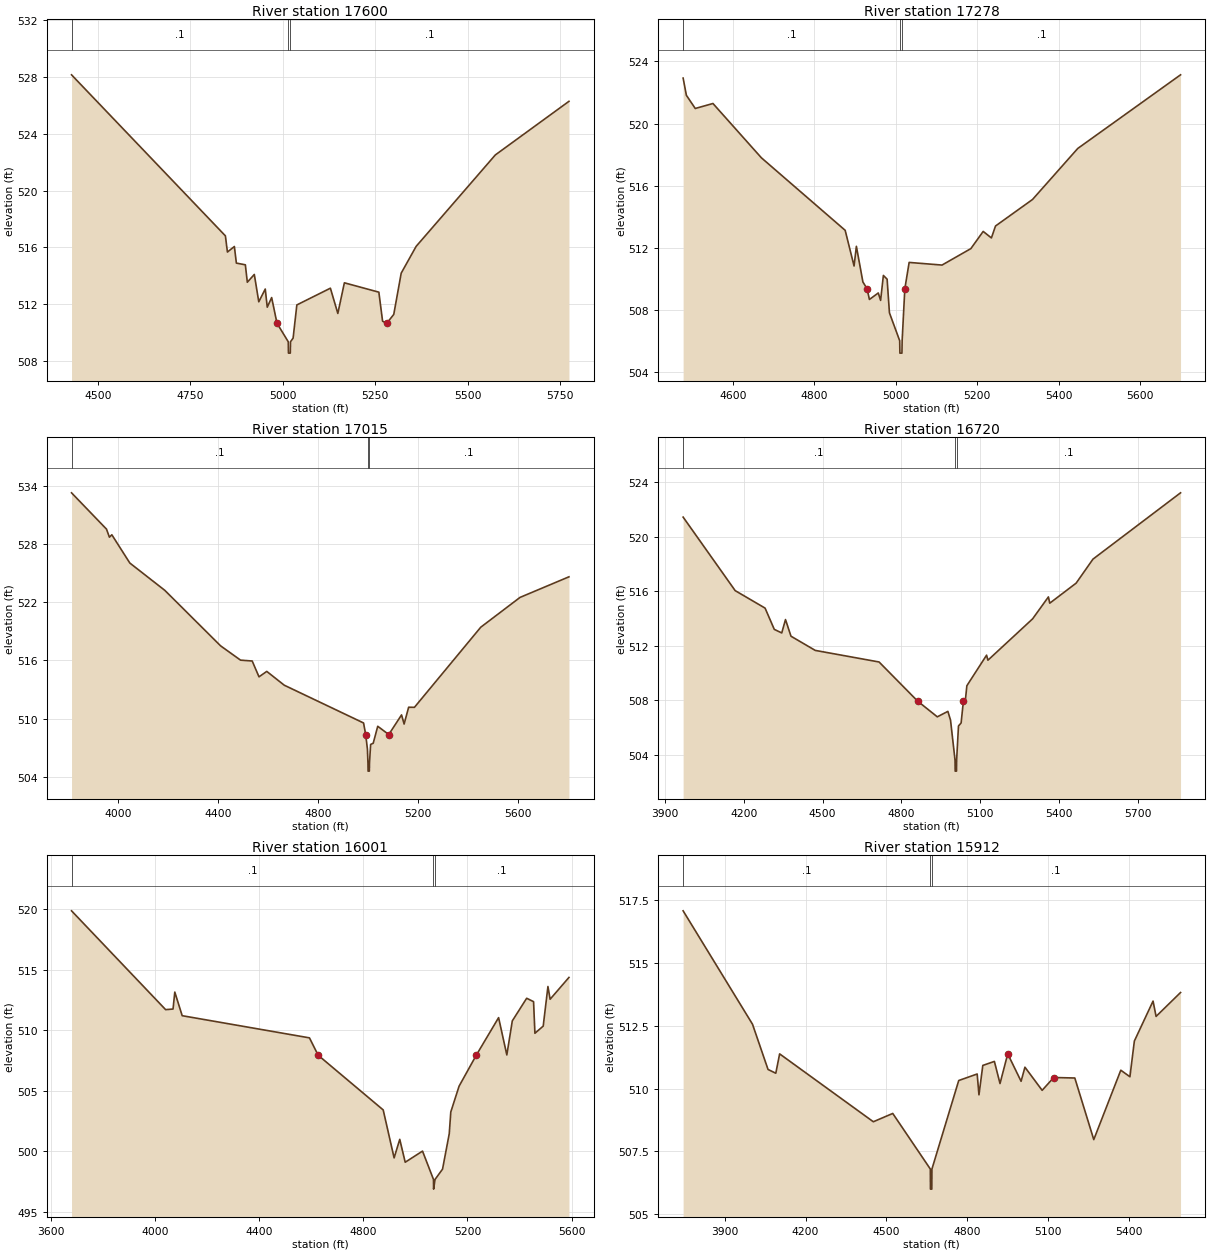
Type RM Length L Ch R = 1 ,17600   ,322,322,322
BEGIN DESCRIPTION:
UNT 185 SanMiguel Cr Watershed 41.0
END DESCRIPTION:
XS GIS Cut Line= 3
        2030175.       13481525.        2030675.       13481325.
      2030774.99     13480525.04
#Sta/Elev= 30
    4429  528.16    4845   516.8  4850.4  515.66  4869.2  516.05  4874.6  514.88
  4898.9  514.76  4904.2  513.53  4923.1  514.08  4935.2  512.15  4952.7  513.05
  4958.1  511.77    4970  512.45 4984.44510.6361  5014.9  509.33  5015.4  508.53
  5020.4  508.53  5020.9  509.33    5028  509.59  5038.1  511.93  5128.8  513.11
  5148.9  511.33  5166.6  513.49  5259.8  512.83  5269.9  510.78 5281.17510.6358
  5300.1  511.26  5320.2  514.17  5360.6  516.06  5574.7  522.51  5773.7  526.29
#Mann= 3 ,-1 , 0
    4429      .1       0  5014.9     .07       0  5020.9      .1       0
Bank Sta=4984.44,5281.17
XS Rating Curve= 0 ,0
Exp/Cntr=0.3,0.1

Type RM Length L Ch R = 1 ,17278   ,263,263,263
BEGIN DESCRIPTION:
UNT 185 SanMiguel Cr Watershed 40.0
END DESCRIPTION:
XS GIS Cut Line= 3
      2030474.97     13481675.02        2030925.       13481425.
        2030825.     13480725.03
#Sta/Elev= 30
  4477.8  522.93  4485.8  521.82  4507.6  520.97  4551.1  521.29    4670  517.79
  4875.9  513.11  4897.7  510.81  4903.4  512.08  4919.4  509.78 4929.79509.3362
  4935.4  508.65  4957.2  509.07  4962.9  508.59  4969.7   510.2  4978.9  509.96
  4984.6  507.79  5009.8  505.99  5010.3  505.19  5015.3  505.19  5015.8  505.99
  5022.4509.3365    5033  511.04  5113.8  510.87  5184.6  511.93  5214.9  513.04
  5235.1  512.62  5245.2  513.39  5336.1   515.1  5447.2  518.39  5699.7  523.14
#Mann= 3 ,-1 , 0
  4477.8      .1       0  5009.8     .07       0  5015.8      .1       0
Bank Sta=4929.79,5022.4
XS Rating Curve= 0 ,0
Exp/Cntr=0.3,0.1

Type RM Length L Ch R = 1 ,17015   ,295,295,295
BEGIN DESCRIPTION:
UNT 185 SanMiguel Cr Watershed 39.0
END DESCRIPTION:
XS GIS Cut Line= 3
      2030524.99     13482425.02        2031125.       13481425.
      2030925.01     13480625.03
#Sta/Elev= 30
  3812.7  533.25  3952.7  529.51  3964.3  528.68    3974  528.93    4046  526.02
  4185.9  523.21  4409.4  517.49  4489.1  516.02  4535.8  515.93    4563   514.3
  4594.1  514.86    4664  513.44  4981.5  509.55 4989.95508.3583  4996.9  506.86
  4999.1  505.39  4999.6  504.59  5004.6  504.59  5005.1  505.39  5009.8  507.34
  5020.1  507.46  5038.2  509.21  5082.3508.3588  5133.5  510.38  5143.8  509.44
  5161.9  511.17  5185.1  511.16  5450.5  519.41  5607.7  522.48  5803.5   524.6
#Mann= 3 ,-1 , 0
  3812.7      .1       0  4999.1     .07       0  5005.1      .1       0
Bank Sta=4989.95,5082.3
XS Rating Curve= 0 ,0
Exp/Cntr=0.3,0.1

Type RM Length L Ch R = 1 ,16720   ,719,719,719
BEGIN DESCRIPTION:
UNT 185 SanMiguel Cr Watershed 37.0
END DESCRIPTION:
XS GIS Cut Line= 4
      2030771.23     13482071.54      2031244.35     13481537.65
      2031339.83     13480782.44      2031079.69     13480452.93
#Sta/Elev= 30
  3968.7  521.43    4167  516.04  4280.8  514.76  4315.9   513.2  4344.3  512.94
  4358.6  513.92  4379.5   512.7  4471.8  511.66    4715  510.81  4862.1507.9374
  4936.7  506.79    4977  507.19  4987.1  506.55  5004.3  503.61  5004.8  502.81
  5009.8  502.81  5010.3  503.61  5017.4  506.12  5027.4  506.34 5036.07507.9366
  5044.3  508.13  5049.3  509.07  5124.4  511.31  5129.5  510.94  5299.6  513.97
  5359.9  515.58    5365  515.12  5465.5  516.59  5529.6  518.35  5863.1  523.21
#Mann= 3 ,-1 , 0
  3968.7      .1       0  5004.3     .07       0  5010.3      .1       0
Bank Sta=4862.1,5036.07
XS Rating Curve= 0 ,0
Exp/Cntr=0.3,0.1

Type RM Length L Ch R = 1 ,16001   ,89,89,89
BEGIN DESCRIPTION:
UNT 185 SanMiguel Cr Watershed 36.0
END DESCRIPTION:
XS GIS Cut Line= 3
      2030824.97     13482075.03        2031825.       13481175.
      2032001.65     13480638.33
#Sta/Elev= 30
  3679.3  519.87  4040.7  511.71  4069.1  511.76  4075.9  513.16  4104.3  511.21
  4593.1  509.38 4626.49 507.946  4876.3  503.43  4918.2  499.47  4939.9     501
  4960.8  499.11  5027.3  500.03  5069.4  497.69  5069.9  496.89  5075.4  497.69
  5104.2  498.54    5130  501.47  5135.9  503.26  5167.7  505.39  5233.7507.9462
  5319.5  511.05  5351.1  507.97  5372.1  510.78  5427.3  512.65  5453.8  512.37
    5459  509.76  5490.8  510.35    5509  513.62  5517.4  512.57  5589.7  514.37
#Mann= 3 ,-1 , 0
  3679.3      .1       0  5069.4     .07       0  5075.4      .1       0
Bank Sta=4626.49,5233.7
XS Rating Curve= 0 ,0
Exp/Cntr=0.3,0.1

Type RM Length L Ch R = 1 ,15912   ,173,173,173
BEGIN DESCRIPTION:
UNT 185 SanMiguel Cr Watershed 35.0
END DESCRIPTION:
XS GIS Cut Line= 4
      2030936.18     13482058.49       2031734.8     13481416.12
      2032055.98     13481029.84      2032090.73     13480714.83
#Sta/Elev= 30
  3746.3  517.07  4003.5  512.56  4061.1  510.76  4089.9  510.61  4104.1  511.38
  4451.5  508.68  4523.5  509.01  4662.8   506.8  4663.3     506  4668.3     506
  4668.8   506.8  4768.1  510.32  4836.5  510.58  4843.1  509.75  4857.4  510.92
  4900.3  511.08  4921.2   510.2  4949.8  511.38  4999.3  510.29  5013.6  510.85
  5077.4  509.93  5120.4  510.44  5198.5  510.42  5268.8  507.97    5369  510.73
  5402.8  510.47  5419.3  511.89  5488.6  513.48  5499.8  512.87  5590.5  513.82
#Mann= 3 ,-1 , 0
  3746.3      .1       0  4662.8     .07       0  4668.8      .1       0
Bank Sta=4949.8,5120.4
XS Rating Curve= 0 ,0
Exp/Cntr=0.3,0.1

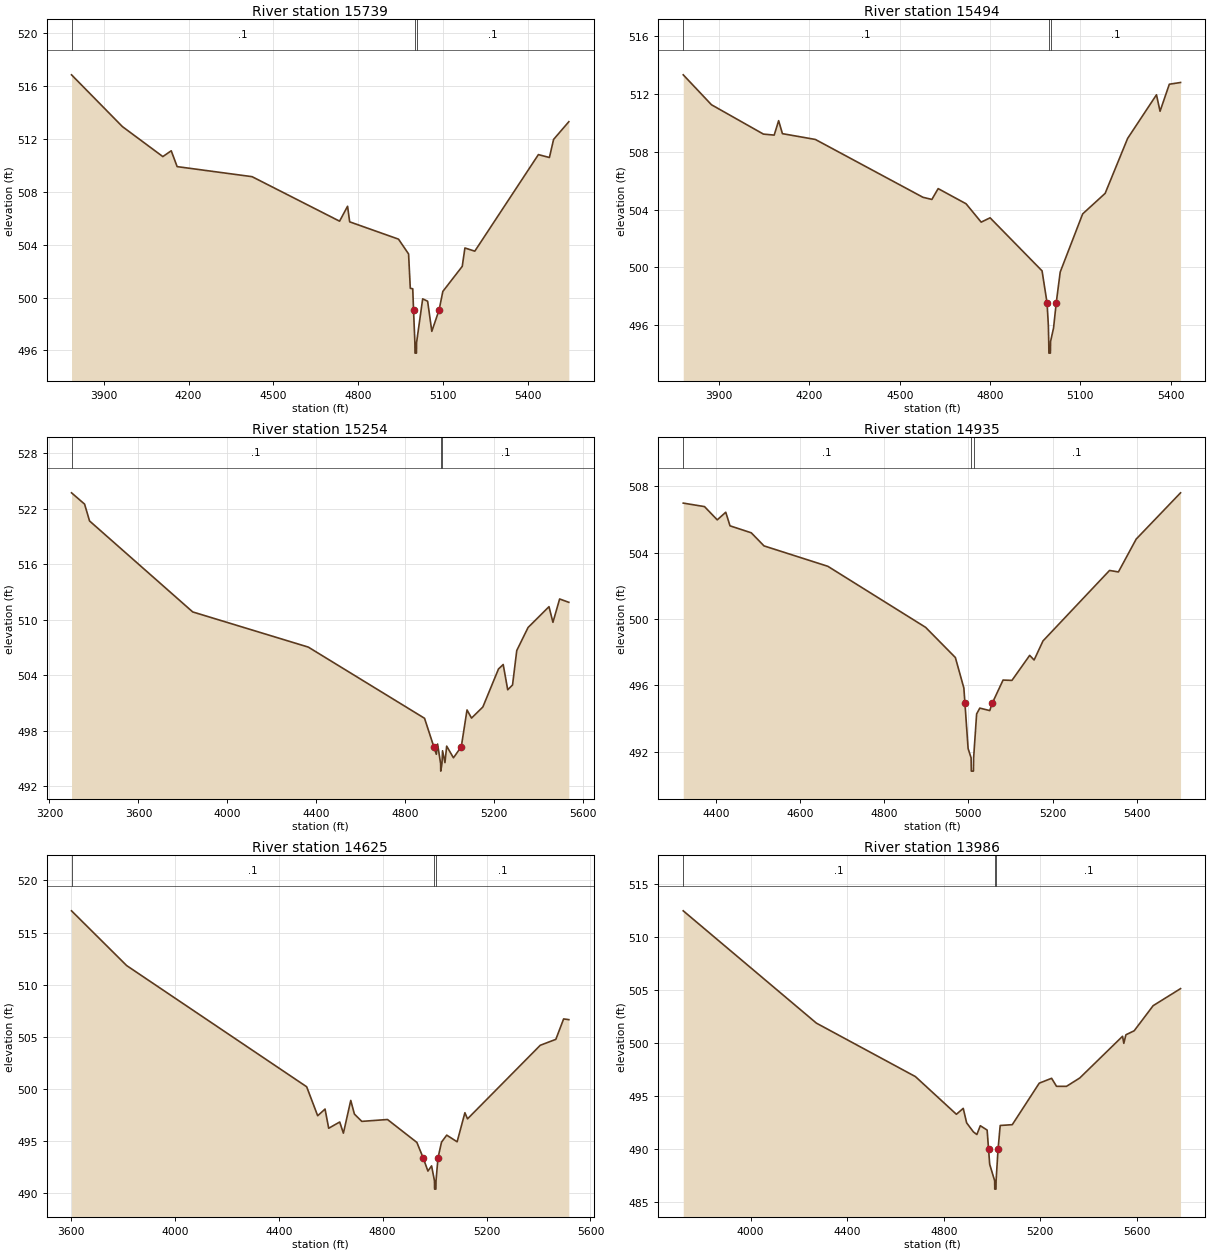
Type RM Length L Ch R = 1 ,15739   ,245,245,245
BEGIN DESCRIPTION:
UNT 185 SanMiguel Cr Watershed 34.0
END DESCRIPTION:
XS GIS Cut Line= 3
      2030975.01     13482074.99        2031975.       13481375.
      2032175.02     13480874.96
#Sta/Elev= 30
  3785.8  516.86  3965.8  512.94  4108.8  510.67  4138.5  511.11  4159.4  509.91
  4424.4  509.15    4734  505.78  4762.3  506.91  4769.7  505.73  4942.4  504.42
  4978.1   503.3  4984.2   500.7  4992.9  500.66 4995.63499.0578  5000.4  496.59
  5000.9  495.79  5005.9  495.79  5006.4  496.59    5028   499.9  5045.5  499.72
  5060.3  497.44 5086.04 499.056  5099.3  500.46    5168  502.36  5177.4  503.75
  5212.4  503.51  5437.3  510.82  5476.3   510.6  5491.1  511.97    5545  513.31
#Mann= 3 ,-1 , 0
  3785.8      .1       0  5000.4     .07       0  5006.4      .1       0
Bank Sta=4995.63,5086.04
XS Rating Curve= 0 ,0
Exp/Cntr=0.3,0.1

Type RM Length L Ch R = 1 ,15494   ,240,240,240
BEGIN DESCRIPTION:
UNT 185 SanMiguel Cr Watershed 33.0
END DESCRIPTION:
XS GIS Cut Line= 3
      2031174.97     13482075.02        2032175.       13481375.
      2032325.11     13480970.02
#Sta/Elev= 30
  3780.6  513.32  3874.4  511.25    4047  509.22  4082.8  509.15  4097.6  510.15
  4110.2  509.25  4219.6  508.85  4577.1  504.85  4606.8   504.7  4627.7  505.45
  4720.5   504.4  4770.7  503.13  4800.3  503.43    4973  499.76 4989.64497.5403
  4993.9  495.99  4995.2  494.87  4995.7  494.07  5000.7  494.07  5001.2  494.87
  5011.2  495.81 5020.07497.5422  5033.3  499.68  5107.9   503.7  5182.6  505.12
  5257.3  508.92  5353.2  511.94  5365.1   510.8  5395.9  512.67  5433.2  512.79
#Mann= 3 ,-1 , 0
  3780.6      .1       0  4995.2     .07       0  5001.2      .1       0
Bank Sta=4989.64,5020.07
XS Rating Curve= 0 ,0
Exp/Cntr=0.3,0.1

Type RM Length L Ch R = 1 ,15254   ,319,319,319
BEGIN DESCRIPTION:
UNT 185 SanMiguel Cr Watershed 32.0
END DESCRIPTION:
XS GIS Cut Line= 3
      2030824.96     13482325.02        2032325.       13481575.
      2032426.67     13481024.71
#Sta/Elev= 30
  3299.1   523.7  3357.8  522.48  3380.2  520.66  3844.2  510.83  4364.1  507.03
  4886.8  499.34 4928.51496.2687  4939.9  495.45  4945.5  496.56  4959.2  494.43
  4959.7  493.63  4965.2  494.43  4967.8  495.83  4978.7  494.55  4986.4  496.33
  5016.9  495.07 5052.12496.2686  5077.9  500.24  5098.2  499.36  5149.1  500.56
  5219.5  504.67  5240.6  505.15  5260.9  502.42  5282.6  502.94  5301.6  506.66
  5352.5  509.15  5446.6   511.4  5464.3  509.71  5494.4  512.23  5535.8  511.87
#Mann= 3 ,-1 , 0
  3299.1      .1       0  4959.2     .07       0  4965.2      .1       0
Bank Sta=4928.51,5052.12
XS Rating Curve= 0 ,0
Exp/Cntr=0.3,0.1

Type RM Length L Ch R = 1 ,14935   ,310,310,310
BEGIN DESCRIPTION:
UNT 185 SanMiguel Cr Watershed 31.0
END DESCRIPTION:
XS GIS Cut Line= 3
      2031724.99       13481925.        2032425.       13481825.
      2032575.01     13481374.96
#Sta/Elev= 30
  4322.7  506.99  4373.2  506.78  4403.5  505.98  4423.7  506.44  4433.8  505.62
  4484.3   505.2  4514.6  504.41  4666.2  503.18  4898.5   499.5  4969.2  497.68
  4989.4  495.84 4991.89494.9401  4999.5  492.19  5006.6  491.63  5007.1  490.83
  5012.1  490.83  5012.6  491.63  5019.7  494.28  5027.3  494.63  5050.9  494.48
 5057.09494.9398  5082.5  496.32  5103.6   496.3  5145.8  497.81  5156.3  497.53
  5177.4  498.68  5335.5  502.93  5356.6  502.84  5398.8  504.82  5504.2  507.61
#Mann= 3 ,-1 , 0
  4322.7      .1       0  5006.6     .07       0  5012.6      .1       0
Bank Sta=4991.89,5057.09
XS Rating Curve= 0 ,0
Exp/Cntr=0.3,0.1

Type RM Length L Ch R = 1 ,14625   ,639,639,639
BEGIN DESCRIPTION:
UNT 185 SanMiguel Cr Watershed 30.0
END DESCRIPTION:
XS GIS Cut Line= 3
      2031625.02     13482924.98        2032625.       13481925.
        2032625.     13481424.99
#Sta/Elev= 30
  3602.6  517.09  3814.7  511.84  4507.7  500.21  4550.1  497.43  4578.4  498.07
  4592.5  496.23  4634.9  496.83  4649.1  495.76  4677.4   498.9  4691.5  497.59
  4719.8  496.89  4818.8  497.07  4931.9  494.87  4956.3493.3802  4974.4  492.12
  4988.5  492.62  4999.6  491.19  5000.1  490.39  5005.1  490.39  5005.6  491.19
 5013.13493.3806  5026.8   494.9  5046.8  495.57  5086.8  494.93  5116.8  497.72
  5126.8  497.13  5406.8  504.19  5466.8  504.76  5496.8  506.72  5516.8  506.65
#Mann= 3 ,-1 , 0
  3602.6      .1       0  4999.6     .07       0  5005.6      .1       0
Bank Sta=4956.3,5013.13
XS Rating Curve= 0 ,0
Exp/Cntr=0.3,0.1

Type RM Length L Ch R = 1 ,13986   ,333,333,333
BEGIN DESCRIPTION:
UNT 185 SanMiguel Cr Watershed 29.0
END DESCRIPTION:
XS GIS Cut Line= 4
      2032074.99     13483125.01        2032975.       13482225.
      2032981.23     13482087.49      2032836.99     13481454.37
#Sta/Elev= 30
  3721.2  512.49  4272.8  501.88  4682.9  496.83  4852.6  493.27  4880.9  493.83
    4895  492.46  4923.3   491.6  4937.4  491.36  4951.6  492.19  4979.9  491.78
  4985.9 489.946  4990.5  488.54    5011     487  5011.5   486.2  5016.5   486.2
    5017     487 5025.05489.9456    5034  492.21  5084.1  492.29  5195.7  496.21
    5247  496.67  5267.3  495.91  5308.6  495.91  5363.6   496.7  5540.8  500.64
    5546  499.97  5554.7  500.78    5589  501.16  5667.5  503.53    5781  505.14
#Mann= 3 ,-1 , 0
  3721.2      .1       0    5011     .07       0    5017      .1       0
Bank Sta=4985.9,5025.05
XS Rating Curve= 0 ,0
Exp/Cntr=0.3,0.1

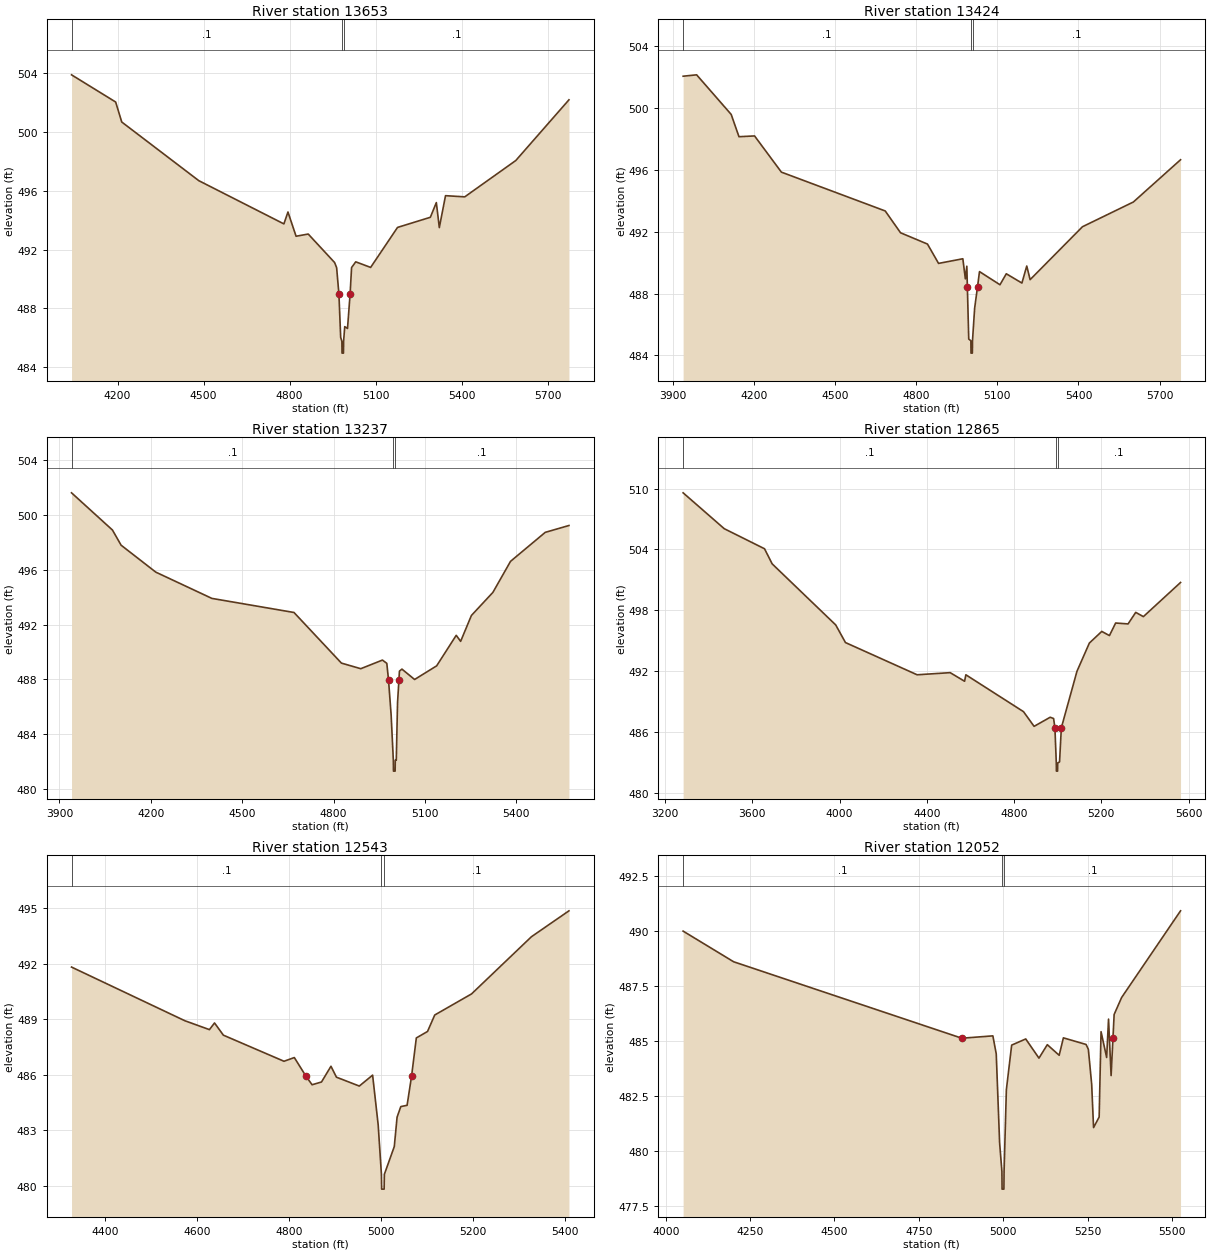
Type RM Length L Ch R = 1 ,13653   ,229,229,229
BEGIN DESCRIPTION:
UNT 185 SanMiguel Cr Watershed 28.0
END DESCRIPTION:
XS GIS Cut Line= 3
      2032486.32     13482943.99        2033175.       13482275.
      2032958.52     13481530.76
#Sta/Elev= 30
  4039.4  503.89  4193.3  502.04  4214.6  500.68  4483.4  496.69  4780.2  493.75
  4794.4  494.56  4822.7  492.91  4865.1  493.06  4957.2  491.12  4964.2  490.77
 4972.16488.9683  4978.3  486.03  4982.5  485.76    4983  484.96    4988  484.96
  4988.5  485.76  4992.4  486.76  5002.1  486.64 5011.15488.9695  5016.3  490.78
  5030.8  491.17  5082.8  490.79  5176.6  493.51  5291.1   494.2    5312   495.2
  5322.4   493.5    5344  495.67  5411.1  495.59  5589.1  498.06  5774.6  502.19
#Mann= 3 ,-1 , 0
  4039.4      .1       0  4982.5     .07       0  4988.5      .1       0
Bank Sta=4972.16,5011.15
XS Rating Curve= 0 ,0
Exp/Cntr=0.3,0.1

Type RM Length L Ch R = 1 ,13424   ,187,187,187
BEGIN DESCRIPTION:
UNT 185 SanMiguel Cr Watershed 27.0
END DESCRIPTION:
XS GIS Cut Line= 4
      2032615.88     13482956.92      2033301.64     13482410.05
      2033462.23     13482041.12      2033314.85     13481499.28
#Sta/Elev= 30
  3936.8  502.05  3986.8  502.14  4114.7  499.58  4143.5  498.14  4201.2  498.19
  4300.5  495.85  4684.8  493.34  4741.5  491.93  4841.2   491.2  4882.2  489.95
  4972.1  490.25  4981.4  488.95  4986.8  489.77 4988.79488.4497  4993.9  485.06
  5001.8  484.95  5002.3  484.15  5007.3  484.15  5007.8  484.95  5015.7  487.05
 5026.53488.4509  5033.7  489.42  5109.5  488.57  5132.9  489.28  5190.7  488.68
  5208.6  489.78  5221.1   488.9  5414.8  492.32  5603.3  493.92  5777.8  496.65
#Mann= 3 ,-1 , 0
  3936.8      .1       0  5001.8     .07       0  5007.8      .1       0
Bank Sta=4988.79,5026.53
XS Rating Curve= 0 ,0
Exp/Cntr=0.3,0.1

Type RM Length L Ch R = 1 ,13237   ,372,372,372
BEGIN DESCRIPTION:
UNT 185 SanMiguel Cr Watershed 26.0
END DESCRIPTION:
XS GIS Cut Line= 3
      2032724.97     13482975.02        2033525.       13482275.
      2033974.97     13481925.02
#Sta/Elev= 30
  3939.6  501.63  4073.9  498.91  4102.4   497.8  4216.3  495.83  4400.4  493.91
    4670  492.88  4825.6  489.18  4889.2  488.77  4960.4   489.4  4974.7  489.16
 4980.26487.9638  4988.9  485.39  4996.1  482.08  4996.6  481.28    5002  481.28
  5002.5  482.08  5005.8  482.08  5009.9  486.27  5014.5487.9639  5016.2  488.59
  5024.4  488.74    5066  487.98  5138.4  488.98  5202.6  491.21  5217.1  490.77
  5252.4  492.66    5323  494.35  5380.9  496.62  5494.9  498.74  5572.7  499.24
#Mann= 3 ,-1 , 0
  3939.6      .1       0  4996.1     .07       0  5002.5      .1       0
Bank Sta=4980.26,5014.5
XS Rating Curve= 0 ,0
Exp/Cntr=0.3,0.1

Type RM Length L Ch R = 1 ,12865   ,322,322,322
BEGIN DESCRIPTION:
UNT 185 SanMiguel Cr Watershed 25.0
END DESCRIPTION:
XS GIS Cut Line= 3
        2032375.       13483275.        2033875.       13482375.
      2034225.01     13481974.99
#Sta/Elev= 30
  3282.6  509.59  3471.1  506.05  3655.8  504.07  3690.8  502.58  3982.3  496.55
    4027  494.81  4355.5  491.63  4507.1  491.84  4573.2  490.99    4579  491.63
  4843.3  487.99  4891.9  486.54  4965.8  487.44  4981.3  487.31 4987.41 486.394
  4993.7  482.92  4994.2  482.12  4999.6  482.12  5000.1  482.92  5008.6  483.03
  5016.8486.3945  5088.4  491.97  5145.3  494.76  5202.2  495.91  5237.4   495.5
  5265.8  496.74  5322.8  496.65  5357.9  497.79    5393  497.37  5563.4  500.74
#Mann= 3 ,-1 , 0
  3282.6      .1       0  4993.7     .07       0  5000.1      .1       0
Bank Sta=4987.41,5016.8
XS Rating Curve= 0 ,0
Exp/Cntr=0.3,0.1

Type RM Length L Ch R = 1 ,12543   ,491,491,491
BEGIN DESCRIPTION:
UNT 185 SanMiguel Cr Watershed 24.0
END DESCRIPTION:
XS GIS Cut Line= 4
      2033299.17     13482792.72       2033794.6     13482706.47
      2034005.71     13482655.78      2034034.25     13482293.59
#Sta/Elev= 30
  4326.2  491.81    4573  488.91  4626.5  488.43  4637.6  488.79  4656.9  488.13
  4788.9  486.72  4811.4  486.92 4836.22485.9339  4850.1  485.45  4870.6   485.6
  4891.2  486.45  4903.1  485.86  4952.9  485.38  4981.9  485.97    4994  483.29
  5001.1  480.61  5001.6  479.81    5007  479.81  5007.5  480.61  5029.1  482.11
  5035.2   483.7  5043.3  484.27    5057  484.34 5066.84485.9341  5077.1  487.98
  5101.5  488.33  5117.2  489.22  5197.4  490.36  5327.8  493.45  5409.5  494.85
#Mann= 3 ,-1 , 0
  4326.2      .1       0  5001.1     .07       0  5007.5      .1       0
Bank Sta=4836.22,5066.84
XS Rating Curve= 0 ,0
Exp/Cntr=0.3,0.1

Type RM Length L Ch R = 1 ,12052   ,711,711,711
BEGIN DESCRIPTION:
UNT 185 SanMiguel Cr Watershed 23.0
END DESCRIPTION:
XS GIS Cut Line= 6
      2033923.53     13483907.23      2034128.97     13483102.19
      2034127.02     13482958.74      2034101.38     13482905.49
      2034064.12     13482763.59      2034198.13     13482501.81
#Sta/Elev= 30
  4051.5  489.98  4201.2  488.59 4877.52485.1229  4969.5  485.23  4979.5  484.41
  4989.5  480.38  4996.3  479.08  4996.8  478.28  5002.2  478.28  5002.7  479.08
  5009.5  482.79  5025.2  484.81  5066.9  485.09  5106.1  484.22  5130.8  484.83
    5166  484.35  5178.5  485.14  5245.7  484.84  5252.5  484.62  5262.3  483.04
  5267.9  481.07  5284.5  481.55  5290.1  485.42  5306.7  484.25  5312.3  485.99
  5319.9  483.43  5325.4485.1228  5328.9   486.2  5351.1  486.97  5525.7   490.9
#Mann= 3 ,-1 , 0
  4051.5      .1       0  4996.3     .07       0  5002.7      .1       0
Bank Sta=4877.52,5325.4
XS Rating Curve= 0 ,0
Exp/Cntr=0.3,0.1

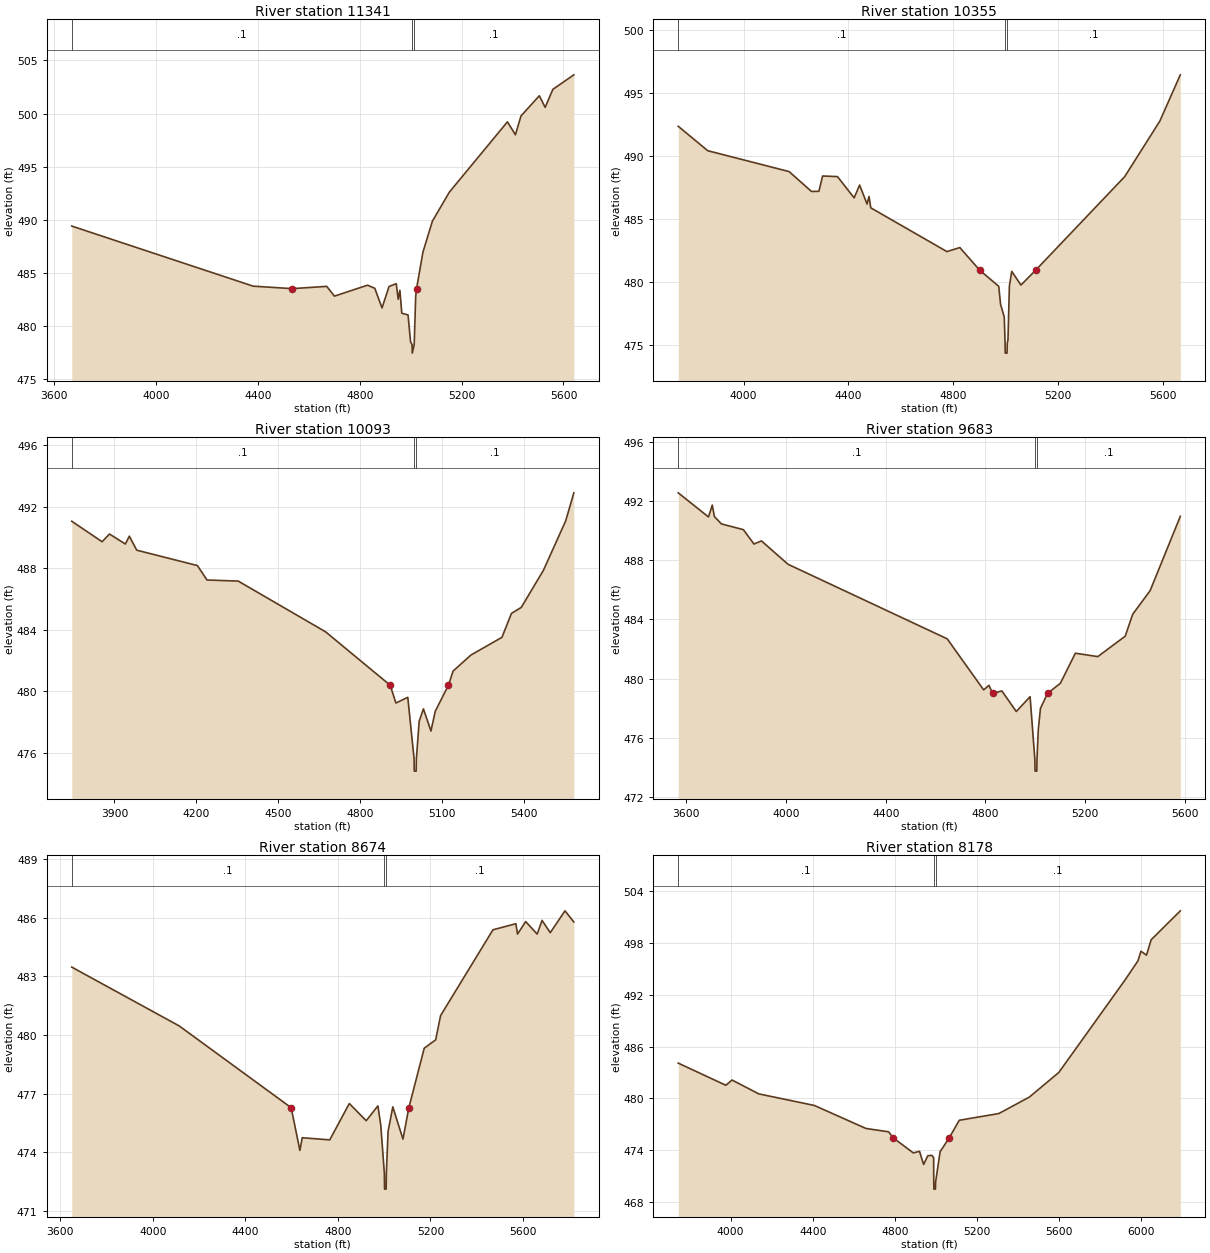
Type RM Length L Ch R = 1 ,11341   ,986,986,986
BEGIN DESCRIPTION:
UNT 185 SanMiguel Cr Watershed 22.0
END DESCRIPTION:
XS GIS Cut Line= 6
      2034031.14     13483907.31      2034406.16      13483053.1
      2034384.03     13482873.56      2034256.83      13482731.3
      2034255.79     13482653.17      2034538.79     13482136.13
#Sta/Elev= 30
  3668.6   489.4    4381  483.74 4534.39 483.507  4670.1  483.72  4700.3   482.8
  4830.4  483.83  4858.9  483.54  4887.3  481.69  4914.9  483.71  4943.3  483.97
  4950.8  482.51  4957.5  483.35    4965  481.19  4989.5  481.03  4999.5  478.49
  5005.4  478.23  5006.1  477.43  5013.7  478.23  5019.5  482.74    5023483.5065
    5048  486.94  5085.1  489.86  5151.9   492.6  5379.9  499.22  5411.3     498
  5433.1  499.77  5505.3  501.68  5528.1  500.58  5558.3  502.28  5640.8  503.65
#Mann= 3 ,-1 , 0
  3668.6      .1       0  5005.4     .07       0  5013.7      .1       0
Bank Sta=4534.39,5023
XS Rating Curve= 0 ,0
Exp/Cntr=0.3,0.1

Type RM Length L Ch R = 1 ,10355   ,262,262,262
BEGIN DESCRIPTION:
UNT 185 SanMiguel Cr Watershed 21.0
END DESCRIPTION:
XS GIS Cut Line= 4
      2033840.49       13484199.      2034744.17     13483389.08
      2034781.93     13483352.62      2035225.01     13482874.99
#Sta/Elev= 30
  3750.3  492.38  3862.9  490.44  4173.8  488.78  4259.1   487.2  4287.5  487.21
  4301.7  488.43  4358.5  488.38  4422.1  486.69    4443  487.71  4471.4   486.2
  4478.9   486.8  4485.6   485.9  4776.4  482.42  4825.8  482.74 4901.77480.9385
  4974.4  479.66  4981.3  478.24  4995.5  477.21  4998.5  475.15  4999.2  474.35
  5006.1  474.35  5006.9  475.15  5009.6   475.4    5015  479.67    5024  480.85
  5059.2  479.76  5115.2480.9388  5455.5  488.38  5589.8   492.8  5667.8  496.47
#Mann= 3 ,-1 , 0
  3750.3      .1       0  4998.5     .07       0  5006.9      .1       0
Bank Sta=4901.77,5115.2
XS Rating Curve= 0 ,0
Exp/Cntr=0.3,0.1

Type RM Length L Ch R = 1 ,10093   ,410,410,410
BEGIN DESCRIPTION:
UNT 185 SanMiguel Cr Watershed 20.0
END DESCRIPTION:
XS GIS Cut Line= 3
      2033986.29     13484240.97       2035005.8     13483462.34
      2035275.01     13482974.99
#Sta/Elev= 30
  3743.7  491.07  3854.8  489.74  3881.9  490.24  3940.1  489.59  3954.6   490.1
  3981.7  489.19    4204  488.19  4239.3  487.25  4353.6  487.18  4673.7  483.88
 4910.32 480.407  4931.4  479.25  4974.9  479.62  4997.9  475.62  4998.6  474.82
  5005.6  474.82  5006.3  475.62  5016.6  478.06  5032.2  478.87  5059.7  477.43
  5075.7  478.72 5123.82480.4072    5141  481.33  5206.3  482.37  5319.8  483.52
  5354.8  485.08  5390.8  485.47  5472.1  487.89  5553.5   491.1  5583.3  492.92
#Mann= 3 ,-1 , 0
  3743.7      .1       0  4997.9     .07       0  5006.3      .1       0
Bank Sta=4910.32,5123.82
XS Rating Curve= 0 ,0
Exp/Cntr=0.3,0.1

Type RM Length L Ch R = 1 ,9683    ,1009,1009,1009
BEGIN DESCRIPTION:
UNT 185 SanMiguel Cr Watershed 19.0
END DESCRIPTION:
XS GIS Cut Line= 4
      2034112.17     13484371.18      2035307.88     13483621.02
        2035325.     13483597.41      2035320.99     13483024.04
#Sta/Elev= 30
  3567.4  492.55  3688.8  490.92  3703.9  491.72  3712.4  490.95  3740.4  490.45
  3828.8  490.06  3871.2  489.09  3901.3   489.3  4007.9  487.72  4646.5  482.68
  4792.6  479.23  4813.8  479.54 4828.67478.9917  4865.7  479.16  4923.4  477.77
  4978.9  478.77    4998  474.54  4998.8  473.74  5005.8  473.74  5006.5  474.54
  5011.8  476.55  5020.5  477.98 5048.95478.9916  5100.5  479.68  5160.5  481.71
  5250.5  481.48  5360.5  482.86  5390.5  484.34  5460.5  485.94  5581.5  490.96
#Mann= 3 ,-1 , 0
  3567.4      .1       0    4998     .07       0  5006.5      .1       0
Bank Sta=4828.67,5048.95
XS Rating Curve= 0 ,0
Exp/Cntr=0.3,0.1

Type RM Length L Ch R = 1 ,8674    ,496,496,496
BEGIN DESCRIPTION:
UNT 185 SanMiguel Cr Watershed 18.0
END DESCRIPTION:
XS GIS Cut Line= 4
      2035001.95     13484105.22       2036044.7     13484180.88
      2036151.72     13483845.68      2035604.87     13483300.99
#Sta/Elev= 30
  3650.2  483.48  4114.5  480.47 4598.17476.2866  4635.8   474.1  4645.9  474.75
  4764.8  474.64  4849.4   476.5  4922.3  475.62  4972.9  476.38  4985.3  475.39
  5000.8  472.92  5001.5  472.12  5008.5  472.12  5009.3  472.92  5016.8  475.07
  5037.2  476.33  5081.1  474.68 5106.54476.2867    5173  479.33  5222.5  479.76
  5243.7     481    5470  485.39    5569   485.7  5576.1  485.17  5611.4  485.81
  5660.9  485.17  5682.1  485.87  5717.5  485.24  5781.1  486.36  5819.4  485.79
#Mann= 3 ,-1 , 0
  3650.2      .1       0  5000.8     .07       0  5009.3      .1       0
Bank Sta=4598.17,5106.54
XS Rating Curve= 0 ,0
Exp/Cntr=0.3,0.1

Type RM Length L Ch R = 1 ,8178    ,808,808,808
BEGIN DESCRIPTION:
UNT 185 SanMiguel Cr Watershed 17.0
END DESCRIPTION:
XS GIS Cut Line= 3
      2034923.85     13484162.52        2036225.       13484275.
      2037125.02     13483574.99
#Sta/Elev= 30
  3744.5  484.08  3976.5  481.51  4006.6  482.12  4137.1  480.51  4407.5  479.17
    4659   476.5  4769.5  476.11 4792.41475.4002  4889.9  473.66    4920  473.85
  4940.1  472.32  4960.2  473.33  4980.2  473.38  4988.9   473.1  4989.4  470.26
  4990.2  469.46  4997.5  469.46  4998.3  470.26  5020.4   473.8 5064.44475.4001
  5113.8  477.45  5306.6  478.23  5455.9  480.15  5598.9     483  5920.1  493.68
  5984.4  495.95  5998.8  497.06    6026  496.61  6048.6  498.39  6190.7  501.75
#Mann= 3 ,-1 , 0
  3744.5      .1       0  4989.4     .07       0  4998.3      .1       0
Bank Sta=4792.41,5064.44
XS Rating Curve= 0 ,0
Exp/Cntr=0.3,0.1

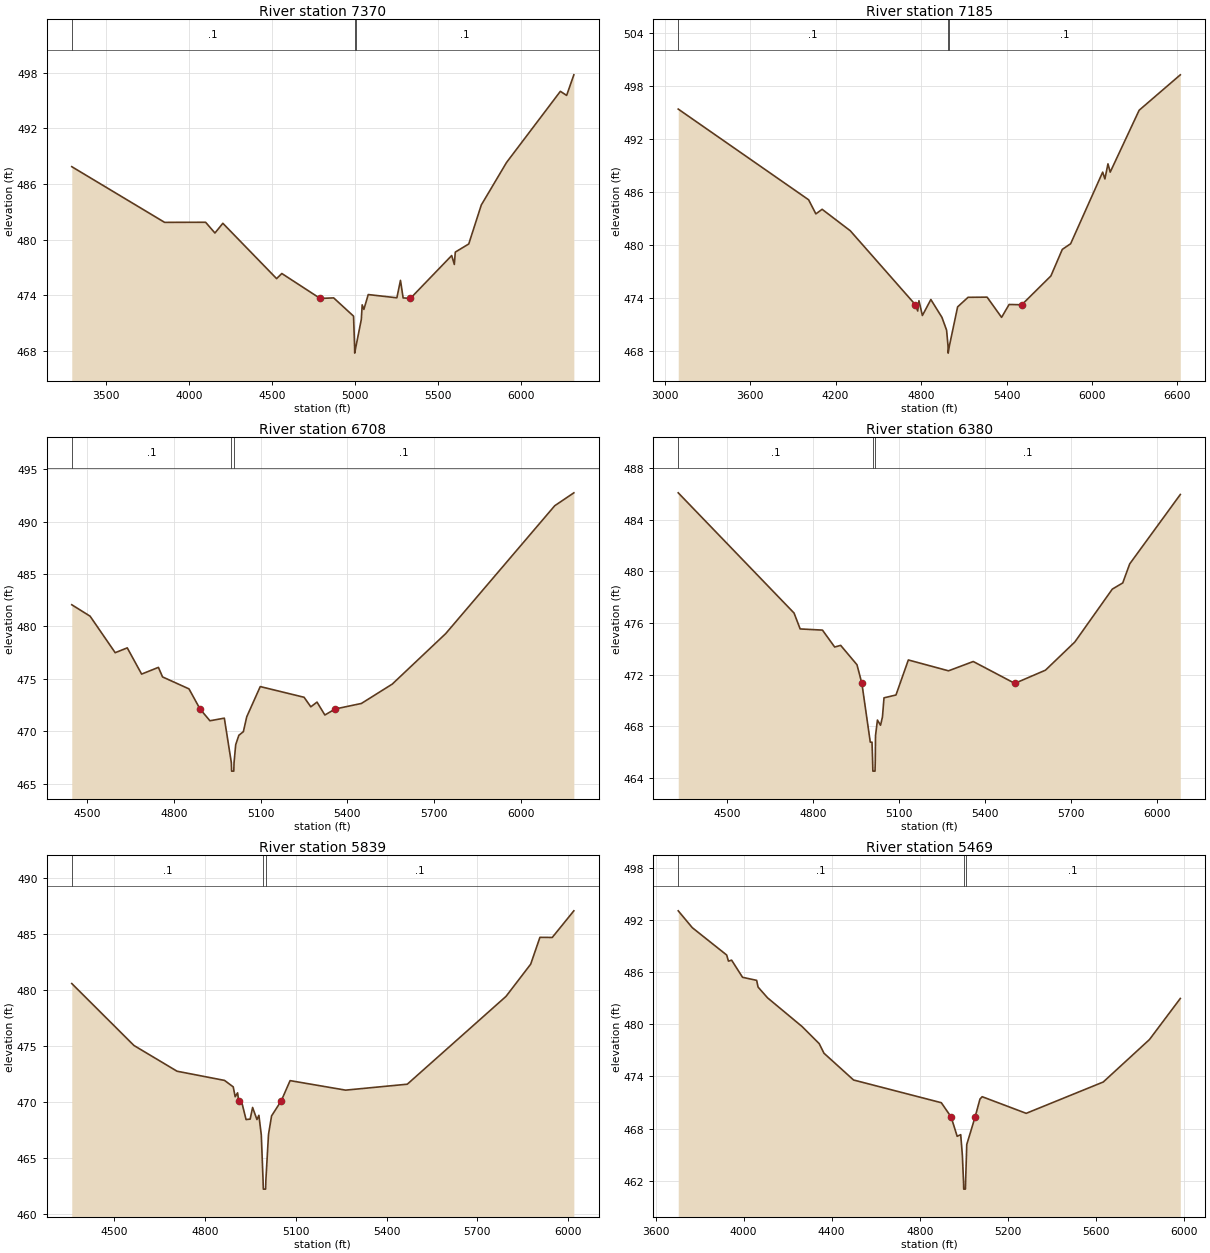
Type RM Length L Ch R = 1 ,7370    ,185,185,185
BEGIN DESCRIPTION:
UNT 185 SanMiguel Cr Watershed 16.0
END DESCRIPTION:
XS GIS Cut Line= 4
      2034699.93     13484295.34      2035611.83     13484572.37
      2036553.67     13484802.41      2037090.62     13483841.08
#Sta/Elev= 30
  3293.1  487.88  3852.3  481.87  4099.1  481.88  4155.4  480.72    4203  481.77
  4526.7   475.8  4558.2  476.35 4788.99473.6613  4870.3  473.72  4990.1  471.75
  4996.3  468.56  4997.1  467.76  5005.5  468.56  5036.9   471.4  5042.1  472.97
  5052.3  472.48  5078.6  474.08    5251  473.73  5272.7  475.61  5288.7  473.72
 5332.15473.6613  5581.1  478.29  5597.1  477.33  5602.8  478.66  5683.9  479.54
  5759.3  483.74  5911.4  488.33  6235.7  496.01  6273.4  495.57  6316.8  497.79
#Mann= 3 ,-1 , 0
  3293.1      .1       0  4996.3     .07       0  5005.5      .1       0
Bank Sta=4788.99,5332.15
XS Rating Curve= 0 ,0
Exp/Cntr=0.3,0.1

Type RM Length L Ch R = 1 ,7185    ,477,477,477
BEGIN DESCRIPTION:
UNT 185 SanMiguel Cr Watershed 15.0
END DESCRIPTION:
XS GIS Cut Line= 4
      2034424.71     13484953.01      2035856.96     13484791.56
      2036528.84     13484994.68      2037226.74       13483802.
#Sta/Elev= 30
    3095  495.43  4010.3  485.16  4061.4  483.56  4105.3  484.08  4302.9  481.65
  4760.2473.2675  4776.3  472.56    4785  473.73  4809.3  472.05  4868.6  473.86
  4946.3  471.85  4979.2  470.39  4989.3  468.59  4990.2  467.79  4998.5  468.59
  5056.6  473.03  5129.8  474.11  5263.6  474.13  5365.3  471.84  5418.1   473.3
 5507.06473.2676  5711.4  476.53  5791.6  479.54  5850.2  480.18    6075  488.29
  6090.7  487.52  6112.2  489.23  6127.9  488.29  6331.2   495.3  6620.1  499.31
#Mann= 3 ,-1 , 0
    3095      .1       0  4989.3     .07       0  4998.5      .1       0
Bank Sta=4760.2,5507.06
XS Rating Curve= 0 ,0
Exp/Cntr=0.3,0.1

Type RM Length L Ch R = 1 ,6708    ,328,328,328
BEGIN DESCRIPTION:
UNT 185 SanMiguel Cr Watershed 14.0
END DESCRIPTION:
XS GIS Cut Line= 3
      2036174.98     13485625.02        2036525.       13485175.
        2037125.     13484175.01
#Sta/Elev= 30
  4446.8  482.07  4510.2  480.98    4597   477.5  4638.7  477.96  4688.4  475.46
  4746.4   476.1  4760.8  475.19  4852.2  474.05 4890.34472.1352  4924.6  471.01
  4974.4  471.26  4998.7  467.01  4999.6  466.21  5007.1  466.21    5008  467.01
  5013.7  468.73  5024.7  469.63  5040.2  469.97  5051.9  471.39  5098.6  474.27
  5250.2  473.25  5273.5  472.34  5294.9  472.79  5322.1  471.56 5357.89472.1351
  5448.4  472.66  5555.3  474.51    5740  479.32    6117  491.51  6183.1  492.74
#Mann= 3 ,-1 , 0
  4446.8      .1       0  4998.7     .07       0    5008      .1       0
Bank Sta=4890.34,5357.89
XS Rating Curve= 0 ,0
Exp/Cntr=0.3,0.1

Type RM Length L Ch R = 1 ,6380    ,541,541,541
BEGIN DESCRIPTION:
UNT 185 SanMiguel Cr Watershed 13.0
END DESCRIPTION:
XS GIS Cut Line= 3
      2036225.02     13485924.97        2036675.       13485425.
      2037075.01     13484424.98
#Sta/Elev= 30
    4330  486.07  4733.6  476.77  4754.9  475.54  4832.6  475.45  4875.2  474.14
  4896.1  474.27  4952.9  472.77 4970.02471.3278  4999.3  466.78  5005.3  466.78
  5007.4  465.34  5008.3  464.54  5015.8  464.54  5016.7  465.34  5017.5  467.28
  5024.2  468.49    5035  468.09  5041.7  468.73  5047.1  470.21  5088.8  470.43
  5131.9  473.14  5271.9   472.3  5358.1  473.02 5502.89471.3283  5609.8  472.35
  5712.1  474.53  5842.7  478.62  5879.1   479.1  5903.3  480.57  6079.7  485.94
#Mann= 3 ,-1 , 0
    4330      .1       0  5007.4     .07       0  5016.7      .1       0
Bank Sta=4970.02,5502.89
XS Rating Curve= 0 ,0
Exp/Cntr=0.3,0.1

Type RM Length L Ch R = 1 ,5839    ,370,370,370
BEGIN DESCRIPTION:
UNT 185 SanMiguel Cr Watershed 12.0
END DESCRIPTION:
XS GIS Cut Line= 3
      2036574.99     13485925.01        2036975.       13485425.
      2037174.99     13484425.03
#Sta/Elev= 30
  4359.2  480.58  4564.9  475.04  4707.4  472.74  4864.3  471.92  4893.1  471.34
  4899.5  470.46  4907.5  470.81 4911.15  470.08  4921.9   469.9  4935.5  468.42
  4949.1  468.46  4957.1   469.5  4971.5  468.42  4977.9   468.8  4985.9  467.04
  4991.7     463  4992.6   462.2  5000.1   462.2    5001     463  5009.7  467.09
  5019.9  468.75 5051.59470.0801  5081.1   471.9  5264.7  471.05  5468.6  471.58
    5795  479.43  5876.6  482.31  5907.2  484.71  5947.9   484.7  6019.3  487.08
#Mann= 3 ,-1 , 0
  4359.2      .1       0  4991.7     .07       0    5001      .1       0
Bank Sta=4911.15,5051.59
XS Rating Curve= 0 ,0
Exp/Cntr=0.3,0.1

Type RM Length L Ch R = 1 ,5469    ,338,338,338
BEGIN DESCRIPTION:
UNT 185 SanMiguel Cr Watershed 11.0
END DESCRIPTION:
XS GIS Cut Line= 3
      2036274.99     13486375.01        2037275.       13485575.
        2037275.     13484575.04
#Sta/Elev= 30
  3703.1  493.03  3767.1  491.09  3923.2  487.95  3931.2  487.25  3945.6  487.36
  3995.3  485.39  4059.3  485.04  4065.7  484.27  4108.9  483.03  4265.8  479.73
  4343.4  477.77    4365  476.67  4499.5  473.59  4898.1  470.98 4942.71469.3402
  4970.1  467.12  4986.2  467.31  4993.7  464.96  4999.1  461.85  4999.9  461.05
  5007.5  461.05  5008.4  461.85  5013.7  466.18 5051.59469.3404  5073.7   471.4
  5083.7  471.67  5283.7  469.76  5633.7  473.36  5843.7  478.24  5983.7  482.96
#Mann= 3 ,-1 , 0
  3703.1      .1       0  4999.1     .07       0  5008.4      .1       0
Bank Sta=4942.71,5051.59
XS Rating Curve= 0 ,0
Exp/Cntr=0.3,0.1