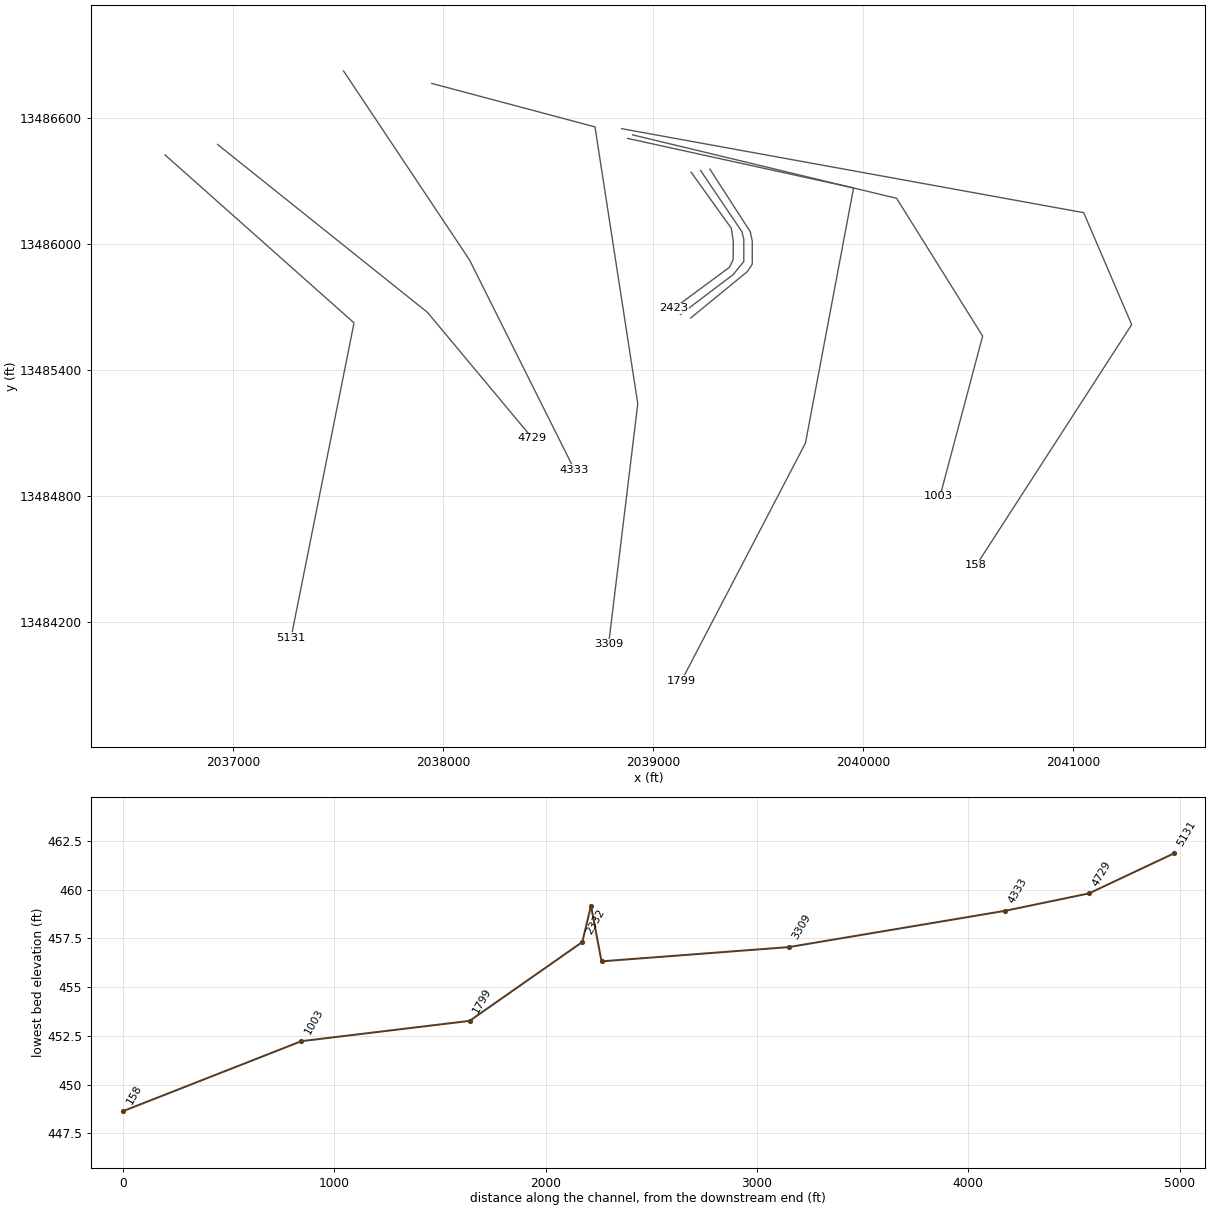
HEC-RAS study UNT 185 SanMiguel Cr Watershed.prj: UNT 185 SanMiguel Cr Watershed Base Level Engineering

--- UNT 185 SanMiguel Cr Watershed.g01 (geometry) --- (continued)

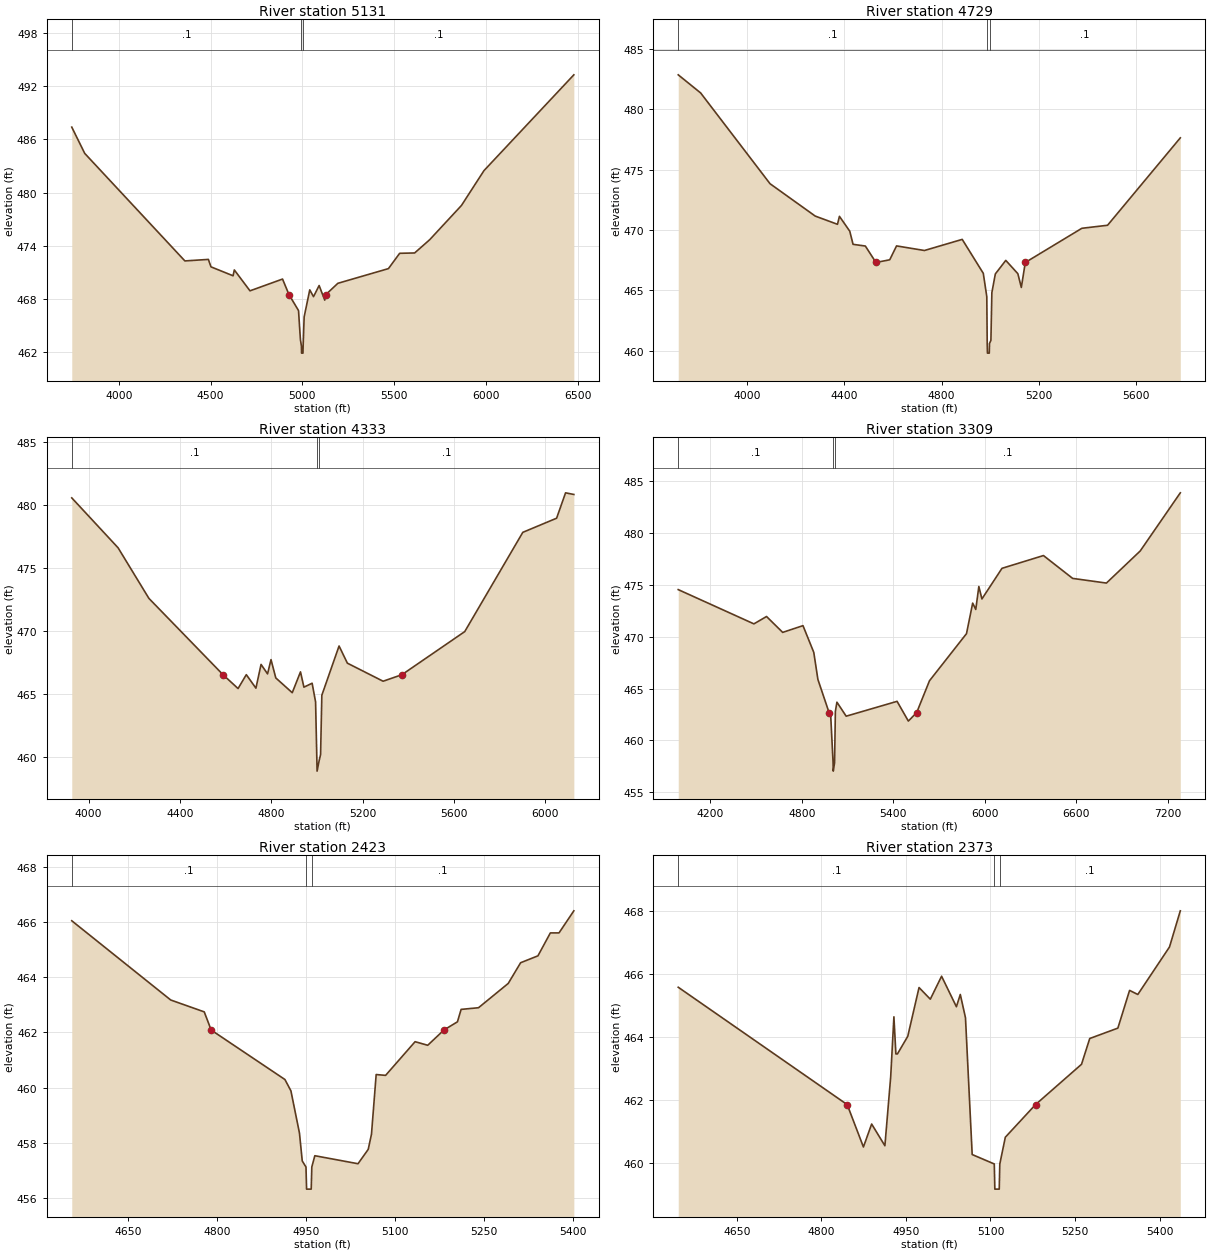
Type RM Length L Ch R = 1 ,5131    ,402,402,402
BEGIN DESCRIPTION:
UNT 185 SanMiguel Cr Watershed 10.0
END DESCRIPTION:
XS GIS Cut Line= 3
      2036675.02     13486424.99        2037575.       13485625.
      2037275.01     13484125.04
#Sta/Elev= 30
  3744.4  487.39    3815  484.42  4360.3  472.27  4488.2  472.44  4502.4   471.6
  4622.8  470.59  4629.5  471.25  4714.8  468.89  4892.1  470.22 4926.87 468.474
  4979.1  466.66  4989.3  463.41  4994.8  462.65  4995.7  461.85  5003.3  461.85
  5004.2  462.65  5009.7  465.94  5040.3     469  5060.7  468.23  5091.3  469.49
  5121.9  467.84 5128.24 468.474  5193.3  469.74  5468.6   471.4  5529.8  473.13
  5611.4  473.17    5693  474.66  5866.4  478.54  5988.7  482.47  6478.2   493.3
#Mann= 3 ,-1 , 0
  3744.4      .1       0  4994.8     .07       0  5004.2      .1       0
Bank Sta=4926.87,5128.24
XS Rating Curve= 0 ,0
Exp/Cntr=0.3,0.1

Type RM Length L Ch R = 1 ,4729    ,396,396,396
BEGIN DESCRIPTION:
UNT 185 SanMiguel Cr Watershed 9.0
END DESCRIPTION:
XS GIS Cut Line= 3
      2036925.02     13486474.98        2037925.       13485675.
      2038424.99     13485075.02
#Sta/Elev= 30
  3718.8  482.85  3810.8  481.35  4095.8  473.83  4281.4  471.15  4372.7  470.47
  4380.7  471.13  4423.1   469.9  4436.7  468.81  4487.1  468.67 4530.65467.3087
  4587.2  467.53  4615.2  468.68  4729.7   468.3  4884.9  469.22  4971.4  466.41
  4985.8  464.48  4987.5   460.6  4988.4   459.8    4996   459.8  4996.9   460.6
  5002.7  460.86  5006.6  464.81  5020.9  466.36  5063.8  467.48  5113.3  466.38
  5127.6  465.24 5143.91467.3081  5376.2  470.14  5481.7  470.39  5780.4  477.63
#Mann= 3 ,-1 , 0
  3718.8      .1       0  4987.5     .07       0  4996.9      .1       0
Bank Sta=4530.65,5143.91
XS Rating Curve= 0 ,0
Exp/Cntr=0.3,0.1

Type RM Length L Ch R = 1 ,4333    ,1024,1024,1024
BEGIN DESCRIPTION:
UNT 185 SanMiguel Cr Watershed 8.0
END DESCRIPTION:
XS GIS Cut Line= 3
        2037525.     13486825.01        2038125.       13485925.
        2038625.     13484925.01
#Sta/Elev= 30
  3925.9  480.55  4128.7   476.6  4263.9  472.59 4588.54466.5467  4654.5  465.45
  4690.6  466.55  4732.7  465.48  4755.2  467.36  4783.7  466.61  4798.8  467.74
  4819.8  466.29  4891.9  465.12    4928  466.77    4943  465.56    4979  465.87
  4994.1  464.39  4999.8  459.71  5000.7  458.91  5009.4  459.71    5016  460.22
  5021.5  464.92    5097  468.82  5133.4  467.46  5289.9  466.03 5372.45466.5468
  5647.6  469.96    5902  477.82  6050.1  478.94  6089.3  480.95  6125.6  480.82
#Mann= 3 ,-1 , 0
  3925.9      .1       0  4999.8     .07       0  5009.4      .1       0
Bank Sta=4588.54,5372.45
XS Rating Curve= 0 ,0
Exp/Cntr=0.3,0.1

Type RM Length L Ch R = 1 ,3309    ,886,886,886
BEGIN DESCRIPTION:
UNT 185 SanMiguel Cr Watershed 7.0
END DESCRIPTION:
XS GIS Cut Line= 4
      2037945.31     13486765.59      2038722.68     13486558.55
      2038926.41     13485239.82      2038787.51     13484093.95
#Sta/Elev= 30
  3989.1  474.53  4485.5  471.23  4568.3  471.94  4674.2  470.41  4807.3  471.06
  4878.1  468.49  4905.2  465.88 4978.45 462.685  4989.4  462.33  5004.8  457.85
  5005.8  457.05  5014.5  457.85  5019.8   462.8  5029.9  463.69  5090.6  462.34
  5424.5  463.77  5498.4  461.87 5553.02462.6851    5637  465.75  5879.9  470.29
  5920.3  473.23  5940.6  472.62  5960.8  474.83    5981  473.63  6112.6  476.58
  6384.6  477.81    6576  475.61  6797.6  475.16  7019.2  478.25  7282.2  483.85
#Mann= 3 ,-1 , 0
  3989.1      .1       0  5004.8     .07       0  5014.5      .1       0
Bank Sta=4978.45,5553.02
XS Rating Curve= 0 ,0
Exp/Cntr=0.3,0.1

Type RM Length L Ch R = 1 ,2423    ,50,50,50
BEGIN DESCRIPTION:
UNT 185 SanMiguel Cr Watershed 6.0
END DESCRIPTION:
XS GIS Cut Line= 6
      2039180.59     13486342.52      2039371.87     13486075.61
      2039381.42     13486012.24      2039380.56     13485926.31
      2039363.19     13485889.85      2039099.68     13485695.34
#Sta/Elev= 30
  4554.7  466.04  4721.5  463.17    4778  462.74 4789.69462.0819    4914  460.29
  4924.1  459.88  4938.5  458.35  4943.2  457.34  4949.5  457.12  4950.5  456.32
  4958.3  456.32  4959.3  457.12  4964.4  457.53  5037.2  457.24  5054.4  457.76
  5059.9  458.31  5067.8  460.47  5083.7  460.44  5133.4  461.66  5154.7  461.53
 5181.94462.0821  5204.8  462.38    5211  462.83  5240.3  462.89  5290.4  463.77
  5311.3  464.52  5340.5  464.77  5361.4   465.6    5376   465.6    5401   466.4
#Mann= 3 ,-1 , 0
  4554.7      .1       0  4949.5     .07       0  4959.3      .1       0
Bank Sta=4789.69,5181.94
XS Rating Curve= 0 ,0
Exp/Cntr=0.3,0.1

Type RM Length L Ch R = 1 ,2373    ,41,41,41
BEGIN DESCRIPTION:
UNT 185 SanMiguel Cr Watershed 5.0
END DESCRIPTION:
XS GIS Cut Line= 6
      2039225.52      13486350.9      2039422.66      13486058.9
      2039431.34     13486023.31      2039431.34     13485917.41
      2039380.32     13485854.74      2039129.47     13485664.77
#Sta/Elev= 30
    4546  465.59 4845.84461.8573  4874.6  460.51  4889.2  461.24  4912.7  460.55
    4923  462.74  4928.7  464.65  4932.2  463.47    4935  463.47  4953.3  464.03
  4973.3  465.58  4993.3  465.21  5013.3  465.94  5039.6  464.97  5046.5  465.36
  5055.7  464.62  5067.6  460.27  5106.8  459.97  5107.8  459.17  5115.6  459.17
  5116.6  459.97  5126.4  460.82 5179.97461.8573  5261.6  463.14  5276.2  463.96
  5326.1  464.29  5346.9  465.49  5361.5  465.36  5417.7  466.87  5436.9  468.02
#Mann= 3 ,-1 , 0
    4546      .1       0  5106.8     .07       0  5116.6      .1       0
Bank Sta=4845.84,5179.97
XS Rating Curve= 0 ,0
Exp/Cntr=0.3,0.1

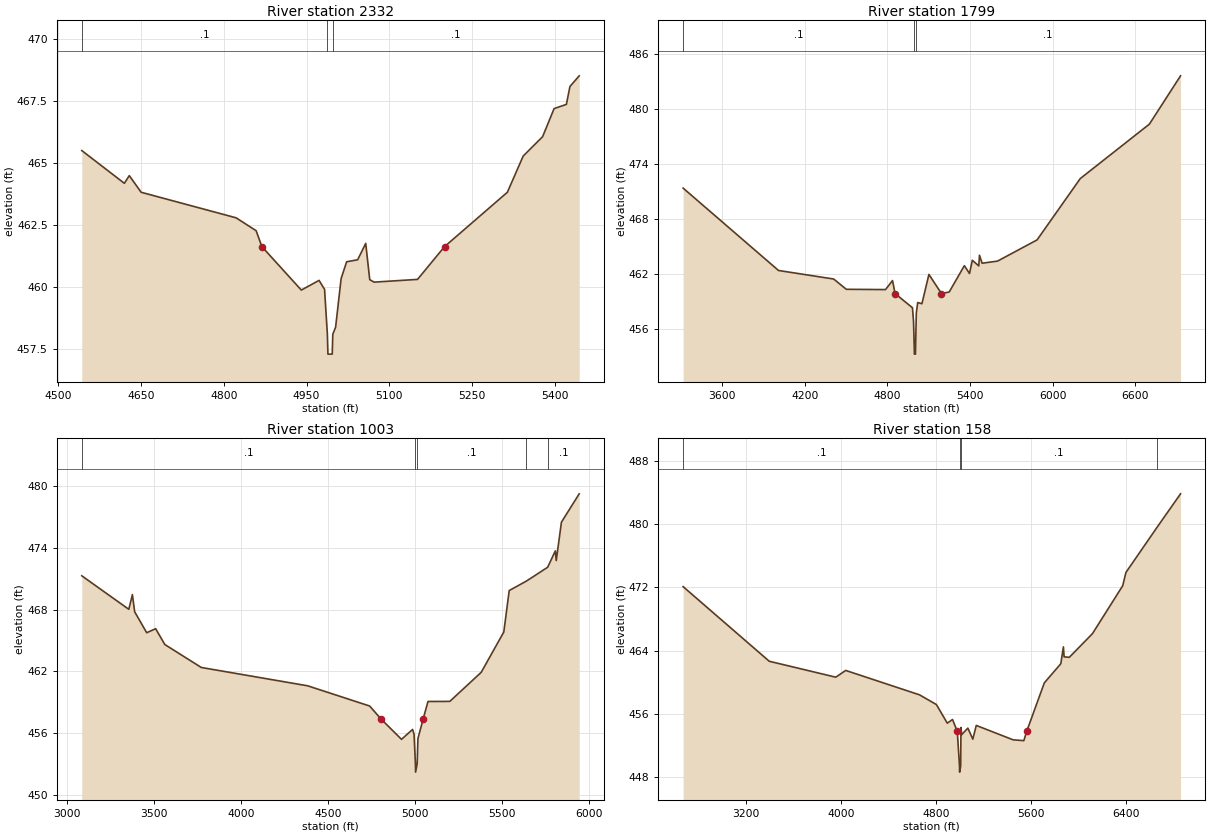
Type RM Length L Ch R = 1 ,2332    ,533,533,533
BEGIN DESCRIPTION:
UNT 185 SanMiguel Cr Watershed 4.0
END DESCRIPTION:
XS GIS Cut Line= 6
      2039269.71     13486357.37      2039462.14     13486059.27
      2039471.69     13486014.13      2039471.69     13485904.76
      2039448.25     13485869.17      2039178.38     13485648.25
#Sta/Elev= 30
  4542.6  465.51  4619.8  464.19  4628.7   464.5  4650.2  463.83  4822.4   462.8
  4858.7  462.28 4869.01461.6412  4940.6  459.89  4972.7  460.28  4982.7  459.92
  4987.8  458.11  4988.8  457.31  4996.6  457.31  4997.6  458.11  5002.7  458.39
  5012.7  460.35  5022.7  461.03  5042.7  461.11  5057.3  461.77  5064.6  460.31
  5072.4  460.21  5151.2  460.32 5200.26461.6411  5314.1  463.83  5342.8  465.29
    5378  466.07  5398.8   467.2  5421.1  467.37  5427.5  468.09  5444.3  468.52
#Mann= 3 ,-1 , 0
  4542.6      .1       0  4987.8     .07       0  4997.6      .1       0
Bank Sta=4869.01,5200.26
XS Rating Curve= 0 ,0
Exp/Cntr=0.3,0.1

Type RM Length L Ch R = 1 ,1799    ,796,796,796
BEGIN DESCRIPTION:
UNT 185 SanMiguel Cr Watershed 3.0
END DESCRIPTION:
XS GIS Cut Line= 4
      2038877.84      13486503.7      2039954.19      13486267.6
      2039725.02     13485052.32      2039134.76     13483920.41
#Sta/Elev= 30
  3314.9  471.35  4008.2  462.38  4409.1  461.45  4500.9  460.33  4785.8   460.3
  4836.7  461.28 4855.47459.8654  4981.7  458.32  4989.4  456.83  4994.6  454.07
  4995.6  453.27  5003.5  453.27  5004.4  454.07  5009.7  457.75  5019.9  458.89
  5050.4  458.76  5101.3  461.95  5192.7459.8651  5248.9  460.04  5358.8   462.9
  5396.4  462.05  5416.8  463.49  5463.7  462.88  5468.7  464.04    5488  463.17
  5599.9   463.4  5887.4  465.71  6201.3  472.39  6703.8  478.32  6930.1  483.58
#Mann= 3 ,-1 , 0
  3314.9      .1       0  4994.6     .07       0  5004.4      .1       0
Bank Sta=4855.47,5192.7
XS Rating Curve= 0 ,0
Exp/Cntr=0.3,0.1

Type RM Length L Ch R = 1 ,1003    ,845,845,845
BEGIN DESCRIPTION:
UNT 185 SanMiguel Cr Watershed 2.0
END DESCRIPTION:
XS GIS Cut Line= 5
      2038902.19     13486520.45       2040159.1     13486218.37
      2040568.82     13485562.12      2040367.43     13484805.18
       2040359.8     13484800.09
#Sta/Elev= 30
  3084.9  471.27  3355.2  468.02  3375.8  469.44  3388.8  467.78    3458  465.75
  3509.5  466.14  3561.8  464.61  3771.6  462.38  4383.4   460.6  4739.6  458.64
 4803.73457.3976  4922.4  455.41  4986.1  456.37  4994.6   455.9  5002.4  453.03
  5003.4  452.23  5012.4  453.03  5016.8  455.48 5047.11457.3978  5074.6  459.08
    5200  459.09  5380.6  461.91  5510.4  465.82  5541.5  469.84  5640.5  470.76
  5762.5   472.1  5806.6  473.69  5811.8  472.75  5841.6  476.47  5943.7  479.22
#Mann= 5 ,-1 , 0
  3084.9      .1       0  5002.4     .07       0  5012.4      .1       0
  5640.5     .08       0  5762.5      .1       0
Bank Sta=4803.73,5047.11
XS Rating Curve= 0 ,0
Exp/Cntr=0.3,0.1

Type RM Length L Ch R = 1 ,158     ,0,0,0
BEGIN DESCRIPTION:
UNT 185 SanMiguel Cr Watershed 1.0
END DESCRIPTION:
XS GIS Cut Line= 4
      2038850.05     13486549.99        2041050.       13486150.
      2041278.55     13485616.67      2040537.84     13484469.48
#Sta/Elev= 30
  2673.5  472.08  3397.6  462.65  3956.7  460.64  4040.5  461.49  4660.5  458.41
  4802.8  457.18  4894.3  454.83  4938.5  455.29 4978.22453.7998    4997  449.44
    4998  448.64    5007  449.44  5009.3  454.28  5014.7  453.37  5067.3   454.2
    5109  452.81    5138  454.54  5448.1  452.72  5537.9  452.62 5562.15453.7997
  5710.1  459.92  5848.8  462.34  5870.5  464.47  5876.4  463.21  5920.3  463.15
  6115.3  466.15  6369.3   472.2  6396.4  473.88  6661.1  479.65  6855.3  483.81
#Mann= 4 ,-1 , 0
  2673.5      .1       0    4997     .07       0    5007      .1       0
  6661.1     .05       0
Bank Sta=4978.22,5562.15
XS Rating Curve= 0 ,0
Exp/Cntr=0.3,0.1
LCMann Table=0

Chan Stop Cuts=-1
Use User Specified Reach Order=0
Composite Channel Slope=5