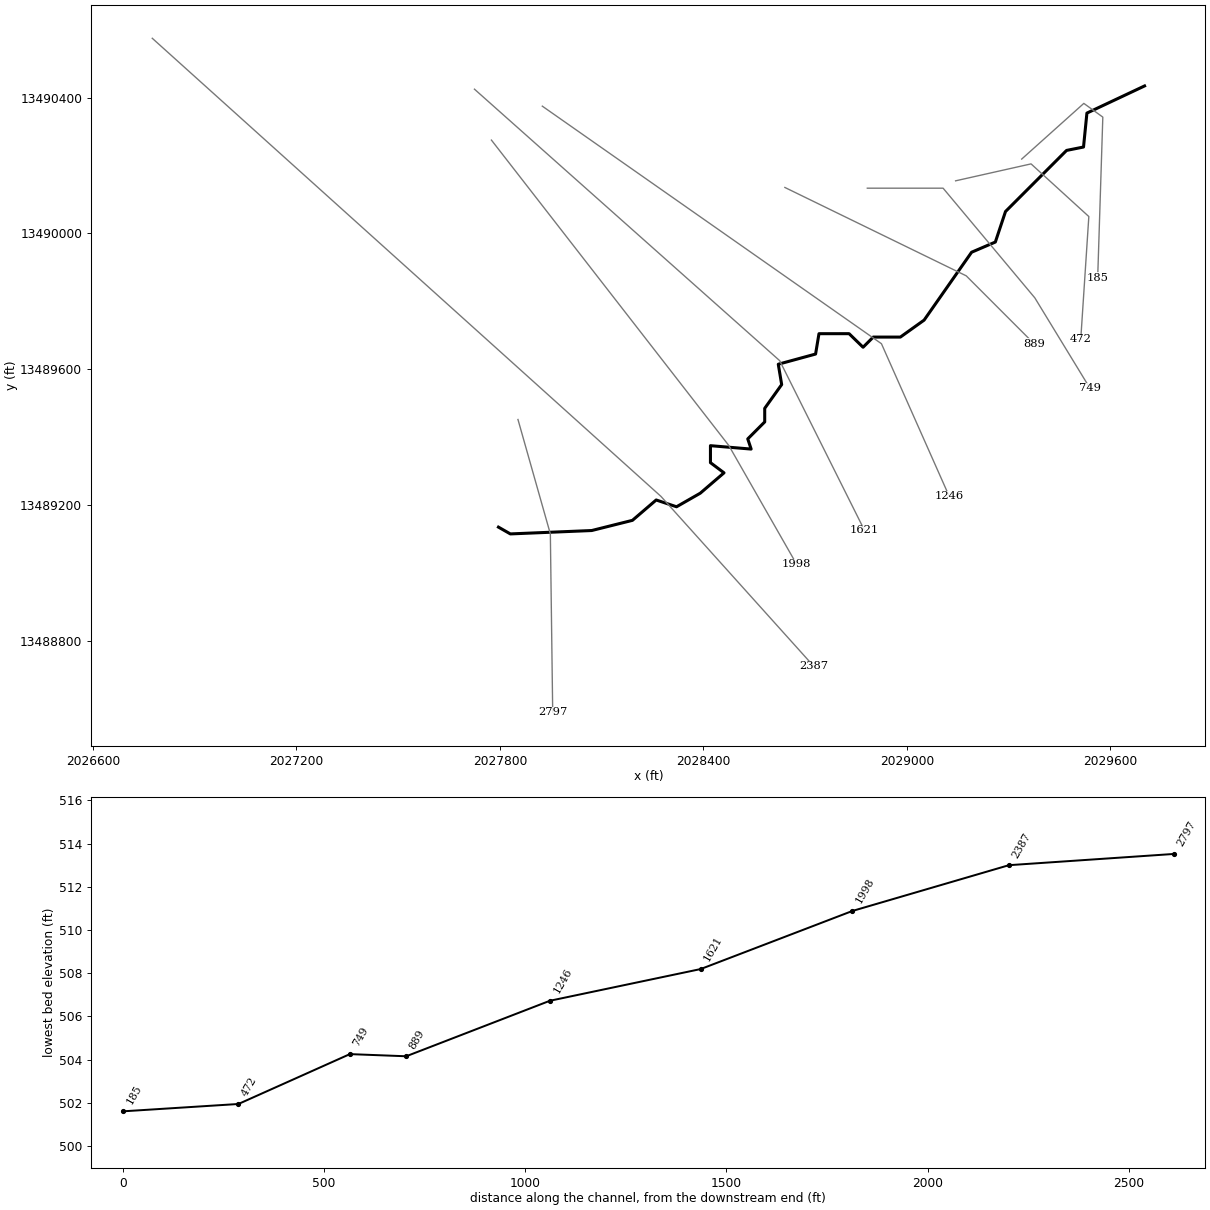
--- UNT 186 SanMiguel Cr Watershed.prj (project) ---

Proj Title=UNT 186 SanMiguel Cr Watershed Base Level Engineering
Current Plan=p01
Default Exp/Contr=0.3,0.1
English Units
Geom File=g01
Flow File=f01
Plan File=p01
Y Axis Title=Elevation
X Axis Title(PF)=Main Channel Distance
X Axis Title(XS)=Station
BEGIN DESCRIPTION:
UNT 186 SanMiguel Cr Watershed
END DESCRIPTION:
DSS Export Rating Curves= 0
DSS Export Rating Curve Sorted= 0
DSS Export Volume Flow Curves= 0
DXF OffsetX= 0
DXF OffsetY= 0
DXF ScaleX= 1
DXF ScaleY= 10

--- UNT 186 SanMiguel Cr Watershed.p01 (plan) ---

Plan Title=Multiple Run
Short Identifier=Multiple
Geom File=g01
Flow File=f01
Subcritical Flow
K Sum by GR= 0
Std Step Tol= 0.01
Critical Tol= 0.01
Num of Std Step Trials= 20
Max Error Tol= 0.3
Flow Tol Ratio= 0.001
Split Flow NTrial= 30
Split Flow Tol= 0.02
Split Flow Ratio= 0.02
Log Output Level= 0
Friction Slope Method= 1
Unsteady Friction Slope Method= 2
Unsteady Bridges Friction Slope Method= 1
Parabolic Critical Depth
Global Vel Dist=  1 , 1 , 1
Global Log Level= 0
CheckData=True
Encroach Param= -1, 0, 0, 0
BEGIN DESCRIPTION:
Multiple Run
END DESCRIPTION:

--- UNT 186 SanMiguel Cr Watershed.f01 (steady flow) ---

Flow Title=Multiple
Number of Profiles=7
Profile Names=10-year,25-year,50-year,1pct_min,100-year,1pct_plu,500-year
River Rch & RM= UNT 186 SanMigue,Reach-1,2797
     199     273     334     204     408     814     616
Boundary for River Rch & Prof#=UNT 186 SanMigue,Reach-1,1
Up Type=0
Dn Type=3
Dn Slope=0.005
Boundary for River Rch & Prof#=UNT 186 SanMigue,Reach-1,2
Up Type=0
Dn Type=3
Dn Slope=0.005
Boundary for River Rch & Prof#=UNT 186 SanMigue,Reach-1,3
Up Type=0
Dn Type=3
Dn Slope=0.005
Boundary for River Rch & Prof#=UNT 186 SanMigue,Reach-1,4
Up Type=0
Dn Type=3
Dn Slope=0.005
Boundary for River Rch & Prof#=UNT 186 SanMigue,Reach-1,5
Up Type=0
Dn Type=3
Dn Slope=0.005
Boundary for River Rch & Prof#=UNT 186 SanMigue,Reach-1,6
Up Type=0
Dn Type=3
Dn Slope=0.005
Boundary for River Rch & Prof#=UNT 186 SanMigue,Reach-1,7
Up Type=0
Dn Type=3
Dn Slope=0.005

--- UNT 186 SanMiguel Cr Watershed.g01 (geometry) ---

Geom Title=Existing Conditions
Program Version=5.05

River Reach=UNT 186 SanMigue,Reach-1
Reach XY= 30
       2027795.8     13489134.54       2027830.8     13489114.54
       2028070.8     13489124.54       2028190.8     13489154.54
       2028260.8     13489214.54       2028320.8     13489194.54
       2028390.8     13489234.54       2028460.8     13489294.54
       2028420.8     13489324.54       2028420.8     13489374.54
       2028540.8     13489364.54       2028530.8     13489394.54
       2028580.8     13489444.54       2028580.8     13489484.54
       2028630.8     13489554.54       2028620.8     13489614.54
       2028730.8     13489644.54       2028740.8     13489704.54
      2028829.61     13489704.57       2028870.8     13489664.54
       2028900.8     13489694.54       2028980.8     13489694.54
       2029050.8     13489744.54       2029190.8     13489944.54
       2029260.8     13489974.54       2029290.8     13490064.54
       2029470.8     13490244.54       2029520.8     13490254.54
       2029530.8     13490354.54       2029700.8     13490434.54

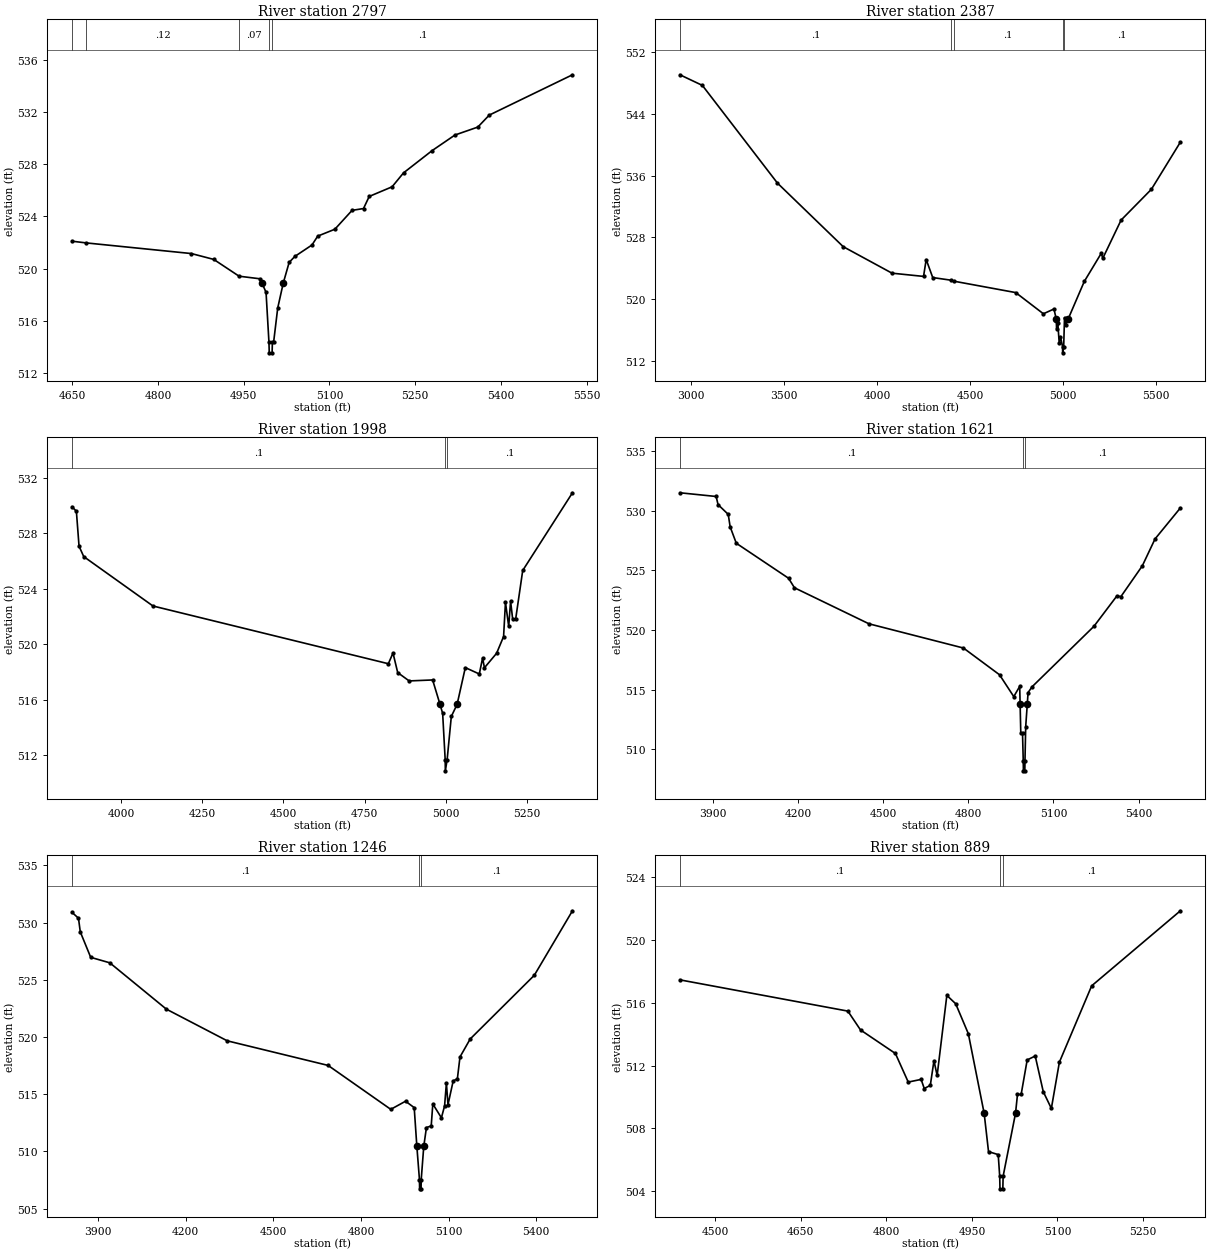
Type RM Length L Ch R = 1 ,2797    ,410,410,410
BEGIN DESCRIPTION:
UNT 186 SanMiguel Cr Watershed 9.0
END DESCRIPTION:
XS GIS Cut Line= 3
      2027853.28     13489451.68      2027948.77     13489114.54
      2027955.71     13488589.38
#Sta/Elev= 30
  4649.6   522.1  4674.1  521.97  4858.5  521.15  4897.6   520.7  4941.9  519.41
  4978.7  519.21 4982.08 518.872  4989.1  518.17  4994.2  514.32  4994.7  513.52
  4999.7  513.52  5000.2  514.32  5002.3  514.32  5009.5  516.96 5019.16518.8727
  5029.5  520.47  5039.5  520.93  5069.5  521.81  5079.5  522.49  5109.5  523.02
  5139.6  524.47  5159.6  524.61  5169.6  525.54  5209.6  526.28  5229.6  527.35
  5279.6  529.06  5319.6  530.26  5359.6  530.87  5379.6  531.79  5525.2  534.89
#Mann= 5 ,-1 , 0
  4649.6      .1       0  4674.1     .12       0  4941.9     .07       0
  4994.2     .07       0  5000.2      .1       0
Bank Sta=4982.08,5019.16
XS Rating Curve= 0 ,0
Exp/Cntr=0.3,0.1

Type RM Length L Ch R = 1 ,2387    ,389,389,389
BEGIN DESCRIPTION:
UNT 186 SanMiguel Cr Watershed 8.0
END DESCRIPTION:
XS GIS Cut Line= 3
      2026775.02     13490574.98        2028275.       13489225.
        2028725.       13488725.
#Sta/Elev= 30
    2941  549.09  3061.7  547.71  3465.3  535.03  3818.8  526.78  4081.2  523.34
  4250.8  522.92    4265  525.11  4300.2  522.77    4401  522.42  4413.9   522.3
  4746.4  520.82  4895.1  518.07  4951.9  518.69 4963.98 517.412  4966.1  516.14
  4972.8  516.82  4980.3  514.22    4987   515.1  4998.2   513.8  4998.7     513
  5004.2   513.8  5008.7  517.58  5015.4   516.6 5028.64517.4139  5114.9  522.26
  5206.8  525.94  5214.3  525.26  5312.9  530.23  5475.9  534.23  5631.7  540.35
#Mann= 5 ,-1 , 0
    2941      .1       0    4401     .05       0  4413.9      .1       0
  4998.2     .07       0  5004.2      .1       0
Bank Sta=4963.98,5028.64
XS Rating Curve= 0 ,0
Exp/Cntr=0.3,0.1

Type RM Length L Ch R = 1 ,1998    ,377,377,377
BEGIN DESCRIPTION:
UNT 186 SanMiguel Cr Watershed 7.0
END DESCRIPTION:
XS GIS Cut Line= 3
      2027775.02     13490274.98        2028475.       13489375.
      2028675.02     13489024.97
#Sta/Elev= 30
  3847.8  529.91  3861.3  529.59  3869.5  527.07    3884  526.32  4097.5  522.76
  4823.3   518.6  4837.7  519.37  4852.2  517.96  4887.5  517.36  4959.9  517.43
 4982.71515.6674  4990.8  515.02  4998.6  511.68  4999.1  510.88  5004.6  511.68
  5017.5   514.8 5035.35515.6694  5060.7  518.32  5103.8  517.86  5113.9     519
  5119.7  518.31  5157.1  519.35  5178.7  520.56  5184.5  523.02  5194.5  521.29
  5200.3  523.11  5206.8  521.79  5216.1  521.84  5237.7  525.32  5391.1  530.92
#Mann= 3 ,-1 , 0
  3847.8      .1       0  4998.6     .07       0  5004.6      .1       0
Bank Sta=4982.71,5035.35
XS Rating Curve= 0 ,0
Exp/Cntr=0.3,0.1

Type RM Length L Ch R = 1 ,1621    ,375,375,375
BEGIN DESCRIPTION:
UNT 186 SanMiguel Cr Watershed 6.0
END DESCRIPTION:
XS GIS Cut Line= 3
      2027724.97     13490425.03        2028625.       13489625.
      2028874.99     13489125.02
#Sta/Elev= 30
  3784.1  531.49  3911.7  531.18  3918.4   530.5  3954.3  529.68    3961  528.64
  3982.7  527.26  4166.7  524.33  4187.6  523.53  4450.2  520.51    4783  518.48
  4910.1  516.24  4960.3  514.41  4981.2  515.27  4982.6513.8148    4985  511.32
  4991.1  511.32  4993.7  508.99  4994.2  508.19  4999.2  508.19  4999.7  508.99
  5002.3  511.89 5007.94513.8102  5010.7  514.75  5024.6  515.23  5242.7   520.3
  5323.7  522.85  5337.7  522.79  5413.2  525.37  5457.9  527.62  5547.3  530.22
#Mann= 3 ,-1 , 0
  3784.1      .1       0  4993.7     .07       0  4999.7      .1       0
Bank Sta=4982.6,5007.94
XS Rating Curve= 0 ,0
Exp/Cntr=0.3,0.1

Type RM Length L Ch R = 1 ,1246    ,357,357,357
BEGIN DESCRIPTION:
UNT 186 SanMiguel Cr Watershed 5.0
END DESCRIPTION:
XS GIS Cut Line= 3
      2027925.04     13490374.97        2028925.       13489675.
      2029124.98     13489225.04
#Sta/Elev= 30
  3810.8  530.89    3833  530.38  3839.1  529.19  3874.8  526.96  3940.2  526.48
  4133.8  522.43  4342.2  519.66  4687.4  517.51  4901.9  513.67  4952.5  514.38
  4982.1  513.82 4991.15510.4373  5000.1  507.52  5000.6  506.72  5005.6  506.72
  5006.1  507.52 5014.83510.4384    5024  512.08  5040.3  512.22  5045.8  514.14
  5075.2  512.93  5086.1  513.97  5092.3  515.98  5097.7  514.07  5115.5  516.15
  5129.9  516.35  5138.8  518.25  5173.7  519.82  5393.2  525.39  5523.8  531.03
#Mann= 3 ,-1 , 0
  3810.8      .1       0  5000.1     .07       0  5006.1      .1       0
Bank Sta=4991.15,5014.83
XS Rating Curve= 0 ,0
Exp/Cntr=0.3,0.1

Type RM Length L Ch R = 1 ,889     ,140,140,140
BEGIN DESCRIPTION:
UNT 186 SanMiguel Cr Watershed 4.0
END DESCRIPTION:
XS GIS Cut Line= 3
      2028640.22     13490135.42        2029175.       13489875.
      2029375.03     13489674.97
#Sta/Elev= 30
  4437.9  517.46  4732.4  515.47  4754.6  514.27  4815.8  512.77  4838.3  510.95
  4860.9  511.12  4866.4  510.54    4877  510.74  4883.4  512.31    4889  511.37
    4906  516.47  4921.5  515.94  4943.7  514.03 4971.46508.9573  4979.1  506.52
  4996.1  506.33  4998.7  504.95  4999.2  504.15  5004.2  504.15  5004.7  504.95
 5026.44508.9581  5029.9  510.16  5036.3  510.16  5046.9  512.36    5061  512.61
  5075.1  510.34  5089.3  509.27  5103.4  512.22    5160  517.08  5315.6  521.86
#Mann= 3 ,-1 , 0
  4437.9      .1       0  4998.7     .07       0  5004.7      .1       0
Bank Sta=4971.46,5026.44
XS Rating Curve= 0 ,0
Exp/Cntr=0.3,0.1

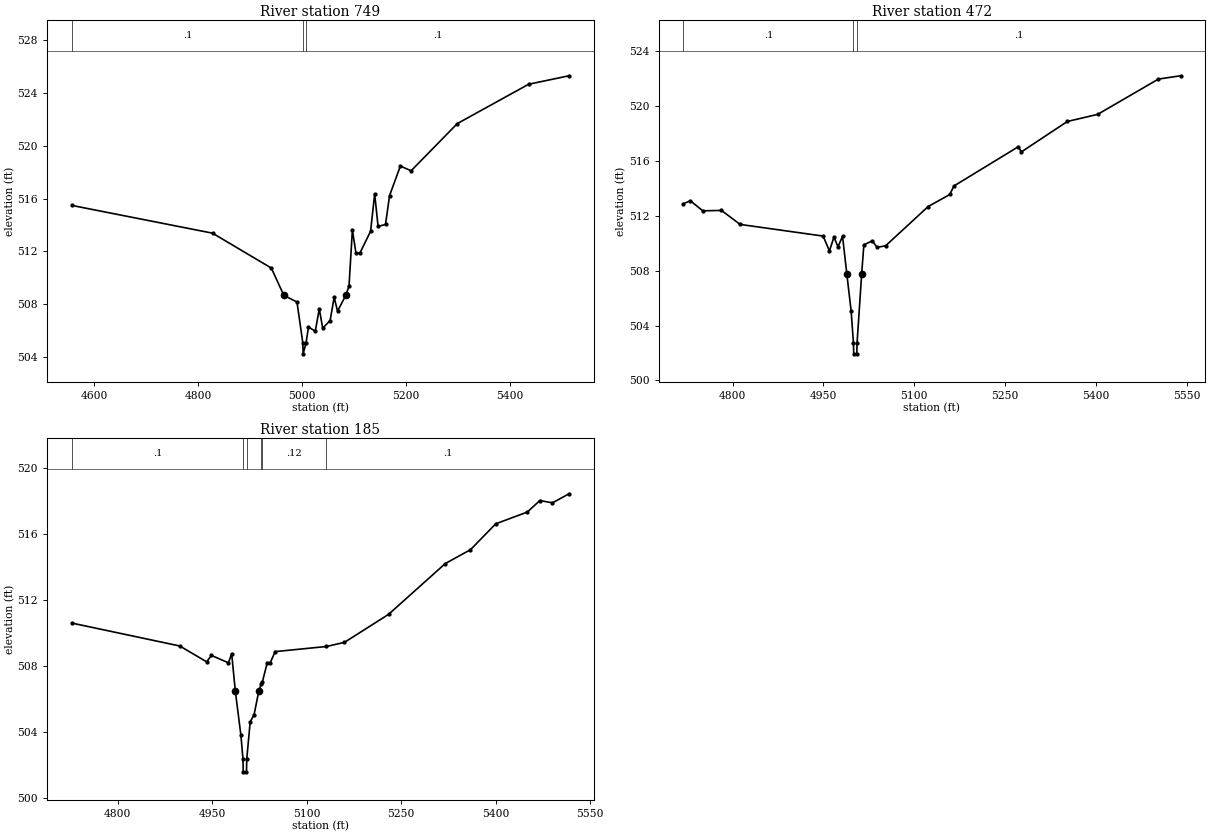
Type RM Length L Ch R = 1 ,749     ,277,277,277
BEGIN DESCRIPTION:
UNT 186 SanMiguel Cr Watershed 3.0
END DESCRIPTION:
XS GIS Cut Line= 4
       2028883.3     13490133.26      2029106.79     13490133.26
      2029377.21     13489810.13      2029540.21     13489543.09
#Sta/Elev= 30
  4556.5  515.48  4827.5  513.38  4940.8  510.74 4964.86 508.675  4990.2  508.17
  5001.5  505.05    5002  504.25  5007.5  505.05  5012.3  506.27  5025.5  505.97
  5033.1  507.66  5039.7  506.19    5054  506.77  5061.8  508.53  5068.3  507.48
 5084.15508.6749  5090.4  509.38  5096.9  513.62  5103.7  511.89  5111.2  511.86
    5132  513.53  5139.8  516.36  5146.4  513.89  5160.7  514.04  5168.5  516.22
  5189.3  518.46    5210   518.1  5298.9  521.67  5436.4  524.65  5514.2  525.29
#Mann= 3 ,-1 , 0
  4556.5      .1       0  5001.5     .07       0  5007.5      .1       0
Bank Sta=4964.86,5084.15
XS Rating Curve= 0 ,0
Exp/Cntr=0.3,0.1

Type RM Length L Ch R = 1 ,472     ,287,287,287
BEGIN DESCRIPTION:
UNT 186 SanMiguel Cr Watershed 2.0
END DESCRIPTION:
XS GIS Cut Line= 4
      2029143.65     13490154.96      2029366.12     13490204.88
      2029536.47     13490049.71      2029512.69     13489688.62
#Sta/Elev= 30
  4718.9  512.88  4730.5  513.09    4751  512.36  4781.8  512.39  4812.5  511.37
  4949.5  510.52  4959.9  509.44  4967.3  510.44  4974.1  509.74  4981.5  510.51
 4988.59507.7599  4995.7  505.06  4999.5  502.74    5000  501.94    5005  501.94
  5005.5  502.74 5013.05507.7596  5016.7  509.88  5030.8  510.18  5038.3   509.7
  5052.5  509.81  5122.7  512.67  5158.5  513.55  5165.3  514.17  5271.5  517.03
  5276.5  516.65  5352.4  518.87  5402.5  519.39  5502.7  521.96  5539.2   522.2
#Mann= 3 ,-1 , 0
  4718.9      .1       0  4999.5     .07       0  5005.5      .1       0
Bank Sta=4988.59,5013.05
XS Rating Curve= 0 ,0
Exp/Cntr=0.3,0.1

Type RM Length L Ch R = 1 ,185     ,0,0,0
BEGIN DESCRIPTION:
UNT 186 SanMiguel Cr Watershed 1.0
END DESCRIPTION:
XS GIS Cut Line= 4
      2029338.54     13490219.05      2029521.72     13490383.13
      2029577.71     13490342.68      2029562.56     13489868.71
#Sta/Elev= 30
  4727.1  510.62  4898.5  509.23  4941.1  508.27  4948.6  508.66  4975.7  508.21
  4980.8  508.77 4986.59506.4948  4995.5  503.81  4998.7   502.4  4999.2   501.6
  5004.3   501.6  5004.8   502.4  5010.2  504.63  5016.4  505.07 5023.87506.4937
  5027.5   506.9  5029.6  507.06  5037.3  508.22  5042.1  508.22  5049.8  508.89
  5131.2   509.2  5159.8  509.45  5229.9  511.15  5319.9  514.23  5359.9  515.07
    5400  516.64    5450  517.35    5470  518.05    5490  517.91  5516.3  518.46
#Mann= 6 ,-1 , 0
  4727.1      .1       0  4998.7     .07       0  5004.8      .1       0
  5027.5     .07       0  5029.6     .12       0  5131.2      .1       0
Bank Sta=4986.59,5023.87
XS Rating Curve= 0 ,0
Exp/Cntr=0.3,0.1
LCMann Table=0

Chan Stop Cuts=-1
Use User Specified Reach Order=0
Composite Channel Slope=5