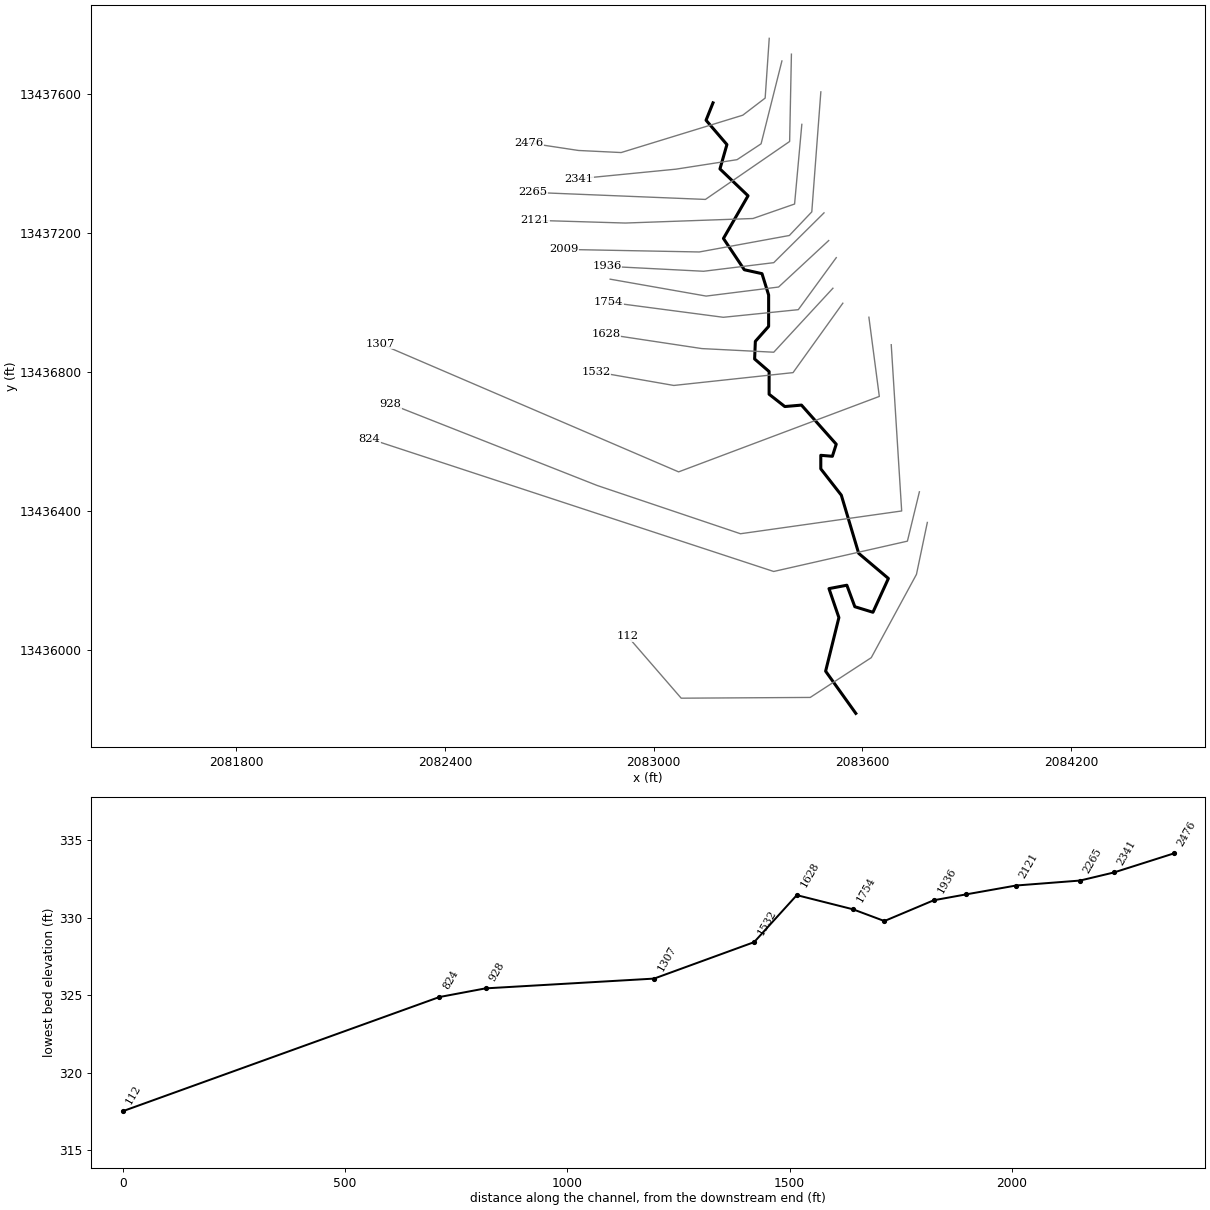
--- UNT 187 SanMiguel Cr Watershed.prj (project) ---

Proj Title=UNT 187 SanMiguel Cr Watershed Base Level Engineering
Current Plan=p01
Default Exp/Contr=0.3,0.1
English Units
Geom File=g01
Flow File=f01
Plan File=p01
Y Axis Title=Elevation
X Axis Title(PF)=Main Channel Distance
X Axis Title(XS)=Station
BEGIN DESCRIPTION:
UNT 187 SanMiguel Cr Watershed
END DESCRIPTION:
DSS Export Rating Curves= 0
DSS Export Rating Curve Sorted= 0
DSS Export Volume Flow Curves= 0
DXF OffsetX= 0
DXF OffsetY= 0
DXF ScaleX= 1
DXF ScaleY= 10

--- UNT 187 SanMiguel Cr Watershed.p01 (plan) ---

Plan Title=Multiple Run
Short Identifier=Multiple
Geom File=g01
Flow File=f01
Subcritical Flow
K Sum by GR= 0
Std Step Tol= 0.01
Critical Tol= 0.01
Num of Std Step Trials= 20
Max Error Tol= 0.3
Flow Tol Ratio= 0.001
Split Flow NTrial= 30
Split Flow Tol= 0.02
Split Flow Ratio= 0.02
Log Output Level= 0
Friction Slope Method= 1
Unsteady Friction Slope Method= 2
Unsteady Bridges Friction Slope Method= 1
Parabolic Critical Depth
Global Vel Dist=  1 , 1 , 1
Global Log Level= 0
CheckData=True
Encroach Param= -1, 0, 0, 0
BEGIN DESCRIPTION:
Multiple Run
END DESCRIPTION:

--- UNT 187 SanMiguel Cr Watershed.f01 (steady flow) ---

Flow Title=Multiple
Number of Profiles=7
Profile Names=10-year,25-year,50-year,1pct_min,100-year,1pct_plu,500-year
River Rch & RM= UNT 187 SanMigue,Reach-1,2476
      72      92     107      62     124     248     171
Boundary for River Rch & Prof#=UNT 187 SanMigue,Reach-1,1
Up Type=0
Dn Type=3
Dn Slope=0.005
Boundary for River Rch & Prof#=UNT 187 SanMigue,Reach-1,2
Up Type=0
Dn Type=3
Dn Slope=0.005
Boundary for River Rch & Prof#=UNT 187 SanMigue,Reach-1,3
Up Type=0
Dn Type=3
Dn Slope=0.005
Boundary for River Rch & Prof#=UNT 187 SanMigue,Reach-1,4
Up Type=0
Dn Type=3
Dn Slope=0.005
Boundary for River Rch & Prof#=UNT 187 SanMigue,Reach-1,5
Up Type=0
Dn Type=3
Dn Slope=0.005
Boundary for River Rch & Prof#=UNT 187 SanMigue,Reach-1,6
Up Type=0
Dn Type=3
Dn Slope=0.005
Boundary for River Rch & Prof#=UNT 187 SanMigue,Reach-1,7
Up Type=0
Dn Type=3
Dn Slope=0.005

--- UNT 187 SanMiguel Cr Watershed.g01 (geometry) ---

Geom Title=Existing Conditions
Program Version=5.05

River Reach=UNT 187 SanMigue,Reach-1
Reach XY= 30
       2083170.8     13437574.54       2083150.8     13437524.54
       2083210.8     13437454.54       2083190.8     13437384.54
      2083271.56     13437307.25       2083200.8     13437184.54
       2083260.8     13437094.54      2083311.67     13437083.29
      2083330.78     13437021.92      2083330.78     13436931.64
      2083292.59     13436888.58       2083290.5     13436837.89
      2083332.17     13436801.78      2083332.17      13436736.5
      2083377.31     13436701.08      2083425.23     13436705.25
      2083525.22     13436592.75      2083514.11     13436558.03
       2083480.8     13436560.81       2083480.8     13436521.92
      2083539.81     13436446.22      2083589.81     13436278.86
      2083675.22     13436206.64      2083630.78     13436109.42
       2083578.7     13436125.39      2083555.78      13436187.2
      2083504.39     13436177.47      2083532.86     13436094.14
      2083494.67     13435939.97      2083581.52     13435818.62

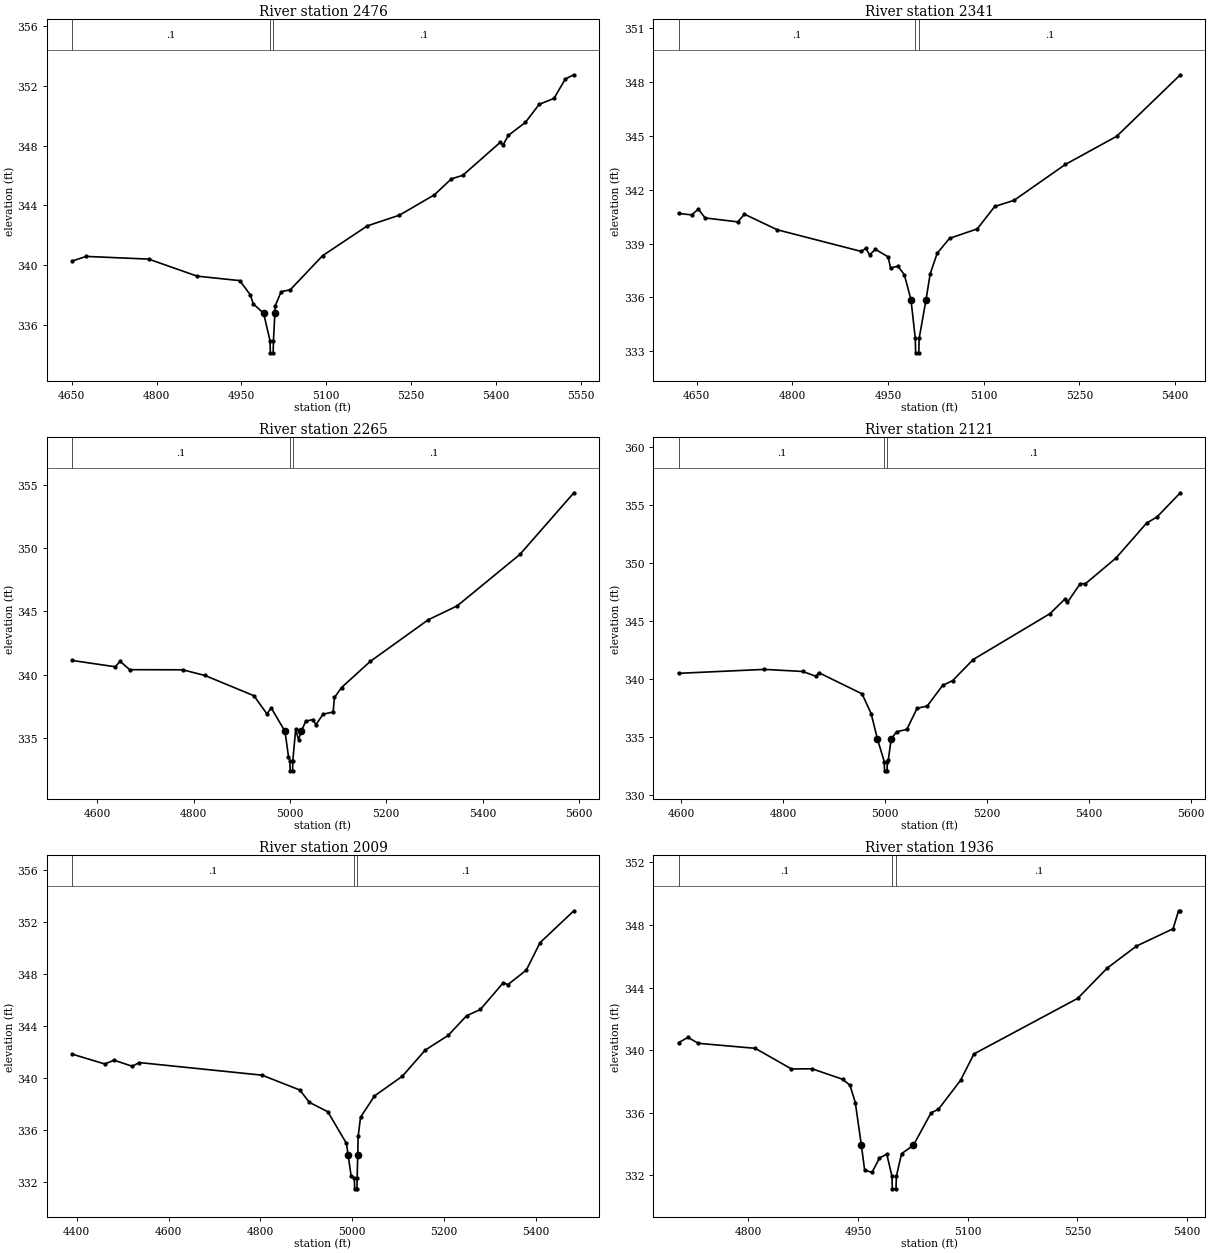
Type RM Length L Ch R = 1 ,2476    ,135,135,135
BEGIN DESCRIPTION:
UNT 187 SanMiguel Cr Watershed 9.0
END DESCRIPTION:
XS GIS Cut Line= 6
      2083332.51     13437760.09      2083320.79     13437588.24
      2083256.41     13437539.02       2082906.6      13437431.6
       2082783.7      13437437.6       2082640.2     13437459.33
#Sta/Elev= 30
  4650.6  340.28  4675.7  340.59    4786  340.41  4871.8  339.27  4947.2  338.97
  4965.8  338.02    4971  337.42 4989.38336.7848  5000.7  334.94  5001.2  334.14
  5006.2  334.14  5006.7  334.94 5009.28336.7849    5010   337.3  5020.4  338.23
  5036.5  338.36  5093.7  340.64  5172.6  342.63  5229.6  343.35  5291.4  344.71
  5321.5  345.78  5341.5  346.01  5407.8  348.22  5412.9  348.04  5421.9  348.68
  5452.2  349.55  5476.6  350.76  5502.8  351.16    5523  352.46    5538  352.74
#Mann= 3 ,-1 , 0
  4650.6      .1       0  5000.7     .07       0  5006.7      .1       0
Bank Sta=4989.38,5009.28
XS Rating Curve= 0 ,0
Exp/Cntr=0.3,0.1

Type RM Length L Ch R = 1 ,2341    ,76,76,76
BEGIN DESCRIPTION:
Mapping XS 7788daa9
END DESCRIPTION:
XS GIS Cut Line= 5
      2083368.98     13437695.06      2083309.08     13437456.73
      2083240.07     13437411.16      2083064.28     13437383.82
      2082785.66     13437356.47
#Sta/Elev= 30
  4621.7  340.68  4642.4   340.6  4652.7  340.92  4663.4  340.43  4714.6  340.21
  4724.9  340.64  4776.4  339.77  4908.3  338.56  4915.1  338.74  4921.1  338.37
  4930.2  338.68  4950.1  338.26  4953.9  337.64  4965.4  337.74  4975.5  337.27
 4985.97335.8617  4992.7  333.71  4993.2  332.91  4998.2  332.91  4998.7  333.71
 5009.46335.8596    5016  337.31    5027  338.46  5046.3  339.29  5089.8  339.82
  5117.2  341.07  5147.4  341.41  5227.8  343.41  5308.2  344.98    5408  348.41
#Mann= 3 ,-1 , 0
  4621.7      .1       0  4992.7     .07       0  4998.7      .1       0
Bank Sta=4985.97,5009.46
XS Rating Curve= 0 ,0
Exp/Cntr=0.3,0.1

Type RM Length L Ch R = 1 ,2265    ,144,144,144
BEGIN DESCRIPTION:
UNT 187 SanMiguel Cr Watershed 8.0
END DESCRIPTION:
XS GIS Cut Line= 5
      2083396.32     13437714.56      2083391.19     13437463.47
        2083149.      13437296.8      2082813.78     13437310.46
      2082653.26       13437317.
#Sta/Elev= 30
    4548  341.12  4637.6  340.62  4647.6  341.05  4667.6  340.39  4777.6  340.38
  4823.9  339.93  4925.4  338.33  4952.4  336.89  4961.2  337.37 4989.85335.5138
  4997.1  333.52  5000.1  333.19  5000.6  332.39  5005.6  332.39  5006.1  333.19
    5012  335.68    5018  334.84 5023.51335.5134  5032.9  336.31  5047.8  336.45
  5053.9  336.03  5068.8  336.87  5089.7  337.04  5092.5  338.19  5107.2  338.98
    5167  341.05  5287.3  344.34  5347.4  345.44  5477.5  349.51  5589.3  354.38
#Mann= 3 ,-1 , 0
    4548      .1       0  5000.1     .07       0  5006.1      .1       0
Bank Sta=4989.85,5023.51
XS Rating Curve= 0 ,0
Exp/Cntr=0.3,0.1

Type RM Length L Ch R = 1 ,2121    ,112,112,112
BEGIN DESCRIPTION:
Mapping XS 1c62700d
END DESCRIPTION:
XS GIS Cut Line= 5
      2083426.26     13437512.73      2083405.43     13437283.56
      2083285.64     13437241.89      2082918.45     13437228.87
      2082659.04     13437236.65
#Sta/Elev= 30
  4594.9  340.49  4763.3  340.83  4838.6  340.65  4864.4  340.23  4869.7  340.55
  4954.7  338.72  4972.5  337.02 4984.83334.8216  4998.3  332.87  4998.8  332.07
  5003.8  332.07  5004.3  332.87  5006.3  333.02 5011.86334.8225  5022.5  335.45
  5042.5  335.64  5062.6  337.47  5082.6  337.67  5112.6  339.44  5132.6  339.87
  5172.6  341.68  5323.5  345.65  5352.4   346.9  5357.4  346.62  5382.7  348.24
  5392.8  348.23  5452.8  350.45  5512.8  353.47  5532.8  353.98  5578.8  356.08
#Mann= 3 ,-1 , 0
  4594.9      .1       0  4998.3     .07       0  5004.3      .1       0
Bank Sta=4984.83,5011.86
XS Rating Curve= 0 ,0
Exp/Cntr=0.3,0.1

Type RM Length L Ch R = 1 ,2009    ,73,73,73
BEGIN DESCRIPTION:
UNT 187 SanMiguel Cr Watershed 7.0
END DESCRIPTION:
XS GIS Cut Line= 5
      2083480.95     13437606.14      2083454.91     13437260.99
      2083390.39     13437193.08      2083131.44     13437145.66
      2082741.37     13437153.06
#Sta/Elev= 30
  4389.9  341.86  4461.2   341.1  4481.3  341.39  4521.4  340.92  4535.9  341.21
  4803.8  340.24    4886   339.1  4906.9  338.15    4947  337.43  4987.7  334.99
  4991.3334.1061  4997.8  332.51    5005   332.3  5005.5   331.5  5010.5   331.5
    5011   332.3 5012.23334.1057  5013.2  335.53  5018.3     337  5048.7  338.64
  5109.4  340.16  5159.4  342.17  5209.4   343.3  5249.4  344.81  5279.4  345.29
  5329.4  347.35  5339.4   347.2  5379.5  348.32  5409.5  350.43  5483.1  352.88
#Mann= 3 ,-1 , 0
  4389.9      .1       0    5005     .07       0    5011      .1       0
Bank Sta=4991.3,5012.23
XS Rating Curve= 0 ,0
Exp/Cntr=0.3,0.1

Type RM Length L Ch R = 1 ,1936    ,111,111,111
BEGIN DESCRIPTION:
Mapping XS 8cddb9c7
END DESCRIPTION:
XS GIS Cut Line= 4
      2083490.07     13437258.14      2083345.53     13437114.91
      2083143.71     13437090.17       2082865.1     13437104.49
#Sta/Elev= 30
  4704.8  340.47  4717.7  340.81  4731.8  340.43  4809.6  340.11  4859.1  338.79
  4887.4   338.8    4929  338.13  4939.1  337.75  4946.4  336.64 4954.68333.9051
  4959.2   332.3  4969.3  332.18  4979.4  333.09  4989.4  333.34  4996.5  331.92
    4997  331.12    5002  331.12  5002.5  331.92  5009.6  333.37 5025.79333.9069
  5049.9  335.98    5060  336.21  5090.2  338.06  5108.5  339.75  5250.5  343.31
  5290.6  345.24  5330.6  346.65  5380.7  347.76  5388.2  348.91  5390.6  348.91
#Mann= 3 ,-1 , 0
  4704.8      .1       0  4996.5     .07       0  5002.5      .1       0
Bank Sta=4954.68,5025.79
XS Rating Curve= 0 ,0
Exp/Cntr=0.3,0.1

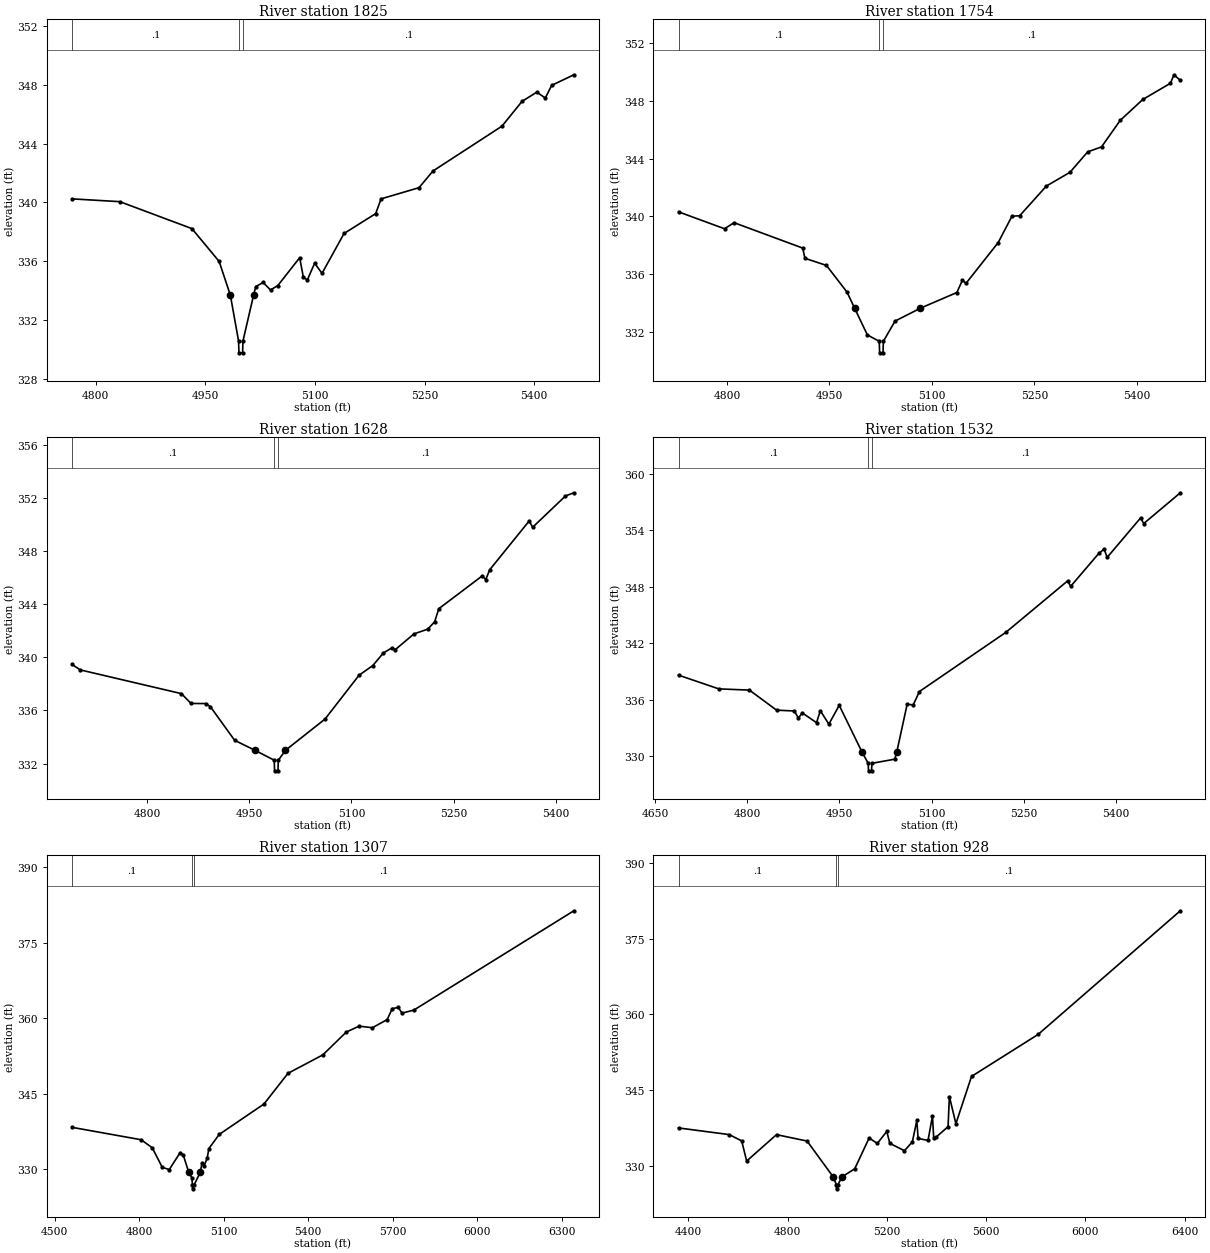
Type RM Length L Ch R = 1 ,1825    ,71,71,71
BEGIN DESCRIPTION:
Mapping XS 06622b5a
END DESCRIPTION:
XS GIS Cut Line= 4
      2083503.53     13437178.53      2083359.42     13437044.84
      2083151.09      13437018.8      2082875.06     13437067.41
#Sta/Elev= 30
  4767.5  340.24  4832.9  340.05  4931.5  338.22  4968.8  335.99 4984.18333.6906
  4995.4  330.58  4995.9  329.78  5000.9  329.78  5001.4  330.58 5015.89  333.69
  5018.9  334.28    5029  334.56  5039.1  334.05  5049.1  334.35    5079  336.24
  5084.1  334.91  5089.5  334.73  5099.5  335.87  5109.6  335.18  5139.8  337.89
  5183.1  339.24  5190.4  340.24  5242.4     341  5261.4  342.13  5355.9  345.18
  5383.3  346.86  5403.6  347.49  5415.2  347.09  5423.9  347.95  5454.3  348.67
#Mann= 3 ,-1 , 0
  4767.5      .1       0  4995.4     .07       0  5001.4      .1       0
Bank Sta=4984.18,5015.89
XS Rating Curve= 0 ,0
Exp/Cntr=0.3,0.1

Type RM Length L Ch R = 1 ,1754    ,126,126,126
BEGIN DESCRIPTION:
UNT 187 SanMiguel Cr Watershed 6.0
END DESCRIPTION:
XS GIS Cut Line= 4
       2083525.3     13437129.35       2083416.1     13436979.72
      2083200.45     13436957.79       2082870.6     13437001.19
#Sta/Elev= 30
    4729  340.31  4796.3  339.14  4810.3  339.56  4910.8   337.8  4914.1  337.09
  4945.5   336.6  4975.7  334.75 4986.83333.6312  5005.5  331.78  5022.9  331.34
  5023.4  330.54  5028.4  330.54  5028.9  331.34    5046  332.74 5083.05333.6314
  5136.5  334.72  5144.7  335.58  5149.8  335.35    5197  338.18  5217.2  340.01
  5228.5  340.04  5267.6   342.1  5302.1  343.05  5328.1  344.47  5348.3  344.81
  5375.7  346.65  5408.8   348.1  5449.2  349.22  5454.4  349.81  5463.7  349.42
#Mann= 3 ,-1 , 0
    4729      .1       0  5022.9     .07       0  5028.9      .1       0
Bank Sta=4986.83,5083.05
XS Rating Curve= 0 ,0
Exp/Cntr=0.3,0.1

Type RM Length L Ch R = 1 ,1628    ,96,96,96
BEGIN DESCRIPTION:
Mapping XS 07be0252
END DESCRIPTION:
XS GIS Cut Line= 4
      2083515.67     13437041.37      2083345.53     13436857.34
      2083138.94     13436867.76      2082862.85     13436909.43
#Sta/Elev= 30
  4689.9  339.47  4701.8  339.06  4850.4  337.27  4864.6  336.53  4886.1  336.52
  4892.9  336.29  4928.6  333.75 4958.46332.9987  4986.7  332.25  4987.2  331.45
  4992.2  331.45  4992.7  332.25 5003.23332.9986  5061.2  335.35  5111.3  338.66
  5131.3  339.38  5146.9  340.33  5159.4  340.72  5164.5  340.59  5191.8  341.77
    5212  342.13  5222.2  342.68  5228.3  343.67  5292.2  346.15  5297.2  345.86
  5303.1  346.61  5361.1  350.29  5366.1  349.81  5414.3  352.17  5426.6  352.41
#Mann= 3 ,-1 , 0
  4689.9      .1       0  4986.7     .07       0  4992.7      .1       0
Bank Sta=4958.46,5003.23
XS Rating Curve= 0 ,0
Exp/Cntr=0.3,0.1

Type RM Length L Ch R = 1 ,1532    ,225,225,225
BEGIN DESCRIPTION:
UNT 187 SanMiguel Cr Watershed 5.0
END DESCRIPTION:
XS GIS Cut Line= 4
      2083544.18      13436998.3      2083400.96     13436798.66
      2083058.07     13436761.76      2082834.53     13436800.83
#Sta/Elev= 30
  4687.8  338.59  4753.4  337.13  4803.3     337  4847.5  334.87  4876.5  334.78
  4883.1  334.02  4889.3  334.58  4912.6  333.54  4918.8  334.81  4932.7  333.38
  4949.6  335.38 4986.94330.3846  4996.8  329.22  4997.3  328.42  5002.3  328.42
  5002.8  329.22  5040.1  329.66 5043.24330.3854  5060.2  335.48  5070.2  335.44
  5080.3  336.85  5221.1  343.14  5321.6   348.6  5326.7  348.03  5372.8  351.55
  5381.1  351.98  5386.2  351.11  5440.6   355.3  5445.7   354.7  5505.3  357.97
#Mann= 3 ,-1 , 0
  4687.8      .1       0  4996.8     .07       0  5002.8      .1       0
Bank Sta=4986.94,5043.24
XS Rating Curve= 0 ,0
Exp/Cntr=0.3,0.1

Type RM Length L Ch R = 1 ,1307    ,379,379,379
BEGIN DESCRIPTION:
UNT 187 SanMiguel Cr Watershed 4.0
END DESCRIPTION:
XS GIS Cut Line= 4
      2083619.16       13436958.      2083649.11     13436730.21
      2083071.85      13436513.2      2082212.45     13436882.13
#Sta/Elev= 30
  4561.7  338.29  4806.5  335.83  4846.4  334.24    4882  330.34  4906.9   329.9
  4945.4  333.27  4956.1  332.86  4975.5329.4421  4986.9  328.28  4989.2  326.87
  4989.7  326.07  4995.2  326.87 5017.68 329.443  5022.5  331.13  5030.9  330.68
  5041.6   332.2  5047.4  334.07  5084.3  336.89    5243  342.92  5328.3  349.02
  5452.2  352.69  5535.3  357.22  5580.9   358.4    5628  358.08  5680.6   359.7
  5698.6  361.88  5720.3  362.12  5733.1  360.99  5774.7  361.57  6343.4  381.32
#Mann= 3 ,-1 , 0
  4561.7      .1       0  4989.2     .07       0  4995.2      .1       0
Bank Sta=4975.5,5017.68
XS Rating Curve= 0 ,0
Exp/Cntr=0.3,0.1

Type RM Length L Ch R = 1 ,928     ,104,104,104
BEGIN DESCRIPTION:
UNT 187 SanMiguel Cr Watershed 3.0
END DESCRIPTION:
XS GIS Cut Line= 5
       2083683.4     13436878.93      2083713.43     13436400.76
       2083249.8     13436335.25      2082837.48     13436474.14
      2082242.84     13436708.52
#Sta/Elev= 30
  4360.9  337.51  4565.2  336.19  4615.3  334.94  4635.4  330.95  4755.6  336.18
  4878.8  334.91 4983.79327.8272    4997  326.24  4997.5  325.44    5003  326.24
 5019.65327.8275  5070.7  329.41  5128.8  335.52  5161.6  334.43  5199.9  336.82
  5212.1  334.46    5271  332.99    5303  334.76  5320.9     339  5326.1  335.44
  5366.1  335.03  5383.9  339.87  5389.1  335.43  5397.7  335.66  5446.8  337.76
  5452.1  343.74  5478.3  338.35  5541.3  347.72  5809.5  356.04  6382.5  380.55
#Mann= 3 ,-1 , 0
  4360.9      .1       0    4997     .07       0    5003      .1       0
Bank Sta=4983.79,5019.65
XS Rating Curve= 0 ,0
Exp/Cntr=0.3,0.1

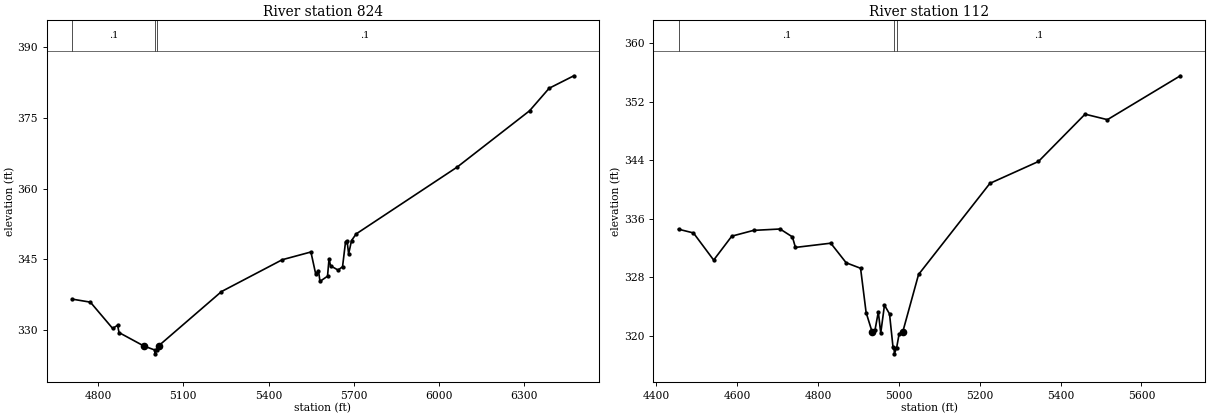
Type RM Length L Ch R = 1 ,824     ,712,712,712
BEGIN DESCRIPTION:
UNT 187 SanMiguel Cr Watershed 2.0
END DESCRIPTION:
XS GIS Cut Line= 4
      2083764.39     13436455.86      2083729.93     13436313.95
      2083345.29     13436226.74      2082182.13     13436608.67
#Sta/Elev= 30
  4708.9  336.51  4773.3  335.86  4851.7  330.27    4869  330.96  4874.1   329.4
 4960.92326.5592  5000.4  325.68  5000.9  324.88  5006.4  325.68 5012.93326.5594
  5234.4  338.11  5448.2  344.88  5548.9  346.52  5565.4  341.92  5575.5  342.56
  5580.8  340.27  5607.3  341.38  5612.6  345.07    5618  343.58  5644.4  342.68
  5660.1  343.39  5670.7  348.71  5676.2  348.77  5681.5  346.11  5691.7  348.95
    5708  350.36  6063.2  364.56  6317.8  376.52  6386.7  381.31  6473.6  383.96
#Mann= 3 ,-1 , 0
  4708.9      .1       0  5000.4     .07       0  5006.4      .1       0
Bank Sta=4960.92,5012.93
XS Rating Curve= 0 ,0
Exp/Cntr=0.3,0.1

Type RM Length L Ch R = 1 ,112     ,0,0,0
BEGIN DESCRIPTION:
UNT 187 SanMiguel Cr Watershed 1.0
END DESCRIPTION:
XS GIS Cut Line= 6
      2083787.22     13436367.76      2083755.97     13436218.46
        2083626.     13435978.89      2083450.41     13435864.47
      2083079.32      13435862.3      2082925.34     13436040.13
#Sta/Elev= 30
  4455.1  334.56    4492  334.05    4542  330.34  4586.8  333.61  4640.6   334.4
  4706.2  334.59  4736.7  333.51  4744.2  332.07  4831.6  332.65  4869.7  329.97
  4905.3  329.22    4919  323.17 4933.84320.5194  4941.1  320.81  4949.2  323.25
  4955.2  320.36  4964.4  324.18  4976.9  322.98  4985.4   318.5  4988.4  318.32
  4988.9  317.52  4994.4  318.32  5000.6  320.23 5009.62320.5186  5048.7  328.37
  5225.2  340.83  5345.2  343.82  5460.5  350.29  5515.8  349.54  5696.1  355.54
#Mann= 3 ,-1 , 0
  4455.1      .1       0  4988.4     .07       0  4994.4      .1       0
Bank Sta=4933.84,5009.62
XS Rating Curve= 0 ,0
Exp/Cntr=0.3,0.1
LCMann Table=0

Chan Stop Cuts=-1
Use User Specified Reach Order=0
Composite Channel Slope=5