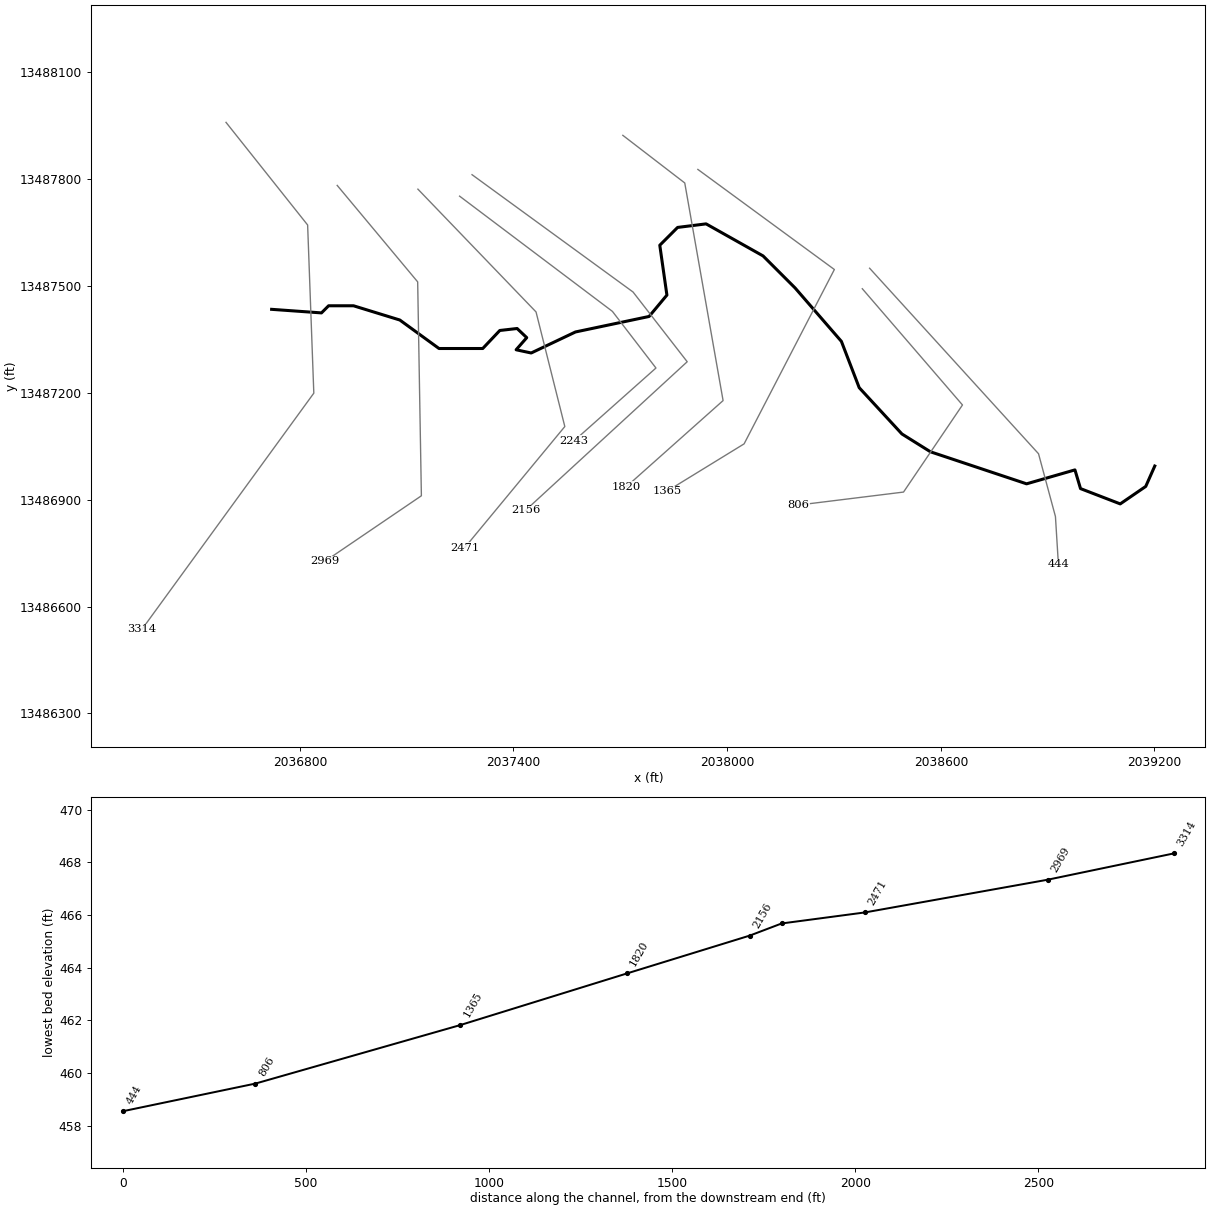
--- UNT 188 SanMiguel Cr Watershed.prj (project) ---

Proj Title=UNT 188 SanMiguel Cr Watershed Base Level Engineering
Current Plan=p01
Default Exp/Contr=0.3,0.1
English Units
Geom File=g01
Flow File=f01
Plan File=p01
Y Axis Title=Elevation
X Axis Title(PF)=Main Channel Distance
X Axis Title(XS)=Station
BEGIN DESCRIPTION:
UNT 188 SanMiguel Cr Watershed
END DESCRIPTION:
DSS Export Rating Curves= 0
DSS Export Rating Curve Sorted= 0
DSS Export Volume Flow Curves= 0
DXF OffsetX= 0
DXF OffsetY= 0
DXF ScaleX= 1
DXF ScaleY= 10

--- UNT 188 SanMiguel Cr Watershed.p01 (plan) ---

Plan Title=Multiple Run
Short Identifier=Multiple
Geom File=g01
Flow File=f01
Subcritical Flow
K Sum by GR= 0
Std Step Tol= 0.01
Critical Tol= 0.01
Num of Std Step Trials= 20
Max Error Tol= 0.3
Flow Tol Ratio= 0.001
Split Flow NTrial= 30
Split Flow Tol= 0.02
Split Flow Ratio= 0.02
Log Output Level= 0
Friction Slope Method= 1
Unsteady Friction Slope Method= 2
Unsteady Bridges Friction Slope Method= 1
Parabolic Critical Depth
Global Vel Dist=  1 , 1 , 1
Global Log Level= 0
CheckData=True
Encroach Param= -1, 0, 0, 0
BEGIN DESCRIPTION:
Multiple Run
END DESCRIPTION:

--- UNT 188 SanMiguel Cr Watershed.f01 (steady flow) ---

Flow Title=Multiple
Number of Profiles=7
Profile Names=10-year,25-year,50-year,1pct_min,100-year,1pct_plu,500-year
River Rch & RM= UNT 188 SanMigue,Reach-1,3314
     148     199     240     144     288     575     421
Boundary for River Rch & Prof#=UNT 188 SanMigue,Reach-1,1
Up Type=0
Dn Type=3
Dn Slope=0.005
Boundary for River Rch & Prof#=UNT 188 SanMigue,Reach-1,2
Up Type=0
Dn Type=3
Dn Slope=0.005
Boundary for River Rch & Prof#=UNT 188 SanMigue,Reach-1,3
Up Type=0
Dn Type=3
Dn Slope=0.005
Boundary for River Rch & Prof#=UNT 188 SanMigue,Reach-1,4
Up Type=0
Dn Type=3
Dn Slope=0.005
Boundary for River Rch & Prof#=UNT 188 SanMigue,Reach-1,5
Up Type=0
Dn Type=3
Dn Slope=0.005
Boundary for River Rch & Prof#=UNT 188 SanMigue,Reach-1,6
Up Type=0
Dn Type=3
Dn Slope=0.005
Boundary for River Rch & Prof#=UNT 188 SanMigue,Reach-1,7
Up Type=0
Dn Type=3
Dn Slope=0.005

--- UNT 188 SanMiguel Cr Watershed.g01 (geometry) ---

Geom Title=Existing Conditions
Program Version=5.05

River Reach=UNT 188 SanMigue,Reach-1
Reach XY= 30
       2036720.8     13487434.54       2036860.8     13487424.54
       2036880.8     13487444.54       2036950.8     13487444.54
       2037080.8     13487404.54       2037190.8     13487324.54
      2037313.61     13487324.54      2037361.53     13487375.16
      2037410.14     13487380.72      2037437.22     13487355.02
      2037407.36     13487320.99      2037449.72     13487311.97
      2037574.03     13487370.99       2037780.8     13487414.54
       2037830.8     13487474.54       2037810.8     13487614.54
       2037860.8     13487664.54       2037940.8     13487674.54
       2038100.8     13487584.54       2038190.8     13487494.54
       2038320.8     13487344.54       2038370.8     13487214.54
       2038490.8     13487084.54       2038570.8     13487034.54
       2038840.8     13486944.54      2038976.63     13486983.67
      2038992.26     13486931.15       2039103.8     13486888.18
      2039175.42     13486937.23       2039200.8     13486994.54

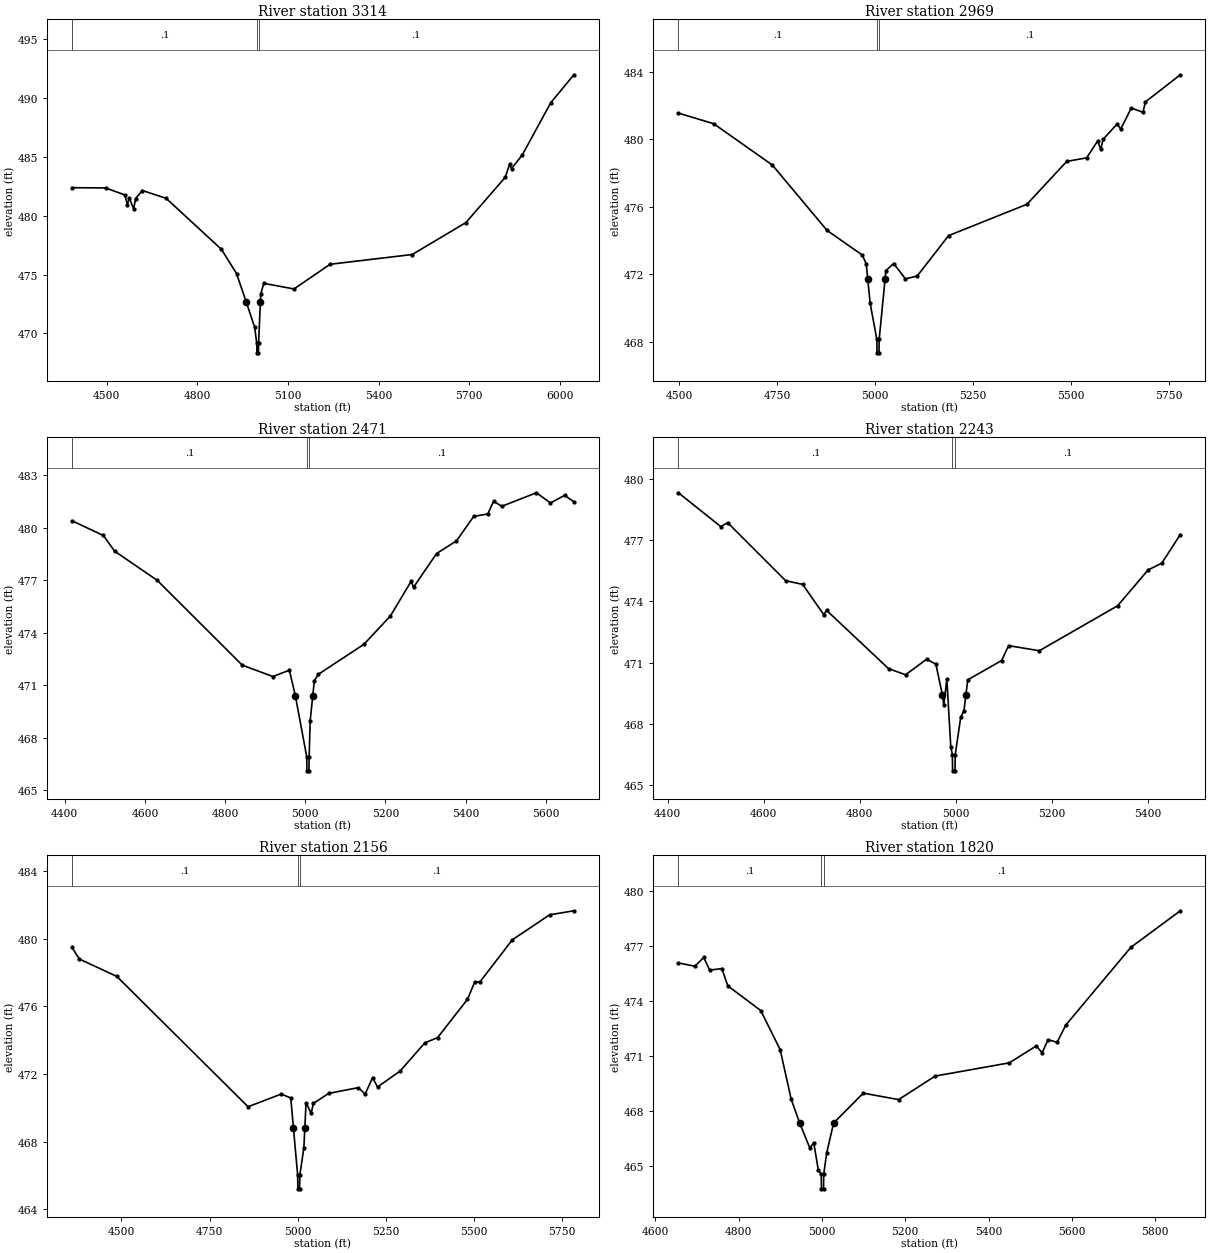
Type RM Length L Ch R = 1 ,3314    ,345,345,345
BEGIN DESCRIPTION:
UNT 188 SanMiguel Cr Watershed 9.0
END DESCRIPTION:
XS GIS Cut Line= 4
      2036592.73     13487959.56       2036821.9     13487671.37
      2036839.26     13487199.15       2036356.6     13486535.93
#Sta/Elev= 30
  4384.8  482.38  4496.1  482.36  4560.1  481.76  4568.2  480.94  4574.5  481.51
    4589  480.58  4595.4  481.46  4617.8  482.14  4696.3  481.48  4879.5  477.14
  4929.5  475.08 4961.72472.6554  4989.5  470.51  4996.5  469.14    4997  468.34
    5002  468.34  5002.5  469.14  5008.4472.6547  5009.5  473.31  5019.6  474.25
  5119.6  473.77  5239.1  475.87  5511.1   476.7  5688.8  479.42  5818.6  483.26
  5833.3  484.38  5839.5     484    5875  485.16  5969.3   489.6  6045.8  491.98
#Mann= 3 ,-1 , 0
  4384.8      .1       0  4996.5     .07       0  5002.5      .1       0
Bank Sta=4961.72,5008.4
XS Rating Curve= 0 ,0
Exp/Cntr=0.3,0.1

Type RM Length L Ch R = 1 ,2969    ,498,498,498
BEGIN DESCRIPTION:
UNT 188 SanMiguel Cr Watershed 8.0
END DESCRIPTION:
XS GIS Cut Line= 4
      2036904.97     13487782.52      2037130.92     13487511.65
      2037141.34     13486910.96      2036870.48     13486726.91
#Sta/Elev= 30
  4497.4  481.54  4587.6  480.91  4737.3  478.46  4876.8  474.59  4966.8  473.13
  4976.8  472.61 4980.69471.6997  4986.8  470.27  5003.8  468.14  5004.3  467.34
  5009.3  467.34  5009.8  468.14 5024.83471.6979  5026.8  472.21  5046.8  472.63
  5076.8  471.72  5106.8  471.89  5186.8  474.28  5386.9  476.14  5488.5  478.68
  5539.4  478.89  5567.4  479.89  5575.3  479.39  5581.4  479.99  5617.3   480.9
  5626.2  480.59  5653.2  481.84  5683.1  481.59  5689.1   482.2  5778.4  483.81
#Mann= 3 ,-1 , 0
  4497.4      .1       0  5003.8     .07       0  5009.8      .1       0
Bank Sta=4980.69,5024.83
XS Rating Curve= 0 ,0
Exp/Cntr=0.3,0.1

Type RM Length L Ch R = 1 ,2471    ,228,228,228
BEGIN DESCRIPTION:
UNT 188 SanMiguel Cr Watershed 7.0
END DESCRIPTION:
XS GIS Cut Line= 4
      2037131.57     13487772.06      2037463.31     13487427.21
      2037544.12      13487105.4      2037262.85      13486765.1
#Sta/Elev= 30
    4418  480.39  4496.3  479.55  4524.6  478.65  4630.5  476.99  4842.8  472.14
  4919.1  471.49  4960.3  471.85 4975.45 470.363  5003.6   466.9  5004.1   466.1
  5009.1   466.1  5009.6   466.9  5012.2  468.97  5018.5470.3645  5022.5  471.25
  5032.8  471.62  5146.2  473.33  5212.3  474.95  5263.7  476.92  5270.2   476.6
  5327.5  478.52    5377  479.24    5420  480.64  5455.2  480.78  5469.5   481.5
  5490.4  481.22  5576.4  481.99  5611.5  481.41  5646.7  481.84  5669.8  481.48
#Mann= 3 ,-1 , 0
    4418      .1       0  5003.6     .07       0  5009.6      .1       0
Bank Sta=4975.45,5018.5
XS Rating Curve= 0 ,0
Exp/Cntr=0.3,0.1

Type RM Length L Ch R = 1 ,2243    ,87,87,87
BEGIN DESCRIPTION:
UNT 188 SanMiguel Cr Watershed 6.0
END DESCRIPTION:
XS GIS Cut Line= 4
      2037248.65     13487752.38       2037677.8     13487428.78
      2037800.03     13487269.75      2037570.07     13487065.23
#Sta/Elev= 30
  4422.4  479.34  4510.6  477.68  4525.1  477.87  4645.9  475.02  4681.3  474.84
    4725  473.36  4731.3  473.56  4860.3   470.7  4895.7   470.4  4939.4  471.16
  4958.9  470.92 4972.37469.4136  4975.4   468.9  4981.7   470.2  4989.9  466.87
  4993.2  466.48  4993.7  465.68  4998.7  465.68  4999.2  466.48  5010.8  468.34
  5017.1   468.6 5021.41469.4147  5025.3  470.15  5095.9   471.1  5110.4  471.83
  5174.5  471.58  5337.6  473.79  5401.1  475.55  5429.5  475.88  5468.2  477.29
#Mann= 3 ,-1 , 0
  4422.4      .1       0  4993.2     .07       0  4999.2      .1       0
Bank Sta=4972.37,5021.41
XS Rating Curve= 0 ,0
Exp/Cntr=0.3,0.1

Type RM Length L Ch R = 1 ,2156    ,336,336,336
BEGIN DESCRIPTION:
UNT 188 SanMiguel Cr Watershed 5.0
END DESCRIPTION:
XS GIS Cut Line= 4
      2037283.58     13487812.66       2037735.7      13487483.2
      2037887.79     13487287.37      2037433.39     13486869.65
#Sta/Elev= 30
  4359.5  479.49  4380.4   478.8    4487  477.77  4859.4  470.07  4953.4  470.82
  4980.6  470.59 4988.07468.8379  5000.2  466.02  5000.7  465.22  5005.7  465.22
  5006.2  466.02  5017.7  467.63 5020.53468.8382    5024  470.32  5038.5  469.68
  5044.8  470.27  5088.3  470.86  5172.2   471.2  5191.8  470.82  5212.8  471.79
  5226.9  471.24    5291  472.18  5361.3  473.85  5397.1  474.15  5482.2  476.42
  5503.1  477.46  5517.3  477.44  5609.2  479.93  5715.2  481.41  5784.1  481.65
#Mann= 3 ,-1 , 0
  4359.5      .1       0  5000.2     .07       0  5006.2      .1       0
Bank Sta=4988.07,5020.53
XS Rating Curve= 0 ,0
Exp/Cntr=0.3,0.1

Type RM Length L Ch R = 1 ,1820    ,455,455,455
BEGIN DESCRIPTION:
UNT 188 SanMiguel Cr Watershed 4.0
END DESCRIPTION:
XS GIS Cut Line= 4
      2037707.07     13487923.13      2037880.92     13487789.43
      2037988.56     13487178.32      2037716.36     13486935.96
#Sta/Elev= 30
  4655.7  476.08  4695.4   475.9  4716.3  476.38  4730.8  475.69  4759.8  475.77
  4774.3  474.83  4853.2  473.49  4899.8  471.36  4926.3  468.66 4946.74467.3581
  4970.9  466.01  4980.5  466.28  4991.2  464.83  4998.4  464.58  4998.9  463.78
  5003.9  463.78  5004.4  464.58  5011.5  465.74 5028.03467.3581  5099.1  468.99
  5184.1  468.64  5271.8  469.92  5449.7  470.64  5514.2  471.56  5528.4  471.19
  5542.6   471.9  5564.4  471.76  5585.3   472.7  5741.3  476.93    5860  478.92
#Mann= 3 ,-1 , 0
  4655.7      .1       0  4998.4     .07       0  5004.4      .1       0
Bank Sta=4946.74,5028.03
XS Rating Curve= 0 ,0
Exp/Cntr=0.3,0.1

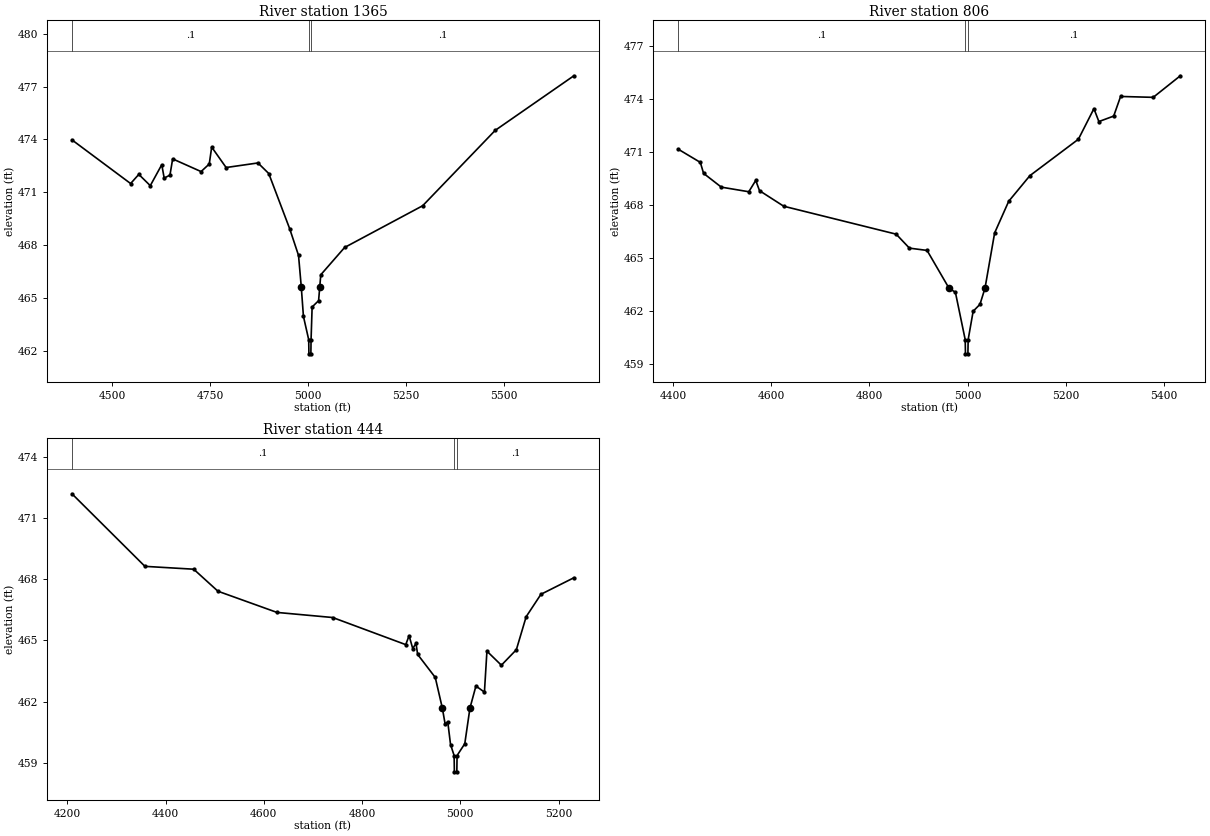
Type RM Length L Ch R = 1 ,1365    ,559,559,559
BEGIN DESCRIPTION:
UNT 188 SanMiguel Cr Watershed 3.0
END DESCRIPTION:
XS GIS Cut Line= 4
      2037917.75     13487827.43      2038301.06     13487546.37
      2038047.59     13487056.79      2037830.96     13486923.82
#Sta/Elev= 30
    4397  473.97  4546.7  471.49  4567.6  472.01  4596.9  471.37  4626.2  472.56
  4632.4   471.8  4647.1  471.97    4654  472.89  4726.5  472.17  4747.4   472.6
  4753.6  473.56  4790.4   472.4  4871.7  472.66  4899.2  472.06  4952.7  468.92
  4975.2  467.41 4982.12465.6439  4987.7  463.95  5001.2  462.62  5001.7  461.82
  5006.7  461.82  5007.2  462.62  5009.9  464.48  5026.4  464.84 5029.46465.6432
    5032  466.31  5092.8  467.86    5292  470.23  5477.1  474.51  5677.8  477.61
#Mann= 3 ,-1 , 0
    4397      .1       0  5001.2     .07       0  5007.2      .1       0
Bank Sta=4982.12,5029.46
XS Rating Curve= 0 ,0
Exp/Cntr=0.3,0.1

Type RM Length L Ch R = 1 ,806     ,362,362,362
BEGIN DESCRIPTION:
UNT 188 SanMiguel Cr Watershed 2.0
END DESCRIPTION:
XS GIS Cut Line= 4
      2038379.52      13487492.4      2038660.79     13487165.99
      2038495.25      13486921.4      2038200.11     13486884.94
#Sta/Elev= 30
  4410.4  471.17  4455.1  470.43  4461.7  469.81  4497.9  469.03  4553.9  468.77
  4568.1  469.41  4575.8  468.83  4625.2  467.95  4854.5  466.37  4881.5  465.58
  4917.5  465.45 4962.17463.3178  4975.3  463.08  4995.3   460.4  4995.8   459.6
  5000.8   459.6  5001.3   460.4  5011.5  462.01  5025.4   462.4 5035.68 463.318
  5055.3  466.44    5084  468.23  5127.2  469.68  5226.1  471.74  5257.8  473.47
  5267.9  472.74  5298.1  473.05  5312.2  474.16  5378.7  474.11    5434  475.33
#Mann= 3 ,-1 , 0
  4410.4      .1       0  4995.3     .07       0  5001.3      .1       0
Bank Sta=4962.17,5035.68
XS Rating Curve= 0 ,0
Exp/Cntr=0.3,0.1

Type RM Length L Ch R = 1 ,444     ,0,0,0
BEGIN DESCRIPTION:
UNT 188 SanMiguel Cr Watershed 1.0
END DESCRIPTION:
XS GIS Cut Line= 4
      2038400.02     13487549.98      2038874.37     13487029.01
      2038921.85     13486852.73       2038930.2     13486718.12
#Sta/Elev= 30
  4209.2  472.19  4357.8  468.63  4457.1  468.49  4506.5  467.41  4626.7  466.37
  4740.2  466.12  4888.9  464.79  4895.7  465.23  4903.1   464.6  4909.8  464.85
  4913.1  464.31    4949  463.18 4963.39461.6781  4969.2  460.88  4974.4  461.01
  4980.1  459.89  4987.4  459.35  4987.9  458.55  4992.9  458.55  4993.4  459.35
  5009.1  459.93 5019.63461.6783  5031.8  462.76  5049.1  462.46  5054.2  464.47
  5083.6  463.78  5114.1  464.54  5134.1  466.16  5164.2  467.26  5231.2  468.07
#Mann= 3 ,-1 , 0
  4209.2      .1       0  4987.4     .07       0  4993.4      .1       0
Bank Sta=4963.39,5019.63
XS Rating Curve= 0 ,0
Exp/Cntr=0.3,0.1
LCMann Table=0

Chan Stop Cuts=-1
Use User Specified Reach Order=0
Composite Channel Slope=5