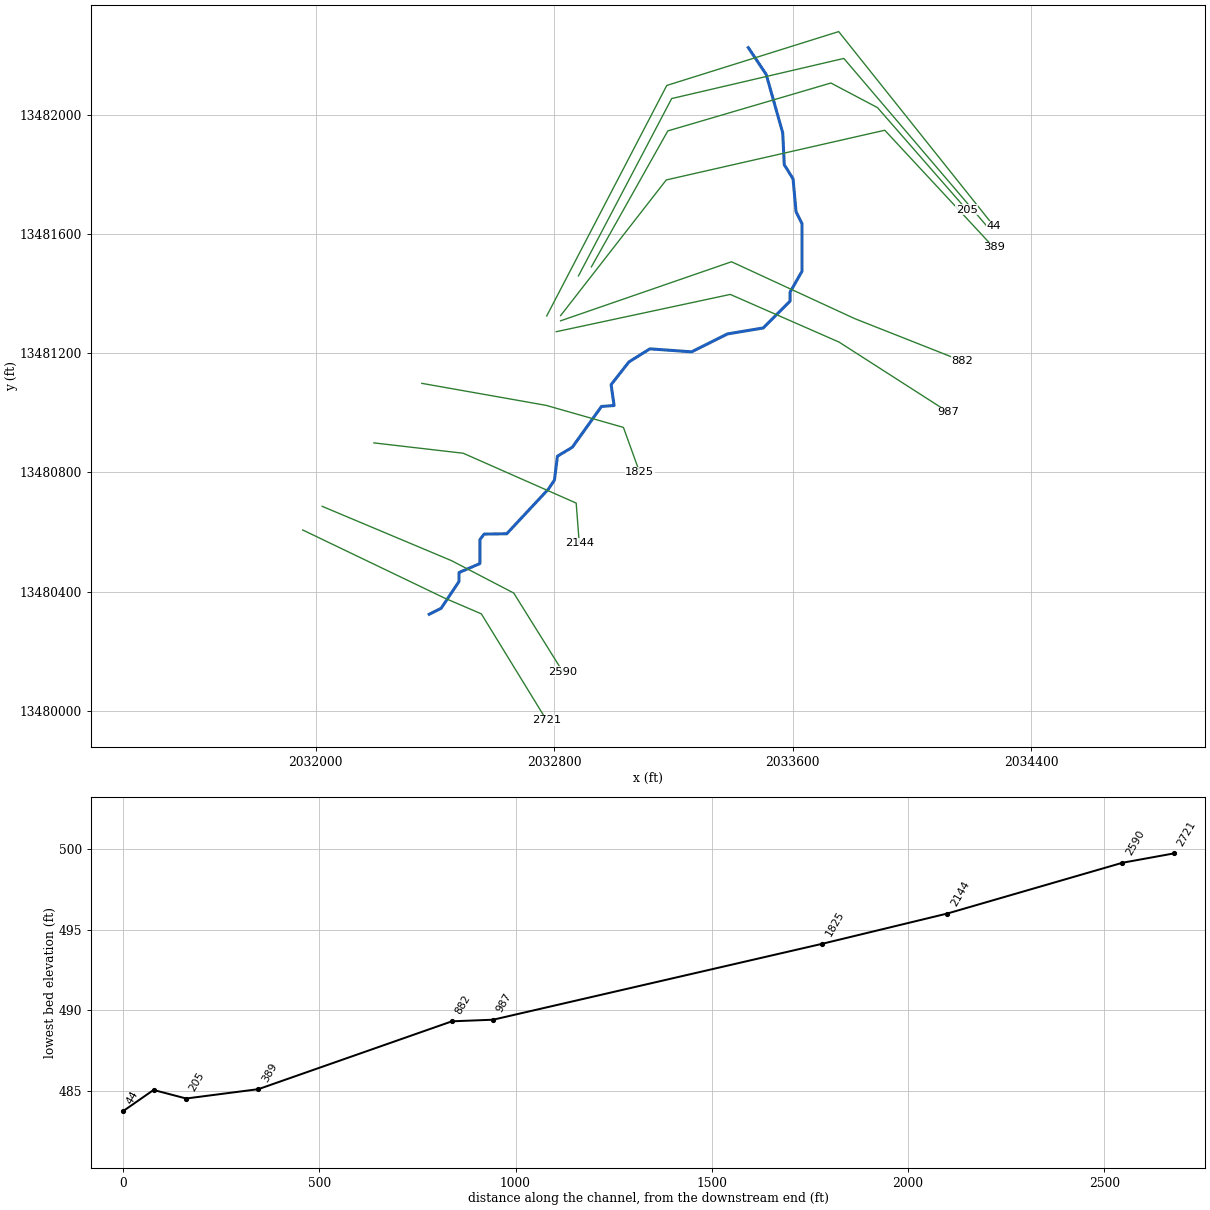
--- UNT 189 SanMiguel Cr Watershed.prj (project) ---

Proj Title=UNT 189 SanMiguel Cr Watershed Base Level Engineering
Current Plan=p01
Default Exp/Contr=0.3,0.1
English Units
Geom File=g01
Flow File=f01
Plan File=p01
Y Axis Title=Elevation
X Axis Title(PF)=Main Channel Distance
X Axis Title(XS)=Station
BEGIN DESCRIPTION:
UNT 189 SanMiguel Cr Watershed
END DESCRIPTION:
DSS Export Rating Curves= 0
DSS Export Rating Curve Sorted= 0
DSS Export Volume Flow Curves= 0
DXF OffsetX= 0
DXF OffsetY= 0
DXF ScaleX= 1
DXF ScaleY= 10

--- UNT 189 SanMiguel Cr Watershed.p01 (plan) ---

Plan Title=Multiple Run
Short Identifier=Multiple
Geom File=g01
Flow File=f01
Subcritical Flow
K Sum by GR= 0
Std Step Tol= 0.01
Critical Tol= 0.01
Num of Std Step Trials= 20
Max Error Tol= 0.3
Flow Tol Ratio= 0.001
Split Flow NTrial= 30
Split Flow Tol= 0.02
Split Flow Ratio= 0.02
Log Output Level= 0
Friction Slope Method= 1
Unsteady Friction Slope Method= 2
Unsteady Bridges Friction Slope Method= 1
Parabolic Critical Depth
Global Vel Dist=  1 , 1 , 1
Global Log Level= 0
CheckData=True
Encroach Param= -1, 0, 0, 0
BEGIN DESCRIPTION:
Multiple Run
END DESCRIPTION:

--- UNT 189 SanMiguel Cr Watershed.f01 (steady flow) ---

Flow Title=Multiple
Number of Profiles=7
Profile Names=10-year,25-year,50-year,1pct_min,100-year,1pct_plu,500-year
River Rch & RM= UNT 189 SanMigue,Reach-1,2721
      85     110     130      77     154     307     217
River Rch & RM= UNT 189 SanMigue,Reach-1,882
     164     223     271     165     329     657     491
Boundary for River Rch & Prof#=UNT 189 SanMigue,Reach-1,1
Up Type=0
Dn Type=3
Dn Slope=0.005
Boundary for River Rch & Prof#=UNT 189 SanMigue,Reach-1,2
Up Type=0
Dn Type=3
Dn Slope=0.005
Boundary for River Rch & Prof#=UNT 189 SanMigue,Reach-1,3
Up Type=0
Dn Type=3
Dn Slope=0.005
Boundary for River Rch & Prof#=UNT 189 SanMigue,Reach-1,4
Up Type=0
Dn Type=3
Dn Slope=0.005
Boundary for River Rch & Prof#=UNT 189 SanMigue,Reach-1,5
Up Type=0
Dn Type=3
Dn Slope=0.005
Boundary for River Rch & Prof#=UNT 189 SanMigue,Reach-1,6
Up Type=0
Dn Type=3
Dn Slope=0.005
Boundary for River Rch & Prof#=UNT 189 SanMigue,Reach-1,7
Up Type=0
Dn Type=3
Dn Slope=0.005

--- UNT 189 SanMiguel Cr Watershed.g01 (geometry) ---

Geom Title=Existing Conditions
Program Version=5.05

River Reach=UNT 189 SanMigue,Reach-1
Reach XY= 30
       2032380.8     13480324.54       2032420.8     13480344.54
       2032480.8     13480434.54       2032480.8     13480464.54
       2032550.8     13480494.54       2032550.8     13480574.54
      2032564.92     13480593.47       2032640.8     13480594.54
       2032780.8     13480744.54       2032800.8     13480774.54
       2032810.8     13480854.54       2032860.8     13480884.54
       2032958.4     13481021.34       2033000.8     13481024.54
       2032990.8     13481094.54      2033050.59     13481170.76
       2033120.8     13481214.54       2033260.8     13481204.54
       2033380.8     13481264.54       2033500.8     13481284.54
       2033590.8     13481374.54       2033590.8     13481404.54
       2033630.8     13481474.54       2033630.8     13481634.54
       2033610.8     13481674.54       2033600.8     13481784.54
      2033571.41      13481831.8       2033566.2     13481938.57
       2033510.8     13482134.54       2033450.8     13482224.54

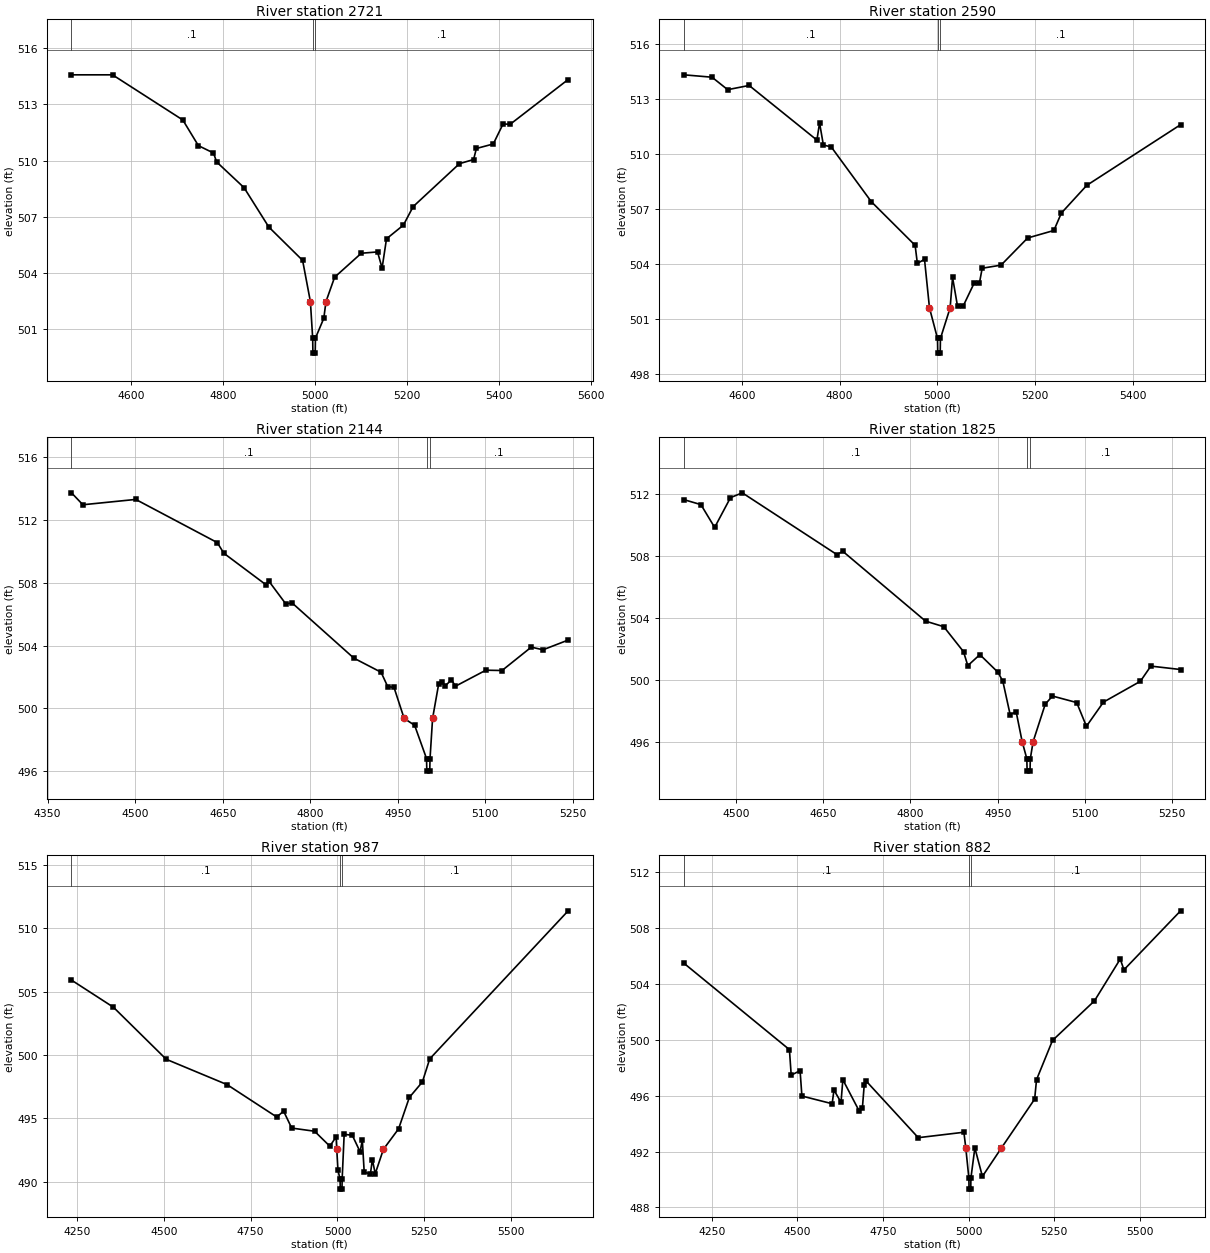
Type RM Length L Ch R = 1 ,2721    ,131,131,131
BEGIN DESCRIPTION:
UNT 189 SanMiguel Cr Watershed 10.0
END DESCRIPTION:
XS GIS Cut Line= 4
       2031956.8     13480607.25      2032432.16     13480379.06
      2032555.74     13480326.01      2032774.22     13479969.75
#Sta/Elev= 30
  4470.3  514.58  4559.5  514.58  4712.3  512.17  4746.2   510.8  4778.9  510.41
  4785.9  509.93  4845.4  508.56  4899.2  506.46  4972.7  504.68 4989.64502.4792
  4994.6  500.53  4995.1  499.73  5000.1  499.73  5000.6  500.53  5018.8  501.59
 5023.51502.4796  5042.3  503.78  5100.3  505.06  5135.6  505.13  5145.5  504.27
  5155.1  505.83  5191.8  506.56  5213.1  507.55  5313.7  509.84  5344.4  510.06
  5350.5  510.65  5387.2  510.89  5408.5  511.96  5423.9  511.94    5550  514.33
#Mann= 3 ,-1 , 0
  4470.3      .1       0  4994.6     .07       0  5000.6      .1       0
Bank Sta=4989.64,5023.51
XS Rating Curve= 0 ,0
Exp/Cntr=0.3,0.1

Type RM Length L Ch R = 1 ,2590    ,446,446,446
BEGIN DESCRIPTION:
UNT 189 SanMiguel Cr Watershed 9.0
END DESCRIPTION:
XS GIS Cut Line= 4
      2032021.97     13480686.56      2032456.02     13480504.26
      2032664.36     13480395.75      2032828.59     13480132.33
#Sta/Elev= 30
  4481.4  514.33  4538.9   514.2  4570.9  513.52  4614.8  513.75  4753.5  510.77
  4758.9  511.71  4766.7   510.5  4782.7   510.4  4864.8  507.41  4954.4  505.03
    4959  504.04  4973.6  504.27 4983.76501.6187  5000.2  499.95  5000.7  499.15
  5005.7  499.15  5006.2  499.95 5026.02501.6201    5031  503.28  5041.2   501.7
  5053.1  501.74  5075.2  502.97    5086  502.98  5091.6  503.78  5130.2  503.95
  5184.6  505.43  5238.3  505.84  5253.6  506.79  5305.5   508.3  5497.5  511.61
#Mann= 3 ,-1 , 0
  4481.4      .1       0  5000.2     .07       0  5006.2      .1       0
Bank Sta=4983.76,5026.02
XS Rating Curve= 0 ,0
Exp/Cntr=0.3,0.1

Type RM Length L Ch R = 1 ,2144    ,319,319,319
BEGIN DESCRIPTION:
UNT 189 SanMiguel Cr Watershed 8.0
END DESCRIPTION:
XS GIS Cut Line= 4
      2032195.65     13480899.22      2032495.09      13480864.5
      2032873.72     13480697.44      2032884.14     13480562.03
#Sta/Elev= 30
  4390.9  513.73  4410.4  512.97    4501  513.31  4640.7  510.56    4652  509.88
  4723.9  507.88  4729.4  508.09  4758.2  506.65  4768.8  506.72  4874.7   503.2
  4921.4   502.3  4932.7  501.39  4943.6  501.33 4960.92499.3583  4978.9  498.92
  4999.3   496.8  4999.8     496  5004.8     496  5005.3   496.8 5009.67499.3587
  5020.1  501.55  5025.6  501.69  5031.1  501.42    5042  501.82  5048.9  501.41
    5101  502.43  5128.7  502.41  5178.8   503.9  5198.9  503.73    5242  504.35
#Mann= 3 ,-1 , 0
  4390.9      .1       0  4999.3     .07       0  5005.3      .1       0
Bank Sta=4960.92,5009.67
XS Rating Curve= 0 ,0
Exp/Cntr=0.3,0.1

Type RM Length L Ch R = 1 ,1825    ,838,838,838
BEGIN DESCRIPTION:
UNT 189 SanMiguel Cr Watershed 7.0
END DESCRIPTION:
XS GIS Cut Line= 4
      2032356.21     13481098.87      2032772.86     13481025.09
       2033032.1     13480951.16      2033086.65     13480800.01
#Sta/Elev= 30
  4410.9  511.62  4440.1   511.3  4463.7  509.83  4490.9  511.75  4511.2  512.06
  4673.7  508.08  4683.9  508.29  4826.1  503.79  4857.4  503.43  4891.3  501.82
  4898.7  500.92  4919.4  501.63  4950.6  500.49  4958.9  499.91  4971.4  497.77
  4981.8  497.94 4992.09496.0206  5000.1  494.92  5000.6  494.12  5005.6  494.12
  5006.1  494.92 5010.91496.0215  5031.8  498.44  5044.2  498.96  5085.8  498.54
  5102.5  497.01  5131.8  498.57  5195.2  499.91  5213.2  500.89  5264.3  500.67
#Mann= 3 ,-1 , 0
  4410.9      .1       0  5000.1     .07       0  5006.1      .1       0
Bank Sta=4992.09,5010.91
XS Rating Curve= 0 ,0
Exp/Cntr=0.3,0.1

Type RM Length L Ch R = 1 ,987     ,105,105,105
BEGIN DESCRIPTION:
UNT 189 SanMiguel Cr Watershed 6.0
END DESCRIPTION:
XS GIS Cut Line= 4
      2032806.95     13481272.05       2033390.3     13481397.05
      2033754.88     13481237.33       2034121.5     13481002.14
#Sta/Elev= 30
  4234.1  505.91  4354.8  503.77  4506.9  499.66  4682.1  497.66  4825.3   495.1
  4844.8  495.57  4868.2  494.23  4934.1  493.98    4978   492.8    4996  493.53
    4998492.5522  5001.4  490.89  5007.5  490.21    5008  489.41    5013  489.41
  5013.5  490.21  5019.3  493.74  5042.7  493.66  5065.1  492.36  5071.6  493.26
    5077  490.74  5094.9  490.61  5100.4  491.74  5108.8  490.63 5132.26492.5528
    5176  494.17    5207  496.65  5244.5  497.87  5265.6  499.69  5664.3  511.38
#Mann= 3 ,-1 , 0
  4234.1      .1       0  5007.5     .07       0  5013.5      .1       0
Bank Sta=4998,5132.26
XS Rating Curve= 0 ,0
Exp/Cntr=0.3,0.1

Type RM Length L Ch R = 1 ,882     ,493,493,493
BEGIN DESCRIPTION:
UNT 189 SanMiguel Cr Watershed 5.0
END DESCRIPTION:
XS GIS Cut Line= 4
      2032821.51     13481308.62      2033394.46     13481506.54
      2033808.24     13481315.57      2034168.75     13481173.22
#Sta/Elev= 30
    4169  505.47  4476.9  499.29  4482.1  497.46    4508  497.79  4513.3  495.97
  4601.6  495.42  4606.9   496.4  4627.5  495.52  4632.8  497.14  4680.5   494.9
  4689.8   495.1  4695.1  496.73  4701.7  497.02  4852.9  492.99  4986.1  493.38
 4991.59492.2599  5000.6  490.11  5001.1  489.31  5006.1  489.31  5006.6  490.11
  5018.1  492.26  5040.1  490.22 5095.76 492.261  5192.6  495.75  5198.1  497.14
  5244.8  499.95  5367.2  502.78  5442.4  505.77  5453.2     505  5618.5  509.22
#Mann= 3 ,-1 , 0
    4169      .1       0  5000.6     .07       0  5006.6      .1       0
Bank Sta=4991.59,5095.76
XS Rating Curve= 0 ,0
Exp/Cntr=0.3,0.1

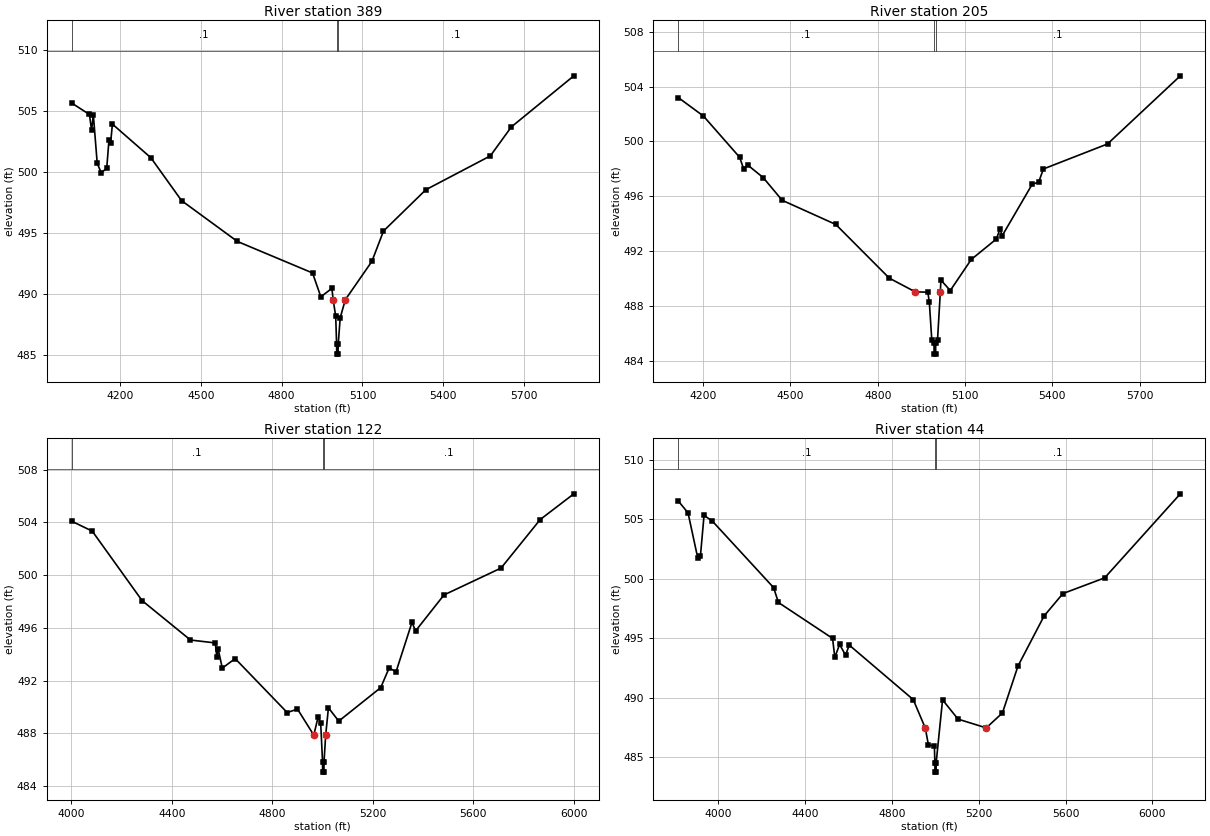
Type RM Length L Ch R = 1 ,389     ,184,184,184
BEGIN DESCRIPTION:
UNT 189 SanMiguel Cr Watershed 4.0
END DESCRIPTION:
XS GIS Cut Line= 4
      2032821.57     13481326.02      2033175.71     13481780.85
      2033908.35     13481947.52      2034272.94     13481555.15
#Sta/Elev= 30
  4021.1  505.64  4086.6  504.71  4094.7  503.41  4101.1   504.7  4115.5  500.72
    4130  499.95  4150.8  500.29    4159  502.59  4165.3  502.38  4171.9  503.92
  4314.6  501.17  4428.6  497.66  4635.7  494.32  4914.7  491.74  4945.5  489.79
  4986.5  490.48 4991.22489.5569  5000.7  488.19    5004   485.9  5004.5   485.1
  5009.5   485.1    5010   485.9  5017.3  488.07  5036.5489.5573    5135  492.69
    5178  495.17  5335.2  498.55  5574.6  501.32  5652.6  503.69  5884.5  507.87
#Mann= 3 ,-1 , 0
  4021.1      .1       0    5004     .07       0    5010      .1       0
Bank Sta=4991.22,5036.5
XS Rating Curve= 0 ,0
Exp/Cntr=0.3,0.1

Type RM Length L Ch R = 1 ,205     ,83,83,83
BEGIN DESCRIPTION:
UNT 189 SanMiguel Cr Watershed 3.0
END DESCRIPTION:
XS GIS Cut Line= 5
      2032924.75     13481489.46      2033180.85     13481945.23
      2033727.72     13482105.82      2033883.97     13482023.36
      2034183.46     13481680.47
#Sta/Elev= 30
  4114.7   503.2  4201.3  501.85  4325.7  498.85    4339  498.03  4353.1  498.29
  4406.6  497.37  4471.7  495.72  4655.9  493.96  4839.8  490.05 4928.83489.0534
    4972  489.03  4977.2  488.31  4985.8  485.52  4993.2  485.32  4993.7  484.52
  4998.7  484.52  4999.2  485.32  5005.4  485.56 5015.04489.0556    5017  489.91
  5049.2  489.15  5121.2  491.41  5207.5   492.9  5220.6  493.66    5227  493.12
  5330.7  496.89  5352.8  497.04  5369.1     498  5589.3  499.82  5839.4  504.78
#Mann= 3 ,-1 , 0
  4114.7      .1       0  4993.2     .07       0  4999.2      .1       0
Bank Sta=4928.83,5015.04
XS Rating Curve= 0 ,0
Exp/Cntr=0.3,0.1

Type RM Length L Ch R = 1 ,122     ,78,78,78
BEGIN DESCRIPTION:
UNT 189 SanMiguel Cr Watershed 2.0
END DESCRIPTION:
XS GIS Cut Line= 4
      2032881.36     13481459.11      2033193.87     13482053.74
      2033771.13     13482188.29      2034247.85     13481629.22
#Sta/Elev= 30
  4001.8  504.08  4083.4  503.33  4281.8  498.06  4474.5  495.07  4573.3  494.85
  4579.1  493.82  4584.7  494.39  4601.1  492.94  4652.4  493.66  4859.5  489.57
  4900.6  489.83 4965.54487.8555  4982.7  489.24    4993  488.76  5000.3  485.85
  5000.8  485.05  5005.8  485.05  5006.3  485.85 5012.83487.8544  5023.8  489.93
  5064.9  488.92    5232  491.46  5265.7  492.96  5292.8  492.65  5356.5  496.41
  5370.8  495.76  5483.9  498.49  5711.2  500.53  5867.1  504.21    6001  506.16
#Mann= 3 ,-1 , 0
  4001.8      .1       0  5000.3     .07       0  5006.3      .1       0
Bank Sta=4965.54,5012.83
XS Rating Curve= 0 ,0
Exp/Cntr=0.3,0.1

Type RM Length L Ch R = 1 ,44      ,0,0,0
BEGIN DESCRIPTION:
UNT 189 SanMiguel Cr Watershed 1.0
END DESCRIPTION:
XS GIS Cut Line= 4
      2032774.99     13481324.98      2033177.45     13482097.69
      2033753.84     13482278.25      2034274.99     13481625.01
#Sta/Elev= 30
  3817.4  506.54  3862.5  505.54  3907.6  501.71  3919.7  501.94  3936.2  505.33
  3974.7  504.84  4256.4  499.25  4278.5     498  4527.8  494.98    4538  493.38
  4560.1  494.47  4587.8  493.56  4604.3  494.42    4899  489.83 4954.28487.4506
  4969.1  486.01  4996.3  485.94  4998.6  484.53  4999.1  483.73  5004.1  483.73
  5004.6  484.53    5034  489.81  5105.2  488.19 5235.14487.4504  5309.6  488.71
  5381.3  492.66  5501.5  496.87  5587.9  498.75    5780  500.07  6128.3  507.14
#Mann= 3 ,-1 , 0
  3817.4      .1       0  4998.6     .07       0  5004.6      .1       0
Bank Sta=4954.28,5235.14
XS Rating Curve= 0 ,0
Exp/Cntr=0.3,0.1
LCMann Table=0

Chan Stop Cuts=-1
Use User Specified Reach Order=0
Composite Channel Slope=5