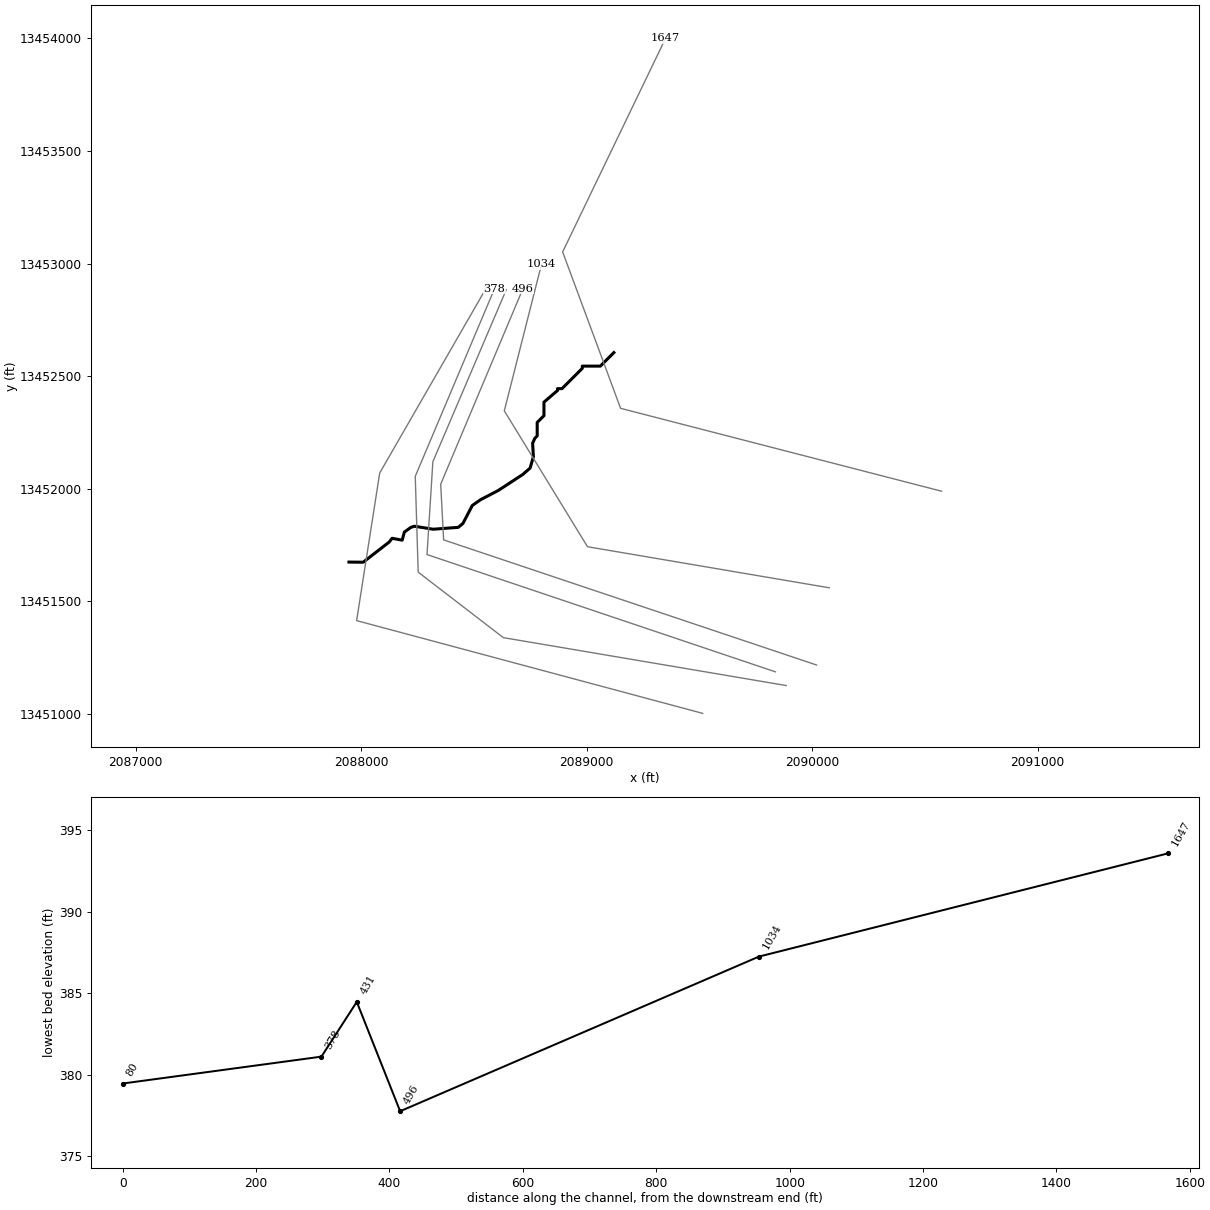
--- UNT 190 SanMiguel Cr Watershed.prj (project) ---

Proj Title=UNT 190 SanMiguel Cr Watershed Base Level Engineering
Current Plan=p01
Default Exp/Contr=0.3,0.1
English Units
Geom File=g01
Flow File=f01
Plan File=p01
Y Axis Title=Elevation
X Axis Title(PF)=Main Channel Distance
X Axis Title(XS)=Station
BEGIN DESCRIPTION:
UNT 190 SanMiguel Cr Watershed
END DESCRIPTION:
DSS Export Rating Curves= 0
DSS Export Rating Curve Sorted= 0
DSS Export Volume Flow Curves= 0
DXF OffsetX= 0
DXF OffsetY= 0
DXF ScaleX= 1
DXF ScaleY= 10

--- UNT 190 SanMiguel Cr Watershed.p01 (plan) ---

Plan Title=Multiple Run
Short Identifier=Multiple
Geom File=g01
Flow File=f01
Subcritical Flow
K Sum by GR= 0
Std Step Tol= 0.01
Critical Tol= 0.01
Num of Std Step Trials= 20
Max Error Tol= 0.3
Flow Tol Ratio= 0.001
Split Flow NTrial= 30
Split Flow Tol= 0.02
Split Flow Ratio= 0.02
Log Output Level= 0
Friction Slope Method= 1
Unsteady Friction Slope Method= 2
Unsteady Bridges Friction Slope Method= 1
Parabolic Critical Depth
Global Vel Dist=  1 , 1 , 1
Global Log Level= 0
CheckData=True
Encroach Param= -1, 0, 0, 0
BEGIN DESCRIPTION:
Multiple Run
END DESCRIPTION:

--- UNT 190 SanMiguel Cr Watershed.f01 (steady flow) ---

Flow Title=Multiple
Program Version=5.05
Number of Profiles= 7
Profile Names=10-year,25-year,50-year,1pct_min,100-year,1pct_plu,500-year
River Rch & RM=UNT 190 SanMigue,Reach-1         ,1647
      99     131     156      94     187     373     270
Boundary for River Rch & Prof#=UNT 190 SanMigue,Reach-1         , 1
Up Type= 0
Dn Type= 3
Dn Slope=0.014
Boundary for River Rch & Prof#=UNT 190 SanMigue,Reach-1         , 2
Up Type= 0
Dn Type= 3
Dn Slope=0.014
Boundary for River Rch & Prof#=UNT 190 SanMigue,Reach-1         , 3
Up Type= 0
Dn Type= 3
Dn Slope=0.014
Boundary for River Rch & Prof#=UNT 190 SanMigue,Reach-1         , 4
Up Type= 0
Dn Type= 3
Dn Slope=0.014
Boundary for River Rch & Prof#=UNT 190 SanMigue,Reach-1         , 5
Up Type= 0
Dn Type= 3
Dn Slope=0.014
Boundary for River Rch & Prof#=UNT 190 SanMigue,Reach-1         , 6
Up Type= 0
Dn Type= 3
Dn Slope=0.014
Boundary for River Rch & Prof#=UNT 190 SanMigue,Reach-1         , 7
Up Type= 0
Dn Type= 3
Dn Slope=0.014
DSS Import GetInterval= 0
DSS Import GetPeak= 0
DSS Import FillOption= 0

--- UNT 190 SanMiguel Cr Watershed.g01 (geometry) ---

Geom Title=Existing Conditions
Program Version=5.05

River Reach=UNT 190 SanMigue,Reach-1
Reach XY= 30
       2089120.8     13452604.54       2089060.8     13452544.54
       2088980.8     13452544.54       2088980.8     13452534.54
       2088890.8     13452444.54       2088870.8     13452444.54
      2088871.22     13452436.55       2088810.8     13452384.54
       2088810.8     13452324.54       2088780.8     13452294.54
       2088780.8     13452234.54      2088770.47     13452224.21
       2088760.5     13452202.23      2088763.97      13452142.5
      2088749.39     13452091.81      2088716.75     13452063.34
      2088608.42      13451992.5      2088529.95     13451951.53
      2088493.14     13451925.84      2088451.47     13451845.98
      2088430.64     13451828.62      2088319.53     13451820.28
      2088236.89     13451833.48      2088220.92     13451828.62
      2088191.75     13451807.78      2088182.03     13451771.67
      2088137.58       13451780.      2088124.39     13451763.34
      2088009.11     13451673.75      2087945.92     13451674.45

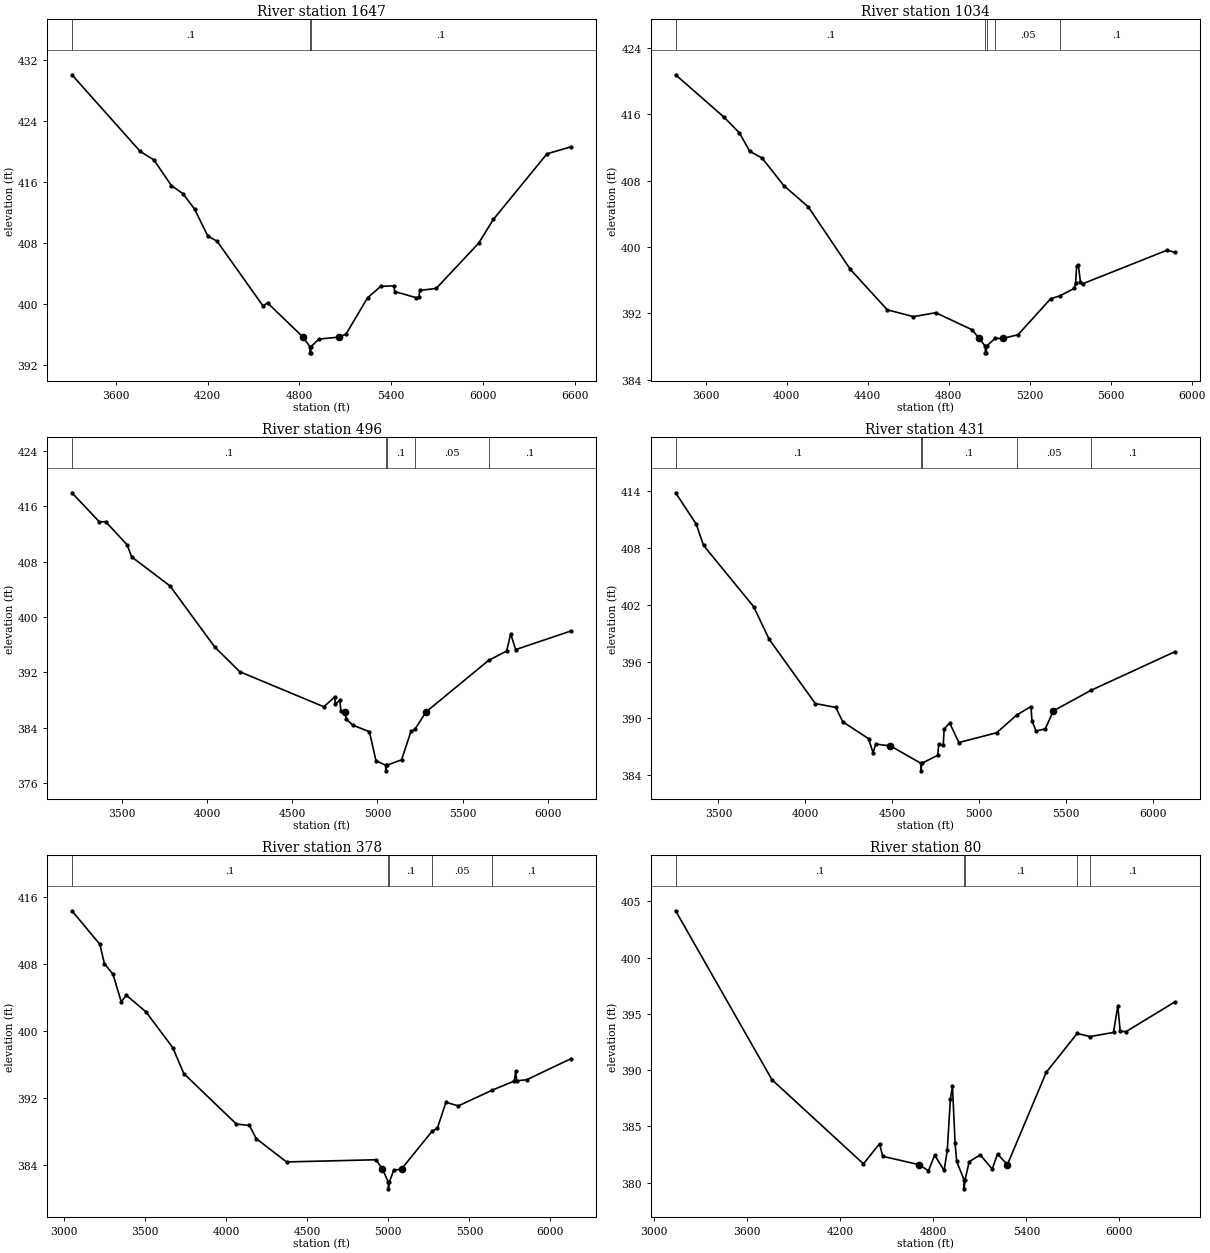
Type RM Length L Ch R = 1 ,1647    ,613,613,613
BEGIN DESCRIPTION:
UNT 190 SanMiguel Cr Watershed 6.0
END DESCRIPTION:
XS GIS Cut Line= 4
      2090574.25     13451989.07      2089150.63     13452357.13
      2088893.68     13453051.58      2089350.01     13454000.02
#Sta/Elev= 30
  3313.8  430.05  3759.6  420.01  3850.1  418.87  3963.7  415.52  4038.9  414.47
    4115  412.45  4201.4  408.92  4263.3   408.2  4562.8  399.73  4592.3  400.13
 4824.33395.6461  4869.5  394.38    4870  393.58    4875  393.58  4875.5  394.38
    4928  395.38 5058.35395.6461  5105.1  396.03  5246.5  400.81  5332.3   402.3
  5418.2  402.36  5423.5  401.62  5564.8  400.81  5581.9  400.88  5587.5  401.76
  5694.9  402.03  5972.2  407.96  6068.2  411.07  6418.8  419.68  6577.2  420.61
#Mann= 3 ,-1 , 0
  3313.8      .1       0  4869.5     .07       0  4875.5      .1       0
Bank Sta=4824.33,5058.35
XS Rating Curve= 0 ,0
Exp/Cntr=0.3,0.1

Type RM Length L Ch R = 1 ,1034    ,538,538,538
BEGIN DESCRIPTION:
UNT 190 SanMiguel Cr Watershed 5.0
END DESCRIPTION:
XS GIS Cut Line= 4
      2090075.94     13451560.26      2089003.92     13451742.55
        2088635.     13452345.85      2088799.94     13452996.91
#Sta/Elev= 30
  3450.8  420.73    3689  415.65  3766.2  413.73  3816.9  411.52  3877.8  410.71
  3985.2  407.39  4105.7  404.84    4314   397.3  4496.5  392.43  4625.7  391.61
  4735.9  392.08  4916.2  390.02 4950.55388.9801  4980.6  388.05  4981.1  387.25
  4986.1  387.25  4986.6  388.05  5029.1  388.99 5066.97388.9801  5142.3  389.43
  5303.8  393.77  5348.1   394.1  5419.9  395.01  5426.8  395.67    5432  397.68
  5440.5  397.78  5450.8  395.75  5461.1  395.56  5877.7   399.6    5917  399.35
#Mann= 5 ,-1 , 0
  3450.8      .1       0  4980.6     .07       0  4986.6      .1       0
  5029.1     .05       0  5348.1      .1       0
Bank Sta=4950.55,5066.97
XS Rating Curve= 0 ,0
Exp/Cntr=0.3,0.1

Type RM Length L Ch R = 1 ,496     ,65,65,65
BEGIN DESCRIPTION:
UNT 190 SanMiguel Cr Watershed 4.0
END DESCRIPTION:
XS GIS Cut Line= 4
      2090019.58     13451217.37       2088365.9     13451772.93
      2088352.88     13452020.33      2088717.45     13452888.34
#Sta/Elev= 30
  3204.8  417.94  3366.3  413.73  3403.1  413.77  3529.2  410.41  3555.5  408.68
  3781.4  404.47    4043  395.68  4191.2  392.08  4685.1  387.02  4748.1  388.42
  4753.4  387.42  4779.6  387.96  4784.9  386.38 4811.58386.2689  4816.4  385.24
  4855.3  384.36  4952.8  383.42  4991.4  379.23  5048.5  378.56    5049  377.76
  5054.5  378.56  5141.6  379.35  5196.9  383.45  5220.1  383.75 5285.23 386.269
  5653.7  393.73  5759.2  395.07    5783  397.56  5812.1  395.28  6138.5  397.98
#Mann= 5 ,-1 , 0
  3204.8      .1       0  5048.5     .07       0  5054.5      .1       0
  5220.1     .05       0  5653.7      .1       0
Bank Sta=4811.58,5285.23
XS Rating Curve= 0 ,0
Exp/Cntr=0.3,0.1

Type RM Length L Ch R = 1 ,431     ,53,53,53
BEGIN DESCRIPTION:
UNT 190 SanMiguel Cr Watershed 3.0
END DESCRIPTION:
XS GIS Cut Line= 4
       2089837.3     13451186.98      2088292.12     13451707.83
      2088318.16     13452120.15      2088643.68     13452884.04
#Sta/Elev= 30
  3253.5  413.82    3372  410.52  3414.2  408.27  3702.8   401.8    3792  398.36
  4057.9  391.57  4175.1  391.17  4216.2  389.64    4364  387.87  4390.2  386.39
  4406.2  387.29  4490.6   387.1  4665.2  385.27  4665.7  384.47  4671.2  385.27
  4762.7  386.11    4768  387.27  4794.2  387.16  4799.5  388.88  4830.9  389.53
  4884.1  387.46  5101.7  388.49    5217  390.36  5299.6  391.26  5304.9  389.77
  5328.6  388.67  5381.3   388.9  5428.5   390.8  5643.9  392.96  6127.6  397.04
#Mann= 5 ,-1 , 0
  3253.5      .1       0  4665.2     .07       0  4671.2      .1       0
    5217     .05       0  5643.9      .1       0
Bank Sta=4490.6,5428.5
XS Rating Curve= 0 ,0
Exp/Cntr=0.3,0.1

Type RM Length L Ch R = 1 ,378     ,298,298,298
BEGIN DESCRIPTION:
UNT 190 SanMiguel Cr Watershed 2.0
END DESCRIPTION:
XS GIS Cut Line= 5
      2089884.98     13451126.23      2088630.66      13451338.9
      2088253.06      13451629.7      2088240.04     13452055.05
      2088591.59     13452888.36
#Sta/Elev= 30
  3048.9  414.39  3221.3  410.37  3248.8  408.08  3302.5  406.77  3353.2  403.48
  3383.6  404.29  3505.3   402.3  3671.2  397.99  3738.6  394.91  4063.2  388.86
  4143.7   388.7  4184.9  387.13  4372.3  384.33  4923.1  384.59 4963.98383.4786
  5000.1  381.91  5000.6  381.11  5006.1  381.91  5033.1  383.33 5081.26383.4787
  5270.2  388.01  5302.5  388.36  5355.3  391.47  5431.9  391.04  5638.2   392.9
  5776.7  394.01  5785.7  395.17  5791.1  394.04  5852.7  394.16  6127.7   396.7
#Mann= 5 ,-1 , 0
  3048.9      .1       0  5000.1     .07       0  5006.1      .1       0
  5270.2     .05       0  5638.2      .1       0
Bank Sta=4963.98,5081.26
XS Rating Curve= 0 ,0
Exp/Cntr=0.3,0.1

Type RM Length L Ch R = 1 ,80      ,0,0,0
BEGIN DESCRIPTION:
UNT 190 SanMiguel Cr Watershed 1.0
END DESCRIPTION:
XS GIS Cut Line= 4
      2089514.74     13451002.59      2087980.06     13451414.53
      2088082.41     13452069.95      2088564.18     13452907.62
#Sta/Elev= 30
  3138.4  404.17  3759.4  389.16  4349.5  381.68  4453.1  383.46  4473.6  382.35
 4705.77381.6155  4768.4  381.07  4808.8  382.45  4869.6  381.09  4889.8  382.89
  4910.1  387.46  4923.3  388.56  4940.4   383.5  4950.5   381.9  4998.2  380.26
  4998.7  379.46  5004.2  380.26  5031.5  381.88  5102.4  382.48  5179.5  381.22
  5213.7  382.55 5277.62381.6153  5527.8  389.81  5727.3  393.27  5810.7  392.99
  5961.8  393.36  5989.2  395.73    6005  393.46  6042.3  393.43  6357.1  396.07
#Mann= 5 ,-1 , 0
  3138.4      .1       0  4998.2     .07       0  5004.2      .1       0
  5727.3     .05       0  5810.7      .1       0
Bank Sta=4705.77,5277.62
XS Rating Curve= 0 ,0
Exp/Cntr=0.3,0.1
LCMann Table=0

Chan Stop Cuts=-1
Use User Specified Reach Order=0
Composite Channel Slope=5