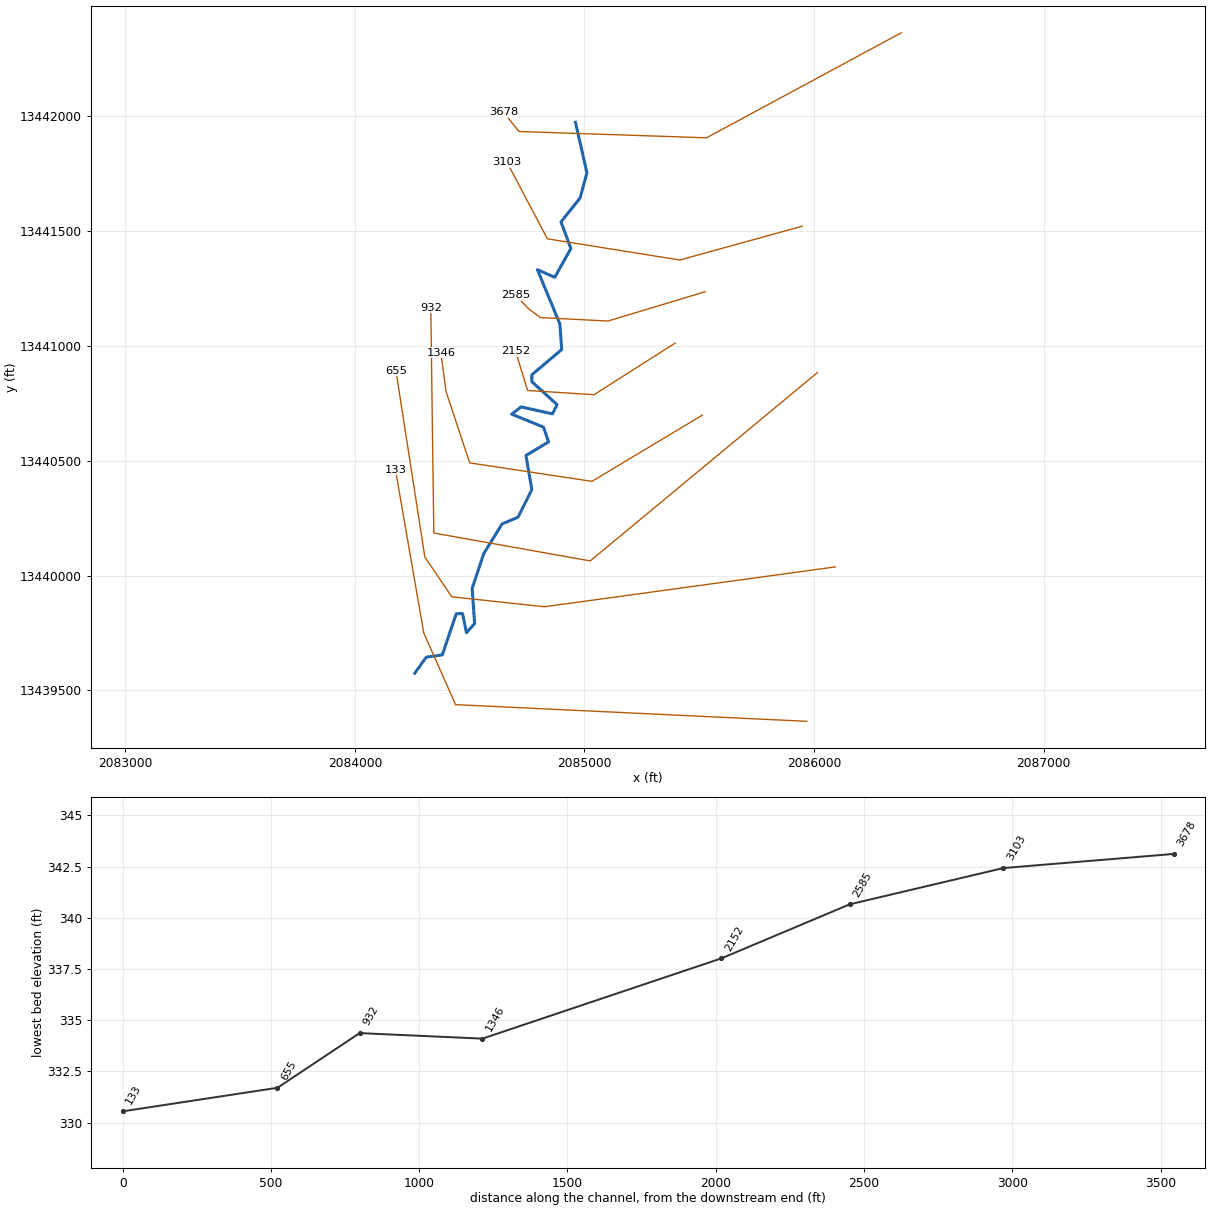
--- UNT 191 SanMiguel Cr Watershed.prj (project) ---

Proj Title=UNT 191 SanMiguel Cr Watershed Base Level Engineering
Current Plan=p01
Default Exp/Contr=0.3,0.1
English Units
Geom File=g01
Flow File=f01
Plan File=p01
Y Axis Title=Elevation
X Axis Title(PF)=Main Channel Distance
X Axis Title(XS)=Station
BEGIN DESCRIPTION:
UNT 191 SanMiguel Cr Watershed
END DESCRIPTION:
DSS Export Rating Curves= 0
DSS Export Rating Curve Sorted= 0
DSS Export Volume Flow Curves= 0
DXF OffsetX= 0
DXF OffsetY= 0
DXF ScaleX= 1
DXF ScaleY= 10

--- UNT 191 SanMiguel Cr Watershed.p01 (plan) ---

Plan Title=Multiple Run
Short Identifier=Multiple
Geom File=g01
Flow File=f01
Subcritical Flow
K Sum by GR= 0
Std Step Tol= 0.01
Critical Tol= 0.01
Num of Std Step Trials= 20
Max Error Tol= 0.3
Flow Tol Ratio= 0.001
Split Flow NTrial= 30
Split Flow Tol= 0.02
Split Flow Ratio= 0.02
Log Output Level= 0
Friction Slope Method= 1
Unsteady Friction Slope Method= 2
Unsteady Bridges Friction Slope Method= 1
Parabolic Critical Depth
Global Vel Dist=  1 , 1 , 1
Global Log Level= 0
CheckData=True
Encroach Param= -1, 0, 0, 0
BEGIN DESCRIPTION:
Multiple Run
END DESCRIPTION:

--- UNT 191 SanMiguel Cr Watershed.f01 (steady flow) ---

Flow Title=Multiple
Number of Profiles=7
Profile Names=10-year,25-year,50-year,1pct_min,100-year,1pct_plu,500-year
River Rch & RM= UNT 191 SanMigue,Reach-1,3678
      68      87     102      60     119     237     165
Boundary for River Rch & Prof#=UNT 191 SanMigue,Reach-1,1
Up Type=0
Dn Type=3
Dn Slope=0.005
Boundary for River Rch & Prof#=UNT 191 SanMigue,Reach-1,2
Up Type=0
Dn Type=3
Dn Slope=0.005
Boundary for River Rch & Prof#=UNT 191 SanMigue,Reach-1,3
Up Type=0
Dn Type=3
Dn Slope=0.005
Boundary for River Rch & Prof#=UNT 191 SanMigue,Reach-1,4
Up Type=0
Dn Type=3
Dn Slope=0.005
Boundary for River Rch & Prof#=UNT 191 SanMigue,Reach-1,5
Up Type=0
Dn Type=3
Dn Slope=0.005
Boundary for River Rch & Prof#=UNT 191 SanMigue,Reach-1,6
Up Type=0
Dn Type=3
Dn Slope=0.005
Boundary for River Rch & Prof#=UNT 191 SanMigue,Reach-1,7
Up Type=0
Dn Type=3
Dn Slope=0.005

--- UNT 191 SanMiguel Cr Watershed.g01 (geometry) ---

Geom Title=Existing Conditions
Program Version=5.05

River Reach=UNT 191 SanMigue,Reach-1
Reach XY= 30
       2084960.8     13441974.54       2085010.8     13441754.54
       2084980.8     13441644.54       2084897.9     13441540.53
       2084940.8     13441424.54      2084870.55     13441299.21
      2084795.03     13441332.63      2084893.12     13441095.21
       2084900.8     13440984.54       2084770.8     13440874.54
       2084770.8     13440844.54       2084880.8     13440744.54
       2084860.8     13440704.54      2084723.85     13440734.54
      2084683.05     13440702.85      2084821.51     13440646.86
      2084843.64     13440582.19      2084745.12     13440523.17
       2084770.8     13440374.54       2084710.8     13440254.54
       2084640.8     13440224.54       2084560.8     13440094.54
       2084510.8     13439944.54      2084521.51     13439790.79
      2084486.09      13439751.2      2084468.73     13439834.54
      2084441.65     13439833.84       2084380.8     13439654.54
       2084310.8     13439644.54       2084260.8     13439574.54

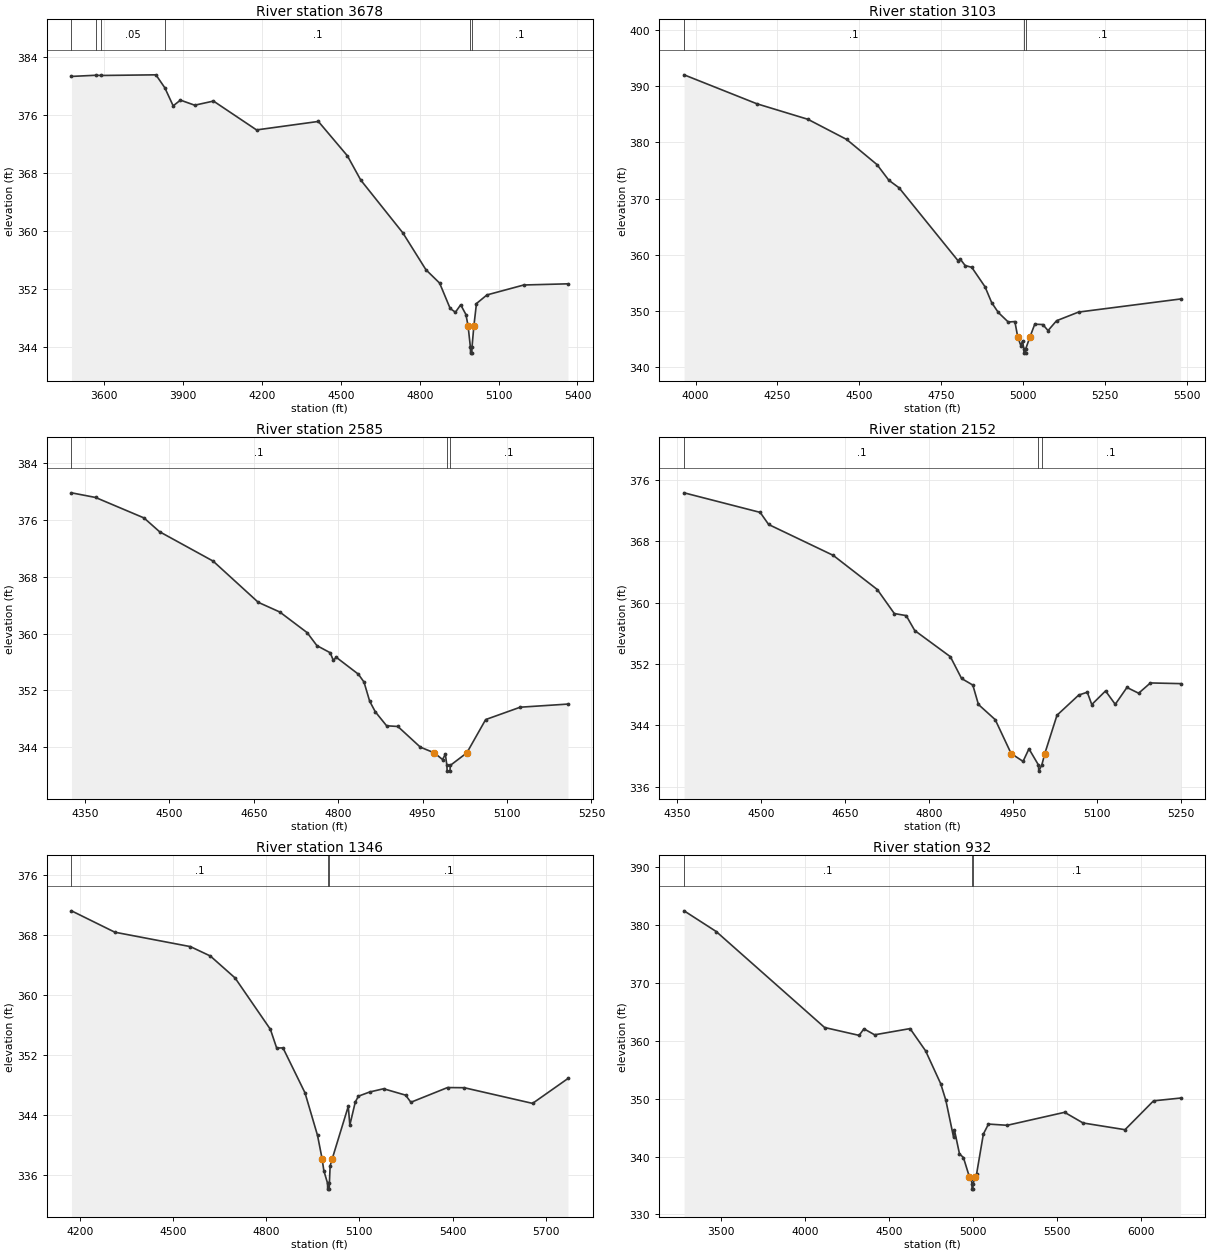
Type RM Length L Ch R = 1 ,3678    ,575,575,575
BEGIN DESCRIPTION:
UNT 191 SanMiguel Cr Watershed 8.0
END DESCRIPTION:
XS GIS Cut Line= 4
      2086379.44      13442364.1      2085531.95     13441906.95
      2084714.82     13441934.44      2084647.27     13442018.42
#Sta/Elev= 30
  3475.6  381.29  3567.8  381.45  3588.4  381.42  3796.7  381.51  3830.6  379.72
  3862.3  377.23  3889.9  378.02  3944.2  377.32  4015.6  377.89  4179.4  373.91
  4414.5  375.08  4524.9  370.34  4575.6     367  4735.6  359.72  4823.7  354.62
  4875.7  352.78  4915.8  349.28  4935.8  348.76  4955.8  349.79  4975.8  348.44
 4984.03346.8434  4992.8  343.92  4993.3  343.12  4998.3  343.12  4998.8  343.92
 5005.91346.8448  5015.8  349.96  5055.8  351.15  5195.9  352.52  5363.9  352.68
#Mann= 6 ,-1 , 0
  3475.6     .15       0  3567.8      .1       0  3588.4     .05       0
  3830.6      .1       0  4992.8     .07       0  4998.8      .1       0
Bank Sta=4984.03,5005.91
XS Rating Curve= 0 ,0
Exp/Cntr=0.3,0.1

Type RM Length L Ch R = 1 ,3103    ,518,518,518
BEGIN DESCRIPTION:
UNT 191 SanMiguel Cr Watershed 7.0
END DESCRIPTION:
XS GIS Cut Line= 4
      2085949.59      13441522.1      2085415.78     13441374.54
      2084838.55     13441466.82      2084662.16     13441801.27
#Sta/Elev= 30
  3965.1  392.07  4187.7   386.9  4343.2  384.14  4461.8  380.54  4554.3  376.06
  4590.6  373.26  4621.5  371.93  4802.6  358.86  4807.6  359.27  4823.5  358.06
  4843.8  357.73  4884.3  354.26  4904.5  351.45  4924.8  349.68  4955.2  347.98
  4975.4  348.06 4984.18345.3227  4993.8  343.75  4998.8   344.6  5002.8  343.23
  5003.3  342.43  5008.3  342.43  5008.8  343.23 5021.47345.3225  5036.2  347.59
  5060.9  347.53  5076.7  346.45  5102.8  348.21  5169.8  349.75  5481.6  352.09
#Mann= 3 ,-1 , 0
  3965.1      .1       0  5002.8     .07       0  5008.8      .1       0
Bank Sta=4984.18,5021.47
XS Rating Curve= 0 ,0
Exp/Cntr=0.3,0.1

Type RM Length L Ch R = 1 ,2585    ,433,433,433
BEGIN DESCRIPTION:
UNT 191 SanMiguel Cr Watershed 6.0
END DESCRIPTION:
XS GIS Cut Line= 5
      2085525.89      13441236.4      2085102.78     13441108.79
       2084808.4      13441123.7      2084758.06     13441160.95
       2084700.8     13441220.87
#Sta/Elev= 30
  4326.2   379.8  4368.9  379.15    4455  376.27  4482.7  374.33  4577.8   370.2
  4658.1   364.4  4696.3  363.04  4744.9  360.14  4762.3  358.31  4785.9  357.31
  4791.5  356.22  4796.5  356.68    4836  354.29    4846  353.18    4856   350.5
    4866  349.01  4886.1  347.04  4906.1  346.94  4946.1  344.03 4970.94343.2283
  4985.5  342.29  4990.5  343.04  4993.2  341.46  4993.7  340.66  4998.7  340.66
  4999.2  341.46 5028.63343.2278  5062.1  347.91  5123.5  349.65  5208.4  350.09
#Mann= 3 ,-1 , 0
  4326.2      .1       0  4993.2     .07       0  4999.2      .1       0
Bank Sta=4970.94,5028.63
XS Rating Curve= 0 ,0
Exp/Cntr=0.3,0.1

Type RM Length L Ch R = 1 ,2152    ,806,806,806
BEGIN DESCRIPTION:
UNT 191 SanMiguel Cr Watershed 5.0
END DESCRIPTION:
XS GIS Cut Line= 4
      2085395.03     13441012.55      2085041.59     13440787.92
      2084752.59     13440806.22      2084699.99     13440976.52
#Sta/Elev= 30
  4362.8  374.31  4498.6  371.76  4513.8  370.18    4629  366.16  4707.8   361.7
  4738.2  358.57  4759.4   358.3  4774.7  356.35  4838.3  352.94  4858.3   350.1
  4878.4  349.24  4888.4  346.71  4918.4  344.73 4946.81340.3129  4968.1  339.29
  4978.6  340.93  4995.6  338.82  4996.1  338.02  5001.6  338.82 5006.93340.3124
  5028.7  345.31  5067.5  347.94  5082.8  348.31  5090.8   346.7  5115.4  348.48
  5132.7  346.73  5153.6  348.93  5174.5  348.18  5195.5  349.52  5249.4  349.43
#Mann= 3 ,-1 , 0
  4362.8      .1       0  4995.6     .07       0  5001.6      .1       0
Bank Sta=4946.81,5006.93
XS Rating Curve= 0 ,0
Exp/Cntr=0.3,0.1

Type RM Length L Ch R = 1 ,1346    ,414,414,414
BEGIN DESCRIPTION:
UNT 191 SanMiguel Cr Watershed 4.0
END DESCRIPTION:
XS GIS Cut Line= 5
      2085514.03     13440699.16      2085032.71     13440410.37
      2084499.93     13440490.95      2084396.96     13440802.11
      2084374.57     13440970.03
#Sta/Elev= 30
  4173.8   371.2  4313.3  368.35  4556.3  366.43  4620.4  365.18  4700.1  362.25
  4813.7   355.4  4833.9  352.91  4854.2  352.93    4925  346.94  4965.4  341.25
 4980.16338.1212  4985.6  336.57  4997.5   334.9    4998   334.1    5003   334.1
  5003.5   334.9  5005.9   337.2 5012.45338.1209  5064.2  345.13  5069.3  342.64
  5086.8  345.71  5096.9  346.49  5133.1  347.05  5177.8  347.48  5248.6  346.63
  5265.7  345.68  5383.5  347.64  5437.2  347.62  5657.2  345.53  5771.1  348.85
#Mann= 3 ,-1 , 0
  4173.8      .1       0  4997.5     .07       0  5003.5      .1       0
Bank Sta=4980.16,5012.45
XS Rating Curve= 0 ,0
Exp/Cntr=0.3,0.1

Type RM Length L Ch R = 1 ,932     ,277,277,277
BEGIN DESCRIPTION:
UNT 191 SanMiguel Cr Watershed 3.0
END DESCRIPTION:
XS GIS Cut Line= 4
      2086014.73     13440884.09      2085025.15     13440063.78
      2084343.73     13440185.31      2084330.71     13441166.17
#Sta/Elev= 30
  3279.2  382.41  3470.4  378.84  4116.4  362.27  4322.1  360.91  4350.8  362.04
  4414.6  361.01  4625.7  362.08  4718.1  358.25  4808.5  352.55    4839  349.69
  4884.7  343.36  4889.8  344.61  4920.2  340.46  4943.7  339.82 4979.46336.4674
  4991.4  336.18  4994.6  335.17  4995.1  334.37  5000.1  334.37  5000.6  335.17
 5012.28336.4681  5021.8  336.93  5062.5  343.88  5092.9   345.6  5204.7  345.39
  5546.5  347.63  5656.5  345.79  5906.5  344.63  6076.5  349.61  6237.7  350.09
#Mann= 3 ,-1 , 0
  3279.2      .1       0  4994.6     .07       0  5000.6      .1       0
Bank Sta=4979.46,5012.28
XS Rating Curve= 0 ,0
Exp/Cntr=0.3,0.1

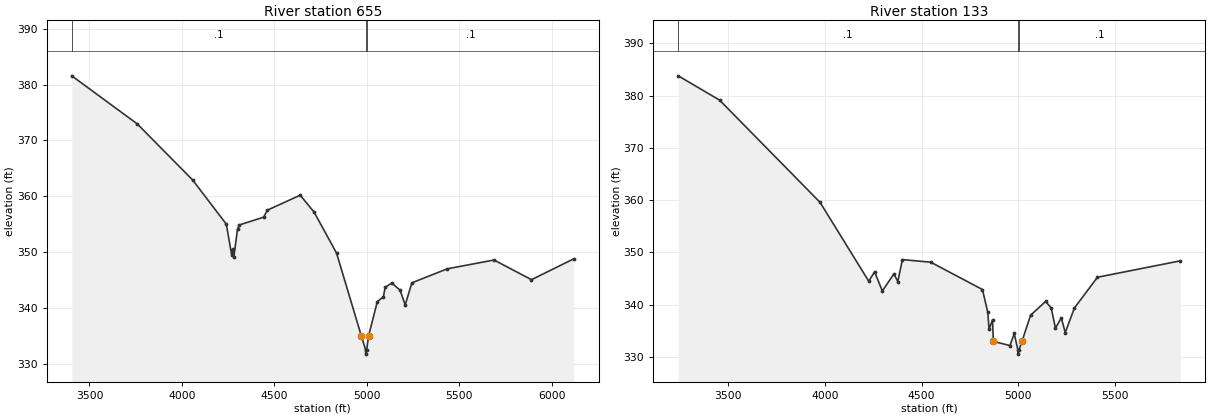
Type RM Length L Ch R = 1 ,655     ,522,522,522
BEGIN DESCRIPTION:
UNT 191 SanMiguel Cr Watershed 2.0
END DESCRIPTION:
XS GIS Cut Line= 5
      2086092.85     13440037.73       2084825.5     13439864.12
      2084421.85     13439907.53      2084304.67     13440081.14
        2084179.     13440891.43
#Sta/Elev= 30
  3404.3  381.58  3758.2  372.97  4058.2   362.9  4239.9  354.99  4268.5  349.54
  4273.5  350.55  4280.3  349.04  4300.4  354.11  4310.5  354.85  4441.7  356.25
  4461.9   357.5  4639.4  360.19  4714.2  357.17  4835.9  349.81 4970.22334.9247
  4992.8   332.5  4993.3   331.7  4998.8   332.5 5008.81334.9251  5056.1  341.08
  5089.5  342.01  5098.6  343.66  5134.7  344.46  5179.5  343.14  5207.1  340.52
  5243.3  344.48  5434.4  346.99  5687.4  348.57  5889.8  345.04  6118.9  348.79
#Mann= 3 ,-1 , 0
  3404.3      .1       0  4992.8     .07       0  4998.8      .1       0
Bank Sta=4970.22,5008.81
XS Rating Curve= 0 ,0
Exp/Cntr=0.3,0.1

Type RM Length L Ch R = 1 ,133     ,0,0,0
BEGIN DESCRIPTION:
UNT 191 SanMiguel Cr Watershed 1.0
END DESCRIPTION:
XS GIS Cut Line= 4
      2085968.57     13439365.07      2084438.64     13439437.76
        2084300.       13439750.      2084176.67     13440460.99
#Sta/Elev= 30
  3242.1   383.8  3455.9  379.15  3974.8   359.6  4226.8   344.5  4256.8  346.31
  4296.9  342.64  4356.9   345.9  4376.9  344.43  4400.7  348.64  4547.1  348.14
  4814.4  342.91  4841.9  338.56  4848.6  335.28  4866.4  337.13 4870.95332.9841
  4956.7  332.19  4978.6  334.51  4997.5  331.35    4998  330.55  5003.5  331.35
 5018.45332.9833  5063.4  338.01  5140.8  340.62    5170  339.38  5191.5  335.53
    5222  337.47  5242.3  334.68  5289.4  339.36  5408.8  345.26    5837   348.4
#Mann= 3 ,-1 , 0
  3242.1      .1       0  4997.5     .07       0  5003.5      .1       0
Bank Sta=4870.95,5018.45
XS Rating Curve= 0 ,0
Exp/Cntr=0.3,0.1
LCMann Table=0

Chan Stop Cuts=-1
Use User Specified Reach Order=0
Composite Channel Slope=5