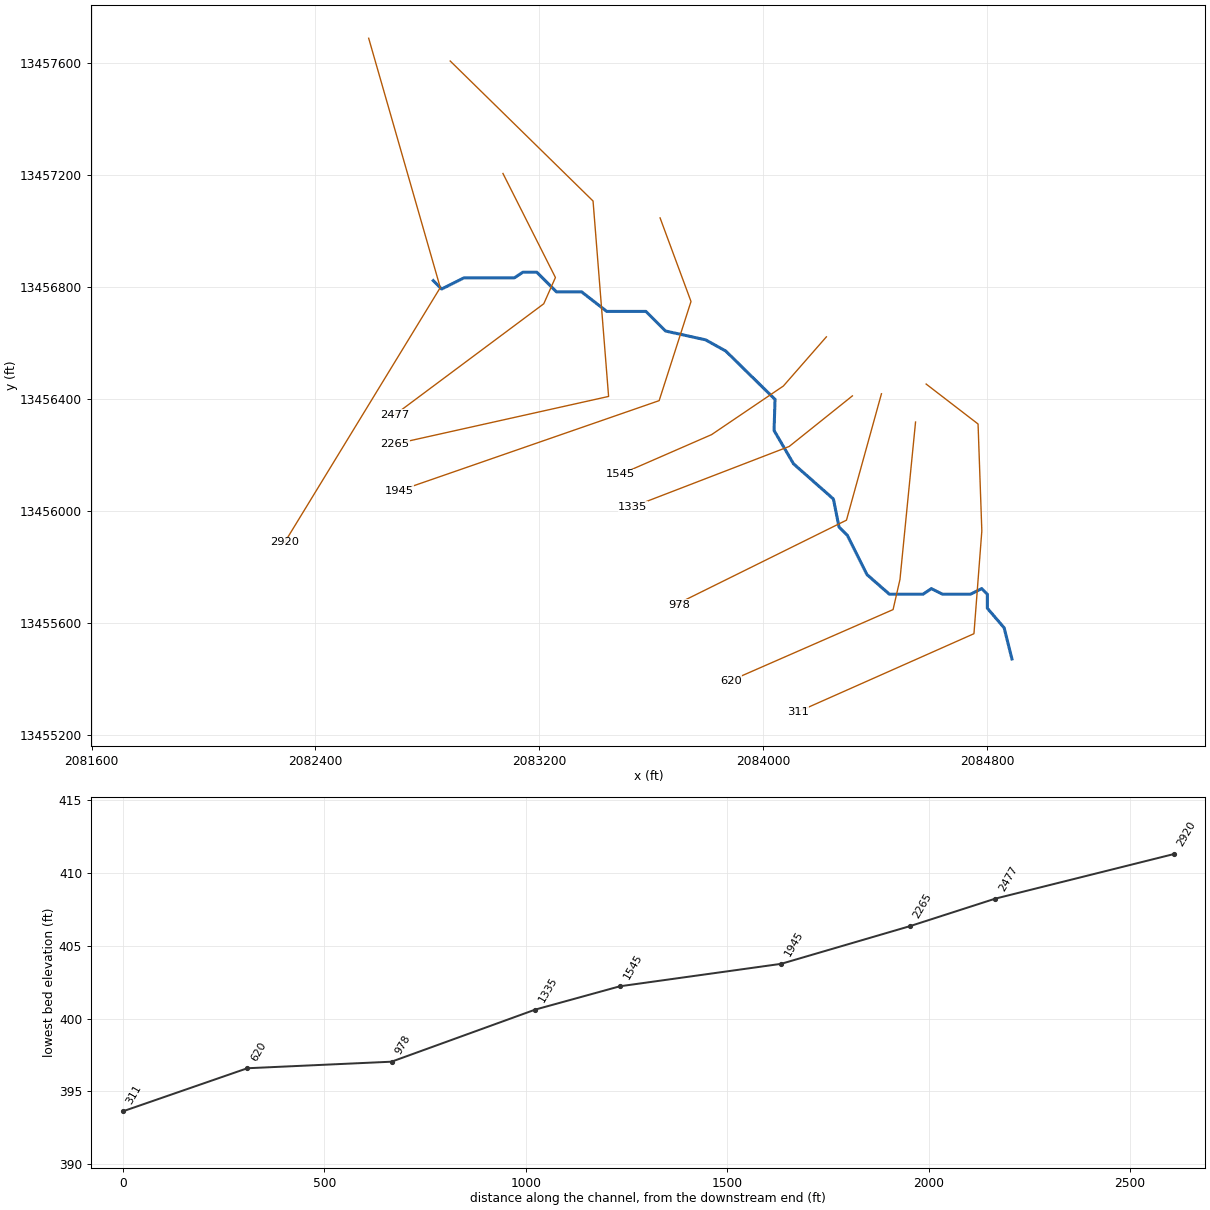
--- UNT 192 SanMiguel Cr Watershed.prj (project) ---

Proj Title=UNT 192 SanMiguel Cr Watershed Base Level Engineering
Current Plan=p01
Default Exp/Contr=0.3,0.1
English Units
Geom File=g01
Flow File=f01
Plan File=p01
Y Axis Title=Elevation
X Axis Title(PF)=Main Channel Distance
X Axis Title(XS)=Station
BEGIN DESCRIPTION:
UNT 192 SanMiguel Cr Watershed
END DESCRIPTION:
DSS Export Rating Curves= 0
DSS Export Rating Curve Sorted= 0
DSS Export Volume Flow Curves= 0
DXF OffsetX= 0
DXF OffsetY= 0
DXF ScaleX= 1
DXF ScaleY= 10

--- UNT 192 SanMiguel Cr Watershed.p01 (plan) ---

Plan Title=Multiple Run
Short Identifier=Multiple
Geom File=g01
Flow File=f01
Subcritical Flow
K Sum by GR= 0
Std Step Tol= 0.01
Critical Tol= 0.01
Num of Std Step Trials= 20
Max Error Tol= 0.3
Flow Tol Ratio= 0.001
Split Flow NTrial= 30
Split Flow Tol= 0.02
Split Flow Ratio= 0.02
Log Output Level= 0
Friction Slope Method= 1
Unsteady Friction Slope Method= 2
Unsteady Bridges Friction Slope Method= 1
Parabolic Critical Depth
Global Vel Dist=  1 , 1 , 1
Global Log Level= 0
CheckData=True
Encroach Param= -1, 0, 0, 0
BEGIN DESCRIPTION:
Multiple Run
END DESCRIPTION:

--- UNT 192 SanMiguel Cr Watershed.f01 (steady flow) ---

Flow Title=Multiple
Number of Profiles=7
Profile Names=10-year,25-year,50-year,1pct_min,100-year,1pct_plu,500-year
River Rch & RM= UNT 192 SanMigue,Reach-1,2920
     105     139     165      99     197     393     282
Boundary for River Rch & Prof#=UNT 192 SanMigue,Reach-1,1
Up Type=0
Dn Type=3
Dn Slope=0.005
Boundary for River Rch & Prof#=UNT 192 SanMigue,Reach-1,2
Up Type=0
Dn Type=3
Dn Slope=0.005
Boundary for River Rch & Prof#=UNT 192 SanMigue,Reach-1,3
Up Type=0
Dn Type=3
Dn Slope=0.005
Boundary for River Rch & Prof#=UNT 192 SanMigue,Reach-1,4
Up Type=0
Dn Type=3
Dn Slope=0.005
Boundary for River Rch & Prof#=UNT 192 SanMigue,Reach-1,5
Up Type=0
Dn Type=3
Dn Slope=0.005
Boundary for River Rch & Prof#=UNT 192 SanMigue,Reach-1,6
Up Type=0
Dn Type=3
Dn Slope=0.005
Boundary for River Rch & Prof#=UNT 192 SanMigue,Reach-1,7
Up Type=0
Dn Type=3
Dn Slope=0.005

--- UNT 192 SanMiguel Cr Watershed.g01 (geometry) ---

Geom Title=Existing Conditions
Program Version=5.05

River Reach=UNT 192 SanMigue,Reach-1
Reach XY= 30
       2082820.8     13456824.54       2082850.8     13456794.54
       2082930.8     13456834.54       2083110.8     13456834.54
       2083140.8     13456854.54       2083190.8     13456854.54
       2083260.8     13456784.54       2083350.8     13456784.54
       2083440.8     13456714.54       2083580.8     13456714.54
       2083650.8     13456644.54      2083793.88     13456613.04
      2083865.93     13456573.11      2084042.14     13456400.37
      2084038.67     13456289.26      2084108.12     13456170.33
       2084250.8     13456044.54       2084270.8     13455944.54
       2084300.8     13455914.54       2084370.8     13455774.54
       2084450.8     13455704.54       2084570.8     13455704.54
       2084600.8     13455724.54       2084640.8     13455704.54
       2084740.8     13455704.54       2084780.8     13455724.54
       2084800.8     13455704.54       2084800.8     13455654.54
       2084860.8     13455584.54      2084888.84     13455473.29

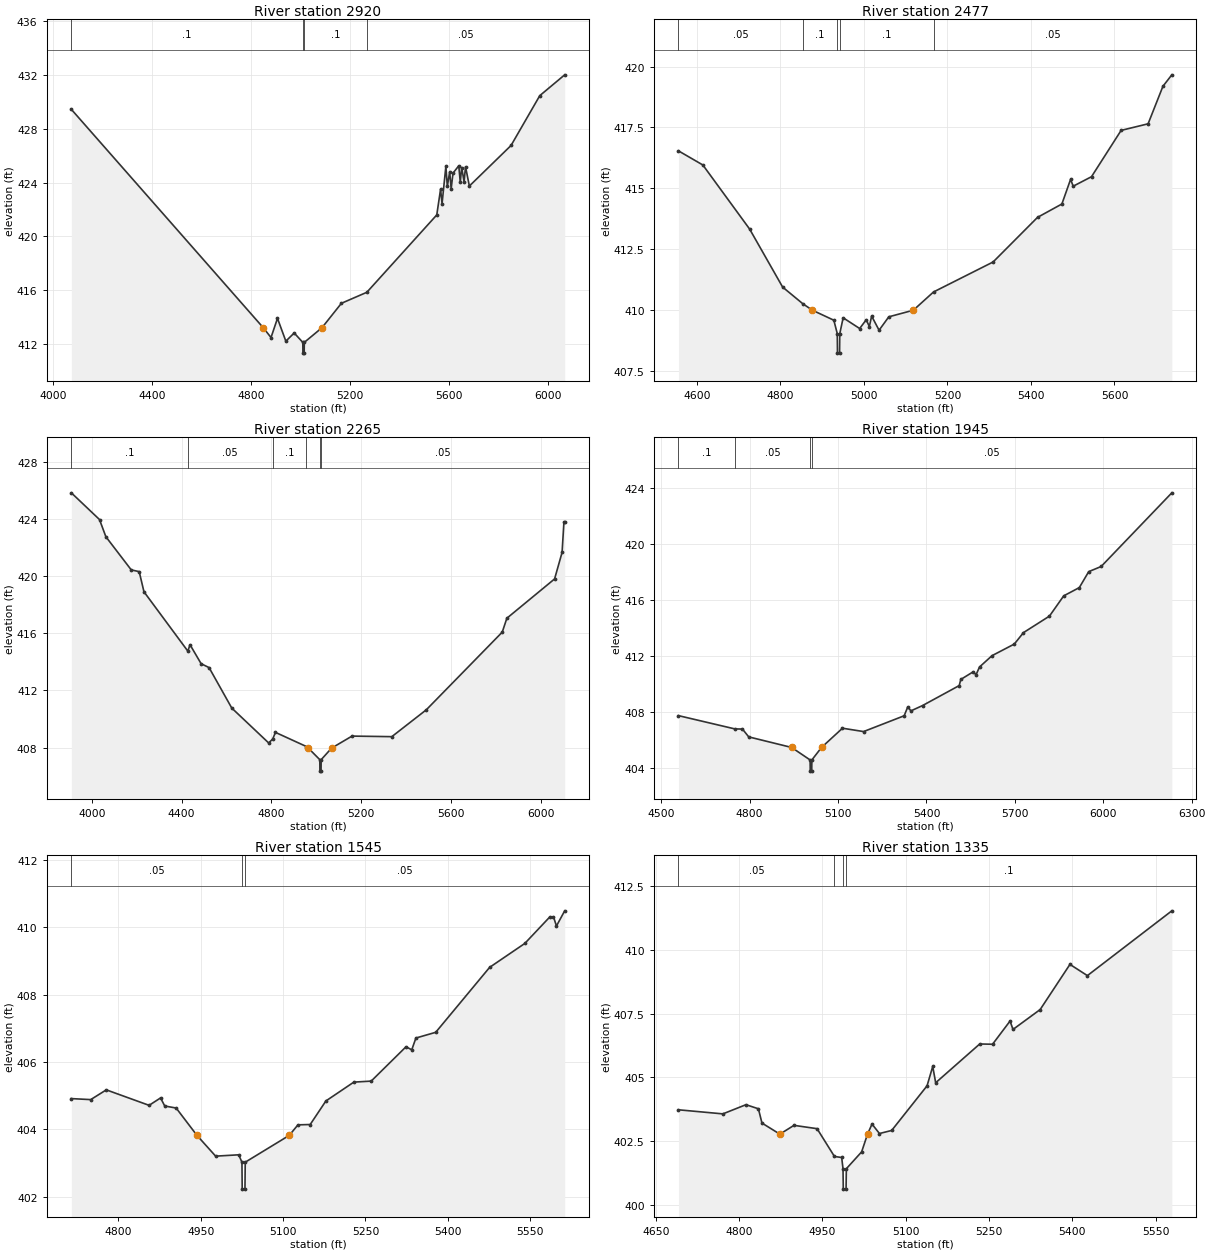
Type RM Length L Ch R = 1 ,2920    ,443,443,443
BEGIN DESCRIPTION:
UNT 192 SanMiguel Cr Watershed 7.0
END DESCRIPTION:
XS GIS Cut Line= 3
      2082590.11     13457690.07       2082845.9      13456799.6
       2082290.1     13455890.06
#Sta/Elev= 30
  4073.4  429.45  4848.6  413.19  4879.8  412.46  4905.9  413.89  4939.7  412.19
  4973.4   412.8  5008.2   412.1  5008.7   411.3  5013.7   411.3  5014.2   412.1
 5085.53  413.19  5164.1  415.01  5266.8  415.83  5549.2  421.59  5564.6  423.51
  5570.5  422.43    5586  425.21  5591.8  423.72  5601.4   424.8  5607.3  423.53
  5614.7   424.7  5638.1  425.25    5644  424.04  5649.9  425.12  5659.5  424.06
  5665.3  425.18  5680.8  423.74  5849.1  426.76  5965.2  430.47  6065.8  432.02
#Mann= 4 ,-1 , 0
  4073.4      .1       0  5008.2     .07       0  5014.2      .1       0
  5266.8     .05       0
Bank Sta=4848.6,5085.53
XS Rating Curve= 0 ,0
Exp/Cntr=0.3,0.1

Type RM Length L Ch R = 1 ,2477    ,212,212,212
BEGIN DESCRIPTION:
Mapping XS 54532c4d
END DESCRIPTION:
XS GIS Cut Line= 4
      2083069.91     13457207.12       2083257.4     13456835.61
      2083215.74     13456741.86      2082684.52     13456346.05
#Sta/Elev= 30
  4556.1  416.54  4614.5  415.96  4726.5  413.33  4805.5  410.95  4854.3  410.26
 4876.83410.0009  4928.1  409.59  4936.3  409.04  4936.8  408.24  4941.8  408.24
  4942.3  409.04  4950.4  409.69  4989.9  409.25  5005.7  409.61  5013.1  409.33
  5018.6  409.76  5036.4  409.18  5059.7  409.73 5118.46 410.001  5166.8  410.75
  5309.4  411.98  5415.7  413.81  5474.1  414.36  5494.9  415.37  5501.2  415.09
    5545  415.48  5615.9  417.38  5680.5  417.65    5716  419.19  5737.3  419.66
#Mann= 5 ,-1 , 0
  4556.1     .05       0  4854.3      .1       0  4936.3     .07       0
  4942.3      .1       0  5166.8     .05       0
Bank Sta=4876.83,5118.46
XS Rating Curve= 0 ,0
Exp/Cntr=0.3,0.1

Type RM Length L Ch R = 1 ,2265    ,320,320,320
BEGIN DESCRIPTION:
UNT 192 SanMiguel Cr Watershed 6.0
END DESCRIPTION:
XS GIS Cut Line= 4
      2082881.42     13457608.83      2083391.84     13457108.82
       2083447.4     13456410.91      2082683.56     13456240.78
#Sta/Elev= 30
  3909.1  425.81  4034.6  423.94  4062.9  422.74    4176  420.42  4211.3   420.3
  4232.6  418.89    4428  414.74  4437.6  415.19  4487.2  413.86  4522.5  413.59
  4623.6  410.76    4788  408.32  4806.1   408.6  4818.1  409.06    4956  408.07
 4964.75407.9575  5015.7  407.15  5016.2  406.35  5021.2  406.35  5021.7  407.15
 5068.07407.9576  5159.1   408.8  5336.4  408.76  5490.1  410.64  5828.2  416.07
  5848.7  417.04  6061.3  419.79  6094.6  421.64    6103  423.78  6106.3  423.78
#Mann= 6 ,-1 , 0
  3909.1      .1       0    4428     .05       0  4806.1      .1       0
    4956     .05       0  5015.7     .03       0  5021.7     .05       0
Bank Sta=4964.75,5068.07
XS Rating Curve= 0 ,0
Exp/Cntr=0.3,0.1

Type RM Length L Ch R = 1 ,1945    ,400,400,400
BEGIN DESCRIPTION:
UNT 192 SanMiguel Cr Watershed 5.0
END DESCRIPTION:
XS GIS Cut Line= 4
      2083631.37     13457048.58      2083741.88       13456750.
      2083628.03     13456395.88       2082698.4     13456073.76
#Sta/Elev= 30
  4558.5  407.73  4749.9  406.78  4775.6  406.77  4796.9  406.21  4942.5405.4537
  5005.2  404.56  5005.7  403.76  5010.7  403.76  5011.2  404.56 5043.97405.4537
  5115.1  406.83  5186.7  406.59  5324.4  407.72  5336.7  408.36  5347.3  408.07
  5386.7  408.45  5511.2  409.88  5516.6  410.32    5559  410.87  5568.2  410.65
  5580.1  411.21  5622.5  412.02  5698.1  412.85  5729.3  413.67  5817.4  414.85
  5865.9   416.3  5918.8  416.89  5950.6  418.03  5992.9   418.4  6232.7  423.67
#Mann= 4 ,-1 , 0
  4558.5      .1       0  4749.9     .05       0  5005.2     .03       0
  5011.2     .05       0
Bank Sta=4942.5,5043.97
XS Rating Curve= 0 ,0
Exp/Cntr=0.3,0.1

Type RM Length L Ch R = 1 ,1545    ,210,210,210
BEGIN DESCRIPTION:
UNT 192 SanMiguel Cr Watershed 4.0
END DESCRIPTION:
XS GIS Cut Line= 4
      2084225.66     13456623.77       2084071.9     13456448.05
      2083815.51     13456274.59      2083489.67     13456132.55
#Sta/Elev= 30
  4714.4  404.91  4749.7  404.88  4778.1  405.17    4856  404.71  4876.9  404.93
  4884.5  404.69  4905.3  404.63 4943.18403.8172  4977.2   403.2  5019.2  403.24
  5025.1  403.02  5025.6  402.22  5030.6  402.22  5031.1  403.02 5111.29403.8174
  5127.1  404.13  5149.4  404.14    5178  404.84  5228.9   405.4  5260.5  405.43
  5323.9  406.45  5334.4  406.36  5341.9  406.71    5378  406.88  5476.2  408.81
  5540.2  409.52  5585.3   410.3  5592.5  410.31  5597.9  410.04  5612.9  410.49
#Mann= 3 ,-1 , 0
  4714.4     .05       0  5025.1     .03       0  5031.1     .05       0
Bank Sta=4943.18,5111.29
XS Rating Curve= 0 ,0
Exp/Cntr=0.3,0.1

Type RM Length L Ch R = 1 ,1335    ,357,357,357
BEGIN DESCRIPTION:
Mapping XS fea69b1c
END DESCRIPTION:
XS GIS Cut Line= 3
      2084318.62     13456412.88      2084092.91     13456232.31
      2083533.88     13456017.03
#Sta/Elev= 30
    4691  403.73  4770.9  403.57  4812.5  403.93  4834.9  403.77  4841.3  403.21
 4873.55402.7753  4898.9  403.12  4940.5  402.99  4971.8   401.9  4984.8  401.86
  4987.2  401.42  4987.7  400.62  4992.7  400.62  4993.2  401.42  5020.7  402.08
 5031.33402.7754  5039.4  403.17  5052.8   402.8  5074.8  402.92  5138.5  404.67
  5148.7  405.43    5154  404.79  5233.3  406.31  5256.4   406.3  5287.9  407.21
  5293.2  406.88  5342.1  407.66  5395.7  409.43  5427.1  408.99  5579.1  411.53
#Mann= 4 ,-1 , 0
    4691     .05       0  4971.8      .1       0  4987.2     .07       0
  4993.2      .1       0
Bank Sta=4873.55,5031.33
XS Rating Curve= 0 ,0
Exp/Cntr=0.3,0.1

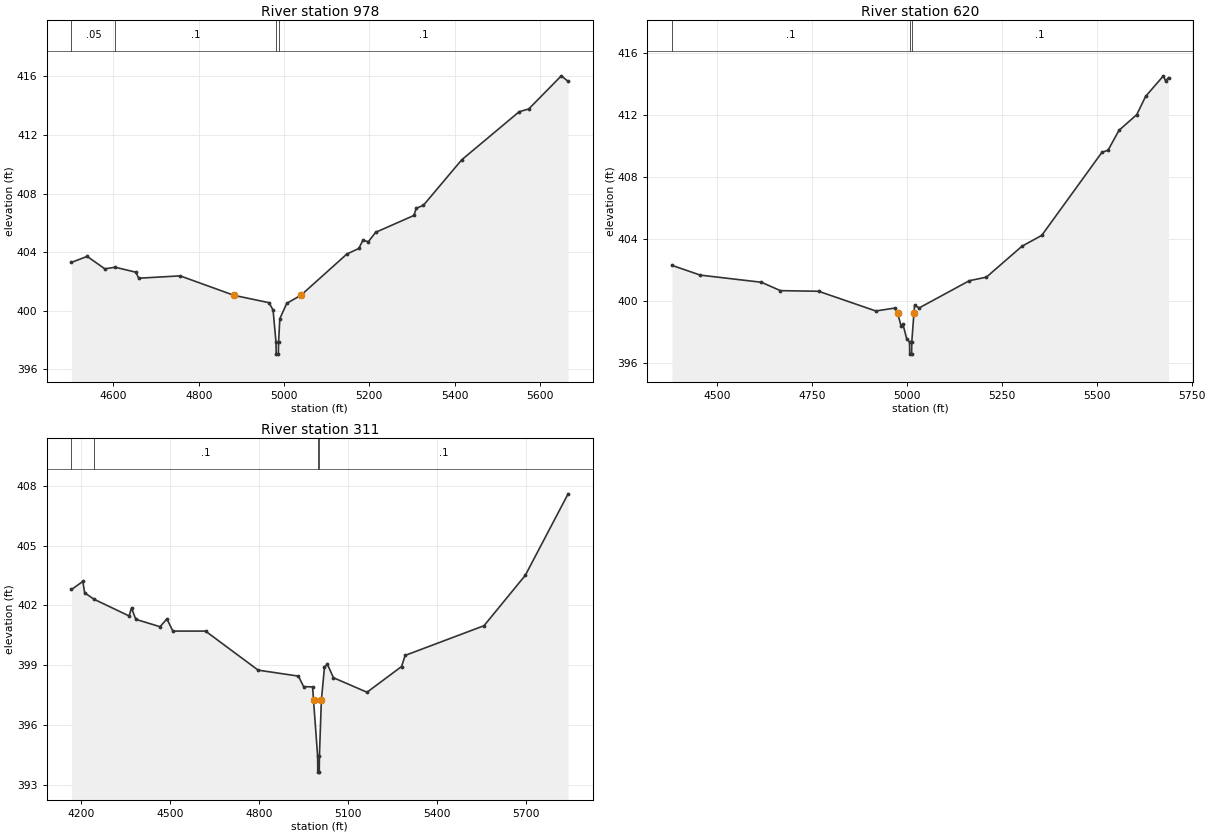
Type RM Length L Ch R = 1 ,978     ,358,358,358
BEGIN DESCRIPTION:
UNT 192 SanMiguel Cr Watershed 3.0
END DESCRIPTION:
XS GIS Cut Line= 4
      2084422.44     13456420.41      2084297.44     13455969.02
      2083686.33     13455666.93      2083700.15     13455666.93
#Sta/Elev= 30
  4501.9   403.3  4538.6  403.71  4580.1  402.86  4604.2  402.97  4652.8  402.63
  4659.4  402.22  4756.5  402.38 4882.92401.0503    4965  400.55  4974.4  400.04
  4981.2  397.84  4981.7  397.04  4986.7  397.04  4987.2  397.84  4990.2  399.46
  5006.5  400.51  5039.4401.0504  5147.3  403.87  5175.3  404.25  5184.9  404.81
  5197.7  404.71  5214.6  405.35  5304.3   406.5  5309.9  406.99  5326.8   407.2
  5416.5   410.3  5551.1  413.58  5573.6  413.77  5649.9  416.03  5665.8  415.65
#Mann= 4 ,-1 , 0
  4501.9     .05       0  4604.2      .1       0  4981.2     .07       0
  4987.2      .1       0
Bank Sta=4882.92,5039.4
XS Rating Curve= 0 ,0
Exp/Cntr=0.3,0.1

Type RM Length L Ch R = 1 ,620     ,309,309,309
BEGIN DESCRIPTION:
UNT 192 SanMiguel Cr Watershed 2.0
END DESCRIPTION:
XS GIS Cut Line= 4
      2084544.27     13456319.43      2084488.58     13455757.06
        2084464.     13455649.67      2083884.22     13455396.09
#Sta/Elev= 30
    4381  402.31  4455.8  401.68  4616.6  401.22  4666.8  400.68  4767.3  400.64
    4918  399.37  4968.8  399.56 4975.21399.2458  4984.4  398.42  4989.5  398.52
  4999.5  397.56  5006.8  397.39  5007.3  396.59  5012.3  396.59  5012.8  397.39
 5018.51399.2457    5020  399.73  5032.4  399.57  5164.3  401.32  5209.3  401.55
  5302.9  403.54  5355.1  404.24  5513.6  409.59  5529.8  409.73  5558.6  411.01
  5605.4  412.02  5628.8   413.2  5675.6  414.52  5681.1   414.2  5689.1   414.4
#Mann= 3 ,-1 , 0
    4381      .1       0  5006.8     .07       0  5012.8      .1       0
Bank Sta=4975.21,5018.51
XS Rating Curve= 0 ,0
Exp/Cntr=0.3,0.1

Type RM Length L Ch R = 1 ,311     ,0,0,0
BEGIN DESCRIPTION:
UNT 192 SanMiguel Cr Watershed 1.0
END DESCRIPTION:
XS GIS Cut Line= 5
      2084582.18     13456455.12      2084767.67     13456312.45
      2084781.15     13455930.74      2084752.97     13455563.52
      2084123.22     13455284.15
#Sta/Elev= 30
  4167.2   402.8  4205.3   403.2  4211.7  402.63    4243  402.31  4361.2  401.47
  4369.4  401.87  4383.9   401.3  4465.4  400.93  4488.7  401.32  4508.7  400.71
  4618.8  400.71    4796  398.75  4931.6  398.45  4949.4  397.92  4979.5  397.91
 4982.69397.2337  4996.5  394.43    4997  393.63    5002  393.63  5002.5  394.43
 5009.09 397.233  5019.6  398.91  5029.6  399.04  5049.7  398.37  5162.9  397.64
  5279.2  398.93  5291.5  399.49  5557.1  400.98  5696.2  403.51  5840.4   407.6
#Mann= 4 ,-1 , 0
  4167.2     .05       0    4243      .1       0  4996.5     .07       0
  5002.5      .1       0
Bank Sta=4982.69,5009.09
XS Rating Curve= 0 ,0
Exp/Cntr=0.3,0.1
LCMann Table=0

Chan Stop Cuts=-1
Use User Specified Reach Order=0
Composite Channel Slope=5