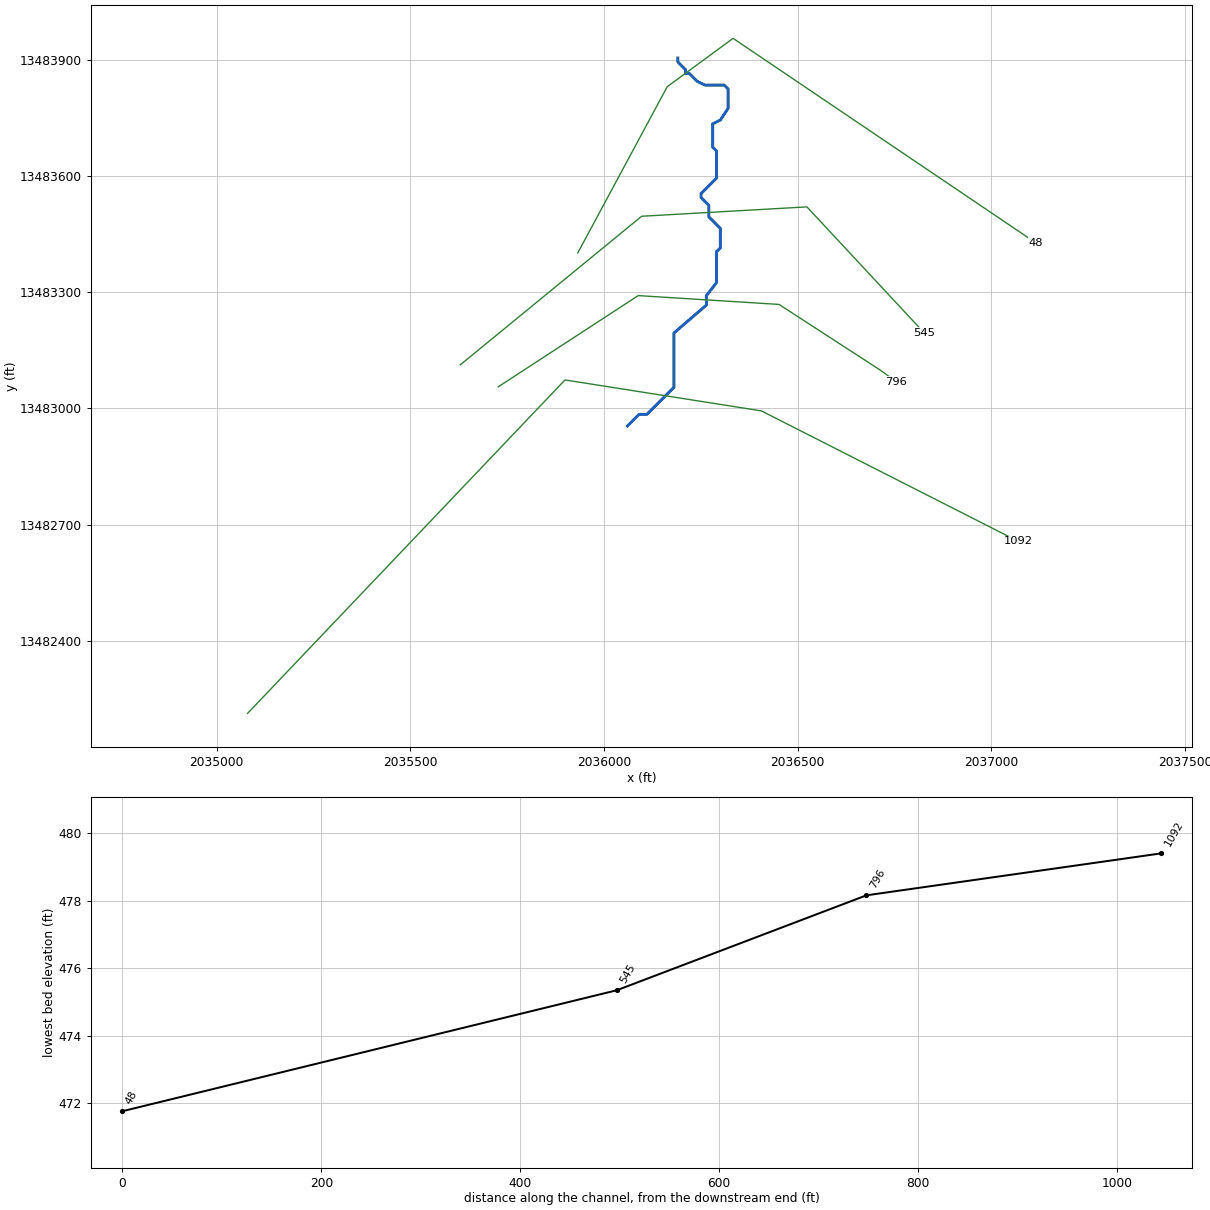
--- UNT 193 SanMiguel Cr Watershed.prj (project) ---

Proj Title=UNT 193 SanMiguel Cr Watershed Base Level Engineering
Current Plan=p01
Default Exp/Contr=0.3,0.1
English Units
Geom File=g01
Flow File=f01
Plan File=p01
Y Axis Title=Elevation
X Axis Title(PF)=Main Channel Distance
X Axis Title(XS)=Station
BEGIN DESCRIPTION:
UNT 193 SanMiguel Cr Watershed
END DESCRIPTION:
DSS Export Rating Curves= 0
DSS Export Rating Curve Sorted= 0
DSS Export Volume Flow Curves= 0
DXF OffsetX= 0
DXF OffsetY= 0
DXF ScaleX= 1
DXF ScaleY= 10

--- UNT 193 SanMiguel Cr Watershed.p01 (plan) ---

Plan Title=Multiple Run
Short Identifier=Multiple
Geom File=g01
Flow File=f01
Subcritical Flow
K Sum by GR= 0
Std Step Tol= 0.01
Critical Tol= 0.01
Num of Std Step Trials= 20
Max Error Tol= 0.3
Flow Tol Ratio= 0.001
Split Flow NTrial= 30
Split Flow Tol= 0.02
Split Flow Ratio= 0.02
Log Output Level= 0
Friction Slope Method= 1
Unsteady Friction Slope Method= 2
Unsteady Bridges Friction Slope Method= 1
Parabolic Critical Depth
Global Vel Dist=  1 , 1 , 1
Global Log Level= 0
CheckData=True
Encroach Param= -1, 0, 0, 0
BEGIN DESCRIPTION:
Multiple Run
END DESCRIPTION:

--- UNT 193 SanMiguel Cr Watershed.f01 (steady flow) ---

Flow Title=Multiple
Number of Profiles=7
Profile Names=10-year,25-year,50-year,1pct_min,100-year,1pct_plu,500-year
River Rch & RM= UNT 193 SanMigue,Reach-1,1092
      66      85      99      58     115     230     160
Boundary for River Rch & Prof#=UNT 193 SanMigue,Reach-1,1
Up Type=0
Dn Type=3
Dn Slope=0.005
Boundary for River Rch & Prof#=UNT 193 SanMigue,Reach-1,2
Up Type=0
Dn Type=3
Dn Slope=0.005
Boundary for River Rch & Prof#=UNT 193 SanMigue,Reach-1,3
Up Type=0
Dn Type=3
Dn Slope=0.005
Boundary for River Rch & Prof#=UNT 193 SanMigue,Reach-1,4
Up Type=0
Dn Type=3
Dn Slope=0.005
Boundary for River Rch & Prof#=UNT 193 SanMigue,Reach-1,5
Up Type=0
Dn Type=3
Dn Slope=0.005
Boundary for River Rch & Prof#=UNT 193 SanMigue,Reach-1,6
Up Type=0
Dn Type=3
Dn Slope=0.005
Boundary for River Rch & Prof#=UNT 193 SanMigue,Reach-1,7
Up Type=0
Dn Type=3
Dn Slope=0.005

--- UNT 193 SanMiguel Cr Watershed.g01 (geometry) ---

Geom Title=Existing Conditions
Program Version=5.05

River Reach=UNT 193 SanMigue,Reach-1
Reach XY= 30
       2036060.8     13482954.54       2036090.8     13482984.54
       2036110.8     13482984.54       2036180.8     13483054.54
       2036180.8     13483194.54      2036265.03     13483267.07
      2036264.59     13483291.15       2036290.8     13483324.54
       2036290.8     13483404.54       2036300.8     13483414.54
       2036300.8     13483464.54       2036270.8     13483494.54
       2036270.8     13483524.54       2036250.8     13483544.54
       2036250.8     13483554.54       2036290.8     13483594.54
       2036290.8     13483664.54       2036280.8     13483674.54
       2036280.8     13483734.54       2036300.8     13483744.54
       2036320.8     13483774.54       2036320.8     13483824.54
       2036310.8     13483834.54       2036260.8     13483834.54
       2036240.8     13483844.54       2036220.8     13483864.54
       2036210.8     13483864.54       2036210.8     13483874.54
       2036190.8     13483894.54       2036190.8     13483904.54

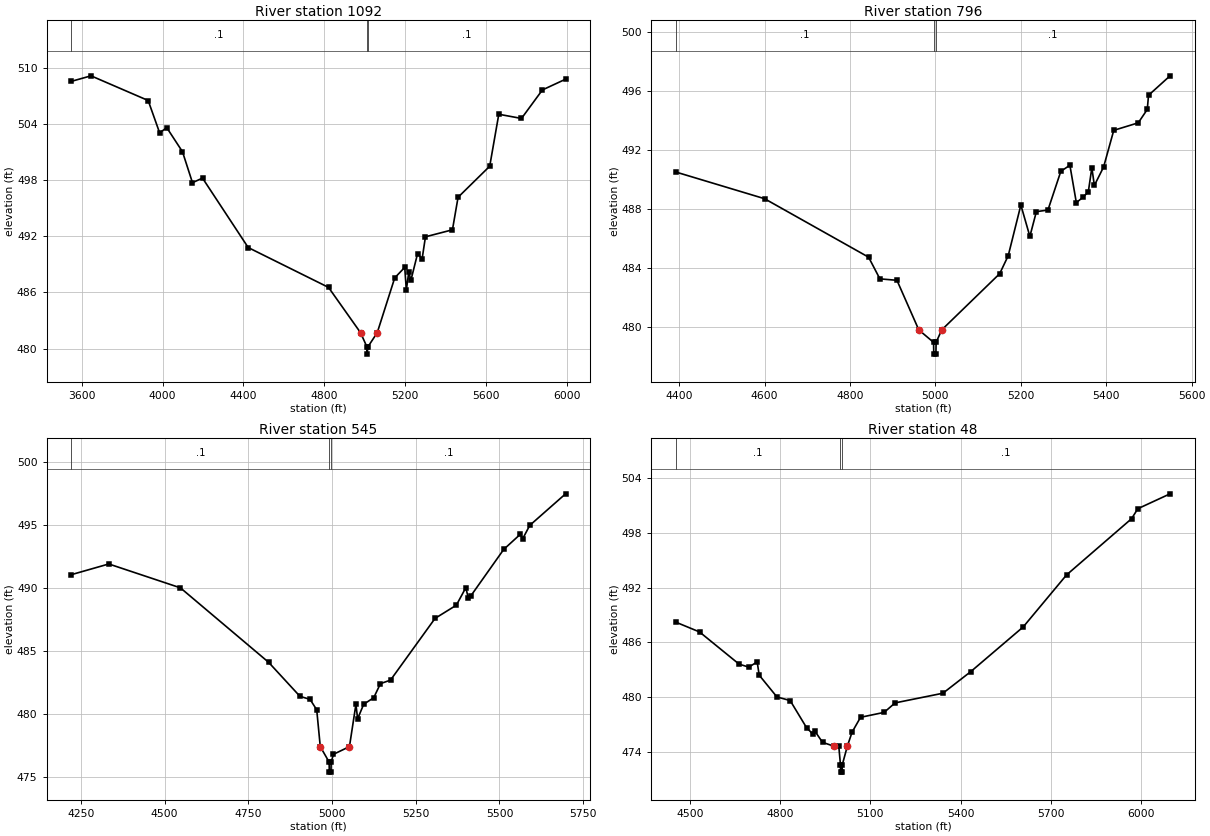
Type RM Length L Ch R = 1 ,1092    ,296,296,296
BEGIN DESCRIPTION:
UNT 193 SanMiguel Cr Watershed 4.0
END DESCRIPTION:
XS GIS Cut Line= 4
      2035080.12     13482212.57      2035899.56     13483073.43
       2036406.5     13482993.57      2037069.67     13482656.78
#Sta/Elev= 30
    3549  508.58  3646.2  509.17    3929  506.53  3985.6  503.08  4021.2  503.62
  4098.8  501.05  4148.2  497.74  4197.9  498.23  4424.1   490.8  4821.4  486.54
 4979.76481.6982    5011   480.2  5011.5   479.4    5017   480.2 5062.58481.6977
  5149.1  487.56  5198.6  488.68  5206.5  486.26  5218.8  488.21  5228.9  487.28
  5262.2  490.16  5284.5  489.57  5301.1  491.95  5434.7   492.7  5462.5  496.18
  5619.1   499.5    5664  505.06  5776.2  504.61  5879.8  507.66  5994.5  508.81
#Mann= 3 ,-1 , 0
    3549      .1       0    5011     .07       0    5017      .1       0
Bank Sta=4979.76,5062.58
XS Rating Curve= 0 ,0
Exp/Cntr=0.3,0.1

Type RM Length L Ch R = 1 ,796     ,251,251,251
BEGIN DESCRIPTION:
UNT 193 SanMiguel Cr Watershed 3.0
END DESCRIPTION:
XS GIS Cut Line= 5
      2035727.38     13483055.73       2036088.7     13483291.18
       2036452.2     13483268.39      2036714.78     13483098.04
      2036754.06     13483069.37
#Sta/Elev= 30
  4392.3  490.52    4600  488.71  4843.6  484.74    4870  483.27    4910  483.17
  4961.1 479.806  4995.7  478.96  4996.2  478.16  5001.2  478.16  5001.7  478.96
 5014.84479.8056  5150.5  483.62  5170.5  484.84  5200.1  488.28  5221.2  486.15
  5236.4  487.83  5263.5  487.94  5293.7  490.57  5314.9  490.98    5330  488.44
  5345.1   488.8    5358  489.17  5366.3  490.81  5372.2  489.61  5393.8  490.86
  5417.6  493.35    5475  493.86  5496.1  494.77    5499  495.73  5549.4  497.05
#Mann= 3 ,-1 , 0
  4392.3      .1       0  4995.7     .07       0  5001.7      .1       0
Bank Sta=4961.1,5014.84
XS Rating Curve= 0 ,0
Exp/Cntr=0.3,0.1

Type RM Length L Ch R = 1 ,545     ,497,497,497
BEGIN DESCRIPTION:
UNT 193 SanMiguel Cr Watershed 2.0
END DESCRIPTION:
XS GIS Cut Line= 4
       2035629.4     13483112.55      2036097.53     13483496.04
      2036524.16     13483520.22      2036826.43      13483195.5
#Sta/Elev= 30
  4221.3  491.06  4333.1  491.91    4547  490.01  4810.3  484.09    4904  481.38
  4934.1  481.14  4954.1  480.31 4964.72477.3789  4991.2  476.15  4991.7  475.35
  4996.7  475.35  4997.2  476.15  5004.2  476.77 5051.86477.3787  5071.2  480.74
  5076.3  479.59  5094.4  480.75  5124.4  481.27  5144.4  482.39  5174.5  482.67
  5307.5  487.58  5371.1  488.63  5399.4  490.02  5406.7  489.23  5413.6  489.34
  5512.7  493.07  5562.1  494.27  5569.4  493.92  5590.4  494.98  5697.4  497.49
#Mann= 3 ,-1 , 0
  4221.3      .1       0  4991.2     .07       0  4997.2      .1       0
Bank Sta=4964.72,5051.86
XS Rating Curve= 0 ,0
Exp/Cntr=0.3,0.1

Type RM Length L Ch R = 1 ,48      ,0,0,0
BEGIN DESCRIPTION:
UNT 193 SanMiguel Cr Watershed 1.0
END DESCRIPTION:
XS GIS Cut Line= 4
      2035932.53     13483401.22      2036163.44     13483830.38
      2036333.58     13483955.38      2037114.85     13483427.59
#Sta/Elev= 30
  4453.9  488.21  4532.5  487.14  4663.9  483.61  4696.4  483.28    4724  483.86
  4730.7   482.4  4789.7  480.01  4833.5  479.62  4887.9  476.65  4909.8  475.91
  4915.5  476.27    4941  475.04 4980.04474.5978  4995.1   474.6  5000.6  472.57
  5001.1  471.77  5006.1  471.77  5006.6  472.57 5023.36474.5974  5039.1  476.15
  5067.3  477.78  5145.6  478.32    5182  479.36  5340.9  480.42  5433.8   482.8
  5607.6  487.69  5751.5  493.39  5967.3  499.55  5988.3  500.65  6095.2  502.28
#Mann= 3 ,-1 , 0
  4453.9      .1       0  5000.6     .07       0  5006.6      .1       0
Bank Sta=4980.04,5023.36
XS Rating Curve= 0 ,0
Exp/Cntr=0.3,0.1
LCMann Table=0

Chan Stop Cuts=-1
Use User Specified Reach Order=0
Composite Channel Slope=5