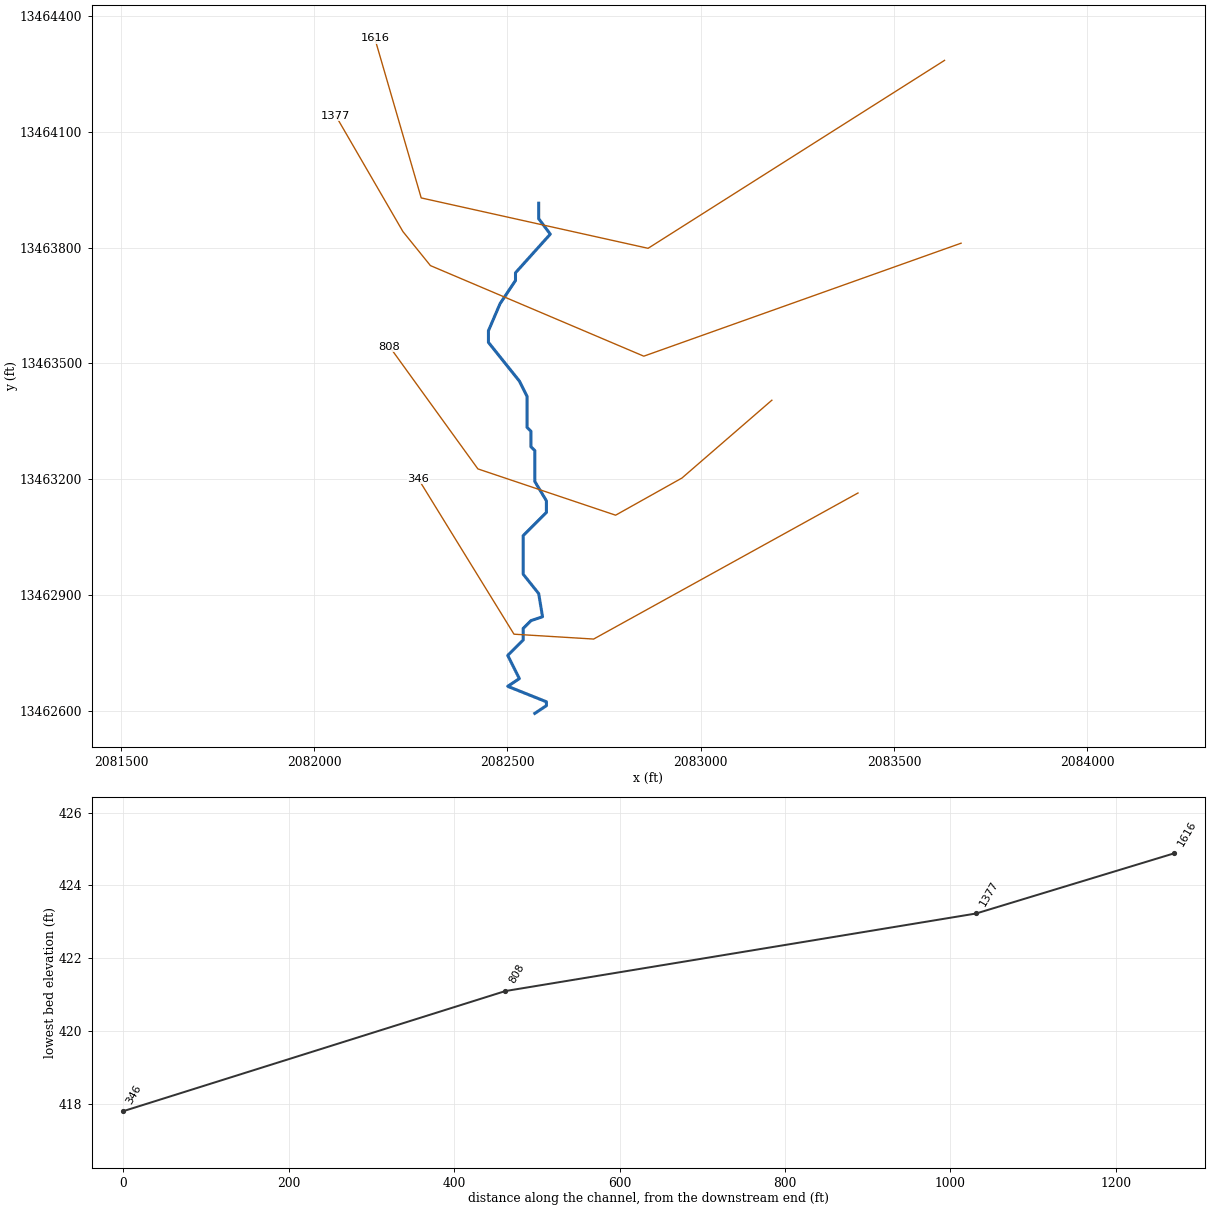
--- UNT 194 SanMiguel Cr Watershed.prj (project) ---

Proj Title=UNT 194 SanMiguel Cr Watershed Base Level Engineering
Current Plan=p01
Default Exp/Contr=0.3,0.1
English Units
Geom File=g01
Flow File=f01
Plan File=p01
Y Axis Title=Elevation
X Axis Title(PF)=Main Channel Distance
X Axis Title(XS)=Station
BEGIN DESCRIPTION:
UNT 194 SanMiguel Cr Watershed
END DESCRIPTION:
DSS Export Rating Curves= 0
DSS Export Rating Curve Sorted= 0
DSS Export Volume Flow Curves= 0
DXF OffsetX= 0
DXF OffsetY= 0
DXF ScaleX= 1
DXF ScaleY= 10

--- UNT 194 SanMiguel Cr Watershed.p01 (plan) ---

Plan Title=Multiple Run
Short Identifier=Multiple
Geom File=g01
Flow File=f01
Subcritical Flow
K Sum by GR= 0
Std Step Tol= 0.01
Critical Tol= 0.01
Num of Std Step Trials= 20
Max Error Tol= 0.3
Flow Tol Ratio= 0.001
Split Flow NTrial= 30
Split Flow Tol= 0.02
Split Flow Ratio= 0.02
Log Output Level= 0
Friction Slope Method= 1
Unsteady Friction Slope Method= 2
Unsteady Bridges Friction Slope Method= 1
Parabolic Critical Depth
Global Vel Dist=  1 , 1 , 1
Global Log Level= 0
CheckData=True
Encroach Param= -1, 0, 0, 0
BEGIN DESCRIPTION:
Multiple Run
END DESCRIPTION:

--- UNT 194 SanMiguel Cr Watershed.f01 (steady flow) ---

Flow Title=Multiple
Number of Profiles=7
Profile Names=10-year,25-year,50-year,1pct_min,100-year,1pct_plu,500-year
River Rch & RM= UNT 194 SanMigue,Reach-1,1616
     127     170     204     123     245     489     358
Boundary for River Rch & Prof#=UNT 194 SanMigue,Reach-1,1
Up Type=0
Dn Type=3
Dn Slope=0.005
Boundary for River Rch & Prof#=UNT 194 SanMigue,Reach-1,2
Up Type=0
Dn Type=3
Dn Slope=0.005
Boundary for River Rch & Prof#=UNT 194 SanMigue,Reach-1,3
Up Type=0
Dn Type=3
Dn Slope=0.005
Boundary for River Rch & Prof#=UNT 194 SanMigue,Reach-1,4
Up Type=0
Dn Type=3
Dn Slope=0.005
Boundary for River Rch & Prof#=UNT 194 SanMigue,Reach-1,5
Up Type=0
Dn Type=3
Dn Slope=0.005
Boundary for River Rch & Prof#=UNT 194 SanMigue,Reach-1,6
Up Type=0
Dn Type=3
Dn Slope=0.005
Boundary for River Rch & Prof#=UNT 194 SanMigue,Reach-1,7
Up Type=0
Dn Type=3
Dn Slope=0.005

--- UNT 194 SanMiguel Cr Watershed.g01 (geometry) ---

Geom Title=Existing Conditions
Program Version=5.05

River Reach=UNT 194 SanMigue,Reach-1
Reach XY= 30
       2082580.8     13463914.54       2082580.8     13463874.54
       2082610.8     13463834.54       2082520.8     13463734.54
       2082520.8     13463714.54       2082480.8     13463654.54
       2082450.8     13463584.54       2082450.8     13463554.54
       2082530.8     13463454.54       2082550.8     13463414.54
       2082550.8     13463334.54       2082560.8     13463324.54
       2082560.8     13463284.54       2082570.8     13463274.54
       2082570.8     13463194.54       2082600.8     13463144.54
       2082600.8     13463114.54       2082540.8     13463054.54
       2082540.8     13462954.54       2082580.8     13462904.54
       2082590.8     13462844.54       2082560.8     13462834.54
       2082540.8     13462814.54       2082540.8     13462784.54
       2082500.8     13462744.54       2082530.8     13462684.54
       2082500.8     13462664.54       2082600.8     13462624.54
       2082600.8     13462614.54       2082570.8     13462594.54

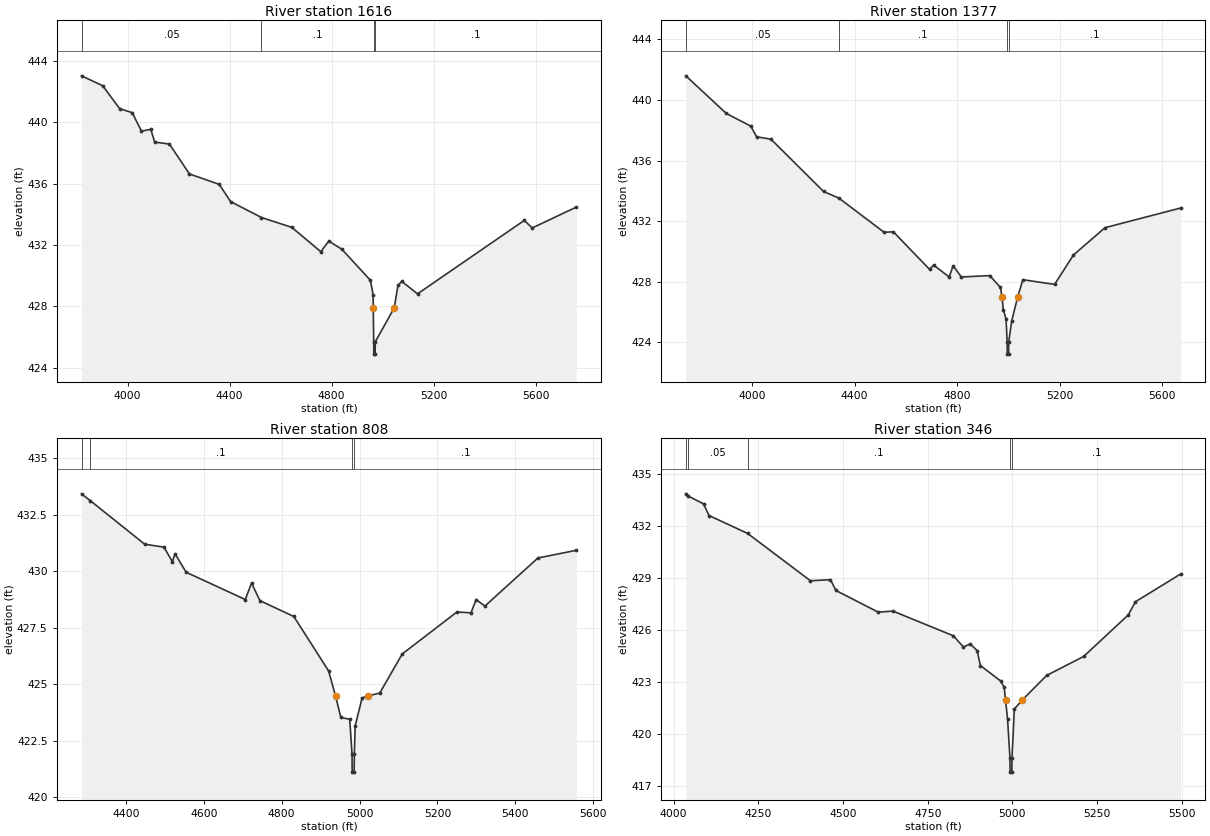
Type RM Length L Ch R = 1 ,1616    ,239,239,239
BEGIN DESCRIPTION:
UNT 194 SanMiguel Cr Watershed 4.0
END DESCRIPTION:
XS GIS Cut Line= 4
      2083631.03     13464284.24      2082863.89     13463797.92
      2082276.83     13463928.31      2082156.76     13464341.24
#Sta/Elev= 30
  3819.8  443.03  3903.2  442.38    3969  440.89  4018.4  440.63  4054.8  439.42
  4091.3  439.54  4106.5  438.71  4164.1  438.58  4242.9  436.63  4359.7  435.95
  4403.9  434.83  4525.1  433.79  4643.7  433.15  4757.7  431.56  4788.7  432.25
  4839.6  431.73  4952.3  429.69  4962.6  428.74 4963.26427.8989    4965  425.68
  4965.5  424.88  4970.5  424.88    4971  425.68 5045.48427.8947  5060.2  429.37
  5075.3  429.62  5136.7  428.81  5555.1   433.6  5586.4  433.11  5759.5  434.47
#Mann= 4 ,-1 , 0
  3819.8     .05       0  4525.1      .1       0    4965     .07       0
    4971      .1       0
Bank Sta=4963.26,5045.48
XS Rating Curve= 0 ,0
Exp/Cntr=0.3,0.1

Type RM Length L Ch R = 1 ,1377    ,569,569,569
BEGIN DESCRIPTION:
UNT 194 SanMiguel Cr Watershed 3.0
END DESCRIPTION:
XS GIS Cut Line= 5
      2083673.79     13463811.16      2082852.78     13463518.81
       2082300.7     13463753.18      2082229.53     13463841.24
      2082056.04     13464140.48
#Sta/Elev= 30
  3741.3  441.59  3899.2  439.11  3994.8  438.27  4017.2  437.57  4073.5  437.41
  4278.7  433.96  4338.8  433.52  4514.7  431.27  4550.9   431.3  4692.2  428.82
  4708.2   429.1  4768.7  428.32  4784.2  429.06    4816  428.32  4926.9  428.41
  4968.8  427.63  4975.1426.9825  4979.8  426.16  4990.6  425.55  4994.9  424.03
  4995.4  423.23  5000.4  423.23  5000.9  424.03  5012.4   425.4 5035.49426.9821
  5056.1  428.14  5179.8  427.83  5253.5  429.77  5376.4  431.57  5671.7  432.87
#Mann= 4 ,-1 , 0
  3741.3     .05       0  4338.8      .1       0  4994.9     .07       0
  5000.9      .1       0
Bank Sta=4975.1,5035.49
XS Rating Curve= 0 ,0
Exp/Cntr=0.3,0.1

Type RM Length L Ch R = 1 ,808     ,462,462,462
BEGIN DESCRIPTION:
UNT 194 SanMiguel Cr Watershed 2.0
END DESCRIPTION:
XS GIS Cut Line= 5
      2083184.17     13463404.88      2082951.56     13463203.52
      2082779.86     13463107.35      2082423.51     13463227.11
      2082194.64     13463543.76
#Sta/Elev= 30
    4286  433.42  4308.3  433.12  4448.2  431.19  4497.6  431.06  4519.5  430.41
  4526.1  430.77  4554.6  429.95  4706.6  428.74  4722.6  429.47  4744.3  428.69
  4831.3  427.99  4920.6  425.58 4938.34424.4758  4952.1  423.52  4974.9  423.44
  4980.7   421.9  4981.2   421.1  4986.2   421.1  4986.7   421.9  4988.9  423.15
  5006.6  424.38 5022.35424.4757    5052   424.6  5109.7  426.33  5250.2  428.19
  5286.4  428.15  5299.5  428.74    5322  428.45  5458.2  430.58  5557.1  430.92
#Mann= 4 ,-1 , 0
    4286     .05       0  4308.3      .1       0  4980.7     .07       0
  4986.7      .1       0
Bank Sta=4938.34,5022.35
XS Rating Curve= 0 ,0
Exp/Cntr=0.3,0.1

Type RM Length L Ch R = 1 ,346     ,0,0,0
BEGIN DESCRIPTION:
UNT 194 SanMiguel Cr Watershed 1.0
END DESCRIPTION:
XS GIS Cut Line= 4
      2083407.01     13463164.76      2082723.01     13462786.85
      2082516.91     13462799.44      2082268.99     13463201.98
#Sta/Elev= 30
    4036  433.84  4042.3  433.72  4088.4  433.26  4104.5  432.59  4218.3  431.56
  4403.9  428.83  4463.1  428.89  4479.1  428.27    4604  427.02  4647.5  427.08
  4825.5  425.66  4855.5  425.01  4875.6  425.19  4895.6  424.81  4905.6  423.94
  4965.7  423.05  4975.8  422.68 4979.69421.9681  4985.8  420.85  4992.8   418.6
  4993.3   417.8  4998.3   417.8  4998.8   418.6  5005.8  421.44 5029.75421.9676
  5100.9  423.37  5210.6  424.47    5342  426.86  5363.2  427.62  5496.7  429.22
#Mann= 5 ,-1 , 0
    4036      .1       0  4042.3     .05       0  4218.3      .1       0
  4992.8     .07       0  4998.8      .1       0
Bank Sta=4979.69,5029.75
XS Rating Curve= 0 ,0
Exp/Cntr=0.3,0.1
LCMann Table=0

Chan Stop Cuts=-1
Use User Specified Reach Order=0
Composite Channel Slope=5