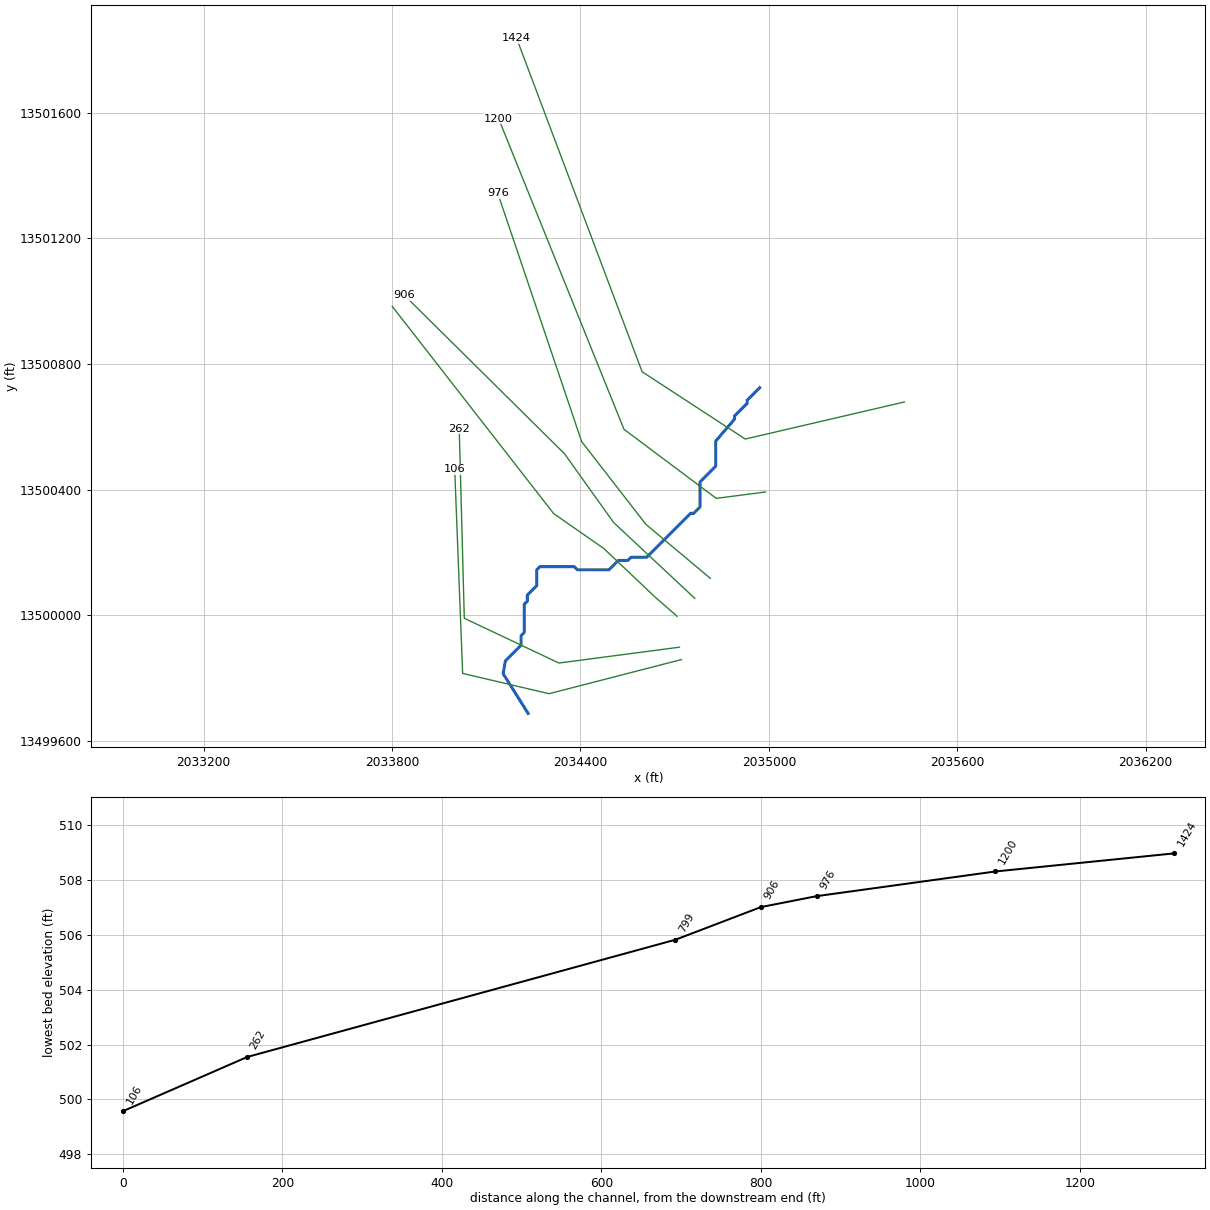
--- UNT 195 SanMiguel Cr Watershed.prj (project) ---

Proj Title=UNT 195 SanMiguel Cr Watershed Base Level Engineering
Current Plan=p01
Default Exp/Contr=0.3,0.1
English Units
Geom File=g01
Flow File=f01
Plan File=p01
Y Axis Title=Elevation
X Axis Title(PF)=Main Channel Distance
X Axis Title(XS)=Station
BEGIN DESCRIPTION:
UNT 195 SanMiguel Cr Watershed
END DESCRIPTION:
DSS Export Rating Curves= 0
DSS Export Rating Curve Sorted= 0
DSS Export Volume Flow Curves= 0
DXF OffsetX= 0
DXF OffsetY= 0
DXF ScaleX= 1
DXF ScaleY= 10

--- UNT 195 SanMiguel Cr Watershed.p01 (plan) ---

Plan Title=Multiple Run
Short Identifier=Multiple
Geom File=g01
Flow File=f01
Subcritical Flow
K Sum by GR= 0
Std Step Tol= 0.01
Critical Tol= 0.01
Num of Std Step Trials= 20
Max Error Tol= 0.3
Flow Tol Ratio= 0.001
Split Flow NTrial= 30
Split Flow Tol= 0.02
Split Flow Ratio= 0.02
Log Output Level= 0
Friction Slope Method= 1
Unsteady Friction Slope Method= 2
Unsteady Bridges Friction Slope Method= 1
Parabolic Critical Depth
Global Vel Dist=  1 , 1 , 1
Global Log Level= 0
CheckData=True
Encroach Param= -1, 0, 0, 0
BEGIN DESCRIPTION:
Multiple Run
END DESCRIPTION:

--- UNT 195 SanMiguel Cr Watershed.f01 (steady flow) ---

Flow Title=Multiple
Program Version=5.05
Number of Profiles= 7
Profile Names=10-year,25-year,50-year,1pct_min,100-year,1pct_plu,500-year
River Rch & RM=UNT 195 SanMigue,Reach-1         ,1424
     139     186     224     135     269     537     393
Boundary for River Rch & Prof#=UNT 195 SanMigue,Reach-1         , 1
Up Type= 0
Dn Type= 3
Dn Slope=0.005
Boundary for River Rch & Prof#=UNT 195 SanMigue,Reach-1         , 2
Up Type= 0
Dn Type= 3
Dn Slope=0.005
Boundary for River Rch & Prof#=UNT 195 SanMigue,Reach-1         , 3
Up Type= 0
Dn Type= 3
Dn Slope=0.005
Boundary for River Rch & Prof#=UNT 195 SanMigue,Reach-1         , 4
Up Type= 0
Dn Type= 3
Dn Slope=0.005
Boundary for River Rch & Prof#=UNT 195 SanMigue,Reach-1         , 5
Up Type= 0
Dn Type= 3
Dn Slope=0.005
Boundary for River Rch & Prof#=UNT 195 SanMigue,Reach-1         , 6
Up Type= 0
Dn Type= 3
Dn Slope=0.005
Boundary for River Rch & Prof#=UNT 195 SanMigue,Reach-1         , 7
Up Type= 0
Dn Type= 3
Dn Slope=0.005
DSS Import GetInterval= 0
DSS Import GetPeak= 0
DSS Import FillOption= 0

--- UNT 195 SanMiguel Cr Watershed.g01 (geometry) ---

Geom Title=Existing Conditions
Program Version=5.05

River Reach=UNT 195 SanMigue,Reach-1
Reach XY= 30
       2034970.8     13500724.54       2034930.8     13500684.54
       2034930.8     13500674.54       2034890.8     13500634.54
       2034890.8     13500624.54       2034830.8     13500554.54
       2034830.8     13500474.54       2034780.8     13500424.54
       2034780.8     13500344.54       2034760.8     13500324.54
       2034750.8     13500324.54       2034610.8     13500184.54
       2034560.8     13500184.54       2034550.8     13500174.54
       2034520.8     13500174.54       2034490.8     13500144.54
       2034390.8     13500144.54       2034380.8     13500154.54
       2034270.8     13500154.54       2034260.8     13500144.54
       2034260.8     13500094.54       2034230.8     13500064.54
       2034230.8     13500044.54       2034220.8     13500034.54
       2034220.8     13499944.54       2034210.8     13499934.54
       2034210.8     13499904.54       2034160.8     13499854.54
      2034153.74      13499813.7      2034233.24     13499687.33

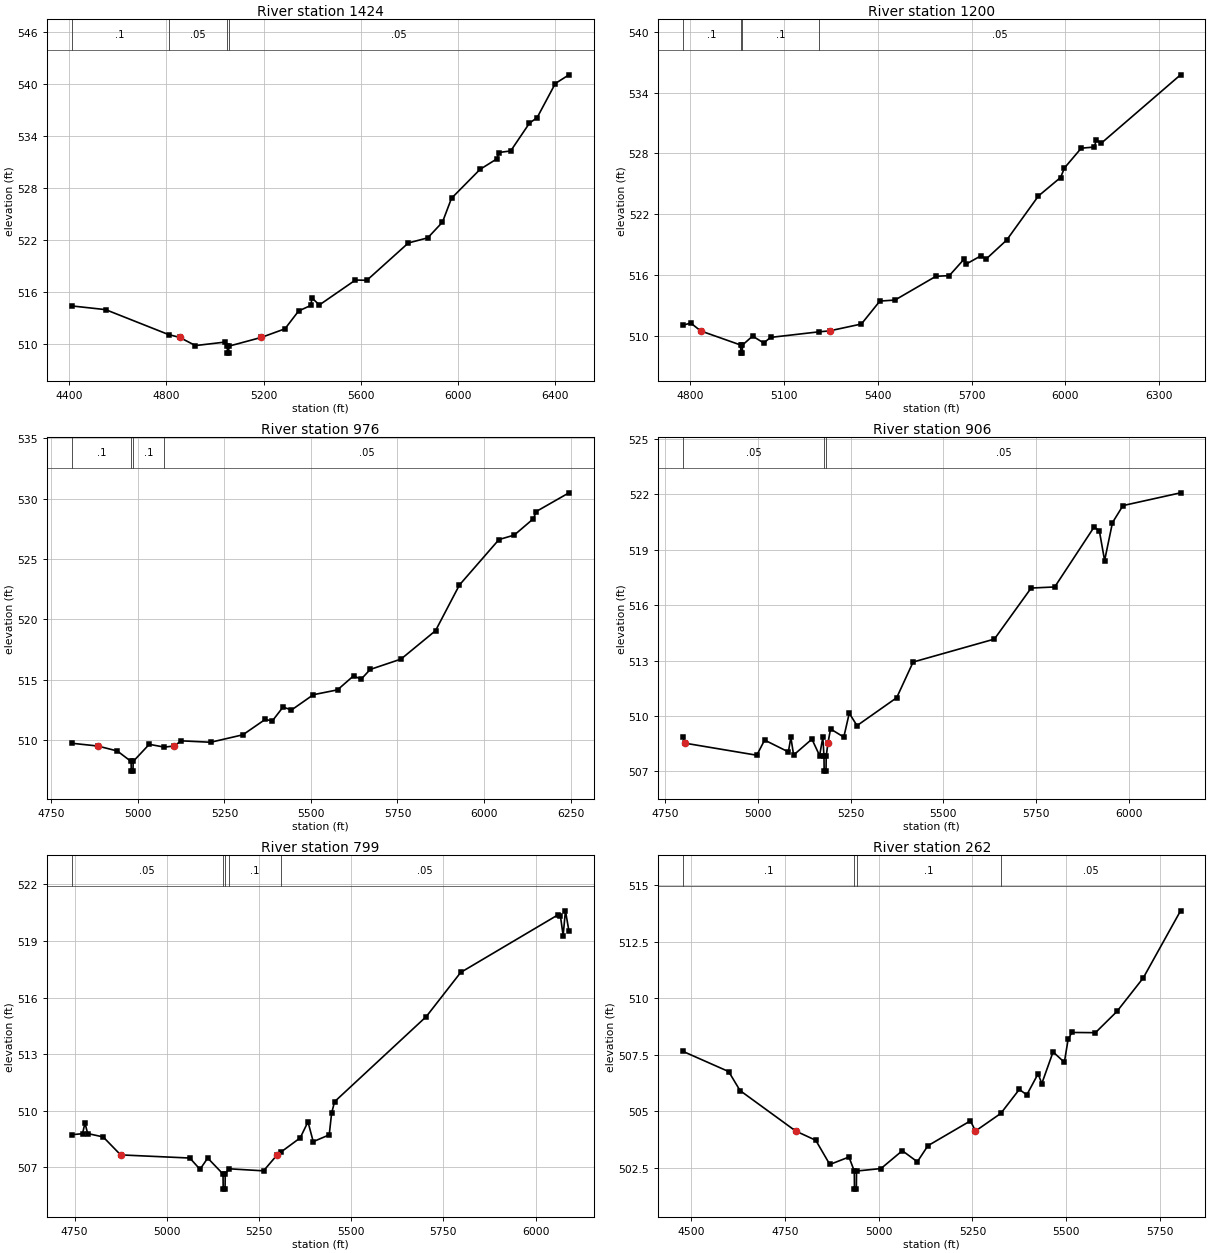
Type RM Length L Ch R = 1 ,1424    ,224,224,224
BEGIN DESCRIPTION:
UNT 195 SanMiguel Cr Watershed 7.0
END DESCRIPTION:
XS GIS Cut Line= 4
      2035431.67     13500679.19      2034924.89     13500561.13
      2034596.38     13500775.49       2034196.7     13501837.46
#Sta/Elev= 30
  4409.2  514.42  4549.5  513.99  4808.4  511.12 4853.97510.7936  4919.2  509.85
  5040.1  510.25  5050.4  509.78  5050.9  508.98  5055.9  508.98  5056.4  509.78
 5190.84510.7938  5287.6  511.78    5344  513.84  5393.7  514.47  5399.1  515.32
  5429.3  514.53  5577.7   517.4  5624.8  517.37  5795.5  521.67  5875.4  522.26
  5935.9  524.07  5973.1  526.82  6090.6  530.15  6161.6  531.39    6167  532.09
  6216.7  532.27  6293.6  535.46  6325.7  536.12  6400.4  540.04  6456.5  541.04
#Mann= 4 ,-1 , 0
  4409.2      .1       0  4808.4     .05       0  5050.4     .03       0
  5056.4     .05       0
Bank Sta=4853.97,5190.84
XS Rating Curve= 0 ,0
Exp/Cntr=0.3,0.1

Type RM Length L Ch R = 1 ,1200    ,224,224,224
BEGIN DESCRIPTION:
UNT 195 SanMiguel Cr Watershed 6.0
END DESCRIPTION:
XS GIS Cut Line= 4
      2034989.18     13500392.48      2034832.59     13500372.16
      2034538.57     13500592.25      2034139.63     13501580.92
#Sta/Elev= 30
  4777.4  511.07  4801.8  511.29  4833.3510.5123  4961.3  509.12  4961.8  508.32
  4966.8  508.32  4967.3  509.12  4999.7     510  5035.1  509.32  5057.2  509.87
    5212  510.42  5245.7510.5124  5347.7  511.19  5406.8  513.45  5455.1  513.55
  5585.9  515.89    5629  515.96  5675.2  517.55    5683   517.1  5728.9  517.89
  5747.7  517.62  5812.4  519.46  5914.1  523.81  5984.9  525.63  5997.3  526.57
    6051  528.52  6092.7  528.63  6099.3  529.33  6114.3  528.99  6368.7  535.75
#Mann= 4 ,-1 , 0
  4777.4      .1       0  4961.3     .07       0  4967.3      .1       0
    5212     .05       0
Bank Sta=4833.3,5245.7
XS Rating Curve= 0 ,0
Exp/Cntr=0.3,0.1

Type RM Length L Ch R = 1 ,976     ,70,70,70
BEGIN DESCRIPTION:
UNT 195 SanMiguel Cr Watershed 5.0
END DESCRIPTION:
XS GIS Cut Line= 4
      2034813.86     13500117.26      2034608.62     13500289.22
      2034403.76      13500553.1      2034136.41     13501344.75
#Sta/Elev= 30
  4808.1  509.73 4883.79509.5003  4940.3  509.09  4980.2  508.22  4980.7  507.42
  4985.7  507.42  4986.2  508.22  5032.6  509.64    5076  509.41 5104.84509.5003
    5125  509.93  5210.1  509.81  5303.3  510.43  5367.6   511.7  5388.4  511.58
  5419.4  512.73  5443.6  512.48  5506.9  513.75  5576.7  514.15    5623  515.31
  5644.9  515.03  5671.1  515.84  5760.2   516.7  5859.9  519.05  5929.1  522.84
  6043.3   526.6  6087.4  526.97    6143  528.33  6150.8  528.92  6245.5  530.47
#Mann= 4 ,-1 , 0
  4808.1      .1       0  4980.2     .07       0  4986.2      .1       0
    5076     .05       0
Bank Sta=4883.79,5104.84
XS Rating Curve= 0 ,0
Exp/Cntr=0.3,0.1

Type RM Length L Ch R = 1 ,906     ,107,107,107
BEGIN DESCRIPTION:
UNT 195 SanMiguel Cr Watershed 4.0
END DESCRIPTION:
XS GIS Cut Line= 5
       2034764.2     13500053.71      2034717.49     13500097.36
      2034505.58     13500295.37      2034349.33     13500514.12
      2033839.44      13501018.8
#Sta/Elev= 30
  4798.9  508.85 4804.53508.5295  4997.4  507.88  5018.4   508.7  5082.4  508.06
  5089.2  508.84  5096.6  507.89  5145.9  508.75  5166.6  507.86  5175.3  508.85
  5178.4  507.82  5178.9  507.02  5183.9  507.02  5184.4  507.82 5189.04508.5302
  5196.1   509.3  5231.8  508.86  5246.5  510.15  5267.4  509.48  5374.3  510.99
  5418.6  512.92  5637.5  514.16  5736.5  516.92  5800.1  516.98  5906.2  520.22
  5920.3  520.02  5934.5  518.41  5955.7  520.46    5984  521.38  6139.1  522.07
#Mann= 3 ,-1 , 0
  4798.9     .05       0  5178.4     .04       0  5184.4     .05       0
Bank Sta=4804.53,5189.04
XS Rating Curve= 0 ,0
Exp/Cntr=0.3,0.1

Type RM Length L Ch R = 1 ,799     ,537,537,537
BEGIN DESCRIPTION:
UNT 195 SanMiguel Cr Watershed 3.0
END DESCRIPTION:
XS GIS Cut Line= 5
      2034707.97     13499996.52      2034639.13     13500056.49
      2034474.47     13500212.47      2034314.75     13500323.58
      2033800.88     13500983.29
#Sta/Elev= 30
  4741.5  508.72  4771.3  508.77  4777.9  509.34  4785.2  508.78  4827.3   508.6
 4874.64507.6466  5062.3  507.48  5089.9  506.88  5110.8  507.48  5152.3  506.63
  5152.8  505.83  5157.8  505.83  5158.3  506.63  5168.3  506.91  5262.1   506.8
 5299.12507.6467  5310.3  507.81  5361.6  508.55  5382.7   509.4  5396.9  508.35
  5440.3  508.71  5446.7  509.85  5454.8  510.47  5703.6  514.99  5796.8  517.33
  6060.1  520.38  6067.2  520.34  6074.6  519.29  6080.9   520.6  6090.4  519.52
#Mann= 5 ,-1 , 0
  4741.5     .05       0  5152.3     .04       0  5158.3     .05       0
  5168.3      .1       0  5310.3     .05       0
Bank Sta=4874.64,5299.12
XS Rating Curve= 0 ,0
Exp/Cntr=0.3,0.1

Type RM Length L Ch R = 1 ,262     ,156,156,156
BEGIN DESCRIPTION:
UNT 195 SanMiguel Cr Watershed 2.0
END DESCRIPTION:
XS GIS Cut Line= 4
      2034715.26     13499898.15      2034331.47     13499847.64
      2034030.03     13499990.25      2034013.88     13500594.36
#Sta/Elev= 30
  4479.4  507.64  4600.7  506.75    4631  505.91 4779.15504.1202  4832.7  503.71
  4870.1  502.64  4921.1  502.97  4935.3  502.35  4935.8  501.55  4940.8  501.55
  4941.3  502.35  5006.4  502.46  5063.2  503.25  5103.2  502.76  5131.4  503.47
  5244.7  504.57 5258.09504.1202  5325.6   504.9  5374.8  505.96  5394.8  505.72
  5424.8  506.65  5434.8  506.22  5464.8  507.62  5494.8  507.16  5504.8  508.17
  5514.8  508.48  5577.6  508.47  5634.9  509.41  5704.9  510.89  5804.3  513.86
#Mann= 4 ,-1 , 0
  4479.4      .1       0  4935.3     .07       0  4941.3      .1       0
  5325.6     .05       0
Bank Sta=4779.15,5258.09
XS Rating Curve= 0 ,0
Exp/Cntr=0.3,0.1

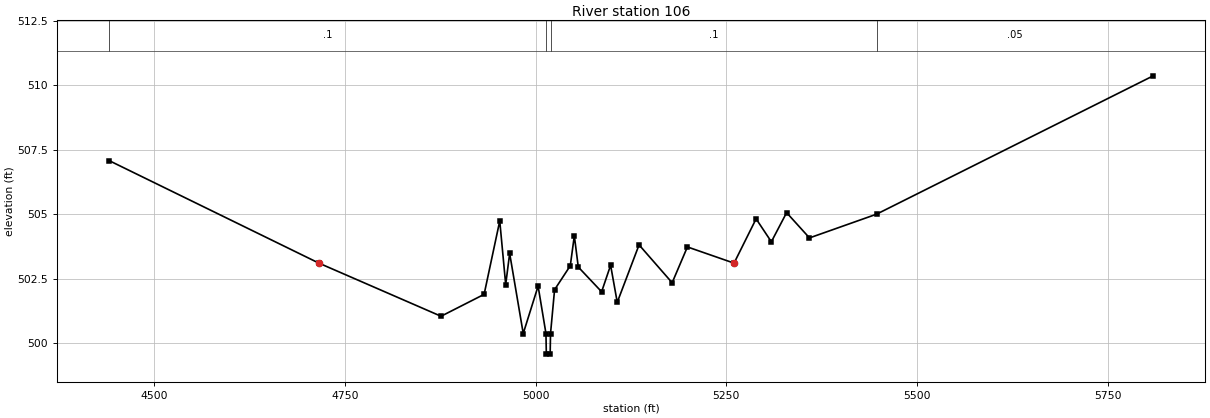
Type RM Length L Ch R = 1 ,106     ,0,0,0
BEGIN DESCRIPTION:
UNT 195 SanMiguel Cr Watershed 1.0
END DESCRIPTION:
XS GIS Cut Line= 4
       2034721.5     13499858.65        2034300.       13499750.
      2034024.79      13499814.6      2033999.45     13500465.43
#Sta/Elev= 30
  4440.5  507.08 4715.65503.1009  4875.8  501.04  4932.3  501.89  4952.8  504.74
  4960.6  502.27  4965.8  503.48  4983.6  500.37  5003.1  502.21  5013.4  500.37
  5013.9  499.57  5018.9  499.57  5019.4  500.37  5024.7  502.07  5045.3     503
  5050.6  504.16  5055.8  502.95  5086.4  501.99  5098.2  503.02  5106.9  501.58
  5135.5  503.81  5178.9  502.34  5198.9  503.73 5260.07 503.101    5289  504.82
    5309  503.93    5329  505.06    5359  504.08  5446.9     505  5809.8  510.37
#Mann= 4 ,-1 , 0
  4440.5      .1       0  5013.4     .07       0  5019.4      .1       0
  5446.9     .05       0
Bank Sta=4715.65,5260.07
XS Rating Curve= 0 ,0
Exp/Cntr=0.3,0.1
LCMann Table=0

Chan Stop Cuts=-1
Use User Specified Reach Order=0
Composite Channel Slope=5