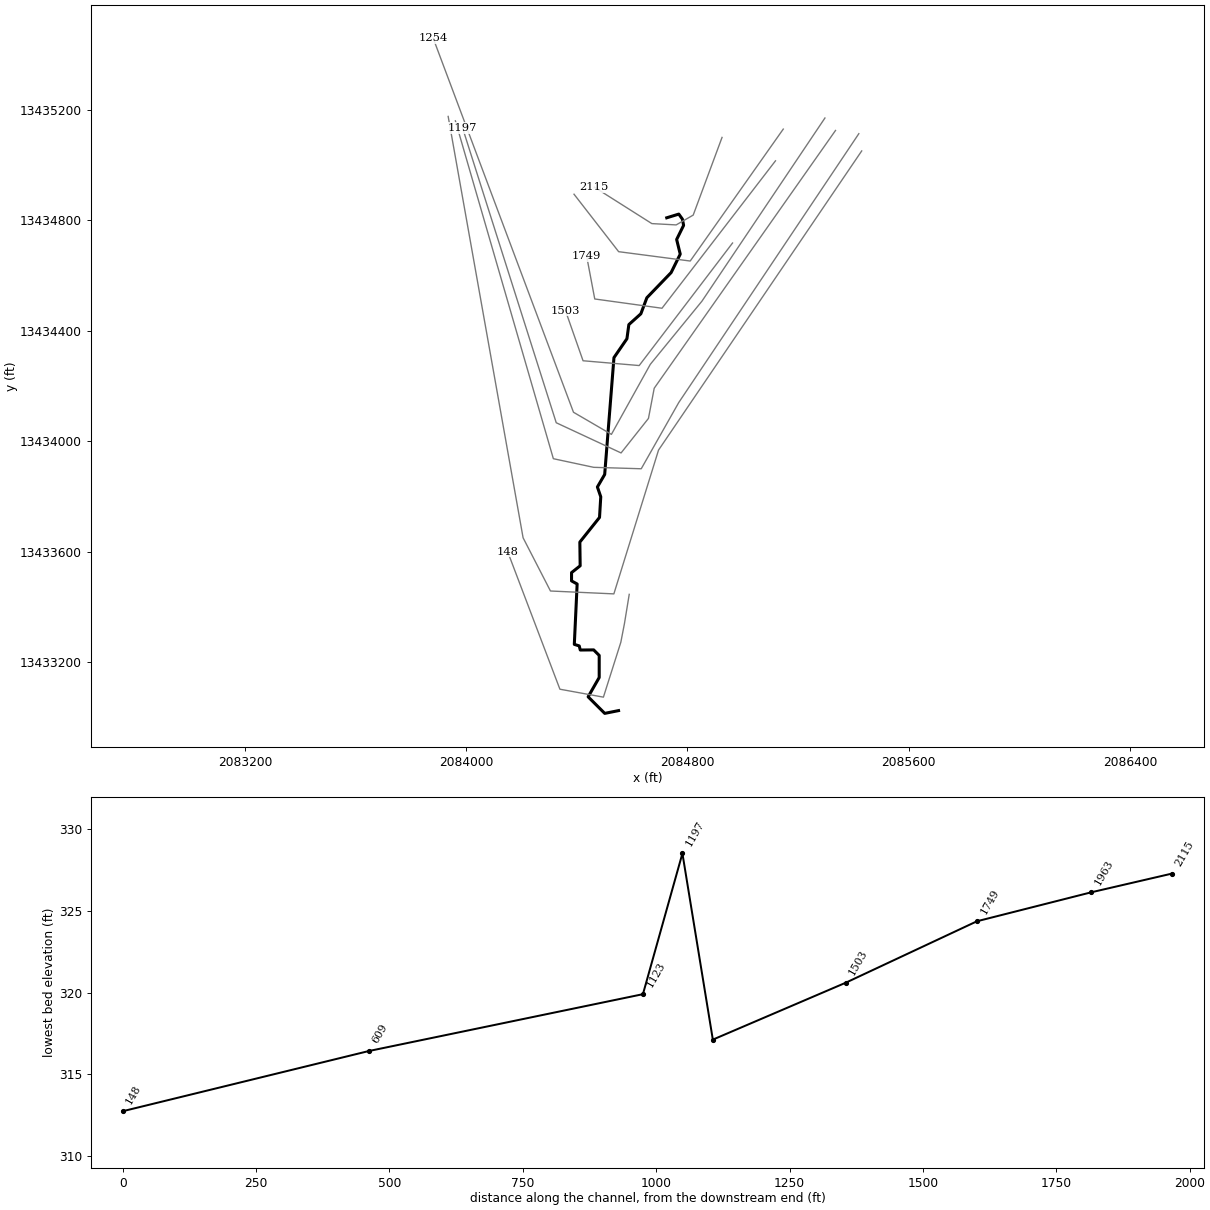
--- UNT 196 SanMiguel Cr Watershed.prj (project) ---

Proj Title=UNT 196 SanMiguel Cr Watershed Base Level Engineering
Current Plan=p01
Default Exp/Contr=0.3,0.1
English Units
Geom File=g01
Flow File=f01
Plan File=p01
Y Axis Title=Elevation
X Axis Title(PF)=Main Channel Distance
X Axis Title(XS)=Station
BEGIN DESCRIPTION:
UNT 196 SanMiguel Cr Watershed
END DESCRIPTION:
DSS Export Rating Curves= 0
DSS Export Rating Curve Sorted= 0
DSS Export Volume Flow Curves= 0
DXF OffsetX= 0
DXF OffsetY= 0
DXF ScaleX= 1
DXF ScaleY= 10

--- UNT 196 SanMiguel Cr Watershed.p01 (plan) ---

Plan Title=Multiple Run
Short Identifier=Multiple
Geom File=g01
Flow File=f01
Subcritical Flow
K Sum by GR= 0
Std Step Tol= 0.01
Critical Tol= 0.01
Num of Std Step Trials= 20
Max Error Tol= 0.3
Flow Tol Ratio= 0.001
Split Flow NTrial= 30
Split Flow Tol= 0.02
Split Flow Ratio= 0.02
Log Output Level= 0
Friction Slope Method= 1
Unsteady Friction Slope Method= 2
Unsteady Bridges Friction Slope Method= 1
Parabolic Critical Depth
Global Vel Dist=  1 , 1 , 1
Global Log Level= 0
CheckData=True
Encroach Param= -1, 0, 0, 0
BEGIN DESCRIPTION:
Multiple Run
END DESCRIPTION:

--- UNT 196 SanMiguel Cr Watershed.f01 (steady flow) ---

Flow Title=Multiple
Number of Profiles=7
Profile Names=10-year,25-year,50-year,1pct_min,100-year,1pct_plu,500-year
River Rch & RM= UNT 196 SanMigue,Reach-1,2115
      41      51      58      33      66     131      87
Boundary for River Rch & Prof#=UNT 196 SanMigue,Reach-1,1
Up Type=0
Dn Type=3
Dn Slope=0.005
Boundary for River Rch & Prof#=UNT 196 SanMigue,Reach-1,2
Up Type=0
Dn Type=3
Dn Slope=0.005
Boundary for River Rch & Prof#=UNT 196 SanMigue,Reach-1,3
Up Type=0
Dn Type=3
Dn Slope=0.005
Boundary for River Rch & Prof#=UNT 196 SanMigue,Reach-1,4
Up Type=0
Dn Type=3
Dn Slope=0.005
Boundary for River Rch & Prof#=UNT 196 SanMigue,Reach-1,5
Up Type=0
Dn Type=3
Dn Slope=0.005
Boundary for River Rch & Prof#=UNT 196 SanMigue,Reach-1,6
Up Type=0
Dn Type=3
Dn Slope=0.005
Boundary for River Rch & Prof#=UNT 196 SanMigue,Reach-1,7
Up Type=0
Dn Type=3
Dn Slope=0.005

--- UNT 196 SanMiguel Cr Watershed.g01 (geometry) ---

Geom Title=Existing Conditions
Program Version=5.05

River Reach=UNT 196 SanMigue,Reach-1
Reach XY= 30
      2084724.99     13434809.36      2084768.57     13434822.74
      2084781.59     13434804.51      2084785.93     13434781.94
      2084760.75     13434730.73      2084773.78     13434677.77
       2084740.8     13434610.93      2084653.12     13434519.79
      2084631.41     13434461.63      2084588.01     13434422.57
      2084581.07     13434371.35      2084534.19     13434302.95
      2084500.66     13433879.76      2084474.33     13433834.45
      2084486.48     13433798.88      2084482.01     13433724.18
      2084410.87     13433634.91      2084412.04     13433549.06
      2084380.89     13433524.27      2084380.89     13433494.28
      2084401.11     13433483.12      2084390.88     13433264.41
      2084408.65     13433258.85      2084412.43     13433243.98
      2084460.85     13433244.42      2084480.83     13433224.43
      2084480.84     13433144.47      2084440.86     13433074.51
      2084500.83     13433014.54       2084550.8     13433024.54

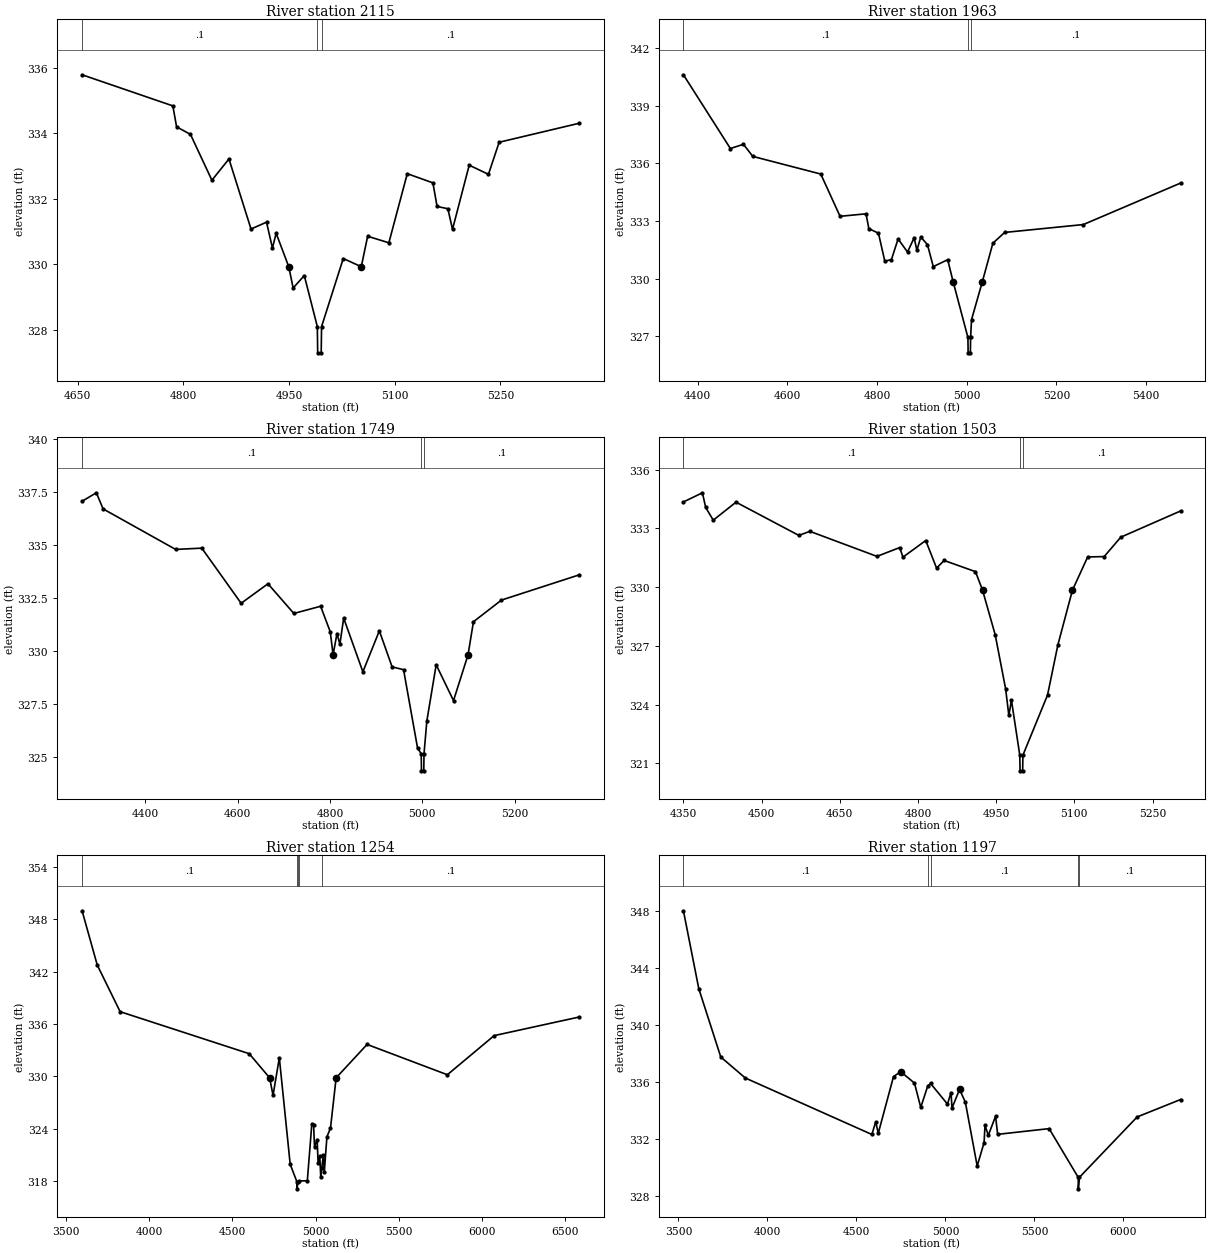
Type RM Length L Ch R = 1 ,2115    ,152,152,152
BEGIN DESCRIPTION:
UNT 196 SanMiguel Cr Watershed 6.0
END DESCRIPTION:
XS GIS Cut Line= 5
      2084924.85     13435100.43      2084820.67     13434819.15
      2084759.04     13434783.56      2084671.16     13434788.32
      2084463.23     13434920.28
#Sta/Elev= 30
  4656.5  335.78  4785.3  334.83  4790.6  334.19  4810.3  333.96  4840.7  332.56
  4864.9  333.21  4896.2  331.07  4918.2  331.28  4926.6  330.49  4931.9  330.94
 4949.72329.9199    4956  329.27  4971.8  329.65  4990.3  328.09  4990.8  327.29
  4995.8  327.29  4996.3  328.09  5027.1  330.17 5052.67329.9199  5061.7  330.85
  5091.8  330.65  5117.9  332.76  5154.3  332.48  5160.2  331.76  5175.5  331.69
  5182.1  331.06  5205.8  333.02  5233.1  332.74  5248.3  333.72  5361.9   334.3
#Mann= 3 ,-1 , 0
  4656.5      .1       0  4990.3     .07       0  4996.3      .1       0
Bank Sta=4949.72,5052.67
XS Rating Curve= 0 ,0
Exp/Cntr=0.3,0.1

Type RM Length L Ch R = 1 ,1963    ,214,214,214
BEGIN DESCRIPTION:
Mapping XS b44c9548
END DESCRIPTION:
XS GIS Cut Line= 4
      2085146.18      13435130.6      2084809.82     13434652.75
      2084551.14     13434686.61      2084389.82     13434894.76
#Sta/Elev= 30
  4368.1  340.62  4472.8  336.78  4501.9     337  4522.8  336.37  4674.4  335.45
  4717.4  333.25  4775.4  333.38  4781.5  332.61    4803  332.37  4817.2  330.91
    4832     331  4846.8  332.07  4867.8  331.39  4882.6  332.13  4888.7  331.48
  4897.4  332.17  4912.2  331.78  4925.3  330.63  4957.4  330.99 4969.46329.8513
  5002.5  326.94    5003  326.14    5008  326.14  5008.5  326.94  5010.6  327.87
 5034.77329.8514  5058.2  331.85  5084.4  332.41  5259.9  332.82  5476.7  334.98
#Mann= 3 ,-1 , 0
  4368.1      .1       0  5002.5     .07       0  5008.5      .1       0
Bank Sta=4969.46,5034.77
XS Rating Curve= 0 ,0
Exp/Cntr=0.3,0.1

Type RM Length L Ch R = 1 ,1749    ,246,246,246
BEGIN DESCRIPTION:
Mapping XS a1884ab3
END DESCRIPTION:
XS GIS Cut Line= 4
      2085118.01     13435015.63      2084707.82     13434481.75
      2084464.77     13434515.33      2084435.41     13434670.75
#Sta/Elev= 30
    4263  337.08  4293.9  337.48  4308.5  336.72  4465.6  334.81  4522.3  334.87
  4607.5  332.27  4665.6  333.19  4721.7  331.79  4779.7  332.13  4800.6  330.92
 4806.67329.8409  4815.1  330.84  4821.4  330.34  4829.6  331.57  4871.2  329.04
  4906.9  330.97  4934.5  329.27  4959.3  329.14  4989.6  325.45  4997.6  325.17
  4998.1  324.37  5003.1  324.37  5003.6  325.17  5009.8  326.73    5030  329.37
  5067.5  327.68 5098.98329.8405  5110.7   331.4  5171.3  332.42  5339.8  333.61
#Mann= 3 ,-1 , 0
    4263      .1       0  4997.6     .07       0  5003.6      .1       0
Bank Sta=4806.67,5098.98
XS Rating Curve= 0 ,0
Exp/Cntr=0.3,0.1

Type RM Length L Ch R = 1 ,1503    ,249,249,249
BEGIN DESCRIPTION:
Mapping XS 8c2fa429
END DESCRIPTION:
XS GIS Cut Line= 4
       2084962.8       13434718.      2084625.36     13434274.23
      2084422.45     13434291.59      2084358.86     13434473.24
#Sta/Elev= 30
  4350.1  334.35  4386.5  334.82  4392.8  334.07  4407.3  333.42    4451  334.34
  4571.6  332.64  4592.6  332.85  4721.3  331.57    4765  332.02  4771.2  331.53
  4814.9  332.38  4835.7  330.97  4850.2  331.36  4910.3  330.79 4923.89329.8395
  4948.1  327.57  4968.2  324.79  4974.3  323.44  4979.3  324.22  4995.3  321.41
  4995.8  320.61  5000.8  320.61  5001.3  321.41  5048.5  324.48  5068.5  327.06
 5096.28329.8395  5125.5  331.54  5157.2  331.56    5189  332.55  5303.7  333.89
#Mann= 3 ,-1 , 0
  4350.1      .1       0  4995.3     .07       0  5001.3      .1       0
Bank Sta=4923.89,5096.28
XS Rating Curve= 0 ,0
Exp/Cntr=0.3,0.1

Type RM Length L Ch R = 1 ,1254    ,57,57,57
BEGIN DESCRIPTION:
UNT 196 SanMiguel Cr Watershed 5.0
END DESCRIPTION:
XS GIS Cut Line= 6
      2085296.77     13435170.72      2084852.35     13434507.56
      2084665.64     13434278.72        2084525.       13434025.
      2084387.86     13434105.11      2083880.92     13435459.27
#Sta/Elev= 30
    3596  348.96  3687.1  342.75  3824.7  337.41  4600.7   332.6 4723.44329.8389
  4743.9  327.83  4781.7  332.13    4847  319.94  4887.5  317.93    4888  317.13
  4893.5  317.93  4899.6  318.03    4950  318.05  4976.9  324.52  4987.6  324.47
  4993.4  321.94  5009.1  322.76  5014.9  320.04  5024.8  320.89  5030.6  318.54
  5037.4  319.57  5046.3  321.03  5052.1  319.06  5067.8  323.08  5089.3  324.09
 5123.24329.8391  5309.3  333.66  5791.8  330.19  6073.2  334.67  6584.5   336.8
#Mann= 5 ,-1 , 0
    3596      .1       0  4887.5    .033       0  4893.5      .1       0
  4899.6     .05       0  5037.4      .1       0
Bank Sta=4723.44,5123.24
XS Rating Curve= 0 ,0
Exp/Cntr=0.3,0.1

Type RM Length L Ch R = 1 ,1197    ,74,74,74
BEGIN DESCRIPTION:
UNT 196 SanMiguel Cr Watershed 4.0
END DESCRIPTION:
XS GIS Cut Line= 6
      2085335.01     13435125.64       2084679.7     13434192.09
      2084658.87     13434082.72      2084559.91     13433957.72
      2084325.54     13434067.09        2083987.     13435134.78
#Sta/Elev= 30
  3527.7  348.01    3614  342.55  3737.6  337.76  3875.3  336.29  4586.7  332.33
  4608.3  333.22  4622.5  332.41  4708.3  336.39  4749.1  336.73  4826.1  335.93
  4861.3  334.23  4899.9   335.7  4916.2  335.91  5011.4  334.46  5031.5  335.27
  5036.8  334.18  5079.6  335.49    5112  334.59  5178.5  330.12  5217.2  331.76
  5222.4  332.97    5241  332.27  5281.7  333.61  5293.4  332.34  5582.7  332.74
  5746.4  329.32  5746.9  328.52  5752.4  329.32  6077.4  333.56  6321.3  334.78
#Mann= 5 ,-1 , 0
  3527.7      .1       0  4899.9     .05       0  4916.2      .1       0
  5746.4     .07       0  5752.4      .1       0
Bank Sta=4749.1,5079.6
XS Rating Curve= 0 ,0
Exp/Cntr=0.3,0.1

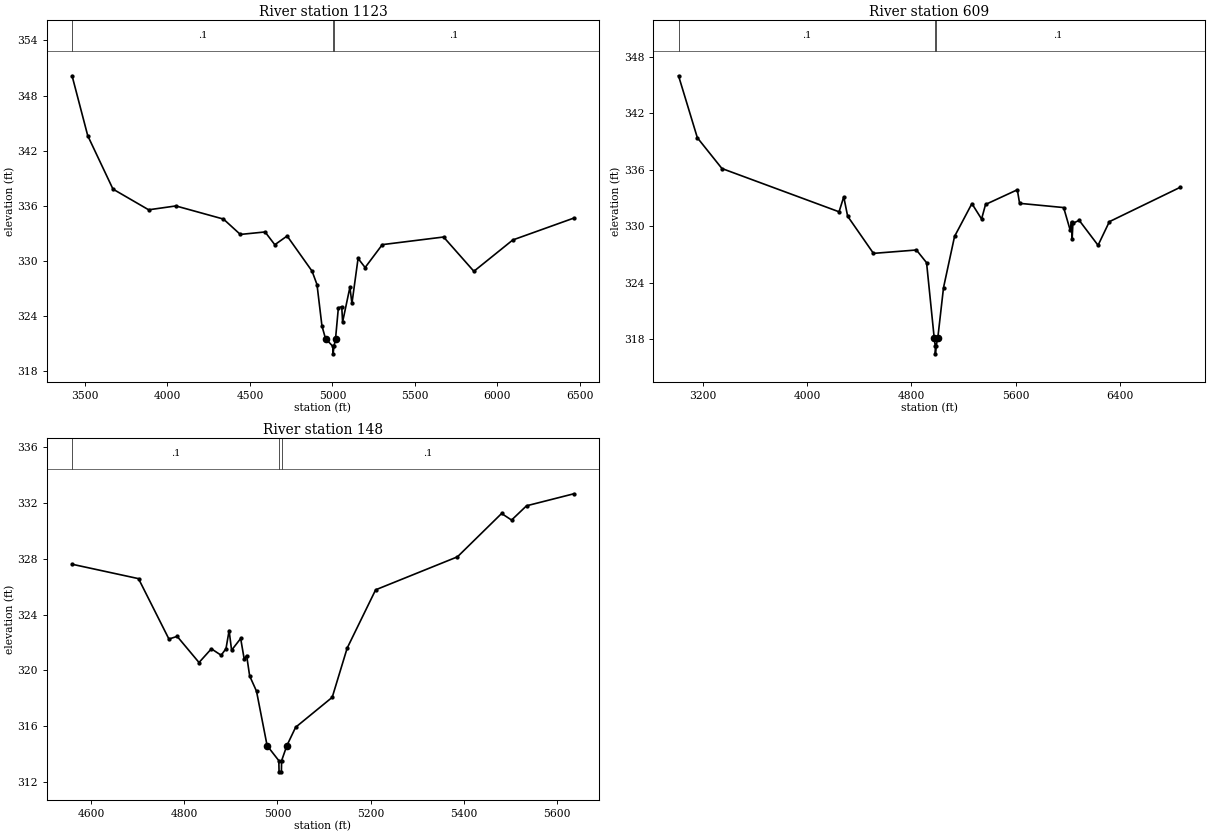
Type RM Length L Ch R = 1 ,1123    ,514,514,514
BEGIN DESCRIPTION:
UNT 196 SanMiguel Cr Watershed 3.0
END DESCRIPTION:
XS GIS Cut Line= 6
      2085419.29     13435113.98      2084768.24     13434140.01
      2084632.83     13433900.43      2084460.95     13433905.63
      2084315.12     13433936.88      2083961.06     13435160.46
#Sta/Elev= 30
  3421.6  350.16  3516.6  343.64  3669.6  337.83  3885.8  335.58    4051     336
  4339.3  334.57  4441.4   332.9  4591.5  333.17  4650.5  331.78  4725.2  332.73
  4876.2  328.91  4906.2  327.45  4936.2  322.95 4957.82321.5637  5003.2  320.71
  5003.7  319.91  5009.2  320.71 5018.67321.5625  5035.8  324.92  5056.3  325.04
  5061.4  323.37  5105.7  327.15    5118  325.39  5155.2  330.29  5197.9   329.3
    5302  331.79  5673.5  332.62  5857.2  328.89  6093.2   332.3  6463.2  334.68
#Mann= 3 ,-1 , 0
  3421.6      .1       0  5003.2     .07       0  5009.2      .1       0
Bank Sta=4957.82,5018.67
XS Rating Curve= 0 ,0
Exp/Cntr=0.3,0.1

Type RM Length L Ch R = 1 ,609     ,461,461,461
BEGIN DESCRIPTION:
UNT 196 SanMiguel Cr Watershed 2.0
END DESCRIPTION:
XS GIS Cut Line= 6
       2085429.7     13435051.47      2084695.33     13433968.13
      2084533.87      13433447.3       2084304.7     13433457.72
      2084205.74     13433650.43      2083934.91     13435176.47
#Sta/Elev= 30
  3012.8  345.99  3157.2   339.4  3345.8  336.13  4244.4  331.53  4280.4  333.12
  4310.3  331.06  4508.3  327.11  4837.9  327.47  4915.8  326.12 4974.37318.1284
  4982.9  317.23  4983.4  316.43  4988.9  317.23  5002.1318.1288  5045.9  323.47
  5130.5  328.91  5263.6   332.4  5337.9  330.76  5368.3  332.31  5612.1  333.87
  5629.6  332.43  5967.6  331.98  6018.3  329.55    6028  330.48    6033  328.69
  6038.6  330.31    6087  330.62  6231.6  327.97  6318.3  330.48  6862.8  334.14
#Mann= 3 ,-1 , 0
  3012.8      .1       0  4982.9     .07       0  4988.9      .1       0
Bank Sta=4974.37,5002.1
XS Rating Curve= 0 ,0
Exp/Cntr=0.3,0.1

Type RM Length L Ch R = 1 ,148     ,0,0,0
BEGIN DESCRIPTION:
UNT 196 SanMiguel Cr Watershed 1.0
END DESCRIPTION:
XS GIS Cut Line= 6
      2084589.38     13433445.59      2084572.02     13433339.28
        2084559.       13433272.      2084496.07     13433073.31
       2084338.8     13433102.07      2084149.99     13433600.03
#Sta/Elev= 30
  4559.2   327.6  4701.8  326.57  4767.1  322.25  4784.8  322.44  4831.7  320.57
  4858.2  321.55  4879.2  321.09  4889.6  321.56  4896.3  322.86  4901.6  321.45
  4921.1  322.29  4928.6  320.83  4933.9  321.07  4940.4  319.61  4955.1  318.52
 4977.87314.6236    5003  313.55  5003.5  312.75  5008.5  312.75    5009  313.55
 5020.25314.6248  5039.1  315.94  5117.6  318.08  5149.7   321.6  5210.8  325.77
  5386.4  328.13  5481.2  331.23  5502.6  330.76  5534.7  331.78  5636.3  332.64
#Mann= 3 ,-1 , 0
  4559.2      .1       0    5003     .07       0    5009      .1       0
Bank Sta=4977.87,5020.25
XS Rating Curve= 0 ,0
Exp/Cntr=0.3,0.1
LCMann Table=0

Chan Stop Cuts=-1
Use User Specified Reach Order=0
Composite Channel Slope=5