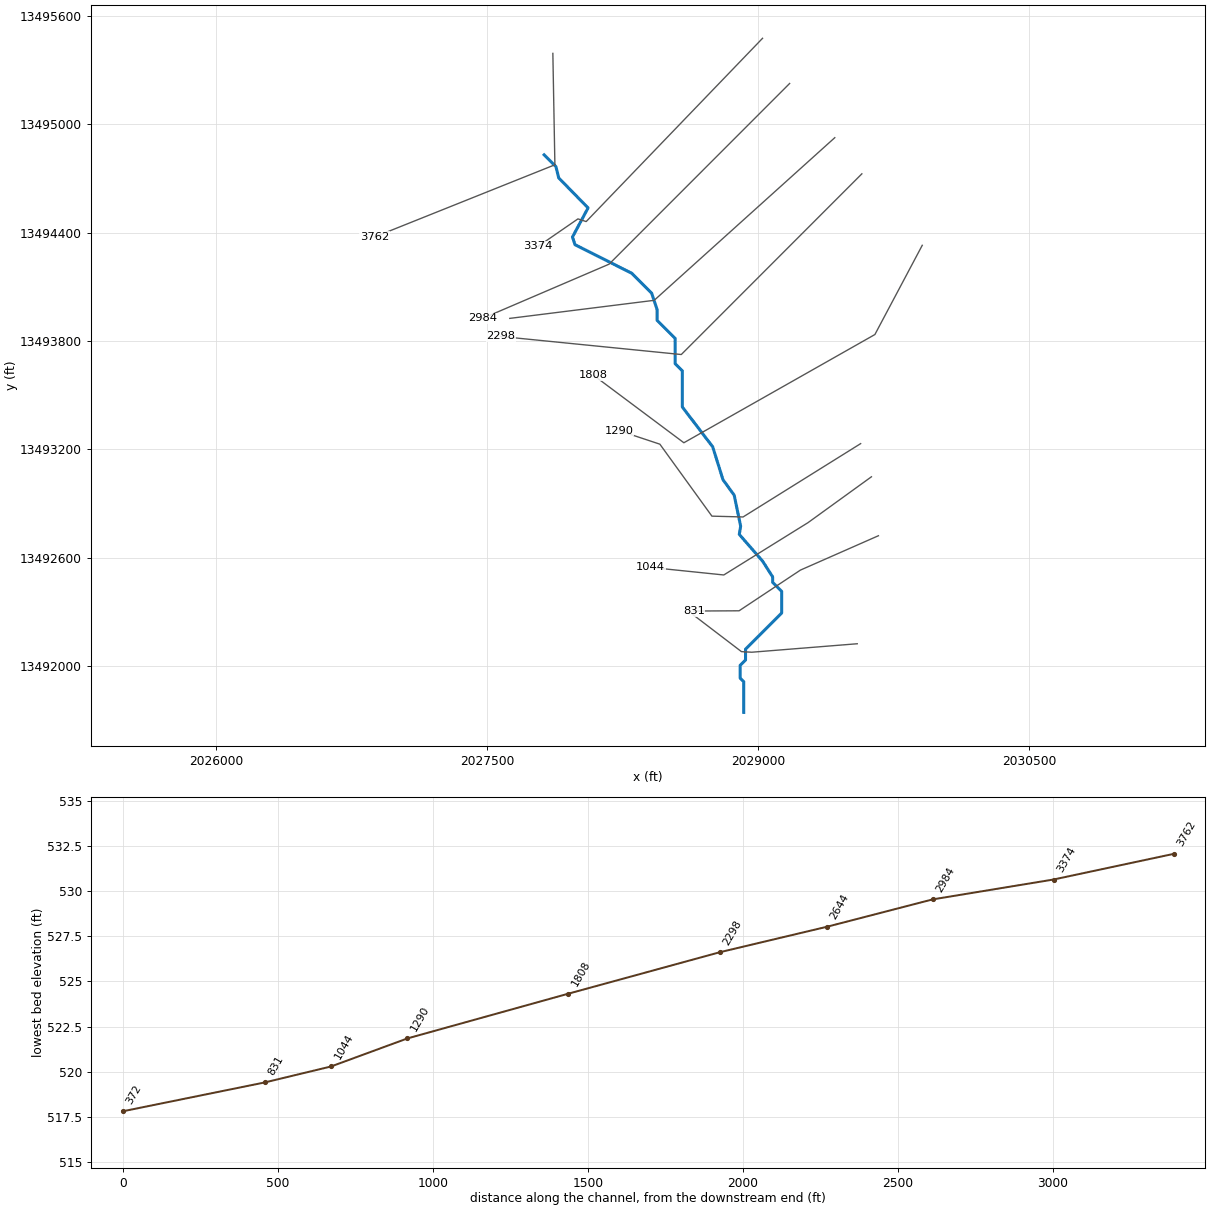
--- UNT 197 SanMiguel Cr Watershed.prj (project) ---

Proj Title=UNT 197 SanMiguel Cr Watershed Base Level Engineering
Current Plan=p01
Default Exp/Contr=0.3,0.1
English Units
Geom File=g01
Flow File=f01
Plan File=p01
Y Axis Title=Elevation
X Axis Title(PF)=Main Channel Distance
X Axis Title(XS)=Station
BEGIN DESCRIPTION:
UNT 197 SanMiguel Cr Watershed
END DESCRIPTION:
DSS File=dss
DSS Export Rating Curves= 0
DSS Export Rating Curve Sorted= 0
DSS Export Volume Flow Curves= 0
DXF OffsetX= 0
DXF OffsetY= 0
DXF ScaleX= 1
DXF ScaleY= 10

--- UNT 197 SanMiguel Cr Watershed.p01 (plan) ---

Plan Title=Multiple Run
Program Version=5.05
Geom File=g01
Subcritical Flow
K Sum by GR= 0
Std Step Tol= 0.01
Critical Tol= 0.01
Num of Std Step Trials= 20
Max Error Tol= 0.3
Flow Tol Ratio= 0.001
Split Flow NTrial= 30
Split Flow Tol= 0.02
Split Flow Ratio= 0.02
Log Output Level= 0
Friction Slope Method= 1
Unsteady Friction Slope Method= 2
Unsteady Bridges Friction Slope Method= 1
Parabolic Critical Depth
Global Vel Dist= 1 , 1 , 1
Global Log Level= 0
CheckData=True
Encroach Param=-1 ,0,0, 0
BEGIN DESCRIPTION:
Multiple Run
END DESCRIPTION:
Computation Interval=1MIN
Output Interval=1HOUR
Instantaneous Interval=1HOUR
Mapping Interval=1HOUR
Computation Time Step Use Courant=        0
Computation Time Step Use Time Series=    0
Computation Time Step Count To Double=0
Computation Time Step Max Doubling=0
Computation Time Step Max Halving=0
Computation Time Step Residence Courant=0
Run HTab= 0
Run UNet= 0
Run Sediment= 0
Run PostProcess= 0
Run WQNet= 0
Run RASMapper= 0
UNET Theta= 1
UNET Theta Warmup= 1
UNET ZTol= 0.02
UNET ZSATol= 0.02
UNET MxIter= 20
UNET Max Iter WO Improvement= 0
UNET MaxInSteps= 0
UNET DtIC= 0
UNET DtMin= 0
UNET MaxCRTS= 20
UNET WFStab= 2
UNET SFStab= 1
UNET WFX= 1
UNET SFX= 1
UNET 1D Methodology=Finite Difference
UNET DSS MLevel= 4
UNET Pardiso=0
UNET DZMax Abort= 100
UNET Use Existing IB Tables=-1
UNET Froude Reduction=False
UNET Froude Limit= 0.8
UNET Froude Power= 4
UNET D1 Cores= 0
UNET D2 Coriolis=0
UNET D2 Cores= 0
UNET D2 Theta= 1
UNET D2 Theta Warmup= 1
UNET D2 Z Tol= 0.01
UNET D2 Volume Tol= 0.01
UNET D2 Max Iterations= 20
UNET D2 Equation= 0
UNET D2 RampUpFraction=0.1
UNET D2 TimeSlices= 1
UNET D2 BCVolumeCheck=0
UNET D1D2 MaxIter= 0
UNET D1D2 ZTol=0.01
UNET D1D2 QTol=0.1
UNET D1D2 MinQTol=1
DSS File=dss
Write IC File= 0
Write IC File at Fixed DateTime=0
Write IC File at Sim End=0
Echo Input=False
Echo Parameters=False
Echo Output=False
Write Detailed= 0
HDF Write Warmup=0
HDF Write Time Slices=0
HDF Flush=0
HDF Face Node Velocities=0
HDF Compression= 1
HDF Chunk Size= 1
HDF Spatial Parts= 1
HDF Use Max Rows=0
HDF Fixed Rows= 1
Calibration Method= 0
Calibration Iterations= 20
Calibration Max Change=0.05
Calibration Tolerance=0.2
Calibration Maximum=1.5
Calibration Minimum=0.5
Calibration Optimization Method= 1
WQ AD Non Conservative
WQ ULTIMATE=-1
WQ Max Comp Step=1HOUR
WQ Output Interval=15MIN
WQ Output Selected Increments= 0
WQ Output face flow=0
WQ Output face velocity=0
WQ Output face area=0
WQ Output face dispersion=0
WQ Output cell volume=0
WQ Output cell surface area=0
WQ Output cell continuity=0
WQ Output cumulative cell continuity=0
WQ Output face conc=0
WQ Output face dconc_dx=0
WQ Output face courant=0
WQ Output face peclet=0
WQ Output face adv mass=0
WQ Output face disp mass=0
WQ Output cell mass=0
WQ Output cell source sink temp=0
WQ Output nsm pathways=0
WQ Output nsm derived pathways=0
WQ Output MaxMinRange=-1
WQ Daily Max Min Mean=-1
WQ Daily Range=0
WQ Daily Time=0
WQ Create Restart=0
WQ Fixed Restart=0
WQ System Summary=0
WQ Write To DSS=0
WQ Use Fixed Temperature=0
Sorting and Armoring Iterations= 10
XS Update Threshold= 0.02
Bed Roughness Predictor= 0
Hydraulics Update Threshold= 0.02
Energy Slope Method= 1
Volume Change Method= 1
Sediment Retention Method= 0
XS Weighting Method= 0
Number of US Weighted Cross Sections= 1
Number of DS Weighted Cross Sections= 1
Upstream XS Weight=0
Main XS Weight=1
Downstream XS Weight=0
Number of DS XS's Weighted with US Boundary= 1
Upstream Boundary Weight= 1
Weight of XSs Associated with US Boundary= 0
Number of US XS's Weighted with DS Boundary= 1
Downstream Boundary Weight= 0.5
Weight of XSs Associated with DS Boundary= 0.5
Percentile Method= 0
Sediment Output Level= 3
Mass or Volume Output= 0
Output Increment Type= 1
Profile and TS Output Increment= 1
XS Output Flag= 0
XS Output Increment= 10
Write Gradation File= 0
Read Gradation Hotstart= 0
Write HDF5 File= 1
Write Binary Output= 1
Write DSS Sediment File= 0
SV Curve= 0
Specific Gage Flag= 0

--- UNT 197 SanMiguel Cr Watershed.f01 (steady flow) ---

Flow Title=Multiple
Number of Profiles=7
Profile Names=10-year,25-year,50-year,1pct_min,100-year,1pct_plu,500-year
River Rch & RM= UNT 197 SanMigue,Reach-1,3762
     168     228     277     168     336     670     498
River Rch & RM= UNT 197 SanMigue,Reach-1,3374
     218     300     368     225     448     895     677
Boundary for River Rch & Prof#=UNT 197 SanMigue,Reach-1,1
Up Type=0
Dn Type=3
Dn Slope=0.005
Boundary for River Rch & Prof#=UNT 197 SanMigue,Reach-1,2
Up Type=0
Dn Type=3
Dn Slope=0.005
Boundary for River Rch & Prof#=UNT 197 SanMigue,Reach-1,3
Up Type=0
Dn Type=3
Dn Slope=0.005
Boundary for River Rch & Prof#=UNT 197 SanMigue,Reach-1,4
Up Type=0
Dn Type=3
Dn Slope=0.005
Boundary for River Rch & Prof#=UNT 197 SanMigue,Reach-1,5
Up Type=0
Dn Type=3
Dn Slope=0.005
Boundary for River Rch & Prof#=UNT 197 SanMigue,Reach-1,6
Up Type=0
Dn Type=3
Dn Slope=0.005
Boundary for River Rch & Prof#=UNT 197 SanMigue,Reach-1,7
Up Type=0
Dn Type=3
Dn Slope=0.005

--- UNT 197 SanMiguel Cr Watershed.g01 (geometry) ---

Geom Title=Existing Conditions
Program Version=5.05

River Reach=UNT 197 SanMigue,Reach-1
Reach XY= 30
      2027815.64      13494829.7       2027880.8     13494764.54
      2027896.23     13494702.27      2028058.73      13494536.3
      2027972.44     13494375.43      2027986.33      13494332.9
       2028300.8     13494174.54       2028410.8     13494064.54
       2028440.8     13493974.54       2028440.8     13493914.54
       2028540.8     13493814.54       2028540.8     13493674.54
       2028580.8     13493634.54       2028580.8     13493434.54
      2028748.92     13493214.23      2028805.86     13493032.29
      2028867.89     13492946.71       2028903.7     13492775.27
       2028896.1      13492729.7      2029025.31     13492581.59
       2029080.8     13492494.54       2029080.8     13492464.54
       2029130.8     13492414.54       2029130.8     13492294.54
       2028930.8     13492094.54       2028930.8     13492034.54
       2028900.8     13492004.54       2028900.8     13491934.54
       2028920.8     13491914.54       2028920.8     13491744.54

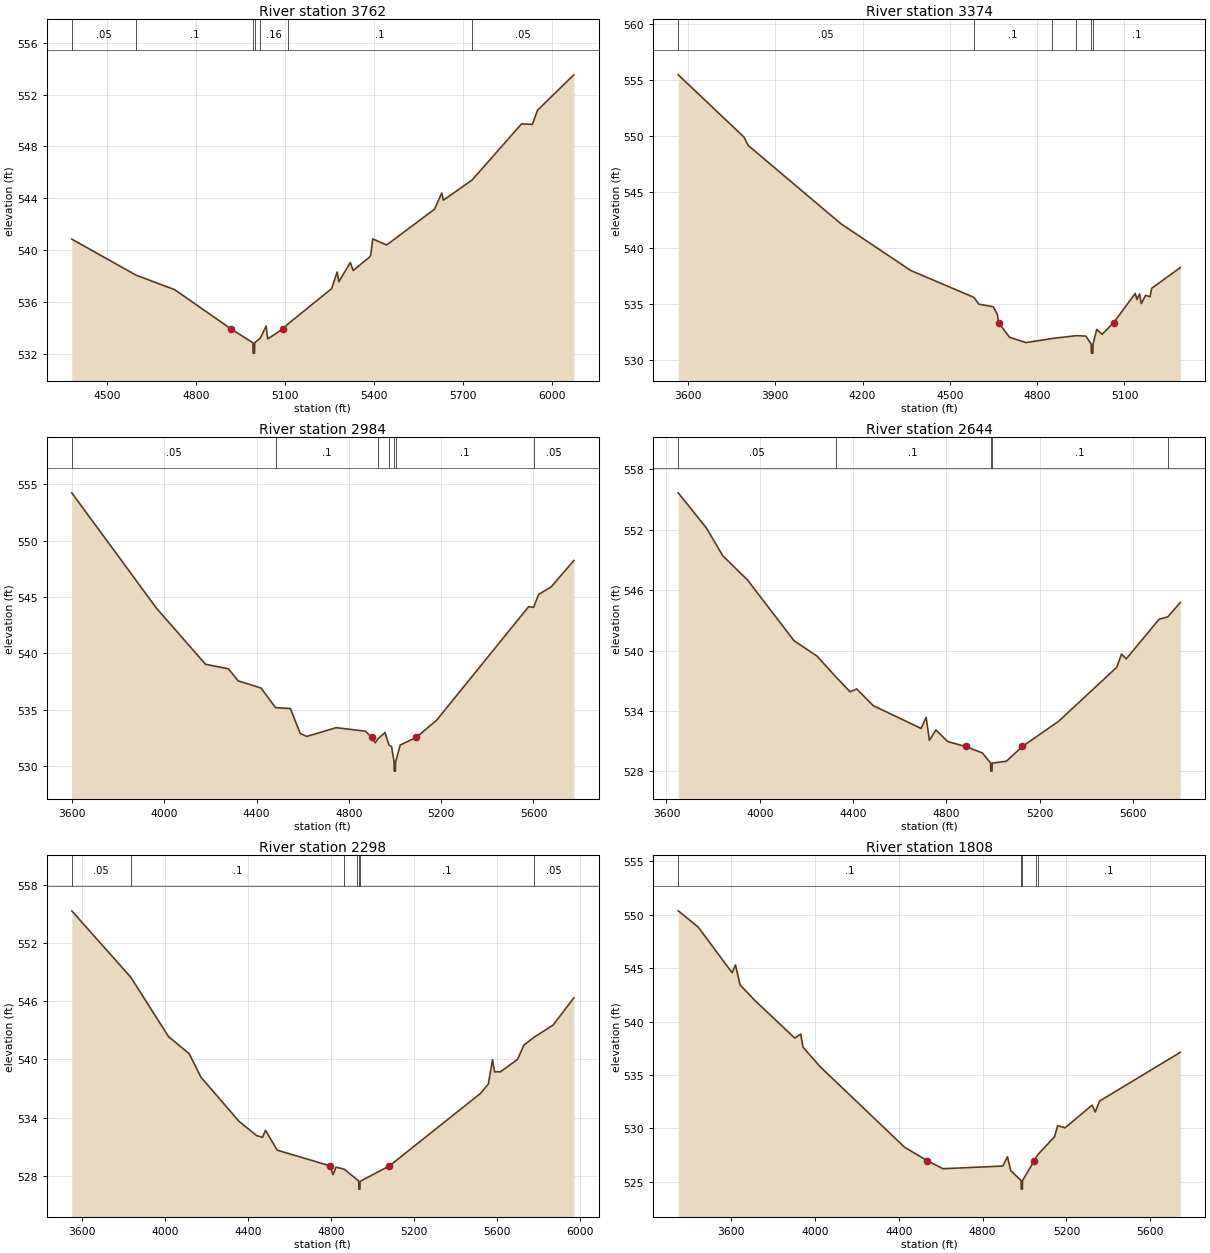
Type RM Length L Ch R = 1 ,3762    ,388,388,388
BEGIN DESCRIPTION:
UNT 197 SanMiguel Cr Watershed 10.0
END DESCRIPTION:
XS GIS Cut Line= 3
      2027863.73     13495391.51        2027875.       13494775.
      2026875.04     13494375.02
#Sta/Elev= 30
  4379.8  540.85  4596.1  538.08  4727.1  536.95  4917.4 533.921  4990.9  532.86
  4991.4  532.06  4996.4  532.06  4996.9  532.86  5015.7  533.22  5035.5  534.15
  5040.8  533.16 5092.25533.9211  5109.2  534.31  5256.2  537.03  5275.1  538.32
  5280.5  537.56  5319.5  539.05  5328.9  538.43  5382.8  539.44  5388.2  539.61
  5394.9  540.87    5442   540.4  5603.6  543.16  5627.8  544.41  5633.2  543.85
  5730.2  545.41  5897.1  549.74  5933.4   549.7  5950.9  550.79  6073.4  553.52
#Mann= 7 ,-1 , 0
  4379.8     .05       0  4596.1      .1       0  4990.9     .07       0
  4996.9      .1       0  5015.7     .16       0  5109.2      .1       0
  5730.2     .05       0
Bank Sta=4917.4,5092.25
XS Rating Curve= 0 ,0
Exp/Cntr=0.3,0.1

Type RM Length L Ch R = 1 ,3374    ,390,390,390
BEGIN DESCRIPTION:
UNT 197 SanMiguel Cr Watershed 9.0
END DESCRIPTION:
XS GIS Cut Line= 4
      2029024.98     13495474.98      2028048.23     13494460.73
      2028002.66     13494475.58      2027781.21     13494322.92
#Sta/Elev= 30
  3566.9  555.47  3793.1  549.91  3807.3  549.17  4125.5  542.19  4366.1  538.01
  4583.1  535.61  4599.4  535.01  4649.1  534.78  4663.2  534.11 4667.77 533.355
  4705.4  532.05    4762  531.58  4852.6  531.95  4934.7   532.2  4967.3  532.16
  4985.9  531.44  4986.4  530.64  4991.5  530.64    4992  531.44  5004.8  532.76
  5022.9  532.32 5062.85533.3555    5137  535.97    5143  535.43  5151.9  535.92
  5157.9  535.06  5172.8   535.8  5187.7  535.67  5193.8  536.43  5291.9  538.27
#Mann= 6 ,-1 , 0
  3566.9     .05       0  4583.1      .1       0  4852.6     .16       0
  4934.7      .1       0  4985.9     .07       0    4992      .1       0
Bank Sta=4667.77,5062.85
XS Rating Curve= 0 ,0
Exp/Cntr=0.3,0.1

Type RM Length L Ch R = 1 ,2984    ,340,340,340
BEGIN DESCRIPTION:
UNT 197 SanMiguel Cr Watershed 8.0
END DESCRIPTION:
XS GIS Cut Line= 3
      2029174.98     13495224.98        2028175.       13494225.
      2027474.97     13493924.99
#Sta/Elev= 30
  3599.3  554.26    3967     544  4179.1  539.03  4278.1  538.63  4320.5  537.56
  4419.5  536.92  4482.5  535.18  4546.8   535.1  4589.2  532.89  4617.5  532.62
  4744.8   533.4  4872.1  533.09  4898.8532.5294  4914.5  532.06  4925.1  532.39
  4956.9  532.97  4974.1  531.85  4985.2  531.73  4996.3  530.34  4996.8  529.54
  5001.9  529.54  5002.4  530.34  5022.6  531.86 5091.78532.5294  5180.3  534.06
  5579.2  544.15  5600.6  544.09  5622.8  545.24  5677.1  545.91  5775.1  548.25
#Mann= 7 ,-1 , 0
  3599.3     .05       0  4482.5      .1       0  4925.1     .16       0
  4974.1      .1       0  4996.3     .07       0  5002.4      .1       0
  5600.6     .05       0
Bank Sta=4898.8,5091.78
XS Rating Curve= 0 ,0
Exp/Cntr=0.3,0.1

Type RM Length L Ch R = 1 ,2644    ,346,346,346
BEGIN DESCRIPTION:
UNT 197 SanMiguel Cr Watershed 7.0
END DESCRIPTION:
XS GIS Cut Line= 3
      2029424.97     13494924.97        2028425.       13494025.
      2027625.05     13493925.01
#Sta/Elev= 30
  3650.5  555.67  3771.2  552.18  3841.4  549.42  3947.6  547.01  4146.4  540.99
    4245  539.46  4325.6   537.4    4387  535.91  4415.4  536.19  4485.7  534.54
  4691.2  532.27  4712.9  533.38  4726.7  531.09  4754.8  532.12  4804.9  530.97
 4881.55530.4788  4953.6  529.84  4989.4  528.83  4989.9  528.03  4995.1  528.03
  4995.6  528.83  5056.3  529.01 5125.47530.4787  5280.5  532.98  5529.9  538.35
  5550.1  539.66  5570.3  539.18  5711.3  543.12  5748.3  543.35    5802  544.78
#Mann= 5 ,-1 , 0
  3650.5     .05       0  4325.6      .1       0  4989.4     .07       0
  4995.6      .1       0  5748.3     .05       0
Bank Sta=4881.55,5125.47
XS Rating Curve= 0 ,0
Exp/Cntr=0.3,0.1

Type RM Length L Ch R = 1 ,2298    ,490,490,490
BEGIN DESCRIPTION:
UNT 197 SanMiguel Cr Watershed 6.0
END DESCRIPTION:
XS GIS Cut Line= 3
      2029575.01     13494725.01        2028575.       13493725.
      2027575.02       13493825.
#Sta/Elev= 30
  3551.4  555.34  3835.6  548.49  4018.1  542.35  4117.1   540.6  4173.7  538.18
  4357.5  533.61  4442.4  532.14  4470.7  531.97  4484.8  532.69  4541.4  530.64
 4796.36529.0195  4810.1  528.11  4824.2  528.89  4864.7  528.67  4927.8  527.57
  4934.2  527.42  4934.7  526.62  4939.9  526.62  4940.4  527.42 5081.98529.0198
  5520.9   536.5  5558.6  537.47  5578.7  539.97  5588.7  538.73  5616.4  538.72
  5699.3  540.01  5729.4  541.47  5779.7  542.31  5870.1  543.54  5970.6  546.36
#Mann= 7 ,-1 , 0
  3551.4     .05       0  3835.6      .1       0  4864.7     .12       0
  4927.8      .1       0  4934.2     .07       0  4940.4      .1       0
  5779.7     .05       0
Bank Sta=4796.36,5081.98
XS Rating Curve= 0 ,0
Exp/Cntr=0.3,0.1

Type RM Length L Ch R = 1 ,1808    ,518,518,518
BEGIN DESCRIPTION:
UNT 197 SanMiguel Cr Watershed 5.0
END DESCRIPTION:
XS GIS Cut Line= 4
      2029909.43     13494329.42      2029647.09      13493835.6
      2028589.27     13493236.75      2028089.71     13493609.76
#Sta/Elev= 30
    3346  550.36  3441.6  548.84  3603.2  544.57  3619.5   545.3  3641.5  543.43
  3713.4  541.95  3902.7  538.45  3930.6  538.84  3942.3   537.6  4023.1  535.79
  4427.2  528.24    4535526.9872  4610.5  526.23  4896.2  526.48  4918.8  527.35
  4933.8  526.06  4984.1  525.12  4984.6  524.32  4989.8  524.32  4990.3  525.12
 5047.07526.9874  5056.5  527.34  5064.8  527.57  5143.8  529.23  5158.4  530.26
  5193.9  530.06  5323.1  532.18  5337.7  531.54  5358.6  532.56  5744.2  537.12
#Mann= 5 ,-1 , 0
    3346      .1       0  4984.1     .07       0  4990.3      .1       0
  5056.5     .12       0  5064.8      .1       0
Bank Sta=4535,5047.07
XS Rating Curve= 0 ,0
Exp/Cntr=0.3,0.1

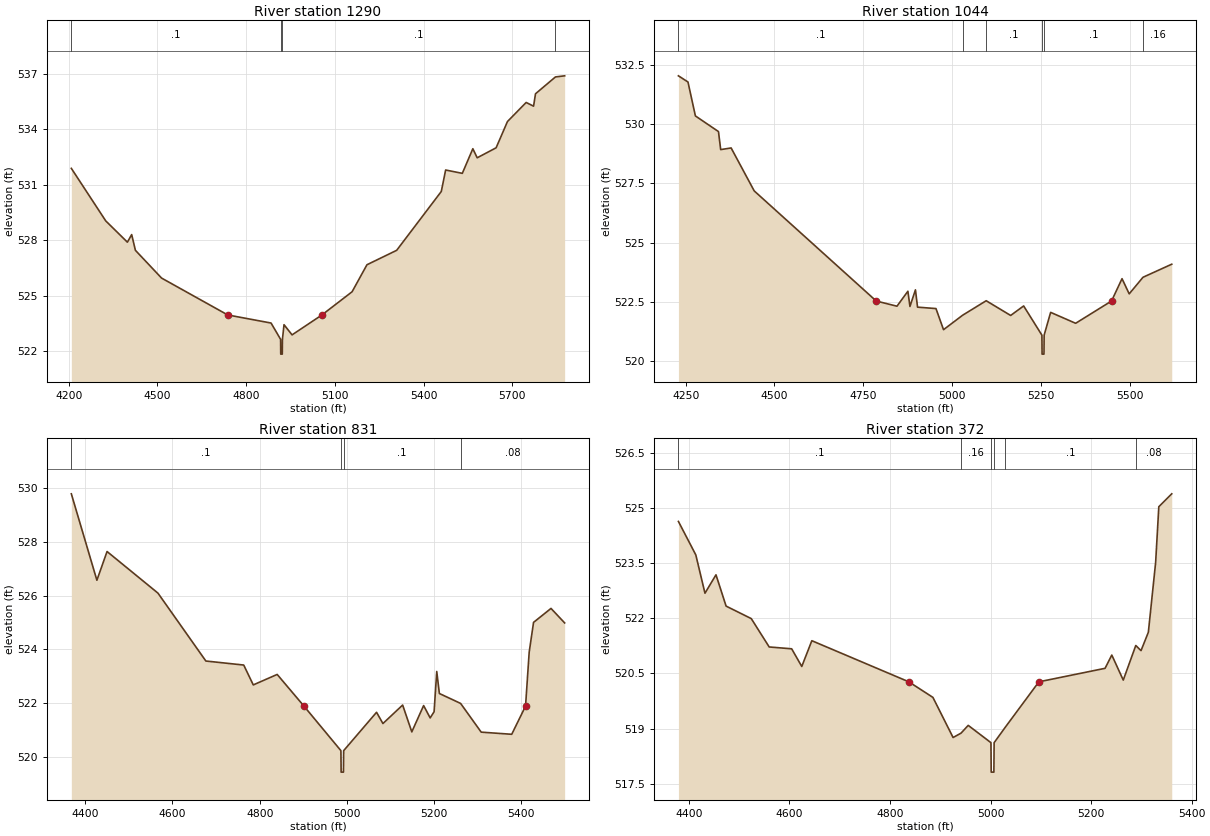
Type RM Length L Ch R = 1 ,1290    ,246,246,246
BEGIN DESCRIPTION:
UNT 197 SanMiguel Cr Watershed 4.0
END DESCRIPTION:
XS GIS Cut Line= 5
      2029568.22     13493231.92      2028917.19     13492826.11
      2028744.57     13492830.62      2028456.34     13493228.87
      2028231.45     13493303.54
#Sta/Elev= 30
  4208.6  531.89    4325  529.05  4398.2   527.9  4412.7  528.31  4425.3  527.46
  4513.8  525.96 4737.58523.9666  4884.1  523.53  4916.3  522.65  4916.8  521.85
    4922  521.85  4922.5  522.65  4927.9  523.44  4955.1  522.89 5056.07523.9665
  5158.1  525.22  5208.4  526.68  5308.9  527.46  5459.8  530.64  5474.5   531.8
  5530.9  531.62  5566.5  532.95  5581.2  532.46  5645.2     533  5683.6  534.42
  5746.8  535.45  5771.9  535.25  5778.4  535.92  5845.9  536.83    5877  536.89
#Mann= 4 ,-1 , 0
  4208.6      .1       0  4916.3     .07       0  4922.5      .1       0
  5845.9     .05       0
Bank Sta=4737.58,5056.07
XS Rating Curve= 0 ,0
Exp/Cntr=0.3,0.1

Type RM Length L Ch R = 1 ,1044    ,213,213,213
BEGIN DESCRIPTION:
UNT 197 SanMiguel Cr Watershed 3.0
END DESCRIPTION:
XS GIS Cut Line= 4
      2029628.05      13493048.5      2029277.36     13492795.03
      2028810.34     13492505.09      2028405.78     13492546.77
#Sta/Elev= 30
  4229.5  532.03  4256.4  531.77  4277.3  530.34  4342.3  529.68  4348.5  528.92
  4377.9  528.99  4442.9  527.18 4786.55522.5383  4844.9  522.32  4875.6  522.95
  4881.5  522.31  4896.9  523.01  4902.8  522.28  4954.7  522.22    4976  521.33
  5029.8  521.94  5096.1  522.55    5165  521.93  5201.6  522.33    5253   521.1
  5253.5   520.3  5258.8   520.3  5259.3   521.1  5277.6  522.06    5348   521.6
 5449.09522.5386  5478.6  523.48  5498.8  522.84  5537.7  523.54  5618.6  524.09
#Mann= 6 ,-1 , 0
  4229.5      .1       0  5029.8     .05       0  5096.1      .1       0
    5253     .07       0  5259.3      .1       0  5537.7     .16       0
Bank Sta=4786.55,5449.09
XS Rating Curve= 0 ,0
Exp/Cntr=0.3,0.1

Type RM Length L Ch R = 1 ,831     ,459,459,459
BEGIN DESCRIPTION:
UNT 197 SanMiguel Cr Watershed 2.0
END DESCRIPTION:
XS GIS Cut Line= 4
      2029666.74     13492722.25      2029234.84     13492532.13
        2028895.     13492306.87      2028643.72     13492305.56
#Sta/Elev= 30
  4368.2  529.79  4426.8  526.57  4450.1  527.64  4566.8  526.09  4676.6  523.56
  4763.4  523.41  4785.3  522.67  4840.1  523.06 4901.45521.8808  4986.2  520.22
  4986.7  519.42    4992  519.42  4992.5  520.22  5067.9  521.65  5082.5  521.23
  5127.7  521.92  5148.7  520.92  5175.8   521.9  5190.8  521.44  5199.8  521.67
  5205.9  523.17  5211.9  522.35  5260.6  521.98  5307.8  520.91  5377.8  520.83
 5409.46521.8801  5417.8  523.89  5427.8     525  5467.8  525.52  5499.1  524.98
#Mann= 4 ,-1 , 0
  4368.2      .1       0  4986.2     .07       0  4992.5      .1       0
  5260.6     .08       0
Bank Sta=4901.45,5409.46
XS Rating Curve= 0 ,0
Exp/Cntr=0.3,0.1

Type RM Length L Ch R = 1 ,372     ,0,0,0
BEGIN DESCRIPTION:
UNT 197 SanMiguel Cr Watershed 1.0
END DESCRIPTION:
XS GIS Cut Line= 4
      2029549.46     13492124.48      2028965.72     13492077.61
      2028908.21     13492080.86      2028639.56      13492285.6
#Sta/Elev= 30
  4379.4  524.63    4414  523.72  4432.2  522.68  4454.1  523.18  4474.2  522.33
  4524.3  521.99  4559.9  521.22  4604.6  521.17  4624.7  520.69  4644.7  521.39
 4837.69520.2726  4885.5  519.85  4925.6  518.76  4941.5  518.88  4955.7  519.09
  5000.9  518.62  5001.4  517.82  5006.7  517.82  5007.2  518.62  5029.4  519.04
 5096.18520.2728  5227.8  520.64  5241.2     521    5264  520.32  5288.9  521.26
  5299.3  521.12  5313.9  521.62  5328.4  523.52  5334.7  525.03  5360.4  525.38
#Mann= 6 ,-1 , 0
  4379.4      .1       0  4941.5     .16       0  5000.9     .07       0
  5007.2     .16       0  5029.4      .1       0  5288.9     .08       0
Bank Sta=4837.69,5096.18
XS Rating Curve= 0 ,0
Exp/Cntr=0.3,0.1
LCMann Table=0

Chan Stop Cuts=-1
Use User Specified Reach Order=0
Composite Channel Slope=5