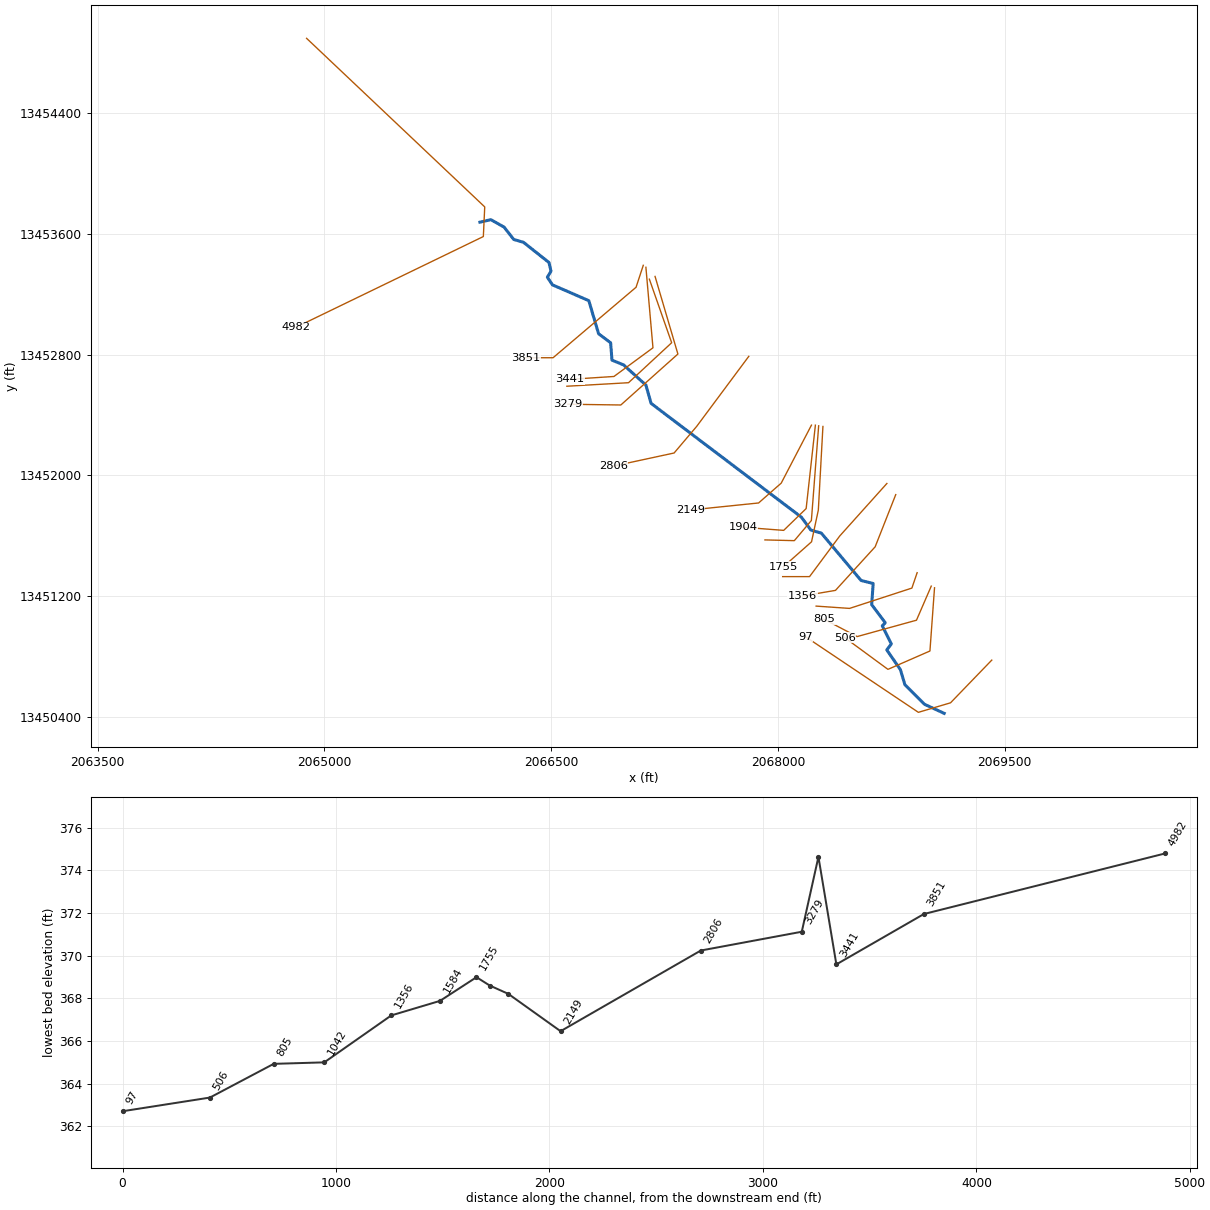
--- UNT 21 in Lagunillas Cr Wtrshd.prj (project) ---

Proj Title=UNT 21 in Lagunillas Cr Wtrshd Base Level Engineering
Current Plan=p01
Default Exp/Contr=0.3,0.1
English Units
Geom File=g01
Flow File=f01
Plan File=p01
BEGIN DESCRIPTION:
UNT 21 in Lagunillas Cr Wtrshd
END DESCRIPTION:

--- UNT 21 in Lagunillas Cr Wtrshd.p01 (plan) ---

Plan Title=Multiple Run
Short Identifier=Multiple
Geom File=g01
Flow File=f01
Subcritical Flow
K Sum by GR= 0
Std Step Tol= 0.01
Critical Tol= 0.01
Num of Std Step Trials= 20
Max Error Tol= 0.3
Flow Tol Ratio= 0.001
Split Flow NTrial= 30
Split Flow Tol= 0.02
Split Flow Ratio= 0.02
Log Output Level= 0
Friction Slope Method= 1
Unsteady Friction Slope Method= 2
Unsteady Bridges Friction Slope Method= 1
Parabolic Critical Depth
Global Vel Dist=  1 , 1 , 1
Global Log Level= 0
CheckData=True
Encroach Param= -1, 0, 0, 0
BEGIN DESCRIPTION:
Multiple Run
END DESCRIPTION:

--- UNT 21 in Lagunillas Cr Wtrshd.f01 (steady flow) ---

Flow Title=Multiple
Number of Profiles=7
Profile Names=10-year,25-year,50-year,1pct_min,100-year,1pct_plu,500-year
River Rch & RM= UNT 21 in Laguni,Reach-1,4982
     172     233     282     170     340     679     502
River Rch & RM= UNT 21 in Laguni,Reach-1,1584
     200     273     332     202     403     804     601
Boundary for River Rch & Prof#=UNT 21 in Laguni,Reach-1,1
Up Type=0
Dn Type=3
Dn Slope=0.005
Boundary for River Rch & Prof#=UNT 21 in Laguni,Reach-1,2
Up Type=0
Dn Type=3
Dn Slope=0.005
Boundary for River Rch & Prof#=UNT 21 in Laguni,Reach-1,3
Up Type=0
Dn Type=3
Dn Slope=0.005
Boundary for River Rch & Prof#=UNT 21 in Laguni,Reach-1,4
Up Type=0
Dn Type=3
Dn Slope=0.005
Boundary for River Rch & Prof#=UNT 21 in Laguni,Reach-1,5
Up Type=0
Dn Type=3
Dn Slope=0.005
Boundary for River Rch & Prof#=UNT 21 in Laguni,Reach-1,6
Up Type=0
Dn Type=3
Dn Slope=0.005
Boundary for River Rch & Prof#=UNT 21 in Laguni,Reach-1,7
Up Type=0
Dn Type=3
Dn Slope=0.005

--- UNT 21 in Lagunillas Cr Wtrshd.g01 (geometry) ---

Geom Title=Existing Conditions

River Reach=UNT 21 in Laguni,Reach-1
Reach XY= 30
      2066029.01     13453677.50      2066101.23     13453694.17
      2066188.73     13453644.86      2066252.62     13453562.92
      2066317.09     13453544.28      2066485.84     13453410.26
      2066499.03     13453353.31      2066474.94     13453312.89
      2066508.79     13453262.37      2066749.42     13453157.69
      2066814.00     13452938.42      2066893.69     13452878.52
      2066902.54     13452763.94      2066978.58     13452732.69
      2067127.02     13452598.83      2067161.40     13452477.48
      2068155.15     13451724.35      2068218.69     13451638.42
      2068287.96     13451618.10      2068550.80     13451304.54
      2068630.80     13451284.54      2068620.80     13451144.54
      2068710.80     13451024.54      2068690.80     13451004.54
      2068750.80     13450884.54      2068720.80     13450844.54
      2068810.80     13450714.54      2068840.80     13450614.54
      2068970.80     13450484.54      2069100.80     13450424.54

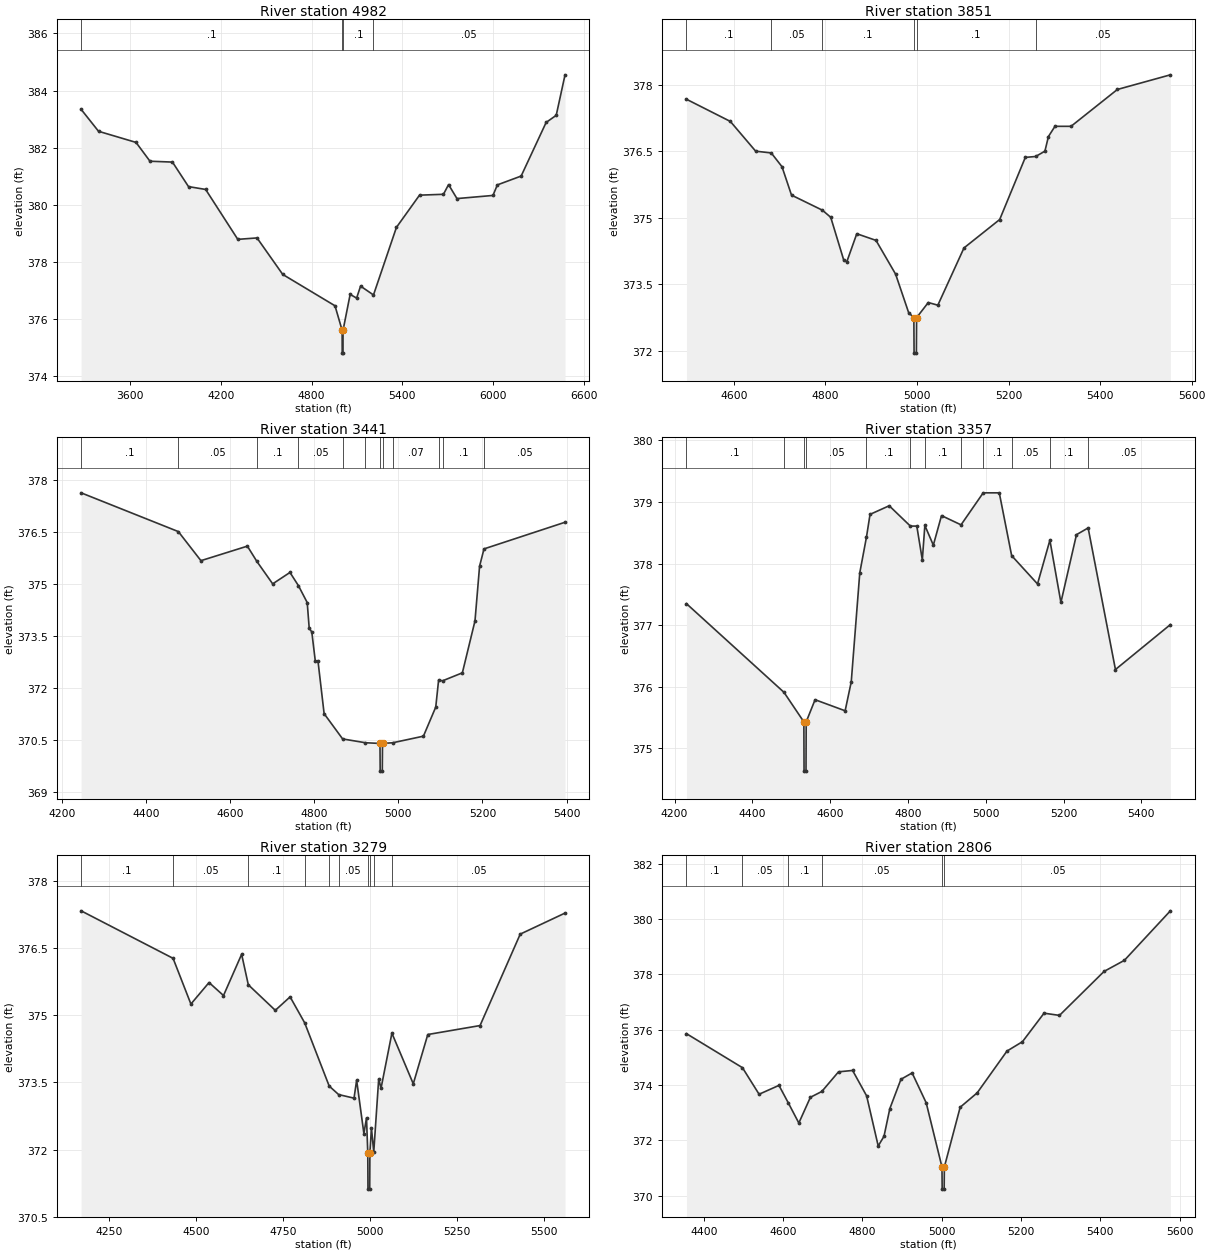
Type RM Length L Ch R = 1,4982,1131,1131,1131
BEGIN DESCRIPTION:
UNT 21 in Lagunillas Cr Wtrshd 13.0
END DESCRIPTION:
XS GIS Cut Line= 4
      2064882.07     13454895.04      2066060.68     13453778.68
      2066051.47     13453582.39      2064812.64     13452981.85
#Sta/Elev= 30
  3277.7  383.34  3392.8  382.57  3640.4  382.18  3732.6  381.52  3881.1  381.49
  3987.1  380.63  4100.3  380.53  4312.7  378.78  4439.7  378.83  4609.6  377.55
  4954.8  376.45  5001.9  375.59  5002.4  374.79  5007.4  374.79  5007.9  375.59
  5054.9  376.85  5097.6  376.72  5123.7  377.14  5209.0  376.83  5360.6  379.20
  5513.1  380.33  5671.1  380.36  5704.9  380.70  5760.4  380.21  5998.3  380.32
  6027.2  380.69  6184.4  381.00  6349.4  382.88  6416.1  383.13  6474.3  384.55
#Mann=4,-1,0
  3277.7     0.1       0  5001.9    0.07       0  5007.9     0.1       0
  5209.0    0.05       0
Bank Sta=5001.9,5007.9
Exp/Cntr=0.3,0.1

Type RM Length L Ch R = 1,3851,410,410,410
BEGIN DESCRIPTION:
Mapping XS 355bf677
END DESCRIPTION:
XS GIS Cut Line= 4
      2067109.64     13453391.89      2067061.89     13453246.45
      2066512.84     13452779.87      2066329.23     13452779.87
#Sta/Elev= 30
  4496.3  377.67  4592.2  377.17  4647.5  376.50  4681.6  376.46  4705.0  376.15
  4725.8  375.51  4793.3  375.17  4811.5  375.01  4840.1  374.04  4846.7  374.01
  4868.4  374.64  4910.4  374.49  4953.2  373.73  4981.8  372.86  4993.1  372.75
  4993.6  371.95  4998.6  371.95  4999.1  372.75  5024.6  373.09  5045.5  373.03
  5102.6  374.32  5180.6  374.96  5236.6  376.36  5259.1  376.38  5279.4  376.50
  5287.1  376.83  5301.4  377.06  5336.5  377.06  5437.7  377.89  5553.5  378.22
#Mann=6,-1,0
  4496.3     0.1       0  4681.6    0.05       0  4793.3     0.1       0
  4993.1    0.07       0  4999.1     0.1       0  5259.1    0.05       0
Bank Sta=4993.1,4999.1
Exp/Cntr=0.3,0.1

Type RM Length L Ch R = 1,3441,84,84,84
BEGIN DESCRIPTION:
Mapping XS 6ab21a86
END DESCRIPTION:
XS GIS Cut Line= 4
      2067126.99     13453378.79      2067173.74     13452845.52
      2066915.50     13452655.64      2066621.36     13452636.65
#Sta/Elev= 30
  4245.7  377.63  4476.9  376.51  4530.6  375.67  4641.0  376.09  4663.5  375.65
  4701.2  375.00  4742.3  375.33  4762.3  374.95  4783.3  374.46  4788.0  373.72
  4794.2  373.61  4802.6  372.76  4808.8  372.78  4823.5  371.25  4867.5  370.52
  4921.8  370.41  4956.3  370.39  4956.8  369.59  4961.8  369.59  4962.3  370.39
  4986.8  370.41  5059.6  370.60  5088.9  371.44  5095.7  372.22  5105.3  372.20
  5152.2  372.43  5182.2  373.93  5193.1  375.51  5203.6  376.01  5396.3  376.78
#Mann=12,-1,0
  4245.7     0.1       0  4476.9    0.05       0  4663.5     0.1       0
  4762.3    0.05       0  4867.5    0.07       0  4921.8    0.05       0
  4956.3    0.07       0  4962.3    0.05       0  4986.8    0.07       0
  5095.7    0.05       0  5105.3     0.1       0  5203.6    0.05       0
Bank Sta=4956.3,4962.3
Exp/Cntr=0.3,0.1

Type RM Length L Ch R = 1,3357,78,78,78
BEGIN DESCRIPTION:
Mapping XS 14d313d3
END DESCRIPTION:
XS GIS Cut Line= 4
      2067150.00     13453299.99      2067297.44     13452879.16
      2067012.07     13452614.40      2066604.01     13452591.07
#Sta/Elev= 30
  4230.5  377.35  4481.2  375.91  4532.3  375.43  4532.8  374.63  4537.8  374.63
  4538.3  375.43  4561.1  375.79  4638.4  375.61  4654.1  376.08  4676.0  377.85
  4693.2  378.43  4702.4  378.80  4751.7  378.94  4806.0  378.61  4822.6  378.61
  4836.8  378.06  4843.3  378.62  4865.1  378.30  4886.1  378.78  4936.3  378.63
  4993.3  379.15  5034.6  379.15  5066.4  378.13  5132.9  377.67  5164.7  378.38
  5193.0  377.37  5233.0  378.47  5263.0  378.58  5333.2  376.28  5474.4  377.01
#Mann=12,-1,0
  4230.5     0.1       0  4481.2    0.05       0  4532.3    0.07       0
  4538.3    0.05       0  4693.2     0.1       0  4806.0    0.05       0
  4843.3     0.1       0  4936.3    0.05       0  4993.3     0.1       0
  5066.4    0.05       0  5164.7     0.1       0  5263.0    0.05       0
Bank Sta=4532.3,4538.3
Exp/Cntr=0.3,0.1

Type RM Length L Ch R = 1,3279,473,473,473
BEGIN DESCRIPTION:
Mapping XS a645d962
END DESCRIPTION:
XS GIS Cut Line= 4
      2067187.62     13453318.21      2067338.67     13452804.29
      2066961.07     13452466.83      2066610.39     13452471.83
#Sta/Elev= 30
  4168.3  377.33  4433.0  376.27  4484.3  375.25  4536.5  375.73  4578.1  375.44
  4630.3  376.36  4649.5  375.68  4727.2  375.11  4769.8  375.41  4811.8  374.83
  4882.3  373.42  4909.5  373.23  4953.8  373.15  4961.3  373.55  4982.2  372.36
  4989.7  372.71  4993.4  371.92  4993.9  371.12  4998.9  371.12  4999.4  371.92
  5003.9  372.48  5010.6  371.95  5024.8  373.58  5031.5  373.37  5062.8  374.60
  5124.3  373.47  5166.1  374.57  5316.5  374.77  5432.1  376.81  5561.1  377.28
#Mann=10,-1,0
  4168.3     0.1       0  4433.0    0.05       0  4649.5     0.1       0
  4811.8    0.05       0  4882.3     0.1       0  4909.5    0.05       0
  4993.4    0.03       0  4999.4    0.05       0  5010.6     0.1       0
  5062.8    0.05       0
Bank Sta=4993.4,4999.4
Exp/Cntr=0.3,0.1

Type RM Length L Ch R = 1,2806,657,657,657
BEGIN DESCRIPTION:
Mapping XS 9c460e2c
END DESCRIPTION:
XS GIS Cut Line= 4
      2067807.83     13452789.07      2067463.46     13452325.78
      2067313.72     13452148.91      2066911.58     13452062.10
#Sta/Elev= 30
  4356.1  375.86  4497.3  374.63  4539.3  373.67  4589.4  373.99  4612.5  373.37
  4639.5  372.63  4668.7  373.56  4697.5  373.77  4739.6  374.48  4775.1  374.53
  4810.5  373.61  4839.7  371.80  4854.3  372.15  4869.0  373.15  4897.0  374.21
  4925.2  374.44  4960.7  373.36  5000.5  371.04  5001.0  370.24  5006.0  370.24
  5006.5  371.04  5046.4  373.20  5089.3  373.72  5164.4  375.23  5203.5  375.57
  5257.9  376.60  5296.8  376.52  5409.3  378.11  5460.5  378.51  5576.5  380.30
#Mann=6,-1,0
  4356.1     0.1       0  4497.3    0.05       0  4612.5     0.1       0
  4697.5    0.05       0  5000.5    0.03       0  5006.5    0.05       0
Bank Sta=5000.5,5006.5
Exp/Cntr=0.3,0.1

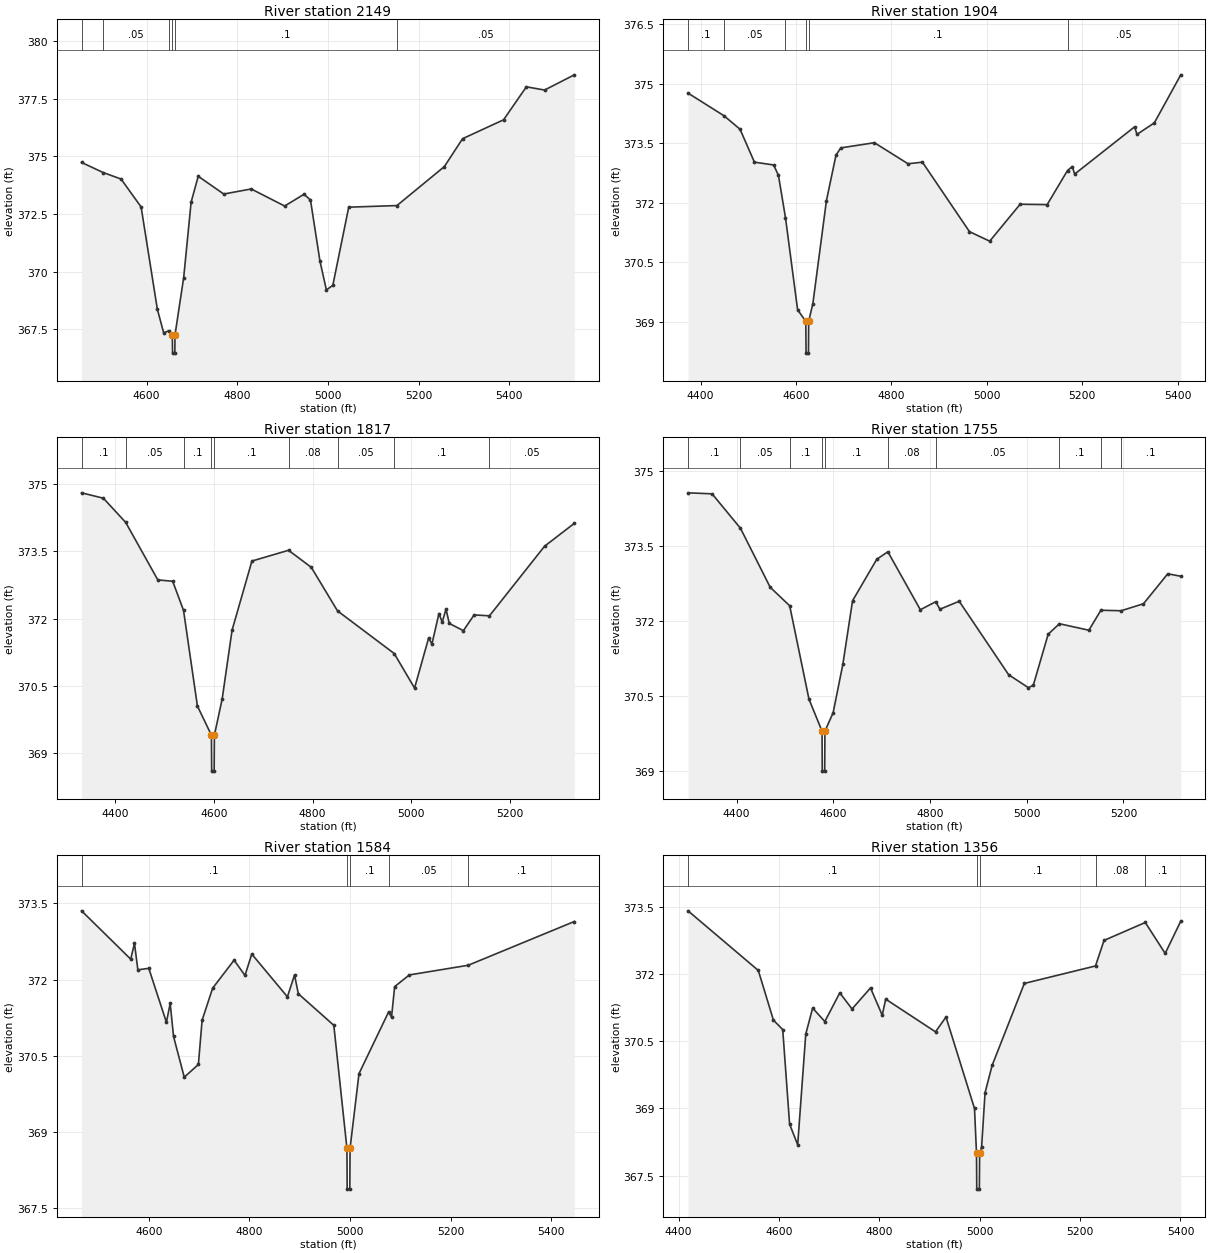
Type RM Length L Ch R = 1,2149,245,245,245
BEGIN DESCRIPTION:
Mapping XS b79723aa
END DESCRIPTION:
XS GIS Cut Line= 4
      2068222.33     13452333.33      2068022.27     13451949.26
      2067872.53     13451817.96      2067419.73     13451771.34
#Sta/Elev= 30
  4456.4  374.73  4504.4  374.29  4543.6  374.01  4587.8  372.80  4623.6  368.37
  4637.6  367.34  4649.1  367.43  4656.7  367.26  4657.2  366.46  4662.2  366.46
  4662.7  367.26  4681.8  369.74  4698.2  373.01  4713.9  374.13  4770.2  373.36
  4830.8  373.58  4904.6  372.84  4947.3  373.35  4961.6  373.10  4982.5  370.45
  4996.7  369.20  5010.9  369.40  5046.0  372.79  5152.4  372.86  5257.0  374.55
  5297.2  375.76  5387.7  376.58  5438.0  378.01  5478.2  377.87  5543.8  378.53
#Mann=6,-1,0
  4456.4     0.1       0  4504.4    0.05       0  4649.1     0.1       0
  4656.7    0.07       0  4662.7     0.1       0  5152.4    0.05       0
Bank Sta=4656.7,4662.7
Exp/Cntr=0.3,0.1

Type RM Length L Ch R = 1,1904,87,87,87
BEGIN DESCRIPTION:
Mapping XS 96e2ac9c
END DESCRIPTION:
XS GIS Cut Line= 4
      2068248.39     13452333.36      2068187.33     13451780.82
      2068038.67     13451636.50      2067769.75     13451657.10
#Sta/Elev= 30
  4373.6  374.76  4448.9  374.19  4482.6  373.85  4512.8  373.02  4553.0  372.95
  4563.1  372.69  4577.9  371.62  4603.3  369.30  4620.5  369.01  4621.0  368.21
  4626.0  368.21  4626.5  369.01  4635.3  369.46  4663.7  372.05  4683.8  373.20
  4693.9  373.38  4764.3  373.51  4834.7  372.98  4864.9  373.02  4963.5  371.27
  5005.9  371.03  5069.7  371.96  5126.3  371.95  5169.0  372.81  5179.0  372.91
  5184.0  372.72  5309.6  373.91  5314.6  373.72  5351.0  374.01  5406.4  375.22
#Mann=6,-1,0
  4373.6     0.1       0  4448.9    0.05       0  4577.9     0.1       0
  4620.5    0.07       0  4626.5     0.1       0  5169.0    0.05       0
Bank Sta=4620.5,4626.5
Exp/Cntr=0.3,0.1

Type RM Length L Ch R = 1,1817,62,62,62
BEGIN DESCRIPTION:
Mapping XS dd6eca8b
END DESCRIPTION:
XS GIS Cut Line= 4
      2068270.09     13452329.05      2068221.92     13451701.86
      2068109.07     13451568.40      2067914.74     13451573.28
#Sta/Elev= 30
  4332.1  374.80  4376.3  374.68  4421.6  374.14  4486.6  372.86  4516.7  372.83
  4538.7  372.18  4566.8  370.05  4595.2  369.40  4595.7  368.60  4600.7  368.60
  4601.2  369.40  4617.0  370.21  4637.0  371.74  4677.2  373.28  4751.4  373.52
  4797.5  373.14  4850.6  372.17  4965.5  371.22  5006.7  370.45  5035.3  371.57
  5041.8  371.43  5056.1  372.11  5062.7  371.92  5070.4  372.21  5077.0  371.89
  5105.6  371.73  5127.3  372.08  5158.4  372.06  5270.0  373.61  5330.3  374.12
#Mann=9,-1,0
  4332.1     0.1       0  4421.6    0.05       0  4538.7     0.1       0
  4595.2    0.07       0  4601.2     0.1       0  4751.4    0.08       0
  4850.6    0.05       0  4965.5     0.1       0  5158.4    0.05       0
Bank Sta=4595.2,4601.2
Exp/Cntr=0.3,0.1

Type RM Length L Ch R = 1,1755,171,171,171
BEGIN DESCRIPTION:
Mapping XS 56433d7e
END DESCRIPTION:
XS GIS Cut Line= 4
      2068298.30     13452324.68      2068267.92     13451771.31
      2068223.00     13451560.80      2068036.31     13451395.36
#Sta/Elev= 30
  4299.6  374.56  4349.4  374.54  4408.1  373.85  4469.5  372.67  4509.8  372.30
  4549.7  370.43  4576.7  369.79  4577.2  368.99  4582.2  368.99  4582.7  369.79
  4599.7  370.16  4619.8  371.13  4639.8  372.40  4689.9  373.23  4712.8  373.38
  4780.0  372.22  4811.7  372.38  4820.5  372.23  4860.3  372.39  4962.5  370.92
  5003.4  370.66  5013.6  370.71  5044.3  371.73  5067.6  371.94  5128.5  371.81
  5153.3  372.21  5195.2  372.20  5241.4  372.34  5291.6  372.94  5318.5  372.89
#Mann=10,-1,0
  4299.6     0.1       0  4408.1    0.05       0  4509.8     0.1       0
  4576.7    0.04       0  4582.7     0.1       0  4712.8    0.08       0
  4811.7    0.05       0  5067.6     0.1       0  5153.3    0.05       0
  5195.2     0.1       0
Bank Sta=4576.7,4582.7
Exp/Cntr=0.3,0.1

Type RM Length L Ch R = 1,1584,228,228,228
BEGIN DESCRIPTION:
Mapping XS 0e6a075d
END DESCRIPTION:
XS GIS Cut Line= 4
      2068721.47     13451947.07      2068409.54     13451599.32
      2068209.89     13451330.22      2068031.91     13451330.22
#Sta/Elev= 30
  4466.0  373.35  4563.8  372.40  4571.3  372.71  4578.0  372.19  4599.7  372.22
  4634.8  371.16  4642.3  371.53  4649.0  370.88  4670.3  370.08  4698.4  370.33
  4705.8  371.20  4726.8  371.83  4769.4  372.38  4791.1  372.08  4804.6  372.50
  4875.5  371.66  4889.7  372.09  4897.2  371.72  4967.8  371.10  4993.9  368.68
  4994.4  367.88  4999.6  367.88  5000.1  368.68  5017.9  370.15  5076.7  371.36
  5082.6  371.26  5088.8  371.86  5118.0  372.09  5235.1  372.28  5446.2  373.14
#Mann=5,-1,0
  4466.0     0.1       0  4993.9    0.07       0  5000.1     0.1       0
  5076.7    0.05       0  5235.1     0.1       0
Bank Sta=4993.9,5000.1
Exp/Cntr=0.3,0.1

Type RM Length L Ch R = 1,1356,314,314,314
BEGIN DESCRIPTION:
Mapping XS b3d7e920
END DESCRIPTION:
XS GIS Cut Line= 4
      2068780.08     13451873.31      2068643.92     13451527.70
      2068381.33     13451239.07      2068164.31     13451202.18
#Sta/Elev= 30
  4418.8  373.41  4558.8  372.08  4589.0  370.97  4607.5  370.76  4621.2  368.65
  4637.3  368.19  4653.4  370.66  4667.1  371.24  4691.4  370.94  4721.2  371.58
  4745.6  371.22  4782.4  371.69  4805.8  371.08  4812.6  371.44  4911.9  370.71
  4932.8  371.04  4989.6  369.00  4993.6  368.00  4994.1  367.20  4999.3  367.20
  4999.8  368.00  5003.8  368.14  5010.6  369.35  5024.7  369.96  5088.9  371.79
  5230.7  372.18  5247.7  372.75  5329.9  373.15  5369.5  372.46  5400.6  373.18
#Mann=5,-1,0
  4418.8     0.1       0  4993.6    0.07       0  4999.8     0.1       0
  5230.7    0.08       0  5329.9     0.1       0
Bank Sta=4993.6,4999.8
Exp/Cntr=0.3,0.1

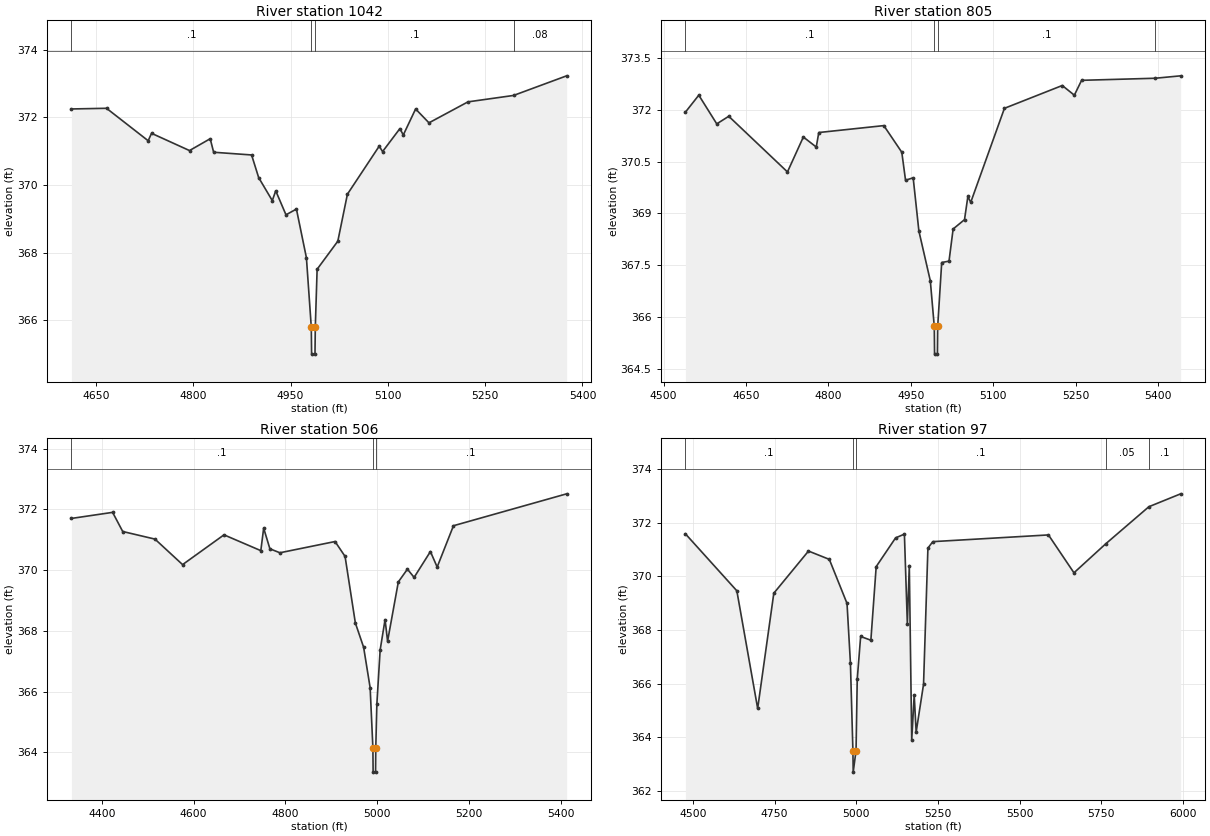
Type RM Length L Ch R = 1,1042,237,237,237
BEGIN DESCRIPTION:
Mapping XS 50abfd15
END DESCRIPTION:
XS GIS Cut Line= 4
      2068921.68     13451356.23      2068886.97     13451254.27
      2068474.65     13451119.72      2068253.30     13451134.91
#Sta/Elev= 30
  4612.3  372.25  4666.4  372.27  4730.6  371.31  4735.8  371.53  4794.3  371.02
  4826.2  371.37  4831.5  370.97  4890.0  370.89  4900.9  370.22  4921.9  369.54
  4927.2  369.83  4943.0  369.12  4959.1  369.29  4974.5  367.85  4982.0  365.80
  4982.5  365.00  4987.7  365.00  4988.2  365.80  4991.0  367.51  5022.9  368.34
  5037.7  369.73  5086.7  371.15  5091.9  370.99  5118.6  371.67  5123.8  371.48
  5142.8  372.25  5163.4  371.84  5223.5  372.46  5293.8  372.65  5375.6  373.23
#Mann=4,-1,0
  4612.3     0.1       0  4982.0    0.07       0  4988.2     0.1       0
  5293.8    0.08       0
Bank Sta=4982,4988.2
Exp/Cntr=0.3,0.1

Type RM Length L Ch R = 1,805,299,299,299
BEGIN DESCRIPTION:
Mapping XS 289b918e
END DESCRIPTION:
XS GIS Cut Line= 4
      2069015.01     13451267.28      2068917.35     13451041.59
      2068524.56     13450933.09      2068305.42     13451048.08
#Sta/Elev= 30
  4539.8  371.93  4564.1  372.42  4596.8  371.59  4618.6  371.81  4725.4  370.20
  4754.3  371.21  4777.8  370.92  4782.4  371.34  4900.7  371.54  4933.4  370.77
  4940.2  369.96  4954.1  370.03  4964.5  368.49  4985.3  367.05  4992.5  365.73
  4993.0  364.93  4998.2  364.93  4998.7  365.73  5006.0  367.58  5019.3  367.62
  5026.8  368.55  5047.5  368.82  5053.6  369.49  5058.8  369.32  5120.1  372.04
  5225.3  372.70  5247.3  372.42  5260.5  372.85  5394.5  372.91  5440.7  372.98
#Mann=4,-1,0
  4539.8     0.1       0  4992.5    0.07       0  4998.7     0.1       0
  5394.5    0.05       0
Bank Sta=4992.5,4998.7
Exp/Cntr=0.3,0.1

Type RM Length L Ch R = 1,506,409,409,409
BEGIN DESCRIPTION:
Mapping XS 8ded0f5b
END DESCRIPTION:
XS GIS Cut Line= 4
      2069036.71     13451256.43      2069006.33     13450837.60
      2068728.55     13450716.07      2068442.10     13450926.57
#Sta/Elev= 30
  4333.9  371.70  4423.6  371.90  4445.6  371.27  4515.8  371.02  4576.0  370.18
  4666.2  371.16  4746.4  370.64  4752.6  371.38  4766.2  370.70  4788.0  370.57
  4908.1  370.94  4929.9  370.45  4952.3  368.26  4970.3  367.46  4984.5  366.13
  4990.5  364.15  4991.0  363.35  4996.3  363.35  4996.8  364.15  4999.1  365.58
  5006.3  367.37  5017.0  368.37  5022.5  367.66  5045.9  369.61  5065.7  370.03
  5080.3  369.76  5115.8  370.61  5130.5  370.10  5166.0  371.46  5412.5  372.51
#Mann=3,-1,0
  4333.9     0.1       0  4990.5    0.07       0  4996.8     0.1       0
Bank Sta=4990.5,4996.8
Exp/Cntr=0.3,0.1

Type RM Length L Ch R = 1,97,0,0,0
BEGIN DESCRIPTION:
UNT 21 in Lagunillas Cr Wtrshd 12.0
END DESCRIPTION:
XS GIS Cut Line= 4
      2069415.40     13450777.31      2069142.49     13450494.40
      2068929.82     13450431.46      2068181.12     13450933.63
#Sta/Elev= 30
  4476.9  371.58  4634.3  369.46  4698.1  365.08  4747.5  369.37  4853.7  370.94
  4917.5  370.63  4971.7  368.99  4982.1  366.77  4989.7  363.51  4990.6  362.71
  4999.3  363.51  5003.0  366.17  5013.4  367.76  5044.7  367.62  5061.0  370.36
  5120.4  371.43  5147.4  371.57  5156.4  368.24  5162.4  370.40  5169.8  363.91
  5177.4  365.58  5183.4  364.20  5206.0  365.98  5219.4  371.05  5234.4  371.29
  5588.5  371.54  5666.6  370.13  5763.9  371.21  5896.0  372.59  5993.3  373.07
#Mann=5,-1,0
  4476.9     0.1       0  4989.7    0.07       0  4999.3     0.1       0
  5763.9    0.05       0  5896.0     0.1       0
Bank Sta=4989.7,4999.3
Exp/Cntr=0.3,0.1

Chan Stop Cuts=-1