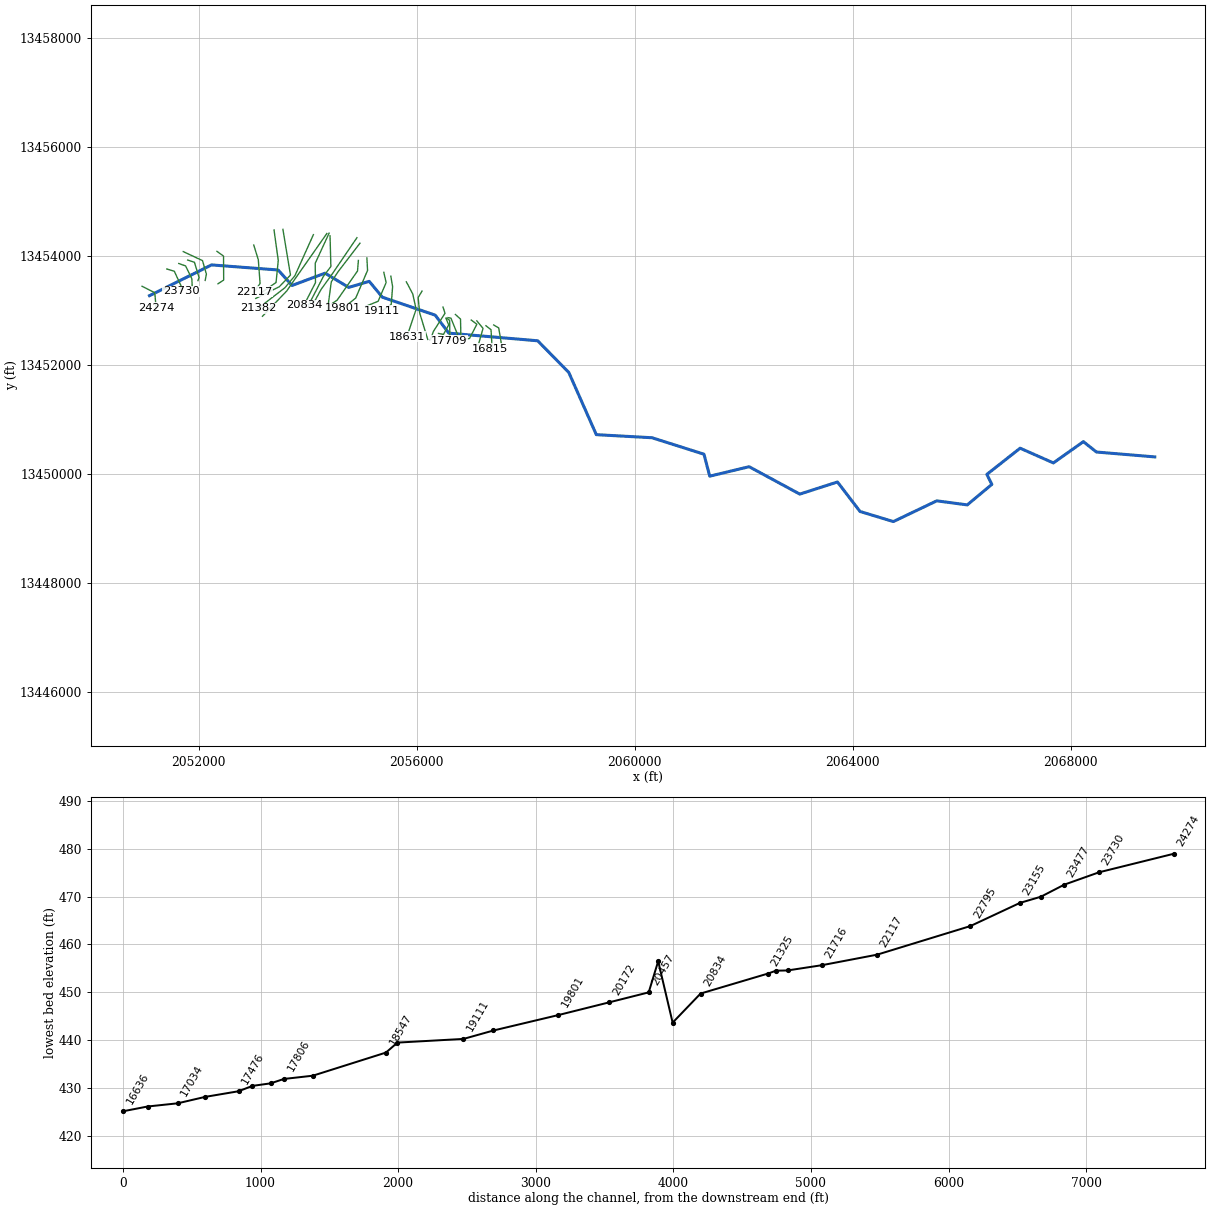
--- UNT 22 in Lagunillas Cr Wtrshd.prj (project) ---

Proj Title=UNT 22 in Lagunillas Cr Wtrshd Base Level Engineering
Current Plan=p01
Default Exp/Contr=0.3,0.1
English Units
Geom File=g01
Flow File=f01
Plan File=p01
BEGIN DESCRIPTION:
UNT 22 in Lagunillas Cr Wtrshd
END DESCRIPTION:

--- UNT 22 in Lagunillas Cr Wtrshd.p01 (plan) ---

Plan Title=Multiple Run
Short Identifier=Multiple
Geom File=g01
Flow File=f01
Subcritical Flow
K Sum by GR= 0
Std Step Tol= 0.01
Critical Tol= 0.01
Num of Std Step Trials= 20
Max Error Tol= 0.3
Flow Tol Ratio= 0.001
Split Flow NTrial= 30
Split Flow Tol= 0.02
Split Flow Ratio= 0.02
Log Output Level= 0
Friction Slope Method= 1
Unsteady Friction Slope Method= 2
Unsteady Bridges Friction Slope Method= 1
Parabolic Critical Depth
Global Vel Dist=  1 , 1 , 1
Global Log Level= 0
CheckData=True
Encroach Param= -1, 0, 0, 0
BEGIN DESCRIPTION:
Multiple Run
END DESCRIPTION:

--- UNT 22 in Lagunillas Cr Wtrshd.f01 (steady flow) ---

Flow Title=Multiple
Number of Profiles=7
Profile Names=10-year,25-year,50-year,1pct_min,100-year,1pct_plu,500-year
River Rch & RM= UNT 22 in Laguni,Reach-1,24274
     171     233     284     173     344     687     515
River Rch & RM= UNT 22 in Laguni,Reach-1,22117
     271     379     468     289     576    1150     887
River Rch & RM= UNT 22 in Laguni,Reach-1,15172
     324     455     565     350     697    1392    1080
River Rch & RM= UNT 22 in Laguni,Reach-1,7724
     456     651     817     510    1017    2030    1604
River Rch & RM= UNT 22 in Laguni,Reach-1,629
     569     820    1035     651    1298    2590    2073
River Rch & RM= UNT 22 in Laguni,Reach-1,114
     854    1229    1550     970    1936    3864    3068
Boundary for River Rch & Prof#=UNT 22 in Laguni,Reach-1,1
Up Type=0
Dn Type=3
Dn Slope=0.005
Boundary for River Rch & Prof#=UNT 22 in Laguni,Reach-1,2
Up Type=0
Dn Type=3
Dn Slope=0.005
Boundary for River Rch & Prof#=UNT 22 in Laguni,Reach-1,3
Up Type=0
Dn Type=3
Dn Slope=0.005
Boundary for River Rch & Prof#=UNT 22 in Laguni,Reach-1,4
Up Type=0
Dn Type=3
Dn Slope=0.005
Boundary for River Rch & Prof#=UNT 22 in Laguni,Reach-1,5
Up Type=0
Dn Type=3
Dn Slope=0.005
Boundary for River Rch & Prof#=UNT 22 in Laguni,Reach-1,6
Up Type=0
Dn Type=3
Dn Slope=0.005
Boundary for River Rch & Prof#=UNT 22 in Laguni,Reach-1,7
Up Type=0
Dn Type=3
Dn Slope=0.005

--- UNT 22 in Lagunillas Cr Wtrshd.g01 (geometry) ---

Geom Title=Existing Conditions

River Reach=UNT 22 in Laguni,Reach-1
Reach XY= 30
      2051099.44     13453272.15      2052237.86     13453836.04
      2053459.64     13453742.99      2053714.85     13453459.13
      2054320.80     13453684.54      2054754.35     13453423.69
      2055130.80     13453534.54      2055370.80     13453244.54
      2056340.80     13452914.54      2056590.80     13452584.54
      2058220.80     13452444.54      2058790.80     13451864.54
      2059296.13     13450722.83      2060317.83     13450666.41
      2061270.80     13450364.54      2061376.86     13449961.55
      2062099.08     13450135.16      2063028.77     13449632.55
      2063719.74     13449854.78      2064133.90     13449314.08
      2064745.01     13449128.66      2065541.54     13449509.22
      2066100.80     13449434.54      2066551.96     13449810.61
      2066460.80     13449994.54      2067070.80     13450474.54
      2067680.80     13450204.54      2068230.80     13450594.54
      2068470.80     13450404.54      2069540.80     13450314.54

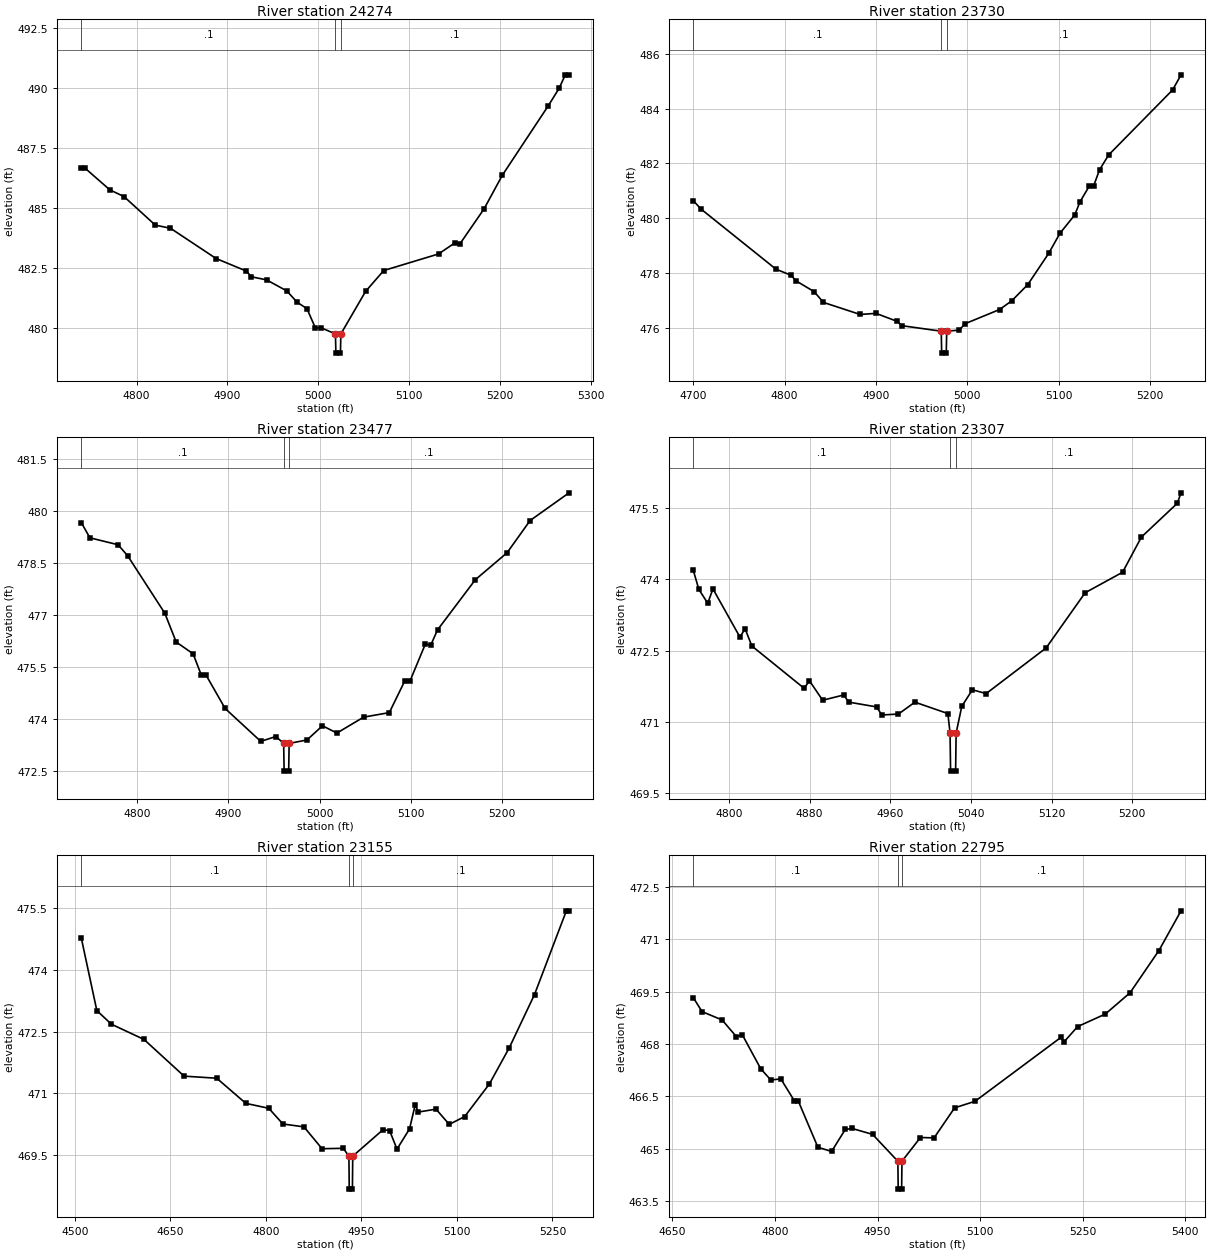
Type RM Length L Ch R = 1,24274,544,544,544
BEGIN DESCRIPTION:
UNT 22 in Lagunillas Cr Wtrshd 49.0
END DESCRIPTION:
XS GIS Cut Line= 3
      2050963.03     13453444.69      2051195.79     13453326.84
      2051221.26     13453051.91
#Sta/Elev= 30
  4739.1  486.67  4743.0  486.67  4770.5  485.76  4786.1  485.48  4820.6  484.29
  4837.3  484.16  4887.5  482.90  4920.7  482.38  4926.4  482.14  4943.1  482.01
  4965.4  481.55  4976.7  481.08  4987.6  480.81  4996.8  480.01  5003.4  480.01
  5018.9  479.76  5019.4  478.96  5024.4  478.96  5024.9  479.76  5052.1  481.53
  5072.1  482.40  5132.4  483.09  5150.8  483.56  5155.8  483.50  5182.6  484.97
  5202.7  486.37  5252.9  489.24  5265.2  489.99  5272.0  490.55  5276.1  490.55
#Mann=3,-1,0
  4739.1     0.1       0  5018.9    0.07       0  5024.9     0.1       0
Bank Sta=5018.9,5024.9
Exp/Cntr=0.3,0.1

Type RM Length L Ch R = 1,23730,253,253,253
BEGIN DESCRIPTION:
Mapping XS c602ba4a
END DESCRIPTION:
XS GIS Cut Line= 4
      2051418.33     13453761.45      2051555.05     13453719.78
      2051678.75     13453451.55      2051680.03     13453355.76
#Sta/Elev= 30
  4700.0  480.64  4708.6  480.33  4790.6  478.14  4807.1  477.92  4812.3  477.72
  4832.4  477.32  4842.5  476.93  4882.7  476.49  4900.1  476.53  4923.1  476.24
  4928.6  476.08  4971.5  475.88  4972.0  475.08  4977.0  475.08  4977.5  475.88
  4991.3  475.92  4997.4  476.15  5035.4  476.67  5048.8  476.99  5066.3  477.58
  5089.2  478.72  5101.5  479.45  5117.7  480.12  5123.5  480.60  5133.6  481.17
  5138.3  481.17  5144.9  481.77  5154.9  482.31  5224.9  484.68  5234.1  485.23
#Mann=3,-1,0
  4700.0     0.1       0  4971.5    0.07       0  4977.5     0.1       0
Bank Sta=4971.5,4977.5
Exp/Cntr=0.3,0.1

Type RM Length L Ch R = 1,23477,170,170,170
BEGIN DESCRIPTION:
Mapping XS 9a184ff7
END DESCRIPTION:
XS GIS Cut Line= 4
      2051637.09     13453861.71      2051762.08     13453817.44
      2051876.66     13453581.76      2051883.17     13453442.47
#Sta/Elev= 30
  4739.0  479.67  4748.4  479.23  4779.3  479.03  4789.8  478.71  4830.5  477.05
  4842.9  476.22  4861.4  475.88  4870.5  475.26  4875.7  475.26  4896.5  474.30
  4935.5  473.35  4952.1  473.49  4960.6  473.29  4961.1  472.49  4966.1  472.49
  4966.6  473.29  4986.1  473.39  5003.1  473.80  5018.9  473.59  5048.2  474.05
  5076.3  474.18  5093.3  475.10  5098.9  475.09  5115.9  476.17  5121.5  476.12
  5129.1  476.57  5170.5  478.02  5205.3  478.80  5230.5  479.73  5273.1  480.53
#Mann=3,-1,0
  4739.0     0.1       0  4960.6    0.07       0  4966.6     0.1       0
Bank Sta=4960.6,4966.6
Exp/Cntr=0.3,0.1

Type RM Length L Ch R = 1,23307,152,152,152
BEGIN DESCRIPTION:
Mapping XS 03f54607
END DESCRIPTION:
XS GIS Cut Line= 4
      2051799.80     13453925.52      2051923.54     13453885.15
      2052009.48     13453605.20      2051987.99     13453548.32
#Sta/Elev= 30
  4764.6  474.19  4770.1  473.79  4778.9  473.50  4784.1  473.80  4810.8  472.79
  4816.0  472.96  4822.7  472.60  4874.6  471.71  4879.8  471.87  4892.9  471.46
  4913.7  471.57  4918.9  471.42  4946.4  471.32  4951.6  471.15  4968.1  471.17
  4984.4  471.42  5017.1  471.18  5019.3  470.77  5019.8  469.97  5024.8  469.97
  5025.3  470.77  5030.9  471.33  5041.4  471.68  5055.1  471.60  5114.6  472.56
  5153.3  473.72  5190.4  474.15  5209.1  474.89  5244.7  475.60  5248.4  475.82
#Mann=3,-1,0
  4764.6     0.1       0  5019.3    0.07       0  5025.3     0.1       0
Bank Sta=5019.3,5025.3
Exp/Cntr=0.3,0.1

Type RM Length L Ch R = 1,23155,360,360,360
BEGIN DESCRIPTION:
Mapping XS fc7d8edb
END DESCRIPTION:
XS GIS Cut Line= 4
      2051718.26     13454080.53      2052071.98     13453915.09
      2052143.59     13453666.40      2052121.46     13453551.81
#Sta/Elev= 30
  4510.0  474.77  4534.4  473.01  4557.3  472.68  4608.5  472.31  4671.5  471.42
  4722.7  471.37  4768.4  470.76  4804.5  470.64  4826.6  470.26  4859.7  470.19
  4888.1  469.66  4921.4  469.67  4930.3  469.48  4930.8  468.68  4935.8  468.68
  4936.3  469.48  4983.8  470.12  4994.2  470.10  5005.8  469.65  5025.5  470.14
  5034.3  470.72  5039.5  470.55  5067.1  470.62  5087.9  470.25  5112.1  470.44
  5150.9  471.23  5182.2  472.11  5221.8  473.40  5271.8  475.43  5276.0  475.43
#Mann=3,-1,0
  4510.0     0.1       0  4930.3    0.07       0  4936.3     0.1       0
Bank Sta=4930.3,4936.3
Exp/Cntr=0.3,0.1

Type RM Length L Ch R = 1,22795,678,678,678
BEGIN DESCRIPTION:
Mapping XS cd99c3a5
END DESCRIPTION:
XS GIS Cut Line= 4
      2052336.62     13454085.30      2052457.70     13453998.08
      2052460.30     13453557.98      2052356.11     13453490.25
#Sta/Elev= 30
  4680.5  469.33  4693.3  468.93  4722.7  468.69  4743.6  468.21  4752.1  468.27
  4779.2  467.29  4793.9  466.97  4808.6  467.00  4828.1  466.38  4833.8  466.38
  4862.8  465.04  4882.8  464.92  4902.8  465.55  4912.8  465.58  4942.8  465.41
  4979.8  464.64  4980.3  463.84  4985.3  463.84  4985.8  464.64  5012.8  465.32
  5032.8  465.31  5062.8  466.17  5092.8  466.36  5218.3  468.19  5223.3  468.07
  5242.8  468.50  5283.3  468.86  5319.5  469.47  5361.7  470.68  5394.1  471.82
#Mann=3,-1,0
  4680.5     0.1       0  4979.8    0.07       0  4985.8     0.1       0
Bank Sta=4979.8,4985.8
Exp/Cntr=0.3,0.1

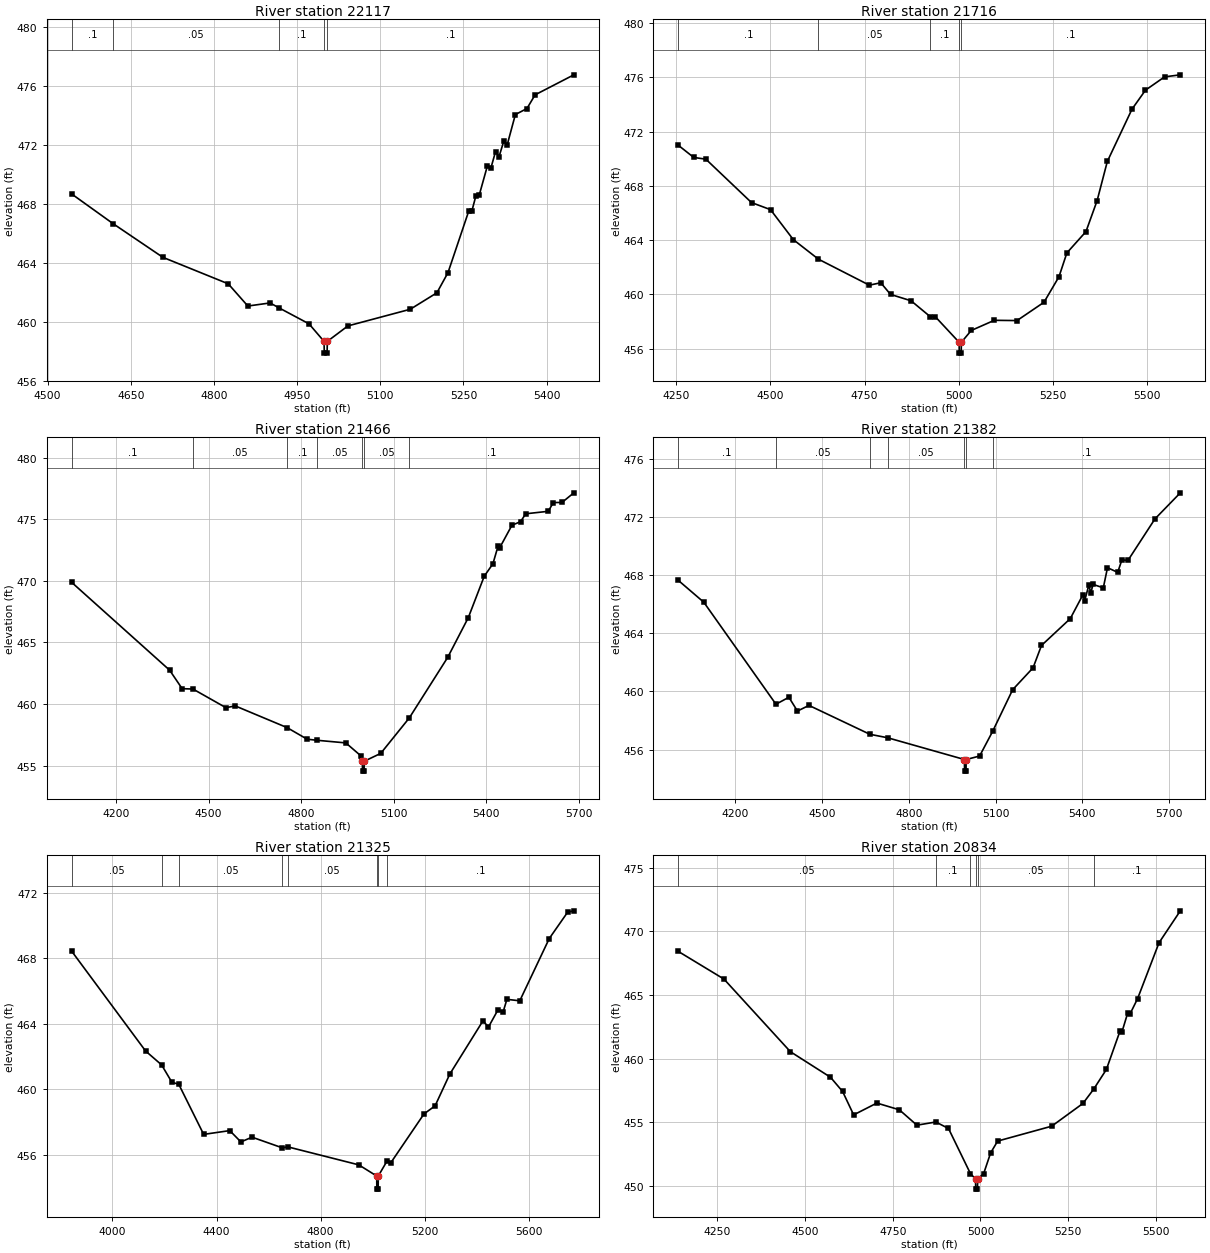
Type RM Length L Ch R = 1,22117,401,401,401
BEGIN DESCRIPTION:
Mapping XS 5fb61d42
END DESCRIPTION:
XS GIS Cut Line= 4
      2053012.40     13454199.94      2053095.72     13453930.37
      2053128.27     13453495.48      2053019.70     13453342.82
#Sta/Elev= 30
  4543.6  468.67  4618.0  466.66  4707.9  464.37  4825.8  462.57  4861.2  461.06
  4901.3  461.27  4917.7  460.93  4971.5  459.85  4998.6  458.66  4999.1  457.86
  5004.1  457.86  5004.6  458.66  5041.7  459.71  5154.1  460.84  5202.2  461.96
  5222.2  463.33  5259.6  467.51  5265.2  467.51  5272.4  468.53  5278.5  468.59
  5293.3  470.59  5299.4  470.41  5308.0  471.56  5314.2  471.20  5322.8  472.26
  5328.9  472.00  5343.7  474.07  5364.6  474.48  5379.3  475.41  5449.2  476.77
#Mann=5,-1,0
  4543.6     0.1       0  4618.0    0.05       0  4917.7     0.1       0
  4998.6    0.07       0  5004.6     0.1       0
Bank Sta=4998.6,5004.6
Exp/Cntr=0.3,0.1

Type RM Length L Ch R = 1,21716,250,250,250
BEGIN DESCRIPTION:
Mapping XS 57797143
END DESCRIPTION:
XS GIS Cut Line= 4
      2053383.93     13454477.74      2053461.60     13453918.65
      2053421.24     13453513.70      2053123.53     13453307.61
#Sta/Elev= 30
  4255.0  470.99  4296.1  470.09  4328.4  469.96  4449.6  466.76  4500.1  466.24
  4560.6  464.03  4627.2  462.59  4762.6  460.67  4792.9  460.85  4818.8  459.99
  4873.4  459.52  4924.7  458.34  4937.6  458.35  5001.0  456.46  5001.5  455.66
  5006.5  455.66  5007.0  456.46  5033.2  457.33  5094.5  458.08  5154.8  458.06
  5226.4  459.41  5266.2  461.29  5287.2  463.05  5337.9  464.62  5367.6  466.91
  5394.6  469.79  5460.2  473.65  5496.0  475.05  5546.7  476.03  5588.5  476.18
#Mann=5,-1,0
  4255.0     0.1       0  4627.2    0.05       0  4924.7     0.1       0
  5001.0    0.07       0  5007.0     0.1       0
Bank Sta=5001,5007
Exp/Cntr=0.3,0.1

Type RM Length L Ch R = 1,21466,84,84,84
BEGIN DESCRIPTION:
Mapping XS 47ceb1dc
END DESCRIPTION:
XS GIS Cut Line= 4
      2053547.12     13454488.19      2053685.58     13453649.77
      2053481.16     13453436.23      2053048.52     13453221.49
#Sta/Elev= 30
  4056.3  469.87  4373.7  462.75  4414.3  461.25  4449.4  461.22  4556.2  459.71
  4586.6  459.85  4754.7  458.09  4819.7  457.15  4853.1  457.06  4945.2  456.85
  4994.9  455.78  4998.8  455.36  4999.3  454.56  5004.3  454.56  5004.8  455.36
  5058.4  456.00  5151.1  458.88  5275.6  463.79  5342.5  467.02  5394.2  470.38
  5422.2  471.38  5439.0  472.83  5444.6  472.70  5483.9  474.51  5511.8  474.80
  5528.7  475.44  5601.5  475.64  5618.3  476.35  5646.3  476.36  5684.7  477.14
#Mann=7,-1,0
  4056.3     0.1       0  4449.4    0.05       0  4754.7     0.1       0
  4853.1    0.05       0  4998.8    0.03       0  5004.8    0.05       0
  5151.1     0.1       0
Bank Sta=4998.8,5004.8
Exp/Cntr=0.3,0.1

Type RM Length L Ch R = 1,21382,57,57,57
BEGIN DESCRIPTION:
Mapping XS a4450c21
END DESCRIPTION:
XS GIS Cut Line= 4
      2054106.14     13454390.91      2053767.85     13453639.36
      2053583.13     13453417.13      2053089.42     13453037.25
#Sta/Elev= 30
  4002.6  467.66  4091.0  466.15  4340.5  459.12  4385.2  459.60  4414.8  458.65
  4454.7  459.04  4665.1  457.05  4726.6  456.81  4992.2  455.31  4992.7  454.51
  4997.7  454.51  4998.2  455.31  5044.7  455.55  5090.0  457.26  5158.9  460.12
  5229.5  461.63  5258.6  463.17  5358.2  465.02  5401.8  466.66  5408.1  466.26
  5422.6  467.35  5428.9  466.78  5437.1  467.38  5472.4  467.14  5486.9  468.53
  5522.2  468.21  5536.7  469.07  5557.6  469.03  5650.9  471.89  5738.7  473.69
#Mann=7,-1,0
  4002.6     0.1       0  4340.5    0.05       0  4665.1     0.1       0
  4726.6    0.05       0  4992.2    0.03       0  4998.2    0.05       0
  5090.0     0.1       0
Bank Sta=4992.2,4998.2
Exp/Cntr=0.3,0.1

Type RM Length L Ch R = 1,21325,491,491,491
BEGIN DESCRIPTION:
Mapping XS 9ff9b2ba
END DESCRIPTION:
XS GIS Cut Line= 4
      2054352.70     13454411.80      2053762.30     13453569.22
      2053617.16     13453358.11      2053172.15     13452894.44
#Sta/Elev= 30
  3844.3  468.43  4127.6  462.35  4189.2  461.50  4228.7  460.44  4255.0  460.32
  4350.7  457.26  4450.9  457.49  4493.7  456.80  4536.4  457.09  4652.5  456.44
  4673.4  456.50  4946.4  455.40  5015.1  454.72  5015.6  453.92  5020.6  453.92
  5021.1  454.72  5054.2  455.62  5068.9  455.52  5196.7  458.51  5239.2  459.00
  5295.8  460.94  5423.1  464.19  5444.2  463.81  5479.7  464.83  5500.8  464.75
  5515.0  465.50  5564.4  465.41  5677.6  469.21  5748.3  470.82  5772.0  470.90
#Mann=8,-1,0
  3844.3    0.05       0  4189.2     0.1       0  4255.0    0.05       0
  4652.5     0.1       0  4673.4    0.05       0  5015.1   0.035       0
  5021.1    0.05       0  5054.2     0.1       0
Bank Sta=5015.1,5021.1
Exp/Cntr=0.3,0.1

Type RM Length L Ch R = 1,20834,203,203,203
BEGIN DESCRIPTION:
Mapping XS 601cc050
END DESCRIPTION:
XS GIS Cut Line= 4
      2054394.35     13454418.72      2054139.30     13453865.61
      2054144.72     13453511.88      2053932.55     13453095.81
#Sta/Elev= 30
  4139.2  468.43  4269.5  466.25  4458.6  460.54  4572.8  458.53  4607.3  457.41
  4638.8  455.57  4704.9  456.50  4768.9  455.97  4818.9  454.76  4872.8  455.01
  4908.9  454.50  4971.4  450.95  4985.9  450.53  4986.4  449.73  4991.4  449.73
  4991.9  450.53  5008.9  450.94  5028.9  452.58  5048.9  453.51  5202.8  454.68
  5291.8  456.47  5322.3  457.59  5358.5  459.14  5397.3  462.16  5402.9  462.09
  5419.5  463.61  5425.2  463.47  5447.4  464.71  5508.5  469.11  5569.1  471.62
#Mann=6,-1,0
  4139.2    0.05       0  4872.8     0.1       0  4971.4    0.05       0
  4985.9   0.033       0  4991.9    0.05       0  5322.3     0.1       0
Bank Sta=4985.9,4991.9
Exp/Cntr=0.3,0.1

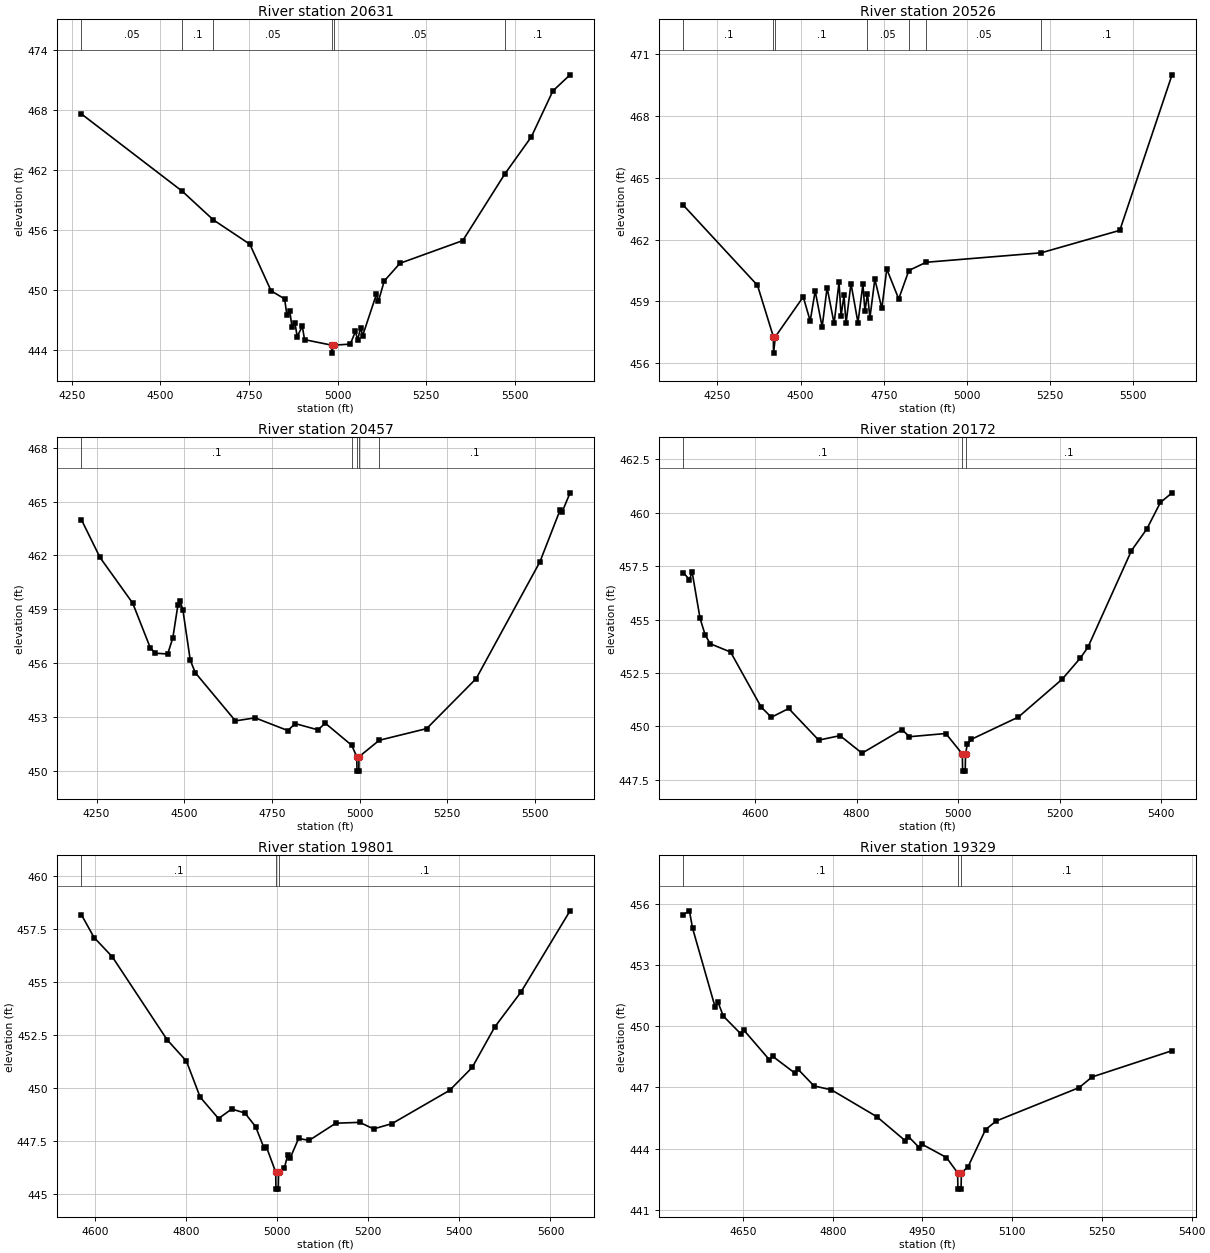
Type RM Length L Ch R = 1,20631,105,105,105
BEGIN DESCRIPTION:
Mapping XS ec8b6952
END DESCRIPTION:
XS GIS Cut Line= 4
      2054411.70     13454370.14      2054426.84     13453807.02
      2054290.12     13453625.81      2054019.68     13453103.38
#Sta/Elev= 30
  4276.9  467.59  4561.6  459.85  4649.0  456.99  4752.2  454.55  4812.2  449.88
  4850.3  449.08  4856.6  447.50  4864.9  447.85  4871.1  446.29  4879.4  446.69
  4885.7  445.31  4900.3  446.33  4906.5  445.00  4982.6  444.45  4983.1  443.65
  4988.7  444.45  5035.6  444.55  5050.1  445.82  5056.4  444.97  5064.6  446.18
  5070.6  445.41  5109.3  449.54  5114.9  448.85  5131.4  450.87  5175.7  452.64
  5352.8  454.91  5471.7  461.59  5546.4  465.30  5607.1  469.89  5655.5  471.50
#Mann=6,-1,0
  4276.9    0.05       0  4561.6     0.1       0  4649.0    0.05       0
  4982.6   0.033       0  4988.7    0.05       0  5471.7     0.1       0
Bank Sta=4982.6,4988.7
Exp/Cntr=0.3,0.1

Type RM Length L Ch R = 1,20526,69,69,69
BEGIN DESCRIPTION:
Mapping XS b6ac407d
END DESCRIPTION:
XS GIS Cut Line= 4
      2054904.79     13454335.41      2054446.37     13453662.71
      2054247.80     13453387.10      2054095.83     13453109.86
#Sta/Elev= 30
  4147.3  463.67  4370.3  459.78  4418.0  457.29  4418.5  456.49  4424.2  457.29
  4507.9  459.22  4528.9  458.05  4543.8  459.51  4564.8  457.76  4579.7  459.67
  4600.7  457.93  4615.6  459.93  4621.7  458.30  4630.5  459.29  4636.6  457.93
  4651.5  459.87  4672.5  457.97  4687.4  459.83  4693.5  458.52  4701.1  459.38
  4708.4  458.20  4723.3  460.08  4744.3  458.66  4759.2  460.57  4795.1  459.12
  4825.5  460.50  4877.5  460.90  5223.6  461.36  5460.1  462.45  5617.2  470.00
#Mann=7,-1,0
  4147.3     0.1       0  4418.0   0.035       0  4424.2     0.1       0
  4701.1    0.05       0  4825.5     0.1       0  4877.5    0.05       0
  5223.6     0.1       0
Bank Sta=4418,4424.2
Exp/Cntr=0.3,0.1

Type RM Length L Ch R = 1,20457,285,285,285
BEGIN DESCRIPTION:
Mapping XS 5e384e28
END DESCRIPTION:
XS GIS Cut Line= 4
      2054960.34     13454234.72      2054563.56     13453716.96
      2054434.43     13453525.99      2054366.61     13453019.75
#Sta/Elev= 30
  4206.5  464.00  4259.6  461.89  4353.0  459.34  4402.9  456.86  4417.4  456.55
  4452.7  456.51  4467.3  457.40  4481.8  459.23  4488.1  459.45  4495.9  458.98
  4517.1  456.16  4531.6  455.46  4645.9  452.78  4702.0  452.95  4795.4  452.24
  4816.3  452.63  4881.2  452.28  4902.1  452.65  4977.5  451.42  4992.0  450.78
  4992.5  449.98  4997.7  449.98  4998.2  450.78  5056.1  451.70  5191.2  452.35
  5332.5  455.14  5514.1  461.64  5572.1  464.55  5577.1  464.40  5600.1  465.49
#Mann=5,-1,0
  4206.5     0.1       0  4977.5    0.05       0  4992.0   0.035       0
  4998.2    0.05       0  5056.1     0.1       0
Bank Sta=4992,4998.2
Exp/Cntr=0.3,0.1

Type RM Length L Ch R = 1,20172,371,371,371
BEGIN DESCRIPTION:
Mapping XS e6f7ff83
END DESCRIPTION:
XS GIS Cut Line= 4
      2054931.33     13453917.82      2054915.70     13453725.08
      2054540.70     13453188.63      2054445.20     13453124.38
#Sta/Elev= 30
  4458.5  457.19  4470.6  456.87  4475.7  457.24  4491.4  455.06  4501.5  454.28
  4511.5  453.87  4551.6  453.48  4611.8  450.91  4631.9  450.43  4666.1  450.84
  4725.2  449.36  4767.2  449.57  4810.6  448.75  4889.3  449.85  4904.1  449.52
  4975.7  449.67  5008.3  448.71  5008.8  447.91  5014.0  447.91  5014.5  448.71
  5018.0  449.16  5026.2  449.40  5118.7  450.44  5205.0  452.21  5240.8  453.20
  5255.6  453.70  5341.6  458.23  5371.6  459.23  5398.6  460.48  5421.5  460.93
#Mann=3,-1,0
  4458.5     0.1       0  5008.3    0.07       0  5014.5     0.1       0
Bank Sta=5008.3,5014.5
Exp/Cntr=0.3,0.1

Type RM Length L Ch R = 1,19801,472,472,472
BEGIN DESCRIPTION:
Mapping XS 3902deae
END DESCRIPTION:
XS GIS Cut Line= 4
      2055087.58     13453962.93      2055099.73     13453735.50
      2054882.72     13453228.56      2054653.56     13453044.53
#Sta/Elev= 30
  4569.9  458.19  4597.9  457.11  4637.9  456.20  4758.1  452.29  4800.6  451.28
  4830.8  449.58  4871.1  448.57  4900.1  449.02  4929.1  448.83  4952.7  448.18
  4970.8  447.19  4976.3  447.23  4996.7  446.04  4997.2  445.24  5002.4  445.24
  5002.9  446.04  5015.8  446.25  5023.4  446.87  5028.9  446.73  5047.0  447.63
  5070.1  447.54  5128.6  448.35  5181.2  448.39  5211.6  448.08  5252.0  448.33
  5378.5  449.90  5428.1  450.98  5477.7  452.89  5535.3  454.54  5643.0  458.37
#Mann=3,-1,0
  4569.9     0.1       0  4996.7    0.07       0  5002.9     0.1       0
Bank Sta=4996.7,5002.9
Exp/Cntr=0.3,0.1

Type RM Length L Ch R = 1,19329,218,218,218
BEGIN DESCRIPTION:
Mapping XS bc9c4d14
END DESCRIPTION:
XS GIS Cut Line= 4
      2055397.81     13453700.01      2055440.80     13453512.05
      2055293.57     13453169.00      2055060.99     13453074.95
#Sta/Elev= 30
  4550.2  455.47  4560.3  455.66  4565.6  454.81  4603.2  450.95  4608.3  451.17
  4616.9  450.50  4646.1  449.63  4651.3  449.81  4694.2  448.35  4699.3  448.53
  4737.1  447.69  4741.2  447.91  4768.7  447.07  4797.7  446.88  4873.8  445.56
  4920.9  444.39  4926.4  444.59  4944.5  444.05  4949.9  444.20  4990.1  443.56
  5008.7  442.81  5009.2  442.01  5014.5  442.01  5015.0  442.81  5026.1  443.10
  5055.4  444.93  5073.2  445.35  5211.9  446.99  5233.4  447.51  5367.2  448.80
#Mann=3,-1,0
  4550.2     0.1       0  5008.7    0.07       0  5015.0     0.1       0
Bank Sta=5008.7,5015
Exp/Cntr=0.3,0.1

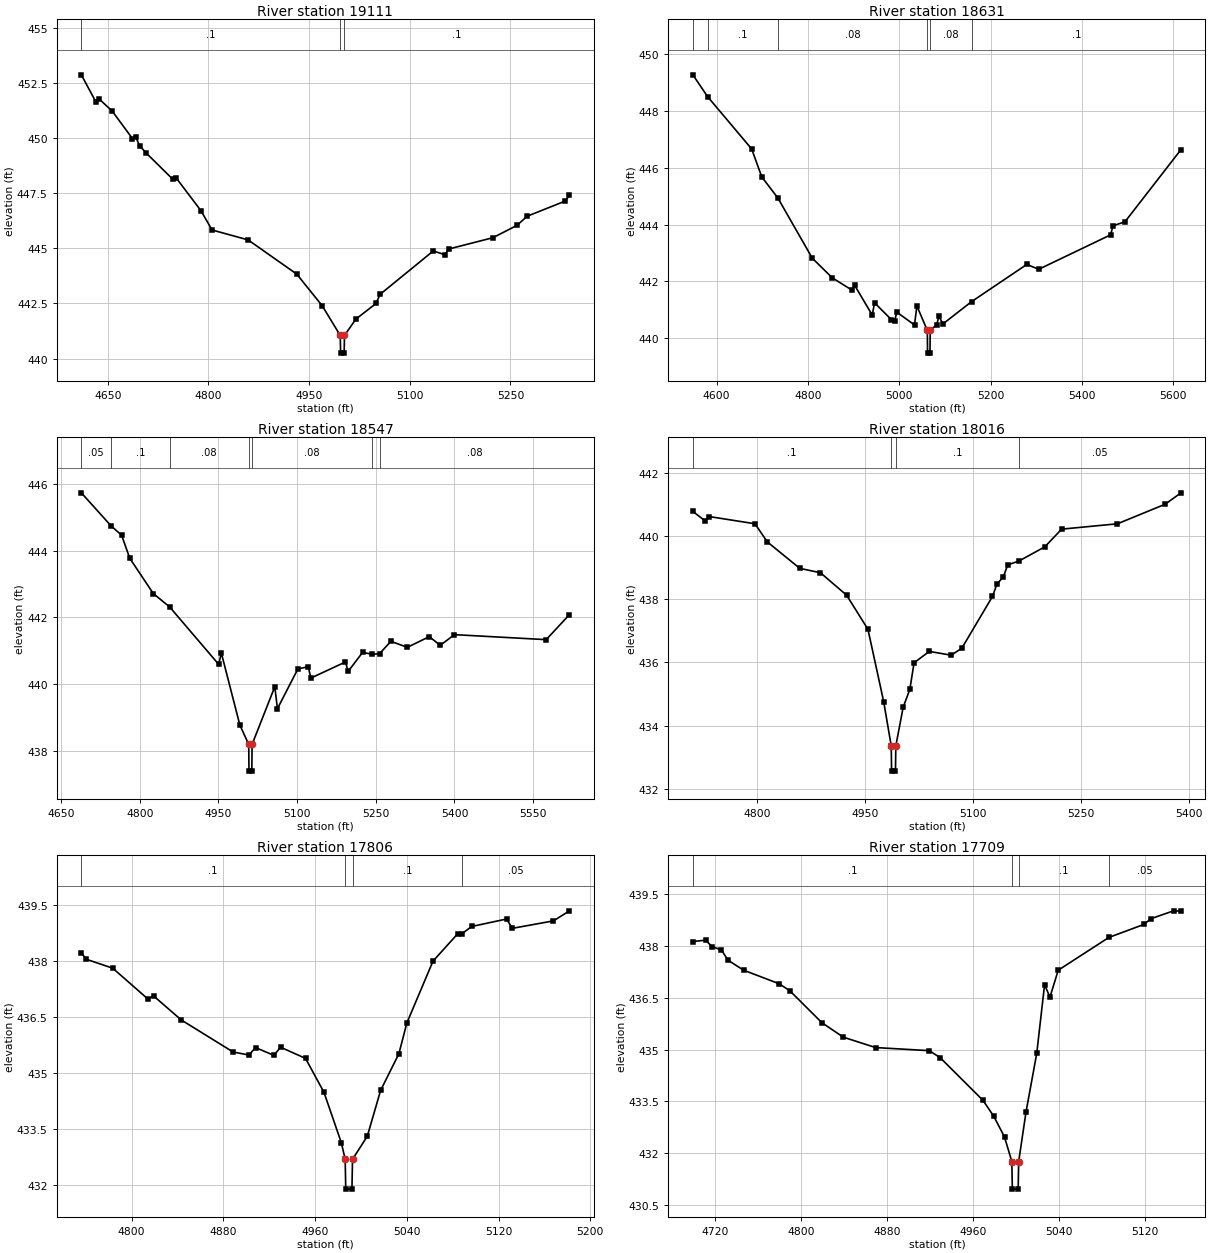
Type RM Length L Ch R = 1,19111,480,480,480
BEGIN DESCRIPTION:
Mapping XS f945ccc9
END DESCRIPTION:
XS GIS Cut Line= 4
      2055526.29     13453630.51      2055559.55     13453437.05
      2055533.85     13453109.97      2055366.57     13452995.10
#Sta/Elev= 30
  4610.6  452.86  4632.0  451.65  4637.0  451.77  4656.8  451.21  4686.8  449.97
  4691.9  450.03  4697.4  449.65  4707.5  449.31  4746.8  448.13  4751.9  448.19
  4788.7  446.71  4805.4  445.83  4859.1  445.38  4931.6  443.83  4969.4  442.40
  4996.4  441.05  4996.9  440.25  5002.2  440.25  5002.7  441.05  5019.6  441.79
  5049.7  442.50  5055.6  442.91  5135.0  444.88  5152.2  444.71  5158.3  444.97
  5223.9  445.48  5259.8  446.04  5274.7  446.45  5331.5  447.14  5337.9  447.40
#Mann=3,-1,0
  4610.6     0.1       0  4996.4    0.07       0  5002.7     0.1       0
Bank Sta=4996.4,5002.7
Exp/Cntr=0.3,0.1

Type RM Length L Ch R = 1,18631,84,84,84
BEGIN DESCRIPTION:
Mapping XS 68ab80f7
END DESCRIPTION:
XS GIS Cut Line= 4
      2055811.03     13453526.32      2055928.99     13453303.03
      2055990.80     13453021.78      2055821.71     13452520.74
#Sta/Elev= 30
  4547.9  449.27  4580.3  448.50  4676.8  446.66  4698.8  445.68  4734.0  444.94
  4809.5  442.82  4853.2  442.13  4897.0  441.69  4902.1  441.87  4940.8  440.82
  4945.9  441.25  4982.7  440.66  4989.7  440.61  4994.8  440.92  5033.4  440.47
  5038.6  441.14  5061.5  440.28  5062.0  439.48  5067.3  439.48  5067.8  440.28
  5082.3  440.48  5086.5  440.78  5095.9  440.51  5158.3  441.29  5279.4  442.60
  5305.6  442.43  5462.9  443.64  5468.2  443.96  5494.4  444.10  5617.2  446.64
#Mann=6,-1,0
  4547.9    0.05       0  4580.3     0.1       0  4734.0    0.08       0
  5061.5    0.07       0  5067.8    0.08       0  5158.3     0.1       0
Bank Sta=5061.5,5067.8
Exp/Cntr=0.3,0.1

Type RM Length L Ch R = 1,18547,531,531,531
BEGIN DESCRIPTION:
Mapping XS 2183909e
END DESCRIPTION:
XS GIS Cut Line= 4
      2056099.14     13453356.52      2056027.60     13453237.75
      2056054.69     13452959.28      2056203.47     13452469.31
#Sta/Elev= 30
  4688.7  445.73  4745.4  444.74  4765.5  444.46  4781.0  443.77  4826.0  442.71
  4857.1  442.31  4950.5  440.59  4955.6  440.93  4990.9  438.77  5007.8  438.19
  5008.3  437.39  5013.7  437.39  5014.2  438.19  5057.5  439.92  5062.5  439.26
  5101.4  440.45  5121.1  440.52  5126.4  440.18  5192.1  440.66  5197.4  440.38
  5225.0  440.95  5243.2  440.89  5257.2  440.91  5278.8  441.28  5310.2  441.10
  5352.0  441.42  5372.9  441.16  5399.9  441.48  5574.8  441.33  5619.2  442.08
#Mann=7,-1,0
  4688.7    0.05       0  4745.4     0.1       0  4857.1    0.08       0
  5007.8    0.07       0  5014.2    0.08       0  5243.2    0.05       0
  5257.2    0.08       0
Bank Sta=5007.8,5014.2
Exp/Cntr=0.3,0.1

Type RM Length L Ch R = 1,18016,210,210,210
BEGIN DESCRIPTION:
Mapping XS f9f94ffd
END DESCRIPTION:
XS GIS Cut Line= 4
      2056483.71     13453063.34      2056520.61     13452949.38
      2056307.83     13452616.23      2056251.40     13452462.13
#Sta/Elev= 30
  4710.3  440.78  4727.5  440.48  4732.8  440.62  4796.8  440.39  4813.7  439.82
  4859.0  438.98  4887.8  438.84  4924.2  438.13  4953.9  437.05  4975.8  434.76
  4986.3  433.36  4986.8  432.56  4992.2  432.56  4992.7  433.36  5002.9  434.58
  5012.2  435.15  5018.1  435.99  5039.3  436.35  5069.7  436.23  5084.5  436.45
  5127.2  438.09  5133.2  438.47  5142.5  438.72  5148.4  439.09  5163.9  439.21
  5200.0  439.66  5223.4  440.22  5301.1  440.39  5367.5  441.01  5389.5  441.37
#Mann=4,-1,0
  4710.3     0.1       0  4986.3    0.07       0  4992.7     0.1       0
  5163.9    0.05       0
Bank Sta=4986.3,4992.7
Exp/Cntr=0.3,0.1

Type RM Length L Ch R = 1,17806,97,97,97
BEGIN DESCRIPTION:
Mapping XS 3f95b773
END DESCRIPTION:
XS GIS Cut Line= 4
      2056536.89     13452860.40      2056587.89     13452735.62
      2056492.40     13452562.01      2056401.28     13452579.37
#Sta/Elev= 30
  4756.1  438.22  4760.4  438.05  4783.5  437.81  4813.9  436.99  4819.3  437.06
  4843.3  436.42  4888.5  435.56  4902.3  435.48  4908.0  435.68  4924.1  435.47
  4929.8  435.69  4951.6  435.39  4967.7  434.48  4982.9  433.12  4986.2  432.68
  4986.7  431.88  4992.1  431.88  4992.6  432.68  5005.5  433.30  5017.1  434.53
  5033.0  435.51  5040.0  436.34  5062.8  438.00  5084.5  438.74  5088.2  438.74
  5096.6  438.93  5126.9  439.13  5132.0  438.88  5167.8  439.08  5181.8  439.35
#Mann=4,-1,0
  4756.1     0.1       0  4986.2    0.07       0  4992.6     0.1       0
  5088.2    0.05       0
Bank Sta=4986.2,4992.6
Exp/Cntr=0.3,0.1

Type RM Length L Ch R = 1,17709,132,132,132
BEGIN DESCRIPTION:
Mapping XS 9e95d22c
END DESCRIPTION:
XS GIS Cut Line= 4
      2056552.12     13452858.21      2056605.25     13452819.17
      2056611.76     13452457.84      2056588.91     13452443.30
#Sta/Elev= 30
  4699.4  438.13  4711.2  438.17  4717.4  437.98  4725.9  437.89  4732.1  437.59
  4746.7  437.30  4779.5  436.91  4789.5  436.71  4819.5  435.78  4839.5  435.36
  4869.5  435.06  4919.5  434.97  4929.5  434.77  4969.5  433.53  4979.5  433.07
  4989.5  432.47  4996.3  431.76  4996.8  430.96  5002.2  430.96  5002.7  431.76
  5009.5  433.19  5019.5  434.89  5026.8  436.88  5031.8  436.52  5039.5  437.30
  5086.7  438.25  5119.6  438.63  5125.6  438.79  5146.9  439.02  5153.8  439.01
#Mann=4,-1,0
  4699.4     0.1       0  4996.3    0.07       0  5002.7     0.1       0
  5086.7    0.05       0
Bank Sta=4996.3,5002.7
Exp/Cntr=0.3,0.1

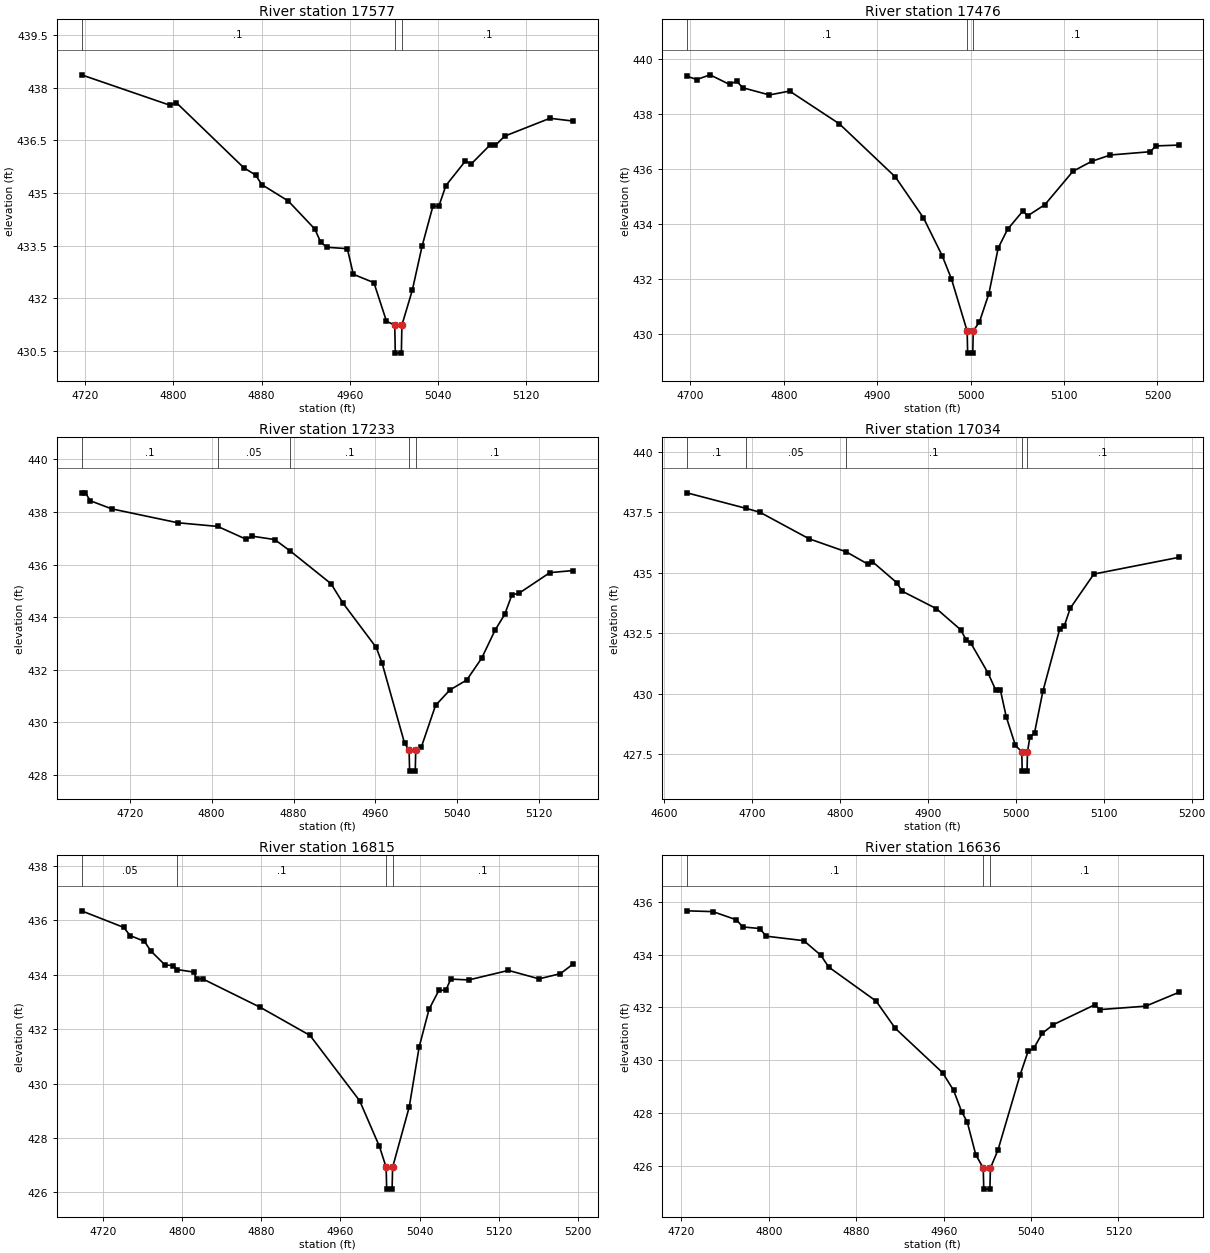
Type RM Length L Ch R = 1,17577,101,101,101
BEGIN DESCRIPTION:
Mapping XS f493ff64
END DESCRIPTION:
XS GIS Cut Line= 4
      2056574.82     13452869.09      2056629.12     13452860.41
      2056748.48     13452566.35      2056735.46     13452493.65
#Sta/Elev= 30
  4716.6  438.37  4797.1  437.50  4802.5  437.58  4863.8  435.72  4874.6  435.51
  4880.1  435.24  4904.2  434.77  4928.3  433.97  4933.7  433.59  4939.3  433.45
  4957.8  433.41  4963.2  432.68  4981.9  432.44  4993.3  431.34  5000.8  431.23
  5001.3  430.43  5006.8  430.43  5007.3  431.23  5016.7  432.22  5025.6  433.48
  5035.4  434.62  5040.8  434.62  5047.2  435.21  5064.9  435.91  5070.3  435.83
  5087.0  436.36  5092.2  436.36  5100.5  436.62  5141.6  437.13  5162.8  437.05
#Mann=3,-1,0
  4716.6     0.1       0  5000.8    0.07       0  5007.3     0.1       0
Bank Sta=5000.8,5007.3
Exp/Cntr=0.3,0.1

Type RM Length L Ch R = 1,17476,243,243,243
BEGIN DESCRIPTION:
Mapping XS 80239d14
END DESCRIPTION:
XS GIS Cut Line= 4
      2056711.59     13452926.59      2056804.90     13452843.04
      2056812.50     13452491.48      2056768.47     13452468.42
#Sta/Elev= 30
  4696.2  439.36  4706.8  439.24  4721.0  439.41  4741.9  439.06  4749.4  439.18
  4756.1  438.94  4784.5  438.68  4806.2  438.82  4859.5  437.63  4919.5  435.70
  4949.5  434.22  4969.5  432.85  4979.5  432.00  4996.3  430.11  4996.8  429.31
  5002.3  429.31  5002.8  430.11  5009.5  430.45  5019.5  431.46  5029.5  433.12
  5039.5  433.80  5056.0  434.47  5061.0  434.29  5079.6  434.70  5109.6  435.91
  5129.6  436.27  5149.6  436.50  5192.5  436.62  5198.2  436.83  5222.8  436.86
#Mann=3,-1,0
  4696.2     0.1       0  4996.3    0.07       0  5002.8     0.1       0
Bank Sta=4996.3,5002.8
Exp/Cntr=0.3,0.1

Type RM Length L Ch R = 1,17233,199,199,199
BEGIN DESCRIPTION:
Mapping XS 9d3736ac
END DESCRIPTION:
XS GIS Cut Line= 4
      2057002.42     13452824.57      2057105.47     13452747.56
      2056969.83     13452487.14      2056912.35     13452478.46
#Sta/Elev= 30
  4672.9  438.73  4676.7  438.73  4681.4  438.43  4702.3  438.12  4766.9  437.59
  4806.0  437.45  4833.8  436.96  4839.5  437.08  4861.6  436.95  4876.6  436.52
  4916.6  435.27  4928.5  434.52  4960.8  432.84  4966.4  432.26  4988.5  429.19
  4992.9  428.93  4993.4  428.13  4998.9  428.13  4999.4  428.93  5005.0  429.06
  5018.7  430.63  5032.7  431.22  5049.2  431.60  5063.8  432.43  5076.9  433.50
  5086.3  434.10  5093.4  434.85  5100.1  434.90  5130.4  435.69  5153.3  435.77
#Mann=5,-1,0
  4672.9     0.1       0  4806.0    0.05       0  4876.6     0.1       0
  4992.9    0.07       0  4999.4     0.1       0
Bank Sta=4992.9,4999.4
Exp/Cntr=0.3,0.1

Type RM Length L Ch R = 1,17034,219,219,219
BEGIN DESCRIPTION:
Mapping XS b12becab
END DESCRIPTION:
XS GIS Cut Line= 4
      2057104.41     13452810.46      2057218.31     13452671.60
      2057133.68     13452376.46      2057062.08     13452363.45
#Sta/Elev= 30
  4625.8  438.30  4692.8  437.66  4708.7  437.50  4764.7  436.40  4807.0  435.86
  4831.7  435.35  4836.9  435.45  4864.3  434.59  4870.7  434.23  4909.6  433.51
  4937.1  432.64  4943.3  432.23  4948.5  432.10  4968.3  430.85  4977.1  430.14
  4982.3  430.16  4989.1  429.03  4999.5  427.85  5006.7  427.59  5007.2  426.79
  5012.7  426.79  5013.2  427.59  5016.0  428.21  5021.2  428.37  5030.7  430.09
  5049.8  432.66  5055.0  432.79  5061.9  433.53  5088.7  434.94  5185.2  435.63
#Mann=5,-1,0
  4625.8     0.1       0  4692.8    0.05       0  4807.0     0.1       0
  5006.7    0.07       0  5013.2     0.1       0
Bank Sta=5006.7,5013.2
Exp/Cntr=0.3,0.1

Type RM Length L Ch R = 1,16815,179,179,179
BEGIN DESCRIPTION:
Mapping XS 0bffdca2
END DESCRIPTION:
XS GIS Cut Line= 4
      2057271.49     13452720.43      2057364.80     13452646.65
      2057385.41     13452307.02      2057349.85     13452295.16
#Sta/Elev= 30
  4698.6  436.35  4741.3  435.74  4747.7  435.44  4762.1  435.23  4768.5  434.88
  4782.9  434.36  4791.0  434.34  4795.3  434.19  4811.8  434.10  4814.9  433.85
  4820.9  433.85  4879.3  432.80  4929.4  431.77  4979.5  429.37  4999.5  427.69
  5006.3  426.92  5006.8  426.12  5012.3  426.12  5012.8  426.92  5029.6  429.14
  5039.6  431.34  5049.6  432.73  5059.6  433.43  5066.5  433.43  5071.6  433.84
  5089.7  433.81  5129.8  434.16  5160.7  433.85  5182.3  434.04  5195.3  434.40
#Mann=4,-1,0
  4698.6    0.05       0  4795.3     0.1       0  5006.3    0.07       0
  5012.8     0.1       0
Bank Sta=5006.3,5012.8
Exp/Cntr=0.3,0.1

Type RM Length L Ch R = 1,16636,175,175,175
BEGIN DESCRIPTION:
Mapping XS b29674cb
END DESCRIPTION:
XS GIS Cut Line= 4
      2057413.66     13452734.52      2057505.86     13452680.28
      2057556.86     13452374.29      2057536.29     13452348.59
#Sta/Elev= 30
  4725.0  435.66  4748.8  435.63  4770.3  435.32  4776.1  435.05  4791.7  434.99
  4797.5  434.70  4832.0  434.53  4847.5  433.98  4854.8  433.53  4898.2  432.24
  4915.7  431.21  4959.0  429.53  4969.1  428.86  4976.5  428.05  4981.6  427.66
  4989.4  426.42  4996.2  425.92  4996.7  425.12  5002.3  425.12  5002.8  425.92
  5009.7  426.60  5029.9  429.44  5037.3  430.34  5042.4  430.45  5050.2  431.02
  5060.4  431.35  5098.2  432.10  5103.2  431.92  5144.9  432.05  5175.1  432.57
#Mann=3,-1,0
  4725.0     0.1       0  4996.2    0.07       0  5002.8     0.1       0
Bank Sta=4996.2,5002.8
Exp/Cntr=0.3,0.1