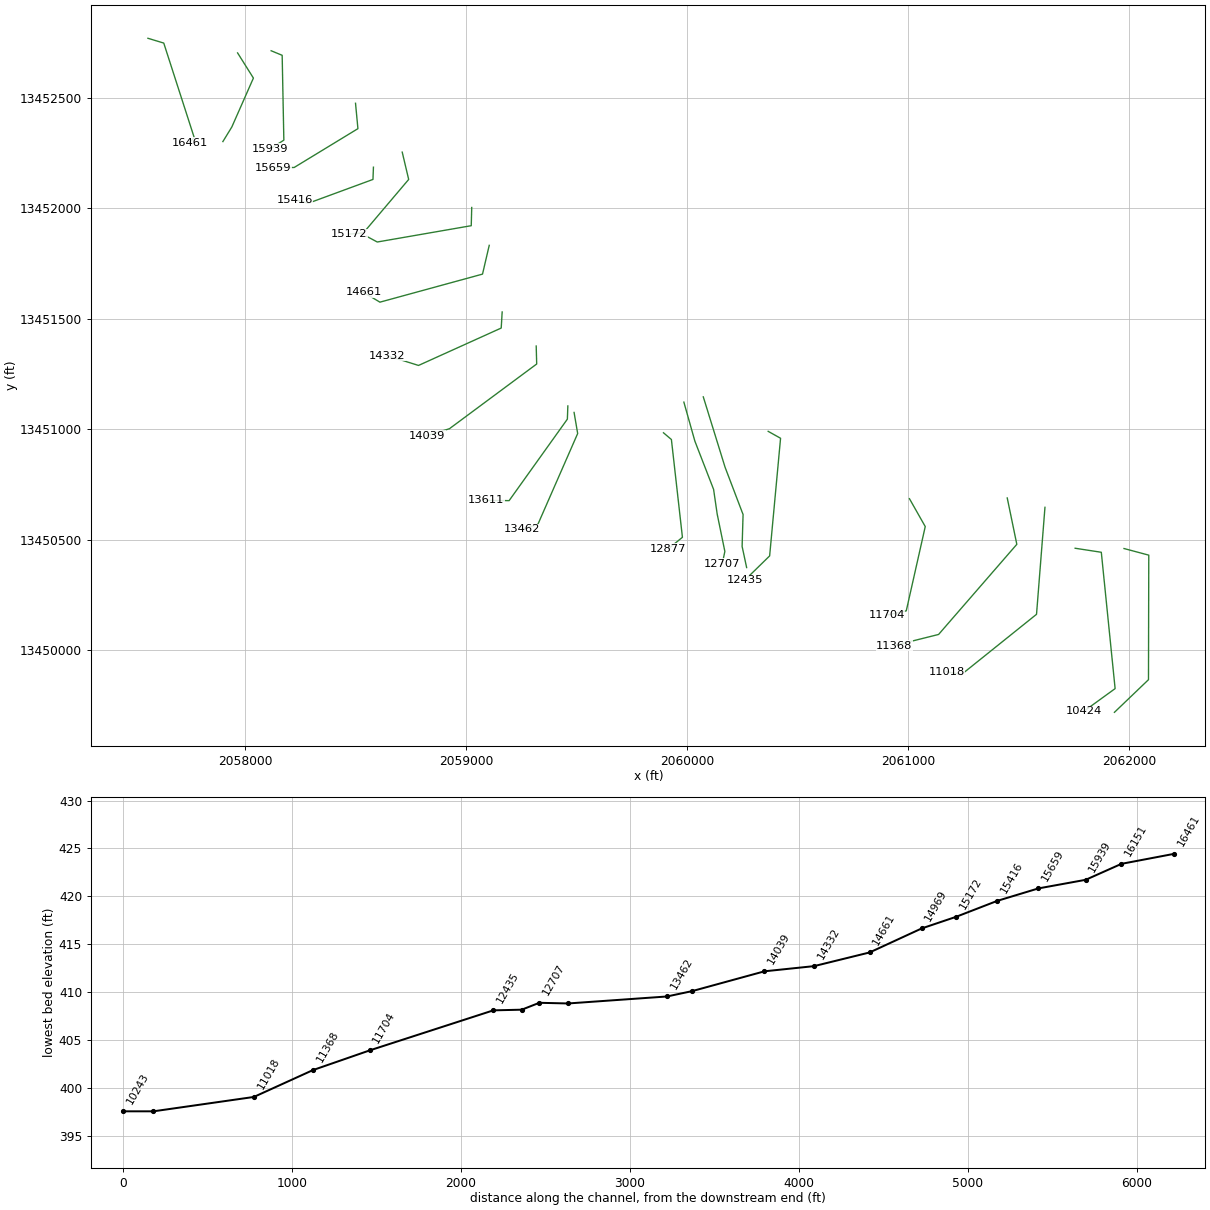
HEC-RAS study UNT 22 in Lagunillas Cr Wtrshd.prj: UNT 22 in Lagunillas Cr Wtrshd Base Level Engineering

--- UNT 22 in Lagunillas Cr Wtrshd.g01 (geometry) --- (continued)

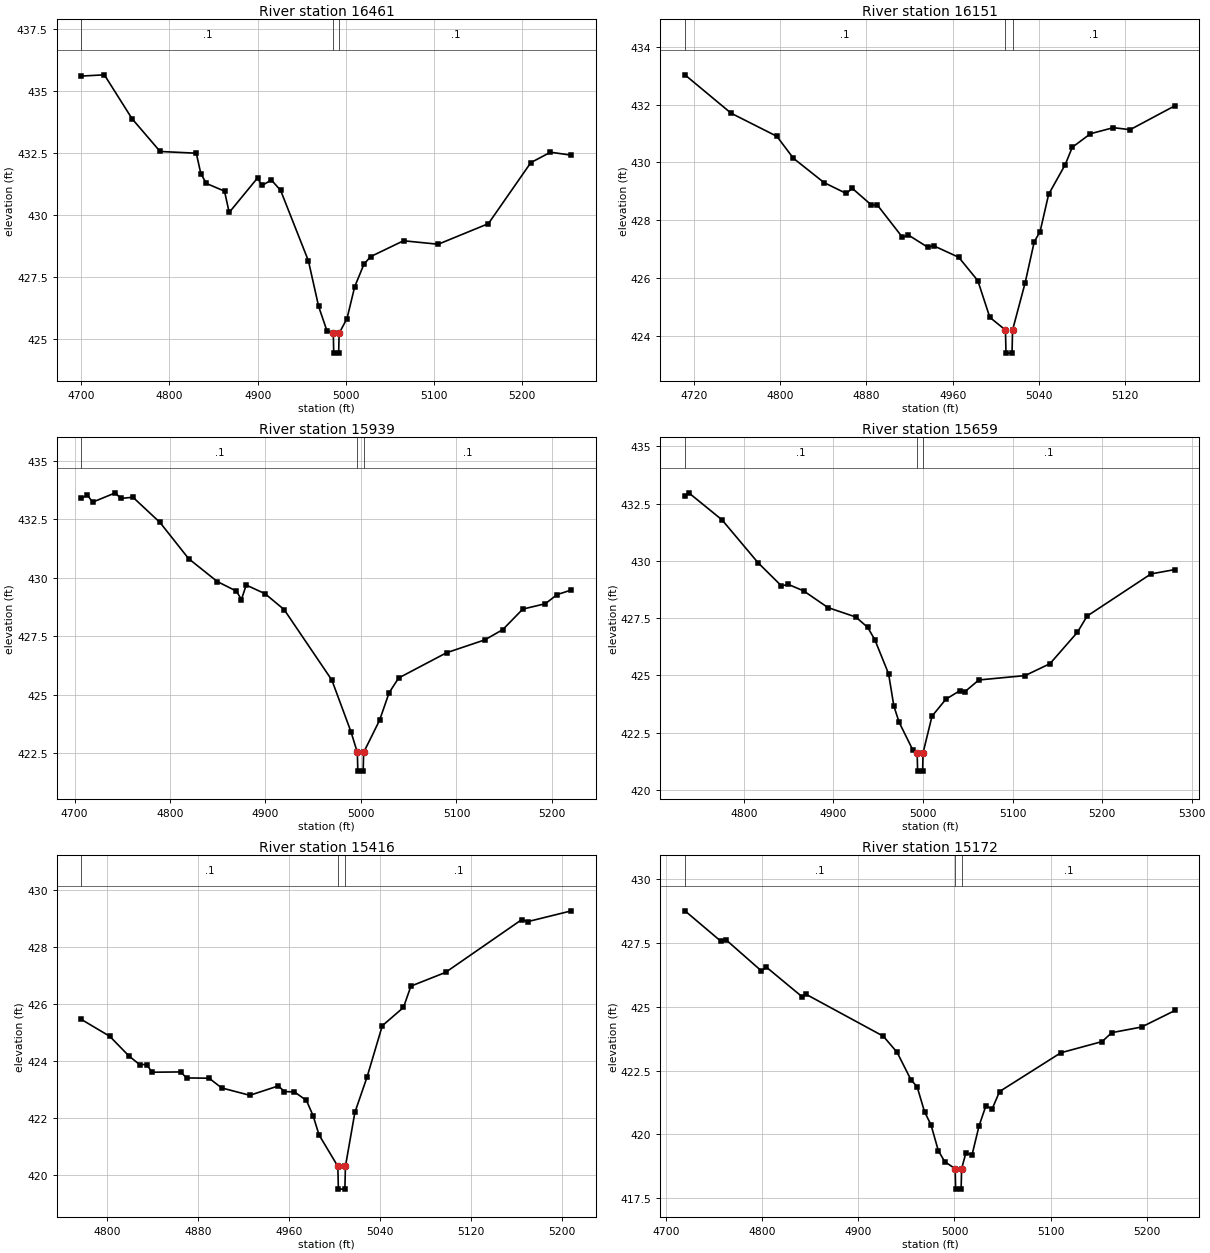
Type RM Length L Ch R = 1,16461,310,310,310
BEGIN DESCRIPTION:
Mapping XS 04d514ba
END DESCRIPTION:
XS GIS Cut Line= 4
      2057560.10     13452770.35      2057631.73     13452748.64
      2057769.53     13452321.13      2057747.82     13452298.33
#Sta/Elev= 30
  4700.2  435.60  4726.2  435.65  4757.6  433.88  4789.4  432.56  4830.4  432.49
  4835.6  431.66  4841.9  431.27  4862.4  430.96  4867.7  430.10  4899.8  431.49
  4905.0  431.19  4915.5  431.41  4926.0  430.99  4957.5  428.15  4969.1  426.31
  4978.5  425.33  4985.7  425.23  4986.2  424.43  4991.8  424.43  4992.3  425.23
  5001.2  425.82  5010.0  427.11  5020.5  428.02  5028.0  428.32  5065.3  428.96
  5104.6  428.82  5161.5  429.65  5209.6  432.11  5231.9  432.53  5255.7  432.41
#Mann=3,-1,0
  4700.2     0.1       0  4985.7    0.07       0  4992.3     0.1       0
Bank Sta=4985.7,4992.3
Exp/Cntr=0.3,0.1

Type RM Length L Ch R = 1,16151,212,212,212
BEGIN DESCRIPTION:
Mapping XS 4b3d6f78
END DESCRIPTION:
XS GIS Cut Line= 4
      2057965.92     13452704.16      2058037.54     13452590.22
      2057939.89     13452368.87      2057899.34     13452302.72
#Sta/Elev= 30
  4711.9  433.03  4754.7  431.70  4797.1  430.90  4812.4  430.14  4840.7  429.30
  4861.4  428.92  4866.9  429.10  4884.7  428.52  4890.2  428.52  4913.5  427.40
  4919.0  427.48  4936.8  427.06  4942.3  427.11  4965.6  426.71  4983.3  425.90
  4994.4  424.63  5008.9  424.19  5009.4  423.39  5015.0  423.39  5015.5  424.19
  5027.1  425.82  5035.6  427.25  5041.0  427.60  5048.9  428.89  5064.3  429.92
  5070.8  430.52  5087.7  430.99  5108.9  431.20  5124.4  431.13  5166.0  431.96
#Mann=3,-1,0
  4711.9     0.1       0  5008.9    0.07       0  5015.5     0.1       0
Bank Sta=5008.9,5015.5
Exp/Cntr=0.3,0.1

Type RM Length L Ch R = 1,15939,280,280,280
BEGIN DESCRIPTION:
Mapping XS b8a91a33
END DESCRIPTION:
XS GIS Cut Line= 4
      2058117.85     13452713.91      2058167.75     13452693.30
      2058175.35     13452309.19      2058111.88     13452268.99
#Sta/Elev= 30
  4707.2  433.40  4713.5  433.54  4718.9  433.24  4742.8  433.64  4748.2  433.40
  4761.2  433.45  4789.5  432.37  4819.5  430.82  4849.5  429.84  4869.5  429.43
  4874.8  429.07  4879.8  429.69  4899.5  429.32  4919.5  428.64  4969.5  425.62
  4989.5  423.41  4996.2  422.52  4996.7  421.72  5002.3  421.72  5002.8  422.52
  5019.5  423.90  5029.5  425.08  5039.5  425.71  5089.6  426.79  5129.6  427.34
  5148.5  427.78  5169.5  428.66  5193.1  428.89  5205.4  429.28  5220.5  429.48
#Mann=3,-1,0
  4707.2     0.1       0  4996.2    0.07       0  5002.8     0.1       0
Bank Sta=4996.2,5002.8
Exp/Cntr=0.3,0.1

Type RM Length L Ch R = 1,15659,243,243,243
BEGIN DESCRIPTION:
Mapping XS 0eea0f24
END DESCRIPTION:
XS GIS Cut Line= 4
      2058499.79     13452476.25      2058510.63     13452361.27
      2058222.00     13452185.49      2058128.24     13452184.43
#Sta/Elev= 30
  4734.2  432.82  4738.5  432.97  4775.6  431.79  4815.8  429.92  4841.9  428.91
  4849.7  428.97  4866.7  428.69  4893.9  427.96  4924.9  427.55  4938.2  427.10
  4946.2  426.56  4961.6  425.07  4967.5  423.66  4973.4  422.95  4988.8  421.73
  4993.5  421.62  4994.0  420.82  4999.6  420.82  5000.1  421.62  5010.1  423.22
  5025.6  423.96  5041.1  424.33  5046.9  424.29  5062.4  424.80  5113.9  424.99
  5141.8  425.51  5172.4  426.88  5183.3  427.59  5254.6  429.43  5281.4  429.62
#Mann=3,-1,0
  4734.2     0.1       0  4993.5    0.07       0  5000.1     0.1       0
Bank Sta=4993.5,5000.1
Exp/Cntr=0.3,0.1

Type RM Length L Ch R = 1,15416,244,244,244
BEGIN DESCRIPTION:
Mapping XS 40941c86
END DESCRIPTION:
XS GIS Cut Line= 4
      2058580.91     13452186.75      2058578.73     13452131.38
      2058286.85     13452023.96      2058224.33     13452040.13
#Sta/Elev= 30
  4777.3  425.47  4802.2  424.88  4819.1  424.19  4828.4  423.89  4834.7  423.89
  4839.4  423.62  4864.5  423.63  4869.8  423.42  4889.6  423.41  4900.6  423.07
  4925.4  422.81  4950.5  423.14  4955.9  422.94  4964.6  422.93  4975.2  422.63
  4981.0  422.10  4986.3  421.42  5002.8  420.32  5003.3  419.52  5009.0  419.52
  5009.5  420.32  5017.8  422.21  5028.5  423.45  5041.9  425.25  5060.5  425.89
  5067.1  426.64  5097.5  427.12  5164.5  428.97  5169.7  428.90  5208.3  429.28
#Mann=3,-1,0
  4777.3     0.1       0  5002.8    0.07       0  5009.5     0.1       0
Bank Sta=5002.8,5009.5
Exp/Cntr=0.3,0.1

Type RM Length L Ch R = 1,15172,203,203,203
BEGIN DESCRIPTION:
Mapping XS 20b3dd21
END DESCRIPTION:
XS GIS Cut Line= 4
      2058711.11     13452255.09      2058740.41     13452131.38
      2058535.33     13451889.41      2058470.27     13451883.99
#Sta/Elev= 30
  4719.7  428.77  4757.0  427.58  4762.2  427.64  4799.3  426.41  4804.4  426.56
  4841.5  425.40  4845.9  425.49  4926.0  423.85  4940.3  423.22  4954.6  422.15
  4961.2  421.86  4968.9  420.88  4975.5  420.38  4983.2  419.36  4989.8  418.93
  5000.7  418.65  5001.2  417.85  5006.9  417.85  5007.4  418.65  5011.8  419.26
  5018.3  419.20  5025.6  420.34  5032.6  421.11  5039.2  421.00  5046.9  421.68
  5110.6  423.20  5153.5  423.64  5163.6  423.99  5194.5  424.21  5229.3  424.86
#Mann=3,-1,0
  4719.7     0.1       0  5000.7    0.07       0  5007.4     0.1       0
Bank Sta=5000.7,5007.4
Exp/Cntr=0.3,0.1

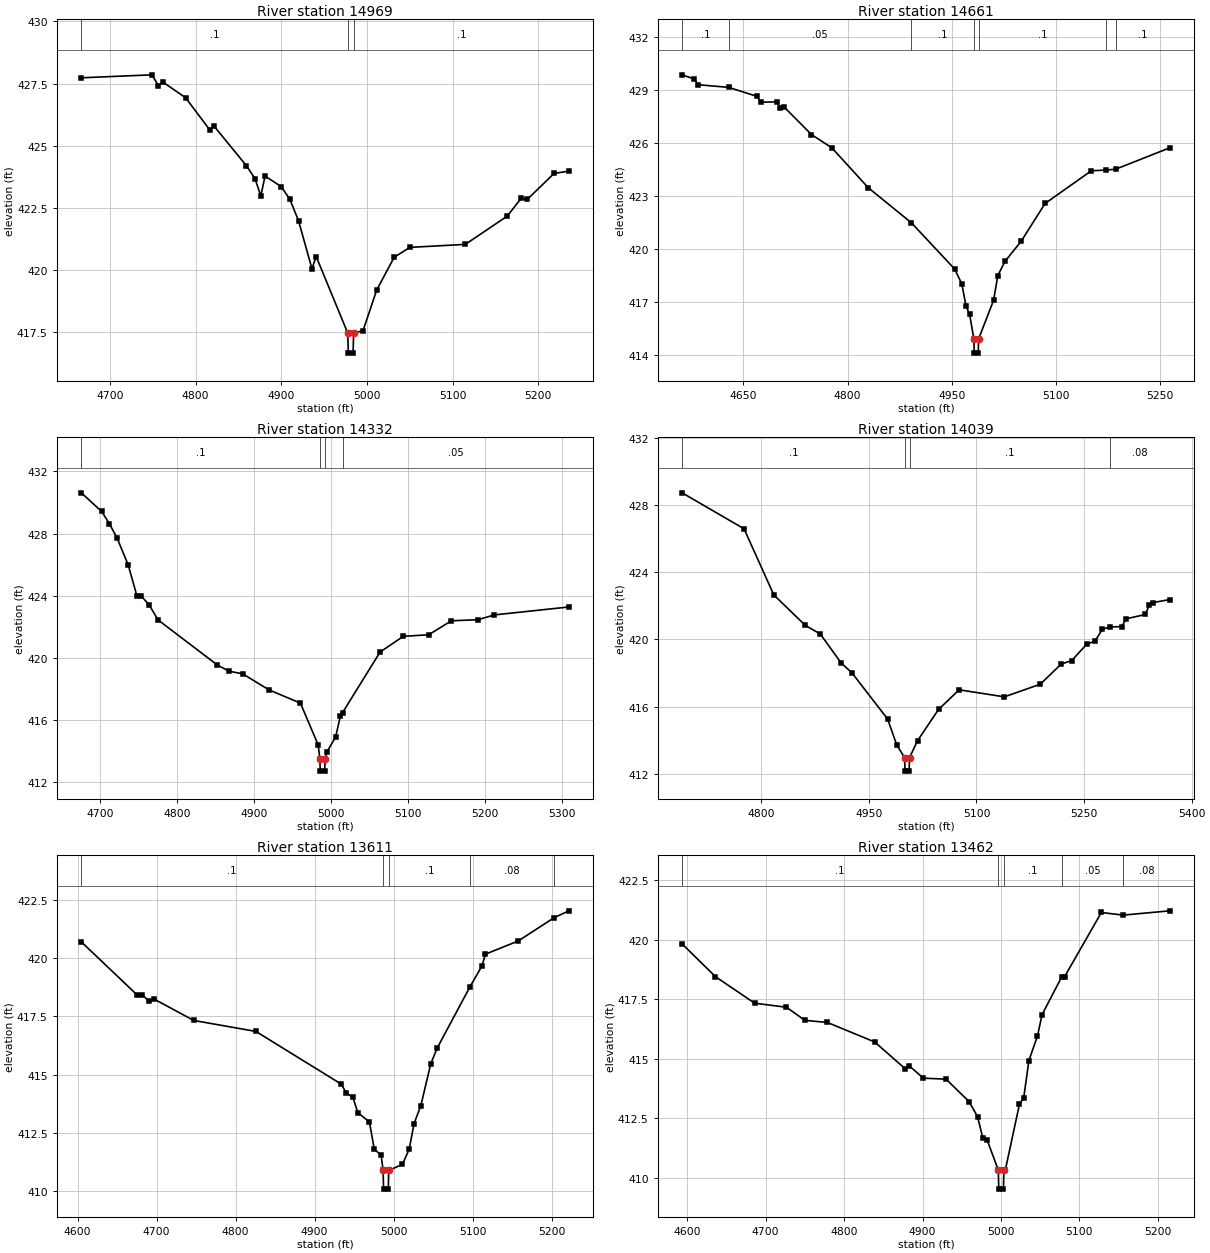
Type RM Length L Ch R = 1,14969,308,308,308
BEGIN DESCRIPTION:
Mapping XS 06cb4304
END DESCRIPTION:
XS GIS Cut Line= 4
      2059025.78     13452004.41      2059023.61     13451921.97
      2058598.27     13451848.18      2058549.71     13451874.08
#Sta/Elev= 30
  4666.5  427.73  4749.0  427.85  4756.6  427.41  4761.6  427.56  4788.2  426.93
  4816.3  425.64  4821.3  425.79  4859.2  424.19  4869.4  423.66  4876.0  422.97
  4881.0  423.77  4899.8  423.35  4910.0  422.83  4920.1  421.97  4935.7  420.04
  4940.7  420.53  4977.6  417.44  4978.1  416.64  4983.8  416.64  4984.3  417.44
  4995.4  417.55  5011.4  419.19  5031.7  420.50  5050.0  420.90  5114.8  421.02
  5163.7  422.16  5179.8  422.87  5187.3  422.84  5218.4  423.88  5235.7  423.97
#Mann=3,-1,0
  4666.5     0.1       0  4977.6    0.07       0  4984.3     0.1       0
Bank Sta=4977.6,4984.3
Exp/Cntr=0.3,0.1

Type RM Length L Ch R = 1,14661,329,329,329
BEGIN DESCRIPTION:
Mapping XS 80e1299a
END DESCRIPTION:
XS GIS Cut Line= 4
      2059104.99     13451832.99      2059074.61     13451702.78
      2058610.20     13451575.83      2058535.39     13451620.72
#Sta/Elev= 30
  4561.7  429.88  4579.4  429.64  4584.5  429.32  4628.7  429.17  4669.6  428.66
  4674.7  428.33  4697.8  428.35  4703.1  428.03  4708.3  428.07  4748.0  426.50
  4777.3  425.75  4829.8  423.49  4891.8  421.51  4954.2  418.89  4964.5  418.05
  4970.6  416.80  4975.8  416.32  4981.9  414.93  4982.4  414.13  4988.2  414.13
  4988.7  414.93  5010.3  417.12  5016.4  418.52  5026.7  419.32  5050.0  420.46
  5084.5  422.60  5151.1  424.45  5172.6  424.49  5186.2  424.54  5264.1  425.75
#Mann=7,-1,0
  4561.7     0.1       0  4628.7    0.05       0  4891.8     0.1       0
  4981.9    0.07       0  4988.7     0.1       0  5172.6    0.05       0
  5186.2     0.1       0
Bank Sta=4981.9,4988.7
Exp/Cntr=0.3,0.1

Type RM Length L Ch R = 1,14332,293,293,293
BEGIN DESCRIPTION:
Mapping XS 80aaa801
END DESCRIPTION:
XS GIS Cut Line= 4
      2059163.59     13451531.39      2059159.25     13451458.64
      2058784.90     13451289.37      2058642.71     13451333.87
#Sta/Elev= 30
  4675.8  430.62  4702.2  429.42  4712.3  428.63  4722.3  427.70  4736.7  425.97
  4748.0  423.97  4753.7  423.97  4764.2  423.38  4775.3  422.44  4852.1  419.54
  4867.7  419.13  4885.0  418.97  4919.4  417.93  4960.1  417.08  4983.2  414.38
  4985.3  413.50  4985.8  412.70  4991.6  412.70  4992.1  413.50  4994.8  413.96
  5005.8  414.90  5011.8  416.22  5014.8  416.47  5063.5  420.37  5093.6  421.38
  5126.5  421.48  5156.0  422.38  5190.4  422.45  5211.8  422.76  5308.5  423.27
#Mann=4,-1,0
  4675.8     0.1       0  4985.3    0.07       0  4992.1     0.1       0
  5014.8    0.05       0
Bank Sta=4985.3,4992.1
Exp/Cntr=0.3,0.1

Type RM Length L Ch R = 1,14039,428,428,428
BEGIN DESCRIPTION:
Mapping XS c613284f
END DESCRIPTION:
XS GIS Cut Line= 4
      2059317.67     13451377.23      2059319.84     13451295.88
      2058924.87     13451002.91      2058822.86     13450971.44
#Sta/Elev= 30
  4689.6  428.72  4775.9  426.58  4817.5  422.64  4861.4  420.83  4882.2  420.32
  4911.4  418.59  4926.1  418.02  4976.1  415.26  4988.7  413.73  4999.8  412.96
  5000.3  412.16  5006.1  412.16  5006.6  412.96  5017.8  413.97  5047.1  415.83
  5075.8  417.00  5138.8  416.58  5188.9  417.33  5218.1  418.53  5232.8  418.74
  5253.6  419.71  5265.3  419.90  5275.5  420.60  5285.5  420.74  5302.9  420.76
  5308.1  421.22  5335.5  421.48  5340.8  422.04  5346.3  422.19  5369.5  422.37
#Mann=4,-1,0
  4689.6     0.1       0  4999.8    0.07       0  5006.6     0.1       0
  5285.5    0.08       0
Bank Sta=4999.8,5006.6
Exp/Cntr=0.3,0.1

Type RM Length L Ch R = 1,13611,149,149,149
BEGIN DESCRIPTION:
Mapping XS edd30cd0
END DESCRIPTION:
XS GIS Cut Line= 4
      2059460.90     13451106.02      2059458.73     13451046.31
      2059195.05     13450677.39      2059090.86     13450678.48
#Sta/Elev= 30
  4604.6  420.69  4675.7  418.40  4681.9  418.42  4690.5  418.14  4696.6  418.24
  4747.0  417.32  4825.7  416.85  4933.8  414.59  4939.9  414.22  4948.5  414.02
  4954.7  413.37  4969.4  412.97  4975.6  411.79  4984.2  411.56  4986.7  410.89
  4987.3  410.09  4993.3  410.09  4993.8  410.89  5011.2  411.15  5019.8  411.81
  5025.9  412.90  5034.5  413.67  5047.0  415.46  5055.4  416.15  5096.8  418.77
  5111.9  419.66  5116.2  420.16  5157.9  420.73  5203.4  421.73  5222.0  422.02
#Mann=5,-1,0
  4604.6     0.1       0  4986.7    0.07       0  4993.8     0.1       0
  5096.8    0.08       0  5203.4    0.05       0
Bank Sta=4986.7,4993.8
Exp/Cntr=0.3,0.1

Type RM Length L Ch R = 1,13462,585,585,585
BEGIN DESCRIPTION:
Mapping XS a9dd245c
END DESCRIPTION:
XS GIS Cut Line= 4
      2059489.11     13451076.66      2059505.38     13450981.21
      2059325.26     13450569.97      2059252.61     13450548.28
#Sta/Elev= 30
  4593.6  419.83  4635.9  418.46  4686.0  417.34  4726.6  417.17  4750.0  416.62
  4778.8  416.53  4839.1  415.71  4877.8  414.59  4883.3  414.70  4901.2  414.19
  4930.0  414.15  4959.2  413.21  4970.1  412.58  4976.8  411.69  4982.3  411.60
  4996.6  410.33  4997.2  409.53  5003.2  409.53  5003.7  410.33  5005.6  410.34
  5023.6  413.10  5029.0  413.37  5035.6  414.93  5046.5  415.96  5052.4  416.86
  5077.2  418.43  5081.2  418.46  5128.0  421.15  5155.8  421.04  5215.2  421.22
#Mann=5,-1,0
  4593.6     0.1       0  4996.6    0.07       0  5003.7     0.1       0
  5077.2    0.05       0  5155.8    0.08       0
Bank Sta=4996.6,5003.7
Exp/Cntr=0.3,0.1

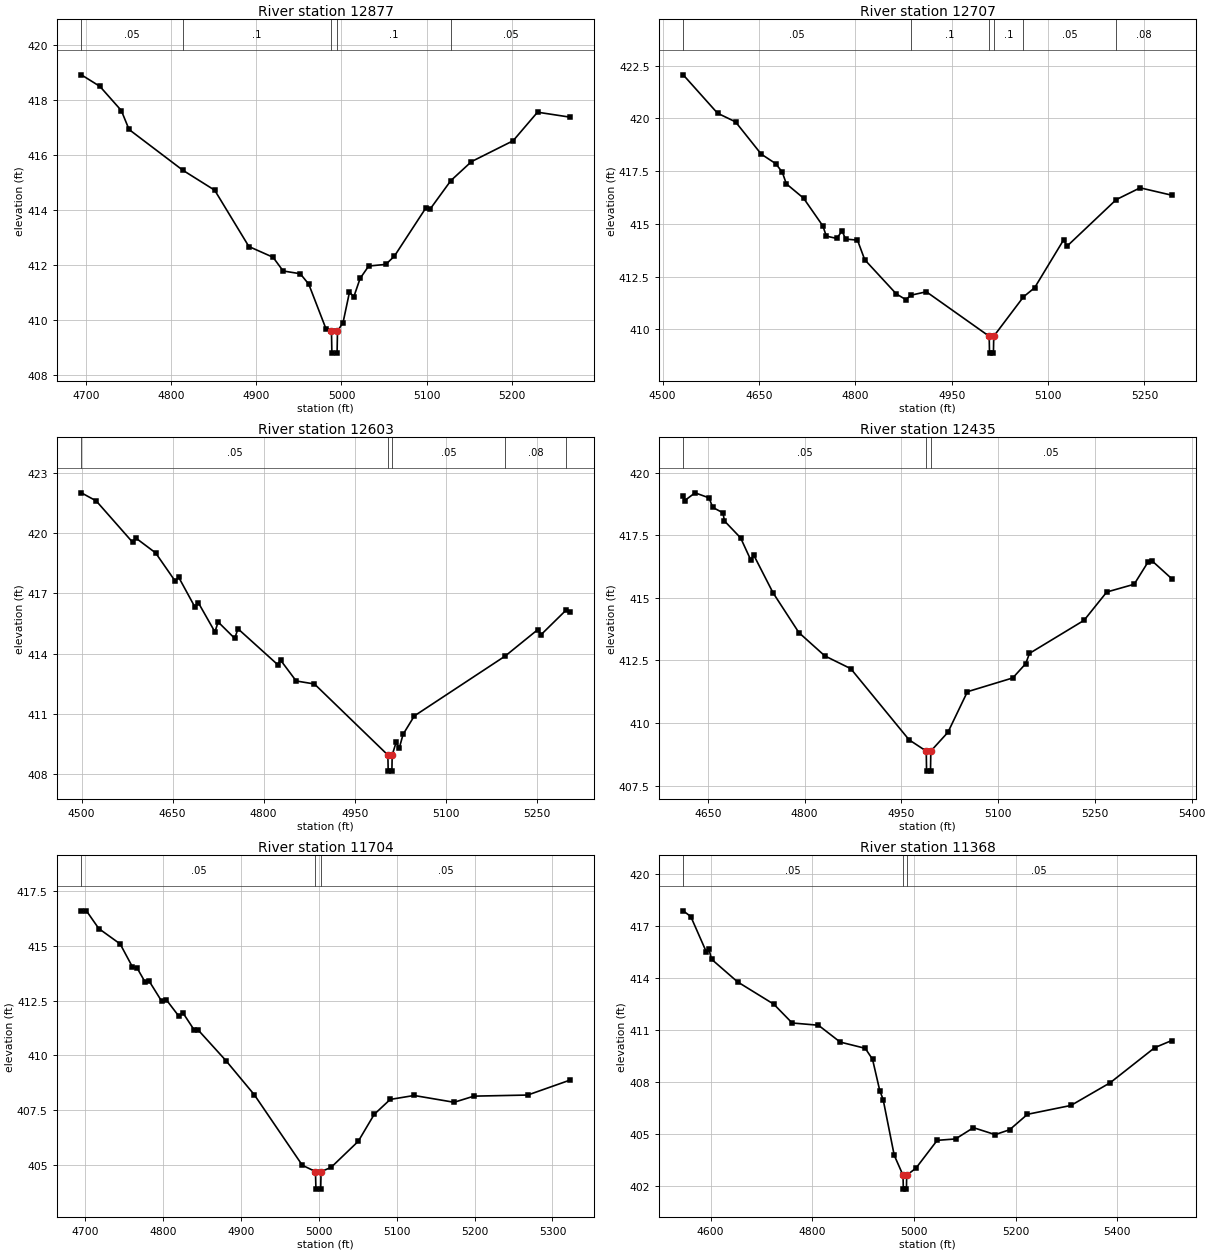
Type RM Length L Ch R = 1,12877,170,170,170
BEGIN DESCRIPTION:
Mapping XS 0ccff65c
END DESCRIPTION:
XS GIS Cut Line= 4
      2059893.83     13450984.48      2059929.65     13450954.08
      2059979.56     13450511.38      2059915.94     13450459.62
#Sta/Elev= 30
  4694.1  418.93  4715.9  418.51  4741.1  417.63  4750.2  416.94  4813.3  415.46
  4850.9  414.73  4891.1  412.68  4919.5  412.29  4931.4  411.79  4951.5  411.69
  4961.5  411.31  4981.7  409.69  4988.2  409.60  4988.7  408.80  4994.8  408.80
  4995.3  409.60  5001.8  409.91  5009.4  411.02  5014.5  410.85  5021.9  411.52
  5032.0  411.97  5052.1  412.03  5062.2  412.33  5099.3  414.09  5104.4  414.05
  5128.6  415.08  5152.8  415.77  5201.8  416.53  5230.5  417.57  5268.6  417.39
#Mann=5,-1,0
  4694.1    0.05       0  4813.3     0.1       0  4988.2    0.07       0
  4995.3     0.1       0  5128.6    0.05       0
Bank Sta=4988.2,4995.3
Exp/Cntr=0.3,0.1

Type RM Length L Ch R = 1,12707,104,104,104
BEGIN DESCRIPTION:
Mapping XS 6de47592
END DESCRIPTION:
XS GIS Cut Line= 6
      2059986.07     13451123.35      2060035.98     13450946.49
      2060120.62     13450728.39      2060136.89     13450616.63
      2060171.62     13450447.36      2060159.83     13450391.64
#Sta/Elev= 30
  4532.1  422.07  4585.5  420.25  4613.5  419.84  4653.5  418.31  4675.9  417.86
  4686.2  417.46  4692.6  416.90  4719.4  416.22  4749.5  414.90  4754.8  414.42
  4771.1  414.31  4779.4  414.67  4784.7  414.28  4803.3  414.23  4814.6  413.30
  4863.7  411.68  4878.4  411.41  4886.9  411.62  4910.5  411.78  5008.3  409.67
  5008.8  408.87  5014.9  408.87  5015.4  409.67  5061.7  411.54  5079.0  411.97
  5124.3  414.25  5129.4  413.94  5206.0  416.15  5243.2  416.71  5292.5  416.36
#Mann=6,-1,0
  4532.1    0.05       0  4886.9     0.1       0  5008.3    0.07       0
  5015.4     0.1       0  5061.7    0.05       0  5206.0    0.08       0
Bank Sta=5008.3,5015.4
Exp/Cntr=0.3,0.1

Type RM Length L Ch R = 1,12603,168,168,168
BEGIN DESCRIPTION:
Mapping XS 1464f1dc
END DESCRIPTION:
XS GIS Cut Line= 5
      2060073.97     13451147.20      2060172.70     13450828.22
      2060254.08     13450614.46      2060249.74     13450470.14
      2060270.18     13450374.42
#Sta/Elev= 30
  4499.7  422.01  4524.1  421.61  4584.1  419.55  4589.4  419.76  4622.0  419.02
  4654.6  417.60  4659.8  417.82  4687.2  416.30  4692.4  416.54  4719.8  415.08
  4725.0  415.58  4752.4  414.76  4757.7  415.24  4822.9  413.46  4828.1  413.67
  4853.6  412.64  4883.7  412.49  5004.7  408.95  5005.2  408.15  5011.3  408.15
  5011.8  408.95  5018.2  409.58  5023.5  409.30  5029.7  409.98  5048.3  410.90
  5197.9  413.88  5251.8  415.20  5256.9  414.94  5298.0  416.16  5304.6  416.06
#Mann=5,-1,0
  4499.7    0.05       0  5004.7    0.03       0  5011.8    0.05       0
  5197.9    0.08       0  5298.0    0.05       0
Bank Sta=5004.7,5011.8
Exp/Cntr=0.3,0.1

Type RM Length L Ch R = 1,12435,731,731,731
BEGIN DESCRIPTION:
Mapping XS c6d8cf98
END DESCRIPTION:
XS GIS Cut Line= 4
      2060367.79     13450990.98      2060423.79     13450959.73
      2060374.31     13450427.17      2060261.06     13450316.53
#Sta/Elev= 30
  4611.9  419.08  4614.2  418.88  4630.2  419.19  4651.9  418.99  4657.6  418.61
  4673.6  418.39  4675.7  418.07  4700.9  417.39  4716.4  416.52  4721.5  416.69
  4751.1  415.20  4791.2  413.61  4831.4  412.68  4871.6  412.17  4962.0  409.33
  4988.6  408.88  4989.1  408.08  4995.2  408.08  4995.7  408.88  5022.2  409.63
  5052.4  411.25  5122.7  411.80  5142.8  412.37  5148.6  412.78  5233.2  414.10
  5268.4  415.23  5310.9  415.54  5332.2  416.42  5339.2  416.46  5369.2  415.76
#Mann=3,-1,0
  4611.9    0.05       0  4988.6    0.03       0  4995.7    0.05       0
Bank Sta=4988.6,4995.7
Exp/Cntr=0.3,0.1

Type RM Length L Ch R = 1,11704,336,336,336
BEGIN DESCRIPTION:
Mapping XS 9d5a3b2b
END DESCRIPTION:
XS GIS Cut Line= 4
      2061007.14     13450686.26      2061078.73     13450559.99
      2060992.80     13450178.48      2060904.25     13450158.94
#Sta/Elev= 30
  4695.5  416.56  4702.0  416.59  4717.9  415.78  4745.3  415.08  4761.1  414.03
  4766.9  413.99  4777.0  413.36  4782.8  413.37  4798.7  412.46  4804.4  412.54
  4820.3  411.80  4826.0  411.93  4840.6  411.14  4845.8  411.14  4881.0  409.76
  4917.5  408.20  4979.0  404.99  4995.9  404.70  4996.5  403.90  5002.6  403.90
  5003.1  404.70  5015.9  404.89  5050.8  406.08  5071.3  407.31  5091.8  407.99
  5122.5  408.17  5173.8  407.86  5199.2  408.14  5268.2  408.19  5322.4  408.87
#Mann=3,-1,0
  4695.5    0.05       0  4995.9    0.03       0  5003.1    0.05       0
Bank Sta=4995.9,5003.1
Exp/Cntr=0.3,0.1

Type RM Length L Ch R = 1,11368,350,350,350
BEGIN DESCRIPTION:
Mapping XS 724cda90
END DESCRIPTION:
XS GIS Cut Line= 4
      2061449.83     13450689.61      2061493.23     13450479.57
      2061139.06     13450071.58      2060938.88     13450021.53
#Sta/Elev= 30
  4546.3  417.87  4561.2  417.54  4591.7  415.51  4596.8  415.66  4602.1  415.08
  4653.1  413.78  4724.6  412.49  4760.6  411.41  4812.3  411.28  4855.1  410.31
  4904.4  409.95  4918.7  409.32  4932.9  407.52  4939.6  407.00  4961.4  403.79
  4978.7  402.64  4979.3  401.84  4985.4  401.84  4985.9  402.64  5004.2  403.05
  5045.9  404.65  5082.0  404.73  5117.2  405.38  5159.9  404.98  5188.4  405.26
  5223.5  406.15  5309.0  406.66  5386.3  407.97  5473.9  409.99  5507.4  410.40
#Mann=3,-1,0
  4546.3    0.05       0  4978.7    0.03       0  4985.9    0.05       0
Bank Sta=4978.7,4985.9
Exp/Cntr=0.3,0.1

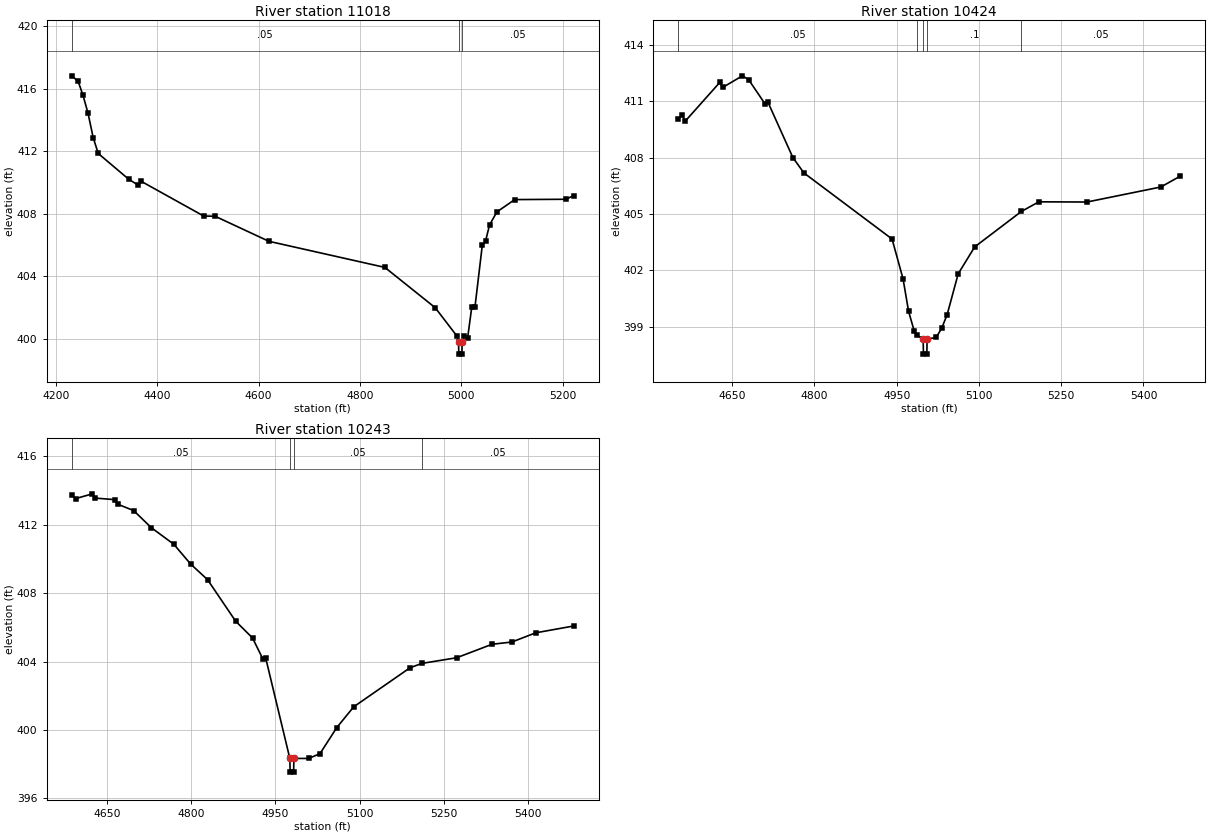
Type RM Length L Ch R = 1,11018,594,594,594
BEGIN DESCRIPTION:
Mapping XS 40502b4d
END DESCRIPTION:
XS GIS Cut Line= 4
      2061620.62     13450647.04      2061582.42     13450162.85
      2061241.71     13449889.41      2061175.56     13449903.51
#Sta/Elev= 30
  4231.7  416.84  4244.2  416.49  4253.8  415.60  4263.8  414.44  4273.9  412.89
  4283.9  411.87  4344.1  410.22  4362.9  409.84  4368.0  410.10  4491.7  407.87
  4514.6  407.85  4620.5  406.25  4849.2  404.58  4948.5  402.00  4991.7  400.17
  4994.5  399.83  4995.0  399.03  5001.1  399.03  5001.7  399.83  5006.1  400.16
  5012.5  400.09  5020.5  402.02  5026.9  402.05  5041.3  405.99  5047.7  406.26
  5055.7  407.30  5070.1  408.13  5105.3  408.92  5206.1  408.94  5221.9  409.18
#Mann=3,-1,0
  4231.7    0.05       0  4994.5    0.03       0  5001.7    0.05       0
Bank Sta=4994.5,5001.7
Exp/Cntr=0.3,0.1

Type RM Length L Ch R = 1,10424,181,181,181
BEGIN DESCRIPTION:
Mapping XS ceb05616
END DESCRIPTION:
XS GIS Cut Line= 4
      2061757.20     13450461.85      2061875.68     13450443.62
      2061938.18     13449826.44      2061796.26     13449723.57
#Sta/Elev= 30
  4551.7  410.06  4559.2  410.25  4564.3  409.93  4627.5  412.00  4632.6  411.73
  4668.7  412.35  4680.2  412.14  4709.9  410.86  4714.9  410.97  4760.7  408.00
  4780.8  407.18  4941.6  403.66  4961.7  401.53  4971.7  399.81  4981.8  398.78
  4987.8  398.53  4998.3  398.33  4998.8  397.53  5005.0  397.53  5005.5  398.33
  5022.0  398.42  5032.0  398.90  5042.1  399.64  5062.2  401.81  5092.3  403.24
  5177.5  405.13  5209.3  405.64  5297.0  405.63  5431.7  406.43  5467.2  407.01
#Mann=5,-1,0
  4551.7    0.05       0  4987.8     0.1       0  4998.3    0.07       0
  5005.5     0.1       0  5177.5    0.05       0
Bank Sta=4998.3,5005.5
Exp/Cntr=0.3,0.1

Type RM Length L Ch R = 1,10243,299,299,299
BEGIN DESCRIPTION:
Mapping XS c76bdca7
END DESCRIPTION:
XS GIS Cut Line= 4
      2061978.59     13450460.54      2062090.53     13450430.60
      2062089.22     13449866.80      2061935.10     13449719.16
#Sta/Elev= 30
  4587.8  413.75  4594.7  413.53  4624.5  413.81  4629.6  413.56  4664.5  413.47
  4669.7  413.20  4697.9  412.83  4729.3  411.83  4769.3  410.86  4799.3  409.70
  4829.3  408.79  4879.3  406.36  4909.3  405.38  4927.6  404.16  4932.6  404.23
  4975.7  398.33  4976.2  397.53  4982.4  397.53  4982.9  398.33  5009.3  398.33
  5029.3  398.61  5059.3  400.14  5089.3  401.35  5189.3  403.63  5210.5  403.89
  5272.4  404.22  5335.4  405.01  5370.6  405.14  5413.1  405.68  5480.9  406.08
#Mann=4,-1,0
  4587.8    0.05       0  4975.7    0.07       0  4982.9    0.05       0
  5210.5    0.05       0
Bank Sta=4975.7,4982.9
Exp/Cntr=0.3,0.1