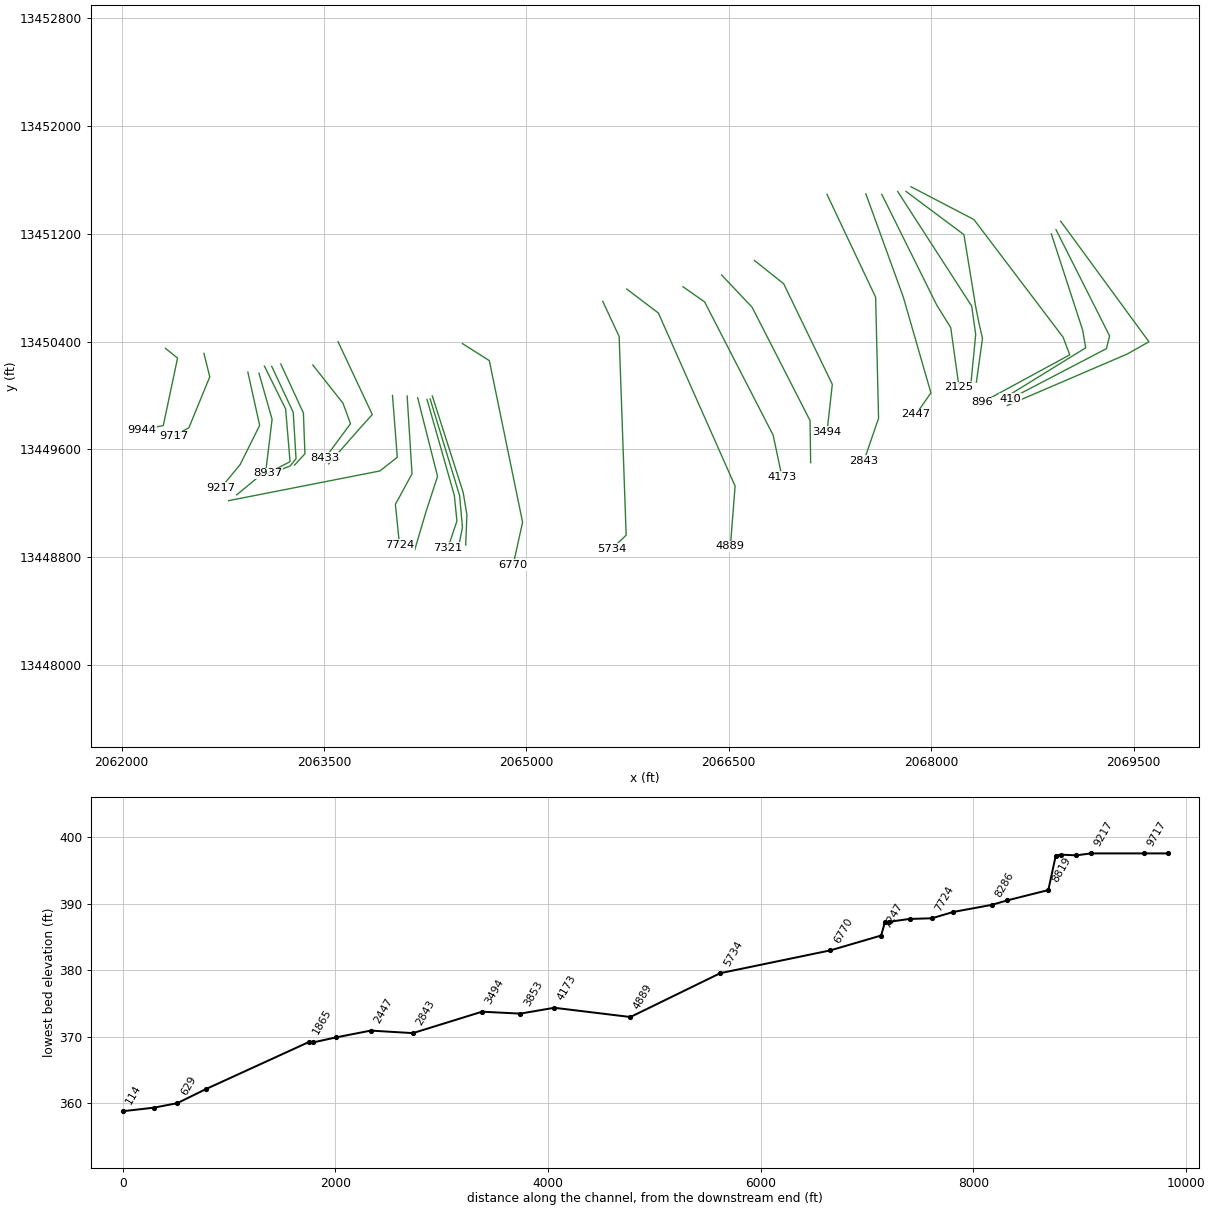
HEC-RAS study UNT 22 in Lagunillas Cr Wtrshd.prj: UNT 22 in Lagunillas Cr Wtrshd Base Level Engineering

--- UNT 22 in Lagunillas Cr Wtrshd.g01 (geometry) --- (continued)

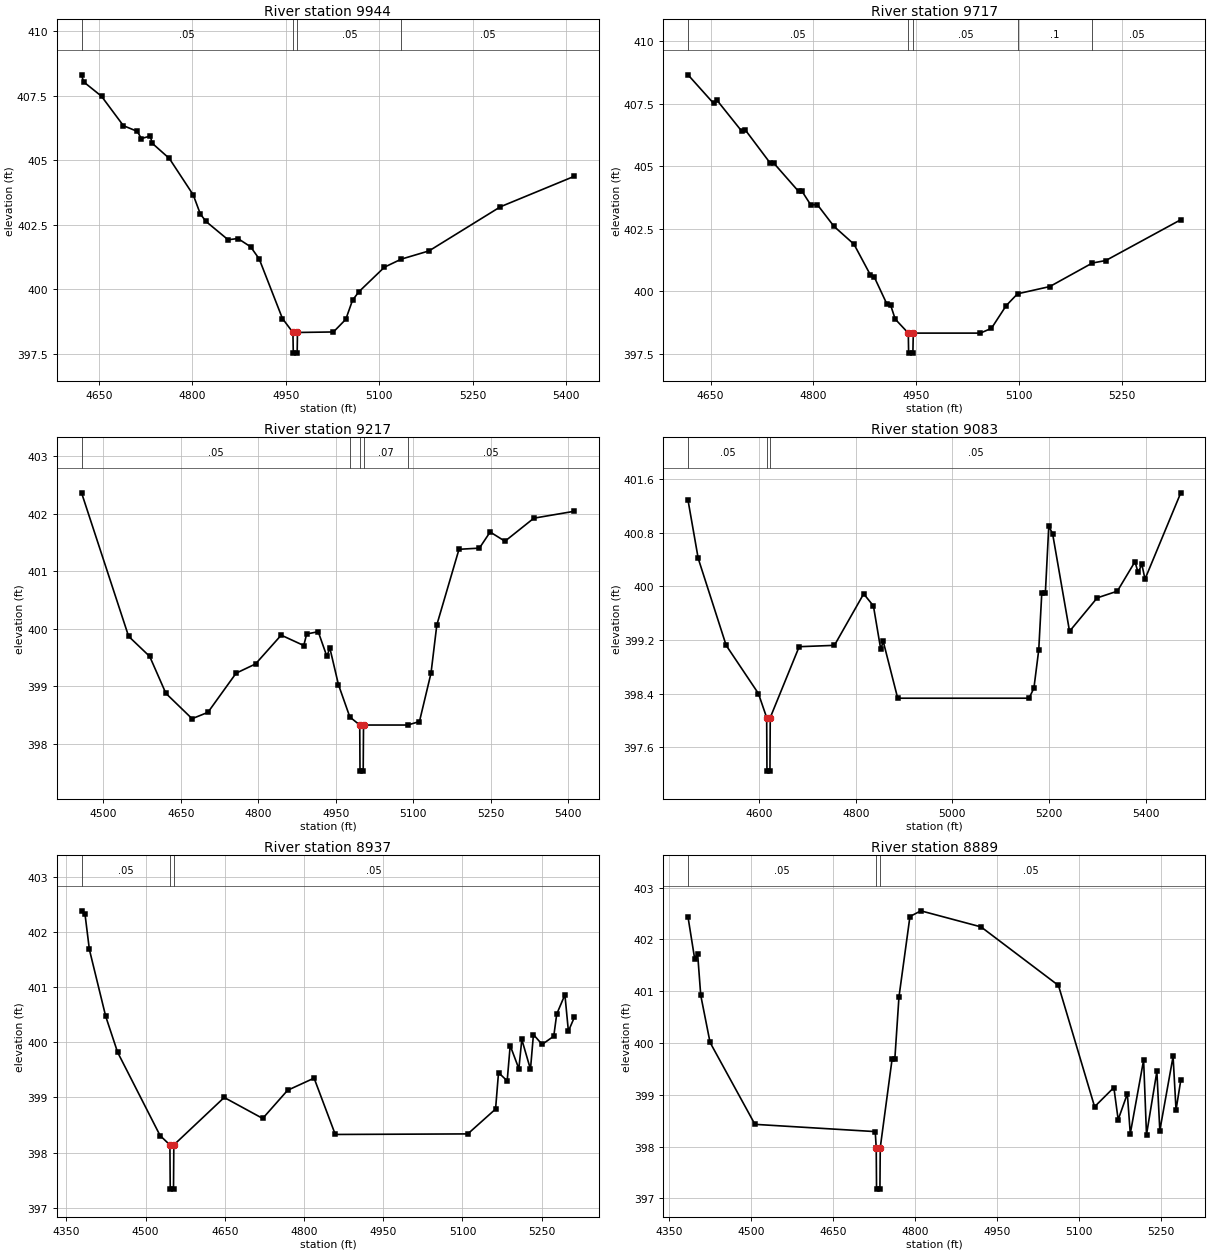
Type RM Length L Ch R = 1,9944,227,227,227
BEGIN DESCRIPTION:
Mapping XS 75287617
END DESCRIPTION:
XS GIS Cut Line= 4
      2062325.35     13450350.29      2062414.74     13450277.39
      2062308.84     13449776.52      2062148.64     13449746.38
#Sta/Elev= 30
  4622.4  408.31  4625.6  408.04  4654.4  407.48  4689.5  406.34  4711.8  406.12
  4718.3  405.84  4732.6  405.94  4735.7  405.66  4763.2  405.07  4801.5  403.66
  4812.9  402.92  4822.0  402.63  4857.5  401.92  4873.1  401.97  4893.5  401.65
  4907.3  401.18  4944.6  398.87  4961.4  398.33  4962.0  397.53  4968.2  397.53
  4968.7  398.33  5026.4  398.35  5046.2  398.84  5057.0  399.58  5067.3  399.91
  5108.2  400.86  5135.1  401.17  5179.7  401.49  5294.3  403.20  5412.7  404.38
#Mann=4,-1,0
  4622.4    0.05       0  4961.4    0.07       0  4968.7    0.05       0
  5135.1    0.05       0
Bank Sta=4961.4,4968.7
Exp/Cntr=0.3,0.1

Type RM Length L Ch R = 1,9717,500,500,500
BEGIN DESCRIPTION:
Mapping XS a7c73f75
END DESCRIPTION:
XS GIS Cut Line= 4
      2062610.19     13450312.84      2062653.46     13450138.50
      2062498.95     13449760.90      2062384.35     13449696.65
#Sta/Elev= 30
  4617.2  408.65  4654.5  407.51  4659.6  407.63  4695.8  406.39  4701.0  406.44
  4737.2  405.12  4742.4  405.12  4778.6  403.99  4783.7  403.99  4796.1  403.46
  4806.0  403.46  4830.0  402.60  4859.4  401.88  4883.4  400.65  4888.8  400.58
  4907.4  399.49  4912.8  399.45  4919.5  398.89  4938.6  398.33  4939.1  397.53
  4945.3  397.53  4945.9  398.33  5043.7  398.33  5059.9  398.52  5081.5  399.43
  5098.0  399.90  5145.1  400.19  5207.1  401.13  5226.8  401.23  5336.2  402.86
#Mann=5,-1,0
  4617.2    0.05       0  4938.6   0.033       0  4945.9    0.05       0
  5098.0     0.1       0  5207.1    0.05       0
Bank Sta=4938.6,4945.9
Exp/Cntr=0.3,0.1

Type RM Length L Ch R = 1,9217,134,134,134
BEGIN DESCRIPTION:
Mapping XS 949b5810
END DESCRIPTION:
XS GIS Cut Line= 4
      2062935.72     13450173.92      2063023.25     13449778.26
      2062878.29     13449486.59      2062736.04     13449314.51
#Sta/Elev= 30
  4457.6  402.36  4548.7  399.87  4589.6  399.52  4620.9  398.88  4671.6  398.44
  4702.3  398.55  4756.9  399.23  4794.5  399.39  4844.2  399.89  4887.9  399.71
  4893.5  399.91  4915.9  399.95  4932.7  399.52  4938.3  399.67  4955.1  399.03
  4977.1  398.47  4996.3  398.33  4996.8  397.53  5003.0  397.53  5003.6  398.33
  5089.0  398.33  5111.9  398.39  5134.3  399.23  5145.6  400.07  5188.5  401.38
  5228.0  401.40  5248.8  401.68  5277.5  401.52  5333.5  401.92  5411.8  402.04
#Mann=5,-1,0
  4457.6    0.05       0  4977.1    0.07       0  4996.3    0.07       0
  5003.6    0.07       0  5089.0    0.05       0
Bank Sta=4996.3,5003.6
Exp/Cntr=0.3,0.1

Type RM Length L Ch R = 1,9083,146,146,146
BEGIN DESCRIPTION:
Mapping XS 23fab010
END DESCRIPTION:
XS GIS Cut Line= 4
      2063018.18     13450165.26      2063115.27     13449823.40
      2063069.26     13449441.45      2062853.26     13449262.47
#Sta/Elev= 30
  4452.4  401.29  4473.5  400.42  4531.4  399.12  4598.2  398.40  4615.3  398.04
  4615.9  397.24  4622.1  397.24  4622.7  398.04  4682.6  399.10  4755.6  399.12
  4816.2  399.89  4836.4  399.71  4851.6  399.06  4856.7  399.18  4886.7  398.33
  5158.7  398.33  5168.8  398.48  5178.8  399.05  5185.1  399.90  5192.5  399.90
  5199.6  400.90  5207.5  400.79  5242.6  399.33  5299.9  399.83  5341.6  399.93
  5378.1  400.37  5384.6  400.21  5392.4  400.33  5398.9  400.11  5473.0  401.40
#Mann=3,-1,0
  4452.4    0.05       0  4615.3   0.033       0  4622.7    0.05       0
Bank Sta=4615.3,4622.7
Exp/Cntr=0.3,0.1

Type RM Length L Ch R = 1,8937,48,48,48
BEGIN DESCRIPTION:
Mapping XS 16f91f67
END DESCRIPTION:
XS GIS Cut Line= 4
      2063058.39     13450218.26      2063215.53     13449900.44
      2063248.51     13449508.95      2063084.28     13449422.53
#Sta/Elev= 30
  4378.8  402.38  4385.2  402.33  4393.6  401.68  4424.5  400.47  4447.0  399.82
  4527.5  398.31  4546.1  398.14  4546.7  397.34  4552.9  397.34  4553.5  398.14
  4648.9  399.00  4721.8  398.62  4768.9  399.13  4819.1  399.35  4859.2  398.33
  5110.1  398.34  5162.7  398.79  5168.3  399.45  5184.7  399.30  5190.4  399.94
  5206.8  399.52  5212.4  400.05  5228.8  399.51  5234.4  400.14  5250.8  399.96
  5272.9  400.11  5278.5  400.51  5294.0  400.86  5300.6  400.20  5311.8  400.45
#Mann=3,-1,0
  4378.8    0.05       0  4546.1   0.035       0  4553.5    0.05       0
Bank Sta=4546.1,4553.5
Exp/Cntr=0.3,0.1

Type RM Length L Ch R = 1,8889,70,70,70
BEGIN DESCRIPTION:
Mapping XS 55275577
END DESCRIPTION:
XS GIS Cut Line= 5
      2063112.64     13450216.11      2063271.95     13449875.26
      2063292.78     13449530.65      2063249.23     13449476.80
      2063145.04     13449435.55
#Sta/Elev= 30
  4384.3  402.43  4396.4  401.63  4401.9  401.72  4407.6  400.92  4424.7  400.01
  4506.9  398.43  4727.3  398.29  4729.1  397.98  4729.7  397.18  4735.9  397.18
  4736.5  397.98  4758.2  399.69  4763.2  399.69  4770.8  400.89  4790.9  402.44
  4810.9  402.55  4921.1  402.24  5063.0  401.11  5129.2  398.77  5164.5  399.14
  5172.4  398.52  5189.2  399.02  5194.6  398.25  5219.0  399.67  5224.3  398.23
  5243.3  399.45  5248.7  398.31  5273.0  399.74  5278.4  398.71  5287.1  399.28
#Mann=3,-1,0
  4384.3    0.05       0  4729.1    0.03       0  4736.5    0.05       0
Bank Sta=4729.1,4736.5
Exp/Cntr=0.3,0.1

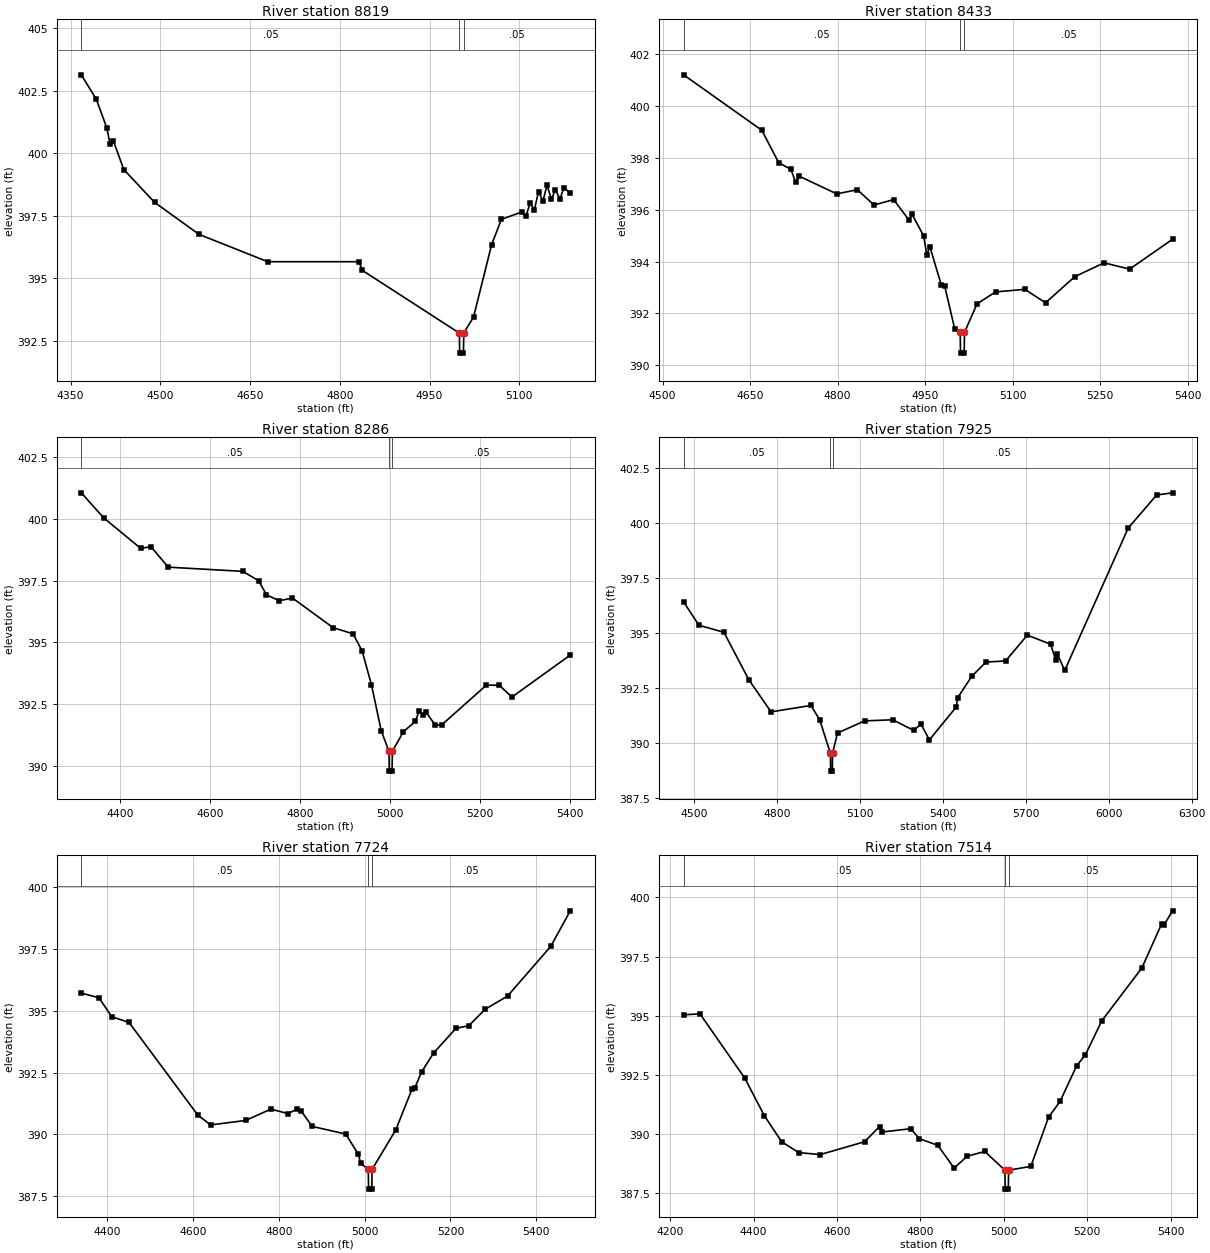
Type RM Length L Ch R = 1,8819,386,386,386
BEGIN DESCRIPTION:
Mapping XS d0c7cd63
END DESCRIPTION:
XS GIS Cut Line= 4
      2063179.91     13450233.49      2063347.47     13449870.06
      2063358.75     13449567.10      2063281.81     13449483.34
#Sta/Elev= 30
  4368.0  403.13  4393.0  402.15  4410.4  401.02  4415.9  400.38  4421.4  400.50
  4438.9  399.35  4490.3  398.04  4564.7  396.76  4679.4  395.67  4832.2  395.67
  4837.2  395.33  4999.7  392.82  5000.3  392.02  5006.5  392.02  5007.1  392.82
  5023.4  393.46  5053.5  396.34  5069.9  397.36  5103.6  397.65  5111.0  397.49
  5117.8  398.00  5125.2  397.75  5132.0  398.47  5139.4  398.09  5146.2  398.73
  5153.6  398.16  5160.3  398.55  5167.7  398.17  5174.5  398.62  5185.1  398.41
#Mann=3,-1,0
  4368.0    0.05       0  4999.7    0.03       0  5007.1    0.05       0
Bank Sta=4999.7,5007.1
Exp/Cntr=0.3,0.1

Type RM Length L Ch R = 1,8433,147,147,147
BEGIN DESCRIPTION:
Mapping XS 83ff12d5
END DESCRIPTION:
XS GIS Cut Line= 4
      2063417.50     13450225.99      2063640.53     13449942.97
      2063696.52     13449790.62      2063509.33     13449536.83
#Sta/Elev= 30
  4536.0  401.20  4670.1  399.06  4699.0  397.81  4719.8  397.56  4727.9  397.06
  4734.3  397.29  4798.4  396.61  4833.7  396.77  4862.5  396.18  4895.9  396.39
  4922.3  395.60  4927.6  395.82  4947.4  394.99  4952.8  394.27  4958.1  394.57
  4977.9  393.08  4983.3  393.07  5000.7  391.40  5010.0  391.27  5010.6  390.47
  5016.9  390.47  5017.4  391.27  5038.9  392.37  5070.7  392.83  5120.9  392.93
  5156.3  392.41  5206.5  393.42  5256.6  393.95  5300.5  393.71  5374.0  394.86
#Mann=3,-1,0
  4536.0    0.05       0  5010.0    0.03       0  5017.4    0.05       0
Bank Sta=5010,5017.4
Exp/Cntr=0.3,0.1

Type RM Length L Ch R = 1,8286,361,361,361
BEGIN DESCRIPTION:
Mapping XS acd465eb
END DESCRIPTION:
XS GIS Cut Line= 4
      2063604.12     13450399.61      2063857.98     13449858.33
      2063761.62     13449751.56      2063534.67     13449492.48
#Sta/Elev= 30
  4314.3  401.06  4363.6  400.05  4446.2  398.81  4469.0  398.88  4507.2  398.05
  4672.8  397.88  4708.2  397.50  4725.5  396.93  4753.9  396.69  4783.3  396.80
  4873.5  395.60  4917.8  395.35  4937.9  394.66  4958.8  393.28  4980.5  391.42
  4997.7  390.59  4998.3  389.79  5004.6  389.79  5005.1  390.59  5029.8  391.39
  5056.0  391.80  5064.9  392.24  5072.5  392.06  5079.1  392.20  5100.9  391.64
  5115.2  391.67  5213.9  393.27  5242.4  393.27  5270.8  392.79  5400.4  394.49
#Mann=3,-1,0
  4314.3    0.05       0  4997.7    0.03       0  5005.1    0.05       0
Bank Sta=4997.7,5005.1
Exp/Cntr=0.3,0.1

Type RM Length L Ch R = 1,7925,201,201,201
BEGIN DESCRIPTION:
Mapping XS fb6be361
END DESCRIPTION:
XS GIS Cut Line= 4
      2064007.77     13450000.32      2064043.13     13449541.18
      2063914.66     13449439.79      2062792.52     13449219.06
#Sta/Elev= 30
  4463.1  396.41  4518.6  395.35  4608.9  395.03  4699.1  392.87  4779.4  391.42
  4923.6  391.71  4955.4  391.05  4994.0  389.53  4994.5  388.73  5000.8  388.73
  5001.4  389.53  5019.6  390.46  5117.5  391.01  5219.4  391.06  5294.6  390.58
  5321.3  390.86  5351.9  390.15  5448.8  391.64  5453.9  392.06  5505.3  393.04
  5556.7  393.68  5627.1  393.73  5705.7  394.90  5790.1  394.49  5808.5  393.77
  5813.6  394.06  5841.1  393.30  6070.5  399.76  6173.3  401.26  6230.9  401.36
#Mann=3,-1,0
  4463.1    0.05       0  4994.0    0.03       0  5001.4    0.05       0
Bank Sta=4994,5001.4
Exp/Cntr=0.3,0.1

Type RM Length L Ch R = 1,7724,210,210,210
BEGIN DESCRIPTION:
Mapping XS 73a08c70
END DESCRIPTION:
XS GIS Cut Line= 4
      2064116.28     13449995.96      2064152.45     13449418.60
      2064029.19     13449191.17      2064059.81     13448889.60
#Sta/Elev= 30
  4339.2  395.72  4380.2  395.53  4410.3  394.76  4450.4  394.53  4610.7  390.78
  4640.7  390.38  4722.3  390.56  4781.0  391.02  4821.1  390.84  4841.1  391.01
  4851.2  390.96  4877.4  390.32  4955.9  390.01  4985.1  389.19  4990.8  388.82
  5008.3  388.58  5009.1  387.78  5016.5  387.78  5017.3  388.58  5072.5  390.18
  5110.6  391.84  5116.3  391.86  5132.5  392.52  5160.6  393.29  5212.7  394.29
  5242.9  394.40  5280.7  395.06  5333.3  395.60  5433.9  397.61  5479.5  399.05
#Mann=3,-1,0
  4339.2    0.05       0  5008.3    0.03       0  5017.3    0.05       0
Bank Sta=5008.3,5017.3
Exp/Cntr=0.3,0.1

Type RM Length L Ch R = 1,7514,193,193,193
BEGIN DESCRIPTION:
Mapping XS dd04fb64
END DESCRIPTION:
XS GIS Cut Line= 4
      2064194.40     13449982.96      2064341.69     13449399.51
      2064256.62     13449139.09      2064172.71     13448854.52
#Sta/Elev= 30
  4232.3  395.04  4271.5  395.08  4378.8  392.37  4426.2  390.77  4467.4  389.68
  4508.7  389.22  4560.2  389.14  4666.1  389.68  4702.0  390.32  4707.2  390.09
  4776.8  390.23  4797.5  389.81  4841.8  389.53  4880.9  388.57  4912.4  389.07
  4954.5  389.27  5002.6  388.48  5003.4  387.68  5010.8  387.68  5011.6  388.48
  5064.9  388.64  5107.5  390.72  5134.9  391.38  5174.8  392.89  5195.7  393.35
  5234.8  394.78  5331.2  397.02  5378.5  398.88  5383.7  398.82  5404.7  399.43
#Mann=3,-1,0
  4232.3    0.05       0  5002.6    0.03       0  5011.6    0.05       0
Bank Sta=5002.6,5011.6
Exp/Cntr=0.3,0.1

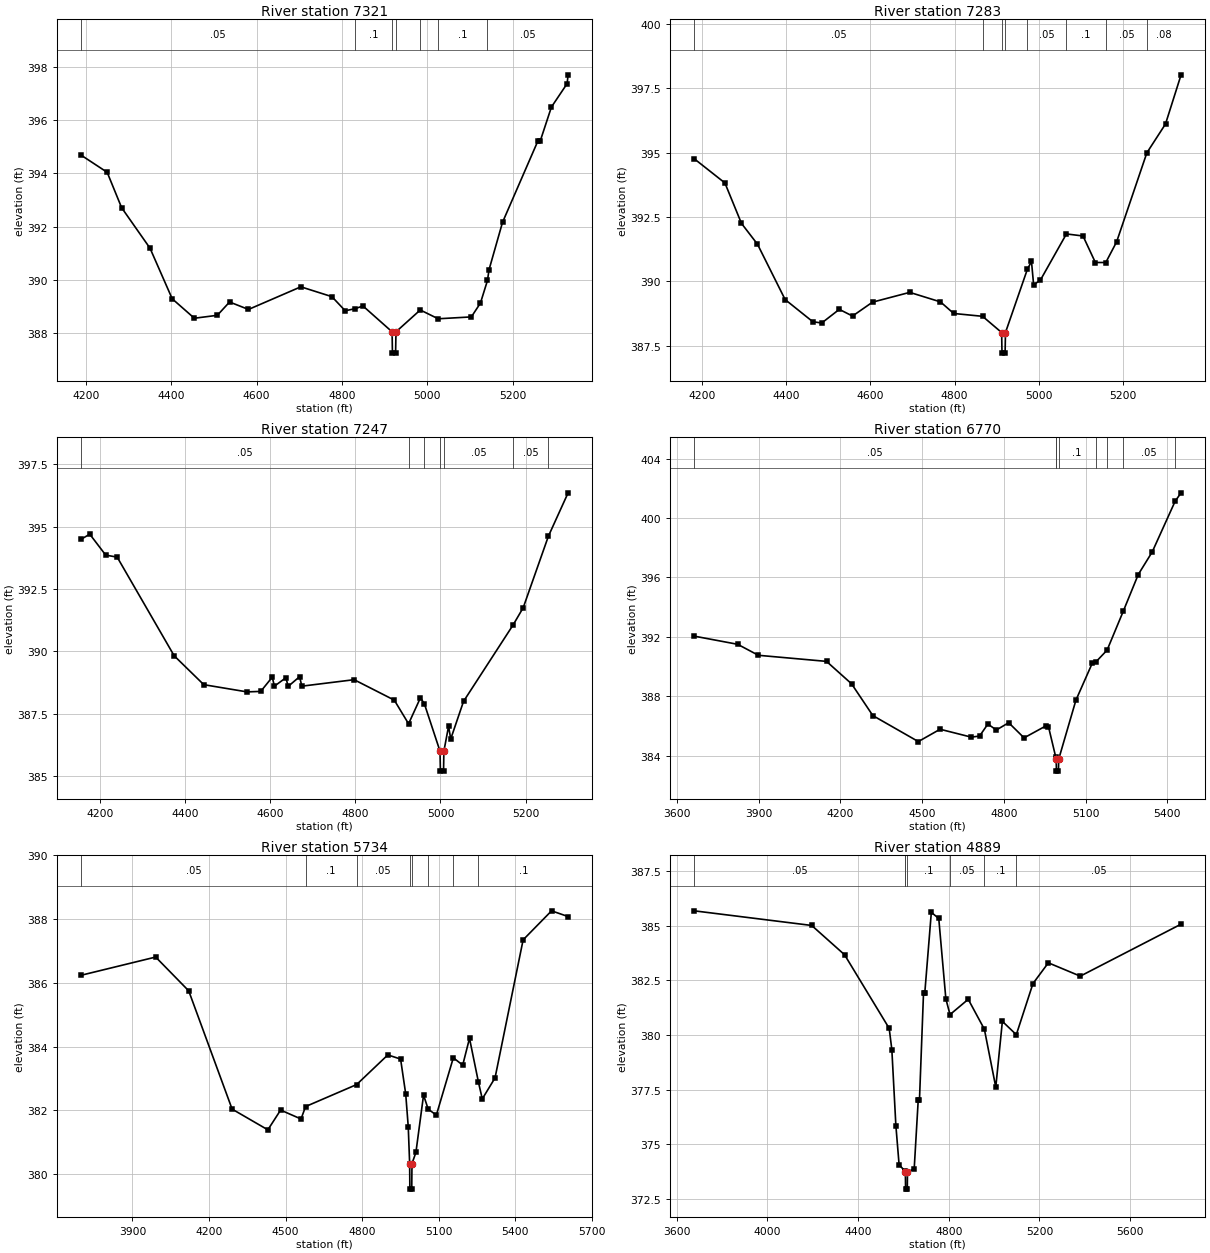
Type RM Length L Ch R = 1,7321,38,38,38
BEGIN DESCRIPTION:
Mapping XS 4171b872
END DESCRIPTION:
XS GIS Cut Line= 4
      2064263.84     13449969.96      2064466.22     13449257.32
      2064485.32     13449068.09      2064418.82     13448869.23
#Sta/Elev= 30
  4189.0  394.68  4249.7  394.04  4283.6  392.71  4350.1  391.19  4402.1  389.29
  4454.0  388.56  4507.8  388.67  4536.5  389.17  4580.8  388.89  4703.5  389.74
  4776.3  389.37  4807.5  388.84  4830.7  388.92  4849.1  389.02  4917.3  388.05
  4918.1  387.25  4925.5  387.25  4926.4  388.05  4983.3  388.87  5025.3  388.54
  5103.0  388.61  5124.3  389.13  5140.8  389.98  5144.4  390.38  5176.0  392.16
  5259.0  395.22  5264.3  395.21  5290.6  396.49  5327.4  397.37  5329.7  397.70
#Mann=7,-1,0
  4189.0    0.05       0  4830.7     0.1       0  4917.3    0.03       0
  4926.4     0.1       0  4983.3    0.05       0  5025.3     0.1       0
  5140.8    0.05       0
Bank Sta=4917.3,4926.4
Exp/Cntr=0.3,0.1

Type RM Length L Ch R = 1,7283,36,36,36
BEGIN DESCRIPTION:
Mapping XS c81d0351
END DESCRIPTION:
XS GIS Cut Line= 4
      2064286.53     13449974.78      2064505.28     13449256.03
      2064526.12     13449019.05      2064492.26     13448855.00
#Sta/Elev= 30
  4181.4  394.76  4254.3  393.82  4293.6  392.25  4331.7  391.44  4397.4  389.29
  4463.1  388.43  4484.3  388.38  4526.1  388.91  4557.5  388.65  4605.0  389.19
  4693.4  389.57  4766.5  389.20  4797.9  388.75  4866.5  388.64  4911.8  388.01
  4912.6  387.21  4920.0  387.21  4920.9  388.01  4973.0  390.47  4982.7  390.77
  4987.8  389.86  5004.0  390.05  5065.7  391.84  5105.1  391.76  5134.5  390.73
  5159.2  390.73  5184.9  391.53  5256.8  394.99  5301.1  396.11  5338.1  398.02
#Mann=8,-1,0
  4181.4    0.05       0  4866.5     0.1       0  4911.8    0.03       0
  4920.9     0.1       0  4973.0    0.05       0  5065.7     0.1       0
  5159.2    0.05       0  5256.8    0.08       0
Bank Sta=4911.8,4920.9
Exp/Cntr=0.3,0.1

Type RM Length L Ch R = 1,7247,477,477,477
BEGIN DESCRIPTION:
Mapping XS 13540c01
END DESCRIPTION:
XS GIS Cut Line= 4
      2064302.91     13449995.96      2064531.32     13449280.76
      2064559.10     13449114.96      2064550.32     13448889.63
#Sta/Elev= 30
  4155.6  394.50  4175.6  394.70  4213.1  393.86  4240.0  393.78  4374.0  389.82
  4443.6  388.66  4545.4  388.37  4577.5  388.39  4604.5  388.96  4609.7  388.60
  4636.7  388.94  4641.9  388.59  4668.8  388.98  4674.1  388.60  4797.0  388.86
  4891.4  388.04  4925.0  387.09  4952.8  388.13  4962.0  387.90  4998.9  385.99
  4999.8  385.19  5007.2  385.19  5008.0  385.99  5019.0  386.99  5024.1  386.48
  5054.2  387.99  5170.8  391.06  5194.5  391.75  5253.7  394.62  5300.0  396.36
#Mann=7,-1,0
  4155.6    0.05       0  4925.0     0.1       0  4962.0    0.05       0
  4998.9    0.03       0  5008.0    0.05       0  5170.8    0.05       0
  5253.7    0.08       0
Bank Sta=4998.9,5008
Exp/Cntr=0.3,0.1

Type RM Length L Ch R = 1,6770,1036,1036,1036
BEGIN DESCRIPTION:
Mapping XS f0f21072
END DESCRIPTION:
XS GIS Cut Line= 4
      2064525.74     13450385.60      2064725.37     13450258.88
      2064971.89     13449059.23      2064901.87     13448741.62
#Sta/Elev= 30
  3664.0  392.05  3823.4  391.50  3899.4  390.76  4149.4  390.35  4241.3  388.84
  4319.4  386.70  4486.3  384.95  4566.1  385.78  4680.3  385.25  4710.9  385.32
  4741.5  386.13  4772.6  385.73  4817.9  386.22  4874.3  385.20  4955.9  386.02
  4963.9  385.95  4990.7  383.89  4992.2  383.76  4993.1  382.96  5000.5  382.96
  5001.3  383.76  5064.6  387.74  5124.8  390.24  5137.1  390.30  5179.0  391.11
  5238.8  393.75  5293.3  396.20  5344.5  397.72  5428.8  401.14  5450.4  401.70
#Mann=8,-1,0
  3664.0    0.05       0  4990.7     0.1       0  4992.2    0.07       0
  5001.3     0.1       0  5137.1    0.05       0  5179.0    0.08       0
  5238.8    0.05       0  5428.8     0.1       0
Bank Sta=4992.2,5001.3
Exp/Cntr=0.3,0.1

Type RM Length L Ch R = 1,5734,845,845,845
BEGIN DESCRIPTION:
Mapping XS 5bd53745
END DESCRIPTION:
XS GIS Cut Line= 4
      2065565.92     13450699.11      2065687.46     13450438.68
      2065739.54     13448962.98      2065635.37     13448863.15
#Sta/Elev= 30
  3699.2  386.24  3990.9  386.81  4120.4  385.75  4290.5  382.04  4430.6  381.39
  4480.6  382.01  4560.6  381.73  4578.5  382.12  4778.6  382.81  4900.8  383.74
  4950.9  383.61  4970.9  382.52  4980.9  381.49  4986.4  380.33  4987.2  379.53
  4994.6  379.53  4995.5  380.33  5010.9  380.68  5040.9  382.48  5059.0  382.04
  5091.0  381.85  5157.6  383.65  5194.4  383.42  5221.0  384.26  5256.2  382.88
  5271.1  382.36  5321.1  383.02  5431.2  387.35  5542.7  388.26  5607.5  388.08
#Mann=8,-1,0
  3699.2    0.05       0  4578.5     0.1       0  4778.6    0.05       0
  4986.4    0.03       0  4995.5    0.05       0  5059.0    0.12       0
  5157.6    0.05       0  5256.2     0.1       0
Bank Sta=4986.4,4995.5
Exp/Cntr=0.3,0.1

Type RM Length L Ch R = 1,4889,716,716,716
BEGIN DESCRIPTION:
Mapping XS e8f527c7
END DESCRIPTION:
XS GIS Cut Line= 4
      2065743.86     13450790.25      2065978.26     13450612.29
      2066546.83     13449327.56      2066512.11     13448880.53
#Sta/Elev= 30
  3677.4  385.68  4195.7  385.01  4340.5  383.67  4537.4  380.30  4549.1  379.33
  4566.9  375.85  4581.1  374.06  4608.2  373.75  4608.8  373.74  4609.7  372.94
  4617.3  372.94  4618.1  373.74  4647.7  373.86  4665.5  377.02  4671.0  377.02
  4688.8  381.90  4694.3  381.90  4723.3  385.61  4756.1  385.33  4787.4  381.65
  4805.7  380.93  4886.1  381.63  4957.3  380.26  5007.6  377.61  5036.7  380.62
  5098.2  380.01  5171.6  382.35  5239.5  383.30  5380.4  382.69  5825.0  385.07
#Mann=7,-1,0
  3677.4    0.05       0  4608.2     0.1       0  4608.8    0.07       0
  4618.1     0.1       0  4805.7    0.05       0  4957.3     0.1       0
  5098.2    0.05       0
Bank Sta=4608.8,4618.1
Exp/Cntr=0.3,0.1

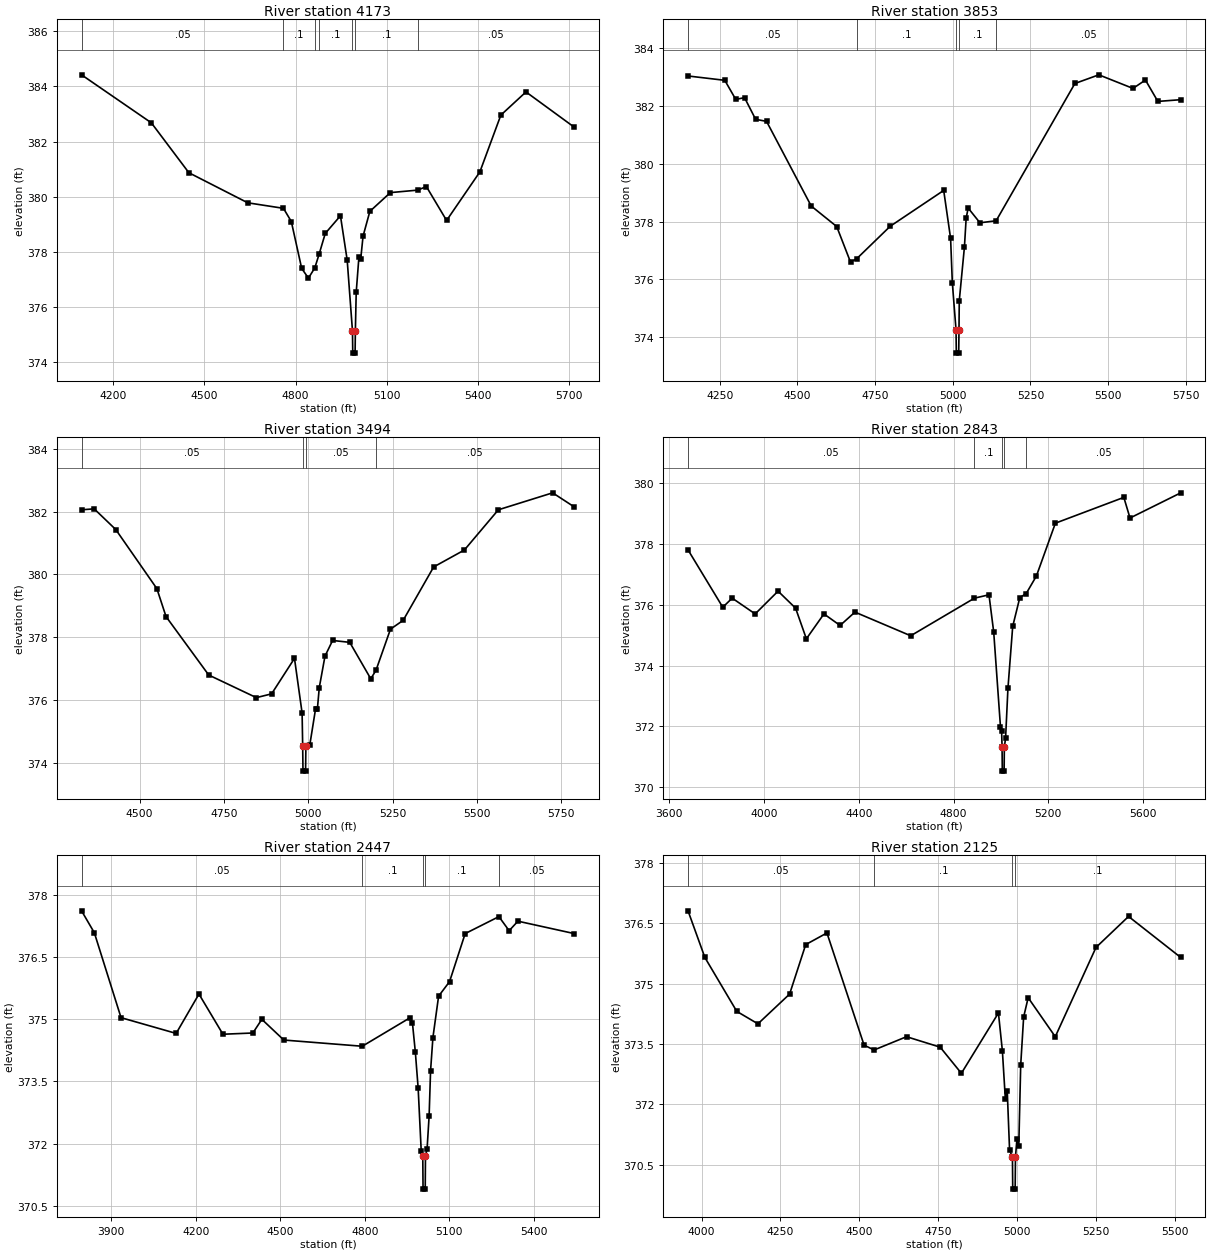
Type RM Length L Ch R = 1,4173,320,320,320
BEGIN DESCRIPTION:
Mapping XS 897345ff
END DESCRIPTION:
XS GIS Cut Line= 4
      2066160.57     13450807.59      2066321.14     13450694.75
      2066828.95     13449705.17      2066893.75     13449398.46
#Sta/Elev= 30
  4095.4  384.42  4325.1  382.68  4448.7  380.87  4642.5  379.78  4760.0  379.58
  4785.9  379.10  4820.0  377.40  4842.2  377.05  4863.2  377.42  4877.7  377.93
  4897.6  378.67  4947.6  379.31  4969.8  377.70  4987.2  375.13  4988.1  374.33
  4995.8  374.33  4996.7  375.13  4999.5  376.54  5008.5  377.83  5014.2  377.73
  5022.0  378.57  5044.4  379.47  5111.9  380.15  5202.1  380.24  5230.4  380.37
  5297.0  379.14  5406.5  380.90  5475.6  382.96  5558.3  383.80  5717.4  382.52
#Mann=7,-1,0
  4095.4    0.05       0  4760.0     0.1       0  4863.2    0.05       0
  4877.7     0.1       0  4987.2    0.07       0  4996.7     0.1       0
  5202.1    0.05       0
Bank Sta=4987.2,4996.7
Exp/Cntr=0.3,0.1

Type RM Length L Ch R = 1,3853,359,359,359
BEGIN DESCRIPTION:
Mapping XS 1081a521
END DESCRIPTION:
XS GIS Cut Line= 4
      2066447.03     13450894.38      2066672.70     13450655.69
      2067102.39     13449813.68      2067106.73     13449501.20
#Sta/Elev= 30
  4147.7  383.04  4266.1  382.89  4301.3  382.23  4329.7  382.29  4365.3  381.54
  4400.5  381.47  4544.3  378.54  4626.4  377.83  4670.8  376.60  4691.1  376.72
  4798.6  377.84  4970.8  379.08  4993.0  377.42  4998.6  375.88  5010.5  374.25
  5011.4  373.45  5019.1  373.45  5020.0  374.25  5020.9  375.26  5037.5  377.12
  5043.1  378.12  5049.5  378.47  5087.5  377.96  5139.6  378.03  5393.1  382.78
  5470.2  383.08  5580.2  382.61  5620.2  382.90  5660.2  382.16  5734.0  382.22
#Mann=5,-1,0
  4147.7    0.05       0  4691.1     0.1       0  5010.5    0.07       0
  5020.0     0.1       0  5139.6    0.05       0
Bank Sta=5010.5,5020
Exp/Cntr=0.3,0.1

Type RM Length L Ch R = 1,3494,651,651,651
BEGIN DESCRIPTION:
Mapping XS faa83b9d
END DESCRIPTION:
XS GIS Cut Line= 4
      2066690.08     13451002.90      2066907.08     13450829.30
      2067267.32     13450082.77      2067228.26     13449731.23
#Sta/Elev= 30
  4328.2  382.06  4365.7  382.09  4429.7  381.43  4551.4  379.55  4578.6  378.66
  4705.1  376.80  4846.3  376.08  4891.5  376.20  4959.3  377.33  4981.9  375.59
  4983.6  374.54  4984.5  373.74  4992.2  373.74  4993.1  374.54  5004.5  374.56
  5021.6  375.71  5027.1  375.71  5032.8  376.40  5049.7  377.40  5072.3  377.90
  5123.1  377.84  5185.4  376.68  5200.9  376.95  5243.8  378.26  5281.4  378.54
  5371.8  380.24  5462.9  380.78  5563.6  382.06  5724.5  382.60  5788.7  382.15
#Mann=4,-1,0
  4328.2    0.05       0  4983.6    0.07       0  4993.1    0.05       0
  5200.9    0.05       0
Bank Sta=4983.6,4993.1
Exp/Cntr=0.3,0.1

Type RM Length L Ch R = 1,2843,396,396,396
BEGIN DESCRIPTION:
Mapping XS 4cec5a3b
END DESCRIPTION:
XS GIS Cut Line= 4
      2067227.81     13451493.43      2067588.50     13450729.47
      2067610.20     13449831.04      2067501.70     13449514.22
#Sta/Elev= 30
  3680.1  377.81  3826.7  375.92  3866.4  376.22  3963.3  375.70  4059.9  376.45
  4133.8  375.89  4179.3  374.88  4253.4  375.70  4321.5  375.32  4384.2  375.76
  4619.4  374.98  4888.4  376.22  4949.5  376.33  4969.5  375.10  4997.9  371.99
  5002.9  371.83  5004.7  371.32  5005.7  370.52  5013.4  370.52  5014.3  371.32
  5019.5  371.60  5029.5  373.25  5049.6  375.29  5079.6  376.24  5106.4  376.37
  5149.6  376.95  5229.6  378.69  5518.3  379.54  5544.3  378.86  5758.5  379.69
#Mann=5,-1,0
  3680.1    0.05       0  4888.4     0.1       0  5004.7    0.07       0
  5014.3     0.1       0  5106.4    0.05       0
Bank Sta=5004.7,5014.3
Exp/Cntr=0.3,0.1

Type RM Length L Ch R = 1,2447,322,322,322
BEGIN DESCRIPTION:
Mapping XS 515f9294
END DESCRIPTION:
XS GIS Cut Line= 4
      2067516.03     13451496.85      2067793.36     13450731.21
      2067998.22     13450019.40      2067887.22     13449859.84
#Sta/Elev= 30
  3794.5  377.62  3839.9  377.09  3934.7  375.04  4130.3  374.66  4211.3  375.61
  4296.4  374.64  4402.7  374.67  4434.6  375.00  4512.6  374.50  4791.1  374.35
  4961.1  375.04  4969.1  374.92  4979.5  374.21  4989.5  373.34  5000.3  371.83
  5005.9  371.70  5006.9  370.90  5014.6  370.90  5015.5  371.70  5021.1  371.86
  5028.4  372.66  5033.6  373.76  5041.9  374.56  5062.1  375.56  5101.0  375.91
  5156.4  377.07  5276.2  377.48  5312.5  377.14  5343.7  377.37  5543.9  377.07
#Mann=5,-1,0
  3794.5    0.05       0  4791.1     0.1       0  5005.9    0.07       0
  5015.5     0.1       0  5276.2    0.05       0
Bank Sta=5005.9,5015.5
Exp/Cntr=0.3,0.1

Type RM Length L Ch R = 1,2125,221,221,221
BEGIN DESCRIPTION:
Mapping XS f2d1ba6c
END DESCRIPTION:
XS GIS Cut Line= 4
      2067634.07     13451493.40      2068041.78     13450670.39
      2068145.08     13450503.72      2068206.55     13450061.12
#Sta/Elev= 30
  3957.0  376.81  4010.4  375.65  4111.5  374.31  4178.5  374.00  4278.9  374.74
  4329.9  375.97  4397.2  376.26  4514.9  373.47  4546.6  373.35  4649.4  373.68
  4756.0  373.42  4823.2  372.77  4940.6  374.27  4953.1  373.33  4962.6  372.12
  4968.5  372.34  4975.9  370.86  4985.0  370.69  4985.9  369.89  4993.6  369.89
  4994.6  370.69  4999.3  371.14  5005.1  370.97  5011.2  372.98  5020.5  374.17
  5034.8  374.65  5120.7  373.68  5249.8  375.90  5352.9  376.67  5518.4  375.65
#Mann=4,-1,0
  3957.0    0.05       0  4546.6     0.1       0  4985.0    0.07       0
  4994.6     0.1       0
Bank Sta=4985,4994.6
Exp/Cntr=0.3,0.1

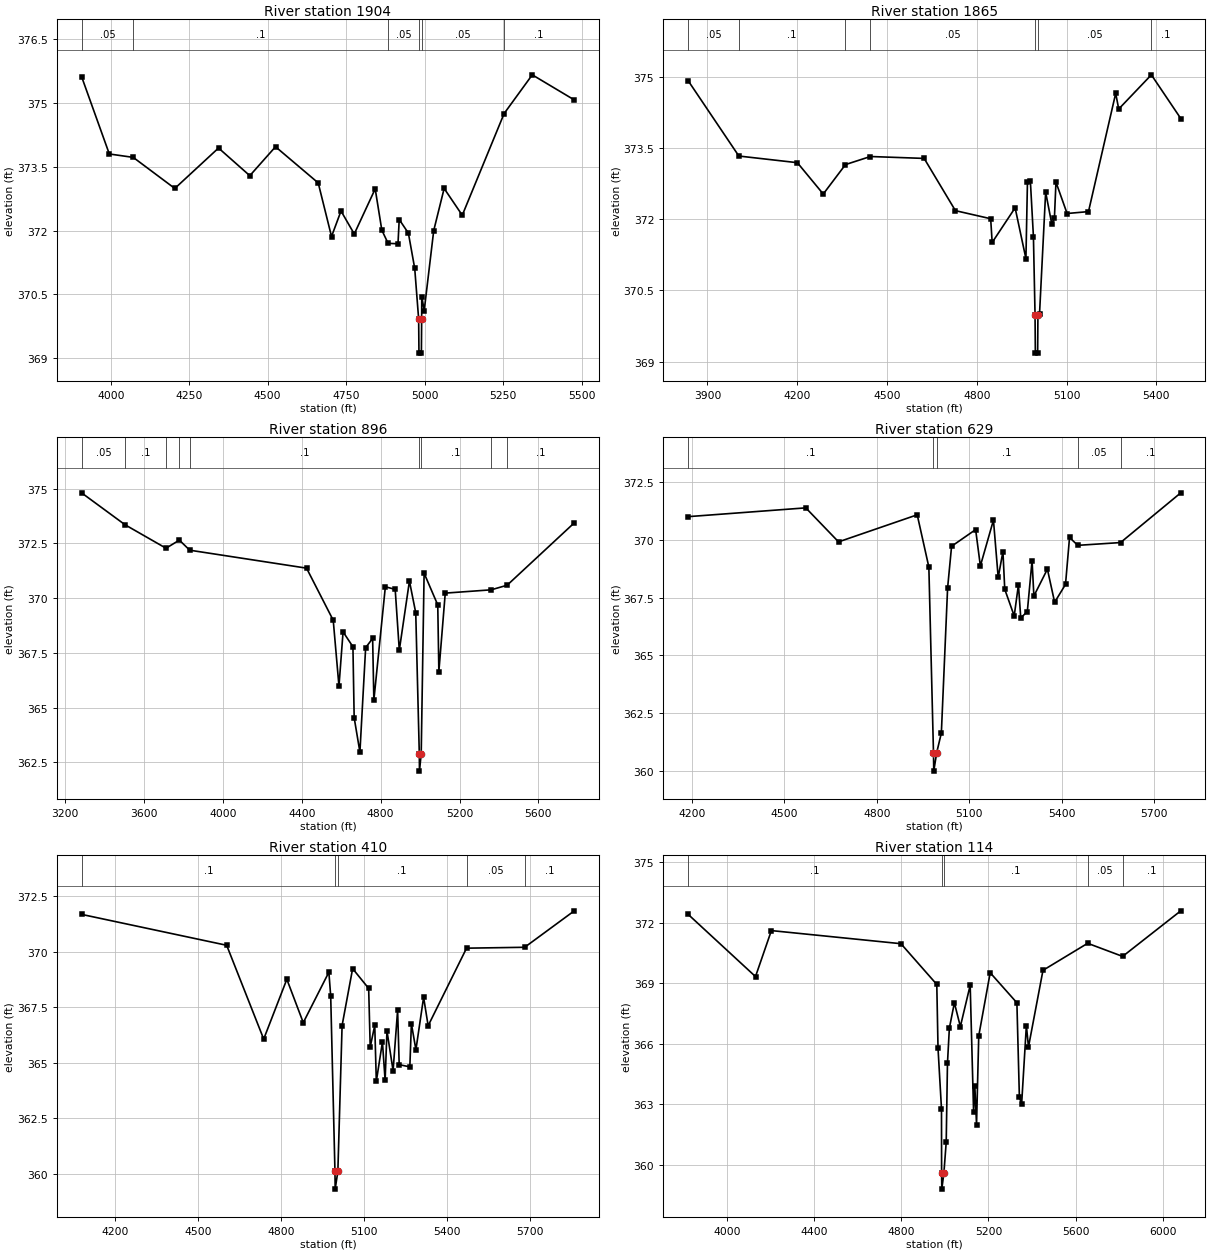
Type RM Length L Ch R = 1,1904,39,39,39
BEGIN DESCRIPTION:
Mapping XS 84ccf8de
END DESCRIPTION:
XS GIS Cut Line= 4
      2067752.10     13451514.28      2068300.46     13450663.44
      2068329.98     13450453.38      2068296.85     13450109.84
#Sta/Elev= 30
  3907.2  375.62  3995.6  373.80  4071.8  373.72  4204.2  372.99  4343.5  373.94
  4443.1  373.29  4525.0  373.97  4661.0  373.12  4703.4  371.86  4733.6  372.46
  4775.8  371.92  4842.5  372.98  4863.6  372.01  4883.6  371.70  4915.1  371.69
  4919.0  372.26  4948.2  371.94  4968.4  371.11  4980.9  369.92  4981.9  369.12
  4989.6  369.12  4990.5  369.92  4990.8  370.45  4998.6  370.12  5028.9  372.00
  5062.1  372.99  5119.8  372.36  5253.1  374.75  5342.8  375.66  5476.7  375.07
#Mann=6,-1,0
  3907.2    0.05       0  4071.8     0.1       0  4883.6    0.05       0
  4980.9    0.04       0  4990.5    0.05       0  5253.1     0.1       0
Bank Sta=4980.9,4990.5
Exp/Cntr=0.3,0.1

Type RM Length L Ch R = 1,1865,969,969,969
BEGIN DESCRIPTION:
Mapping XS 0396ad88
END DESCRIPTION:
XS GIS Cut Line= 6
      2067813.24     13451515.79      2068242.81     13451194.14
      2068330.85     13450654.76      2068355.15     13450534.10
      2068380.33     13450422.99      2068335.08     13450099.62
#Sta/Elev= 30
  3835.0  374.92  4004.9  373.33  4200.4  373.19  4286.9  372.53  4361.2  373.15
  4444.4  373.32  4624.1  373.28  4728.6  372.18  4846.4  372.01  4851.4  371.51
  4928.1  372.24  4964.2  371.17  4969.3  372.78  4979.1  372.80  4989.3  371.63
  4994.7  369.98  4995.7  369.18  5003.4  369.18  5004.3  369.98  5009.7  370.01
  5030.1  372.57  5050.6  371.90  5059.4  372.02  5064.6  372.78  5101.8  372.12
  5173.3  372.16  5264.2  374.65  5274.3  374.32  5383.4  375.04  5481.7  374.12
#Mann=7,-1,0
  3835.0    0.05       0  4004.9     0.1       0  4361.2    0.08       0
  4444.4    0.05       0  4994.7    0.04       0  5004.3    0.05       0
  5383.4     0.1       0
Bank Sta=4994.7,5004.3
Exp/Cntr=0.3,0.1

Type RM Length L Ch R = 1,896,267,267,267
BEGIN DESCRIPTION:
UNT 22 in Lagunillas Cr Wtrshd 1.0
END DESCRIPTION:
XS GIS Cut Line= 5
      2067849.98     13451550.01      2068316.60     13451306.72
      2068977.77     13450432.76      2069027.17     13450301.78
      2068380.23     13449950.00
#Sta/Elev= 30
  3283.6  374.81  3504.4  373.35  3711.9  372.28  3779.5  372.65  3832.1  372.19
  4424.4  371.37  4559.7  368.99  4588.8  365.98  4609.6  368.46  4659.6  367.78
  4665.9  364.54  4695.0  362.97  4724.1  367.74  4759.5  368.16  4765.7  365.34
  4824.0  370.52  4873.9  370.40  4894.7  367.62  4946.1  370.78  4978.1  369.33
  4996.1  362.90  4997.0  362.10  5005.8  362.90  5020.5  371.14  5089.7  369.69
  5095.3  366.65  5127.7  370.23  5360.5  370.38  5441.4  370.59  5782.1  373.44
#Mann=9,-1,0
  3283.6    0.05       0  3504.4     0.1       0  3711.9    0.05       0
  3779.5    0.08       0  3832.1     0.1       0  4996.1    0.07       0
  5005.8     0.1       0  5360.5    0.05       0  5441.4     0.1       0
Bank Sta=4996.1,5005.8
Exp/Cntr=0.3,0.1

Type RM Length L Ch R = 1,629,219,219,219
BEGIN DESCRIPTION:
Mapping XS 0ebe39fa
END DESCRIPTION:
XS GIS Cut Line= 4
      2068890.57     13451199.98      2069122.66     13450485.80
      2069145.23     13450353.86      2068536.44     13449977.75
#Sta/Elev= 30
  4186.9  371.00  4569.4  371.38  4675.8  369.91  4931.3  371.08  4969.1  368.82
  4984.1  360.80  4985.0  360.00  4994.6  360.80  5009.7  361.65  5030.0  367.92
  5042.9  369.72  5121.0  370.44  5136.4  368.87  5178.9  370.85  5194.3  368.37
  5209.7  369.49  5215.6  367.86  5246.3  366.71  5260.0  368.05  5267.6  366.62
  5288.9  366.90  5304.3  369.10  5310.2  367.57  5354.1  368.73  5377.6  367.30
  5412.9  368.07  5426.0  370.10  5452.7  369.76  5591.7  369.88  5787.3  372.03
#Mann=5,-1,0
  4186.9     0.1       0  4984.1    0.07       0  4994.6     0.1       0
  5452.7    0.05       0  5591.7     0.1       0
Bank Sta=4984.1,4994.6
Exp/Cntr=0.3,0.1

Type RM Length L Ch R = 1,410,296,296,296
BEGIN DESCRIPTION:
Mapping XS df3f62de
END DESCRIPTION:
XS GIS Cut Line= 4
      2068925.29     13451231.24      2069322.31     13450442.40
      2069299.18     13450348.04      2068588.71     13449976.55
#Sta/Elev= 30
  4077.9  371.68  4602.7  370.29  4736.6  366.07  4820.3  368.76  4879.7  366.81
  4972.3  369.08  4978.9  368.01  4994.3  360.12  4995.1  359.32  5004.8  360.12
  5020.1  366.68  5058.2  369.24  5116.2  368.35  5121.8  365.71  5138.2  366.69
  5143.9  364.17  5166.0  365.94  5175.7  364.21  5182.4  366.44  5204.5  364.65
  5220.9  367.37  5226.6  364.92  5265.1  364.82  5270.7  366.76  5287.1  365.59
  5314.9  367.95  5331.3  366.67  5470.2  370.16  5680.4  370.20  5859.9  371.84
#Mann=5,-1,0
  4077.9     0.1       0  4994.3    0.07       0  5004.8     0.1       0
  5470.2    0.05       0  5680.4     0.1       0
Bank Sta=4994.3,5004.8
Exp/Cntr=0.3,0.1

Type RM Length L Ch R = 1,114,0,0,0
BEGIN DESCRIPTION:
UNT 176 in Lagunillas Cr Wtrshd 1.0
END DESCRIPTION:
XS GIS Cut Line= 4
      2068960.02     13451293.72      2069613.98     13450399.00
      2069453.69     13450308.11      2068564.22     13449925.67
#Sta/Elev= 30
  3821.9  372.41  4131.5  369.32  4204.3  371.60  4798.7  370.95  4963.2  368.93
  4968.9  365.76  4984.8  362.75  4985.3  359.58  4986.2  358.78  4995.8  359.58
  5006.4  361.10  5012.2  365.02  5020.9  366.76  5043.9  368.02  5071.3  366.84
  5116.4  368.89  5132.1  362.58  5137.6  363.91  5145.6  361.98  5155.7  366.38
  5208.2  369.51  5330.7  368.02  5342.2  363.33  5352.5  363.01  5374.2  366.89
  5383.9  365.83  5450.4  369.63  5655.4  370.97  5815.8  370.32  6082.6  372.58
#Mann=5,-1,0
  3821.9     0.1       0  4985.3    0.07       0  4995.8     0.1       0
  5655.4    0.05       0  5815.8     0.1       0
Bank Sta=4985.3,4995.8
Exp/Cntr=0.3,0.1

Chan Stop Cuts=-1