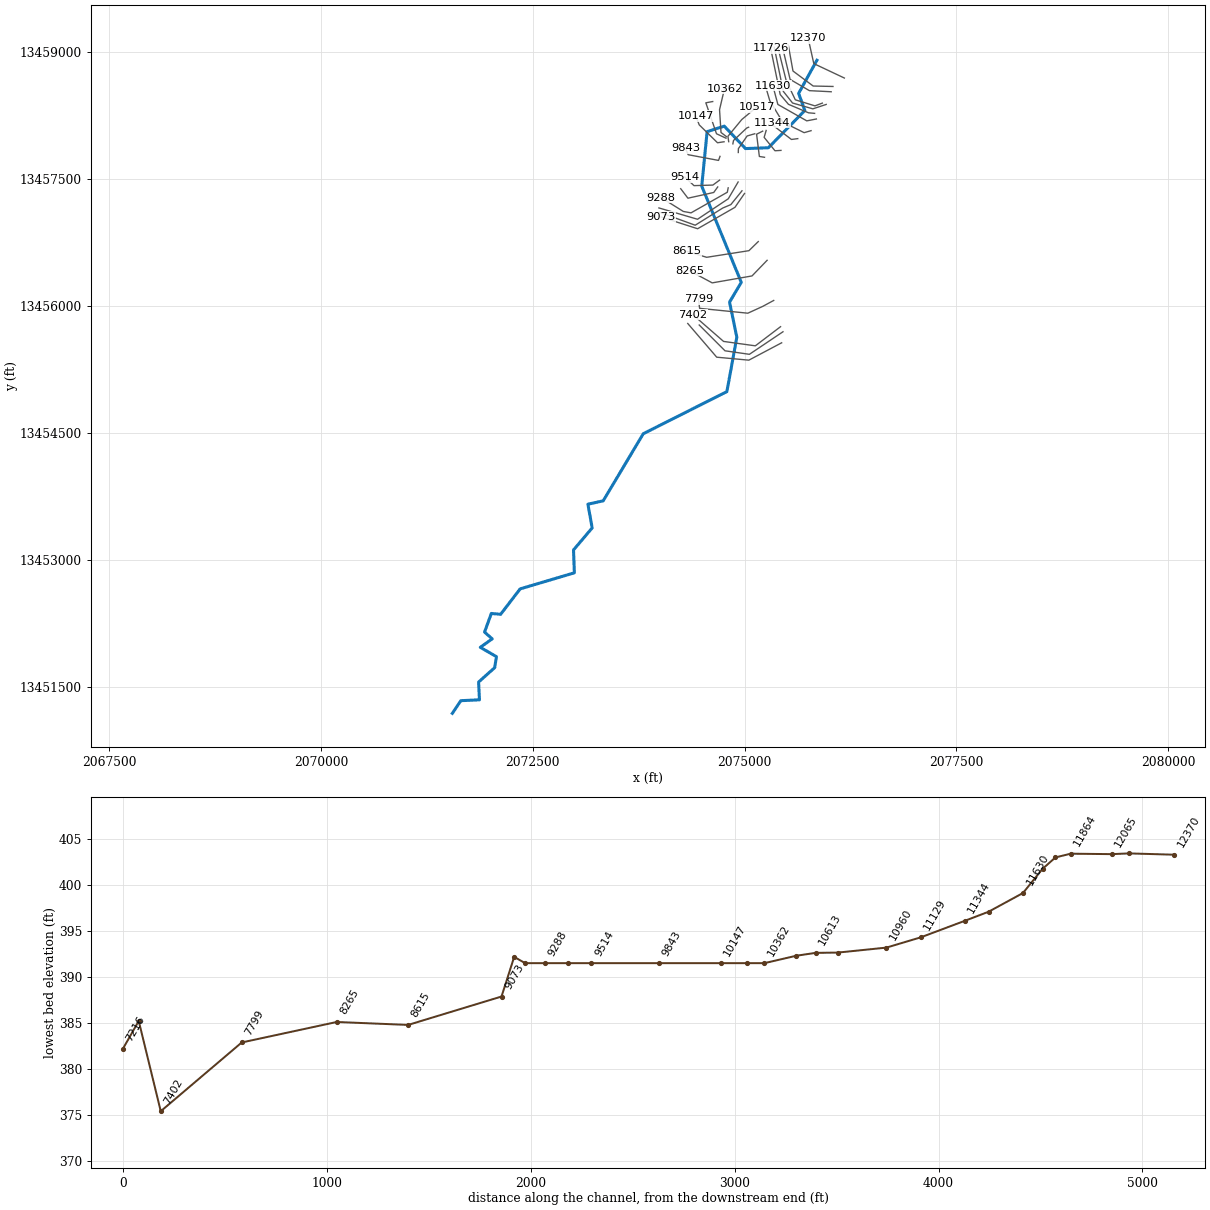
--- UNT 24 in Lagunillas Cr Wtrshd.prj (project) ---

Proj Title=UNT 24 in Lagunillas Cr Wtrshd Base Level Engineering
Current Plan=p01
Default Exp/Contr=0.3,0.1
English Units
Geom File=g01
Flow File=f01
Plan File=p01
BEGIN DESCRIPTION:
UNT 24 in Lagunillas Cr Wtrshd
END DESCRIPTION:

--- UNT 24 in Lagunillas Cr Wtrshd.p01 (plan) ---

Plan Title=Multiple Run
Short Identifier=Multiple
Geom File=g01
Flow File=f01
Subcritical Flow
K Sum by GR= 0
Std Step Tol= 0.01
Critical Tol= 0.01
Num of Std Step Trials= 20
Max Error Tol= 0.3
Flow Tol Ratio= 0.001
Split Flow NTrial= 30
Split Flow Tol= 0.02
Split Flow Ratio= 0.02
Log Output Level= 0
Friction Slope Method= 1
Unsteady Friction Slope Method= 2
Unsteady Bridges Friction Slope Method= 1
Parabolic Critical Depth
Global Vel Dist=  1 , 1 , 1
Global Log Level= 0
CheckData=True
Encroach Param= -1, 0, 0, 0
BEGIN DESCRIPTION:
Multiple Run
END DESCRIPTION:

--- UNT 24 in Lagunillas Cr Wtrshd.f01 (steady flow) ---

Flow Title=Multiple
Number of Profiles=7
Profile Names=10-year,25-year,50-year,1pct_min,100-year,1pct_plu,500-year
River Rch & RM= UNT 24 in Laguni,Reach-1,12370
     136     183     220     133     266     530     391
River Rch & RM= UNT 24 in Laguni,Reach-1,10517
     265     370     458     282     563    1124     867
River Rch & RM= UNT 24 in Laguni,Reach-1,6293
     341     482     601     373     745    1487    1164
River Rch & RM= UNT 24 in Laguni,Reach-1,4335
     369     522     651     405     808    1611    1262
Boundary for River Rch & Prof#=UNT 24 in Laguni,Reach-1,1
Up Type=0
Dn Type=3
Dn Slope=0.005
Boundary for River Rch & Prof#=UNT 24 in Laguni,Reach-1,2
Up Type=0
Dn Type=3
Dn Slope=0.005
Boundary for River Rch & Prof#=UNT 24 in Laguni,Reach-1,3
Up Type=0
Dn Type=3
Dn Slope=0.005
Boundary for River Rch & Prof#=UNT 24 in Laguni,Reach-1,4
Up Type=0
Dn Type=3
Dn Slope=0.005
Boundary for River Rch & Prof#=UNT 24 in Laguni,Reach-1,5
Up Type=0
Dn Type=3
Dn Slope=0.005
Boundary for River Rch & Prof#=UNT 24 in Laguni,Reach-1,6
Up Type=0
Dn Type=3
Dn Slope=0.005
Boundary for River Rch & Prof#=UNT 24 in Laguni,Reach-1,7
Up Type=0
Dn Type=3
Dn Slope=0.005

--- UNT 24 in Lagunillas Cr Wtrshd.g01 (geometry) ---

Geom Title=Existing Conditions

River Reach=UNT 24 in Laguni,Reach-1
Reach XY= 30
      2075853.52     13458898.24      2075637.59     13458506.53
      2075710.80     13458304.54      2075280.80     13457864.54
      2075010.80     13457854.54      2074759.68     13458119.65
      2074557.42     13458054.55      2074494.05     13457411.32
      2074960.80     13456274.54      2074822.18     13456041.53
      2074908.12     13455627.47      2074790.80     13454984.54
      2073804.45     13454487.28      2073330.80     13453694.54
      2073150.80     13453654.54      2073200.80     13453374.54
      2072980.80     13453114.54      2072990.80     13452844.54
      2072350.80     13452654.54      2072120.80     13452354.54
      2072010.80     13452364.54      2071930.80     13452144.54
      2072020.80     13452064.54      2071880.80     13451964.54
      2072070.80     13451854.54      2072050.80     13451724.54
      2071860.80     13451554.54      2071870.80     13451344.54
      2071650.80     13451334.54      2071550.80     13451184.54

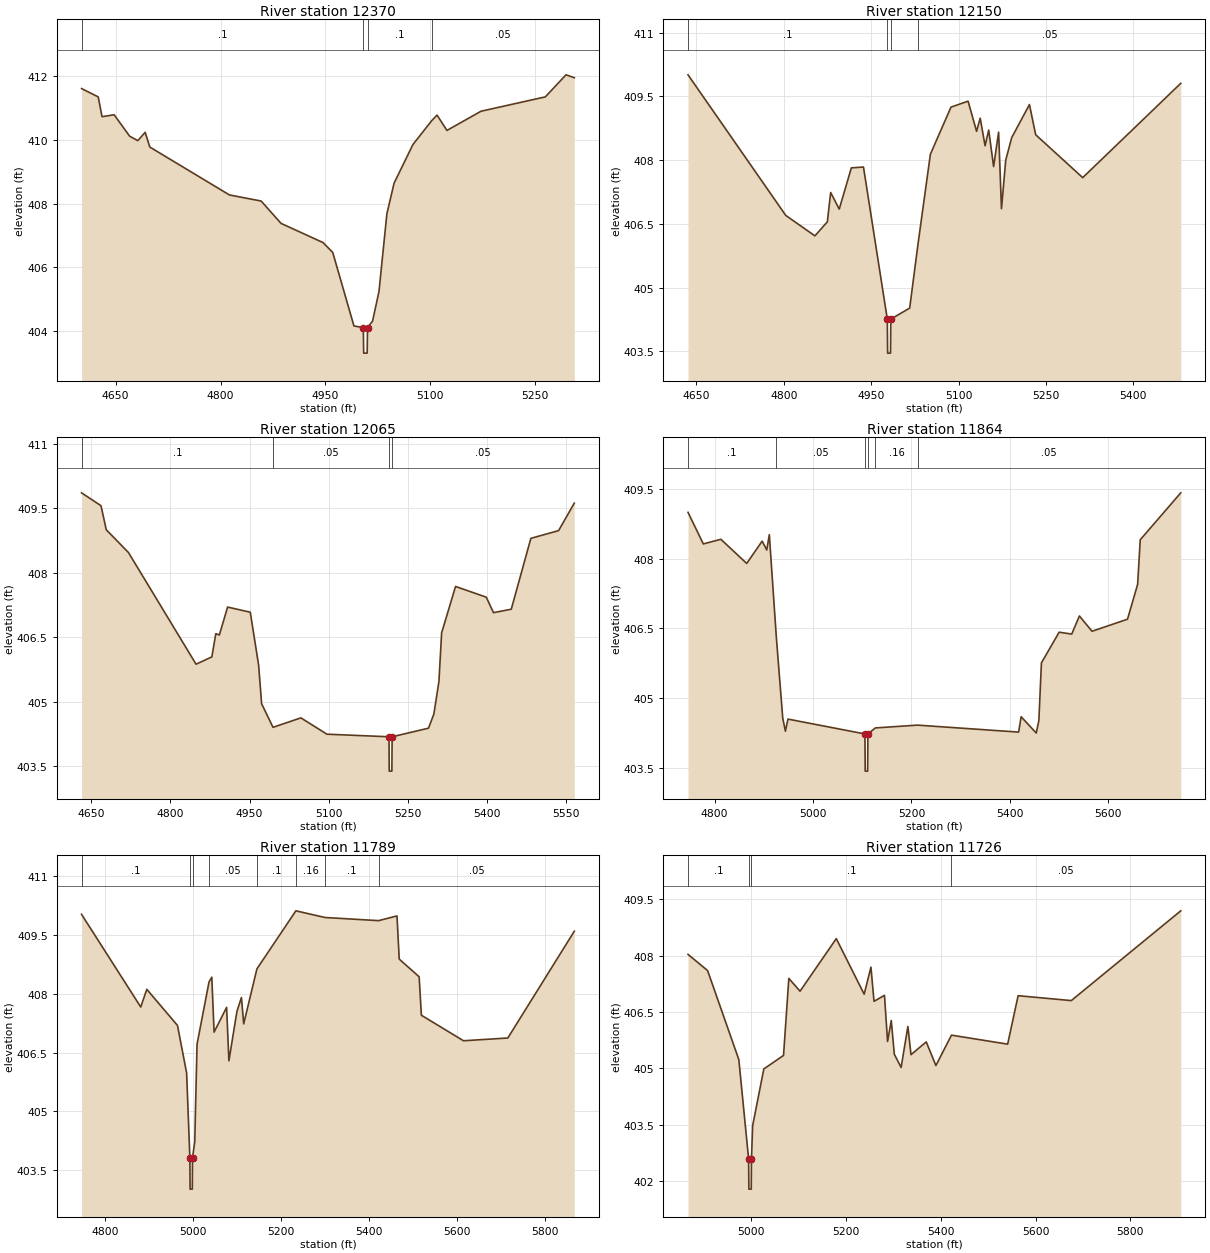
Type RM Length L Ch R = 1,12370,220,220,220
BEGIN DESCRIPTION:
UNT 24 in Lagunillas Cr Wtrshd 19.0
END DESCRIPTION:
XS GIS Cut Line= 3
      2076177.24     13458687.81      2075816.62     13458858.09
      2075750.17     13459156.59
#Sta/Elev= 30
  4601.2  411.60  4625.0  411.34  4630.5  410.72  4647.8  410.78  4670.0  410.11
  4681.6  409.97  4692.2  410.23  4698.8  409.77  4812.7  408.27  4858.0  408.08
  4886.5  407.38  4946.5  406.78  4960.4  406.47  4990.7  404.17  5004.1  404.12
  5004.6  403.32  5009.6  403.32  5010.1  404.12  5017.3  404.32  5026.5  405.25
  5037.8  407.68  5048.1  408.64  5075.1  409.85  5101.7  410.59  5109.5  410.77
  5123.7  410.29  5172.3  410.89  5264.4  411.34  5293.9  412.03  5305.8  411.94
#Mann=4,-1,0
  4601.2     0.1       0  5004.1    0.07       0  5010.1     0.1       0
  5101.7    0.05       0
Bank Sta=5004.1,5010.1
Exp/Cntr=0.3,0.1

Type RM Length L Ch R = 1,12150,85,85,85
BEGIN DESCRIPTION:
Mapping XS c8dc9076
END DESCRIPTION:
XS GIS Cut Line= 4
      2076042.72     13458588.13      2075809.19     13458593.40
      2075570.91     13458770.49      2075515.05     13459080.62
#Sta/Elev= 30
  4635.8  410.01  4803.6  406.70  4853.6  406.22  4874.9  406.55  4880.6  407.24
  4895.3  406.85  4916.1  407.82  4936.9  407.84  4977.8  404.26  4978.3  403.46
  4983.3  403.46  4983.8  404.26  5016.2  404.52  5030.3  406.01  5051.7  408.14
  5087.1  409.25  5116.4  409.39  5131.0  408.68  5137.2  408.99  5145.6  408.34
  5151.8  408.71  5160.2  407.85  5168.8  408.66  5173.7  406.86  5181.0  408.00
  5191.2  408.53  5221.7  409.31  5232.4  408.60  5313.1  407.59  5481.4  409.81
#Mann=4,-1,0
  4635.8     0.1       0  4977.8    0.07       0  4983.8     0.1       0
  5030.3    0.05       0
Bank Sta=4977.8,4983.8
Exp/Cntr=0.3,0.1

Type RM Length L Ch R = 1,12065,201,201,201
BEGIN DESCRIPTION:
Mapping XS 5c579e7d
END DESCRIPTION:
XS GIS Cut Line= 4
      2076021.87     13458525.63      2075764.92     13458538.71
      2075537.06     13458671.53      2075442.03     13459074.24
#Sta/Elev= 30
  4631.3  409.86  4668.2  409.56  4678.2  409.00  4720.3  408.47  4848.5  405.87
  4878.5  406.04  4886.0  406.58  4892.7  406.55  4908.4  407.20  4951.4  407.08
  4967.2  405.85  4972.9  404.95  4994.5  404.40  5047.4  404.62  5096.8  404.24
  5214.5  404.18  5215.0  403.38  5220.0  403.38  5220.5  404.18  5289.5  404.38
  5299.7  404.71  5309.3  405.47  5314.4  406.60  5340.8  407.68  5399.1  407.43
  5412.8  407.07  5446.5  407.15  5483.7  408.80  5536.3  408.98  5566.1  409.62
#Mann=4,-1,0
  4631.3     0.1       0  4994.5    0.05       0  5214.5   0.033       0
  5220.5    0.05       0
Bank Sta=5214.5,5220.5
Exp/Cntr=0.3,0.1

Type RM Length L Ch R = 1,11864,75,75,75
BEGIN DESCRIPTION:
Mapping XS d25d1238
END DESCRIPTION:
XS GIS Cut Line= 5
      2075917.30     13458391.59      2075830.03     13458359.03
      2075598.25     13458430.64      2075491.48     13458654.60
      2075390.02     13459060.05
#Sta/Elev= 30
  4745.8  409.00  4776.9  408.32  4812.6  408.42  4865.1  407.90  4896.5  408.38
  4905.9  408.19  4911.1  408.52  4925.3  406.32  4938.4  404.57  4943.8  404.29
  4949.0  404.55  5105.5  404.23  5106.0  403.43  5111.0  403.43  5111.5  404.23
  5126.7  404.36  5212.5  404.42  5417.9  404.27  5423.1  404.60  5453.8  404.25
  5459.1  404.52  5464.3  405.76  5500.3  406.42  5525.9  406.38  5541.5  406.77
  5567.1  406.44  5639.3  406.70  5659.9  407.45  5665.2  408.41  5747.6  409.42
#Mann=6,-1,0
  4745.8     0.1       0  4925.3    0.05       0  5105.5   0.033       0
  5111.5    0.05       0  5126.7    0.16       0  5212.5    0.05       0
Bank Sta=5105.5,5111.5
Exp/Cntr=0.3,0.1

Type RM Length L Ch R = 1,11789,63,63,63
BEGIN DESCRIPTION:
Mapping XS 6dec23ff
END DESCRIPTION:
XS GIS Cut Line= 5
      2075962.88     13458375.97      2075805.29     13458323.87
      2075565.70     13458392.88      2075456.33     13458530.90
      2075350.00     13459050.02
#Sta/Elev= 30
  4746.1  410.02  4880.8  407.66  4894.6  408.11  4964.4  407.19  4985.2  405.98
  4992.6  403.82  4993.1  403.02  4998.1  403.02  4998.6  403.82  5003.7  404.23
  5008.9  406.71  5036.2  408.30  5042.5  408.42  5047.7  407.02  5076.2  407.65
  5081.4  406.29  5099.7  407.55  5109.9  407.90  5115.1  407.23  5145.1  408.63
  5233.8  410.11  5300.1  409.94  5422.0  409.86  5463.9  409.98  5469.0  408.88
  5514.3  408.43  5519.4  407.45  5615.2  406.80  5716.1  406.87  5867.4  409.59
#Mann=8,-1,0
  4746.1     0.1       0  4992.6    0.07       0  4998.6     0.1       0
  5036.2    0.05       0  5145.1     0.1       0  5233.8    0.16       0
  5300.1     0.1       0  5422.0    0.05       0
Bank Sta=4992.6,4998.6
Exp/Cntr=0.3,0.1

Type RM Length L Ch R = 1,11726,96,96,96
BEGIN DESCRIPTION:
Mapping XS c939662d
END DESCRIPTION:
XS GIS Cut Line= 5
      2075826.12     13458270.49      2075754.50     13458277.00
      2075517.53     13458377.26      2075419.87     13458493.14
      2075306.93     13459041.46
#Sta/Elev= 30
  4866.1  408.03  4907.4  407.60  4973.4  405.23  4994.1  402.58  4994.6  401.78
  4999.6  401.78  5000.1  402.58  5002.6  403.47  5026.2  404.98  5067.8  405.34
  5079.0  407.39  5102.7  407.05  5179.2  408.45  5238.1  406.97  5252.4  407.69
  5258.9  406.78  5281.0  406.94  5287.5  405.71  5295.3  406.27  5301.8  405.37
  5316.1  405.02  5330.4  406.11  5337.0  405.36  5369.2  405.70  5389.6  405.07
  5422.5  405.88  5541.1  405.64  5563.2  406.93  5675.5  406.80  5906.7  409.19
#Mann=4,-1,0
  4866.1     0.1       0  4994.1    0.07       0  5000.1     0.1       0
  5422.5    0.05       0
Bank Sta=4994.1,5000.1
Exp/Cntr=0.3,0.1

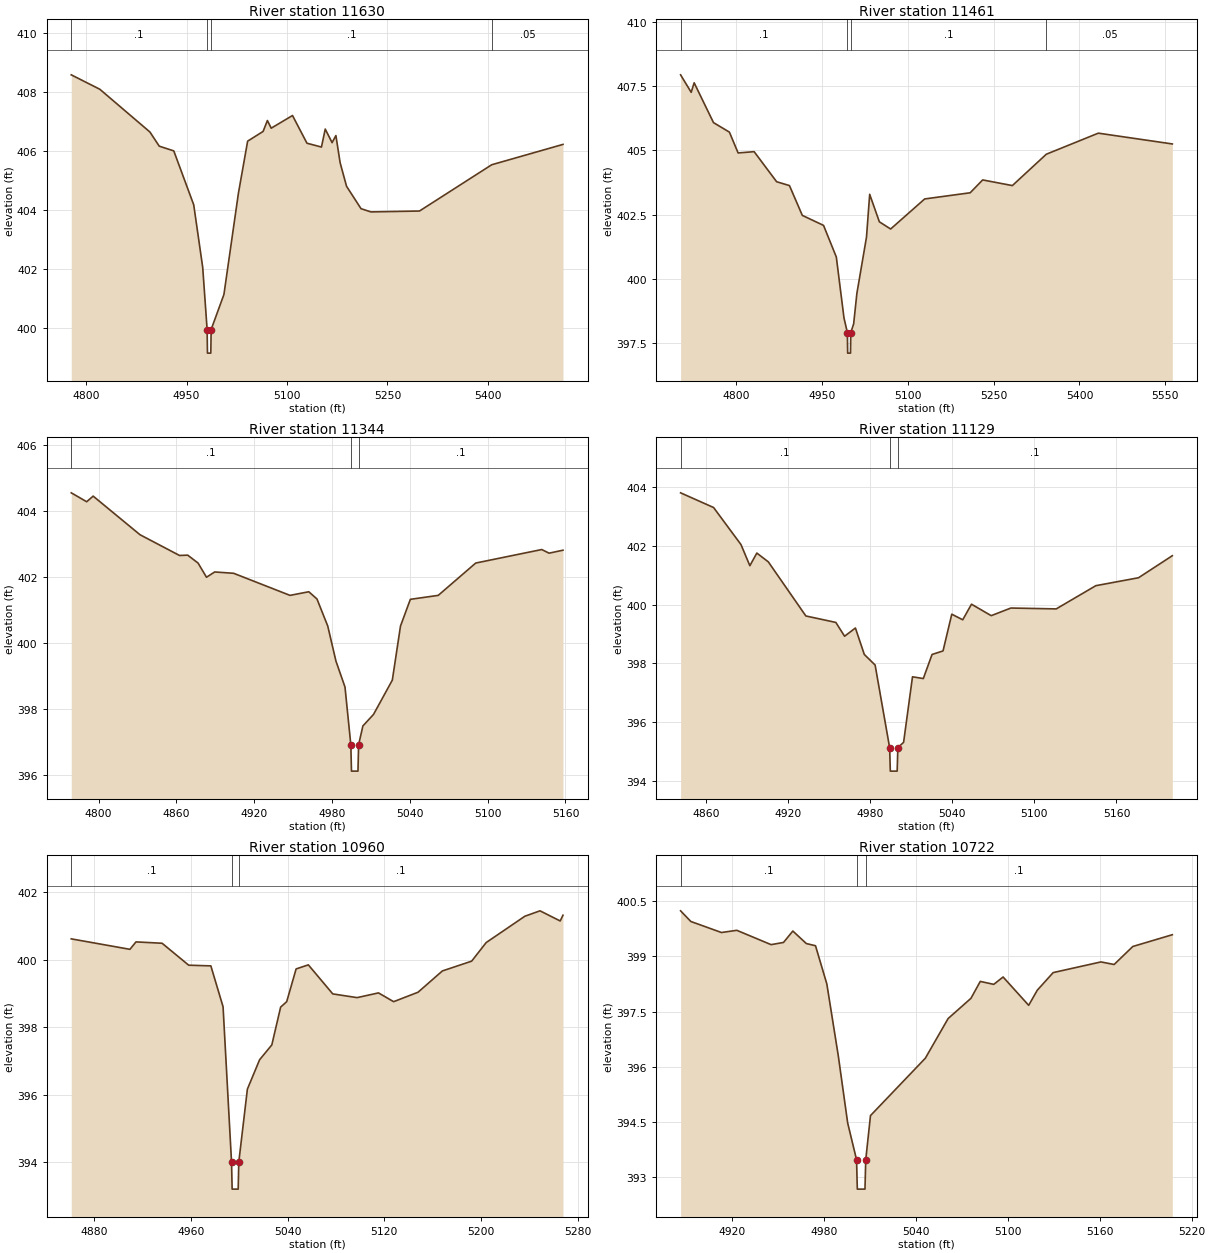
Type RM Length L Ch R = 1,11630,169,169,169
BEGIN DESCRIPTION:
Mapping XS 0e89b99d
END DESCRIPTION:
XS GIS Cut Line= 4
      2075846.95     13458204.08      2075733.67     13458181.94
      2075392.53     13458375.95      2075333.94     13458594.67
#Sta/Elev= 30
  4777.9  408.59  4820.6  408.10  4895.4  406.65  4909.3  406.17  4931.0  406.01
  4960.8  404.18  4974.2  402.06  4980.8  399.95  4981.3  399.15  4986.3  399.15
  4986.8  399.95  5005.9  401.14  5027.5  404.57  5041.3  406.34  5064.4  406.67
  5070.8  407.04  5076.5  406.78  5108.3  407.21  5129.9  406.27  5151.5  406.14
  5157.2  406.75  5167.4  406.29  5173.1  406.53  5179.4  405.61  5189.0  404.81
  5210.6  404.05  5225.4  403.94  5297.9  403.97  5405.8  405.54  5512.2  406.23
#Mann=4,-1,0
  4777.9     0.1       0  4980.8    0.07       0  4986.8     0.1       0
  5405.8    0.05       0
Bank Sta=4980.8,4986.8
Exp/Cntr=0.3,0.1

Type RM Length L Ch R = 1,11461,117,117,117
BEGIN DESCRIPTION:
Mapping XS 45a41993
END DESCRIPTION:
XS GIS Cut Line= 5
      2075784.41     13458066.05      2075702.42     13458042.62
      2075449.82     13458167.62      2075297.47     13458418.92
      2075241.47     13458609.07
#Sta/Elev= 30
  4703.1  407.94  4721.6  407.26  4726.8  407.63  4760.6  406.08  4788.4  405.71
  4803.6  404.90  4831.6  404.95  4870.9  403.78  4893.3  403.63  4915.8  402.47
  4952.9  402.08  4975.2  400.85  4988.6  398.48  4994.5  397.91  4995.0  397.11
  5000.0  397.11  5000.5  397.91  5005.5  398.25  5011.1  399.43  5027.9  401.62
  5033.5  403.29  5050.4  402.22  5070.1  401.94  5129.6  403.11  5209.1  403.35
  5230.9  403.85  5282.8  403.63  5342.1  404.85  5433.0  405.67  5562.3  405.25
#Mann=4,-1,0
  4703.1     0.1       0  4994.5    0.07       0  5000.5     0.1       0
  5342.1    0.05       0
Bank Sta=4994.5,5000.5
Exp/Cntr=0.3,0.1

Type RM Length L Ch R = 1,11344,215,215,215
BEGIN DESCRIPTION:
Mapping XS 965e9775
END DESCRIPTION:
XS GIS Cut Line= 4
      2075627.56     13457972.09      2075552.68     13457962.33
      2075344.35     13458121.83      2075323.74     13458157.62
#Sta/Elev= 30
  4778.9  404.56  4790.8  404.29  4795.8  404.46  4831.9  403.29  4862.4  402.66
  4868.7  402.67  4876.7  402.43  4883.2  402.00  4889.5  402.16  4904.1  402.12
  4947.6  401.45  4962.1  401.56  4968.4  401.34  4976.7  400.52  4983.0  399.46
  4990.0  398.67  4994.5  396.92  4995.0  396.12  5000.0  396.12  5000.5  396.92
  5003.8  397.49  5012.0  397.84  5026.5  398.88  5032.8  400.52  5040.4  401.33
  5061.9  401.45  5090.8  402.43  5141.7  402.84  5147.4  402.73  5158.1  402.82
#Mann=3,-1,0
  4778.9     0.1       0  4994.5    0.07       0  5000.5     0.1       0
Bank Sta=4994.5,5000.5
Exp/Cntr=0.3,0.1

Type RM Length L Ch R = 1,11129,169,169,169
BEGIN DESCRIPTION:
Mapping XS 79b696dd
END DESCRIPTION:
XS GIS Cut Line= 4
      2075429.02     13457833.20      2075358.45     13457828.86
      2075230.42     13457987.28      2075254.29     13458068.66
#Sta/Elev= 30
  4841.6  403.80  4865.7  403.30  4885.7  402.04  4892.2  401.32  4897.3  401.75
  4905.7  401.45  4933.1  399.61  4955.0  399.39  4961.4  398.92  4969.3  399.20
  4975.8  398.30  4983.7  397.94  4994.3  395.13  4994.8  394.33  4999.8  394.33
  5000.3  395.13  5004.5  395.31  5011.0  397.54  5018.9  397.48  5025.3  398.30
  5033.3  398.42  5039.7  399.67  5047.7  399.48  5054.1  400.01  5068.5  399.62
  5082.9  399.88  5116.0  399.85  5144.9  400.64  5176.1  400.91  5200.8  401.66
#Mann=3,-1,0
  4841.6     0.1       0  4994.3    0.07       0  5000.3     0.1       0
Bank Sta=4994.3,5000.3
Exp/Cntr=0.3,0.1

Type RM Length L Ch R = 1,10960,238,238,238
BEGIN DESCRIPTION:
Mapping XS c637e6f2
END DESCRIPTION:
XS GIS Cut Line= 4
      2075234.78     13457751.82      2075173.99     13457761.59
      2075141.44     13458024.17      2075213.08     13458060.53
#Sta/Elev= 30
  4861.2  400.62  4909.7  400.31  4914.7  400.53  4936.3  400.49  4958.3  399.84
  4976.6  399.82  4986.7  398.61  4993.7  394.01  4994.2  393.21  4999.2  393.21
  4999.7  394.01  5006.8  396.17  5016.9  397.04  5027.0  397.48  5034.3  398.60
  5039.3  398.76  5047.1  399.73  5057.2  399.85  5077.4  398.99  5097.5  398.88
  5115.2  399.02  5127.7  398.76  5147.9  399.04  5168.0  399.67  5192.2  399.96
  5204.2  400.51  5236.2  401.29  5248.7  401.45  5265.4  401.15  5267.7  401.32
#Mann=3,-1,0
  4861.2     0.1       0  4993.7    0.07       0  4999.7     0.1       0
Bank Sta=4993.7,4999.7
Exp/Cntr=0.3,0.1

Type RM Length L Ch R = 1,10722,109,109,109
BEGIN DESCRIPTION:
Mapping XS 5fec08f2
END DESCRIPTION:
XS GIS Cut Line= 4
      2074925.51     13457808.28      2074926.60     13457853.82
      2075029.68     13458003.56      2075119.75     13458029.60
#Sta/Elev= 30
  4886.2  400.24  4892.9  399.95  4912.9  399.65  4922.9  399.71  4945.3  399.32
  4953.4  399.38  4959.5  399.69  4968.3  399.35  4974.3  399.29  4981.7  398.25
  4989.2  396.29  4995.3  394.47  5001.1  393.47  5001.6  392.67  5006.6  392.67
  5007.1  393.47  5010.2  394.67  5046.0  396.23  5060.9  397.31  5075.8  397.86
  5081.9  398.32  5090.7  398.24  5096.8  398.44  5113.5  397.67  5119.1  398.08
  5129.5  398.56  5160.7  398.85  5169.3  398.78  5181.5  399.27  5207.3  399.59
#Mann=3,-1,0
  4886.2     0.1       0  5001.1    0.07       0  5007.1     0.1       0
Bank Sta=5001.1,5007.1
Exp/Cntr=0.3,0.1

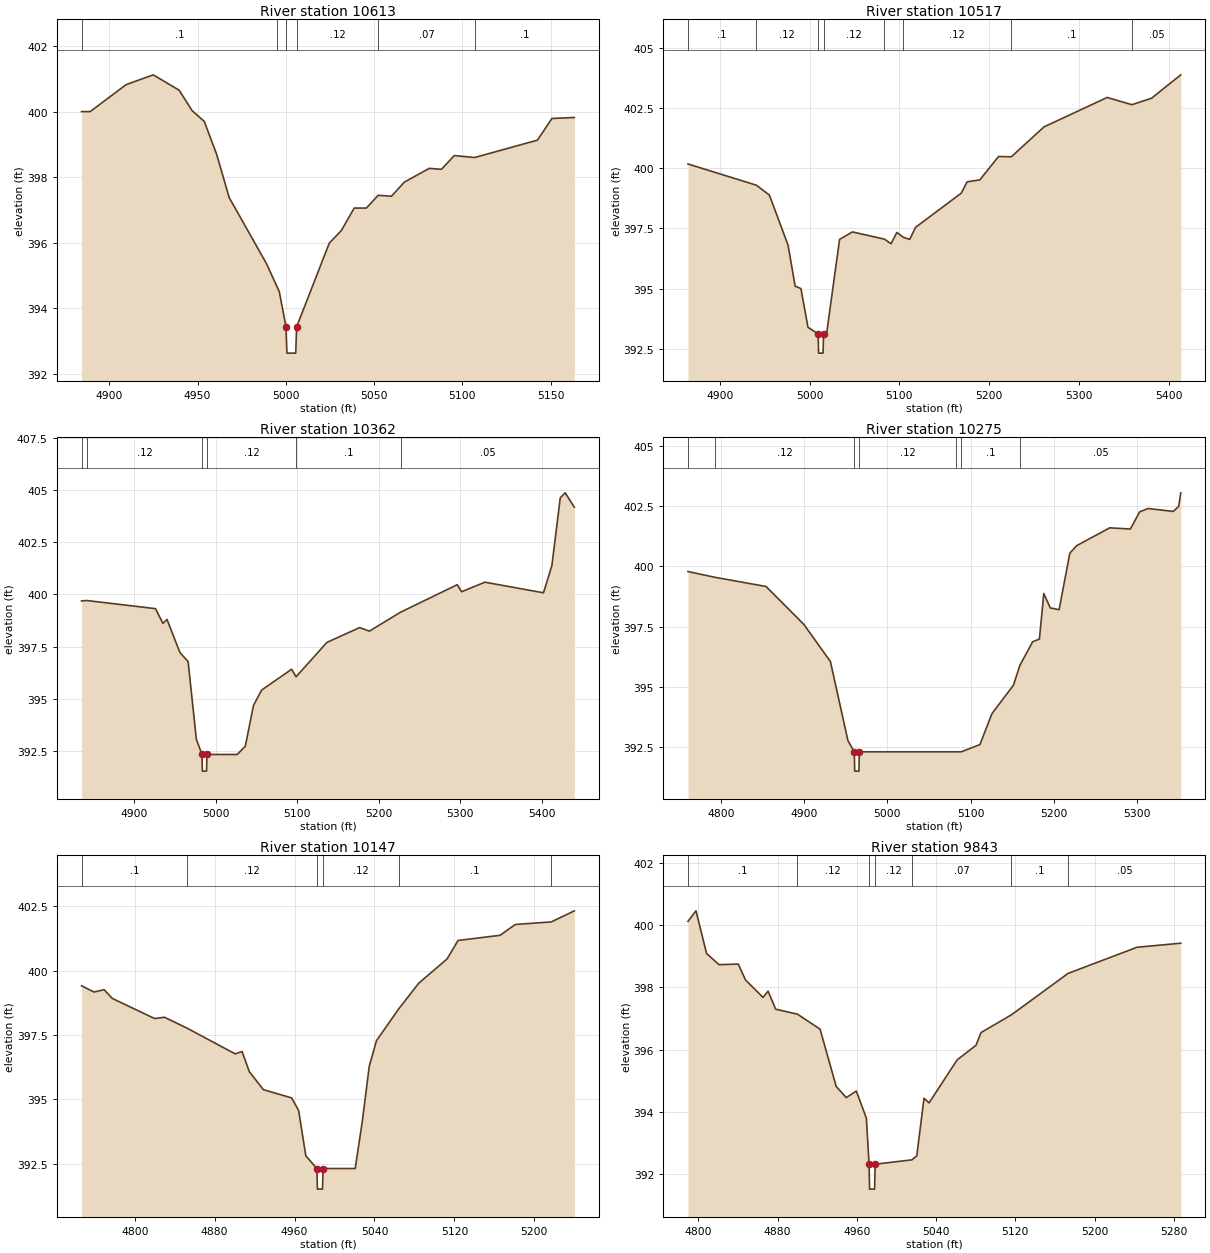
Type RM Length L Ch R = 1,10613,96,96,96
BEGIN DESCRIPTION:
Mapping XS f95fa0c9
END DESCRIPTION:
XS GIS Cut Line= 4
      2074861.50     13457910.29      2074869.09     13457950.39
      2075025.34     13458097.96      2075047.03     13458106.64
#Sta/Elev= 30
  4884.3  400.00  4889.2  400.00  4909.5  400.82  4924.9  401.12  4939.6  400.65
  4946.9  400.03  4953.8  399.70  4960.8  398.70  4967.9  397.38  4989.0  395.37
  4995.2  394.64  4996.3  394.51  5000.1  393.44  5000.6  392.64  5005.6  392.64
  5006.1  393.44  5024.6  395.99  5031.5  396.38  5038.7  397.06  5045.6  397.06
  5052.3  397.45  5059.8  397.42  5067.1  397.85  5081.2  398.27  5088.1  398.24
  5095.4  398.66  5106.9  398.60  5142.5  399.13  5150.7  399.79  5163.4  399.82
#Mann=6,-1,0
  4884.3     0.1       0  4995.2    0.12       0  5000.1    0.07       0
  5006.1    0.12       0  5052.3    0.07       0  5106.9     0.1       0
Bank Sta=5000.1,5006.1
Exp/Cntr=0.3,0.1

Type RM Length L Ch R = 1,10517,155,155,155
BEGIN DESCRIPTION:
Mapping XS 22ce54ac
END DESCRIPTION:
XS GIS Cut Line= 4
      2074812.28     13457936.13      2074802.90     13457999.22
      2074966.74     13458197.79      2075141.51     13458343.72
#Sta/Elev= 30
  4864.5  400.17  4940.7  399.29  4955.2  398.88  4976.0  396.80  4983.9  395.10
  4990.3  395.00  4998.2  393.39  5009.5  393.12  5010.0  392.32  5015.0  392.32
  5015.5  393.12  5019.0  393.15  5033.4  397.04  5047.7  397.35  5083.4  397.05
  5090.7  396.86  5097.2  397.33  5104.2  397.13  5111.5  397.04  5118.0  397.54
  5168.9  398.96  5175.4  399.43  5189.6  399.51  5210.4  400.48  5224.7  400.47
  5261.1  401.71  5331.4  402.93  5359.0  402.63  5380.9  402.90  5413.4  403.87
#Mann=8,-1,0
  4864.5     0.1       0  4940.7    0.12       0  5009.5    0.07       0
  5015.5    0.12       0  5083.4    0.07       0  5104.2    0.12       0
  5224.7     0.1       0  5359.0    0.05       0
Bank Sta=5009.5,5015.5
Exp/Cntr=0.3,0.1

Type RM Length L Ch R = 1,10362,87,87,87
BEGIN DESCRIPTION:
Mapping XS 675f8ed7
END DESCRIPTION:
XS GIS Cut Line= 4
      2074785.54     13457995.96      2074721.52     13458044.79
      2074704.16     13458313.89      2074762.37     13458561.87
#Sta/Elev= 30
  4835.1  399.69  4841.6  399.71  4925.9  399.32  4935.0  398.61  4940.0  398.80
  4955.9  397.21  4965.9  396.78  4976.0  393.05  4982.9  392.32  4983.4  391.52
  4988.5  391.52  4989.0  392.32  5026.1  392.32  5036.1  392.71  5046.1  394.67
  5056.1  395.41  5092.9  396.41  5098.4  396.05  5136.3  397.70  5176.4  398.41
  5188.4  398.24  5226.7  399.15  5296.3  400.47  5301.5  400.13  5330.2  400.59
  5402.1  400.08  5412.4  401.39  5422.7  404.64  5428.7  404.88  5440.0  404.19
#Mann=6,-1,0
  4835.1     0.1       0  4841.6    0.12       0  4982.9    0.07       0
  4989.0    0.12       0  5098.4     0.1       0  5226.7    0.05       0
Bank Sta=4982.9,4989
Exp/Cntr=0.3,0.1

Type RM Length L Ch R = 1,10275,128,128,128
BEGIN DESCRIPTION:
Mapping XS 4f2f3a6e
END DESCRIPTION:
XS GIS Cut Line= 4
      2074780.09     13457977.53      2074668.35     13458029.60
      2074542.48     13458395.27      2074623.71     13458410.23
#Sta/Elev= 30
  4760.2  399.79  4792.7  399.55  4854.1  399.17  4899.8  397.59  4931.5  396.06
  4952.6  392.78  4960.2  392.32  4960.7  391.52  4965.8  391.52  4966.3  392.32
  5082.2  392.32  5088.9  392.32  5111.3  392.62  5125.7  393.90  5151.6  395.08
  5159.3  395.90  5174.7  396.88  5182.8  396.99  5188.1  398.88  5195.9  398.28
  5206.5  398.21  5219.4  400.55  5227.6  400.86  5267.4  401.60  5292.2  401.55
  5303.3  402.26  5313.4  402.40  5343.9  402.28  5350.3  402.49  5352.8  403.05
#Mann=7,-1,0
  4760.2     0.1       0  4792.7    0.12       0  4960.2    0.07       0
  4966.3    0.12       0  5082.2    0.07       0  5088.9     0.1       0
  5159.3    0.05       0
Bank Sta=4960.2,4966.3
Exp/Cntr=0.3,0.1

Type RM Length L Ch R = 1,10147,304,304,304
BEGIN DESCRIPTION:
Mapping XS 8031fa01
END DESCRIPTION:
XS GIS Cut Line= 4
      2074757.37     13457935.21      2074680.29     13457923.26
      2074464.36     13458134.85      2074423.15     13458240.05
#Sta/Elev= 30
  4746.8  399.41  4759.3  399.17  4769.4  399.26  4777.6  398.92  4819.9  398.14
  4829.8  398.19  4852.3  397.77  4900.5  396.77  4907.5  396.86  4914.7  396.08
  4928.8  395.38  4957.1  395.06  4964.1  394.57  4971.3  392.81  4982.4  392.32
  4982.9  391.52  4988.0  391.52  4988.5  392.32  5020.7  392.32  5027.8  394.14
  5034.8  396.29  5042.0  397.28  5064.2  398.51  5084.3  399.51  5112.6  400.45
  5123.7  401.17  5165.7  401.37  5181.0  401.79  5217.0  401.89  5240.1  402.32
#Mann=6,-1,0
  4746.8     0.1       0  4852.3    0.12       0  4982.4    0.07       0
  4988.5    0.12       0  5064.2     0.1       0  5217.0    0.05       0
Bank Sta=4982.4,4988.5
Exp/Cntr=0.3,0.1

Type RM Length L Ch R = 1,9843,329,329,329
BEGIN DESCRIPTION:
Mapping XS 0d3da93a
END DESCRIPTION:
XS GIS Cut Line= 4
      2074709.57     13457762.63      2074692.22     13457714.93
      2074334.15     13457782.20      2074301.61     13457858.13
#Sta/Elev= 30
  4789.4  400.12  4797.5  400.46  4808.2  399.09  4820.8  398.73  4840.2  398.75
  4847.5  398.24  4865.2  397.68  4870.3  397.88  4878.0  397.30  4900.0  397.14
  4922.8  396.66  4939.1  394.82  4949.3  394.46  4959.4  394.67  4969.6  393.80
  4972.3  392.32  4972.8  391.52  4977.9  391.52  4978.4  392.32  5015.5  392.46
  5020.5  392.59  5027.8  394.44  5032.9  394.29  5061.2  395.67  5080.3  396.14
  5085.4  396.55  5116.1  397.12  5173.3  398.45  5243.0  399.29  5287.1  399.42
#Mann=7,-1,0
  4789.4     0.1       0  4900.0    0.12       0  4972.3    0.07       0
  4978.4    0.12       0  5015.5    0.07       0  5116.1     0.1       0
  5173.3    0.05       0
Bank Sta=4972.3,4978.4
Exp/Cntr=0.3,0.1

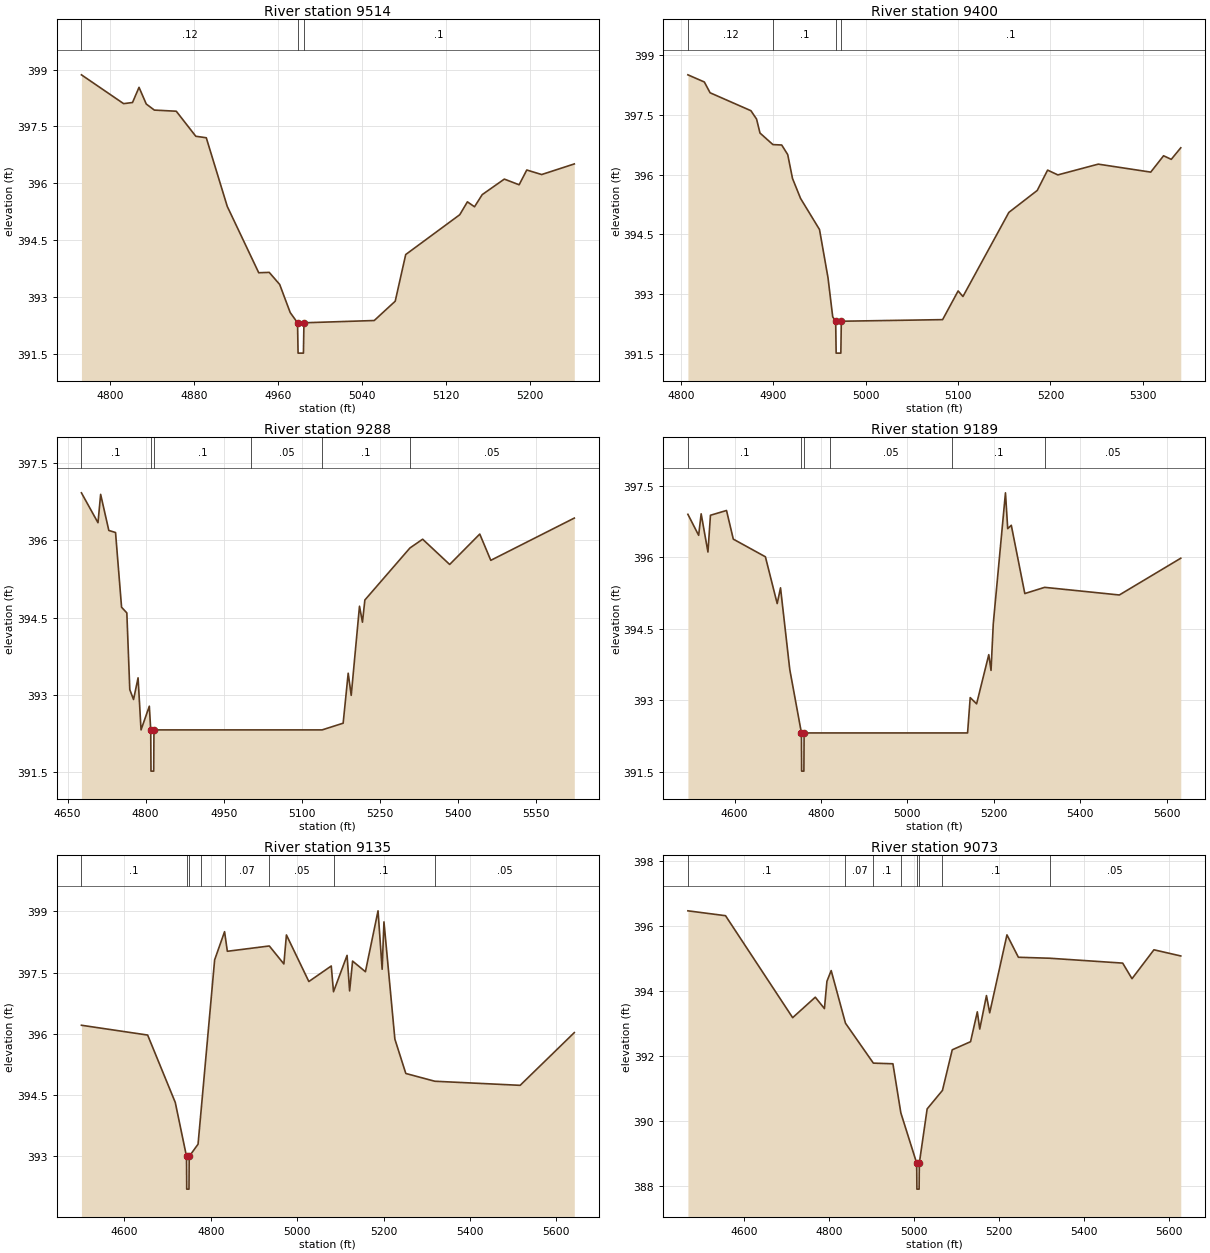
Type RM Length L Ch R = 1,9514,114,114,114
BEGIN DESCRIPTION:
Mapping XS 10b2c9a9
END DESCRIPTION:
XS GIS Cut Line= 4
      2074704.71     13457482.18      2074625.29     13457423.59
      2074402.63     13457417.08      2074294.53     13457518.67
#Sta/Elev= 30
  4772.3  398.86  4812.5  398.10  4821.0  398.13  4827.2  398.53  4834.1  398.09
  4841.8  397.93  4862.7  397.90  4881.3  397.24  4891.3  397.20  4911.3  395.39
  4941.3  393.64  4951.3  393.65  4961.3  393.33  4971.3  392.59  4978.3  392.32
  4978.8  391.52  4983.9  391.52  4984.4  392.32  5051.4  392.38  5071.4  392.89
  5081.4  394.12  5132.9  395.17  5140.2  395.51  5147.0  395.38  5154.3  395.70
  5175.4  396.11  5189.5  395.96  5196.8  396.35  5211.0  396.23  5242.1  396.51
#Mann=3,-1,0
  4772.3    0.12       0  4978.3    0.07       0  4984.4     0.1       0
Bank Sta=4978.3,4984.4
Exp/Cntr=0.3,0.1

Type RM Length L Ch R = 1,9400,112,112,112
BEGIN DESCRIPTION:
Mapping XS f8b767c6
END DESCRIPTION:
XS GIS Cut Line= 4
      2074682.59     13457401.47      2074635.71     13457336.35
      2074331.02     13457268.64      2074245.84     13457380.92
#Sta/Elev= 30
  4807.7  398.50  4825.5  398.32  4831.7  398.05  4875.9  397.60  4882.0  397.39
  4885.7  397.04  4899.7  396.75  4909.2  396.74  4915.7  396.50  4920.9  395.90
  4929.6  395.40  4950.1  394.62  4959.3  393.41  4964.4  392.43  4967.6  392.32
  4968.1  391.52  4973.2  391.52  4973.7  392.32  5083.3  392.36  5100.1  393.08
  5105.3  392.94  5155.0  395.05  5185.7  395.60  5196.9  396.11  5208.0  395.99
  5251.7  396.26  5308.5  396.06  5322.4  396.47  5330.7  396.38  5341.0  396.67
#Mann=4,-1,0
  4807.7    0.12       0  4899.7     0.1       0  4967.6    0.07       0
  4973.7     0.1       0
Bank Sta=4967.6,4973.7
Exp/Cntr=0.3,0.1

Type RM Length L Ch R = 1,9288,99,99,99
BEGIN DESCRIPTION:
Mapping XS 8c801df6
END DESCRIPTION:
XS GIS Cut Line= 5
      2074806.28     13457391.03      2074795.86     13457338.95
      2074367.48     13457095.46      2074276.33     13457112.39
      2074014.97     13457275.61
#Sta/Elev= 30
  4676.7  396.92  4708.5  396.34  4713.6  396.89  4729.3  396.19  4742.2  396.15
  4753.8  394.70  4763.9  394.59  4769.6  393.10  4776.8  392.91  4785.5  393.33
  4791.2  392.32  4807.1  392.78  4809.8  392.32  4810.3  391.52  4815.5  391.52
  4816.0  392.32  5002.9  392.32  5139.0  392.32  5179.4  392.45  5189.1  393.42
  5194.9  392.99  5210.8  394.72  5216.5  394.41  5221.1  394.84  5307.7  395.85
  5332.1  396.02  5384.0  395.53  5441.8  396.12  5463.0  395.61  5623.4  396.43
#Mann=6,-1,0
  4676.7     0.1       0  4809.8    0.07       0  4816.0     0.1       0
  5002.9    0.05       0  5139.0     0.1       0  5307.7    0.05       0
Bank Sta=4809.8,4816
Exp/Cntr=0.3,0.1

Type RM Length L Ch R = 1,9189,54,54,54
BEGIN DESCRIPTION:
Mapping XS 3637ab58
END DESCRIPTION:
XS GIS Cut Line= 4
      2074923.46     13457460.03      2074807.58     13457262.13
      2074444.30     13457019.94      2073988.56     13457153.69
#Sta/Elev= 30
  4492.1  396.90  4517.0  396.46  4522.8  396.91  4538.5  396.11  4544.3  396.88
  4581.5  396.98  4597.2  396.38  4671.5  396.01  4698.8  395.03  4706.5  395.36
  4727.9  393.65  4754.9  392.32  4755.4  391.52  4760.6  391.52  4761.1  392.32
  4820.4  392.32  5103.9  392.32  5139.5  392.32  5145.6  393.06  5160.4  392.93
  5188.6  393.96  5193.8  393.63  5199.0  394.61  5227.2  397.35  5232.4  396.60
  5240.7  396.67  5272.0  395.24  5317.9  395.37  5490.8  395.21  5633.0  395.98
#Mann=6,-1,0
  4492.1     0.1       0  4754.9   0.033       0  4761.1     0.1       0
  4820.4    0.05       0  5103.9     0.1       0  5317.9    0.05       0
Bank Sta=4754.9,4761.1
Exp/Cntr=0.3,0.1

Type RM Length L Ch R = 1,9135,62,62,62
BEGIN DESCRIPTION:
Mapping XS ff2686a7
END DESCRIPTION:
XS GIS Cut Line= 5
      2074969.02     13457355.86      2074837.53     13457193.12
      2074742.48     13457152.76      2074416.96     13456949.63
      2073998.79     13457101.58
#Sta/Elev= 30
  4500.4  396.21  4653.7  395.97  4717.7  394.32  4743.7  393.00  4744.2  392.20
  4749.4  392.20  4749.9  393.00  4770.4  393.30  4777.6  394.14  4808.8  397.81
  4831.8  398.50  4838.2  398.02  4935.4  398.15  4969.1  397.71  4975.0  398.42
  5026.9  397.28  5078.8  397.66  5084.0  397.03  5115.4  397.92  5121.3  397.05
  5128.2  397.78  5157.9  397.52  5187.1  399.01  5196.6  397.58  5200.8  398.74
  5226.1  395.87  5251.4  395.03  5318.5  394.84  5516.1  394.74  5641.5  396.03
#Mann=8,-1,0
  4500.4     0.1       0  4743.7   0.033       0  4749.9     0.1       0
  4777.6    0.05       0  4831.8    0.07       0  4935.4    0.05       0
  5084.0     0.1       0  5318.5    0.05       0
Bank Sta=4743.7,4749.9
Exp/Cntr=0.3,0.1

Type RM Length L Ch R = 1,9073,458,458,458
BEGIN DESCRIPTION:
Mapping XS 9fff6161
END DESCRIPTION:
XS GIS Cut Line= 4
      2074998.99     13457324.63      2074885.71     13457160.57
      2074445.60     13456907.96      2074014.94     13457046.46
#Sta/Elev= 30
  4468.5  396.46  4557.0  396.31  4714.9  393.17  4768.1  393.80  4789.6  393.45
  4795.5  394.29  4805.5  394.62  4839.1  393.00  4904.7  391.77  4950.7  391.75
  4969.3  390.24  5006.6  388.69  5007.1  387.89  5012.3  387.89  5012.8  388.69
  5031.2  390.36  5067.2  390.93  5090.2  392.18  5133.3  392.43  5149.2  393.35
  5154.9  392.82  5170.7  393.85  5178.3  393.32  5218.9  395.72  5245.8  395.03
  5319.4  395.00  5491.1  394.85  5513.0  394.37  5564.6  395.26  5627.7  395.07
#Mann=8,-1,0
  4468.5     0.1       0  4839.1    0.07       0  4904.7     0.1       0
  4969.3    0.05       0  5006.6   0.033       0  5012.8    0.05       0
  5067.2     0.1       0  5319.4    0.05       0
Bank Sta=5006.6,5012.8
Exp/Cntr=0.3,0.1

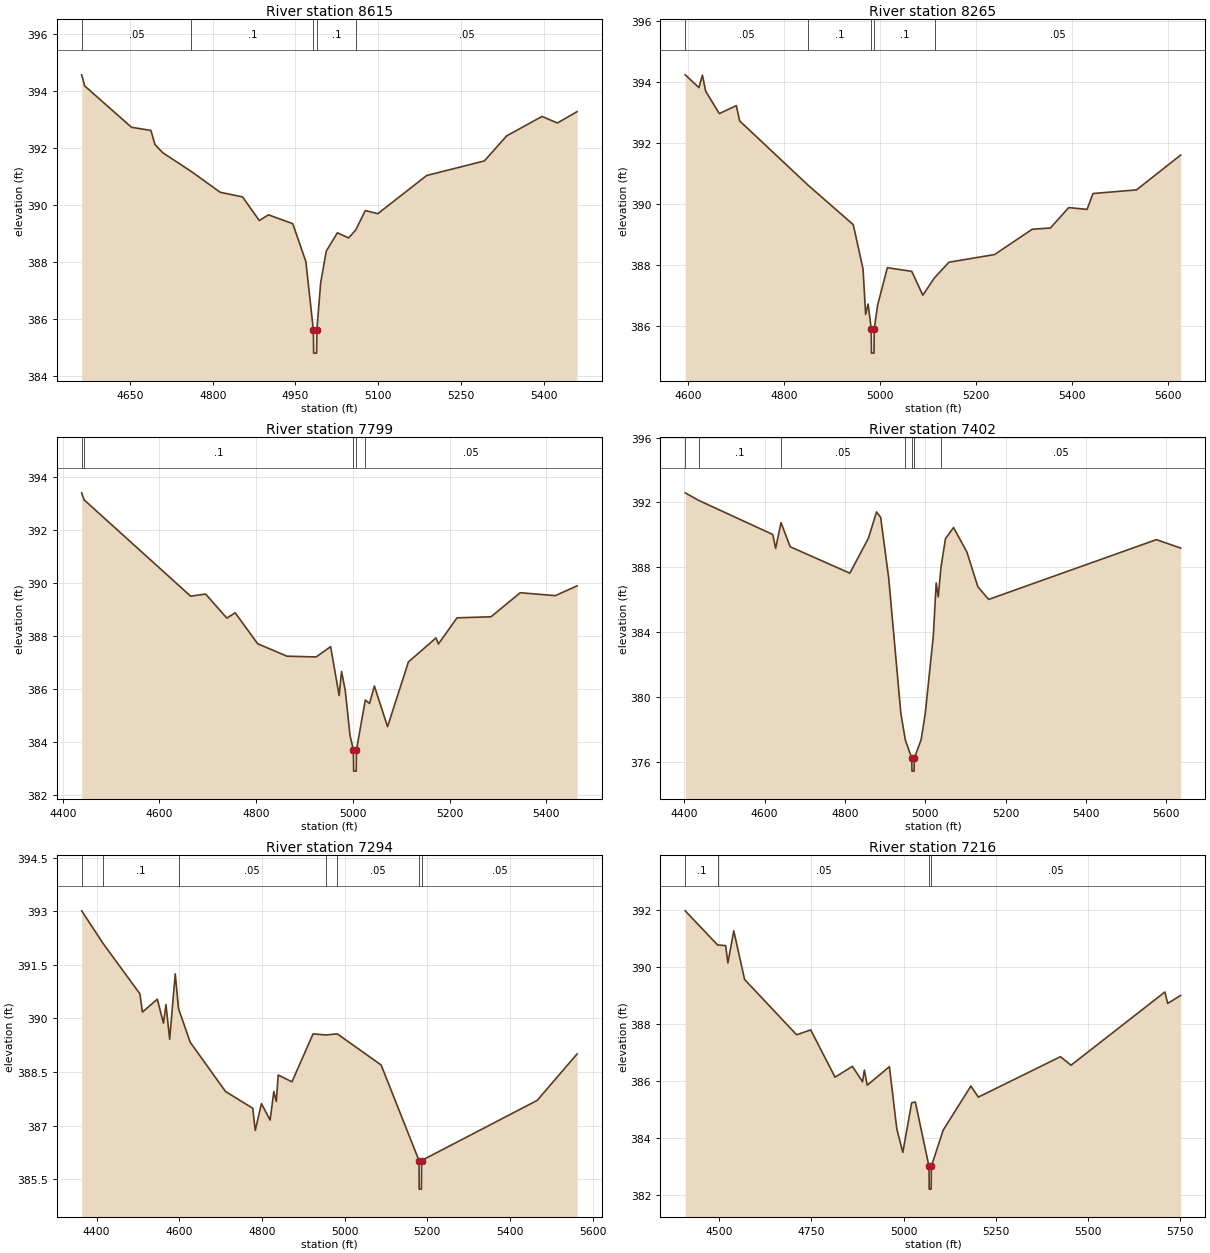
Type RM Length L Ch R = 1,8615,350,350,350
BEGIN DESCRIPTION:
Mapping XS 780e542e
END DESCRIPTION:
XS GIS Cut Line= 4
      2075161.26     13456756.45      2075051.07     13456648.85
      2074552.37     13456570.72      2074322.67     13456639.25
#Sta/Elev= 30
  4562.3  394.56  4567.8  394.17  4652.7  392.72  4687.9  392.61  4695.1  392.12
  4709.2  391.83  4761.1  391.17  4813.6  390.44  4854.0  390.28  4884.4  389.45
  4901.1  389.65  4945.1  389.34  4968.9  388.01  4982.5  385.60  4983.0  384.80
  4988.3  384.80  4988.8  385.60  4995.7  387.26  5005.9  388.38  5026.1  389.02
  5046.4  388.84  5059.3  389.12  5076.7  389.80  5099.3  389.69  5188.1  391.03
  5292.6  391.54  5333.1  392.42  5397.2  393.10  5425.1  392.87  5460.8  393.27
#Mann=5,-1,0
  4562.3    0.05       0  4761.1     0.1       0  4982.5    0.07       0
  4988.8     0.1       0  5059.3    0.05       0
Bank Sta=4982.5,4988.8
Exp/Cntr=0.3,0.1

Type RM Length L Ch R = 1,8265,466,466,466
BEGIN DESCRIPTION:
Mapping XS 684b30ee
END DESCRIPTION:
XS GIS Cut Line= 4
      2075265.44     13456535.10      2075087.53     13456350.67
      2074617.48     13456268.64      2074354.03     13456410.03
#Sta/Elev= 30
  4594.8  394.24  4623.4  393.82  4630.6  394.23  4637.5  393.70  4665.8  392.97
  4701.3  393.23  4708.2  392.73  4850.4  390.63  4945.0  389.33  4965.3  387.88
  4970.8  386.39  4975.9  386.73  4982.4  385.92  4982.9  385.12  4988.2  385.12
  4988.7  385.92  4995.7  386.69  5016.0  387.92  5066.8  387.80  5089.9  387.02
  5114.3  387.59  5144.4  388.10  5239.4  388.35  5317.9  389.18  5355.8  389.22
  5394.0  389.89  5432.2  389.83  5444.5  390.35  5535.3  390.47  5627.2  391.61
#Mann=5,-1,0
  4594.8    0.05       0  4850.4     0.1       0  4982.4    0.07       0
  4988.7     0.1       0  5114.3    0.05       0
Bank Sta=4982.4,4988.7
Exp/Cntr=0.3,0.1

Type RM Length L Ch R = 1,7799,397,397,397
BEGIN DESCRIPTION:
Mapping XS f623ab4d
END DESCRIPTION:
XS GIS Cut Line= 5
      2075343.56     13456061.13      2075213.32     13455990.80
      2075038.05     13455910.57      2074469.04     13455967.86
      2074454.71     13456078.57
#Sta/Elev= 30
  4439.2  393.42  4443.9  393.16  4664.5  389.51  4695.4  389.59  4739.3  388.68
  4756.6  388.88  4803.1  387.71  4863.5  387.24  4923.8  387.21  4953.9  387.60
  4971.5  385.75  4976.5  386.66  4984.1  385.95  4994.1  384.23  5001.0  383.69
  5001.5  382.89  5006.8  382.89  5007.3  383.69  5025.6  385.58  5034.3  385.45
  5044.4  386.11  5071.6  384.57  5114.7  387.02  5171.8  387.93  5176.8  387.70
  5215.2  388.69  5285.6  388.73  5345.9  389.64  5418.4  389.53  5463.5  389.90
#Mann=5,-1,0
  4439.2    0.05       0  4443.9     0.1       0  5001.0    0.07       0
  5007.3     0.1       0  5025.6    0.05       0
Bank Sta=5001,5007.3
Exp/Cntr=0.3,0.1

Type RM Length L Ch R = 1,7402,108,108,108
BEGIN DESCRIPTION:
Mapping XS 1402b111
END DESCRIPTION:
XS GIS Cut Line= 4
      2075424.26     13455751.22      2075126.59     13455525.15
      2074751.59     13455577.23      2074388.89     13455893.50
#Sta/Elev= 30
  4402.2  392.59  4435.9  392.12  4620.1  390.02  4627.3  389.16  4640.7  390.75
  4663.7  389.26  4812.1  387.63  4858.4  389.79  4878.5  391.41  4888.8  391.08
  4908.8  387.34  4939.1  378.98  4950.2  377.34  4966.3  376.21  4966.8  375.41
  4972.1  375.41  4972.6  376.21  4989.6  377.35  4999.7  378.93  5019.9  383.74
  5027.1  387.03  5032.2  386.17  5039.0  387.99  5050.2  389.76  5070.4  390.45
  5103.8  388.92  5130.9  386.79  5157.7  386.01  5575.4  389.70  5635.8  389.18
#Mann=7,-1,0
  4402.2    0.05       0  4435.9     0.1       0  4640.7    0.05       0
  4950.2    0.12       0  4966.3    0.07       0  4972.6    0.12       0
  5039.0    0.05       0
Bank Sta=4966.3,4972.6
Exp/Cntr=0.3,0.1

Type RM Length L Ch R = 1,7294,78,78,78
BEGIN DESCRIPTION:
Mapping XS bb41b7c1
END DESCRIPTION:
XS GIS Cut Line= 4
      2075452.91     13455691.32      2075056.28     13455424.89
      2074768.52     13455466.56      2074464.38     13455771.00
#Sta/Elev= 30
  4363.8  393.01  4416.1  392.09  4504.7  390.69  4510.8  390.18  4546.8  390.54
  4561.7  389.87  4567.8  390.39  4576.7  389.42  4590.2  391.25  4598.1  390.28
  4626.3  389.34  4711.8  387.96  4777.8  387.49  4783.8  386.87  4798.8  387.62
  4819.8  387.16  4828.8  387.96  4834.8  387.68  4839.4  388.42  4872.7  388.23
  4923.7  389.57  4954.8  389.54  4982.4  389.57  5088.5  388.70  5180.1  386.03
  5180.6  385.23  5185.9  385.23  5186.4  386.03  5466.1  387.71  5562.7  389.01
#Mann=7,-1,0
  4363.8    0.05       0  4416.1     0.1       0  4598.1    0.05       0
  4954.8    0.12       0  4982.4    0.05       0  5180.1    0.03       0
  5186.4    0.05       0
Bank Sta=5180.1,5186.4
Exp/Cntr=0.3,0.1

Type RM Length L Ch R = 1,7216,234,234,234
BEGIN DESCRIPTION:
Mapping XS fa9f54e5
END DESCRIPTION:
XS GIS Cut Line= 4
      2075437.26     13455561.10      2075049.77     13455355.88
      2074670.86     13455391.04      2074329.11     13455788.89
#Sta/Elev= 30
  4407.6  391.96  4495.5  390.76  4517.2  390.74  4523.3  390.13  4539.2  391.26
  4568.6  389.55  4709.6  387.61  4747.9  387.78  4813.9  386.12  4860.9  386.50
  4888.4  385.96  4893.4  386.37  4901.1  385.84  4961.3  386.49  4981.4  384.30
  4997.7  383.48  5021.6  385.22  5031.6  385.25  5068.7  382.99  5069.2  382.19
  5074.5  382.19  5075.0  382.99  5107.1  384.26  5182.3  385.81  5202.4  385.42
  5425.2  386.84  5453.8  386.54  5708.4  389.11  5716.0  388.71  5751.1  388.99
#Mann=4,-1,0
  4407.6     0.1       0  4495.5    0.05       0  5068.7    0.03       0
  5075.0    0.05       0
Bank Sta=5068.7,5075
Exp/Cntr=0.3,0.1