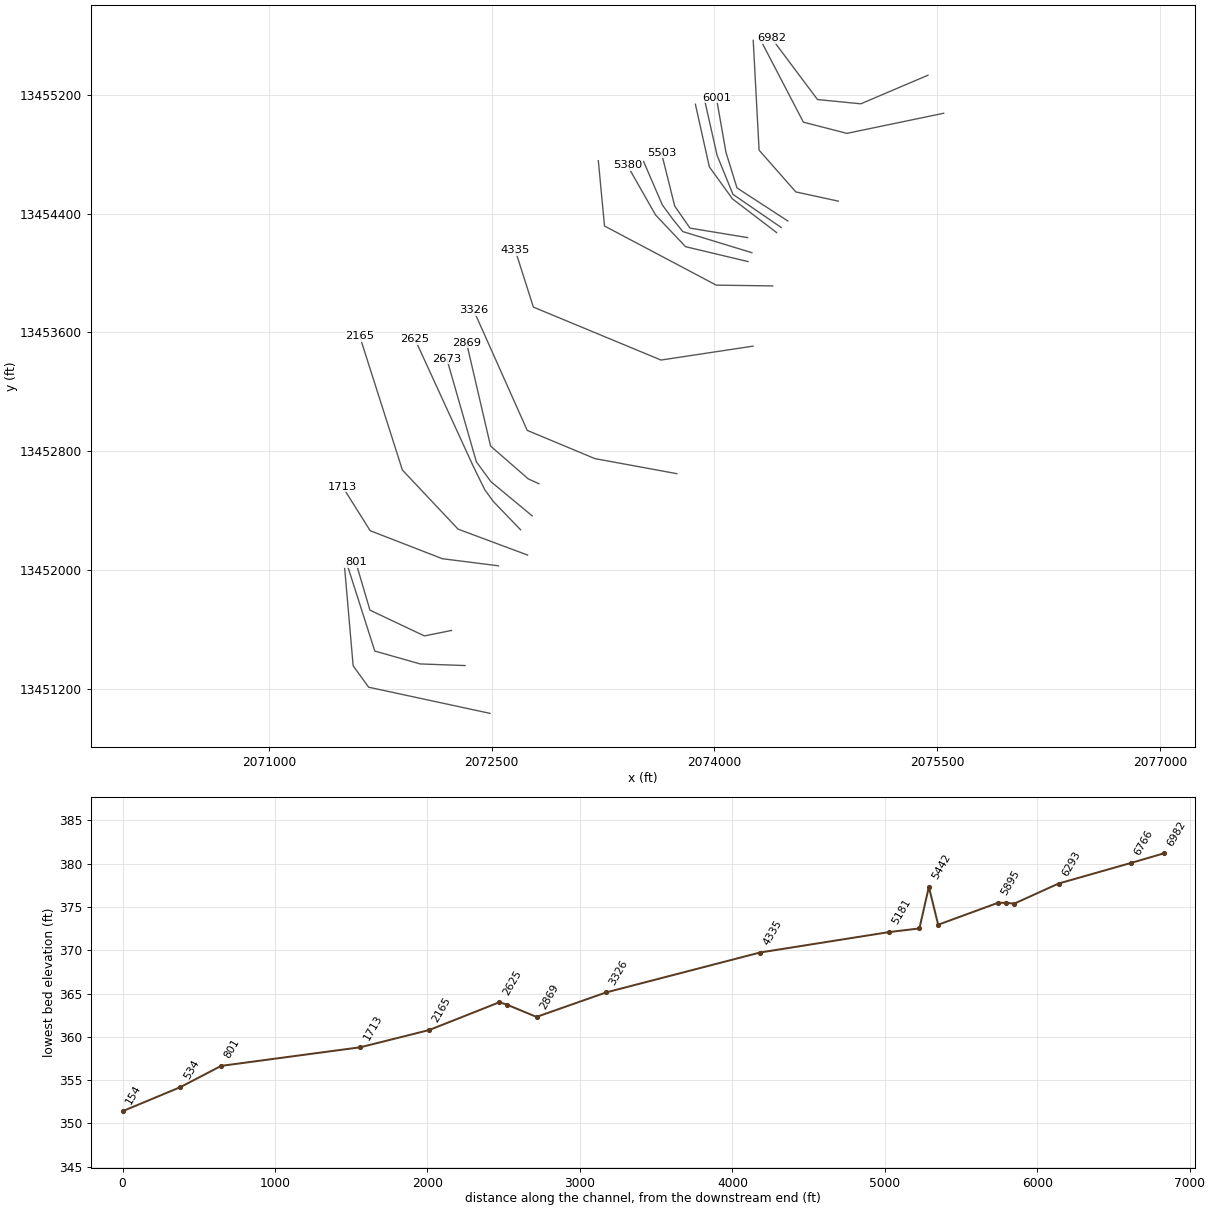
HEC-RAS study UNT 24 in Lagunillas Cr Wtrshd.prj: UNT 24 in Lagunillas Cr Wtrshd Base Level Engineering

--- UNT 24 in Lagunillas Cr Wtrshd.g01 (geometry) --- (continued)

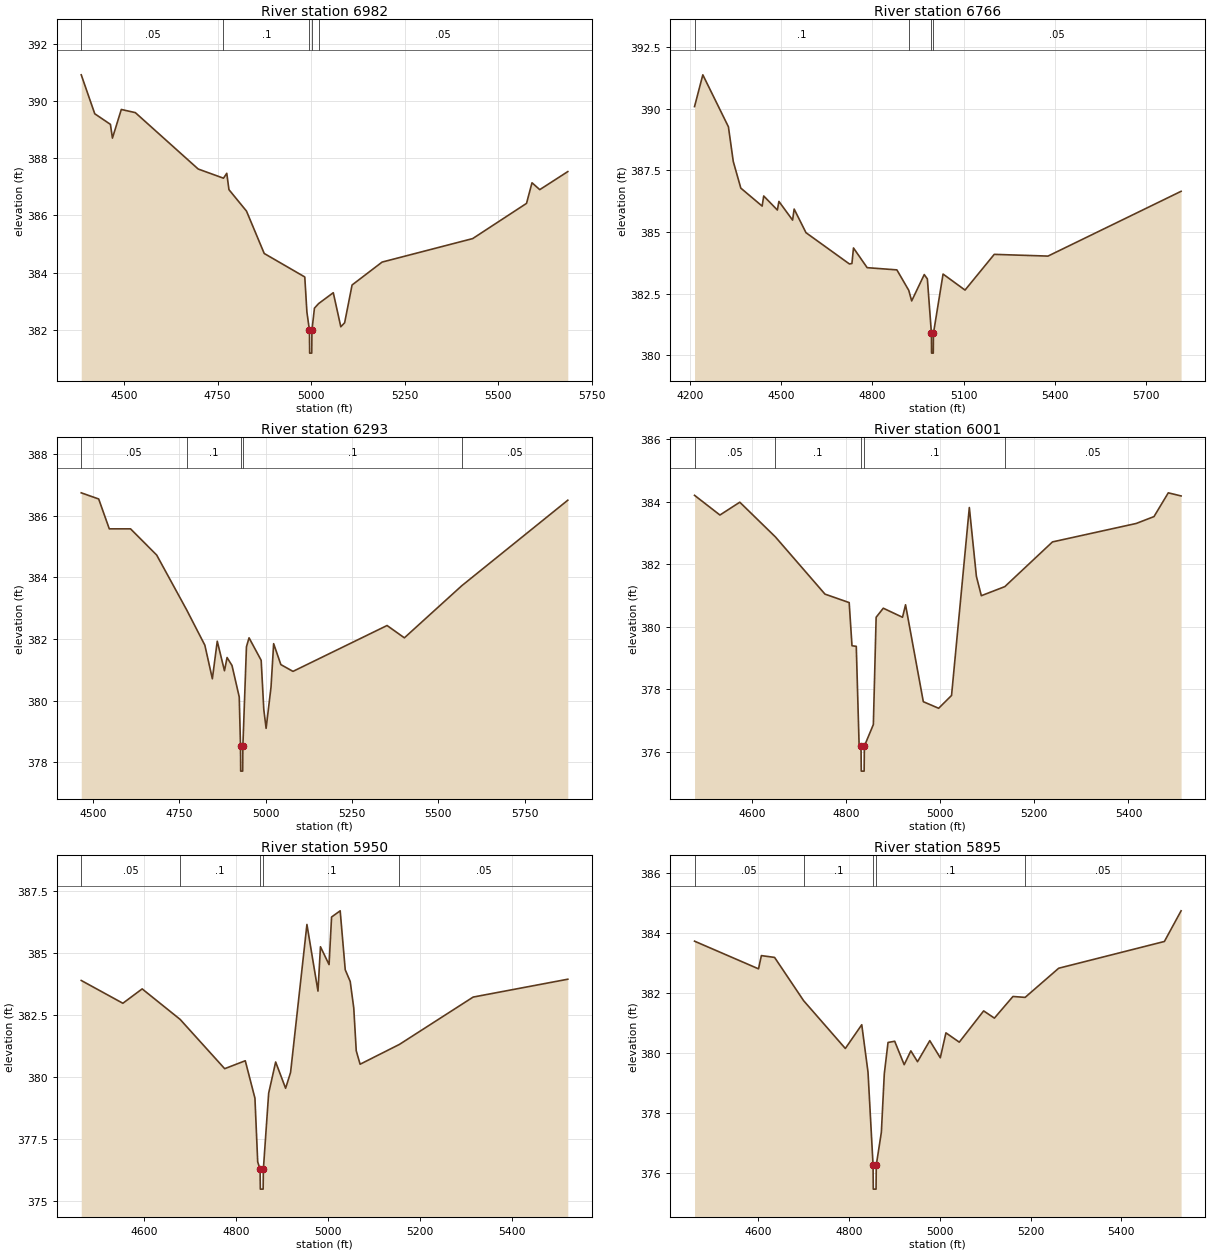
Type RM Length L Ch R = 1,6982,216,216,216
BEGIN DESCRIPTION:
Mapping XS b6e35f63
END DESCRIPTION:
XS GIS Cut Line= 4
      2075437.83     13455332.17      2074985.97     13455139.73
      2074694.30     13455168.38      2074385.92     13455580.84
#Sta/Elev= 30
  4386.1  390.91  4422.2  389.55  4464.0  389.18  4469.4  388.70  4493.1  389.70
  4530.5  389.59  4698.4  387.62  4765.9  387.30  4774.7  387.47  4780.5  386.90
  4827.4  386.15  4874.7  384.67  4983.0  383.85  4988.7  382.62  4995.5  381.99
  4996.0  381.19  5001.6  381.19  5002.1  381.99  5008.8  382.76  5019.9  382.92
  5059.1  383.30  5079.2  382.11  5089.4  382.25  5109.3  383.57  5189.5  384.37
  5431.3  385.19  5575.1  386.42  5589.7  387.14  5610.5  386.90  5685.3  387.53
#Mann=5,-1,0
  4386.1    0.05       0  4765.9     0.1       0  4995.5    0.07       0
  5002.1     0.1       0  5019.9    0.05       0
Bank Sta=4995.5,5002.1
Exp/Cntr=0.3,0.1

Type RM Length L Ch R = 1,6766,473,473,473
BEGIN DESCRIPTION:
Mapping XS 31fa8e29
END DESCRIPTION:
XS GIS Cut Line= 4
      2075544.16     13455076.08      2074892.22     13454940.52
      2074599.25     13455016.04      2074307.16     13455577.35
#Sta/Elev= 30
  4214.7  390.09  4242.0  391.38  4326.2  389.27  4342.2  387.86  4367.0  386.78
  4437.2  386.05  4442.4  386.46  4487.3  385.89  4492.4  386.24  4537.4  385.48
  4542.5  385.93  4581.5  384.97  4724.5  383.70  4732.7  383.72  4737.8  384.35
  4782.8  383.55  4880.6  383.46  4919.7  382.63  4929.3  382.20  4970.7  383.27
  4981.0  383.09  4994.3  380.88  4994.8  380.08  5000.4  380.08  5000.9  380.88
  5032.6  383.29  5104.9  382.64  5201.0  384.09  5377.9  384.02  5815.9  386.65
#Mann=4,-1,0
  4214.7     0.1       0  4919.7    0.05       0  4994.3    0.03       0
  5000.9    0.05       0
Bank Sta=4994.3,5000.9
Exp/Cntr=0.3,0.1

Type RM Length L Ch R = 1,6293,292,292,292
BEGIN DESCRIPTION:
Mapping XS ccc23a07
END DESCRIPTION:
XS GIS Cut Line= 4
      2074834.38     13454483.96      2074548.47     13454545.98
      2074301.07     13454827.23      2074261.47     13455567.33
#Sta/Elev= 30
  4466.3  386.75  4516.8  386.55  4547.5  385.58  4608.9  385.58  4684.6  384.73
  4771.8  382.94  4824.1  381.80  4845.8  380.71  4860.0  381.93  4880.9  380.97
  4888.4  381.40  4902.7  381.14  4923.6  380.12  4927.3  378.51  4927.8  377.71
  4933.6  377.71  4934.1  378.51  4944.5  381.75  4952.0  382.04  4987.1  381.31
  4994.7  379.71  5001.4  379.10  5015.6  380.44  5023.2  381.85  5044.1  381.17
  5079.2  380.95  5351.5  382.44  5401.6  382.04  5567.5  383.73  5874.6  386.51
#Mann=5,-1,0
  4466.3    0.05       0  4771.8     0.1       0  4927.3    0.07       0
  4934.1     0.1       0  5567.5    0.05       0
Bank Sta=4927.3,4934.1
Exp/Cntr=0.3,0.1

Type RM Length L Ch R = 1,6001,51,51,51
BEGIN DESCRIPTION:
Mapping XS 1e4ed33c
END DESCRIPTION:
XS GIS Cut Line= 4
      2074494.60     13454350.16      2074152.20     13454572.89
      2074077.98     13454812.48      2074013.11     13455181.74
#Sta/Elev= 30
  4477.7  384.20  4531.7  383.57  4573.9  383.98  4649.6  382.87  4755.0  381.04
  4806.4  380.77  4812.4  379.39  4821.5  379.37  4827.5  376.22  4831.6  376.18
  4832.1  375.38  4838.2  375.38  4838.7  376.18  4857.8  376.87  4863.7  380.30
  4878.9  380.59  4919.8  380.30  4926.2  380.70  4964.0  377.60  4996.6  377.39
  5024.0  377.80  5061.8  383.81  5076.8  381.61  5087.3  380.99  5137.2  381.28
  5238.5  382.71  5416.5  383.30  5454.3  383.52  5484.7  384.28  5511.9  384.18
#Mann=5,-1,0
  4477.7    0.05       0  4649.6     0.1       0  4831.6    0.07       0
  4838.7     0.1       0  5137.2    0.05       0
Bank Sta=4831.6,4838.7
Exp/Cntr=0.3,0.1

Type RM Length L Ch R = 1,5950,55,55,55
BEGIN DESCRIPTION:
Mapping XS 5225b843
END DESCRIPTION:
XS GIS Cut Line= 4
      2074450.32     13454305.90      2074124.86     13454529.93
      2074018.09     13454792.95      2073934.99     13455161.31
#Sta/Elev= 30
  4464.2  383.91  4554.6  382.99  4596.5  383.57  4678.9  382.34  4775.7  380.35
  4820.4  380.67  4841.4  379.16  4847.4  376.59  4852.6  376.29  4853.1  375.49
  4859.2  375.49  4859.7  376.29  4871.2  379.36  4886.4  380.62  4908.0  379.56
  4918.8  380.20  4954.3  386.17  4978.3  383.48  4983.7  385.27  5002.4  384.55
  5007.8  386.47  5026.5  386.72  5037.5  384.34  5048.3  383.87  5056.0  382.80
  5061.4  381.07  5069.8  380.53  5155.2  381.33  5315.3  383.24  5520.8  383.96
#Mann=5,-1,0
  4464.2    0.05       0  4678.9     0.1       0  4852.6    0.07       0
  4859.7     0.1       0  5155.2    0.05       0
Bank Sta=4852.6,4859.7
Exp/Cntr=0.3,0.1

Type RM Length L Ch R = 1,5895,392,392,392
BEGIN DESCRIPTION:
Mapping XS 85d7bdf7
END DESCRIPTION:
XS GIS Cut Line= 4
      2074419.02     13454272.08      2074122.25     13454498.68
      2073966.00     13454714.82      2073872.18     13455136.62
#Sta/Elev= 30
  4459.3  383.73  4600.3  382.81  4606.6  383.25  4635.7  383.19  4699.7  381.75
  4791.6  380.16  4827.8  380.95  4841.6  379.37  4852.7  376.28  4853.2  375.48
  4859.3  375.48  4859.8  376.28  4871.0  377.37  4877.5  379.32  4885.7  380.36
  4900.4  380.40  4921.3  379.62  4936.0  380.08  4950.7  379.72  4977.7  380.42
  5000.9  379.85  5013.3  380.68  5042.7  380.37  5096.4  381.41  5120.1  381.17
  5161.0  381.89  5187.8  381.86  5261.8  382.83  5494.7  383.72  5531.5  384.74
#Mann=5,-1,0
  4459.3    0.05       0  4699.7     0.1       0  4852.7    0.07       0
  4859.8     0.1       0  5187.8    0.05       0
Bank Sta=4852.7,4859.8
Exp/Cntr=0.3,0.1

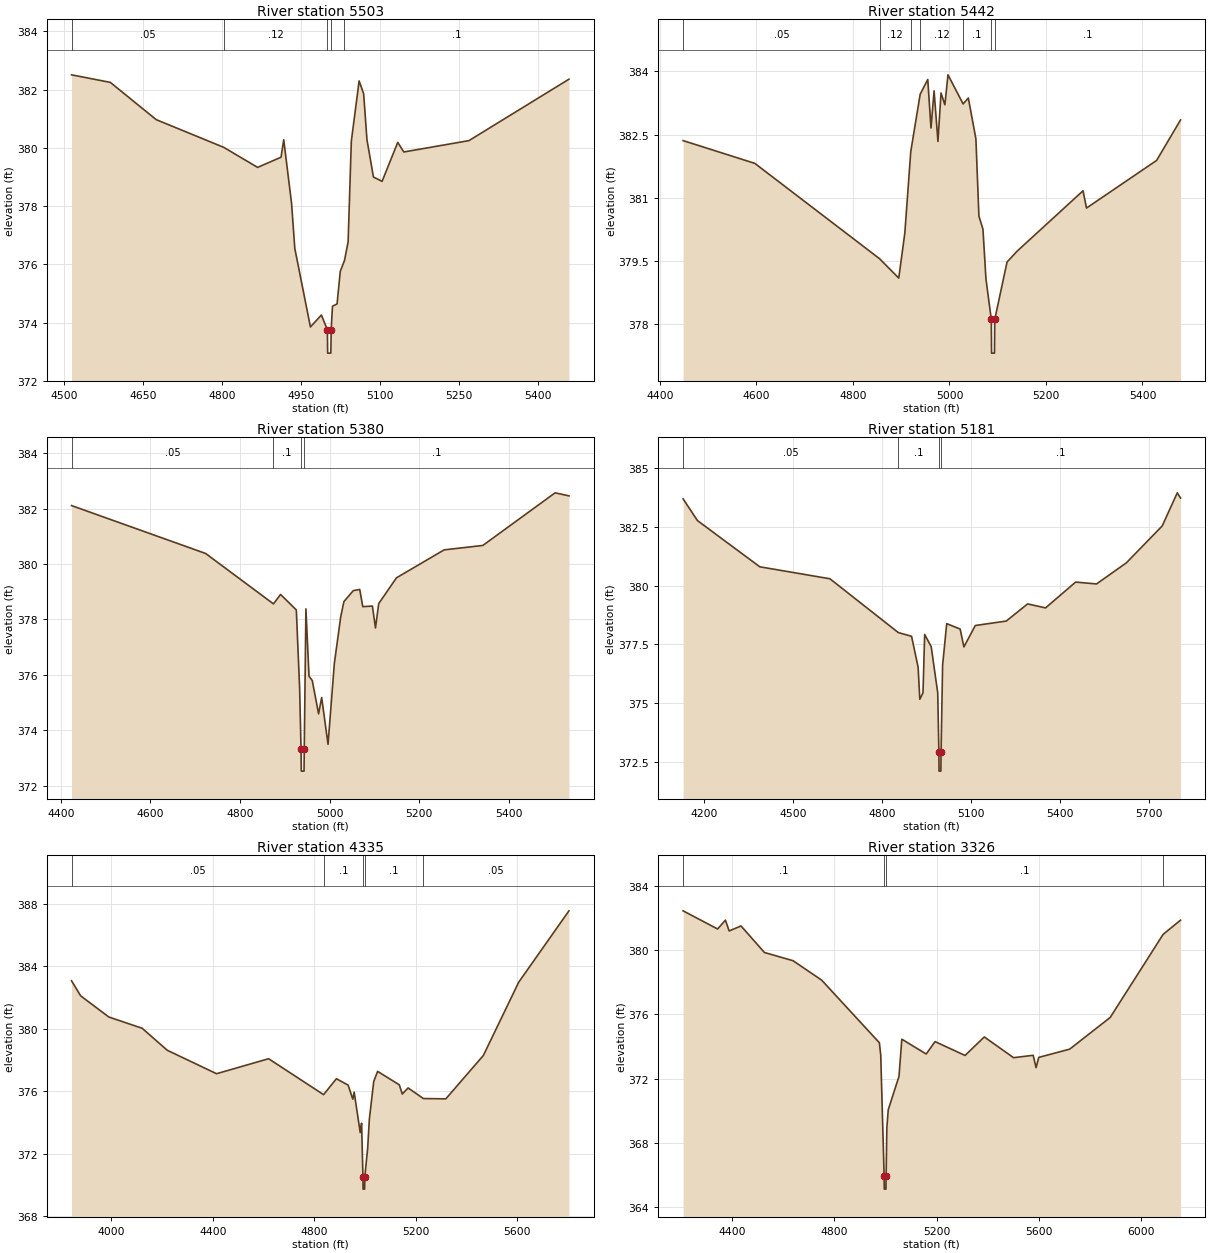
Type RM Length L Ch R = 1,5503,61,61,61
BEGIN DESCRIPTION:
Mapping XS e174936b
END DESCRIPTION:
XS GIS Cut Line= 4
      2074223.77     13454238.19      2073835.79     13454302.06
      2073732.93     13454450.50      2073643.14     13454810.58
#Sta/Elev= 30
  4514.5  382.51  4588.2  382.25  4675.4  380.97  4803.5  380.02  4868.0  379.33
  4912.5  379.68  4917.6  380.28  4932.5  378.09  4938.6  376.55  4968.3  373.85
  4989.2  374.26  5000.5  373.75  5001.0  372.95  5007.1  372.95  5007.7  373.75
  5010.2  374.56  5018.9  374.64  5025.0  375.76  5033.0  376.13  5039.9  376.77
  5046.0  380.23  5060.8  382.30  5069.4  381.86  5075.7  380.28  5088.0  379.00
  5104.4  378.85  5134.2  380.19  5145.7  379.86  5269.5  380.25  5459.4  382.36
#Mann=5,-1,0
  4514.5    0.05       0  4803.5    0.12       0  5000.5    0.07       0
  5007.7    0.12       0  5033.0     0.1       0
Bank Sta=5000.5,5007.7
Exp/Cntr=0.3,0.1

Type RM Length L Ch R = 1,5442,62,62,62
BEGIN DESCRIPTION:
Mapping XS c847d5b2
END DESCRIPTION:
XS GIS Cut Line= 5
      2074252.37     13454136.64      2073787.62     13454278.62
      2073721.21     13454360.65      2073649.60     13454458.31
      2073523.50     13454750.57
#Sta/Elev= 30
  4448.0  382.36  4596.6  381.82  4855.0  379.56  4894.9  379.10  4907.5  380.17
  4919.8  382.10  4939.3  383.46  4955.0  383.81  4961.7  382.66  4968.1  383.54
  4976.1  382.34  4982.5  383.49  4990.5  383.21  4996.9  383.92  5028.3  383.23
  5039.1  383.37  5054.8  382.40  5061.0  380.57  5069.4  380.26  5075.6  379.08
  5086.7  378.12  5087.2  377.32  5093.3  377.32  5093.9  378.12  5119.3  379.48
  5140.4  379.74  5276.8  381.17  5284.0  380.76  5429.3  381.89  5478.9  382.85
#Mann=7,-1,0
  4448.0    0.05       0  4855.0    0.12       0  4919.8     0.1       0
  4939.3    0.12       0  5028.3     0.1       0  5086.7    0.07       0
  5093.9     0.1       0
Bank Sta=5086.7,5093.9
Exp/Cntr=0.3,0.1

Type RM Length L Ch R = 1,5380,199,199,199
BEGIN DESCRIPTION:
Mapping XS ba1322df
END DESCRIPTION:
XS GIS Cut Line= 4
      2074226.33     13454076.74      2073805.85     13454177.06
      2073604.02     13454390.60      2073413.82     13454725.22
#Sta/Elev= 30
  4423.7  382.11  4723.2  380.38  4874.7  378.56  4890.6  378.90  4925.8  378.34
  4933.1  375.53  4936.3  373.32  4936.9  372.52  4943.0  372.52  4943.5  373.32
  4947.2  378.38  4954.1  375.95  4961.4  375.79  4975.5  374.59  4982.4  375.18
  4996.6  373.49  5010.7  376.41  5024.9  378.09  5032.0  378.64  5053.2  379.04
  5067.4  379.08  5074.2  378.46  5095.7  378.48  5102.6  377.69  5109.8  378.57
  5149.4  379.50  5255.9  380.51  5342.4  380.67  5503.8  382.57  5534.7  382.46
#Mann=4,-1,0
  4423.7    0.05       0  4874.7     0.1       0  4936.3    0.07       0
  4943.5     0.1       0
Bank Sta=4936.3,4943.5
Exp/Cntr=0.3,0.1

Type RM Length L Ch R = 1,5181,846,846,846
BEGIN DESCRIPTION:
Mapping XS 09140dfa
END DESCRIPTION:
XS GIS Cut Line= 4
      2074393.06     13453912.68      2074012.80     13453917.89
      2073260.20     13454316.32      2073218.54     13454756.40
#Sta/Elev= 30
  4130.9  383.69  4179.0  382.77  4389.0  380.80  4625.0  380.29  4855.0  378.00
  4899.7  377.84  4921.7  376.52  4927.4  375.16  4938.1  375.43  4943.7  377.92
  4965.7  377.40  4987.7  375.43  4991.6  372.90  4992.1  372.10  4998.3  372.10
  4998.9  372.90  5004.1  376.61  5017.9  378.38  5063.1  378.15  5075.8  377.39
  5114.1  378.30  5218.4  378.49  5290.1  379.22  5350.5  379.05  5451.8  380.15
  5522.1  380.07  5622.6  380.97  5743.1  382.54  5793.8  383.95  5804.8  383.73
#Mann=4,-1,0
  4130.9    0.05       0  4855.0     0.1       0  4991.6    0.07       0
  4998.9     0.1       0
Bank Sta=4991.6,4998.9
Exp/Cntr=0.3,0.1

Type RM Length L Ch R = 1,4335,1009,1009,1009
BEGIN DESCRIPTION:
Mapping XS cbae3dcb
END DESCRIPTION:
XS GIS Cut Line= 4
      2074260.41     13453506.92      2073640.62     13453413.17
      2072781.24     13453769.94      2072658.64     13454154.85
#Sta/Elev= 30
  3842.8  383.08  3878.6  382.12  3989.9  380.76  4121.3  380.04  4220.4  378.63
  4414.6  377.13  4619.9  378.09  4836.6  375.79  4887.2  376.81  4933.4  376.40
  4951.8  375.50  4957.2  375.95  4981.1  373.36  4986.5  373.96  4991.8  370.54
  4992.3  369.74  4998.6  369.74  4999.2  370.54  5010.4  372.35  5017.1  374.22
  5034.3  376.63  5049.6  377.28  5135.1  376.42  5147.0  375.83  5169.8  376.22
  5230.2  375.54  5318.5  375.52  5466.7  378.30  5606.0  382.99  5804.1  387.56
#Mann=5,-1,0
  3842.8    0.05       0  4836.6     0.1       0  4991.8    0.07       0
  4999.2     0.1       0  5230.2    0.05       0
Bank Sta=4991.8,4999.2
Exp/Cntr=0.3,0.1

Type RM Length L Ch R = 1,3326,457,457,457
BEGIN DESCRIPTION:
Mapping XS 2d5f49de
END DESCRIPTION:
XS GIS Cut Line= 4
      2073747.44     13452647.53      2073195.31     13452749.10
      2072739.87     13452939.21      2072377.97     13453750.87
#Sta/Elev= 30
  4209.3  382.43  4344.0  381.30  4374.5  381.85  4389.2  381.18  4435.5  381.49
  4527.0  379.84  4638.8  379.33  4750.7  378.12  4976.1  374.23  4981.5  373.46
  4994.7  365.93  4995.3  365.13  5001.8  365.13  5002.5  365.93  5005.3  368.93
  5010.7  370.06  5052.8  372.14  5063.8  374.45  5159.1  373.53  5193.7  374.30
  5310.9  373.44  5386.1  374.59  5500.5  373.30  5577.1  373.45  5588.3  372.68
  5599.0  373.32  5719.5  373.83  5878.0  375.80  6085.0  380.97  6152.9  381.85
#Mann=4,-1,0
  4209.3     0.1       0  4994.7    0.07       0  5002.5     0.1       0
  6085.0    0.05       0
Bank Sta=4994.7,5002.5
Exp/Cntr=0.3,0.1

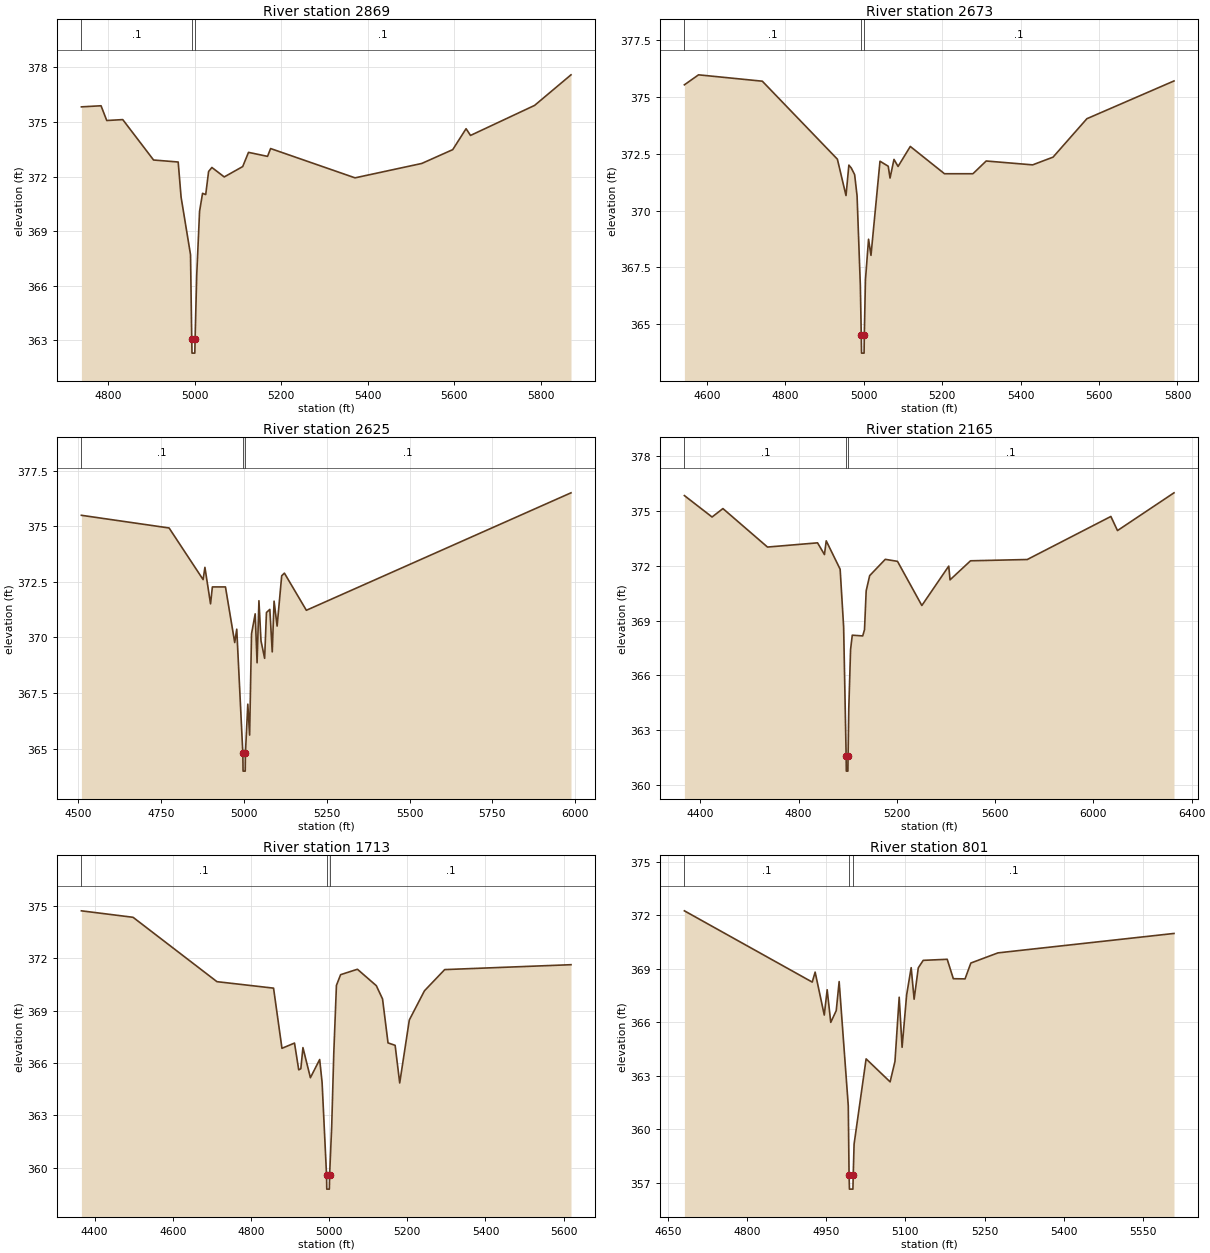
Type RM Length L Ch R = 1,2869,196,196,196
BEGIN DESCRIPTION:
Mapping XS c78a8f22
END DESCRIPTION:
XS GIS Cut Line= 4
      2072818.39     13452579.86      2072746.82     13452612.39
      2072492.91     13452833.74      2072330.81     13453531.19
#Sta/Elev= 30
  4738.4  375.83  4783.8  375.89  4797.0  375.08  4834.0  375.13  4905.2  372.91
  4962.1  372.80  4968.8  370.87  4990.6  367.71  4993.4  363.10  4994.0  362.30
  5000.5  362.30  5001.2  363.10  5004.9  366.56  5011.5  370.09  5018.4  371.08
  5025.7  371.01  5032.4  372.28  5040.0  372.50  5068.5  371.98  5111.2  372.55
  5124.6  373.33  5168.6  373.11  5175.7  373.54  5370.8  371.93  5525.0  372.72
  5596.6  373.48  5627.4  374.63  5637.7  374.26  5785.8  375.91  5869.9  377.59
#Mann=3,-1,0
  4738.4     0.1       0  4993.4    0.07       0  5001.2     0.1       0
Bank Sta=4993.4,5001.2
Exp/Cntr=0.3,0.1

Type RM Length L Ch R = 1,2673,48,48,48
BEGIN DESCRIPTION:
Mapping XS 145094da
END DESCRIPTION:
XS GIS Cut Line= 4
      2072773.22     13452363.20      2072494.96     13452594.05
      2072397.30     13452727.52      2072198.14     13453421.57
#Sta/Elev= 30
  4542.1  375.53  4578.2  375.97  4740.9  375.69  4932.4  372.26  4954.4  370.66
  4961.7  372.00  4967.9  371.87  4976.4  371.58  4982.6  370.65  4991.0  366.69
  4993.3  364.53  4994.0  363.73  5000.5  363.73  5001.1  364.53  5004.0  366.95
  5011.9  368.74  5018.1  368.03  5041.1  372.17  5062.1  371.95  5066.7  371.43
  5076.8  372.25  5087.2  371.94  5118.4  372.82  5205.6  371.62  5278.2  371.62
  5312.0  372.18  5430.5  372.01  5482.6  372.35  5568.9  374.04  5791.1  375.70
#Mann=3,-1,0
  4542.1     0.1       0  4993.3    0.07       0  5001.1     0.1       0
Bank Sta=4993.3,5001.1
Exp/Cntr=0.3,0.1

Type RM Length L Ch R = 1,2625,460,460,460
BEGIN DESCRIPTION:
Mapping XS c95a07d0
END DESCRIPTION:
XS GIS Cut Line= 5
      2072695.11     13452269.43      2072511.23     13452460.59
      2072453.72     13452539.80      2072374.51     13452701.47
      2071984.90     13453551.69
#Sta/Elev= 30
  4509.1  375.49  4773.9  374.92  4876.6  372.60  4882.1  373.15  4899.1  371.51
  4904.6  372.27  4944.1  372.27  4972.1  369.77  4978.2  370.37  4996.6  364.79
  4997.3  363.99  5003.8  363.99  5004.4  364.79  5011.6  367.00  5017.1  365.61
  5022.8  370.16  5033.9  371.06  5039.6  368.86  5045.2  371.65  5051.4  369.85
  5062.4  369.06  5067.9  371.12  5078.1  371.26  5085.4  369.35  5090.9  371.63
  5100.1  370.51  5113.9  372.77  5122.1  372.89  5188.4  371.22  5987.5  376.50
#Mann=3,-1,0
  4509.1     0.1       0  4996.6    0.07       0  5004.4     0.1       0
Bank Sta=4996.6,5004.4
Exp/Cntr=0.3,0.1

Type RM Length L Ch R = 1,2165,452,452,452
BEGIN DESCRIPTION:
Mapping XS 3fadbcca
END DESCRIPTION:
XS GIS Cut Line= 4
      2072741.97     13452099.27      2072274.16     13452273.85
      2071899.16     13452672.29      2071611.77     13453574.12
#Sta/Elev= 30
  4335.1  375.82  4447.8  374.65  4492.0  375.11  4673.4  373.01  4877.2  373.24
  4905.2  372.60  4912.5  373.35  4969.1  371.80  4983.3  368.66  4993.6  361.58
  4994.2  360.78  5000.7  360.78  5001.4  361.58  5004.3  364.19  5011.6  367.42
  5018.5  368.20  5061.0  368.16  5068.3  368.50  5075.1  370.62  5089.3  371.45
  5152.8  372.34  5202.6  372.23  5301.7  369.82  5411.2  371.97  5416.5  371.22
  5499.9  372.26  5730.8  372.33  6071.2  374.68  6098.1  373.91  6328.1  375.97
#Mann=3,-1,0
  4335.1     0.1       0  4993.6    0.07       0  5001.4     0.1       0
Bank Sta=4993.6,5001.4
Exp/Cntr=0.3,0.1

Type RM Length L Ch R = 1,1713,912,912,912
BEGIN DESCRIPTION:
Mapping XS 6539ab4e
END DESCRIPTION:
XS GIS Cut Line= 4
      2072546.16     13452026.75      2072168.55     13452074.49
      2071682.44     13452263.29      2071495.99     13452560.32
#Sta/Elev= 30
  4366.1  374.70  4498.3  374.33  4713.0  370.65  4857.8  370.28  4879.3  366.84
  4911.4  367.14  4922.2  365.61  4927.6  365.67  4933.0  366.88  4952.1  365.16
  4975.8  366.20  4982.0  364.89  4993.4  359.59  4994.0  358.79  5000.6  358.79
  5001.2  359.59  5006.6  362.38  5011.9  366.55  5018.7  370.44  5029.4  371.05
  5072.4  371.36  5120.8  370.42  5136.7  369.66  5150.7  367.15  5168.9  367.01
  5180.6  364.86  5205.2  368.46  5244.0  370.13  5295.7  371.34  5618.9  371.62
#Mann=3,-1,0
  4366.1     0.1       0  4993.4    0.07       0  5001.2     0.1       0
Bank Sta=4993.4,5001.2
Exp/Cntr=0.3,0.1

Type RM Length L Ch R = 1,801,267,267,267
BEGIN DESCRIPTION:
Mapping XS cc830a4c
END DESCRIPTION:
XS GIS Cut Line= 4
      2072229.89     13451591.23      2072047.60     13451554.34
      2071680.85     13451727.95      2071585.81     13452050.38
#Sta/Elev= 30
  4681.1  372.26  4923.4  368.26  4928.9  368.82  4946.2  366.41  4951.7  367.83
  4958.5  366.00  4968.9  366.66  4974.4  368.29  4991.7  361.32  4993.2  357.44
  4993.9  356.64  5000.5  356.64  5001.1  357.44  5002.7  359.16  5025.5  363.95
  5071.0  362.66  5080.2  363.81  5088.2  367.41  5093.7  364.60  5102.3  367.54
  5110.9  369.07  5116.5  367.30  5124.4  369.06  5133.7  369.48  5179.2  369.54
  5190.8  368.45  5213.0  368.44  5224.0  369.33  5275.4  369.90  5609.0  370.99
#Mann=3,-1,0
  4681.1     0.1       0  4993.2    0.07       0  5001.1     0.1       0
Bank Sta=4993.2,5001.1
Exp/Cntr=0.3,0.1

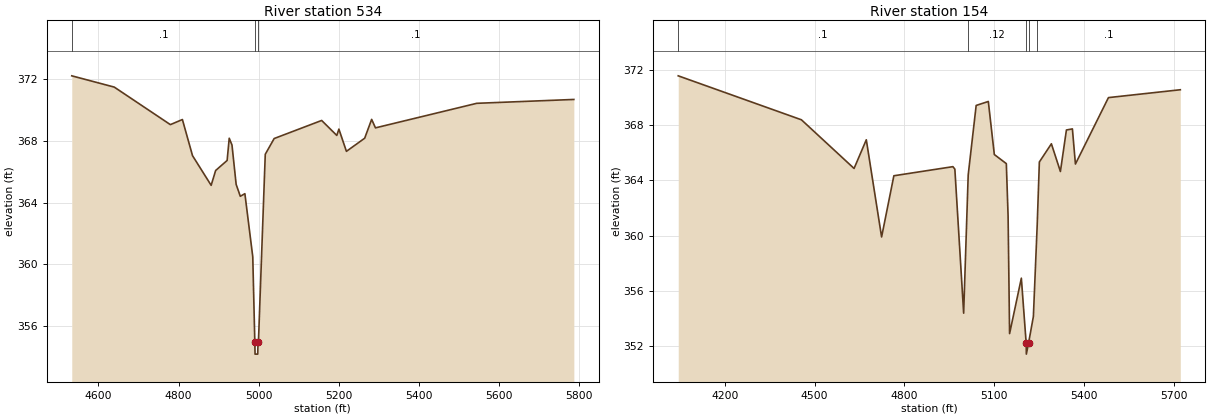
Type RM Length L Ch R = 1,534,380,380,380
BEGIN DESCRIPTION:
Mapping XS cc47c3ad
END DESCRIPTION:
XS GIS Cut Line= 4
      2072321.05     13451354.69      2072019.39     13451365.54
      2071713.40     13451452.34      2071520.62     13452055.89
#Sta/Elev= 30
  4533.3  372.21  4639.4  371.48  4779.5  369.05  4809.5  369.38  4834.8  367.04
  4881.3  365.12  4892.5  366.08  4921.2  366.73  4926.4  368.17  4933.3  367.73
  4943.7  365.18  4954.1  364.41  4965.5  364.58  4985.2  360.49  4990.3  354.99
  4990.9  354.19  4997.6  354.19  4998.3  354.99  4999.4  355.01  5016.4  367.13
  5038.6  368.15  5157.2  369.32  5195.0  368.35  5200.2  368.76  5219.0  367.32
  5264.6  368.17  5282.0  369.39  5291.5  368.84  5544.4  370.43  5786.8  370.68
#Mann=3,-1,0
  4533.3     0.1       0  4990.3    0.07       0  4998.3     0.1       0
Bank Sta=4990.3,4998.3
Exp/Cntr=0.3,0.1

Type RM Length L Ch R = 1,154,0,0,0
BEGIN DESCRIPTION:
UNT 24 in Lagunillas Cr Wtrshd 1.0
END DESCRIPTION:
XS GIS Cut Line= 4
      2072489.35     13451032.47      2071671.88     13451208.90
      2071567.71     13451353.00      2071510.20     13452014.20
#Sta/Elev= 30
  4044.3  371.59  4456.0  368.40  4631.9  364.87  4672.8  366.95  4723.9  359.90
  4764.9  364.34  4962.2  365.00  4968.7  364.82  4998.1  354.37  5013.3  364.40
  5039.9  369.44  5080.5  369.73  5100.6  365.88  5140.7  365.22  5146.6  361.41
  5151.6  352.89  5190.9  356.91  5207.0  352.20  5207.6  351.40  5215.0  352.20
  5231.1  354.13  5243.9  360.78  5251.1  365.34  5291.3  366.66  5321.4  364.65
  5341.5  367.66  5361.5  367.74  5371.6  365.19  5482.0  370.01  5722.1  370.58
#Mann=5,-1,0
  4044.3     0.1       0  5013.3    0.12       0  5207.0    0.07       0
  5215.0    0.12       0  5243.9     0.1       0
Bank Sta=5207,5215
Exp/Cntr=0.3,0.1

Chan Stop Cuts=-1