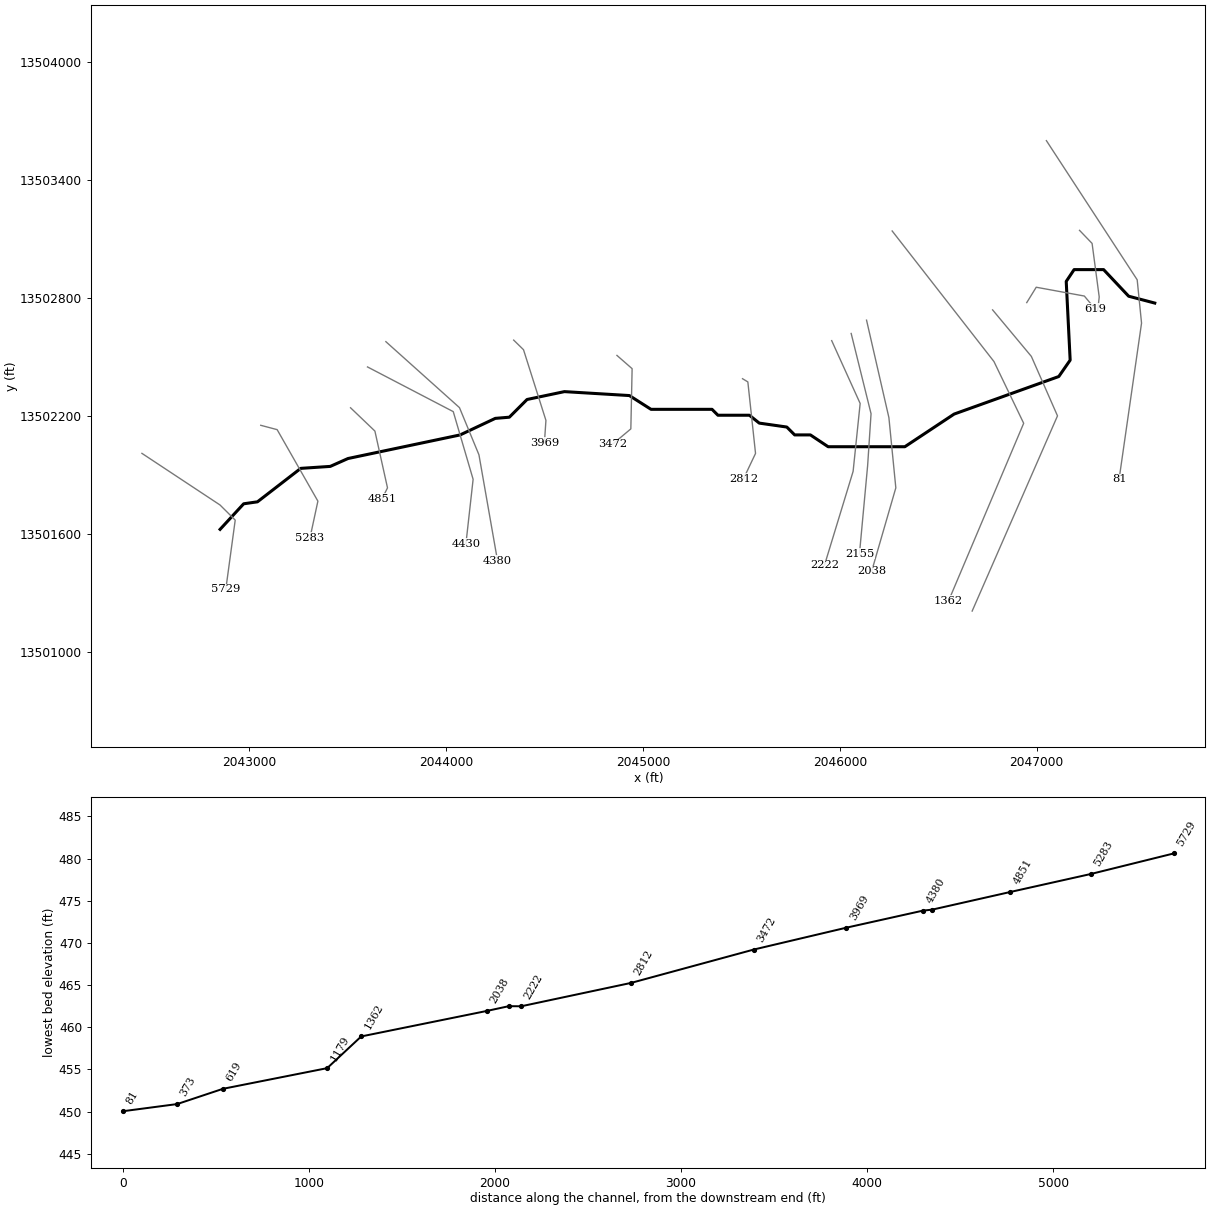
--- UNT 29 in Lagunillas Cr Wtrshd.prj (project) ---

Proj Title=UNT 29 in Lagunillas Cr Wtrshd Base Level Engineering
Current Plan=p01
Default Exp/Contr=0.3,0.1
English Units
Geom File=g01
Flow File=f01
Plan File=p01
BEGIN DESCRIPTION:
UNT 29 in Lagunillas Cr Wtrshd
END DESCRIPTION:

--- UNT 29 in Lagunillas Cr Wtrshd.p01 (plan) ---

Plan Title=Multiple Run
Short Identifier=Multiple
Geom File=g01
Flow File=f01
Subcritical Flow
K Sum by GR= 0
Std Step Tol= 0.01
Critical Tol= 0.01
Num of Std Step Trials= 20
Max Error Tol= 0.3
Flow Tol Ratio= 0.001
Split Flow NTrial= 30
Split Flow Tol= 0.02
Split Flow Ratio= 0.02
Log Output Level= 0
Friction Slope Method= 1
Unsteady Friction Slope Method= 2
Unsteady Bridges Friction Slope Method= 1
Parabolic Critical Depth
Global Vel Dist=  1 , 1 , 1
Global Log Level= 0
CheckData=True
Encroach Param= -1, 0, 0, 0
BEGIN DESCRIPTION:
Multiple Run
END DESCRIPTION:

--- UNT 29 in Lagunillas Cr Wtrshd.f01 (steady flow) ---

Flow Title=Multiple
Number of Profiles=7
Profile Names=10-year,25-year,50-year,1pct_min,100-year,1pct_plu,500-year
River Rch & RM= UNT 29 in Laguni,Reach-1,5729
     180     245     297     180     360     718     535
River Rch & RM= UNT 29 in Laguni,Reach-1,4380
     244     337     413     253     504    1006     764
Boundary for River Rch & Prof#=UNT 29 in Laguni,Reach-1,1
Up Type=0
Dn Type=3
Dn Slope=0.005
Boundary for River Rch & Prof#=UNT 29 in Laguni,Reach-1,2
Up Type=0
Dn Type=3
Dn Slope=0.005
Boundary for River Rch & Prof#=UNT 29 in Laguni,Reach-1,3
Up Type=0
Dn Type=3
Dn Slope=0.005
Boundary for River Rch & Prof#=UNT 29 in Laguni,Reach-1,4
Up Type=0
Dn Type=3
Dn Slope=0.005
Boundary for River Rch & Prof#=UNT 29 in Laguni,Reach-1,5
Up Type=0
Dn Type=3
Dn Slope=0.005
Boundary for River Rch & Prof#=UNT 29 in Laguni,Reach-1,6
Up Type=0
Dn Type=3
Dn Slope=0.005
Boundary for River Rch & Prof#=UNT 29 in Laguni,Reach-1,7
Up Type=0
Dn Type=3
Dn Slope=0.005

--- UNT 29 in Lagunillas Cr Wtrshd.g01 (geometry) ---

Geom Title=Existing Conditions

River Reach=UNT 29 in Laguni,Reach-1
Reach XY= 30
      2042850.80     13501624.54      2042970.80     13501754.54
      2043040.80     13501764.54      2043260.80     13501934.54
      2043410.80     13501944.54      2043500.80     13501984.54
      2044070.80     13502104.54      2044249.50     13502188.61
      2044320.80     13502194.54      2044410.80     13502284.54
      2044600.80     13502324.54      2044930.80     13502304.54
      2045040.80     13502234.54      2045350.80     13502234.54
      2045380.80     13502204.54      2045540.80     13502204.54
      2045590.80     13502164.54      2045730.80     13502144.54
      2045770.80     13502104.54      2045850.80     13502104.54
      2045940.80     13502044.54      2046330.80     13502044.54
      2046581.00     13502210.37      2047113.12     13502401.34
      2047170.80     13502484.54      2047150.80     13502884.54
      2047190.80     13502944.54      2047340.80     13502944.54
      2047468.15     13502809.33      2047600.80     13502774.54

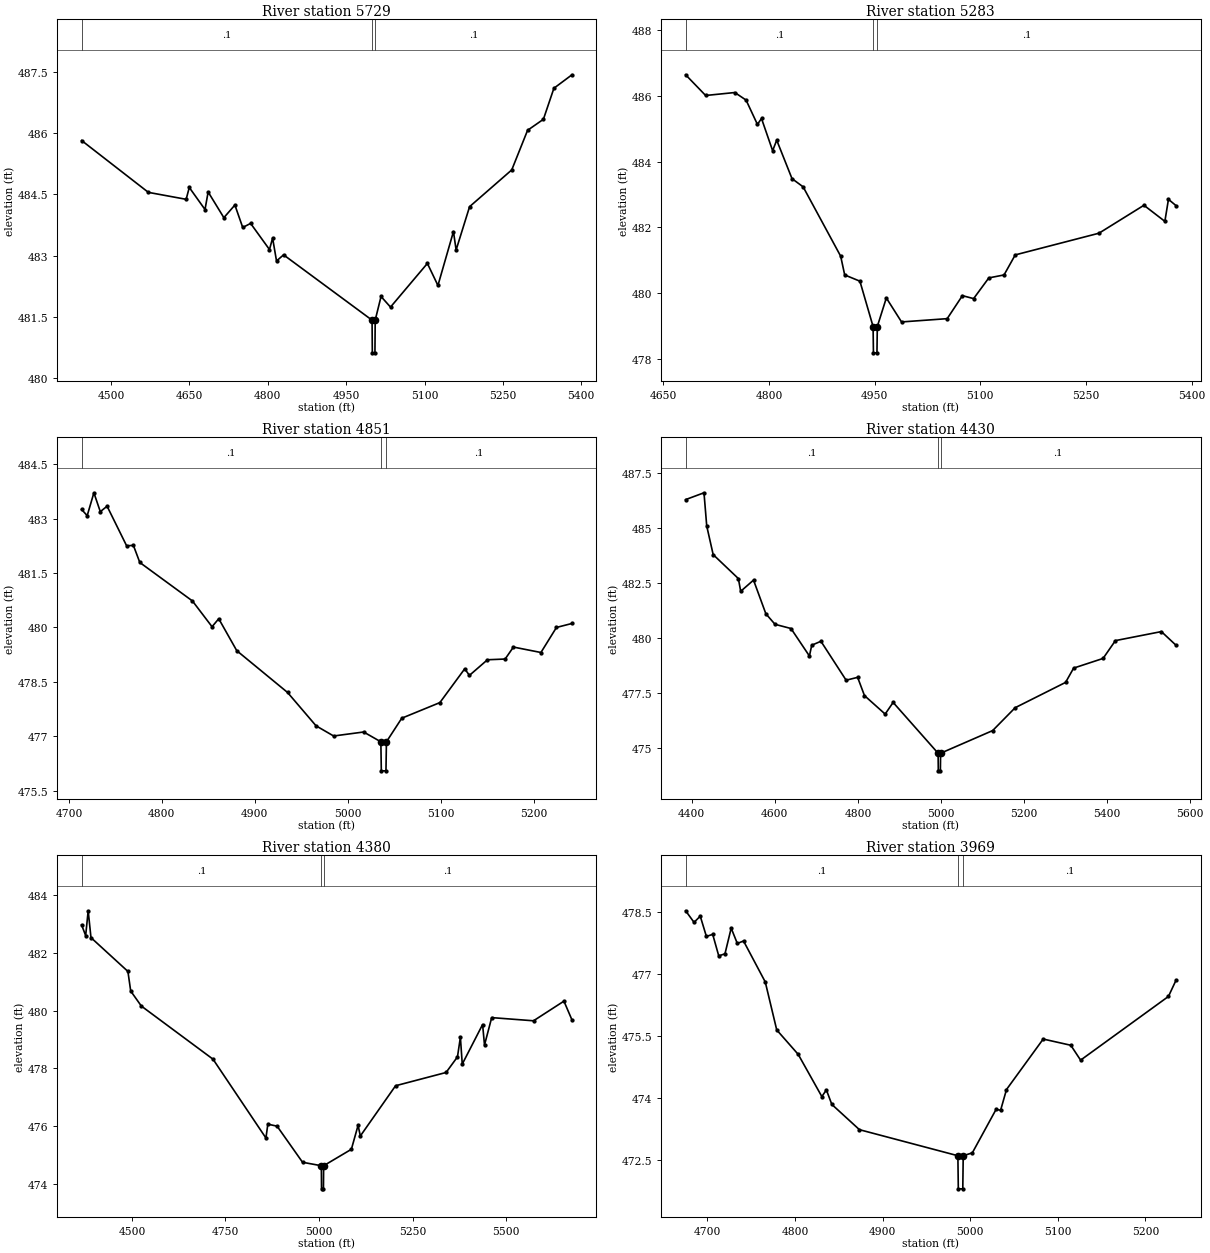
Type RM Length L Ch R = 1,5729,446,446,446
BEGIN DESCRIPTION:
UNT 29 in Lagunillas Cr Wtrshd 9.0
END DESCRIPTION:
XS GIS Cut Line= 4
      2042453.72     13502010.74      2042850.50     13501748.47
      2042927.76     13501671.65      2042880.02     13501320.76
#Sta/Elev= 30
  4443.6  485.82  4571.4  484.55  4643.7  484.38  4649.7  484.67  4679.8  484.13
  4685.8  484.56  4715.9  483.93  4737.0  484.24  4752.0  483.69  4767.1  483.79
  4803.2  483.15  4809.2  483.43  4816.7  482.87  4830.2  483.02  4999.6  481.42
  5000.1  480.62  5005.1  480.62  5005.6  481.42  5016.8  482.00  5034.9  481.74
  5105.5  482.81  5125.7  482.27  5155.4  483.59  5160.5  483.14  5186.3  484.20
  5267.0  485.10  5297.3  486.07  5327.6  486.34  5347.7  487.10  5382.3  487.43
#Mann=3,-1,0
  4443.6     0.1       0  4999.6    0.07       0  5005.6     0.1       0
Bank Sta=4999.6,5005.6
Exp/Cntr=0.3,0.1

Type RM Length L Ch R = 1,5283,432,432,432
BEGIN DESCRIPTION:
Mapping XS e42964fa
END DESCRIPTION:
XS GIS Cut Line= 4
      2043057.53     13502153.42      2043140.86     13502131.29
      2043347.89     13501768.00      2043307.54     13501580.55
#Sta/Elev= 30
  4681.6  486.64  4710.0  486.01  4751.4  486.10  4767.4  485.87  4783.5  485.13
  4789.3  485.31  4805.1  484.33  4810.9  484.65  4832.6  483.48  4848.4  483.23
  4901.7  481.12  4907.4  480.55  4929.0  480.36  4947.7  478.98  4948.2  478.18
  4953.2  478.18  4953.7  478.98  4966.5  479.85  4988.1  479.12  5052.9  479.22
  5074.5  479.92  5090.4  479.83  5112.0  480.46  5133.6  480.55  5149.5  481.16
  5268.4  481.82  5332.2  482.67  5361.9  482.18  5367.0  482.85  5377.7  482.66
#Mann=3,-1,0
  4681.6     0.1       0  4947.7    0.07       0  4953.7     0.1       0
Bank Sta=4947.7,4953.7
Exp/Cntr=0.3,0.1

Type RM Length L Ch R = 1,4851,421,421,421
BEGIN DESCRIPTION:
Mapping XS 21fd52cf
END DESCRIPTION:
XS GIS Cut Line= 4
      2043513.89     13502242.42      2043637.61     13502124.12
      2043701.63     13501835.50      2043674.49     13501781.22
#Sta/Elev= 30
  4713.7  483.25  4719.7  483.08  4726.9  483.71  4733.8  483.19  4741.1  483.34
  4762.1  482.25  4769.4  482.26  4776.3  481.79  4832.9  480.73  4854.0  480.02
  4861.2  480.24  4880.6  479.36  4935.2  478.21  4965.9  477.29  4984.8  477.01
  5017.1  477.12  5035.6  476.85  5036.1  476.05  5041.1  476.05  5041.6  476.85
  5058.1  477.50  5099.1  477.93  5125.8  478.86  5130.9  478.68  5150.3  479.11
  5169.3  479.13  5178.2  479.46  5207.8  479.31  5224.5  480.00  5241.2  480.11
#Mann=3,-1,0
  4713.7     0.1       0  5035.6    0.07       0  5041.6     0.1       0
Bank Sta=5035.6,5041.6
Exp/Cntr=0.3,0.1

Type RM Length L Ch R = 1,4430,50,50,50
BEGIN DESCRIPTION:
Mapping XS 3247d1a1
END DESCRIPTION:
XS GIS Cut Line= 4
      2043599.98     13502450.01      2044035.83     13502222.87
      2044136.74     13501878.90      2044100.00     13501549.99
#Sta/Elev= 30
  4385.2  486.28  4429.4  486.59  4436.0  485.08  4451.5  483.78  4512.2  482.69
  4517.8  482.11  4548.7  482.62  4578.4  481.09  4600.5  480.61  4638.9  480.42
  4683.3  479.17  4688.9  479.66  4711.0  479.84  4771.7  478.07  4799.4  478.20
  4815.9  477.37  4865.7  476.53  4884.9  477.06  4993.2  474.75  4993.7  473.95
  4998.7  473.95  4999.2  474.75  5124.6  475.78  5178.8  476.82  5300.2  477.97
  5319.6  478.62  5390.5  479.06  5420.2  479.87  5530.9  480.28  5566.1  479.66
#Mann=3,-1,0
  4385.2     0.1       0  4993.2    0.07       0  4999.2     0.1       0
Bank Sta=4993.2,4999.2
Exp/Cntr=0.3,0.1

Type RM Length L Ch R = 1,4380,411,411,411
BEGIN DESCRIPTION:
Mapping XS 3c5978b9
END DESCRIPTION:
XS GIS Cut Line= 4
      2043693.35     13502578.42      2044067.39     13502243.19
      2044166.34     13502003.60      2044261.05     13501463.84
#Sta/Elev= 30
  4365.8  482.97  4376.6  482.60  4383.3  483.46  4390.8  482.53  4489.4  481.36
  4496.9  480.68  4525.3  480.16  4716.7  478.32  4858.0  475.59  4863.1  476.07
  4887.8  476.00  4955.8  474.75  5006.0  474.63  5006.5  473.83  5011.6  473.83
  5012.1  474.63  5086.2  475.20  5104.1  476.03  5110.1  475.66  5204.2  477.40
  5339.1  477.86  5369.5  478.40  5377.3  479.08  5382.3  478.15  5436.6  479.52
  5441.7  478.81  5460.9  479.76  5572.6  479.65  5653.8  480.33  5675.3  479.68
#Mann=3,-1,0
  4365.8     0.1       0  5006.0    0.07       0  5012.1     0.1       0
Bank Sta=5006,5012.1
Exp/Cntr=0.3,0.1

Type RM Length L Ch R = 1,3969,497,497,497
BEGIN DESCRIPTION:
Mapping XS 4b20bb60
END DESCRIPTION:
XS GIS Cut Line= 4
      2044342.87     13502586.39      2044392.82     13502537.54
      2044506.75     13502178.38      2044499.15     13502065.50
#Sta/Elev= 30
  4675.2  478.53  4684.8  478.25  4691.9  478.40  4698.9  477.91  4706.1  477.96
  4713.0  477.44  4720.1  477.49  4727.2  478.11  4734.2  477.74  4741.3  477.80
  4766.1  476.81  4779.2  475.65  4803.7  475.06  4830.7  474.04  4835.9  474.20
  4842.1  473.85  4873.6  473.24  4986.0  472.61  4986.5  471.81  4991.6  471.81
  4992.1  472.61  5002.5  472.68  5029.6  473.73  5034.8  473.71  5041.5  474.21
  5083.4  475.43  5114.9  475.28  5126.1  474.92  5226.4  476.46  5235.0  476.85
#Mann=3,-1,0
  4675.2     0.1       0  4986.0    0.07       0  4992.1     0.1       0
Bank Sta=4986,4992.1
Exp/Cntr=0.3,0.1

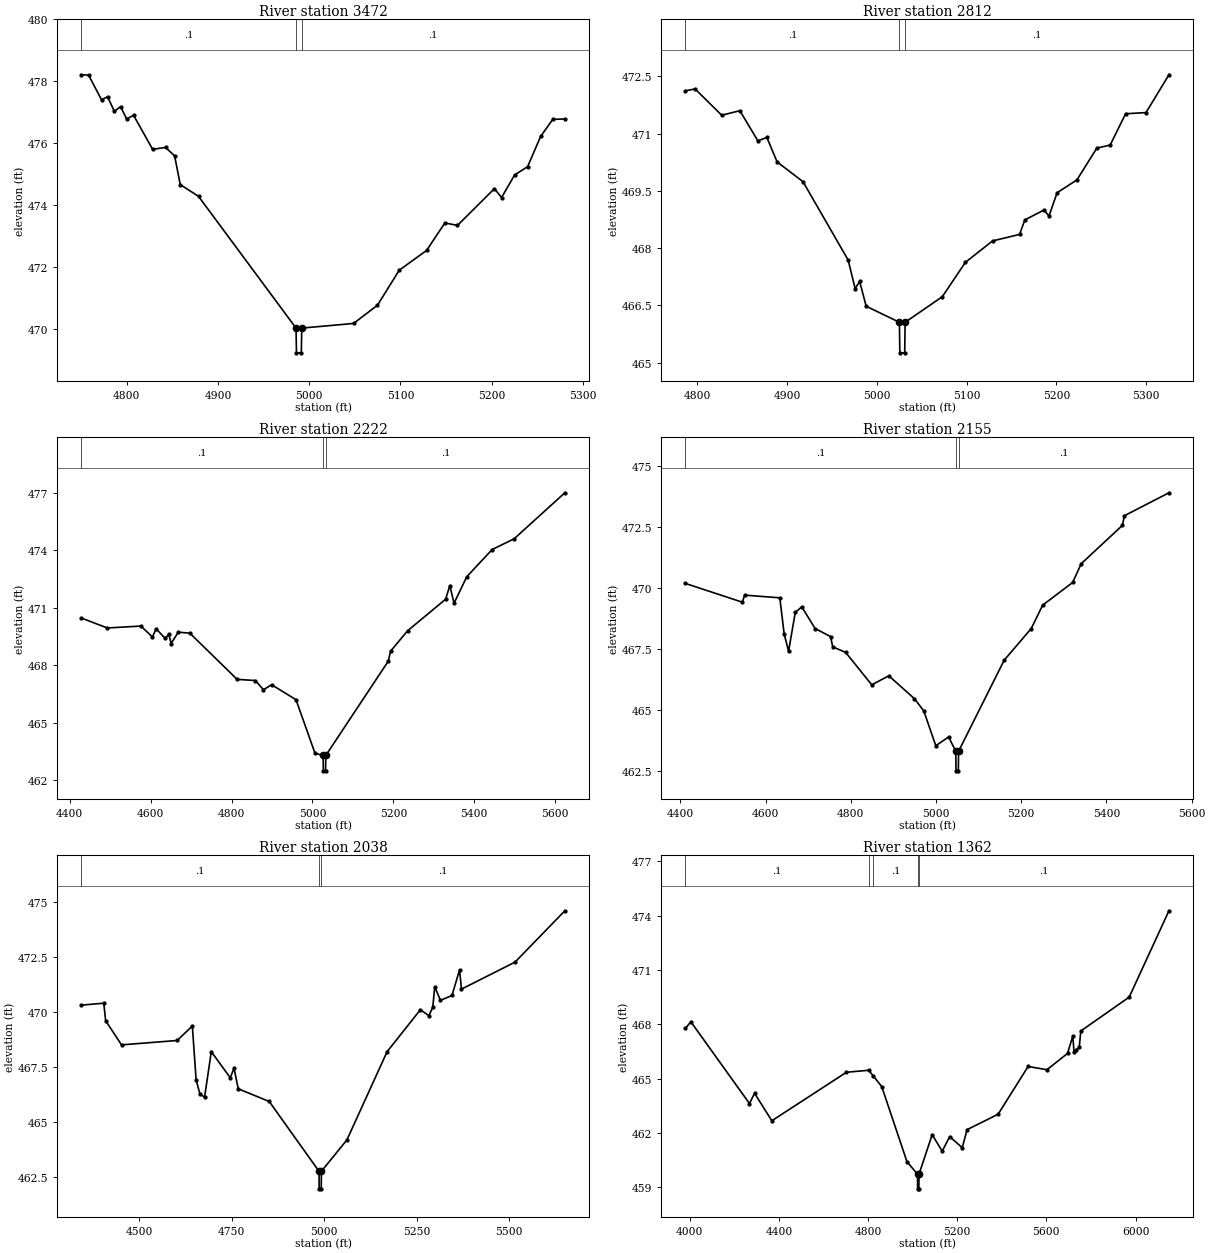
Type RM Length L Ch R = 1,3472,660,660,660
BEGIN DESCRIPTION:
Mapping XS 839b4786
END DESCRIPTION:
XS GIS Cut Line= 4
      2044867.70     13502508.47      2044944.76     13502441.18
      2044938.25     13502135.19      2044844.90     13502057.04
#Sta/Elev= 30
  4750.2  478.21  4758.2  478.20  4772.4  477.40  4779.0  477.50  4786.4  477.03
  4793.3  477.18  4799.9  476.78  4807.5  476.90  4828.4  475.80  4842.6  475.86
  4852.5  475.59  4858.7  474.66  4878.7  474.28  4985.6  470.02  4986.1  469.22
  4991.4  469.22  4991.9  470.02  5048.7  470.17  5074.9  470.76  5098.7  471.89
  5128.7  472.53  5148.8  473.42  5162.6  473.34  5203.1  474.53  5210.9  474.24
  5225.2  474.97  5239.5  475.24  5253.8  476.22  5267.1  476.77  5280.3  476.78
#Mann=3,-1,0
  4750.2     0.1       0  4985.6    0.07       0  4991.9     0.1       0
Bank Sta=4985.6,4991.9
Exp/Cntr=0.3,0.1

Type RM Length L Ch R = 1,2812,590,590,590
BEGIN DESCRIPTION:
Mapping XS a463db6c
END DESCRIPTION:
XS GIS Cut Line= 4
      2045505.78     13502390.16      2045532.86     13502373.91
      2045571.93     13502010.41      2045511.16     13501882.37
#Sta/Elev= 30
  4786.5  472.12  4797.3  472.17  4827.0  471.48  4847.2  471.60  4867.3  470.81
  4877.3  470.90  4888.7  470.26  4917.6  469.74  4967.9  467.69  4975.7  466.94
  4980.7  467.13  4988.0  466.48  5025.0  466.06  5025.5  465.26  5030.9  465.26
  5031.4  466.06  5072.8  466.73  5098.6  467.63  5128.8  468.19  5158.9  468.36
  5164.8  468.74  5186.2  469.00  5191.7  468.84  5200.7  469.45  5222.9  469.79
  5245.0  470.62  5259.9  470.70  5277.1  471.52  5299.8  471.55  5325.4  472.54
#Mann=3,-1,0
  4786.5     0.1       0  5025.0    0.07       0  5031.4     0.1       0
Bank Sta=5025,5031.4
Exp/Cntr=0.3,0.1

Type RM Length L Ch R = 1,2222,67,67,67
BEGIN DESCRIPTION:
Mapping XS 7976e7fa
END DESCRIPTION:
XS GIS Cut Line= 4
      2045958.97     13502583.63      2046103.61     13502264.31
      2046067.80     13501919.26      2045922.50     13501442.98
#Sta/Elev= 30
  4428.5  470.46  4492.9  469.94  4575.8  470.04  4604.4  469.47  4613.6  469.90
  4635.6  469.40  4645.1  469.60  4650.6  469.13  4668.2  469.72  4696.8  469.67
  4813.8  467.26  4858.8  467.20  4878.9  466.72  4899.0  466.98  4959.3  466.20
  5006.2  463.41  5026.4  463.29  5026.9  462.49  5032.4  462.49  5032.9  463.29
  5187.4  468.21  5193.1  468.73  5235.0  469.79  5329.2  471.44  5339.5  472.15
  5350.0  471.23  5381.3  472.61  5444.1  474.03  5498.5  474.59  5623.9  476.99
#Mann=3,-1,0
  4428.5     0.1       0  5026.4    0.07       0  5032.9     0.1       0
Bank Sta=5026.4,5032.9
Exp/Cntr=0.3,0.1

Type RM Length L Ch R = 1,2155,117,117,117
BEGIN DESCRIPTION:
Mapping XS 88767e7b
END DESCRIPTION:
XS GIS Cut Line= 4
      2046057.94     13502620.05      2046158.95     13502212.23
      2046141.59     13501948.56      2046100.00     13501499.97
#Sta/Elev= 30
  4411.8  470.19  4545.5  469.42  4550.9  469.71  4633.4  469.60  4643.7  468.11
  4654.0  467.41  4669.7  469.00  4684.9  469.23  4716.2  468.34  4752.5  468.01
  4757.6  467.59  4787.9  467.36  4849.2  466.03  4889.3  466.40  4949.4  465.46
  4971.3  464.96  4999.5  463.53  5029.6  463.89  5046.4  463.30  5046.9  462.50
  5052.4  462.50  5052.9  463.30  5160.0  467.04  5223.5  468.34  5250.4  469.30
  5320.7  470.23  5340.8  471.00  5437.3  472.57  5442.3  472.97  5546.7  473.91
#Mann=3,-1,0
  4411.8     0.1       0  5046.4    0.07       0  5052.9     0.1       0
Bank Sta=5046.4,5052.9
Exp/Cntr=0.3,0.1

Type RM Length L Ch R = 1,2038,676,676,676
BEGIN DESCRIPTION:
Mapping XS 9c4e772d
END DESCRIPTION:
XS GIS Cut Line= 4
      2046136.06     13502687.76      2046249.70     13502192.27
      2046284.86     13501835.50      2046162.10     13501411.78
#Sta/Elev= 30
  4343.2  470.31  4404.0  470.40  4409.1  469.60  4452.0  468.50  4602.5  468.70
  4643.6  469.36  4653.8  466.91  4664.1  466.26  4676.7  466.12  4694.9  468.19
  4746.2  467.00  4756.4  467.44  4767.6  466.50  4851.6  465.92  4986.2  462.74
  4986.7  461.94  4992.2  461.94  4992.7  462.74  5061.7  464.17  5170.4  468.19
  5260.4  470.10  5283.4  469.83  5293.9  470.21  5299.2  471.15  5314.7  470.53
  5345.9  470.75  5366.4  471.92  5371.6  471.04  5516.4  472.27  5651.2  474.61
#Mann=3,-1,0
  4343.2     0.1       0  4986.2    0.07       0  4992.7     0.1       0
Bank Sta=4986.2,4992.7
Exp/Cntr=0.3,0.1

Type RM Length L Ch R = 1,1362,183,183,183
BEGIN DESCRIPTION:
Mapping XS b9006591
END DESCRIPTION:
XS GIS Cut Line= 4
      2046266.29     13503140.90      2046783.56     13502477.42
      2046934.60     13502163.62      2046552.71     13501260.71
#Sta/Elev= 30
  3980.2  467.77  4004.6  468.14  4267.9  463.62  4290.5  464.19  4368.1  462.67
  4703.0  465.35  4802.7  465.46  4823.7  465.14  4861.2  464.56  4974.3  460.42
  5021.8  459.71  5022.3  458.91  5027.9  458.91  5028.4  459.71  5087.5  461.90
  5132.7  460.99  5166.2  461.80  5222.5  461.18  5244.3  462.18  5383.5  463.03
  5518.2  465.67  5602.6  465.49  5694.9  466.39  5718.6  467.35  5724.0  466.49
  5732.8  466.56  5747.7  466.74  5754.6  467.63  5971.7  469.50  6150.1  474.27
#Mann=5,-1,0
  3980.2     0.1       0  4802.7    0.16       0  4823.7     0.1       0
  5021.8    0.07       0  5028.4     0.1       0
Bank Sta=5021.8,5028.4
Exp/Cntr=0.3,0.1

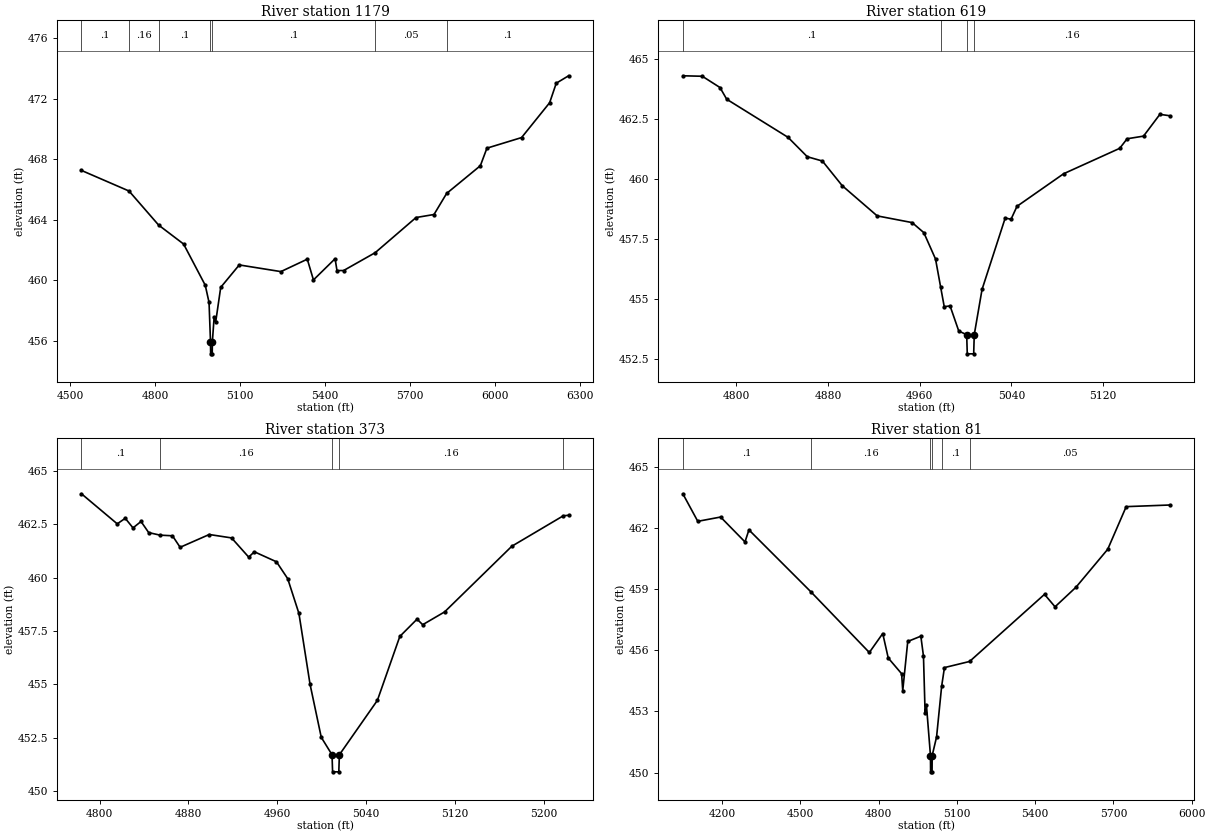
Type RM Length L Ch R = 1,1179,560,560,560
BEGIN DESCRIPTION:
Mapping XS 193a4949
END DESCRIPTION:
XS GIS Cut Line= 4
      2046776.66     13502739.90      2046973.66     13502503.46
      2047106.47     13502201.38      2046672.83     13501209.36
#Sta/Elev= 30
  4539.1  467.26  4707.1  465.90  4811.7  463.65  4899.8  462.40  4976.3  459.68
  4989.7  458.54  4994.8  455.95  4995.3  455.15  5000.9  455.15  5001.4  455.95
  5007.6  457.56  5013.1  457.25  5030.9  459.54  5096.4  461.02  5243.4  460.58
  5336.6  461.40  5358.4  460.03  5434.8  461.43  5441.5  460.65  5464.9  460.65
  5576.5  461.83  5720.7  464.15  5784.1  464.35  5828.7  465.74  5947.8  467.57
  5971.0  468.73  6093.4  469.43  6192.5  471.73  6215.9  473.02  6259.5  473.51
#Mann=7,-1,0
  4539.1     0.1       0  4707.1    0.16       0  4811.7     0.1       0
  4994.8    0.07       0  5001.4     0.1       0  5576.5    0.05       0
  5828.7     0.1       0
Bank Sta=4994.8,5001.4
Exp/Cntr=0.3,0.1

Type RM Length L Ch R = 1,619,246,246,246
BEGIN DESCRIPTION:
Mapping XS 1466e212
END DESCRIPTION:
XS GIS Cut Line= 4
      2046950.23     13502776.92      2046998.40     13502855.03
      2047242.93     13502810.25      2047297.13     13502745.11
#Sta/Elev= 30
  4753.3  464.31  4770.3  464.29  4785.7  463.82  4791.6  463.33  4845.1  461.74
  4861.9  460.93  4875.1  460.75  4892.4  459.72  4922.9  458.46  4953.4  458.18
  4963.6  457.76  4973.8  456.66  4978.3  455.48  4981.4  454.67  4986.5  454.70
  4994.1  453.65  5001.0  453.50  5001.5  452.70  5007.1  452.70  5007.6  453.50
  5014.4  455.39  5034.6  458.37  5039.7  458.32  5044.9  458.86  5085.6  460.22
  5134.5  461.28  5141.0  461.68  5155.3  461.79  5169.6  462.70  5178.4  462.64
#Mann=4,-1,0
  4753.3     0.1       0  4978.3    0.16       0  5001.0    0.07       0
  5007.6    0.16       0
Bank Sta=5001,5007.6
Exp/Cntr=0.3,0.1

Type RM Length L Ch R = 1,373,292,292,292
BEGIN DESCRIPTION:
Mapping XS 107c5ee9
END DESCRIPTION:
XS GIS Cut Line= 4
      2047218.47     13503144.07      2047282.26     13503077.68
      2047318.45     13502805.56      2047310.64     13502734.18
#Sta/Elev= 30
  4783.7  463.93  4815.9  462.52  4823.1  462.78  4830.1  462.33  4837.3  462.63
  4844.2  462.11  4854.4  461.99  4865.6  461.96  4872.5  461.42  4898.7  462.02
  4918.8  461.86  4934.2  460.96  4939.3  461.21  4959.2  460.74  4969.3  459.95
  4979.4  458.32  4989.4  455.00  4999.5  452.51  5009.2  451.69  5009.7  450.89
  5015.3  450.89  5015.8  451.69  5050.0  454.24  5070.2  457.24  5085.7  458.05
  5090.8  457.79  5110.5  458.39  5171.0  461.47  5217.4  462.90  5222.1  462.92
#Mann=5,-1,0
  4783.7     0.1       0  4854.4    0.16       0  5009.2    0.07       0
  5015.8    0.16       0  5217.4     0.1       0
Bank Sta=5009.2,5015.8
Exp/Cntr=0.3,0.1

Type RM Length L Ch R = 1,81,0,0,0
BEGIN DESCRIPTION:
UNT 29 in Lagunillas Cr Wtrshd 1.0
END DESCRIPTION:
XS GIS Cut Line= 4
      2047050.02     13503599.97      2047511.42     13502892.79
      2047533.56     13502672.73      2047419.34     13501878.76
#Sta/Elev= 30
  4049.2  463.67  4106.5  462.32  4194.0  462.53  4287.5  461.31  4302.6  461.90
  4539.7  458.87  4764.2  455.89  4815.6  456.82  4836.7  455.62  4888.0  454.85
  4892.3  454.02  4911.5  456.43  4961.7  456.69  4971.8  455.71  4978.0  452.94
  4983.1  453.32  4998.6  450.84  4999.1  450.04  5004.7  450.04  5005.2  450.84
  5022.0  451.75  5041.5  454.24  5052.2  455.15  5148.6  455.45  5435.8  458.74
  5476.2  458.13  5556.5  459.09  5678.2  460.95  5749.0  463.04  5916.9  463.12
#Mann=6,-1,0
  4049.2     0.1       0  4539.7    0.16       0  4998.6    0.07       0
  5005.2    0.16       0  5041.5     0.1       0  5148.6    0.05       0
Bank Sta=4998.6,5005.2
Exp/Cntr=0.3,0.1

Chan Stop Cuts=-1