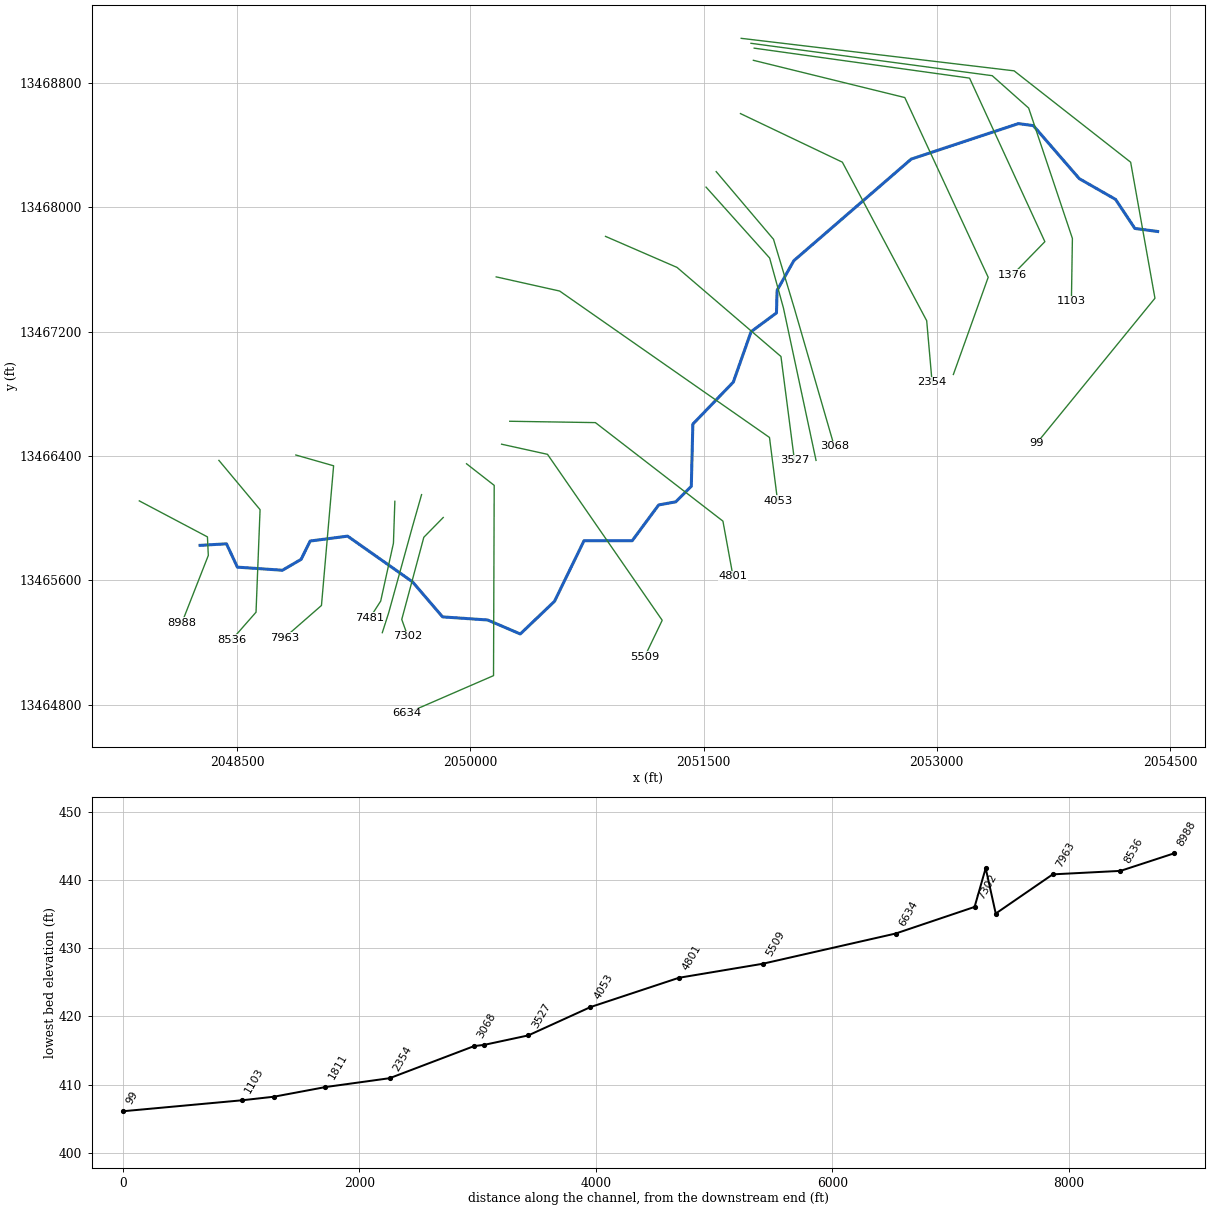
--- UNT 31 in Lagunillas Cr Wtrshd.prj (project) ---

Proj Title=UNT 31 in Lagunillas Cr Wtrshd Base Level Engineering
Current Plan=p01
Default Exp/Contr=0.3,0.1
English Units
Geom File=g01
Flow File=f01
Plan File=p01
Y Axis Title=Elevation
X Axis Title(PF)=Main Channel Distance
X Axis Title(XS)=Station
BEGIN DESCRIPTION:
UNT 31 in Lagunillas Cr Wtrshd
END DESCRIPTION:
DSS Export Rating Curves= 0
DSS Export Rating Curve Sorted= 0
DSS Export Volume Flow Curves= 0
DXF OffsetX= 0
DXF OffsetY= 0
DXF ScaleX= 1
DXF ScaleY= 10

--- UNT 31 in Lagunillas Cr Wtrshd.p01 (plan) ---

Plan Title=Multiple Run
Short Identifier=Multiple
Geom File=g01
Flow File=f01
Subcritical Flow
K Sum by GR= 0
Std Step Tol= 0.01
Critical Tol= 0.01
Num of Std Step Trials= 20
Max Error Tol= 0.3
Flow Tol Ratio= 0.001
Split Flow NTrial= 30
Split Flow Tol= 0.02
Split Flow Ratio= 0.02
Log Output Level= 0
Friction Slope Method= 1
Unsteady Friction Slope Method= 2
Unsteady Bridges Friction Slope Method= 1
Parabolic Critical Depth
Global Vel Dist=  1 , 1 , 1
Global Log Level= 0
CheckData=True
Encroach Param= -1, 0, 0, 0
BEGIN DESCRIPTION:
Multiple Run
END DESCRIPTION:

--- UNT 31 in Lagunillas Cr Wtrshd.f01 (steady flow) ---

Flow Title=Multiple
Number of Profiles=7
Profile Names=10-year,25-year,50-year,1pct_min,100-year,1pct_plu,500-year
River Rch & RM= UNT 31 in Laguni,Reach-1,8988
     207     286     352     217     432     862     660
River Rch & RM= UNT 31 in Laguni,Reach-1,7396
     296     416     517     321     640    1276     994
River Rch & RM= UNT 31 in Laguni,Reach-1,99
     296     416     517     321     640    1276     994
Boundary for River Rch & Prof#=UNT 31 in Laguni,Reach-1,1
Up Type=0
Dn Type=3
Dn Slope=0.005
Boundary for River Rch & Prof#=UNT 31 in Laguni,Reach-1,2
Up Type=0
Dn Type=3
Dn Slope=0.005
Boundary for River Rch & Prof#=UNT 31 in Laguni,Reach-1,3
Up Type=0
Dn Type=3
Dn Slope=0.005
Boundary for River Rch & Prof#=UNT 31 in Laguni,Reach-1,4
Up Type=0
Dn Type=3
Dn Slope=0.005
Boundary for River Rch & Prof#=UNT 31 in Laguni,Reach-1,5
Up Type=0
Dn Type=3
Dn Slope=0.005
Boundary for River Rch & Prof#=UNT 31 in Laguni,Reach-1,6
Up Type=0
Dn Type=3
Dn Slope=0.005
Boundary for River Rch & Prof#=UNT 31 in Laguni,Reach-1,7
Up Type=0
Dn Type=3
Dn Slope=0.005

--- UNT 31 in Lagunillas Cr Wtrshd.g01 (geometry) ---

Geom Title=Existing Conditions

River Reach=UNT 31 in Laguni,Reach-1
Reach XY= 30
      2048260.80     13465824.54      2048430.80     13465834.54
      2048500.80     13465684.54      2048790.80     13465664.54
      2048910.80     13465734.54      2048969.03     13465852.46
      2049209.92     13465883.92      2049627.67     13465589.87
      2049820.80     13465364.54      2050110.80     13465344.54
      2050320.80     13465254.54      2050540.80     13465464.54
      2050730.80     13465854.54      2051040.80     13465854.54
      2051210.80     13466084.54      2051320.80     13466104.54
      2051420.80     13466204.54      2051430.80     13466604.54
      2051690.80     13466874.54      2051805.49     13467199.20
      2051968.68     13467319.86      2051972.79     13467465.17
      2052080.31     13467655.73      2052835.52     13468309.38
      2053524.75     13468537.68      2053621.11     13468524.66
      2053916.68     13468183.51      2054150.00     13468050.00
      2054274.00     13467863.27      2054420.80     13467843.60

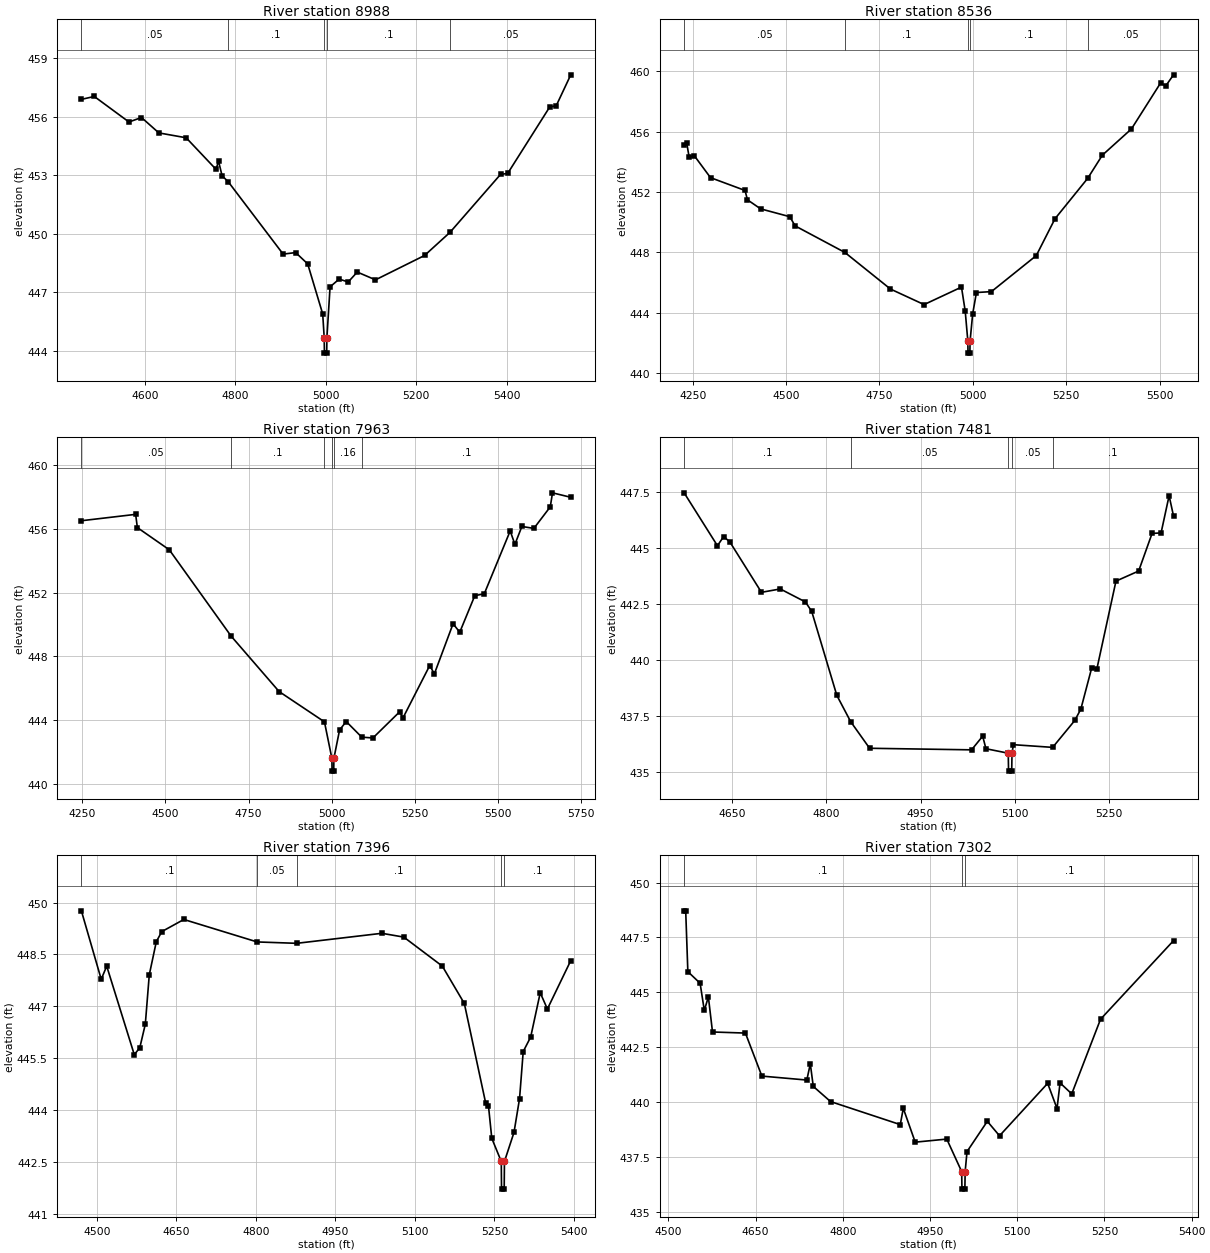
Type RM Length L Ch R = 1,8988,452,452,452
BEGIN DESCRIPTION:
Mapping XS e4240102
END DESCRIPTION:
XS GIS Cut Line= 4
      2047869.92     13466110.74      2048308.28     13465879.08
      2048313.92     13465759.72      2048143.40     13465325.18
#Sta/Elev= 30
  4459.6  456.89  4488.1  457.04  4564.8  455.73  4592.5  455.96  4630.9  455.17
  4691.3  454.92  4757.3  453.30  4762.9  453.72  4770.7  452.97  4784.1  452.67
  4905.7  448.95  4933.4  449.03  4960.0  448.45  4993.2  445.88  4996.5  444.67
  4997.0  443.87  5002.0  443.87  5002.5  444.67  5009.5  447.27  5029.6  447.67
  5049.6  447.52  5069.6  448.03  5109.9  447.63  5218.4  448.88  5274.8  450.07
  5386.4  453.04  5402.2  453.09  5494.9  456.49  5509.7  456.57  5541.7  458.15
#Mann=5,-1,0
  4459.6    0.05       0  4784.1     0.1       0  4996.5    0.07       0
  5002.5     0.1       0  5274.8    0.05       0
Bank Sta=4996.5,5002.5
Exp/Cntr=0.3,0.1

Type RM Length L Ch R = 1,8536,573,573,573
BEGIN DESCRIPTION:
Mapping XS 800a5fe8
END DESCRIPTION:
XS GIS Cut Line= 4
      2048382.13     13466371.11      2048646.85     13466054.31
      2048620.81     13465394.59      2048464.56     13465216.63
#Sta/Elev= 30
  4227.1  455.09  4234.0  455.24  4240.5  454.32  4254.8  454.39  4297.7  452.95
  4390.1  452.10  4396.6  451.48  4431.8  450.88  4509.9  450.36  4524.2  449.75
  4657.3  447.99  4779.4  445.56  4869.4  444.53  4969.5  445.69  4979.5  444.09
  4986.5  442.11  4987.0  441.31  4992.0  441.31  4992.5  442.11  4999.5  443.92
  5009.5  445.33  5049.6  445.39  5169.7  447.78  5219.7  450.22  5307.2  452.90
  5346.5  454.44  5424.4  456.18  5502.2  459.22  5516.4  459.04  5537.0  459.77
#Mann=5,-1,0
  4227.1    0.05       0  4657.3     0.1       0  4986.5    0.07       0
  4992.5     0.1       0  5307.2    0.05       0
Bank Sta=4986.5,4992.5
Exp/Cntr=0.3,0.1

Type RM Length L Ch R = 1,7963,482,482,482
BEGIN DESCRIPTION:
Mapping XS ebdff59d
END DESCRIPTION:
XS GIS Cut Line= 4
      2048876.91     13466405.86      2049119.94     13466336.43
      2049041.82     13465437.99      2048803.27     13465229.80
#Sta/Elev= 30
  4247.5  456.50  4410.6  456.90  4415.8  456.07  4511.7  454.68  4697.5  449.27
  4841.9  445.79  4978.2  443.89  5000.6  441.60  5001.1  440.80  5006.1  440.80
  5006.6  441.60  5023.7  443.38  5043.7  443.91  5090.4  442.93  5124.0  442.88
  5204.3  444.52  5214.4  444.14  5294.7  447.42  5308.7  446.90  5364.9  450.04
  5385.0  449.51  5430.2  451.80  5458.7  451.92  5536.6  455.86  5550.8  455.02
  5571.7  456.14  5607.8  456.02  5657.1  457.37  5663.8  458.25  5718.7  457.97
#Mann=6,-1,0
  4247.5    0.05       0  4697.5     0.1       0  4978.2    0.16       0
  5000.6    0.07       0  5006.6    0.16       0  5090.4     0.1       0
Bank Sta=5000.6,5006.6
Exp/Cntr=0.3,0.1

Type RM Length L Ch R = 1,7481,85,85,85
BEGIN DESCRIPTION:
Mapping XS ffecb441
END DESCRIPTION:
XS GIS Cut Line= 4
      2049513.88     13466108.00      2049504.77     13465838.49
      2049422.74     13465466.10      2049353.45     13465358.33
#Sta/Elev= 30
  4573.5  447.48  4626.5  445.12  4636.5  445.53  4646.5  445.28  4696.6  443.04
  4726.6  443.19  4766.6  442.61  4776.6  442.19  4816.6  438.44  4838.6  437.27
  4868.8  436.08  5031.1  436.01  5048.8  436.62  5054.0  436.06  5089.5  435.86
  5090.0  435.06  5095.0  435.06  5095.5  435.86  5097.7  436.24  5160.2  436.12
  5195.4  437.32  5205.1  437.83  5222.5  439.68  5230.6  439.62  5261.0  443.54
  5297.1  443.99  5318.5  445.67  5332.8  445.69  5345.6  447.35  5352.6  446.45
#Mann=5,-1,0
  4573.5     0.1       0  4838.6    0.05       0  5089.5   0.033       0
  5095.5    0.05       0  5160.2     0.1       0
Bank Sta=5089.5,5095.5
Exp/Cntr=0.3,0.1

Type RM Length L Ch R = 1,7396,94,94,94
BEGIN DESCRIPTION:
Mapping XS 1e863aa4
END DESCRIPTION:
XS GIS Cut Line= 4
      2049685.74     13466150.95      2049627.16     13465945.27
      2049474.82     13465393.18      2049433.15     13465262.97
#Sta/Elev= 30
  4470.8  449.76  4508.2  447.78  4518.6  448.16  4570.6  445.60  4581.0  445.80
  4591.4  446.48  4598.9  447.91  4612.2  448.87  4622.6  449.16  4664.1  449.51
  4802.4  448.86  4877.0  448.82  5037.7  449.11  5079.1  449.00  5151.8  448.16
  5193.3  447.08  5233.7  444.19  5238.9  444.11  5245.1  443.18  5263.0  442.51
  5263.5  441.71  5268.5  441.71  5269.0  442.51  5287.0  443.35  5297.5  444.33
  5304.4  445.69  5318.5  446.11  5336.5  447.39  5350.0  446.92  5394.1  448.32
#Mann=5,-1,0
  4470.8     0.1       0  4802.4    0.05       0  4877.0     0.1       0
  5263.0    0.07       0  5269.0     0.1       0
Bank Sta=5263,5269
Exp/Cntr=0.3,0.1

Type RM Length L Ch R = 1,7302,668,668,668
BEGIN DESCRIPTION:
Mapping XS fadc4ca3
END DESCRIPTION:
XS GIS Cut Line= 4
      2049825.11     13466003.89      2049700.19     13465876.57
      2049558.29     13465348.00      2049597.36     13465238.82
#Sta/Elev= 30
  4527.2  448.71  4529.9  448.71  4533.6  445.94  4554.7  445.41  4561.9  444.17
  4568.9  444.79  4576.0  443.19  4632.6  443.14  4660.9  441.18  4738.2  441.00
  4744.2  441.74  4749.3  440.71  4779.0  440.02  4898.9  438.97  4904.1  439.71
  4924.6  438.17  4978.9  438.31  5004.5  436.83  5005.0  436.03  5010.0  436.03
  5010.5  436.83  5013.7  437.74  5048.6  439.12  5069.6  438.46  5152.4  440.85
  5168.5  439.70  5173.7  440.87  5193.8  440.37  5243.3  443.77  5368.8  447.35
#Mann=3,-1,0
  4527.2     0.1       0  5004.5    0.07       0  5010.5     0.1       0
Bank Sta=5004.5,5010.5
Exp/Cntr=0.3,0.1

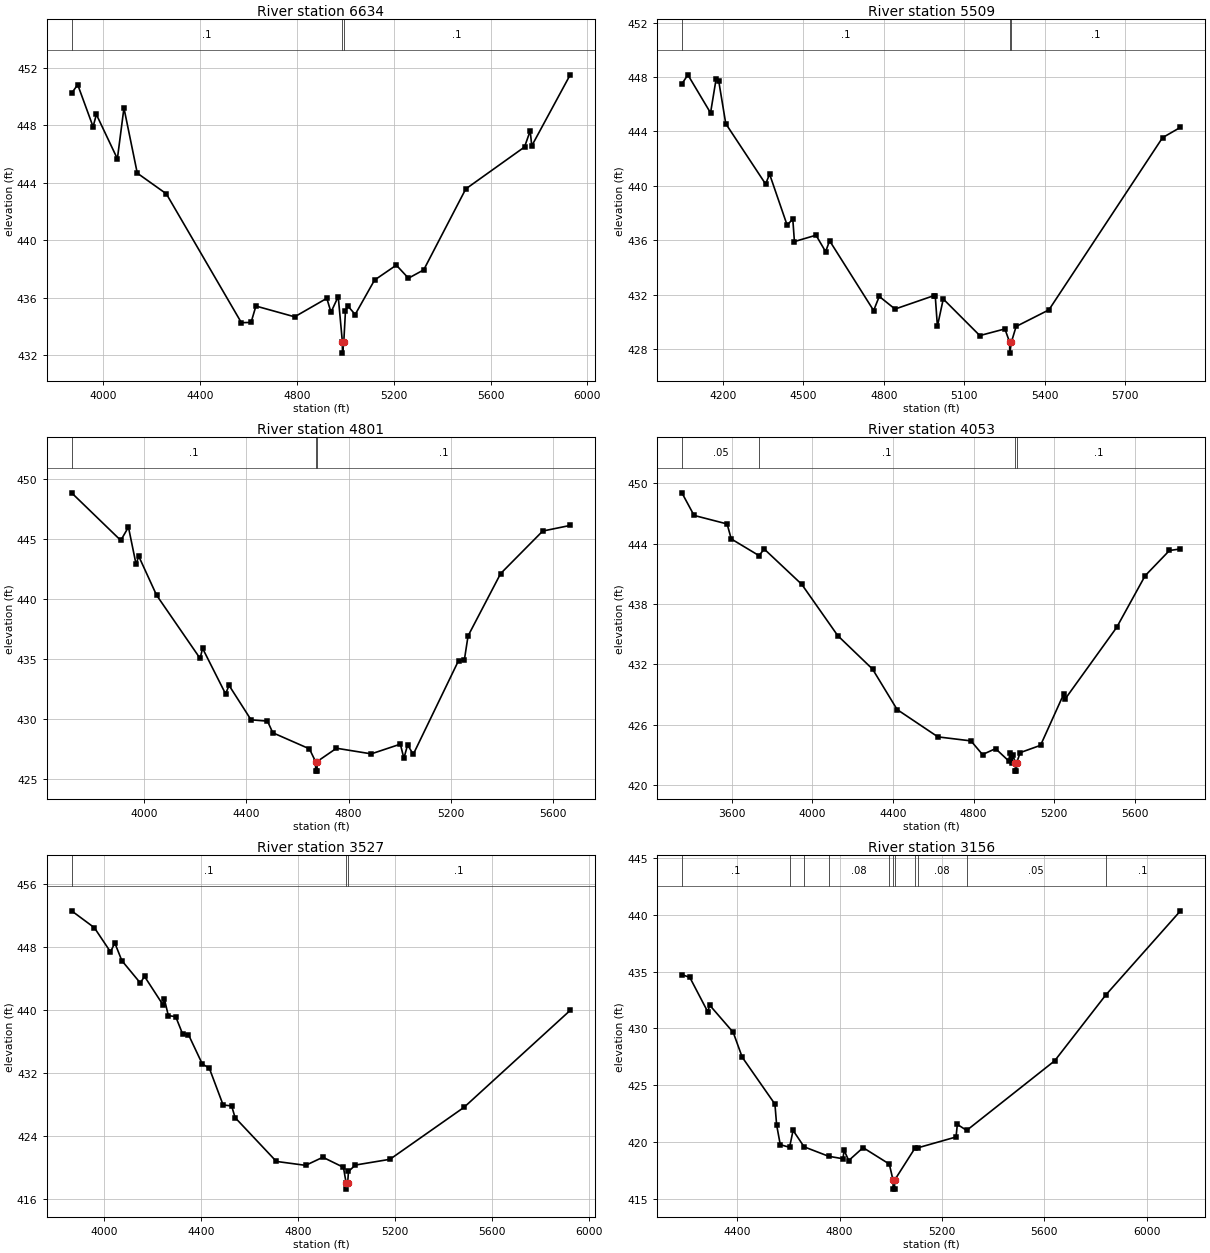
Type RM Length L Ch R = 1,6634,1125,1125,1125
BEGIN DESCRIPTION:
Mapping XS 02685d68
END DESCRIPTION:
XS GIS Cut Line= 4
      2049974.97     13466349.46      2050152.93     13466210.56
      2050148.59     13464986.60      2049589.33     13464743.82
#Sta/Elev= 30
  3869.3  450.24  3894.6  450.83  3958.1  447.90  3971.6  448.76  4058.4  445.67
  4085.5  449.21  4140.6  444.67  4260.6  443.23  4570.6  434.25  4610.6  434.27
  4630.6  435.41  4790.6  434.66  4923.5  435.95  4940.6  434.98  4970.6  436.07
  4987.6  432.93  4988.1  432.13  4993.6  432.93  5000.6  435.10  5010.6  435.41
  5040.6  434.82  5120.6  437.22  5210.6  438.26  5260.6  437.35  5323.7  437.93
  5497.4  443.57  5740.0  446.49  5763.5  447.62  5769.9  446.57  5928.7  451.52
#Mann=3,-1,0
  3869.3     0.1       0  4987.6    0.07       0  4993.6     0.1       0
Bank Sta=4987.6,4993.6
Exp/Cntr=0.3,0.1

Type RM Length L Ch R = 1,5509,708,708,708
BEGIN DESCRIPTION:
Mapping XS bf02ca66
END DESCRIPTION:
XS GIS Cut Line= 4
      2050200.65     13466475.32      2050495.81     13466410.21
      2051233.66     13465342.50      2051121.26     13465109.07
#Sta/Elev= 30
  4046.6  447.49  4068.9  448.16  4153.5  445.36  4173.9  447.82  4184.2  447.68
  4210.2  444.57  4358.8  440.13  4373.6  440.86  4439.2  437.10  4460.1  437.57
  4466.2  435.90  4546.7  436.37  4582.5  435.16  4597.4  435.96  4761.6  430.83
  4782.5  431.87  4841.4  430.94  4985.3  431.92  4991.4  431.89  4999.4  429.67
  5021.2  431.68  5157.5  428.99  5251.0  429.48  5268.8  428.50  5269.3  427.70
  5275.1  428.50  5292.9  429.66  5415.2  430.88  5838.9  443.54  5905.8  444.30
#Mann=3,-1,0
  4046.6     0.1       0  5268.8    0.07       0  5275.1     0.1       0
Bank Sta=5268.8,5275.1
Exp/Cntr=0.3,0.1

Type RM Length L Ch R = 1,4801,748,748,748
BEGIN DESCRIPTION:
Mapping XS 93a48196
END DESCRIPTION:
XS GIS Cut Line= 4
      2050252.74     13466622.89      2050803.97     13466614.21
      2051624.28     13465980.52      2051689.39     13465624.60
#Sta/Elev= 30
  3716.9  448.87  3909.2  444.90  3939.2  446.01  3969.2  442.89  3979.2  443.59
  4049.2  440.33  4219.2  435.06  4229.2  435.89  4318.9  432.10  4332.7  432.80
  4418.6  429.93  4482.9  429.82  4503.7  428.85  4646.8  427.51  4670.8  426.45
  4671.3  425.65  4676.6  425.65  4677.1  426.45  4752.7  427.56  4888.7  427.09
  5002.4  427.90  5016.3  426.72  5030.8  427.84  5052.9  427.05  5230.0  434.87
  5252.7  434.92  5267.2  436.93  5394.5  442.13  5559.1  445.68  5666.6  446.15
#Mann=3,-1,0
  3716.9     0.1       0  4670.8    0.07       0  4677.1     0.1       0
Bank Sta=4670.8,4677.1
Exp/Cntr=0.3,0.1

Type RM Length L Ch R = 1,4053,526,526,526
BEGIN DESCRIPTION:
Mapping XS 38f4c345
END DESCRIPTION:
XS GIS Cut Line= 4
      2050165.93     13467551.71      2050573.94     13467460.56
      2051923.76     13466518.72      2051975.85     13466110.73
#Sta/Elev= 30
  3351.7  449.07  3412.2  446.82  3576.2  445.97  3596.7  444.48  3734.4  442.82
  3760.6  443.47  3946.7  439.96  4125.5  434.85  4298.2  431.52  4420.4  427.49
  4622.8  424.77  4786.8  424.37  4844.1  423.01  4908.9  423.60  4974.4  422.37
  4980.4  423.17  4989.2  422.19  4995.3  422.98  5006.9  422.16  5007.4  421.36
  5012.8  421.36  5013.3  422.16  5031.0  423.20  5132.3  423.93  5246.5  429.00
  5254.4  428.54  5510.2  435.67  5651.3  440.81  5772.3  443.33  5827.0  443.48
#Mann=4,-1,0
  3351.7    0.05       0  3734.4     0.1       0  5006.9    0.07       0
  5013.3     0.1       0
Bank Sta=5006.9,5013.3
Exp/Cntr=0.3,0.1

Type RM Length L Ch R = 1,3527,371,371,371
BEGIN DESCRIPTION:
Mapping XS 0952f267
END DESCRIPTION:
XS GIS Cut Line= 4
      2050869.04     13467812.14      2051329.15     13467612.47
      2051997.55     13467039.55      2052084.35     13466371.17
#Sta/Elev= 30
  3866.5  452.57  3960.2  450.43  4026.8  447.36  4044.8  448.48  4073.7  446.24
  4149.6  443.41  4167.3  444.23  4243.4  440.62  4248.9  441.38  4265.4  439.26
  4295.8  439.12  4324.7  436.89  4348.2  436.85  4405.6  433.10  4434.2  432.59
  4491.3  427.90  4526.4  427.78  4540.6  426.30  4710.8  420.73  4831.5  420.23
  4902.6  421.26  4987.4  419.98  4998.4  418.01  4998.9  417.21  5004.8  418.01
  5008.2  419.45  5036.7  420.27  5179.2  421.00  5484.9  427.61  5922.4  439.92
#Mann=3,-1,0
  3866.5     0.1       0  4998.4    0.07       0  5004.8     0.1       0
Bank Sta=4998.4,5004.8
Exp/Cntr=0.3,0.1

Type RM Length L Ch R = 1,3156,88,88,88
BEGIN DESCRIPTION:
Mapping XS a0f1fdeb
END DESCRIPTION:
XS GIS Cut Line= 4
      2051515.76     13468128.98      2051924.75     13467672.99
      2052013.72     13467350.72      2052223.25     13466371.14
#Sta/Elev= 30
  4183.4  434.75  4214.3  434.51  4284.6  431.47  4292.0  432.06  4384.0  429.66
  4419.1  427.47  4547.0  423.33  4553.7  421.49  4567.9  419.75  4604.2  419.52
  4618.0  421.01  4661.1  419.56  4756.7  418.73  4812.5  418.51  4817.7  419.25
  4835.3  418.35  4891.6  419.49  4994.1  418.04  5008.5  416.63  5009.0  415.83
  5014.4  415.83  5014.9  416.63  5095.6  419.49  5104.8  419.47  5254.8  420.43
  5259.9  421.54  5296.4  421.01  5640.3  427.15  5840.2  432.96  6132.0  440.38
#Mann=11,-1,0
  4183.4     0.1       0  4604.2    0.05       0  4661.1     0.1       0
  4756.7    0.08       0  4994.1    0.05       0  5008.5    0.04       0
  5014.9    0.05       0  5095.6     0.1       0  5104.8    0.08       0
  5296.4    0.05       0  5840.2     0.1       0
Bank Sta=5008.5,5014.9
Exp/Cntr=0.3,0.1

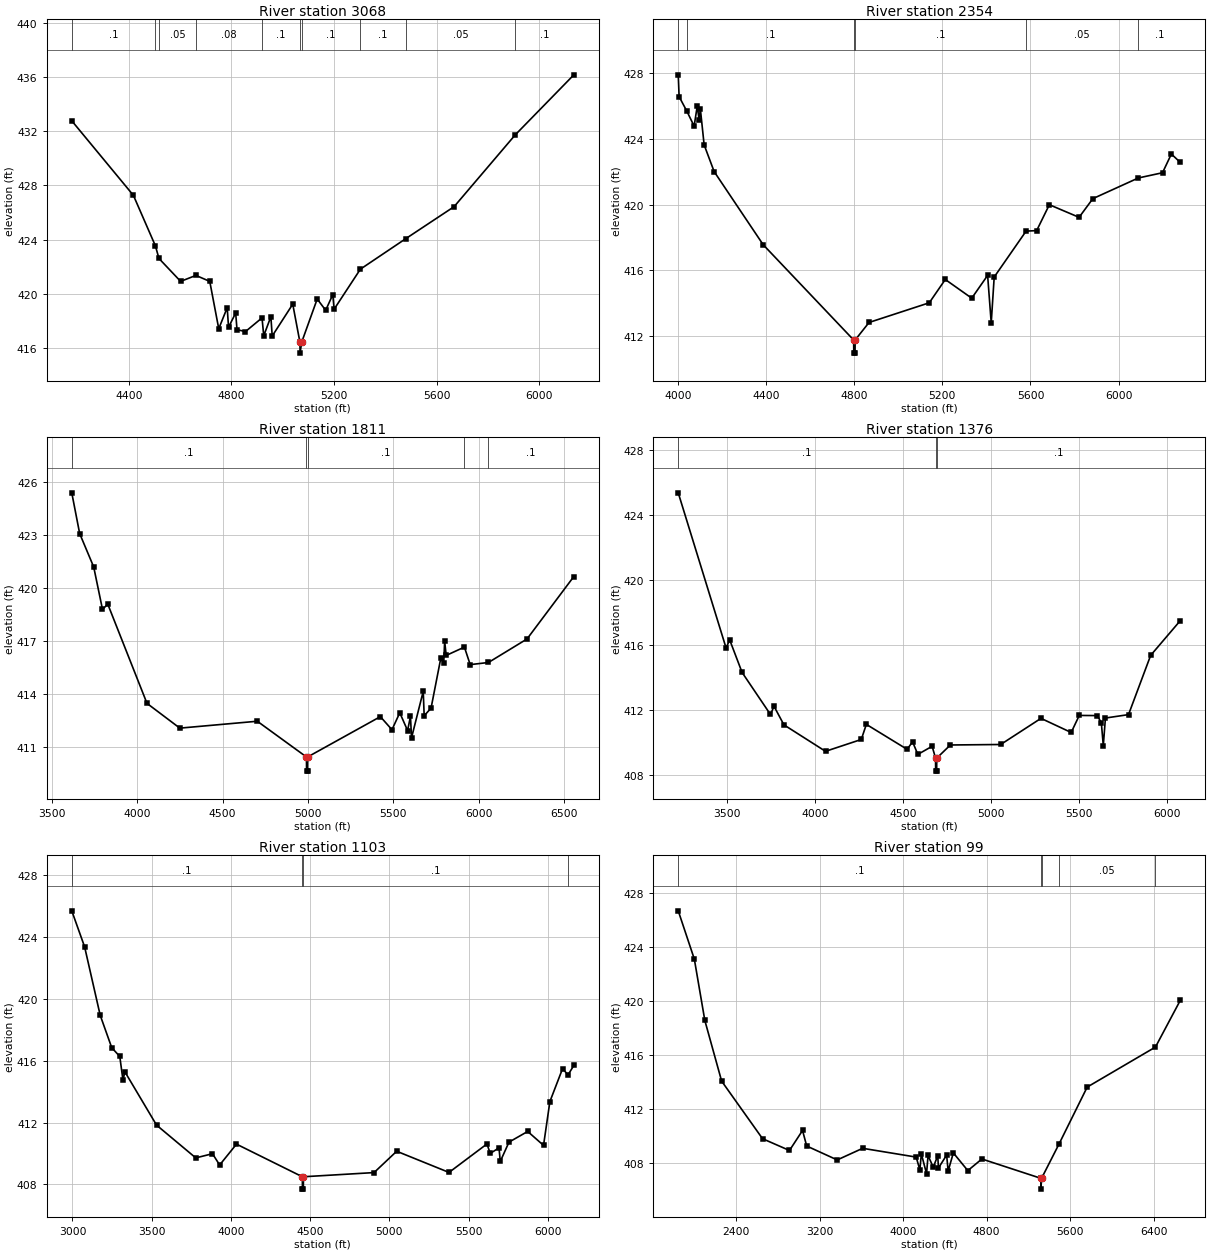
Type RM Length L Ch R = 1,3068,714,714,714
BEGIN DESCRIPTION:
Mapping XS 94209a0f
END DESCRIPTION:
XS GIS Cut Line= 4
      2051580.88     13468228.80      2051949.70     13467793.43
      2052083.17     13467350.72      2052340.21     13466463.07
#Sta/Elev= 30
  4178.1  432.77  4418.4  427.27  4504.1  423.55  4517.9  422.62  4602.5  420.93
  4662.0  421.37  4716.0  420.93  4751.0  417.44  4784.0  418.99  4789.2  417.55
  4817.0  418.60  4822.2  417.37  4855.2  417.23  4919.7  418.24  4926.4  416.92
  4954.2  418.33  4959.4  416.90  5039.5  419.25  5067.5  416.44  5068.0  415.64
  5074.2  416.44  5134.8  419.63  5167.8  418.80  5195.5  419.95  5200.8  418.88
  5303.1  421.83  5479.3  424.07  5668.5  426.44  5906.6  431.73  6135.2  436.16
#Mann=10,-1,0
  4178.1     0.1       0  4504.1    0.08       0  4517.9    0.05       0
  4662.0    0.08       0  4919.7     0.1       0  5067.5    0.07       0
  5074.2     0.1       0  5303.1     0.1       0  5479.3    0.05       0
  5906.6     0.1       0
Bank Sta=5067.5,5074.2
Exp/Cntr=0.3,0.1

Type RM Length L Ch R = 1,2354,543,543,543
BEGIN DESCRIPTION:
Mapping XS 9a619a81
END DESCRIPTION:
XS GIS Cut Line= 4
      2051737.11     13468602.06      2052392.51     13468289.55
      2052935.05     13467269.59      2052969.77     13466874.59
#Sta/Elev= 30
  4001.9  427.91  4005.9  426.58  4041.5  425.68  4074.0  424.78  4088.2  426.01
  4096.7  425.15  4102.2  425.84  4119.4  423.64  4164.8  422.01  4387.3  417.55
  4797.8  411.74  4798.3  410.94  4804.0  410.94  4804.5  411.74  4867.6  412.81
  5140.9  414.01  5213.5  415.43  5333.5  414.29  5405.6  415.68  5421.9  412.78
  5435.4  415.58  5580.1  418.38  5628.0  418.41  5685.6  419.99  5820.5  419.22
  5883.0  420.36  6089.3  421.62  6199.1  421.94  6239.2  423.08  6279.8  422.57
#Mann=6,-1,0
  4001.9    0.08       0  4041.5     0.1       0  4797.8    0.07       0
  4804.5     0.1       0  5580.1    0.05       0  6089.3     0.1       0
Bank Sta=4797.8,4804.5
Exp/Cntr=0.3,0.1

Type RM Length L Ch R = 1,1811,435,435,435
BEGIN DESCRIPTION:
Mapping XS ffb0a03e
END DESCRIPTION:
XS GIS Cut Line= 4
      2051820.18     13468944.80      2052794.17     13468705.21
      2053330.63     13467548.96      2053106.67     13466923.95
#Sta/Elev= 30
  3616.4  425.37  3662.6  423.07  3744.9  421.18  3796.4  418.78  3827.3  419.08
  4057.1  413.47  4249.5  412.07  4703.4  412.46  4991.5  410.44  4992.0  409.64
  4997.7  409.64  4998.2  410.44  5424.4  412.72  5492.4  411.98  5538.2  412.94
  5584.0  411.93  5600.8  412.74  5606.9  411.52  5675.6  414.15  5681.1  412.77
  5721.4  413.20  5778.2  416.01  5795.6  415.74  5801.1  416.98  5810.2  416.18
  5916.8  416.65  5950.7  415.66  6057.5  415.78  6283.7  417.11  6558.0  420.64
#Mann=5,-1,0
  3616.4     0.1       0  4991.5    0.07       0  4998.2     0.1       0
  5916.8    0.05       0  6057.5     0.1       0
Bank Sta=4991.5,4998.2
Exp/Cntr=0.3,0.1

Type RM Length L Ch R = 1,1376,273,273,273
BEGIN DESCRIPTION:
Mapping XS 839fe229
END DESCRIPTION:
XS GIS Cut Line= 4
      2051825.42     13469022.92      2053210.84     13468830.21
      2053695.22     13467778.13      2053486.90     13467564.60
#Sta/Elev= 30
  3222.8  425.37  3495.0  415.81  3515.2  416.32  3585.8  414.31  3747.2  411.72
  3767.6  412.22  3823.9  411.08  4060.4  409.45  4263.8  410.18  4292.6  411.11
  4524.8  409.57  4555.3  410.04  4585.4  409.26  4666.6  409.76  4686.2  409.03
  4686.7  408.23  4692.4  408.23  4692.9  409.03  4770.4  409.84  5056.6  409.87
  5285.7  411.48  5457.5  410.61  5503.4  411.66  5607.1  411.65  5629.2  411.18
  5640.1  409.80  5652.2  411.50  5783.5  411.71  5909.5  415.36  6078.1  417.50
#Mann=3,-1,0
  3222.8     0.1       0  4686.2    0.07       0  4692.9     0.1       0
Bank Sta=4686.2,4692.9
Exp/Cntr=0.3,0.1

Type RM Length L Ch R = 1,1103,1004,1004,1004
BEGIN DESCRIPTION:
Mapping XS 417da46c
END DESCRIPTION:
XS GIS Cut Line= 5
      2051804.58     13469054.17      2053356.67     13468845.84
      2053591.05     13468637.50      2053872.30     13467798.96
      2053865.89     13467393.76
#Sta/Elev= 30
  2995.5  425.70  3076.6  423.37  3174.8  418.95  3247.7  416.85  3298.6  416.28
  3318.8  414.74  3330.7  415.29  3530.7  411.84  3778.2  409.72  3883.8  409.99
  3929.0  409.26  4035.2  410.61  4451.1  408.50  4451.6  407.70  4457.3  407.70
  4457.8  408.50  4903.7  408.77  5046.5  410.15  5376.8  408.78  5616.1  410.62
  5637.2  410.01  5692.3  410.37  5700.4  409.49  5755.4  410.74  5873.5  411.43
  5973.5  410.53  6013.5  413.36  6093.5  415.49  6128.1  415.09  6164.8  415.70
#Mann=4,-1,0
  2995.5     0.1       0  4451.1    0.07       0  4457.8     0.1       0
  6128.1    0.05       0
Bank Sta=4451.1,4457.8
Exp/Cntr=0.3,0.1

Type RM Length L Ch R = 1,99,0,0,0
BEGIN DESCRIPTION:
UNT 31 in Lagunillas Cr Wtrshd 1.0
END DESCRIPTION:
XS GIS Cut Line= 5
      2051741.91     13469086.14      2053497.30     13468877.09
      2054247.07     13468289.27      2054403.32     13467414.27
      2053642.93     13466482.01
#Sta/Elev= 30
  1843.5  426.69  1997.7  423.12  2098.4  418.58  2259.5  414.09  2651.8  409.83
  2909.6  408.96  3035.0  410.44  3074.7  409.29  3367.3  408.26  3611.3  409.12
  4124.1  408.47  4159.4  407.53  4173.8  408.71  4223.6  407.24  4238.0  408.59
  4287.7  407.72  4331.1  408.58  4337.5  407.66  4416.1  408.62  4430.6  407.44
  4480.3  408.78  4619.1  407.47  4753.8  408.33  5319.3  406.90  5319.8  406.10
  5326.0  406.90  5493.5  409.44  5763.4  413.65  6417.6  416.61  6655.9  420.07
#Mann=5,-1,0
  1843.5     0.1       0  5319.3    0.07       0  5326.0     0.1       0
  5493.5    0.05       0  6417.6     0.1       0
Bank Sta=5319.3,5326
Exp/Cntr=0.3,0.1

Chan Stop Cuts=-1