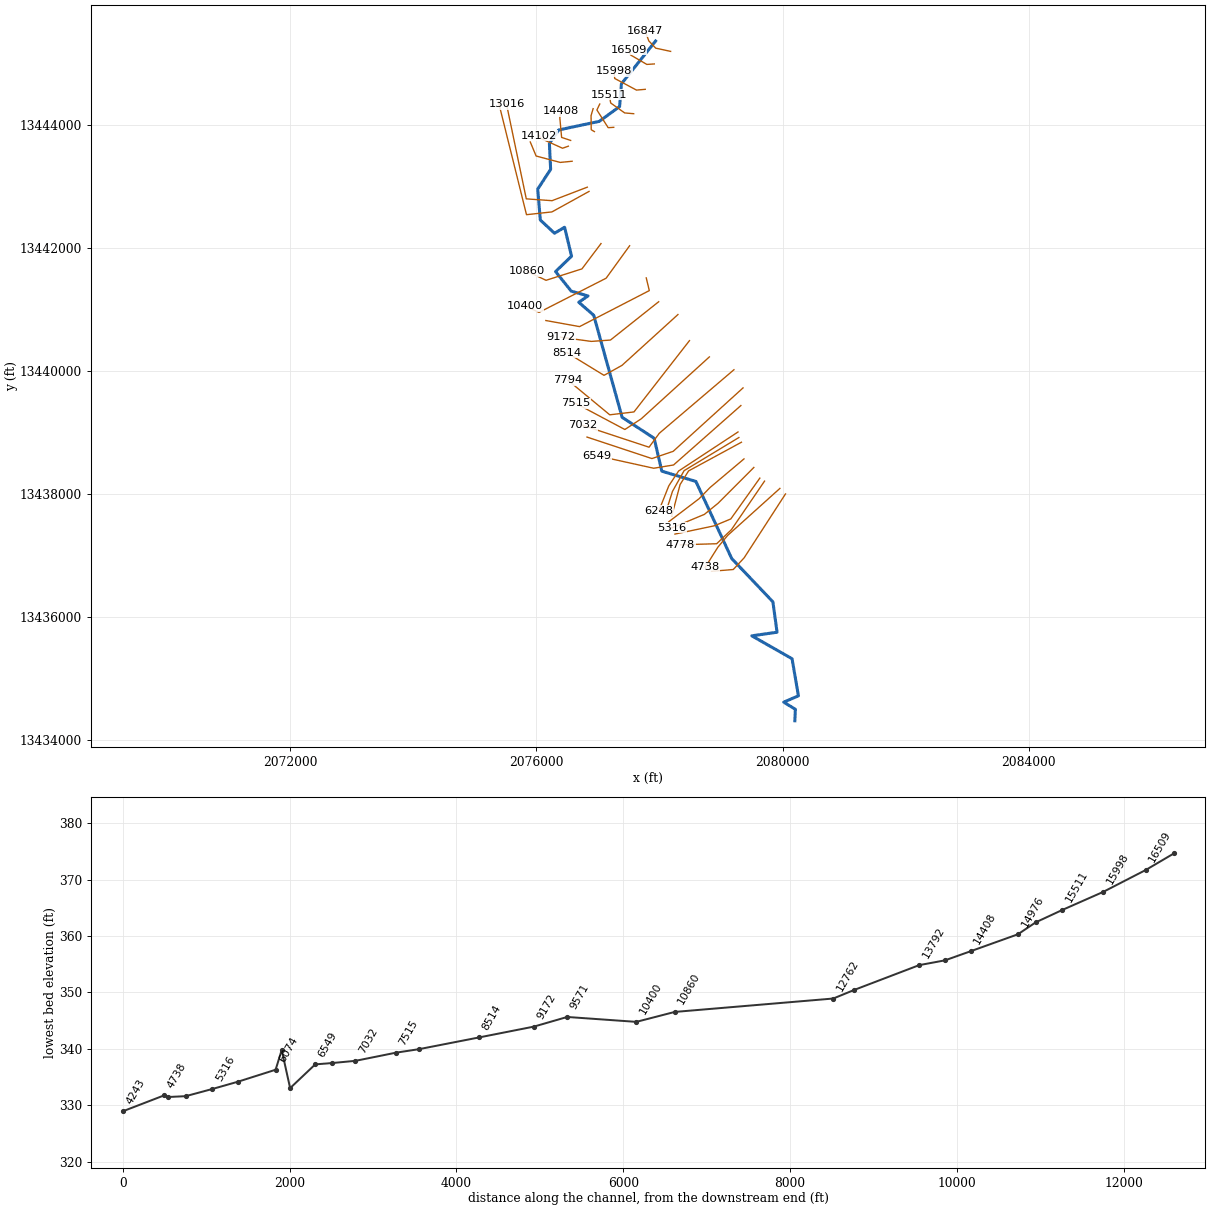
--- UNT 35 in Lagunillas Cr Wtrshd.prj (project) ---

Proj Title=UNT 35 in Lagunillas Cr Wtrshd Base Level Engineering
Current Plan=p01
Default Exp/Contr=0.3,0.1
English Units
Geom File=g01
Flow File=f01
Plan File=p01
BEGIN DESCRIPTION:
UNT 35 in Lagunillas Cr Wtrshd
END DESCRIPTION:

--- UNT 35 in Lagunillas Cr Wtrshd.p01 (plan) ---

Plan Title=Multiple Run
Short Identifier=Multiple
Geom File=g01
Flow File=f01
Subcritical Flow
K Sum by GR= 0
Std Step Tol= 0.01
Critical Tol= 0.01
Num of Std Step Trials= 20
Max Error Tol= 0.3
Flow Tol Ratio= 0.001
Split Flow NTrial= 30
Split Flow Tol= 0.02
Split Flow Ratio= 0.02
Log Output Level= 0
Friction Slope Method= 1
Unsteady Friction Slope Method= 2
Unsteady Bridges Friction Slope Method= 1
Parabolic Critical Depth
Global Vel Dist=  1 , 1 , 1
Global Log Level= 0
CheckData=True
Encroach Param= -1, 0, 0, 0
BEGIN DESCRIPTION:
Multiple Run
END DESCRIPTION:

--- UNT 35 in Lagunillas Cr Wtrshd.f01 (steady flow) ---

Flow Title=Multiple
Number of Profiles=7
Profile Names=10-year,25-year,50-year,1pct_min,100-year,1pct_plu,500-year
River Rch & RM= UNT 35 in Laguni,Reach-1,16847
     129     172     206     124     247     492     358
River Rch & RM= UNT 35 in Laguni,Reach-1,9571
     195     265     321     195     388     774     575
Boundary for River Rch & Prof#=UNT 35 in Laguni,Reach-1,1
Up Type=0
Dn Type=3
Dn Slope=0.005
Boundary for River Rch & Prof#=UNT 35 in Laguni,Reach-1,2
Up Type=0
Dn Type=3
Dn Slope=0.005
Boundary for River Rch & Prof#=UNT 35 in Laguni,Reach-1,3
Up Type=0
Dn Type=3
Dn Slope=0.005
Boundary for River Rch & Prof#=UNT 35 in Laguni,Reach-1,4
Up Type=0
Dn Type=3
Dn Slope=0.005
Boundary for River Rch & Prof#=UNT 35 in Laguni,Reach-1,5
Up Type=0
Dn Type=3
Dn Slope=0.005
Boundary for River Rch & Prof#=UNT 35 in Laguni,Reach-1,6
Up Type=0
Dn Type=3
Dn Slope=0.005
Boundary for River Rch & Prof#=UNT 35 in Laguni,Reach-1,7
Up Type=0
Dn Type=3
Dn Slope=0.005

--- UNT 35 in Lagunillas Cr Wtrshd.g01 (geometry) ---

Geom Title=Existing Conditions

River Reach=UNT 35 in Laguni,Reach-1
Reach XY= 30
      2077935.80     13445359.54      2077380.80     13444664.54
      2077350.80     13444294.54      2077020.80     13444054.54
      2076360.80     13443914.54      2076210.80     13443694.54
      2076230.80     13443274.54      2076020.80     13442954.54
      2076063.16     13442452.33      2076293.71     13442237.05
      2076457.60     13442334.27      2076570.80     13441864.54
      2076310.80     13441614.54      2076565.24     13441296.77
      2076838.16     13441218.30      2076687.46     13441116.22
      2076930.80     13440904.54      2077392.17     13439247.01
      2077912.23     13438906.81      2078037.02     13438372.19
      2078590.80     13438204.54      2079172.05     13436953.28
      2079841.68     13436249.30      2079909.04     13435755.55
      2079498.62     13435697.22      2080152.79     13435324.99
      2080256.26     13434722.22      2080017.37     13434619.44
      2080206.26     13434503.47      2080198.27     13434317.19

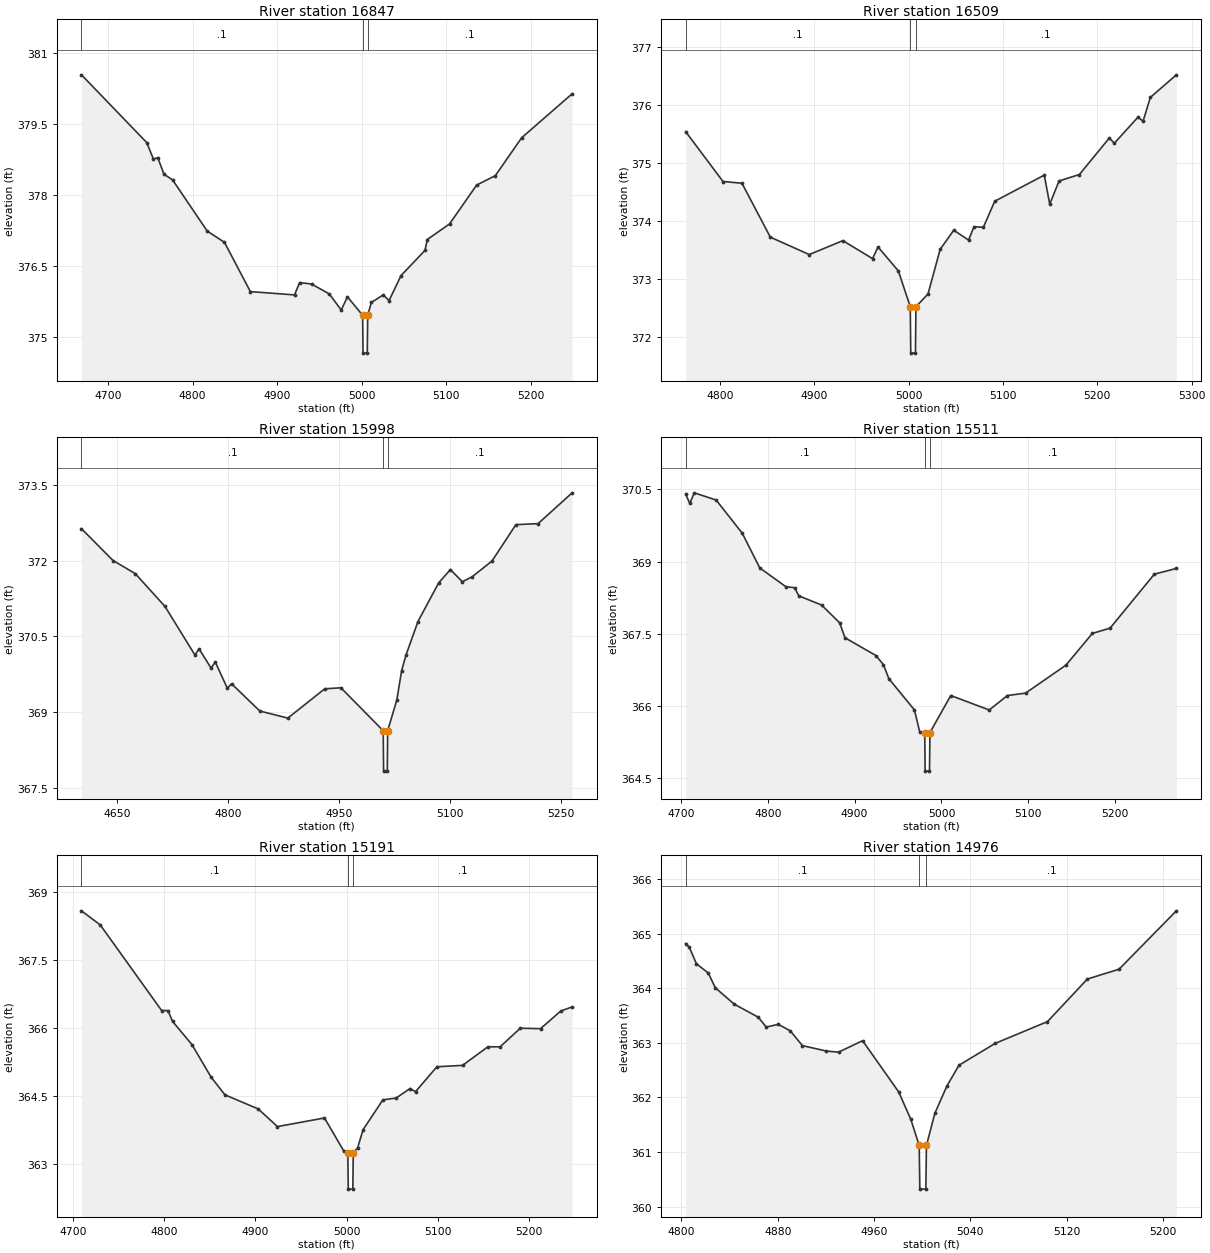
Type RM Length L Ch R = 1,16847,338,338,338
BEGIN DESCRIPTION:
UNT 35 in Lagunillas Cr Wtrshd 17.0
END DESCRIPTION:
XS GIS Cut Line= 4
      2078180.47     13445191.49      2077938.29     13445243.57
      2077826.31     13445360.76      2077766.84     13445521.08
#Sta/Elev= 30
  4668.5  380.54  4745.7  379.11  4753.7  378.76  4758.8  378.79  4766.2  378.44
  4776.4  378.32  4817.3  377.24  4837.8  377.00  4868.4  375.96  4920.7  375.89
  4926.7  376.15  4940.8  376.12  4961.9  375.91  4976.0  375.57  4983.3  375.85
  5001.3  375.46  5001.8  374.66  5006.8  374.66  5007.3  375.46  5011.6  375.73
  5025.7  375.89  5032.6  375.77  5046.8  376.30  5075.1  376.83  5077.8  377.06
  5104.2  377.39  5136.2  378.21  5158.4  378.41  5189.5  379.21  5249.3  380.14
#Mann=3,-1,0
  4668.5     0.1       0  5001.3    0.07       0  5007.3     0.1       0
Bank Sta=5001.3,5007.3
Exp/Cntr=0.3,0.1

Type RM Length L Ch R = 1,16509,511,511,511
BEGIN DESCRIPTION:
Mapping XS f34297e9
END DESCRIPTION:
XS GIS Cut Line= 4
      2077914.57     13444987.45      2077793.50     13444979.64
      2077529.17     13445133.28      2077496.96     13445220.90
#Sta/Elev= 30
  4763.4  375.54  4803.0  374.68  4823.1  374.65  4853.2  373.72  4894.5  373.42
  4930.1  373.66  4961.6  373.35  4967.4  373.55  4988.9  373.14  5001.6  372.52
  5002.1  371.72  5007.1  371.72  5007.6  372.52  5020.4  372.74  5033.3  373.51
  5047.7  373.84  5063.4  373.67  5069.2  373.90  5079.1  373.89  5091.2  374.34
  5143.7  374.79  5149.5  374.29  5159.4  374.69  5180.9  374.80  5212.7  375.43
  5218.0  375.34  5243.1  375.79  5248.5  375.72  5256.2  376.13  5283.8  376.52
#Mann=3,-1,0
  4763.4     0.1       0  5001.6    0.07       0  5007.6     0.1       0
Bank Sta=5001.6,5007.6
Exp/Cntr=0.3,0.1

Type RM Length L Ch R = 1,15998,487,487,487
BEGIN DESCRIPTION:
Mapping XS 89f4cc5c
END DESCRIPTION:
XS GIS Cut Line= 4
      2077767.54     13444575.04      2077625.14     13444562.88
      2077270.98     13444752.12      2077262.37     13444870.93
#Sta/Elev= 30
  4601.4  372.63  4644.1  372.00  4674.2  371.74  4714.4  371.09  4754.8  370.13
  4760.5  370.25  4776.7  369.87  4782.4  369.99  4798.7  369.47  4804.4  369.56
  4842.6  369.02  4880.5  368.88  4930.4  369.46  4952.3  369.48  5009.5  368.63
  5010.0  367.83  5015.0  367.83  5015.5  368.63  5027.9  369.24  5034.4  369.82
  5040.1  370.12  5056.4  370.79  5084.6  371.56  5100.3  371.82  5116.6  371.58
  5130.0  371.68  5156.6  371.99  5188.9  372.71  5218.9  372.73  5265.0  373.34
#Mann=3,-1,0
  4601.4     0.1       0  5009.5    0.07       0  5015.5     0.1       0
Bank Sta=5009.5,5015.5
Exp/Cntr=0.3,0.1

Type RM Length L Ch R = 1,15511,320,320,320
BEGIN DESCRIPTION:
Mapping XS 92292278
END DESCRIPTION:
XS GIS Cut Line= 4
      2077580.02     13444179.20      2077434.17     13444191.35
      2077206.74     13444352.81      2077180.69     13444489.99
#Sta/Elev= 30
  4705.5  370.40  4710.3  370.21  4715.4  370.43  4740.6  370.28  4770.7  369.59
  4790.8  368.87  4820.9  368.48  4830.8  368.46  4835.8  368.29  4861.9  368.10
  4882.8  367.73  4888.9  367.42  4924.6  367.05  4933.2  366.86  4939.4  366.57
  4968.9  365.92  4975.0  365.46  4980.7  365.45  4981.2  364.65  4986.2  364.65
  4986.7  365.45  5010.7  366.22  5055.0  365.92  5075.9  366.22  5096.8  366.27
  5143.2  366.85  5173.7  367.51  5194.1  367.62  5245.0  368.74  5270.4  368.86
#Mann=3,-1,0
  4705.5     0.1       0  4980.7    0.07       0  4986.7     0.1       0
Bank Sta=4980.7,4986.7
Exp/Cntr=0.3,0.1

Type RM Length L Ch R = 1,15191,215,215,215
BEGIN DESCRIPTION:
Mapping XS 32f02b28
END DESCRIPTION:
XS GIS Cut Line= 4
      2077255.55     13443957.55      2077165.50     13443952.12
      2076982.13     13444239.66      2077028.78     13444336.23
#Sta/Elev= 30
  4709.1  368.59  4729.7  368.28  4797.1  366.39  4804.0  366.39  4809.1  366.15
  4830.3  365.64  4851.4  364.92  4866.6  364.53  4903.0  364.22  4924.2  363.83
  4975.8  364.02  4997.0  363.29  5001.4  363.25  5001.9  362.45  5006.9  362.45
  5007.4  363.25  5012.2  363.36  5018.1  363.76  5039.9  364.42  5054.5  364.46
  5069.7  364.67  5075.7  364.60  5099.2  365.15  5127.3  365.18  5155.1  365.59
  5168.5  365.59  5190.7  366.00  5212.9  365.99  5235.1  366.38  5247.6  366.47
#Mann=3,-1,0
  4709.1     0.1       0  5001.4    0.07       0  5007.4     0.1       0
Bank Sta=5001.4,5007.4
Exp/Cntr=0.3,0.1

Type RM Length L Ch R = 1,14976,568,568,568
BEGIN DESCRIPTION:
Mapping XS 4da24583
END DESCRIPTION:
XS GIS Cut Line= 4
      2076942.02     13443888.08      2076889.90     13443918.48
      2076887.72     13444148.52      2076921.15     13444260.66
#Sta/Elev= 28
  4803.6  364.82  4806.7  364.75  4812.5  364.45  4822.4  364.28  4828.2  364.01
  4843.9  363.71  4863.9  363.47  4870.5  363.29  4880.5  363.34  4890.5  363.22
  4900.5  362.95  4920.5  362.85  4930.5  362.83  4950.5  363.04  4980.5  362.10
  4990.5  361.60  4997.5  361.12  4998.0  360.32  5003.0  360.32  5003.5  361.12
  5010.5  361.71  5020.5  362.21  5030.5  362.59  5060.5  362.99  5104.0  363.39
  5137.1  364.17  5163.4  364.35  5211.0  365.42
#Mann=3,-1,0
  4803.6     0.1       0  4997.5    0.07       0  5003.5     0.1       0
Bank Sta=4997.5,5003.5
Exp/Cntr=0.3,0.1

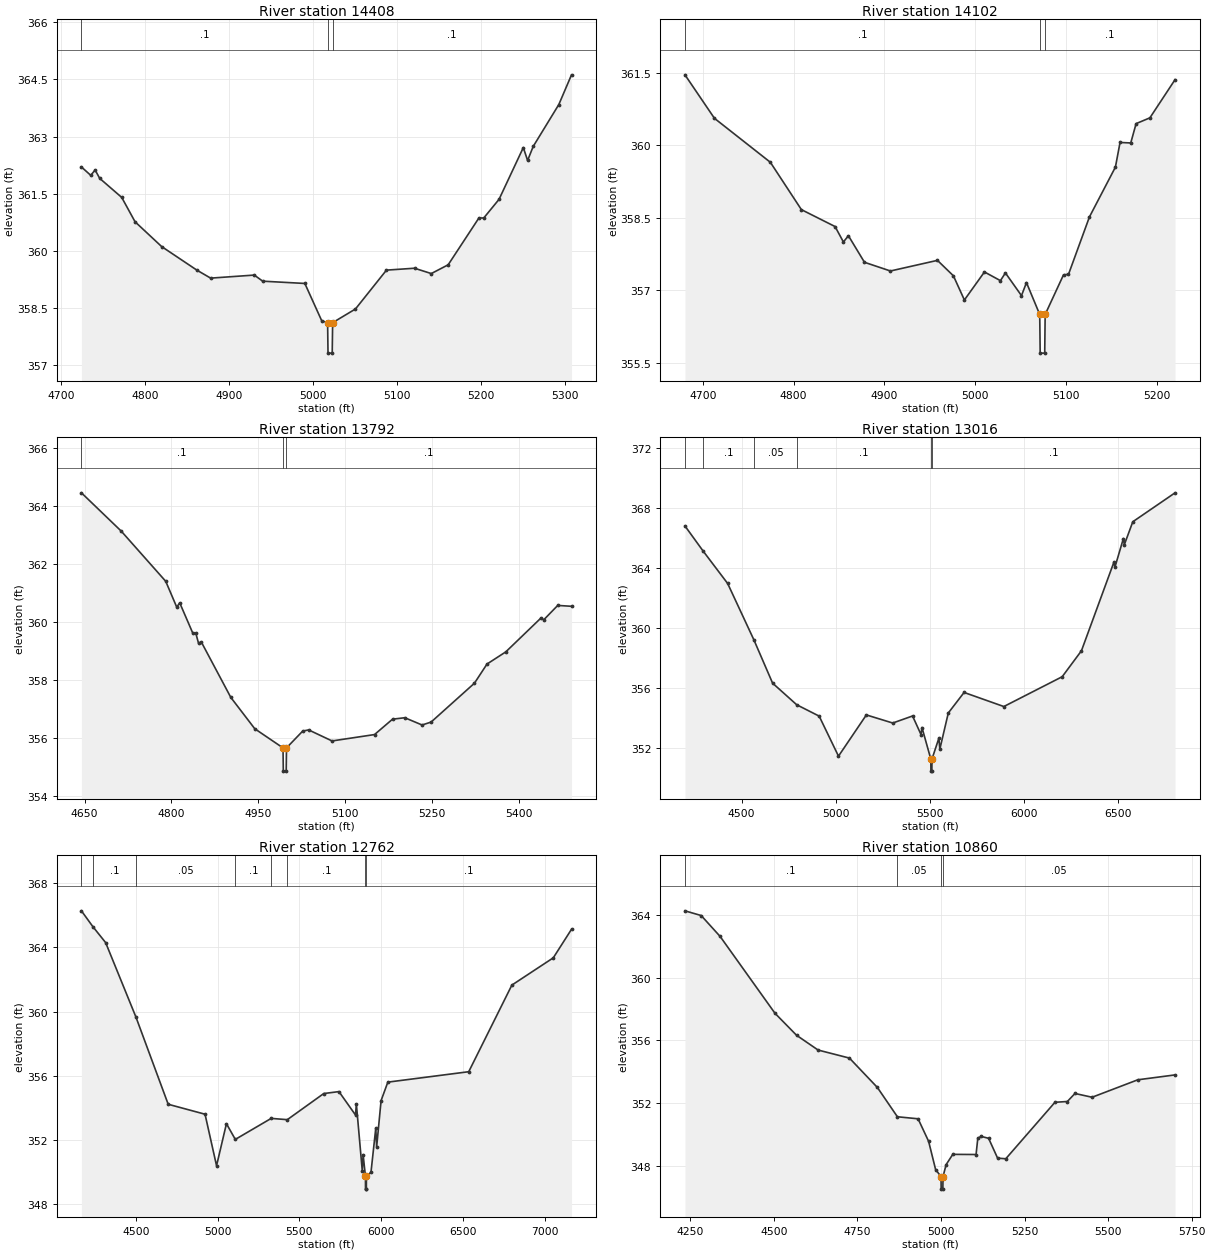
Type RM Length L Ch R = 1,14408,306,306,306
BEGIN DESCRIPTION:
Mapping XS ad8f1c83
END DESCRIPTION:
XS GIS Cut Line= 4
      2076555.65     13443744.89      2076409.21     13443793.70
      2076379.91     13444113.80      2076400.05     13444219.81
#Sta/Elev= 30
  4724.3  362.20  4735.4  361.98  4740.6  362.12  4746.1  361.90  4772.3  361.40
  4788.2  360.76  4819.8  360.11  4861.8  359.49  4878.2  359.28  4930.2  359.36
  4940.2  359.20  4990.4  359.14  5010.5  358.16  5017.5  358.11  5018.0  357.31
  5023.0  357.31  5023.5  358.11  5050.7  358.47  5087.6  359.49  5121.0  359.54
  5141.0  359.40  5161.1  359.63  5197.7  360.86  5203.5  360.86  5221.7  361.35
  5250.6  362.71  5255.7  362.37  5262.4  362.74  5292.9  363.84  5308.0  364.62
#Mann=3,-1,0
  4724.3     0.1       0  5017.5    0.07       0  5023.5     0.1       0
Bank Sta=5017.5,5023.5
Exp/Cntr=0.3,0.1

Type RM Length L Ch R = 1,14102,310,310,310
BEGIN DESCRIPTION:
Mapping XS f62deead
END DESCRIPTION:
XS GIS Cut Line= 4
      2076518.80     13443651.56      2076424.40     13443617.92
      2076077.18     13443774.17      2076045.70     13443824.10
#Sta/Elev= 30
  4680.3  361.46  4712.8  360.56  4774.4  359.65  4808.6  358.67  4845.7  358.32
  4854.9  358.00  4860.4  358.13  4878.1  357.58  4906.7  357.40  4958.5  357.62
  4976.1  357.30  4988.2  356.80  5010.3  357.38  5027.9  357.20  5033.4  357.36
  5051.1  356.89  5056.6  357.16  5071.2  356.50  5071.7  355.70  5076.7  355.70
  5077.2  356.50  5097.4  357.32  5102.9  357.33  5126.0  358.52  5154.6  359.55
  5159.7  360.06  5171.5  360.05  5177.4  360.45  5192.6  360.57  5220.3  361.36
#Mann=3,-1,0
  4680.3     0.1       0  5071.2    0.07       0  5077.2     0.1       0
Bank Sta=5071.2,5077.2
Exp/Cntr=0.3,0.1

Type RM Length L Ch R = 1,13792,776,776,776
BEGIN DESCRIPTION:
Mapping XS 33748aaf
END DESCRIPTION:
XS GIS Cut Line= 4
      2076580.03     13443406.63      2076387.30     13443387.53
      2075994.94     13443491.70      2075899.91     13443719.76
#Sta/Elev= 30
  4644.4  364.44  4713.2  363.12  4790.1  361.39  4809.1  360.50  4814.2  360.65
  4836.7  359.61  4841.9  359.61  4846.7  359.26  4851.8  359.29  4902.5  357.39
  4943.9  356.31  4992.7  355.65  4993.2  354.85  4998.2  354.85  4998.7  355.65
  5026.7  356.23  5037.0  356.27  5077.4  355.89  5150.8  356.11  5181.9  356.64
  5203.1  356.69  5232.9  356.44  5248.5  356.54  5323.4  357.88  5345.1  358.54
  5377.6  358.96  5438.0  360.12  5443.4  360.07  5467.3  360.56  5491.1  360.53
#Mann=3,-1,0
  4644.4     0.1       0  4992.7    0.07       0  4998.7     0.1       0
Bank Sta=4992.7,4998.7
Exp/Cntr=0.3,0.1

Type RM Length L Ch R = 1,13016,254,254,254
BEGIN DESCRIPTION:
Mapping XS d1fb6a26
END DESCRIPTION:
XS GIS Cut Line= 4
      2076826.74     13442985.82      2076253.62     13442766.00
      2075835.21     13442795.52      2075514.56     13444331.53
#Sta/Elev= 30
  4199.5  366.83  4294.5  365.18  4426.3  362.99  4565.9  359.22  4664.9  356.34
  4792.8  354.90  4912.2  354.14  5014.8  351.47  5162.8  354.22  5302.9  353.68
  5408.1  354.15  5453.0  352.91  5458.1  353.38  5505.1  351.27  5505.6  350.47
  5510.6  350.47  5511.1  351.27  5547.9  352.67  5553.0  351.94  5597.9  354.35
  5681.7  355.72  5892.8  354.78  6202.7  356.77  6304.9  358.50  6477.5  364.42
  6482.7  364.08  6527.6  365.99  6532.7  365.58  6577.6  367.11  6801.9  369.04
#Mann=6,-1,0
  4199.5    0.05       0  4294.5     0.1       0  4565.9    0.05       0
  4792.8     0.1       0  5505.1    0.07       0  5511.1     0.1       0
Bank Sta=5505.1,5511.1
Exp/Cntr=0.3,0.1

Type RM Length L Ch R = 1,12762,1902,1902,1902
BEGIN DESCRIPTION:
Mapping XS 853dba43
END DESCRIPTION:
XS GIS Cut Line= 4
      2076854.53     13442916.38      2076252.31     13442583.72
      2075838.69     13442538.57      2075382.29     13444374.73
#Sta/Elev= 30
  4168.0  366.28  4238.2  365.29  4316.0  364.30  4501.2  359.66  4698.5  354.22
  4923.7  353.60  4994.1  350.39  5054.5  353.01  5108.8  352.03  5328.2  353.34
  5426.7  353.26  5649.6  354.89  5742.4  355.01  5843.6  353.55  5848.8  354.24
  5885.0  350.07  5890.1  351.08  5904.3  349.73  5904.8  348.93  5909.8  348.93
  5910.3  349.73  5938.2  349.98  5967.6  352.74  5972.8  351.56  6000.0  354.45
  6041.2  355.60  6535.8  356.25  6799.5  361.65  7052.7  363.35  7164.1  365.13
#Mann=8,-1,0
  4168.0    0.05       0  4238.2     0.1       0  4501.2    0.05       0
  5108.8     0.1       0  5328.2    0.12       0  5426.7     0.1       0
  5904.3    0.03       0  5910.3     0.1       0
Bank Sta=5904.3,5910.3
Exp/Cntr=0.3,0.1

Type RM Length L Ch R = 1,10860,460,460,460
BEGIN DESCRIPTION:
Mapping XS d94f1c5d
END DESCRIPTION:
XS GIS Cut Line= 4
      2077048.96     13442069.15      2076739.73     13441658.37
      2076156.39     13441472.60      2075848.75     13441617.21
#Sta/Elev= 30
  4234.0  364.24  4282.6  363.94  4339.3  362.61  4503.3  357.73  4567.9  356.33
  4632.4  355.39  4726.1  354.88  4809.8  353.01  4869.6  351.15  4931.5  351.02
  4963.0  349.59  4984.0  347.79  5000.1  347.35  5000.6  346.55  5005.6  346.55
  5006.1  347.35  5015.5  348.11  5035.3  348.76  5105.0  348.75  5110.2  349.79
  5120.4  349.90  5142.5  349.78  5169.4  348.52  5193.9  348.48  5341.0  352.07
  5378.1  352.12  5400.9  352.63  5452.1  352.39  5588.9  353.50  5700.3  353.81
#Mann=4,-1,0
  4234.0     0.1       0  4869.6    0.05       0  5000.1    0.03       0
  5006.1    0.05       0
Bank Sta=5000.1,5006.1
Exp/Cntr=0.3,0.1

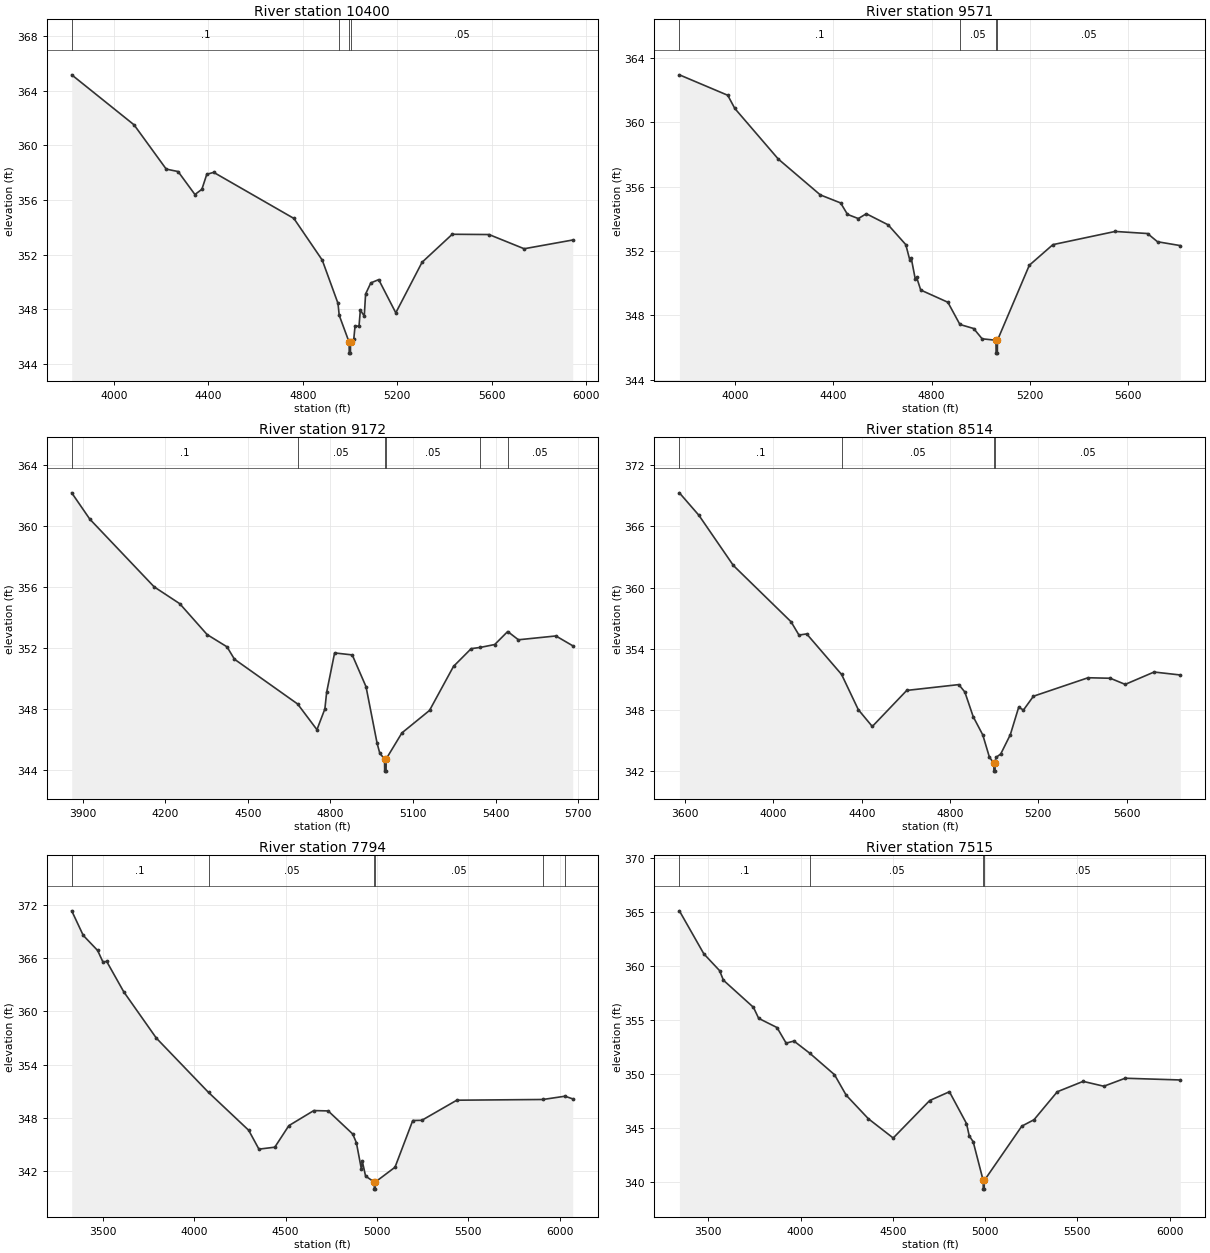
Type RM Length L Ch R = 1,10400,829,829,829
BEGIN DESCRIPTION:
Mapping XS 9e2152e5
END DESCRIPTION:
XS GIS Cut Line= 4
      2077514.26     13442034.46      2077132.30     13441506.65
      2076042.02     13440951.10      2075819.89     13441055.22
#Sta/Elev= 30
  3821.6  365.16  4085.5  361.50  4221.6  358.26  4271.9  358.08  4343.1  356.40
  4372.5  356.78  4393.3  357.88  4422.7  358.02  4761.9  354.65  4882.0  351.60
  4948.7  348.43  4953.8  347.56  4995.8  345.59  4996.3  344.79  5001.3  344.79
  5001.8  345.59  5015.4  345.80  5021.0  346.79  5037.6  346.75  5043.3  347.94
  5059.9  347.50  5065.5  349.12  5087.7  349.93  5121.0  350.17  5193.3  347.74
  5304.5  351.44  5432.3  353.49  5587.9  353.47  5736.7  352.43  5942.1  353.07
#Mann=4,-1,0
  3821.6     0.1       0  4953.8    0.05       0  4995.8    0.03       0
  5001.8    0.05       0
Bank Sta=4995.8,5001.8
Exp/Cntr=0.3,0.1

Type RM Length L Ch R = 1,9571,399,399,399
BEGIN DESCRIPTION:
Mapping XS 85b6607f
END DESCRIPTION:
XS GIS Cut Line= 4
      2077784.02     13441512.10      2077833.69     13441305.26
      2076700.69     13440720.42      2076153.18     13440819.14
#Sta/Elev= 30
  3771.2  362.95  3968.5  361.68  3997.4  360.86  4174.6  357.72  4346.2  355.49
  4429.2  354.99  4457.0  354.28  4501.3  354.02  4533.9  354.32  4623.0  353.63
  4695.0  352.40  4711.6  351.43  4717.2  351.56  4733.7  350.26  4739.4  350.36
  4755.9  349.58  4866.7  348.82  4915.8  347.44  4971.8  347.19  5006.5  346.55
  5063.0  346.46  5063.5  345.66  5068.5  345.66  5069.0  346.46  5199.0  351.12
  5295.2  352.40  5549.3  353.22  5681.4  353.09  5722.0  352.58  5815.3  352.34
#Mann=4,-1,0
  3771.2     0.1       0  4915.8    0.05       0  5063.0    0.04       0
  5069.0    0.05       0
Bank Sta=5063,5069
Exp/Cntr=0.3,0.1

Type RM Length L Ch R = 1,9172,658,658,658
BEGIN DESCRIPTION:
Mapping XS d33f60ba
END DESCRIPTION:
XS GIS Cut Line= 4
      2077986.50     13441124.73      2077202.21     13440501.67
      2076890.79     13440479.97      2076389.65     13440548.26
#Sta/Elev= 30
  3860.5  362.15  3926.2  360.43  4160.0  356.00  4252.9  354.90  4352.3  352.88
  4424.4  352.08  4451.6  351.27  4681.1  348.34  4751.2  346.66  4780.0  348.02
  4786.4  349.10  4815.3  351.68  4879.4  351.55  4929.5  349.47  4969.6  345.78
  4979.6  345.11  4996.7  344.75  4997.2  343.95  5002.2  343.95  5002.7  344.75
  5059.8  346.45  5160.1  347.92  5247.2  350.80  5311.4  351.96  5344.4  352.04
  5396.9  352.23  5444.0  353.08  5482.9  352.54  5619.1  352.79  5680.1  352.15
#Mann=6,-1,0
  3860.5     0.1       0  4681.1    0.05       0  4996.7    0.03       0
  5002.7    0.05       0  5344.4    0.08       0  5444.0    0.05       0
Bank Sta=4996.7,5002.7
Exp/Cntr=0.3,0.1

Type RM Length L Ch R = 1,8514,720,720,720
BEGIN DESCRIPTION:
Mapping XS 671a2e05
END DESCRIPTION:
XS GIS Cut Line= 4
      2078298.93     13440916.34      2077389.92     13440090.43
      2077098.04     13439928.76      2076493.38     13440298.33
#Sta/Elev= 30
  3573.6  369.27  3662.1  367.07  3818.2  362.16  4079.7  356.65  4115.5  355.35
  4150.6  355.46  4308.8  351.49  4384.4  348.05  4447.9  346.40  4604.0  349.93
  4840.0  350.50  4867.4  349.77  4905.2  347.36  4948.7  345.57  4978.9  343.38
  4998.7  342.83  4999.2  342.03  5004.2  342.03  5004.7  342.83  5008.3  343.37
  5030.0  343.71  5073.5  345.60  5111.3  348.28  5133.0  348.01  5178.1  349.36
  5425.8  351.17  5526.5  351.12  5594.1  350.52  5725.0  351.73  5844.1  351.44
#Mann=4,-1,0
  3573.6     0.1       0  4308.8    0.05       0  4998.7    0.03       0
  5004.7    0.05       0
Bank Sta=4998.7,5004.7
Exp/Cntr=0.3,0.1

Type RM Length L Ch R = 1,7794,279,279,279
BEGIN DESCRIPTION:
Mapping XS cc359dfa
END DESCRIPTION:
XS GIS Cut Line= 4
      2078486.44     13440492.73      2077584.15     13439334.14
      2077191.36     13439287.48      2076514.23     13439846.94
#Sta/Elev= 30
  3328.9  371.34  3392.0  368.57  3470.7  366.87  3499.6  365.58  3520.4  365.63
  3613.6  362.21  3791.9  356.99  4077.7  350.86  4297.6  346.59  4353.7  344.46
  4440.6  344.68  4517.5  347.11  4654.1  348.81  4732.8  348.77  4867.0  346.17
  4887.2  345.19  4914.8  342.18  4919.8  343.08  4937.5  341.42  4984.9  340.75
  4985.4  339.95  4990.4  339.95  4990.9  340.75  5098.6  342.42  5195.8  347.69
  5245.3  347.71  5436.8  349.98  5908.2  350.06  6029.1  350.43  6071.3  350.13
#Mann=6,-1,0
  3328.9     0.1       0  4077.7    0.05       0  4984.9    0.03       0
  4990.9    0.05       0  5908.2    0.08       0  6029.1    0.05       0
Bank Sta=4984.9,4990.9
Exp/Cntr=0.3,0.1

Type RM Length L Ch R = 1,7515,483,483,483
BEGIN DESCRIPTION:
Mapping XS 607995cb
END DESCRIPTION:
XS GIS Cut Line= 4
      2078809.41     13440228.03      2077701.34     13439221.29
      2077436.58     13439048.76      2076639.59     13439472.61
#Sta/Elev= 30
  3343.0  365.07  3475.6  361.09  3560.8  359.54  3581.7  358.65  3744.6  356.14
  3772.9  355.12  3872.3  354.27  3921.6  352.83  3964.2  353.02  4049.4  351.90
  4183.8  349.91  4247.3  348.01  4367.6  345.83  4502.1  344.05  4700.1  347.52
  4806.8  348.33  4899.4  345.39  4914.5  344.24  4935.6  343.71  4989.9  340.12
  4990.4  339.32  4995.4  339.32  4995.9  340.12  5199.4  345.15  5265.4  345.74
  5391.6  348.33  5531.7  349.29  5643.9  348.84  5759.5  349.58  6058.8  349.42
#Mann=4,-1,0
  3343.0     0.1       0  4049.4    0.05       0  4989.9    0.03       0
  4995.9    0.05       0
Bank Sta=4989.9,4995.9
Exp/Cntr=0.3,0.1

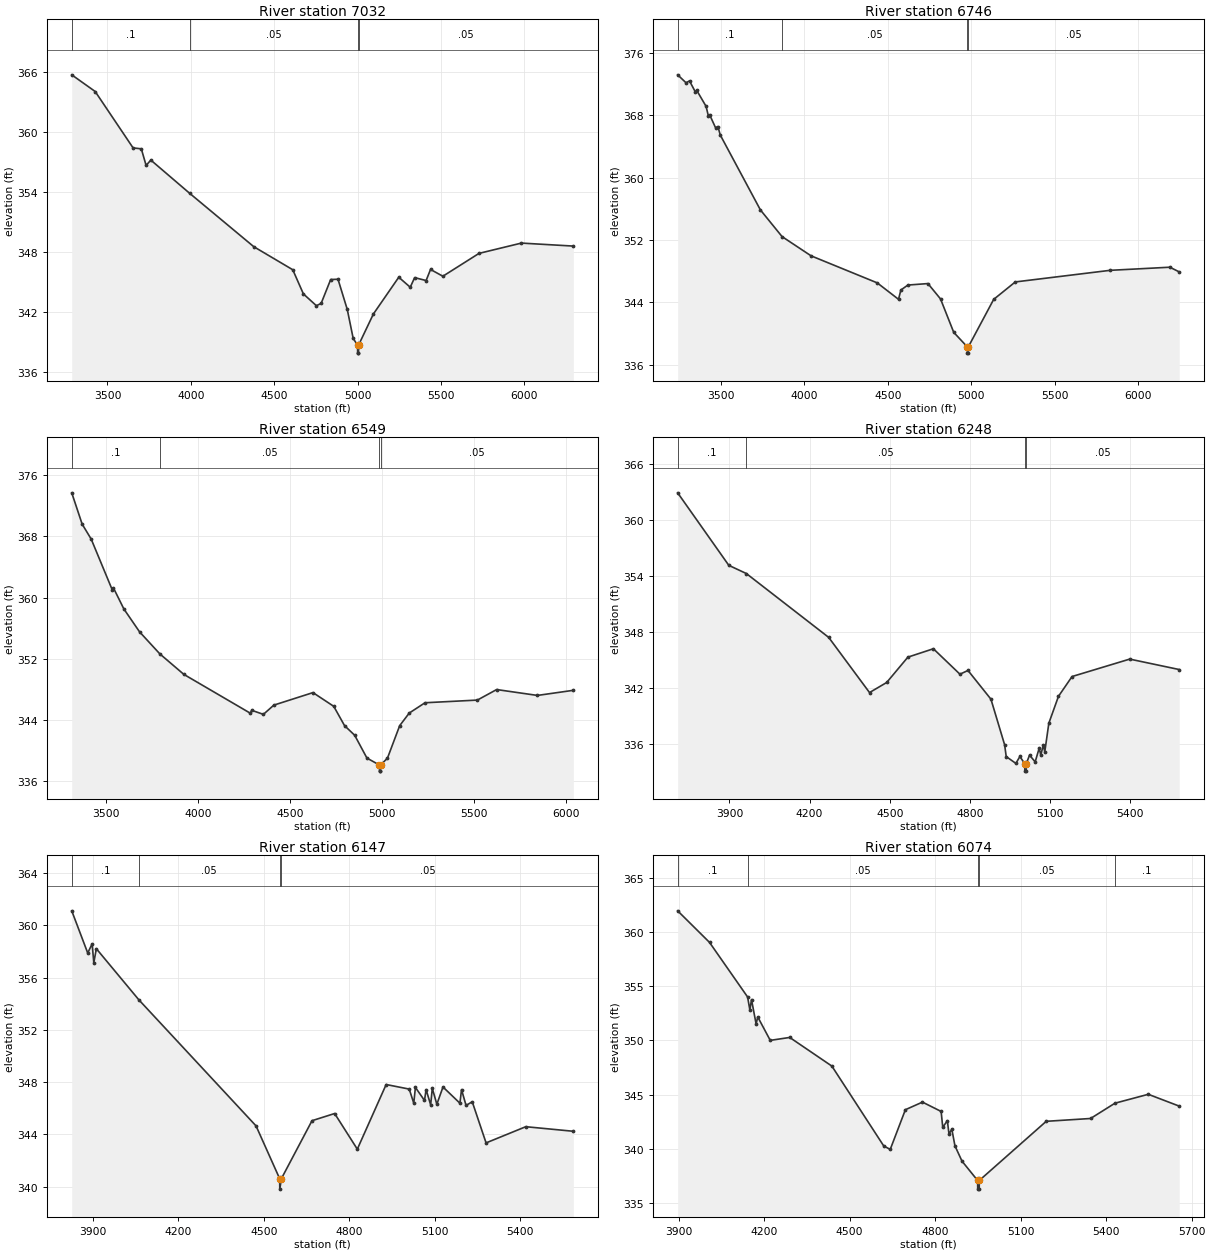
Type RM Length L Ch R = 1,7032,286,286,286
BEGIN DESCRIPTION:
Mapping XS 31aa903a
END DESCRIPTION:
XS GIS Cut Line= 4
      2079208.70     13440019.68      2077996.48     13438988.00
      2077829.38     13438761.22      2076752.07     13439116.90
#Sta/Elev= 30
  3285.8  365.75  3426.4  364.08  3653.7  358.43  3703.1  358.34  3731.7  356.68
  3760.2  357.21  3993.3  353.88  4377.4  348.54  4611.3  346.23  4675.0  343.81
  4752.9  342.63  4781.5  342.86  4838.6  345.25  4882.6  345.28  4938.2  342.25
  4973.7  339.35  4999.9  338.68  5000.4  337.88  5005.4  337.88  5005.9  338.68
  5094.8  341.80  5247.0  345.48  5315.8  344.48  5342.2  345.44  5411.0  345.15
  5437.5  346.26  5511.5  345.58  5728.4  347.87  5982.4  348.90  6293.8  348.60
#Mann=4,-1,0
  3285.8     0.1       0  3993.3    0.05       0  4999.9   0.033       0
  5005.9    0.05       0
Bank Sta=4999.9,5005.9
Exp/Cntr=0.3,0.1

Type RM Length L Ch R = 1,6746,197,197,197
BEGIN DESCRIPTION:
Mapping XS 0e32ff70
END DESCRIPTION:
XS GIS Cut Line= 4
      2079356.26     13439724.53      2078221.09     13438693.95
      2077876.04     13438576.76      2076821.55     13438925.92
#Sta/Elev= 30
  3239.7  373.21  3289.9  372.19  3310.8  372.43  3346.6  370.98  3353.4  371.24
  3410.2  369.16  3424.4  367.88  3431.1  368.10  3466.9  366.42  3481.1  366.57
  3495.3  365.48  3735.9  355.87  3865.9  352.44  4040.0  349.97  4436.7  346.50
  4564.4  344.39  4578.5  345.58  4620.5  346.22  4740.8  346.41  4816.3  344.44
  4895.5  340.15  4977.0  338.28  4977.5  337.48  4982.5  337.48  4983.0  338.28
  5135.2  344.38  5264.8  346.62  5833.6  348.11  6191.8  348.51  6248.1  347.91
#Mann=4,-1,0
  3239.7     0.1       0  3865.9    0.05       0  4977.0   0.033       0
  4983.0    0.05       0
Bank Sta=4977,4983
Exp/Cntr=0.3,0.1

Type RM Length L Ch R = 1,6549,301,301,301
BEGIN DESCRIPTION:
Mapping XS eb80c591
END DESCRIPTION:
XS GIS Cut Line= 4
      2079321.55     13439438.09      2078227.60     13438472.59
      2077905.33     13438419.42      2076988.27     13438621.70
#Sta/Elev= 30
  3313.2  373.72  3369.7  369.62  3419.0  367.65  3532.8  361.03  3539.5  361.27
  3596.4  358.50  3681.7  355.50  3791.9  352.61  3922.1  349.93  4283.2  344.84
  4290.8  345.22  4354.3  344.69  4411.2  345.90  4623.7  347.54  4736.6  345.74
  4795.2  343.21  4850.3  341.95  4916.8  338.96  4984.7  338.05  4985.2  337.25
  4990.2  337.25  4990.7  338.05  5028.3  338.95  5094.8  343.21  5146.7  344.86
  5232.4  346.21  5516.7  346.56  5621.5  347.94  5843.0  347.17  6038.0  347.84
#Mann=4,-1,0
  3313.2     0.1       0  3791.9    0.05       0  4984.7   0.033       0
  4990.7    0.05       0
Bank Sta=4984.7,4990.7
Exp/Cntr=0.3,0.1

Type RM Length L Ch R = 1,6248,101,101,101
BEGIN DESCRIPTION:
Mapping XS 92cdad5d
END DESCRIPTION:
XS GIS Cut Line= 4
      2079274.98     13439008.72      2078308.98     13438373.85
      2078150.56     13438134.05      2077990.30     13437731.00
#Sta/Elev= 30
  3706.2  362.90  3897.6  355.12  3963.3  354.24  4271.4  347.39  4424.2  341.47
  4488.4  342.55  4567.8  345.27  4663.2  346.17  4762.6  343.44  4792.7  343.84
  4878.6  340.76  4929.8  335.87  4935.8  334.60  4971.9  333.87  4987.0  334.61
  5005.0  333.84  5005.5  333.04  5010.5  333.04  5011.0  333.84  5023.1  334.76
  5044.1  334.03  5059.2  335.50  5065.2  334.77  5074.3  335.81  5080.2  335.13
  5095.3  338.18  5131.4  341.07  5182.2  343.19  5398.0  345.06  5583.3  343.94
#Mann=4,-1,0
  3706.2     0.1       0  3963.3    0.05       0  5005.0    0.03       0
  5011.0    0.05       0
Bank Sta=5005,5011
Exp/Cntr=0.3,0.1

Type RM Length L Ch R = 1,6147,73,73,73
BEGIN DESCRIPTION:
Mapping XS f21c5d30
END DESCRIPTION:
XS GIS Cut Line= 4
      2079288.93     13438918.48      2078399.04     13438380.36
      2078210.24     13438043.99      2078108.33     13437724.00
#Sta/Elev= 30
  3825.2  361.11  3881.3  357.88  3896.8  358.58  3902.7  357.14  3911.6  358.21
  4060.7  354.30  4472.5  344.64  4555.4  340.60  4555.9  339.80  4561.4  340.60
  4669.0  345.04  4748.5  345.59  4828.1  342.86  4929.4  347.81  5010.4  347.46
  5026.4  346.38  5032.1  347.59  5064.0  346.59  5069.7  347.42  5085.7  346.25
  5091.4  347.52  5107.4  346.30  5129.0  347.62  5188.4  346.38  5194.1  347.42
  5210.0  346.21  5231.7  346.49  5280.3  343.34  5419.7  344.58  5586.7  344.23
#Mann=4,-1,0
  3825.2     0.1       0  4060.7    0.05       0  4555.4    0.03       0
  4561.4    0.05       0
Bank Sta=4555.4,4561.4
Exp/Cntr=0.3,0.1

Type RM Length L Ch R = 1,6074,451,451,451
BEGIN DESCRIPTION:
Mapping XS 0f4c0c17
END DESCRIPTION:
XS GIS Cut Line= 4
      2079330.56     13438842.07      2078471.74     13438376.02
      2078333.93     13438154.67      2078200.00     13437650.01
#Sta/Elev= 30
  3896.5  361.95  4008.3  359.04  4141.9  354.01  4149.9  352.81  4155.6  353.77
  4171.8  351.52  4177.5  352.17  4221.4  350.01  4289.7  350.28  4437.6  347.64
  4619.6  340.28  4642.4  339.96  4695.6  343.62  4755.5  344.32  4821.0  343.46
  4826.7  342.00  4842.9  342.61  4848.6  341.37  4858.5  341.83  4869.5  340.29
  4894.2  338.88  4949.0  337.10  4949.5  336.30  4954.5  336.30  4955.0  337.10
  5189.8  342.55  5345.4  342.81  5431.0  344.22  5547.9  345.04  5656.5  343.95
#Mann=5,-1,0
  3896.5     0.1       0  4141.9    0.05       0  4949.0    0.03       0
  4955.0    0.05       0  5431.0     0.1       0
Bank Sta=4949,4955
Exp/Cntr=0.3,0.1

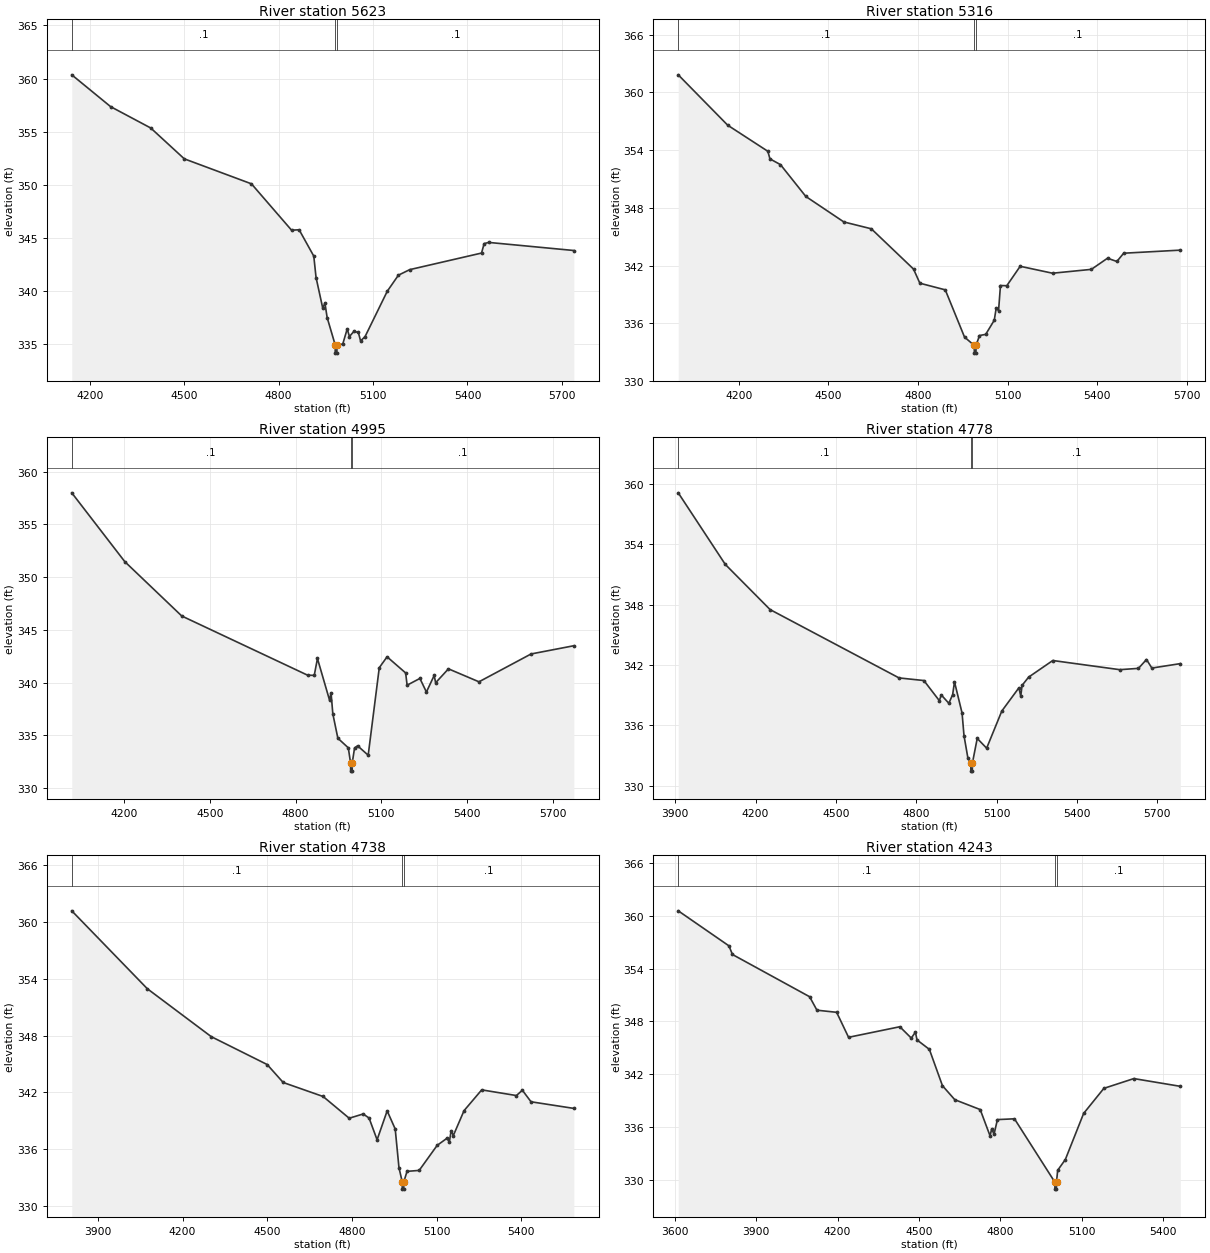
Type RM Length L Ch R = 1,5623,307,307,307
BEGIN DESCRIPTION:
Mapping XS 02fb7398
END DESCRIPTION:
XS GIS Cut Line= 4
      2079372.23     13438571.24      2078820.05     13438105.84
      2078645.35     13437926.80      2078149.98     13437549.98
#Sta/Elev= 30
  4143.1  360.35  4266.4  357.36  4393.9  355.35  4500.5  352.45  4713.8  350.10
  4841.2  345.74  4865.3  345.78  4911.8  343.30  4919.0  341.29  4940.1  338.43
  4947.2  338.88  4954.2  337.53  4979.5  334.98  4980.0  334.18  4985.1  334.18
  4985.6  334.98  5003.8  335.03  5018.0  336.46  5025.0  335.74  5039.1  336.22
  5053.3  336.13  5060.4  335.33  5074.6  335.73  5145.2  340.00  5180.6  341.51
  5216.4  342.03  5444.6  343.59  5452.9  344.48  5467.4  344.59  5737.8  343.83
#Mann=3,-1,0
  4143.1     0.1       0  4979.5    0.07       0  4985.6     0.1       0
Bank Sta=4979.5,4985.6
Exp/Cntr=0.3,0.1

Type RM Length L Ch R = 1,5316,321,321,321
BEGIN DESCRIPTION:
Mapping XS 094a0e5a
END DESCRIPTION:
XS GIS Cut Line= 4
      2079531.95     13438432.35      2078952.42     13437851.93
      2078727.81     13437669.64      2078199.97     13437449.99
#Sta/Elev= 30
  3997.4  361.83  4163.1  356.59  4297.4  353.88  4304.5  353.09  4339.8  352.49
  4424.7  349.18  4552.0  346.53  4643.9  345.82  4785.3  341.63  4806.5  340.16
  4891.6  339.47  4956.0  334.56  4988.6  333.69  4989.1  332.89  4994.2  332.89
  4994.7  333.69  5006.1  334.72  5026.9  334.84  5055.6  336.31  5062.1  337.57
  5070.0  337.31  5076.4  339.92  5097.6  339.90  5142.4  341.92  5250.7  341.20
  5380.7  341.60  5434.9  342.76  5466.1  342.42  5489.0  343.28  5678.6  343.60
#Mann=3,-1,0
  3997.4     0.1       0  4988.6    0.07       0  4994.7     0.1       0
Bank Sta=4988.6,4994.7
Exp/Cntr=0.3,0.1

Type RM Length L Ch R = 1,4995,217,217,217
BEGIN DESCRIPTION:
Mapping XS 8e70a7c7
END DESCRIPTION:
XS GIS Cut Line= 4
      2079629.15     13438258.70      2079157.50     13437595.86
      2078889.49     13437484.09      2078250.00     13437350.00
#Sta/Elev= 30
  4016.7  358.00  4202.1  351.48  4401.7  346.32  4841.9  340.71  4865.4  340.69
  4876.6  342.29  4918.8  338.35  4924.2  339.04  4930.4  337.05  4948.0  334.73
  4984.6  333.82  4992.4  332.41  4992.9  331.61  4998.0  331.61  4998.5  332.41
  5006.5  333.81  5017.1  334.01  5054.2  333.12  5093.0  341.42  5120.3  342.45
  5185.3  340.92  5190.4  339.76  5235.2  340.40  5258.0  339.11  5285.1  340.68
  5290.3  339.99  5335.1  341.31  5441.9  340.08  5624.3  342.72  5774.0  343.50
#Mann=3,-1,0
  4016.7     0.1       0  4992.4    0.07       0  4998.5     0.1       0
Bank Sta=4992.4,4998.5
Exp/Cntr=0.3,0.1

Type RM Length L Ch R = 1,4778,40,40,40
BEGIN DESCRIPTION:
Mapping XS 3459e049
END DESCRIPTION:
XS GIS Cut Line= 4
      2079705.58     13438210.16      2079167.27     13437421.16
      2078928.55     13437193.30      2078338.78     13437175.44
#Sta/Elev= 30
  3911.1  359.11  4086.8  352.00  4254.2  347.51  4735.8  340.72  4828.6  340.46
  4886.3  338.46  4893.5  339.03  4921.8  338.20  4936.0  339.06  4942.9  340.33
  4971.2  337.23  4978.4  334.99  4992.6  332.81  5003.7  332.26  5004.2  331.46
  5009.3  331.46  5009.8  332.26  5027.8  334.71  5063.0  333.74  5119.6  337.43
  5183.5  339.74  5190.4  338.91  5195.3  339.98  5219.8  340.80  5310.0  342.45
  5560.0  341.54  5630.0  341.67  5660.0  342.55  5680.0  341.70  5786.3  342.14
#Mann=3,-1,0
  3911.1     0.1       0  5003.7    0.07       0  5009.8     0.1       0
Bank Sta=5003.7,5009.8
Exp/Cntr=0.3,0.1

Type RM Length L Ch R = 1,4738,495,495,495
BEGIN DESCRIPTION:
Mapping XS 31573012
END DESCRIPTION:
XS GIS Cut Line= 4
      2079955.57     13438092.08      2079108.67     13437330.01
      2078948.08     13437137.96      2078741.10     13436808.64
#Sta/Elev= 30
  3807.3  361.20  4074.9  352.96  4301.4  347.89  4499.5  344.94  4556.3  343.04
  4697.6  341.56  4790.1  339.26  4839.6  339.71  4860.5  339.28  4888.9  336.98
  4924.6  340.04  4953.1  338.12  4966.4  334.03  4977.7  332.56  4978.2  331.76
  4983.3  331.76  4983.8  332.56  4995.0  333.64  5038.0  333.74  5101.7  336.39
  5136.9  337.15  5144.7  336.72  5151.2  337.94  5159.0  337.43  5196.9  340.06
  5259.5  342.26  5382.4  341.66  5403.6  342.22  5434.2  341.00  5585.9  340.30
#Mann=3,-1,0
  3807.3     0.1       0  4977.7    0.07       0  4983.8     0.1       0
Bank Sta=4977.7,4983.8
Exp/Cntr=0.3,0.1

Type RM Length L Ch R = 1,4243,180,180,180
BEGIN DESCRIPTION:
Mapping XS 67100f87
END DESCRIPTION:
XS GIS Cut Line= 4
      2080045.85     13438001.80      2079374.52     13436964.35
      2079197.65     13436774.46      2078844.41     13436744.84
#Sta/Elev= 30
  3613.2  360.56  3800.0  356.58  3812.9  355.60  4097.2  350.80  4124.2  349.27
  4196.8  349.03  4240.7  346.19  4429.6  347.39  4471.8  346.10  4487.0  346.78
  4492.9  345.89  4538.4  344.82  4586.6  340.69  4632.1  339.10  4725.7  337.98
  4762.0  334.99  4768.0  335.79  4776.7  335.18  4789.1  336.84  4851.9  336.93
  5000.6  329.74  5001.1  328.94  5006.3  328.94  5006.8  329.74  5011.1  331.08
  5039.3  332.30  5106.7  337.54  5181.3  340.39  5291.7  341.50  5462.9  340.62
#Mann=3,-1,0
  3613.2     0.1       0  5000.6    0.07       0  5006.8     0.1       0
Bank Sta=5000.6,5006.8
Exp/Cntr=0.3,0.1