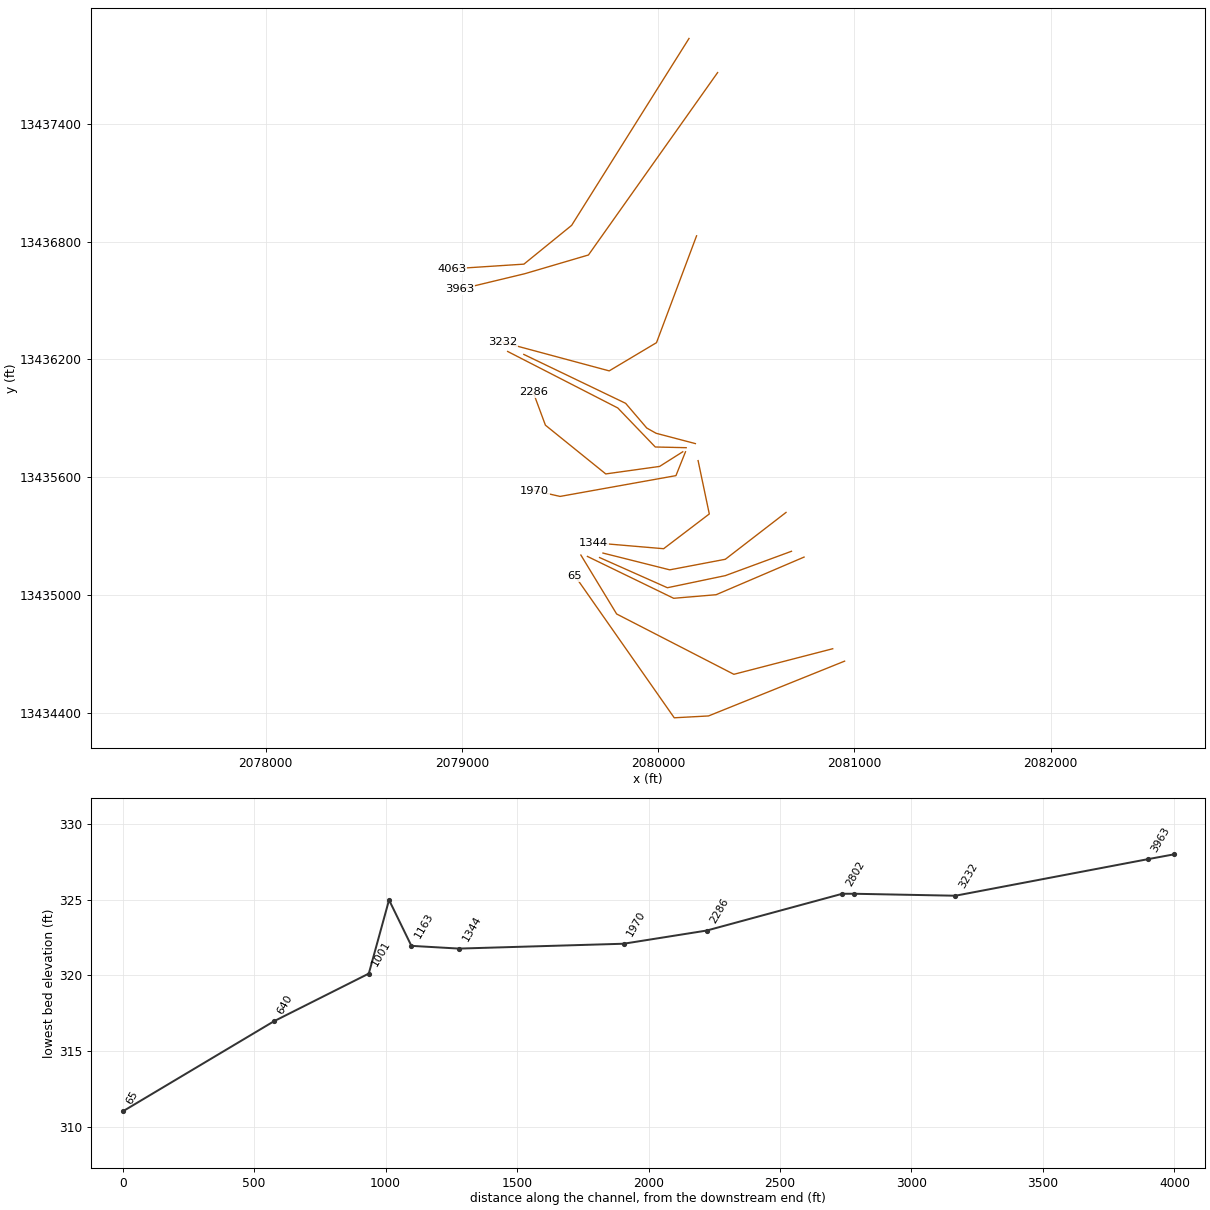
HEC-RAS study UNT 35 in Lagunillas Cr Wtrshd.prj: UNT 35 in Lagunillas Cr Wtrshd Base Level Engineering

--- UNT 35 in Lagunillas Cr Wtrshd.g01 (geometry) --- (continued)

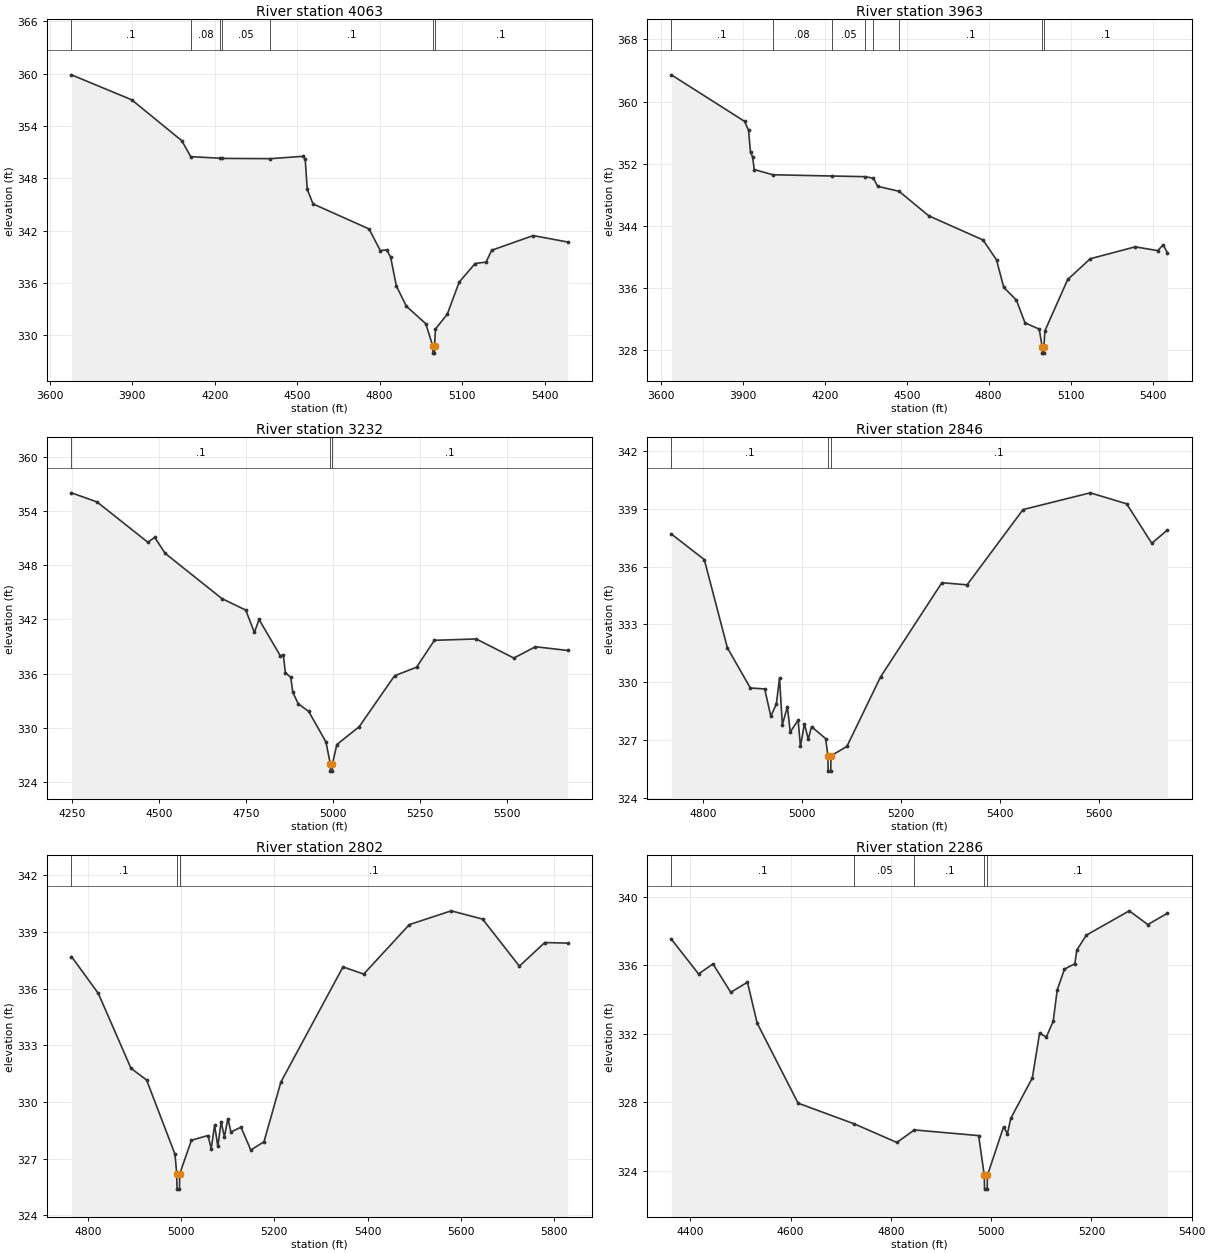
Type RM Length L Ch R = 1,4063,100,100,100
BEGIN DESCRIPTION:
Mapping XS 9dc88968
END DESCRIPTION:
XS GIS Cut Line= 4
      2080156.95     13437835.13      2079558.98     13436882.97
      2079315.92     13436685.48      2078949.34     13436661.56
#Sta/Elev= 30
  3679.0  359.85  3898.3  356.99  4080.6  352.30  4112.8  350.48  4220.0  350.30
  4226.9  350.28  4403.1  350.25  4521.4  350.52  4529.4  350.22  4536.7  346.75
  4557.9  345.07  4761.7  342.20  4802.4  339.73  4825.9  339.80  4840.2  338.97
  4861.1  335.66  4897.7  333.34  4968.1  331.35  4993.7  328.78  4994.2  327.98
  4999.4  327.98  4999.9  328.78  5003.3  330.74  5046.4  332.45  5089.5  336.11
  5147.5  338.24  5187.6  338.41  5207.7  339.76  5358.6  341.44  5483.9  340.71
#Mann=7,-1,0
  3679.0     0.1       0  4112.8    0.08       0  4220.0     0.1       0
  4226.9    0.05       0  4403.1     0.1       0  4993.7    0.07       0
  4999.9     0.1       0
Bank Sta=4993.7,4999.9
Exp/Cntr=0.3,0.1

Type RM Length L Ch R = 1,3963,731,731,731
BEGIN DESCRIPTION:
Mapping XS 4d87942e
END DESCRIPTION:
XS GIS Cut Line= 4
      2080302.76     13437661.48      2079644.70     13436732.14
      2079320.26     13436636.66      2078990.28     13436557.35
#Sta/Elev= 30
  3638.3  363.45  3906.2  357.47  3920.9  356.32  3928.1  353.47  3935.7  352.90
  3941.8  351.27  4009.3  350.60  4225.0  350.44  4348.6  350.35  4378.2  350.15
  4393.7  349.11  4472.2  348.47  4580.6  345.32  4779.5  342.21  4828.8  339.65
  4855.2  336.12  4901.8  334.47  4933.1  331.55  4985.2  330.75  4995.9  328.46
  4996.4  327.66  5001.6  327.66  5002.1  328.46  5006.0  330.53  5089.4  337.13
  5172.1  339.80  5336.6  341.33  5418.9  340.84  5438.8  341.58  5454.6  340.58
#Mann=8,-1,0
  3638.3     0.1       0  4009.3    0.08       0  4225.0    0.05       0
  4348.6     0.1       0  4378.2    0.05       0  4472.2     0.1       0
  4995.9    0.07       0  5002.1     0.1       0
Bank Sta=4995.9,5002.1
Exp/Cntr=0.3,0.1

Type RM Length L Ch R = 1,3232,386,386,386
BEGIN DESCRIPTION:
Mapping XS cb44d028
END DESCRIPTION:
XS GIS Cut Line= 4
      2080195.50     13436829.77      2079991.36     13436285.44
      2079750.38     13436141.69      2079205.87     13436288.08
#Sta/Elev= 30
  4249.2  355.99  4322.8  354.98  4468.7  350.53  4488.3  351.07  4518.6  349.30
  4681.5  344.31  4750.0  343.04  4774.9  340.57  4788.3  342.00  4849.6  337.98
  4858.1  338.10  4863.9  336.14  4879.5  335.60  4885.3  333.97  4900.9  332.69
  4931.1  331.84  4980.7  328.47  4993.1  326.05  4993.6  325.25  4998.8  325.25
  4999.3  326.05  5011.8  328.19  5076.0  330.15  5177.7  335.78  5241.0  336.73
  5292.4  339.70  5412.3  339.85  5520.6  337.74  5582.7  338.99  5675.0  338.58
#Mann=3,-1,0
  4249.2     0.1       0  4993.1    0.07       0  4999.3     0.1       0
Bank Sta=4993.1,4999.3
Exp/Cntr=0.3,0.1

Type RM Length L Ch R = 1,2846,44,44,44
BEGIN DESCRIPTION:
Mapping XS 05177a26
END DESCRIPTION:
XS GIS Cut Line= 5
      2080189.39     13435771.21      2079989.27     13435823.81
      2079941.88     13435850.37      2079834.06     13435976.41
      2079315.30     13436225.56
#Sta/Elev= 30
  4736.6  337.70  4803.2  336.37  4849.8  331.79  4896.2  329.70  4925.3  329.65
  4937.6  328.23  4948.8  328.87  4955.2  330.23  4960.9  327.79  4971.1  328.73
  4976.9  327.41  4992.8  328.03  4997.5  326.66  5005.6  327.84  5013.3  327.04
  5019.9  327.69  5048.4  327.07  5053.0  326.18  5053.5  325.38  5058.7  325.38
  5059.2  326.18  5091.3  326.66  5159.5  330.28  5283.3  335.17  5334.2  335.06
  5447.4  338.97  5583.2  339.84  5656.7  339.27  5707.5  337.22  5739.2  337.91
#Mann=3,-1,0
  4736.6     0.1       0  5053.0    0.07       0  5059.2     0.1       0
Bank Sta=5053,5059.2
Exp/Cntr=0.3,0.1

Type RM Length L Ch R = 1,2802,516,516,516
BEGIN DESCRIPTION:
Mapping XS 1a00b2b7
END DESCRIPTION:
XS GIS Cut Line= 4
      2080142.53     13435750.38      2079985.15     13435753.93
      2079794.18     13435952.71      2079233.10     13436240.60
#Sta/Elev= 30
  4765.2  337.70  4822.7  335.75  4892.8  331.78  4926.3  331.16  4987.1  327.23
  4991.0  326.18  4991.5  325.38  4996.7  325.38  4997.2  326.18  5022.4  327.97
  5057.9  328.22  5064.8  327.53  5072.1  328.77  5079.0  327.65  5086.2  328.95
  5093.1  328.14  5100.4  329.11  5107.3  328.41  5128.7  328.66  5149.7  327.45
  5178.0  327.89  5214.2  331.05  5347.4  337.15  5391.8  336.77  5489.6  339.39
  5579.5  340.12  5646.8  339.68  5725.6  337.19  5780.0  338.44  5828.9  338.41
#Mann=3,-1,0
  4765.2     0.1       0  4991.0    0.07       0  4997.2     0.1       0
Bank Sta=4991,4997.2
Exp/Cntr=0.3,0.1

Type RM Length L Ch R = 1,2286,316,316,316
BEGIN DESCRIPTION:
Mapping XS 3eba8627
END DESCRIPTION:
XS GIS Cut Line= 5
      2080125.12     13435729.53      2080007.09     13435654.89
      2079732.78     13435616.70      2079425.49     13435864.96
      2079363.61     13436031.71
#Sta/Elev= 30
  4362.2  337.52  4416.5  335.49  4445.2  336.08  4480.7  334.42  4514.0  335.01
  4533.3  332.63  4615.0  327.96  4727.4  326.75  4812.0  325.67  4846.8  326.40
  4975.1  326.07  4986.4  323.75  4986.9  322.95  4992.1  322.95  4992.6  323.75
  5024.7  326.57  5032.6  326.19  5039.1  327.07  5082.2  329.43  5096.6  332.03
  5110.2  331.82  5123.8  332.73  5131.8  334.55  5146.2  335.77  5167.0  336.09
  5170.9  336.88  5189.8  337.75  5275.5  339.17  5312.5  338.37  5351.7  339.03
#Mann=5,-1,0
  4362.2     0.1       0  4727.4    0.05       0  4846.8     0.1       0
  4986.4    0.07       0  4992.6     0.1       0
Bank Sta=4986.4,4992.6
Exp/Cntr=0.3,0.1

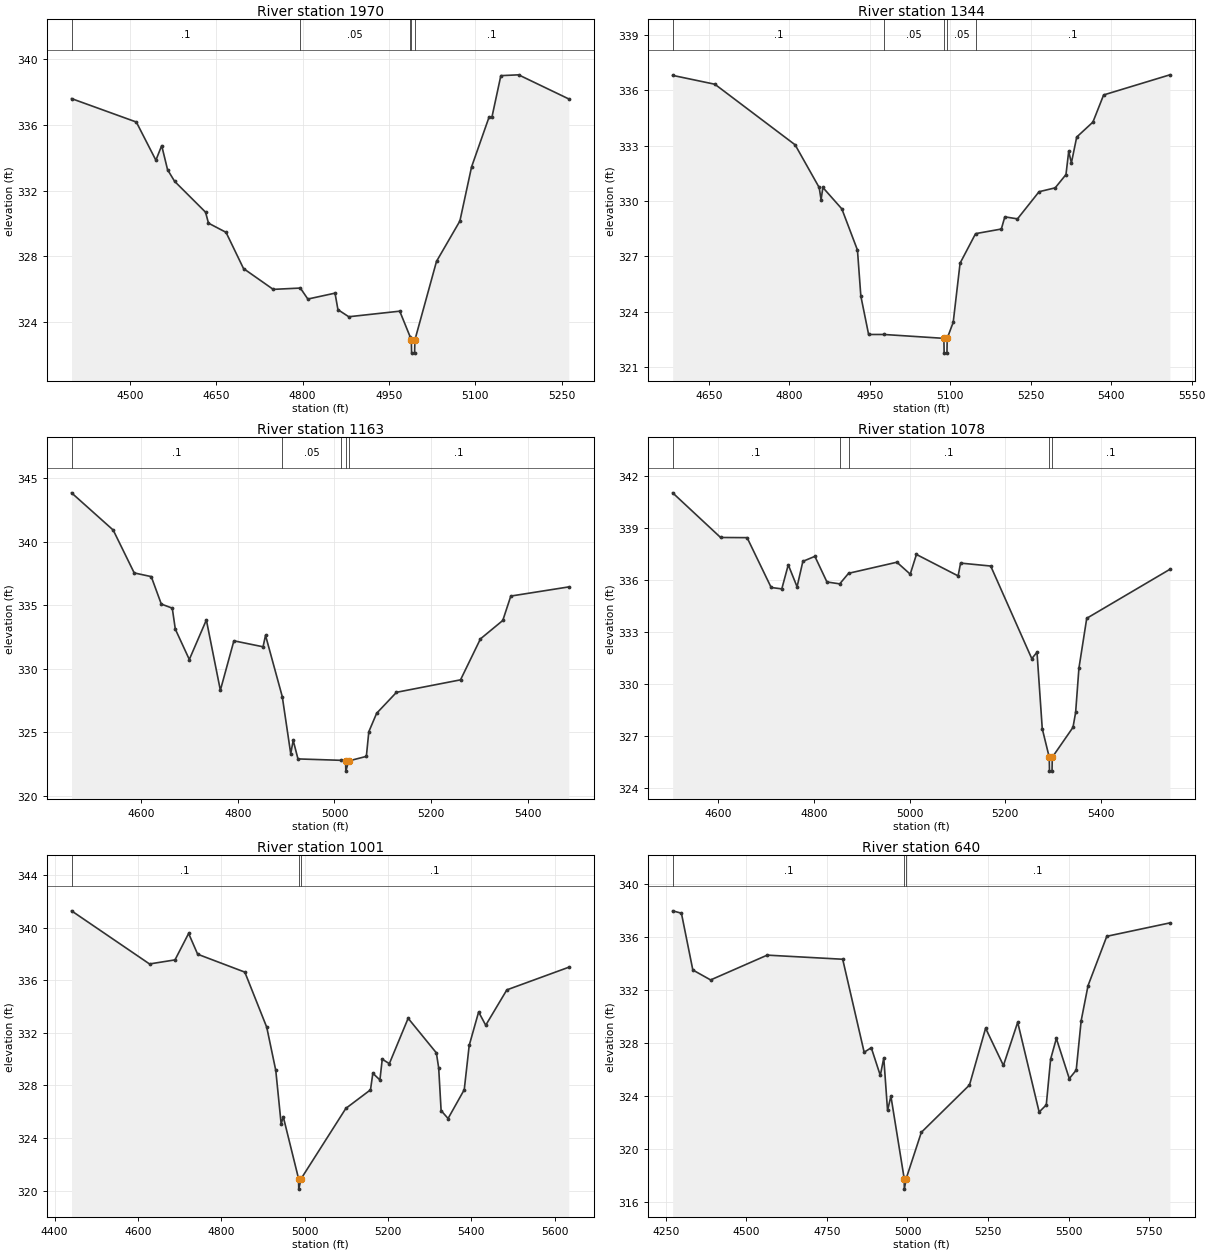
Type RM Length L Ch R = 1,1970,626,626,626
BEGIN DESCRIPTION:
Mapping XS 297ecc24
END DESCRIPTION:
XS GIS Cut Line= 4
      2080139.03     13435729.54      2080090.42     13435608.02
      2079500.14     13435502.12      2079369.94     13435531.63
#Sta/Elev= 30
  4398.4  337.61  4511.0  336.18  4545.0  333.85  4555.1  334.74  4565.3  333.27
  4577.6  332.56  4631.3  330.68  4636.4  330.01  4666.9  329.45  4697.3  327.24
  4748.9  325.97  4796.0  326.05  4809.1  325.38  4856.3  325.74  4861.4  324.73
  4880.2  324.30  4968.8  324.64  4986.7  323.09  4988.9  322.88  4989.4  322.08
  4994.6  322.08  4995.1  322.88  5032.7  327.68  5073.3  330.14  5093.6  333.44
  5124.0  336.48  5129.0  336.48  5144.5  339.01  5175.3  339.06  5262.5  337.59
#Mann=5,-1,0
  4398.4     0.1       0  4796.0    0.05       0  4986.7     0.1       0
  4988.9    0.07       0  4995.1     0.1       0
Bank Sta=4988.9,4995.1
Exp/Cntr=0.3,0.1

Type RM Length L Ch R = 1,1344,181,181,181
BEGIN DESCRIPTION:
Mapping XS 59cdcac6
END DESCRIPTION:
XS GIS Cut Line= 4
      2080203.27     13435684.39      2080260.32     13435412.78
      2080027.68     13435235.70      2079671.98     13435266.01
#Sta/Elev= 30
  4582.5  336.80  4661.2  336.32  4810.8  333.04  4855.6  330.73  4859.2  330.07
  4862.5  330.73  4897.9  329.57  4927.0  327.34  4933.3  324.85  4947.8  322.77
  4976.4  322.77  5088.1  322.56  5088.6  321.76  5093.8  321.76  5094.3  322.56
  5105.5  323.43  5118.3  326.63  5147.2  328.23  5195.2  328.48  5201.7  329.14
  5225.3  329.03  5265.5  330.50  5295.6  330.71  5315.7  331.43  5320.8  332.69
  5325.8  332.06  5335.7  333.46  5365.9  334.27  5385.9  335.74  5509.4  336.83
#Mann=5,-1,0
  4582.5     0.1       0  4976.4    0.05       0  5088.1   0.033       0
  5094.3    0.05       0  5147.2     0.1       0
Bank Sta=5088.1,5094.3
Exp/Cntr=0.3,0.1

Type RM Length L Ch R = 1,1163,85,85,85
BEGIN DESCRIPTION:
Mapping XS e6918a0e
END DESCRIPTION:
XS GIS Cut Line= 4
      2080651.17     13435420.50      2080341.92     13435181.88
      2080058.93     13435128.06      2079718.58     13435213.57
#Sta/Elev= 30
  4455.5  343.83  4541.8  340.90  4585.3  337.53  4620.6  337.24  4641.4  335.08
  4664.1  334.76  4670.4  333.11  4699.4  330.72  4734.7  333.83  4763.7  328.30
  4791.7  332.19  4852.1  331.72  4857.2  332.62  4891.9  327.80  4909.4  323.31
  4914.5  324.36  4924.4  322.90  5013.7  322.79  5023.0  322.74  5023.5  321.94
  5029.3  322.74  5066.0  323.10  5071.1  325.04  5087.3  326.49  5128.4  328.14
  5261.0  329.12  5302.2  332.34  5348.5  333.79  5365.1  335.71  5485.1  336.43
#Mann=5,-1,0
  4455.5     0.1       0  4891.9    0.05       0  5013.7     0.1       0
  5023.0   0.033       0  5029.3     0.1       0
Bank Sta=5023,5029.3
Exp/Cntr=0.3,0.1

Type RM Length L Ch R = 1,1078,77,77,77
BEGIN DESCRIPTION:
Mapping XS 2a05727c
END DESCRIPTION:
XS GIS Cut Line= 4
      2080678.95     13435222.60      2080341.92     13435098.55
      2080046.78     13435036.92      2079701.39     13435190.64
#Sta/Elev= 30
  4505.0  341.05  4605.1  338.47  4660.5  338.46  4710.8  335.58  4733.0  335.50
  4746.5  336.89  4764.9  335.62  4777.0  337.09  4802.1  337.38  4827.3  335.90
  4854.0  335.79  4872.5  336.40  4973.4  337.04  5001.3  336.35  5014.2  337.49
  5101.3  336.25  5106.5  336.99  5169.4  336.82  5255.2  331.47  5266.1  331.84
  5277.1  327.42  5291.7  325.77  5292.2  324.97  5297.5  324.97  5298.0  325.77
  5341.3  327.50  5346.8  328.36  5353.7  330.92  5370.0  333.80  5543.7  336.63
#Mann=5,-1,0
  4505.0     0.1       0  4854.0    0.05       0  4872.5     0.1       0
  5291.7    0.07       0  5298.0     0.1       0
Bank Sta=5291.7,5298
Exp/Cntr=0.3,0.1

Type RM Length L Ch R = 1,1001,361,361,361
BEGIN DESCRIPTION:
Mapping XS a06c1039
END DESCRIPTION:
XS GIS Cut Line= 4
      2080743.21     13435193.09      2080295.05     13435001.33
      2080078.90     13434983.10      2079639.49     13435196.34
#Sta/Elev= 30
  4440.7  341.27  4627.8  337.23  4688.9  337.54  4721.6  339.55  4743.3  337.97
  4856.4  336.61  4909.0  332.42  4930.7  329.13  4943.6  325.06  4948.6  325.62
  4985.3  320.91  4985.8  320.11  4991.6  320.91  5098.8  326.25  5157.9  327.66
  5163.5  328.92  5180.5  328.41  5186.1  329.99  5203.1  329.65  5248.2  333.10
  5315.9  330.47  5321.5  329.32  5327.3  326.08  5344.0  325.48  5382.8  327.67
  5394.7  331.04  5417.3  333.58  5434.3  332.57  5485.0  335.26  5633.5  336.98
#Mann=3,-1,0
  4440.7     0.1       0  4985.3    0.07       0  4991.6     0.1       0
Bank Sta=4985.3,4991.6
Exp/Cntr=0.3,0.1

Type RM Length L Ch R = 1,640,575,575,575
BEGIN DESCRIPTION:
Mapping XS f23f5d21
END DESCRIPTION:
XS GIS Cut Line= 4
      2080889.08     13434726.09      2080385.56     13434595.87
      2079788.34     13434903.16      2079606.03     13435203.53
#Sta/Elev= 30
  4271.3  337.94  4298.5  337.76  4333.9  333.48  4389.1  332.73  4564.7  334.60
  4799.0  334.29  4865.6  327.28  4887.7  327.62  4915.7  325.53  4926.5  326.85
  4938.2  322.89  4948.6  323.97  4989.8  317.76  4990.3  316.96  4996.1  317.76
  5043.0  321.24  5192.5  324.81  5242.5  329.09  5297.8  326.28  5342.1  329.54
  5408.7  322.77  5430.8  323.31  5444.3  326.76  5462.1  328.32  5502.2  325.29
  5523.7  325.93  5539.1  329.66  5560.4  332.30  5618.6  336.02  5814.4  337.03
#Mann=3,-1,0
  4271.3     0.1       0  4989.8    0.07       0  4996.1     0.1       0
Bank Sta=4989.8,4996.1
Exp/Cntr=0.3,0.1

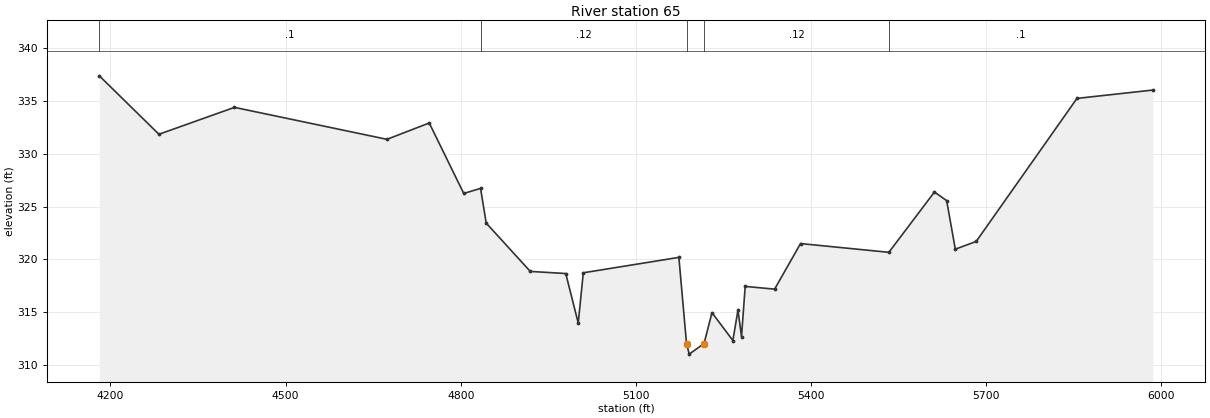
Type RM Length L Ch R = 1,65,0,0,0
BEGIN DESCRIPTION:
UNT 35 in Lagunillas Cr Wtrshd 1.0
END DESCRIPTION:
XS GIS Cut Line= 4
      2080949.74     13434662.96      2080256.47     13434383.71
      2080081.72     13434374.34      2079576.07     13435097.01
#Sta/Elev= 30
  4181.0  337.39  4283.1  331.85  4412.5  334.40  4673.7  331.37  4746.1  332.92
  4805.2  326.24  4834.0  326.72  4843.7  323.43  4919.2  318.85  4979.9  318.65
  5001.3  313.96  5010.0  318.72  5173.7  320.18  5186.8  312.01  5191.4  311.01
  5216.8  312.01  5230.4  314.94  5266.2  312.30  5274.9  315.18  5281.0  312.68
  5287.3  317.43  5337.7  317.17  5382.1  321.49  5533.4  320.66  5611.5  326.38
  5632.4  325.56  5647.2  320.96  5683.0  321.69  5855.6  335.25  5985.4  336.04
#Mann=5,-1,0
  4181.0     0.1       0  4834.0    0.12       0  5186.8    0.07       0
  5216.8    0.12       0  5533.4     0.1       0
Bank Sta=5186.8,5216.8
Exp/Cntr=0.3,0.1

Chan Stop Cuts=-1