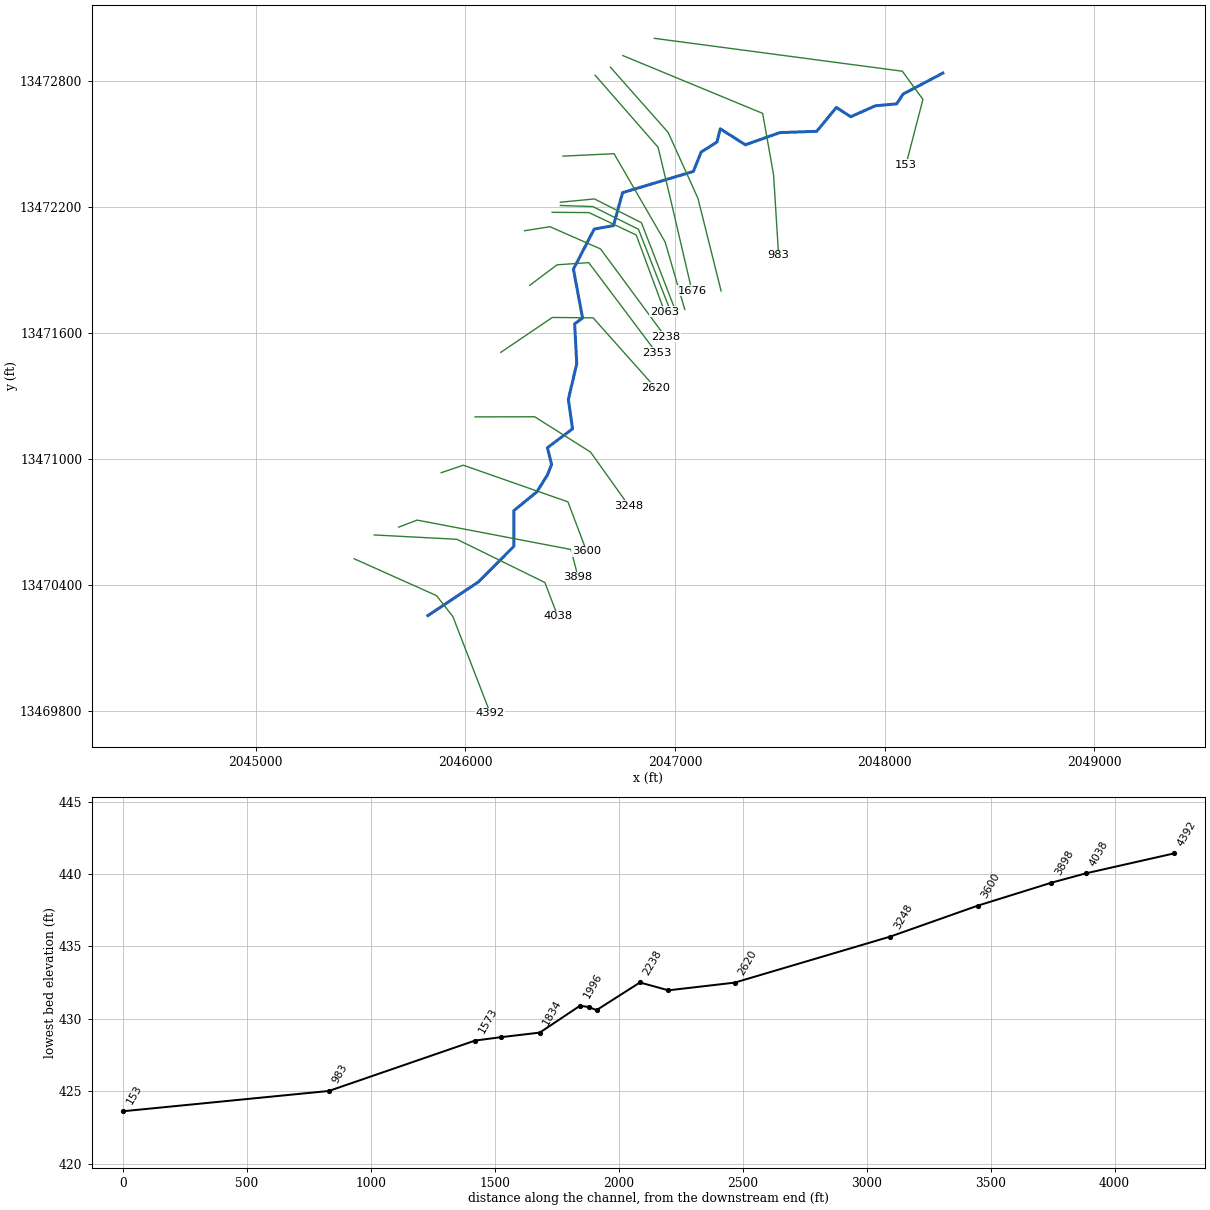
--- UNT 40 in Lagunillas Cr Wtrshd.prj (project) ---

Proj Title=UNT 40 in Lagunillas Cr Wtrshd Base Level Engineering
Current Plan=p01
Default Exp/Contr=0.3,0.1
English Units
Geom File=g01
Flow File=f01
Plan File=p01
BEGIN DESCRIPTION:
UNT 40 in Lagunillas Cr Wtrshd
END DESCRIPTION:

--- UNT 40 in Lagunillas Cr Wtrshd.p01 (plan) ---

Plan Title=Multiple Run
Short Identifier=Multiple
Geom File=g01
Flow File=f01
Subcritical Flow
K Sum by GR= 0
Std Step Tol= 0.01
Critical Tol= 0.01
Num of Std Step Trials= 20
Max Error Tol= 0.3
Flow Tol Ratio= 0.001
Split Flow NTrial= 30
Split Flow Tol= 0.02
Split Flow Ratio= 0.02
Log Output Level= 0
Friction Slope Method= 1
Unsteady Friction Slope Method= 2
Unsteady Bridges Friction Slope Method= 1
Parabolic Critical Depth
Global Vel Dist=  1 , 1 , 1
Global Log Level= 0
CheckData=True
Encroach Param= -1, 0, 0, 0
BEGIN DESCRIPTION:
Multiple Run
END DESCRIPTION:

--- UNT 40 in Lagunillas Cr Wtrshd.f01 (steady flow) ---

Flow Title=Multiple
Number of Profiles=7
Profile Names=10-year,25-year,50-year,1pct_min,100-year,1pct_plu,500-year
River Rch & RM= UNT 40 in Laguni,Reach-1,4392
     225     312     385     237     472     942     722
River Rch & RM= UNT 40 in Laguni,Reach-1,2353
     225     312     383     235     470     938     716
Boundary for River Rch & Prof#=UNT 40 in Laguni,Reach-1,1
Up Type=0
Dn Type=3
Dn Slope=0.005
Boundary for River Rch & Prof#=UNT 40 in Laguni,Reach-1,2
Up Type=0
Dn Type=3
Dn Slope=0.005
Boundary for River Rch & Prof#=UNT 40 in Laguni,Reach-1,3
Up Type=0
Dn Type=3
Dn Slope=0.005
Boundary for River Rch & Prof#=UNT 40 in Laguni,Reach-1,4
Up Type=0
Dn Type=3
Dn Slope=0.005
Boundary for River Rch & Prof#=UNT 40 in Laguni,Reach-1,5
Up Type=0
Dn Type=3
Dn Slope=0.005
Boundary for River Rch & Prof#=UNT 40 in Laguni,Reach-1,6
Up Type=0
Dn Type=3
Dn Slope=0.005
Boundary for River Rch & Prof#=UNT 40 in Laguni,Reach-1,7
Up Type=0
Dn Type=3
Dn Slope=0.005

--- UNT 40 in Lagunillas Cr Wtrshd.g01 (geometry) ---

Geom Title=Existing Conditions

River Reach=UNT 40 in Laguni,Reach-1
Reach XY= 30
      2045820.80     13470254.54      2046060.80     13470414.54
      2046230.80     13470584.54      2046230.80     13470754.54
      2046340.80     13470844.54      2046390.80     13470924.54
      2046410.80     13470974.54      2046390.80     13471054.54
      2046510.80     13471144.54      2046490.80     13471284.54
      2046530.80     13471454.54      2046520.80     13471644.54
      2046558.63     13471672.37      2046515.01     13471905.23
      2046613.97     13472096.20      2046705.99     13472112.69
      2046749.39     13472269.81      2047086.92     13472370.65
      2047123.96     13472462.95      2047199.48     13472510.70
      2047215.10     13472574.07      2047334.89     13472497.68
      2047499.82     13472555.84      2047675.17     13472561.91
      2047768.92     13472675.63      2047837.50     13472631.36
      2047954.68     13472683.44      2048057.12     13472692.99
      2048086.63     13472739.00      2048276.63     13472839.18

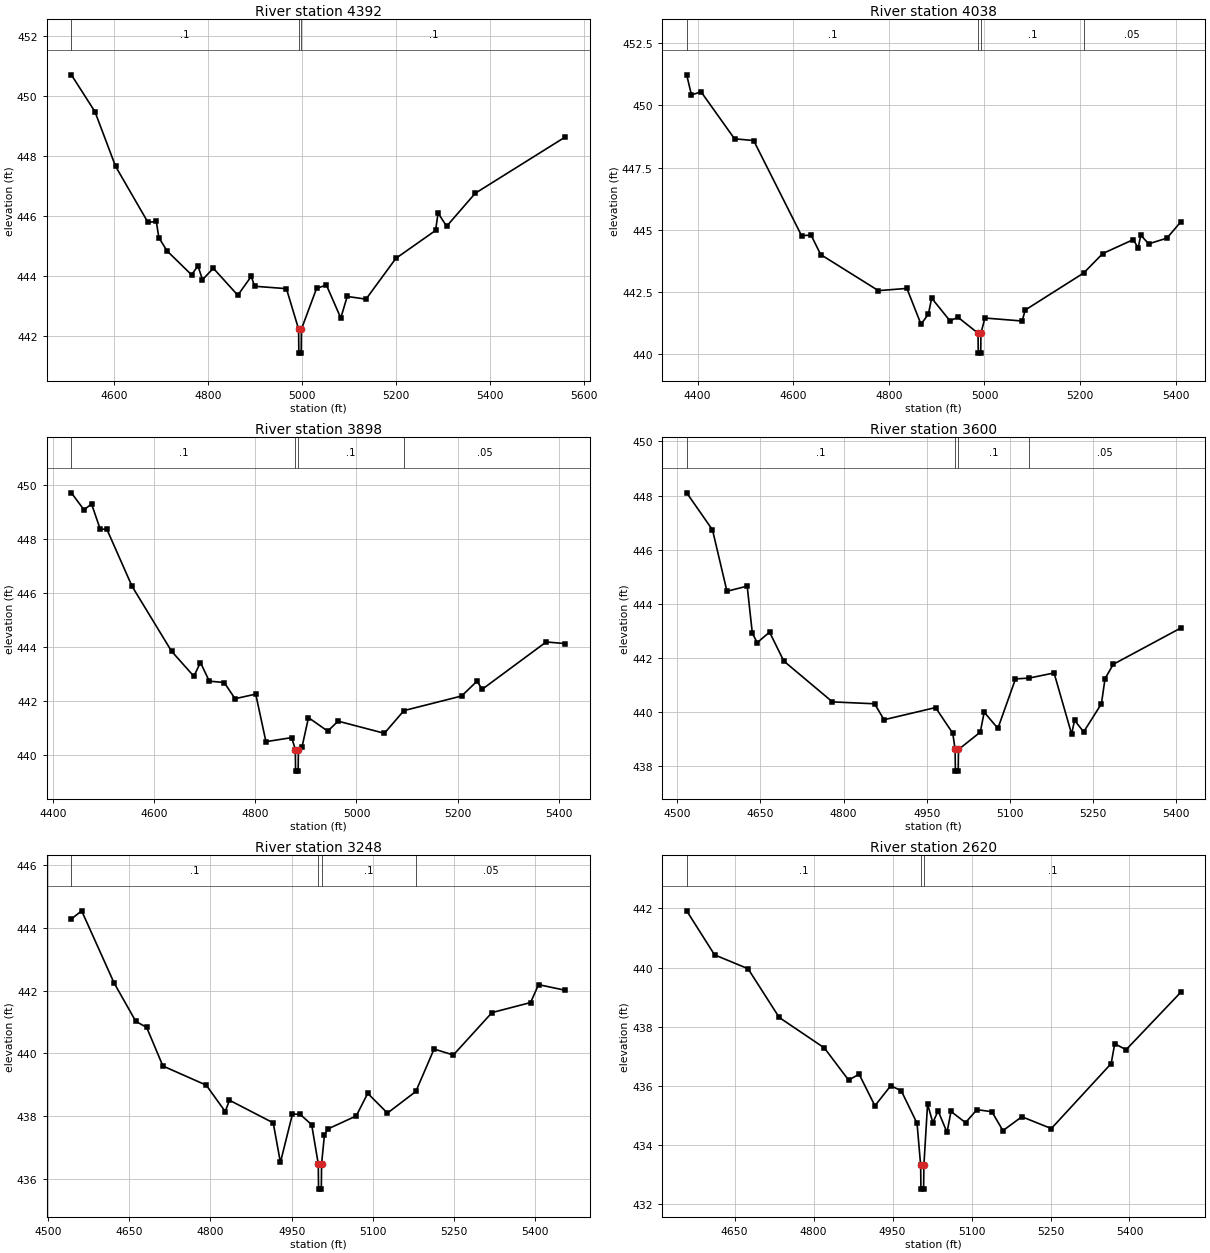
Type RM Length L Ch R = 1,4392,354,354,354
BEGIN DESCRIPTION:
UNT 40 in Lagunillas Cr Wtrshd 3.0
END DESCRIPTION:
XS GIS Cut Line= 4
      2045469.21     13470525.68      2045861.90     13470350.05
      2045940.02     13470250.22      2046118.67     13469789.37
#Sta/Elev= 30
  4509.7  450.70  4559.9  449.47  4603.7  447.65  4672.7  445.78  4690.4  445.81
  4695.9  445.27  4713.2  444.83  4765.5  444.03  4779.0  444.33  4788.7  443.87
  4811.8  444.25  4863.8  443.35  4892.5  443.98  4899.5  443.65  4967.3  443.57
  4993.2  442.22  4993.7  441.42  4998.7  441.42  4999.2  442.22  5031.5  443.58
  5052.3  443.69  5083.0  442.59  5096.6  443.31  5136.6  443.22  5200.2  444.58
  5284.6  445.51  5290.0  446.09  5308.2  445.65  5369.0  446.75  5560.9  448.63
#Mann=3,-1,0
  4509.7     0.1       0  4993.2    0.07       0  4999.2     0.1       0
Bank Sta=4993.2,4999.2
Exp/Cntr=0.3,0.1

Type RM Length L Ch R = 1,4038,140,140,140
BEGIN DESCRIPTION:
Mapping XS 9256bd75
END DESCRIPTION:
XS GIS Cut Line= 4
      2045565.05     13470639.02      2045959.60     13470618.19
      2046378.87     13470412.46      2046440.04     13470252.37
#Sta/Elev= 30
  4377.1  451.23  4387.1  450.42  4407.1  450.55  4477.2  448.66  4517.2  448.59
  4617.4  444.77  4637.4  444.79  4657.4  444.01  4778.2  442.56  4837.8  442.65
  4867.3  441.21  4882.8  441.62  4889.6  442.26  4927.8  441.35  4944.7  441.49
  4986.6  440.85  4987.1  440.05  4992.2  440.05  4992.7  440.85  5001.0  441.46
  5079.0  441.34  5085.2  441.78  5207.7  443.27  5247.5  444.05  5311.4  444.61
  5321.6  444.27  5327.0  444.79  5343.6  444.44  5381.8  444.67  5410.6  445.32
#Mann=4,-1,0
  4377.1     0.1       0  4986.6    0.07       0  4992.7     0.1       0
  5207.7    0.05       0
Bank Sta=4986.6,4992.7
Exp/Cntr=0.3,0.1

Type RM Length L Ch R = 1,3898,298,298,298
BEGIN DESCRIPTION:
Mapping XS 655625fc
END DESCRIPTION:
XS GIS Cut Line= 4
      2045681.64     13470676.15      2045769.49     13470709.77
      2046503.00     13470569.80      2046537.24     13470438.19
#Sta/Elev= 30
  4436.3  449.70  4461.3  449.07  4476.2  449.29  4493.4  448.35  4506.3  448.36
  4556.3  446.24  4634.3  443.84  4678.5  442.91  4691.5  443.42  4709.0  442.73
  4738.5  442.68  4759.9  442.08  4800.8  442.25  4821.0  440.49  4871.9  440.64
  4879.1  440.20  4879.6  439.40  4884.7  439.40  4885.2  440.20  4892.3  440.29
  4905.1  441.38  4943.2  440.88  4963.6  441.25  5055.2  440.80  5093.8  441.64
  5207.9  442.18  5238.4  442.73  5248.6  442.43  5375.1  444.18  5413.1  444.12
#Mann=4,-1,0
  4436.3     0.1       0  4879.1    0.07       0  4885.2     0.1       0
  5093.8    0.05       0
Bank Sta=4879.1,4885.2
Exp/Cntr=0.3,0.1

Type RM Length L Ch R = 1,3600,352,352,352
BEGIN DESCRIPTION:
Mapping XS 9cd643c1
END DESCRIPTION:
XS GIS Cut Line= 4
      2045884.50     13470935.46      2045989.76     13470971.27
      2046488.89     13470796.58      2046577.86     13470561.13
#Sta/Elev= 30
  4516.9  448.10  4563.5  446.73  4589.6  444.46  4626.1  444.65  4635.4  442.91
  4644.2  442.56  4666.5  442.95  4692.2  441.88  4780.0  440.37  4856.1  440.30
  4873.1  439.71  4966.1  440.16  4997.2  439.21  5001.4  438.61  5001.9  437.81
  5007.0  437.81  5007.5  438.61  5046.8  439.25  5053.9  439.99  5078.6  439.39
  5110.4  441.22  5135.0  441.25  5180.0  441.44  5211.7  439.18  5217.0  439.69
  5233.4  439.26  5265.5  440.30  5272.0  441.23  5286.9  441.76  5408.6  443.10
#Mann=4,-1,0
  4516.9     0.1       0  5001.4    0.07       0  5007.5     0.1       0
  5135.0    0.05       0
Bank Sta=5001.4,5007.5
Exp/Cntr=0.3,0.1

Type RM Length L Ch R = 1,3248,628,628,628
BEGIN DESCRIPTION:
Mapping XS 7b72da7e
END DESCRIPTION:
XS GIS Cut Line= 4
      2046046.01     13471201.47      2046330.24     13471202.04
      2046596.73     13471033.64      2046778.47     13470779.15
#Sta/Elev= 30
  4543.2  444.28  4562.2  444.54  4622.2  442.24  4662.2  441.02  4682.2  440.83
  4712.2  439.60  4792.2  438.99  4827.3  438.15  4835.1  438.51  4915.9  437.79
  4929.2  436.53  4951.4  438.07  4965.7  438.06  4986.9  437.73  4999.1  436.48
  4999.6  435.68  5004.7  435.68  5005.2  436.48  5010.5  437.41  5017.4  437.60
  5069.2  438.01  5090.4  438.73  5126.8  438.10  5179.3  438.79  5212.9  440.14
  5248.5  439.95  5319.8  441.30  5391.1  441.62  5405.8  442.19  5455.4  442.01
#Mann=4,-1,0
  4543.2     0.1       0  4999.1    0.07       0  5005.2     0.1       0
  5179.3    0.05       0
Bank Sta=4999.1,5005.2
Exp/Cntr=0.3,0.1

Type RM Length L Ch R = 1,2620,267,267,267
BEGIN DESCRIPTION:
Mapping XS 1f87a097
END DESCRIPTION:
XS GIS Cut Line= 4
      2046168.41     13471508.76      2046414.44     13471675.13
      2046608.89     13471673.40      2046906.44     13471339.77
#Sta/Elev= 30
  4558.8  441.92  4611.8  440.43  4675.4  439.96  4734.6  438.31  4820.3  437.28
  4866.4  436.19  4886.4  436.39  4916.4  435.32  4946.4  436.00  4966.4  435.83
  4996.4  434.73  5003.3  433.30  5003.8  432.50  5008.9  432.50  5009.4  433.30
  5016.4  435.38  5026.4  434.75  5036.4  435.15  5053.4  434.42  5060.9  435.13
  5088.5  434.75  5110.2  435.19  5138.6  435.12  5159.6  434.48  5195.5  434.95
  5251.5  434.55  5365.2  436.75  5371.9  437.42  5393.6  437.22  5497.3  439.16
#Mann=3,-1,0
  4558.8     0.1       0  5003.3    0.07       0  5009.4     0.1       0
Bank Sta=5003.3,5009.4
Exp/Cntr=0.3,0.1

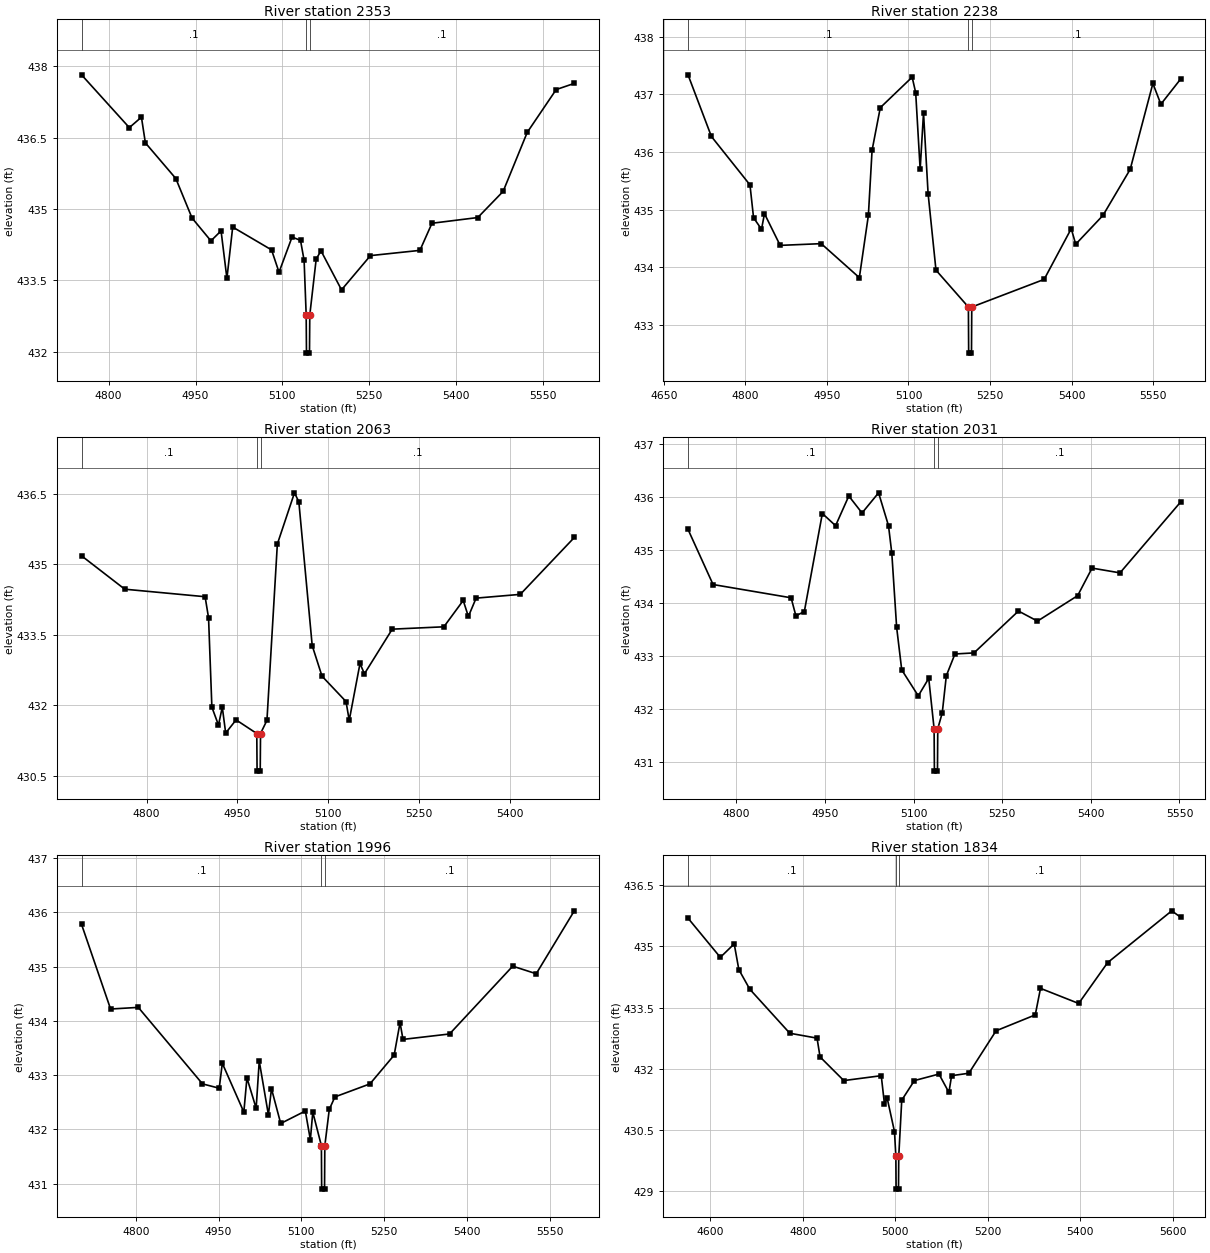
Type RM Length L Ch R = 1,2353,115,115,115
BEGIN DESCRIPTION:
Mapping XS b2c663c5
END DESCRIPTION:
XS GIS Cut Line= 4
      2046306.81     13471828.35      2046437.01     13471926.00
      2046588.05     13471936.42      2046910.63     13471507.42
#Sta/Elev= 30
  4753.2  437.82  4835.7  436.71  4856.6  436.93  4863.4  436.39  4916.0  435.64
  4944.0  434.81  4976.6  434.33  4994.1  434.54  5004.2  433.54  5014.2  434.62
  5081.3  434.14  5094.2  433.67  5116.7  434.41  5131.3  434.34  5137.5  433.92
  5141.1  432.77  5141.6  431.97  5146.8  431.97  5147.3  432.77  5158.4  433.95
  5166.7  434.12  5202.1  433.30  5252.1  434.02  5337.5  434.13  5358.3  434.70
  5437.4  434.82  5481.2  435.37  5522.8  436.61  5572.8  437.51  5604.1  437.64
#Mann=3,-1,0
  4753.2     0.1       0  5141.1    0.07       0  5147.3     0.1       0
Bank Sta=5141.1,5147.3
Exp/Cntr=0.3,0.1

Type RM Length L Ch R = 1,2238,175,175,175
BEGIN DESCRIPTION:
Mapping XS 1b662e08
END DESCRIPTION:
XS GIS Cut Line= 4
      2046282.52     13472088.33      2046403.16     13472107.43
      2046644.48     13472001.52      2046953.58     13471582.96
#Sta/Elev= 30
  4694.7  437.34  4737.7  436.27  4808.6  435.43  4815.2  434.86  4829.8  434.66
  4835.3  434.93  4864.1  434.38  4939.6  434.41  5009.7  433.82  5026.3  434.90
  5033.1  436.03  5048.2  436.77  5106.8  437.30  5113.3  437.03  5121.5  435.70
  5127.7  436.68  5136.1  435.28  5150.6  433.95  5210.2  433.31  5210.7  432.51
  5215.9  432.51  5216.4  433.31  5349.5  433.79  5399.3  434.67  5407.5  434.40
  5457.6  434.90  5507.7  435.70  5549.4  437.19  5564.1  436.83  5600.7  437.27
#Mann=3,-1,0
  4694.7     0.1       0  5210.2    0.07       0  5216.4     0.1       0
Bank Sta=5210.2,5216.4
Exp/Cntr=0.3,0.1

Type RM Length L Ch R = 1,2063,32,32,32
BEGIN DESCRIPTION:
Mapping XS 3533d264
END DESCRIPTION:
XS GIS Cut Line= 4
      2046413.57     13472176.00      2046589.36     13472174.70
      2046814.62     13472067.93      2046949.66     13471702.77
#Sta/Elev= 30
  4692.4  435.18  4763.8  434.47  4896.6  434.31  4902.3  433.86  4907.8  431.96
  4918.7  431.58  4925.0  431.96  4930.6  431.41  4947.8  431.69  4982.0  431.40
  4982.5  430.60  4987.7  430.60  4988.2  431.40  4998.8  431.68  5016.0  435.43
  5044.3  436.52  5051.5  436.33  5073.6  433.27  5089.8  432.62  5129.5  432.08
  5134.8  431.68  5152.6  432.89  5159.9  432.67  5205.9  433.62  5291.2  433.67
  5323.2  434.23  5331.7  433.89  5344.5  434.28  5417.5  434.36  5506.8  435.57
#Mann=3,-1,0
  4692.4     0.1       0  4982.0    0.07       0  4988.2     0.1       0
Bank Sta=4982,4988.2
Exp/Cntr=0.3,0.1

Type RM Length L Ch R = 1,2031,35,35,35
BEGIN DESCRIPTION:
Mapping XS db89fd3f
END DESCRIPTION:
XS GIS Cut Line= 4
      2046452.59     13472208.56      2046607.58     13472203.35
      2046825.03     13472095.27      2046984.53     13471689.18
#Sta/Elev= 30
  4718.0  435.38  4760.4  434.34  4892.5  434.09  4900.6  433.75  4914.9  433.83
  4945.4  435.68  4967.8  435.45  4990.2  436.01  5012.6  435.69  5040.6  436.07
  5057.4  435.45  5063.0  434.93  5071.2  433.53  5079.8  432.73  5107.8  432.24
  5125.5  432.57  5134.6  431.62  5135.1  430.82  5140.3  430.82  5140.8  431.62
  5148.4  431.92  5155.3  432.62  5169.9  433.03  5202.1  433.05  5277.4  433.84
  5309.6  433.65  5377.6  434.13  5402.0  434.65  5449.3  434.56  5552.2  435.90
#Mann=3,-1,0
  4718.0     0.1       0  5134.6    0.07       0  5140.8     0.1       0
Bank Sta=5134.6,5140.8
Exp/Cntr=0.3,0.1

Type RM Length L Ch R = 1,1996,162,162,162
BEGIN DESCRIPTION:
Mapping XS 61ccbc39
END DESCRIPTION:
XS GIS Cut Line= 4
      2046452.64     13472224.18      2046615.40     13472239.80
      2046839.36     13472126.52      2047012.17     13471680.62
#Sta/Elev= 30
  4701.8  435.78  4754.4  434.22  4804.6  434.25  4920.9  432.84  4951.2  432.76
  4956.8  433.22  4995.8  432.32  5001.4  432.95  5018.1  432.39  5023.7  433.26
  5040.3  432.27  5045.9  432.75  5062.6  432.11  5107.2  432.34  5116.3  431.81
  5120.7  432.32  5136.3  431.70  5136.8  430.90  5142.0  430.90  5142.5  431.70
  5150.6  432.37  5160.8  432.60  5224.3  432.84  5268.1  433.37  5278.8  433.97
  5284.1  433.66  5368.5  433.76  5482.9  435.01  5525.5  434.87  5594.5  436.03
#Mann=3,-1,0
  4701.8     0.1       0  5136.3    0.07       0  5142.5     0.1       0
Bank Sta=5136.3,5142.5
Exp/Cntr=0.3,0.1

Type RM Length L Ch R = 1,1834,158,158,158
BEGIN DESCRIPTION:
Mapping XS 113e14fa
END DESCRIPTION:
XS GIS Cut Line= 4
      2046465.33     13472443.66      2046708.77     13472455.37
      2046952.26     13472034.80      2047046.01     13471713.19
#Sta/Elev= 30
  4552.2  435.69  4622.0  434.73  4652.0  435.06  4662.0  434.43  4685.6  433.95
  4772.1  432.87  4831.0  432.75  4837.5  432.29  4888.8  431.71  4969.7  431.83
  4976.7  431.13  4982.5  431.28  4998.3  430.46  5001.3  429.85  5001.8  429.05
  5007.0  429.05  5007.5  429.85  5014.0  431.23  5041.3  431.71  5094.4  431.87
  5115.9  431.42  5121.7  431.83  5159.0  431.89  5217.8  432.93  5302.5  433.32
  5313.8  433.97  5396.3  433.60  5458.8  434.60  5597.4  435.87  5616.9  435.71
#Mann=3,-1,0
  4552.2     0.1       0  5001.3    0.07       0  5007.5     0.1       0
Bank Sta=5001.3,5007.5
Exp/Cntr=0.3,0.1

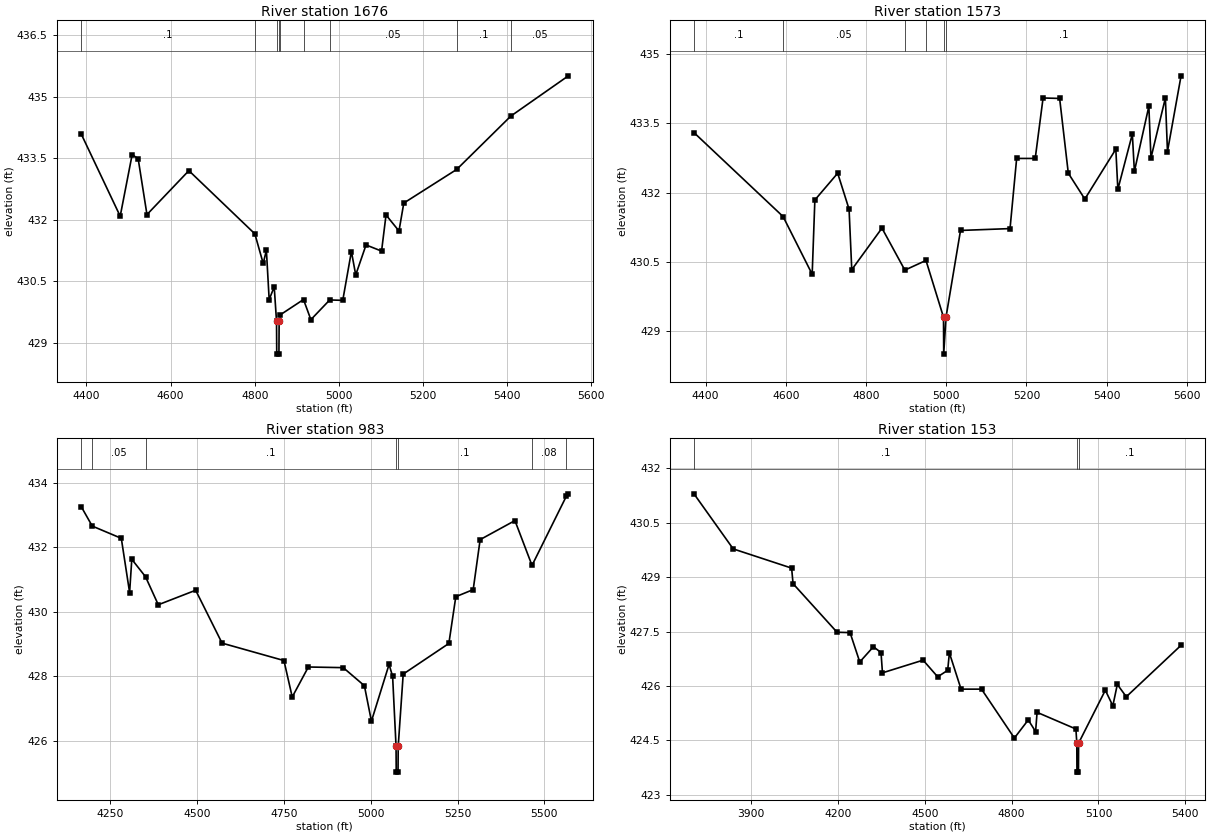
Type RM Length L Ch R = 1,1676,103,103,103
BEGIN DESCRIPTION:
Mapping XS d01e0f95
END DESCRIPTION:
XS GIS Cut Line= 4
      2046618.60     13472829.02      2046918.78     13472485.90
      2046979.98     13472230.69      2047079.87     13471803.04
#Sta/Elev= 30
  4387.7  434.09  4480.2  432.09  4508.6  433.59  4522.9  433.49  4543.8  432.13
  4643.4  433.20  4800.2  431.66  4820.0  430.94  4827.6  431.26  4834.2  430.06
  4846.2  430.37  4851.7  429.53  4852.2  428.73  4857.4  428.73  4857.9  429.53
  4861.0  429.69  4915.8  430.06  4933.3  429.57  4978.1  430.05  5009.1  430.04
  5029.6  431.23  5039.9  430.66  5064.4  431.39  5101.3  431.24  5111.9  432.12
  5142.7  431.73  5154.1  432.41  5279.9  433.23  5408.6  434.53  5545.2  435.51
#Mann=9,-1,0
  4387.7     0.1       0  4800.2    0.05       0  4851.7    0.04       0
  4857.9    0.05       0  4861.0     0.1       0  4915.8    0.08       0
  4978.1    0.05       0  5279.9     0.1       0  5408.6    0.05       0
Bank Sta=4851.7,4857.9
Exp/Cntr=0.3,0.1

Type RM Length L Ch R = 1,1573,590,590,590
BEGIN DESCRIPTION:
Mapping XS 8959c9a4
END DESCRIPTION:
XS GIS Cut Line= 4
      2046691.46     13472867.28      2046966.96     13472556.21
      2047108.89     13472242.41      2047219.27     13471801.24
#Sta/Elev= 30
  4371.0  433.30  4593.3  431.48  4665.8  430.23  4672.5  431.84  4729.4  432.42
  4757.8  431.64  4764.5  430.33  4839.8  431.23  4896.9  430.32  4949.6  430.53
  4993.3  429.30  4993.8  428.50  4999.5  429.30  5035.7  431.18  5159.2  431.22
  5175.7  432.74  5222.0  432.74  5241.6  434.05  5282.9  434.04  5304.5  432.42
  5345.7  431.86  5423.0  432.94  5428.1  432.07  5464.2  433.27  5469.3  432.46
  5505.4  433.87  5510.6  432.75  5546.6  434.05  5551.8  432.89  5585.7  434.53
#Mann=6,-1,0
  4371.0     0.1       0  4593.3    0.05       0  4896.9    0.08       0
  4949.6     0.1       0  4993.3    0.07       0  4999.5     0.1       0
Bank Sta=4993.3,4999.5
Exp/Cntr=0.3,0.1

Type RM Length L Ch R = 1,983,830,830,830
BEGIN DESCRIPTION:
Mapping XS 1da24688
END DESCRIPTION:
XS GIS Cut Line= 4
      2046750.49     13472922.81      2047417.48     13472647.36
      2047469.56     13472354.39      2047493.57     13471971.43
#Sta/Elev= 30
  4166.1  433.25  4197.7  432.65  4281.4  432.27  4305.3  430.59  4311.6  431.62
  4351.1  431.08  4387.9  430.21  4495.6  430.66  4571.6  429.02  4749.8  428.48
  4773.7  427.35  4820.1  428.28  4920.6  428.26  4981.5  427.70  5001.8  426.60
  5052.6  428.36  5062.8  427.99  5072.7  425.82  5073.2  425.02  5078.4  425.02
  5078.9  425.82  5093.3  428.06  5224.8  429.01  5244.8  430.46  5294.9  430.68
  5314.9  432.23  5415.1  432.82  5464.3  431.43  5562.9  433.57  5569.0  433.65
#Mann=7,-1,0
  4166.1     0.1       0  4197.7    0.05       0  4351.1     0.1       0
  5072.7    0.07       0  5078.9     0.1       0  5464.3    0.08       0
  5562.9    0.05       0
Bank Sta=5072.7,5078.9
Exp/Cntr=0.3,0.1

Type RM Length L Ch R = 1,153,0,0,0
BEGIN DESCRIPTION:
UNT 40 in Lagunillas Cr Wtrshd 1.0
END DESCRIPTION:
XS GIS Cut Line= 4
      2046900.65     13473004.93      2048083.64     13472848.24
      2048181.80     13472713.76      2048100.69     13472401.96
#Sta/Elev= 30
  3703.2  431.30  3838.7  429.78  4040.4  429.25  4045.4  428.82  4197.3  427.48
  4242.2  427.47  4275.7  426.66  4322.9  427.08  4349.1  426.92  4354.1  426.36
  4494.4  426.71  4544.8  426.25  4579.3  426.43  4585.2  426.91  4625.5  425.91
  4696.1  425.91  4809.6  424.56  4857.5  425.06  4882.9  424.74  4888.0  425.27
  5022.1  424.81  5025.2  424.42  5025.7  423.62  5030.9  423.62  5031.4  424.42
  5123.7  425.88  5149.6  425.45  5165.1  426.04  5196.1  425.70  5385.2  427.12
#Mann=3,-1,0
  3703.2     0.1       0  5025.2    0.07       0  5031.4     0.1       0
Bank Sta=5025.2,5031.4
Exp/Cntr=0.3,0.1

Chan Stop Cuts=-1