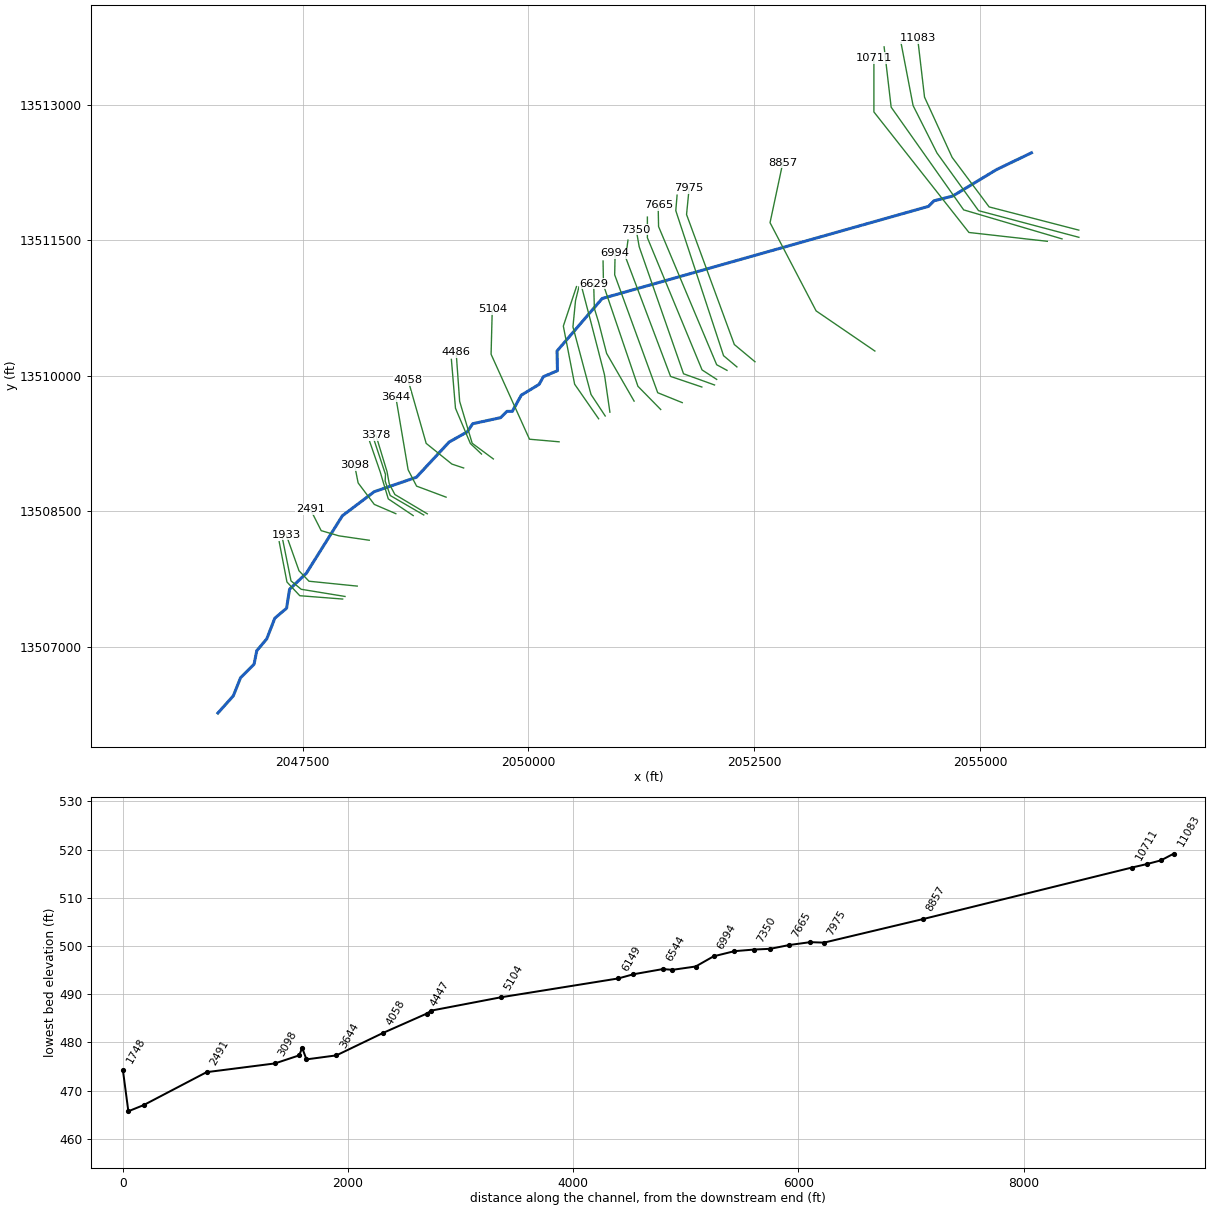
--- UNT 42 in Lagunillas Cr Wtrshd.prj (project) ---

Proj Title=UNT 42 in Lagunillas Cr Wtrshd Base Level Engineering
Current Plan=p01
Default Exp/Contr=0.3,0.1
English Units
Geom File=g01
Flow File=f01
Plan File=p01
Y Axis Title=Elevation
X Axis Title(PF)=Main Channel Distance
X Axis Title(XS)=Station
BEGIN DESCRIPTION:
UNT 42 in Lagunillas Cr Wtrshd
END DESCRIPTION:
DSS Export Rating Curves= 0
DSS Export Rating Curve Sorted= 0
DSS Export Volume Flow Curves= 0
DXF OffsetX= 0
DXF OffsetY= 0
DXF ScaleX= 1
DXF ScaleY= 10

--- UNT 42 in Lagunillas Cr Wtrshd.p01 (plan) ---

Plan Title=Multiple Run
Short Identifier=Multiple
Geom File=g01
Flow File=f01
Subcritical Flow
K Sum by GR= 0
Std Step Tol= 0.01
Critical Tol= 0.01
Num of Std Step Trials= 20
Max Error Tol= 0.3
Flow Tol Ratio= 0.001
Split Flow NTrial= 30
Split Flow Tol= 0.02
Split Flow Ratio= 0.02
Log Output Level= 0
Friction Slope Method= 1
Unsteady Friction Slope Method= 2
Unsteady Bridges Friction Slope Method= 1
Parabolic Critical Depth
Global Vel Dist=  1 , 1 , 1
Global Log Level= 0
CheckData=True
Encroach Param= -1, 0, 0, 0
BEGIN DESCRIPTION:
Multiple Run
END DESCRIPTION:

--- UNT 42 in Lagunillas Cr Wtrshd.f01 (steady flow) ---

Flow Title=Multiple
Number of Profiles=7
Profile Names=10-year,25-year,50-year,1pct_min,100-year,1pct_plu,500-year
River Rch & RM= UNT 42 in Laguni,Reach-1,11083
     213     293     358     219     436     870     657
River Rch & RM= UNT 42 in Laguni,Reach-1,8857
     314     439     544     336     670    1336    1031
River Rch & RM= UNT 42 in Laguni,Reach-1,2491
     360     506     630     390     779    1553    1208
Boundary for River Rch & Prof#=UNT 42 in Laguni,Reach-1,1
Up Type=0
Dn Type=3
Dn Slope=0.005
Boundary for River Rch & Prof#=UNT 42 in Laguni,Reach-1,2
Up Type=0
Dn Type=3
Dn Slope=0.005
Boundary for River Rch & Prof#=UNT 42 in Laguni,Reach-1,3
Up Type=0
Dn Type=3
Dn Slope=0.005
Boundary for River Rch & Prof#=UNT 42 in Laguni,Reach-1,4
Up Type=0
Dn Type=3
Dn Slope=0.005
Boundary for River Rch & Prof#=UNT 42 in Laguni,Reach-1,5
Up Type=0
Dn Type=3
Dn Slope=0.005
Boundary for River Rch & Prof#=UNT 42 in Laguni,Reach-1,6
Up Type=0
Dn Type=3
Dn Slope=0.005
Boundary for River Rch & Prof#=UNT 42 in Laguni,Reach-1,7
Up Type=0
Dn Type=3
Dn Slope=0.005

--- UNT 42 in Lagunillas Cr Wtrshd.g01 (geometry) ---

Geom Title=Existing Conditions
Program Version=5.05

River Reach=UNT 42 in Laguni,Reach-1
Reach XY= 30
      2055570.76     13512467.63      2055183.16     13512281.42
      2054698.14     13511988.45      2054491.17     13511936.15
       2054430.8     13511874.54      2050815.83     13510854.13
      2050316.17     13510273.35       2050320.8     13510054.54
      2050164.68     13509988.41      2050117.28     13509903.17
      2049920.06     13509783.72       2049820.8     13509604.54
       2049760.8     13509604.54       2049690.8     13509534.54
      2049381.87     13509467.75      2049322.84     13509378.17
       2049120.8     13509264.54      2048758.26     13508874.69
       2048290.8     13508714.54      2047938.57     13508448.03
      2047539.26     13507811.22      2047353.85     13507634.83
       2047320.8     13507424.54       2047190.8     13507314.54
       2047100.8     13507084.54       2046990.8     13506954.54
       2046960.8     13506804.54       2046810.8     13506654.54
       2046730.8     13506454.54       2046560.8     13506264.54

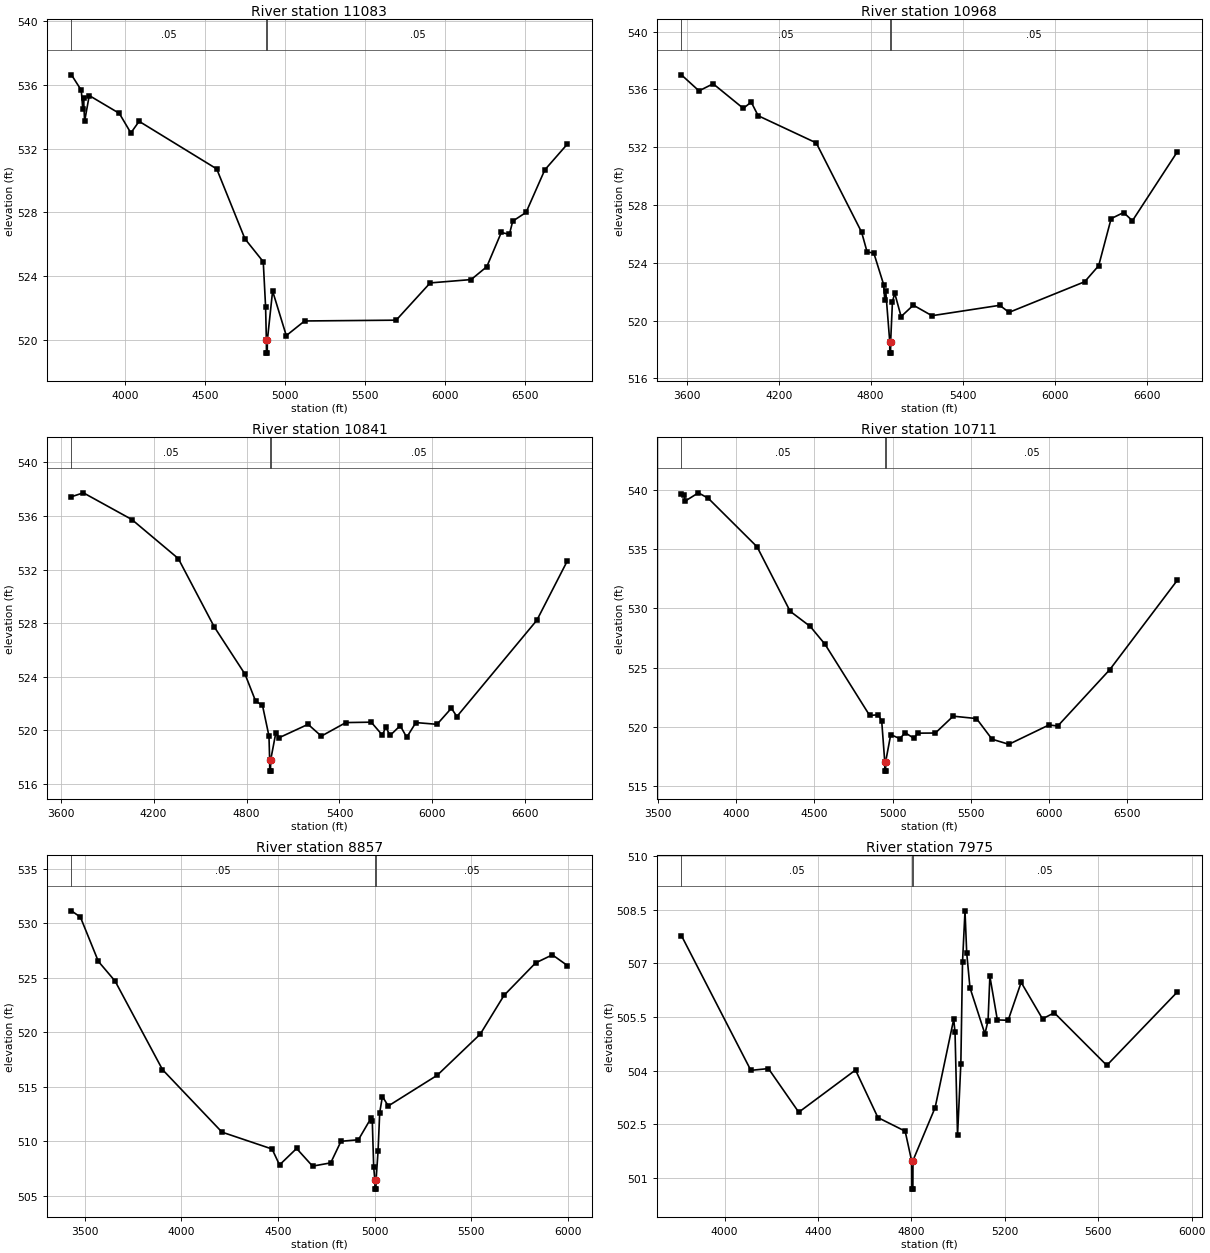
Type RM Length L Ch R = 1 ,11083   ,115,115,115
BEGIN DESCRIPTION:
Mapping XS a20fa21c
END DESCRIPTION:
XS GIS Cut Line= 5
      2056094.46     13511611.35      2055101.36     13511868.31
      2054691.64     13512416.92      2054386.08     13513083.59
      2054309.84     13513735.06
#Sta/Elev= 30
  3663.5  536.64  3724.9  535.67    3734  534.52  3739.2  535.18  3745.6  533.71
  3774.6  535.34  3962.5  534.22  4034.8  532.99  4086.4  533.72  4571.5  530.73
  4747.8  526.34  4862.4   524.9    4877  522.07  4881.9  519.96  4882.4  519.16
  4887.4  519.16  4887.9  519.96  4920.8  523.06  5006.3  520.26  5120.9  521.18
  5693.2  521.23  5905.7  523.57  6161.9  523.78  6259.8  524.59  6350.4  526.74
  6400.8  526.62  6421.9  527.45  6505.2     528  6622.3  530.67  6763.3  532.29
#Mann= 3 ,-1 , 0
  3663.5     .05       0  4881.9     .03       0  4887.9     .05       0
Bank Sta=4881.9,4887.9
XS Rating Curve= 0 ,0
Exp/Cntr=0.3,0.1

Type RM Length L Ch R = 1 ,10968   ,127,127,127
BEGIN DESCRIPTION:
Mapping XS 395a7947
END DESCRIPTION:
XS GIS Cut Line= 5
      2056095.38     13511531.68      2054984.24     13511826.82
      2054524.17     13512464.84      2054259.41     13512990.02
      2054124.87     13513688.78
#Sta/Elev= 30
  3564.8  537.01  3679.7   535.9  3772.1  536.39  3968.7  534.69  4020.5  535.12
  4065.8  534.18  4444.7   532.3  4740.9  526.12  4776.5  524.76  4820.7  524.67
  4884.8  522.49  4891.8  521.43    4898  522.08  4924.4  518.55  4924.9  517.75
  4929.9  517.75  4930.4  518.55  4942.1  521.31  4956.9   521.9  4998.6  520.28
  5078.3  521.07  5199.8  520.34  5642.4  521.06  5702.8  520.57  6196.5  522.69
  6287.8   523.8  6369.2  527.06  6450.7  527.48    6508  526.91  6800.8  531.68
#Mann= 3 ,-1 , 0
  3564.8     .05       0  4924.4     .03       0  4930.4     .05       0
Bank Sta=4924.4,4930.4
XS Rating Curve= 0 ,0
Exp/Cntr=0.3,0.1

Type RM Length L Ch R = 1 ,10841   ,130,130,130
BEGIN DESCRIPTION:
Mapping XS 6be9af76
END DESCRIPTION:
XS GIS Cut Line= 4
      2055908.72     13511514.32      2054819.31      13511835.5
      2054016.36     13512972.66      2053938.29     13513640.57
#Sta/Elev= 30
  3670.3  537.43  3747.2  537.72  4059.9  535.73  4359.7  532.82  4591.6  527.73
  4790.8  524.19  4858.7  522.19  4903.1  521.87  4944.9  519.59  4949.4  517.77
  4949.9  516.97  4954.9  516.97  4955.4  517.77  4989.1  519.82  5010.2  519.46
  5197.2  520.46  5282.9  519.58  5441.1  520.59  5604.8  520.62  5676.2  519.66
  5699.1  520.24  5726.7  519.63    5792  520.36  5833.8  519.49    5893  520.59
  6029.6  520.46    6122  521.66  6157.7  521.04  6673.7  528.22  6870.6  532.65
#Mann= 3 ,-1 , 0
  3670.3     .05       0  4949.4     .03       0  4955.4     .05       0
Bank Sta=4949.4,4955.4
XS Rating Curve= 0 ,0
Exp/Cntr=0.3,0.1

Type RM Length L Ch R = 1 ,10711   ,1854,1854,1854
BEGIN DESCRIPTION:
Mapping XS f9a50247
END DESCRIPTION:
XS GIS Cut Line= 4
      2055745.85      13511487.6      2054877.81     13511585.25
      2053825.29     13512919.89      2053825.29     13513516.65
#Sta/Elev= 30
  3650.1  539.58  3668.8  539.52  3673.9  539.02  3758.8  539.72    3822  539.26
    4134  535.17  4345.3  529.74  4473.9  528.46  4568.2  526.96  4853.6  520.96
  4909.7  521.02  4930.8  520.47    4950  517.07  4950.5  516.27  4955.5  516.27
    4956  517.07  4988.3  519.35  5045.5  519.01  5081.3   519.5  5137.4  519.03
  5159.9  519.47  5273.7  519.48  5387.5   520.9  5536.6   520.7    5636  518.96
  5743.5  518.53    6000  520.16  6056.1  520.07  6388.5  524.82  6820.1  532.35
#Mann= 3 ,-1 , 0
  3650.1     .05       0    4950     .03       0    4956     .05       0
Bank Sta=4950,4956
XS Rating Curve= 0 ,0
Exp/Cntr=0.3,0.1

Type RM Length L Ch R = 1 ,8857    ,882,882,882
BEGIN DESCRIPTION:
Mapping XS 3cb2ffcd
END DESCRIPTION:
XS GIS Cut Line= 4
      2053836.13     13510272.32       2053185.1     13510717.19
      2052675.12     13511693.76      2052816.18     13512355.67
#Sta/Elev= 30
  3430.9  531.13  3477.3  530.55  3570.1  526.49  3656.8  524.68    3902  516.56
  4210.1  510.82  4469.4  509.27  4507.9  507.81  4596.3  509.32    4679   507.7
  4772.9     508  4826.1  509.98  4916.2  510.12  4982.5  512.13  4988.1  511.85
  4995.4  507.61  5001.5  506.39    5002  505.59  5007.1  505.59  5007.6  506.39
  5017.9  509.06  5026.6  512.62  5040.5  514.09  5070.8  513.22  5324.3  516.04
  5547.3  519.82    5670  523.37  5833.6  526.35  5920.4  527.09  5997.9  526.11
#Mann= 3 ,-1 , 0
  3430.9     .05       0  5001.5     .03       0  5007.6     .05       0
Bank Sta=5001.5,5007.6
XS Rating Curve= 0 ,0
Exp/Cntr=0.3,0.1

Type RM Length L Ch R = 1 ,7975    ,122,122,122
BEGIN DESCRIPTION:
Mapping XS 00ab7545
END DESCRIPTION:
XS GIS Cut Line= 4
      2052508.25     13510153.98      2052279.46     13510344.64
      2051750.41     13511784.02      2051779.01     13512074.77
#Sta/Elev= 30
    3815  507.78  4112.5  504.01  4187.8  504.06  4317.6  502.84  4560.7  504.02
  4656.6  502.69  4773.2  502.31  4800.6  501.49  4801.1  500.69  4806.2  500.69
  4806.7  501.49  4901.6  502.97  4981.2  505.44  4986.8  505.07  4997.5  502.19
  5011.7   504.2  5018.8  507.03  5029.5  508.47  5036.8  507.29  5050.8  506.32
  5114.7  505.03  5128.2   505.4    5136  506.64    5168  505.42  5214.3  505.41
  5269.9  506.47  5361.4  505.45  5411.7  505.62  5636.7  504.15  5938.5   506.2
#Mann= 3 ,-1 , 0
    3815     .05       0  4800.6     .03       0  4806.7     .05       0
Bank Sta=4800.6,4806.7
XS Rating Curve= 0 ,0
Exp/Cntr=0.3,0.1

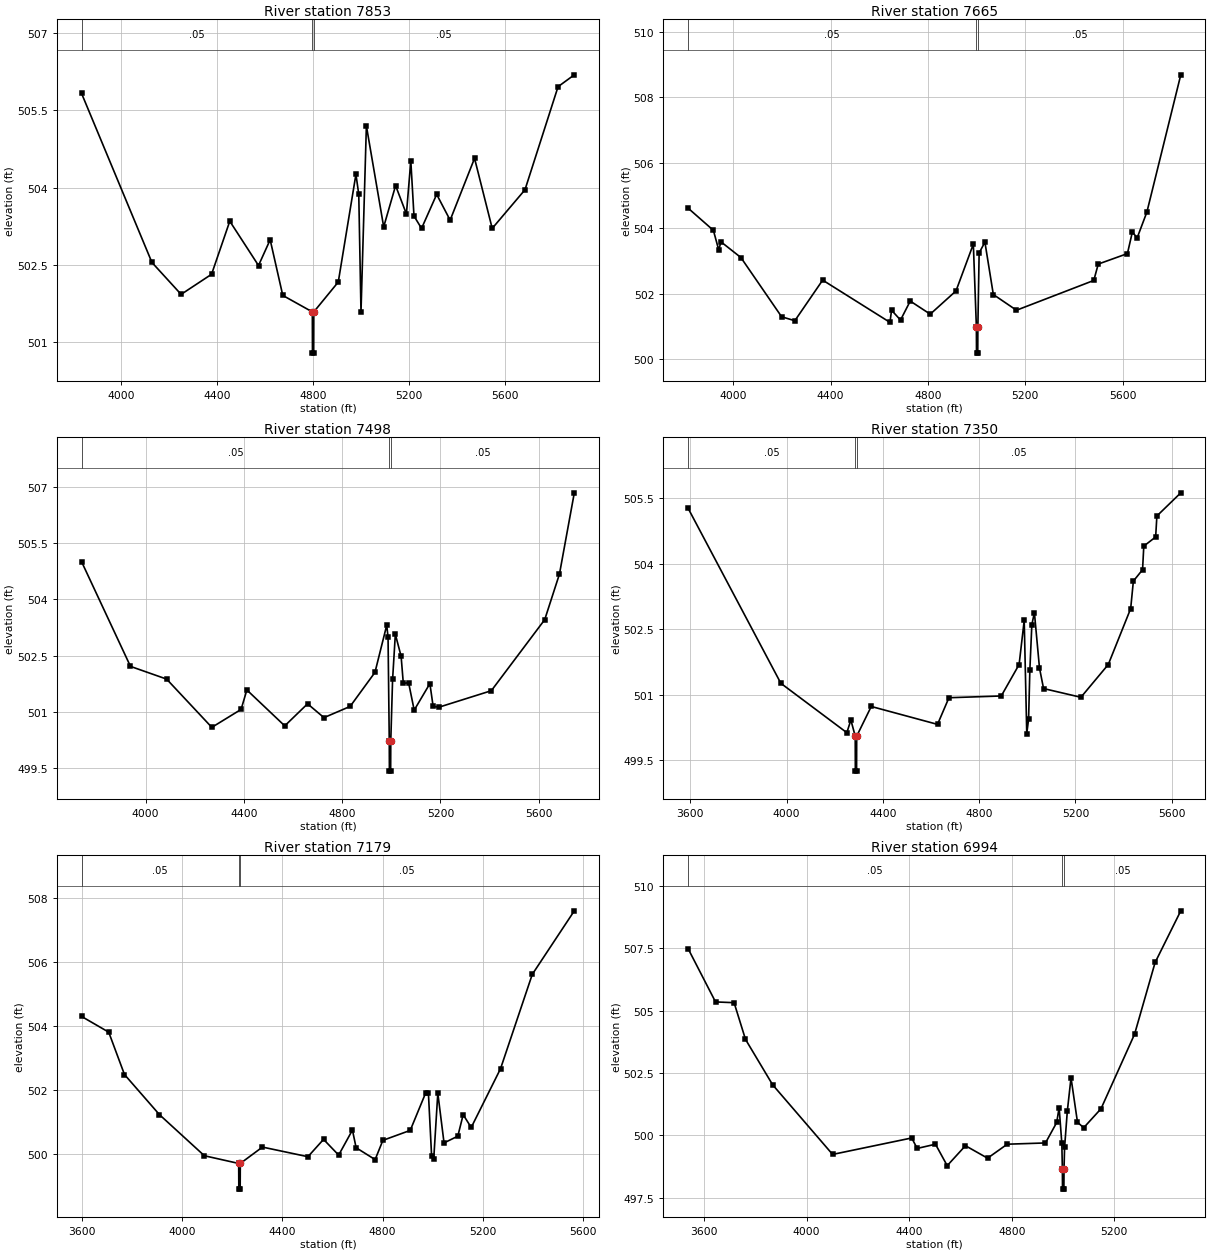
Type RM Length L Ch R = 1 ,7853    ,188,188,188
BEGIN DESCRIPTION:
Mapping XS 91732220
END DESCRIPTION:
XS GIS Cut Line= 4
      2052308.06     13510096.79       2052160.3     13510220.72
      2051631.26     13511826.91      2051645.56     13511998.49
#Sta/Elev= 30
  3834.7  505.83  4128.3  502.55  4250.1  501.93  4377.2  502.32  4453.2  503.35
  4573.1  502.49  4621.7  502.99  4674.3  501.91  4797.7  501.59  4798.2  500.79
  4803.3  500.79  4803.8  501.59  4905.9  502.17  4979.6  504.26  4991.4  503.87
  5000.7  501.59  5023.2   505.2  5095.4  503.24  5145.1  504.04  5190.2  503.49
  5208.6  504.52  5221.8  503.45  5253.4  503.21  5316.5  503.87  5372.7  503.37
  5474.5  504.57  5548.2  503.21    5685  503.96    5823  505.96  5890.8  506.19
#Mann= 3 ,-1 , 0
  3834.7     .05       0  4797.7     .03       0  4803.8     .05       0
Bank Sta=4797.7,4803.8
XS Rating Curve= 0 ,0
Exp/Cntr=0.3,0.1

Type RM Length L Ch R = 1 ,7665    ,167,167,167
BEGIN DESCRIPTION:
Mapping XS 90a75f1a
END DESCRIPTION:
XS GIS Cut Line= 4
      2052198.46     13510058.65      2052084.05     13510120.63
      2051440.61     13511650.56      2051435.85     13511884.06
#Sta/Elev= 30
  3814.9  504.62  3919.1  503.94    3941  503.34  3950.1  503.59    4032  503.11
  4199.3   501.3  4253.5  501.18  4367.8  502.42  4644.1  501.13  4650.7   501.5
  4687.5   501.2  4727.4  501.78  4809.5  501.38  4915.3  502.09  4986.5  503.52
    4999  500.99  4999.5  500.19  5004.6  500.19  5005.1  500.99  5010.3  503.25
    5034  503.58  5068.6  501.98  5163.6   501.5  5481.1  502.41  5499.4  502.91
  5619.2  503.23  5639.5  503.89  5659.2  503.71  5699.2   504.5  5838.3  508.69
#Mann= 3 ,-1 , 0
  3814.9     .05       0    4999     .03       0  5005.1     .05       0
Bank Sta=4999,5005.1
XS Rating Curve= 0 ,0
Exp/Cntr=0.3,0.1

Type RM Length L Ch R = 1 ,7498    ,148,148,148
BEGIN DESCRIPTION:
Mapping XS 0b9f4520
END DESCRIPTION:
XS GIS Cut Line= 4
      2052084.01      13509958.6        2051922.     13510063.43
      2051316.69     13511526.64      2051316.69      13511755.4
#Sta/Elev= 30
  3739.5  505.01  3938.6  502.21  4085.7  501.87  4269.6  500.58  4388.7  501.06
  4412.2  501.58  4566.4  500.62  4659.2  501.21    4726  500.84  4832.5  501.14
  4933.5  502.05  4981.3  503.31  4986.7     503  4991.7  500.21  4992.2  499.41
  4997.3  499.41  4997.8  500.21  5005.2  501.86  5016.4  503.07  5039.9  502.48
  5048.8  501.76  5070.5  501.77  5093.1  501.04    5157  501.75  5170.2  501.14
  5194.1  501.12    5407  501.56  5624.3  503.46  5684.3  504.68  5744.7  506.85
#Mann= 3 ,-1 , 0
  3739.5     .05       0  4991.7     .03       0  4997.8     .05       0
Bank Sta=4991.7,4997.8
XS Rating Curve= 0 ,0
Exp/Cntr=0.3,0.1

Type RM Length L Ch R = 1 ,7350    ,171,171,171
BEGIN DESCRIPTION:
Mapping XS a165ff57
END DESCRIPTION:
XS GIS Cut Line= 4
      2052060.18     13509896.63      2051717.05     13510020.54
      2051226.14     13511426.55      2051192.78     13511617.19
#Sta/Elev= 30
  3590.3  505.27  3976.1  501.26  4250.3  500.13    4267  500.42  4285.1  500.05
  4285.6  499.25  4290.7  499.25  4291.2  500.05  4351.7  500.73  4627.1  500.32
  4674.5  500.93  4891.9  500.97  4966.1  501.69  4987.3   502.7  4997.9  500.11
  5005.5  500.44  5010.8  501.57    5019   502.6  5029.6  502.88  5050.8  501.61
  5067.7  501.14  5222.9  500.94  5336.6  501.69  5429.7  502.97  5440.9   503.6
  5479.1  503.86  5484.2   504.4  5533.5  504.61  5538.6  505.09  5637.9  505.62
#Mann= 3 ,-1 , 0
  3590.3     .05       0  4285.1     .03       0  4291.2     .05       0
Bank Sta=4285.1,4291.2
XS Rating Curve= 0 ,0
Exp/Cntr=0.3,0.1

Type RM Length L Ch R = 1 ,7179    ,185,185,185
BEGIN DESCRIPTION:
Mapping XS fb8b1cf8
END DESCRIPTION:
XS GIS Cut Line= 4
      2051919.73     13509874.19      2051573.35     13509991.39
      2051075.95     13511309.09      2051101.87     13511500.92
#Sta/Elev= 30
  3598.1   504.3  3706.6  503.81  3769.5  502.49  3909.2  501.24  4088.5  499.96
  4225.6  499.72  4226.1  498.92  4231.5  498.92    4232  499.72  4320.4  500.23
  4502.1  499.93  4564.4  500.47  4624.8  499.98  4679.8  500.76  4694.5  500.21
  4770.4  499.84  4801.4  500.44  4910.6  500.75  4972.4  501.92  4983.1  501.92
  4995.9  499.96  5004.4  499.86  5020.7  501.91  5045.6  500.36  5100.6  500.57
    5122  501.24  5154.1  500.84  5271.1  502.67  5397.9  505.61  5565.8  507.59
#Mann= 3 ,-1 , 0
  3598.1     .05       0  4225.6     .03       0    4232     .05       0
Bank Sta=4225.6,4232
XS Rating Curve= 0 ,0
Exp/Cntr=0.3,0.1

Type RM Length L Ch R = 1 ,6994    ,159,159,159
BEGIN DESCRIPTION:
Mapping XS 36fd3499
END DESCRIPTION:
XS GIS Cut Line= 4
      2051702.78     13509701.19      2051431.08     13509810.83
      2050954.47     13511116.75      2050959.23     13511355.04
#Sta/Elev= 30
  3537.8  507.49  3645.1  505.35  3717.5  505.32  3761.9  503.85  3867.8  502.03
  4101.6  499.24  4410.1   499.9  4431.4  499.48  4502.7  499.65  4548.5  498.79
  4619.6  499.59  4705.9  499.09  4782.6  499.65  4931.7   499.7  4975.5  500.52
  4984.9  501.12  4995.4  499.69  4997.6  498.65  4998.1  497.85  5003.5  497.85
    5004  498.65  5006.2  499.52  5016.8  500.97  5031.3  502.31  5056.5  500.53
  5080.7  500.31  5148.2  501.07  5279.2  504.06  5359.2  506.93  5459.3     509
#Mann= 3 ,-1 , 0
  3537.8     .05       0  4997.6     .03       0    5004     .05       0
Bank Sta=4997.6,5004
XS Rating Curve= 0 ,0
Exp/Cntr=0.3,0.1

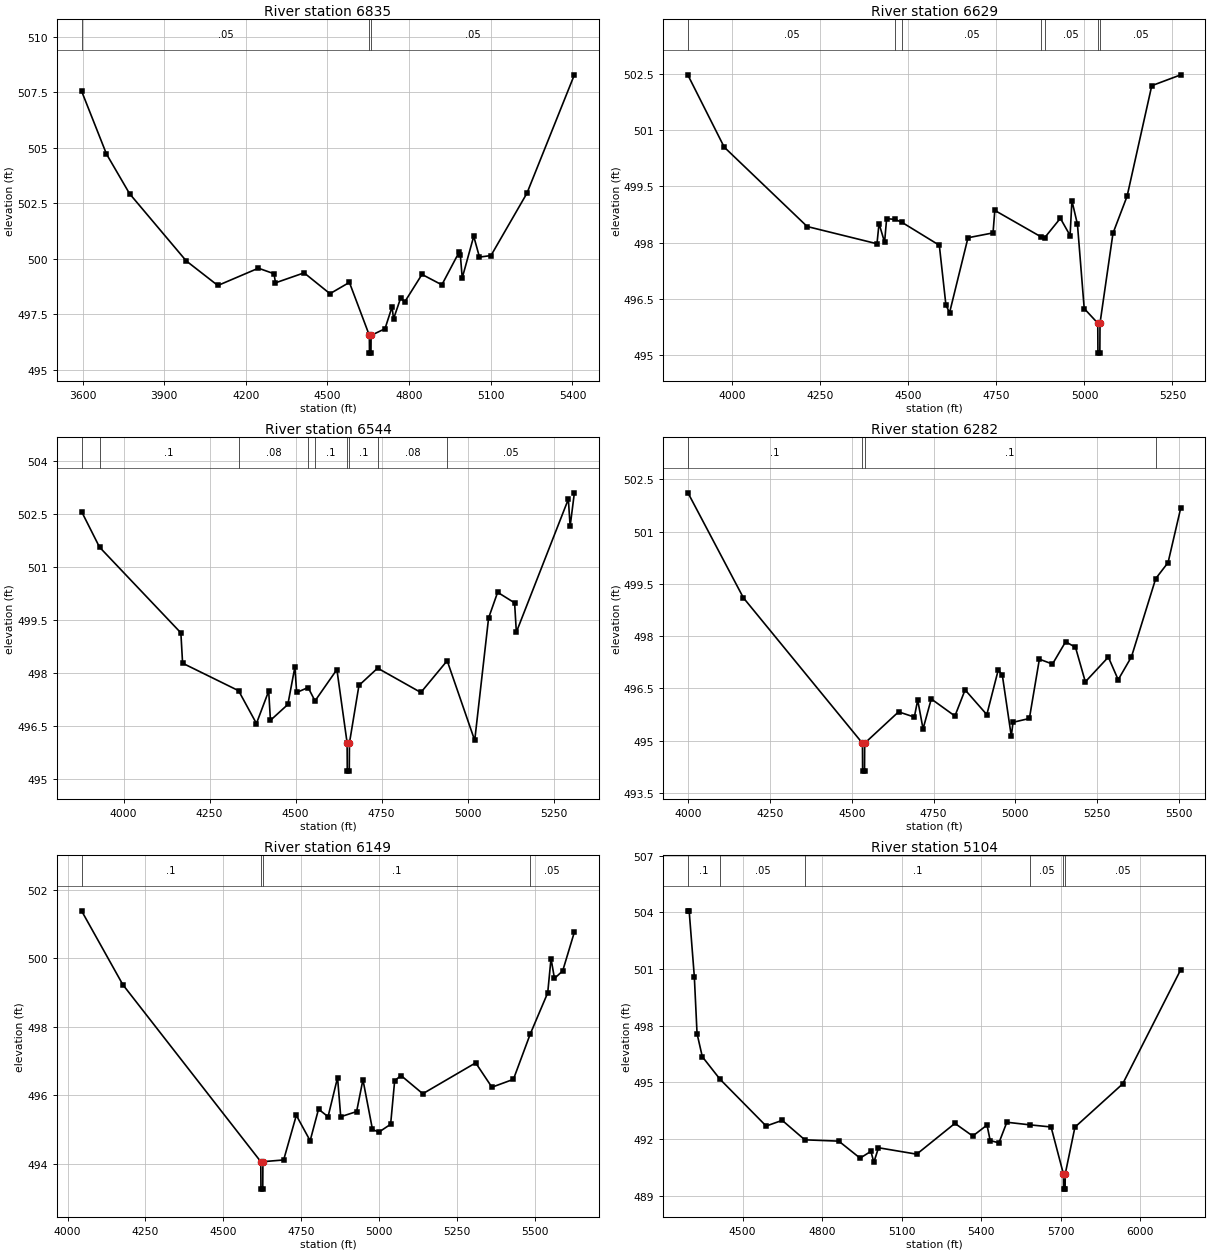
Type RM Length L Ch R = 1 ,6835    ,206,206,206
BEGIN DESCRIPTION:
Mapping XS ffe65807
END DESCRIPTION:
XS GIS Cut Line= 4
      2051464.42     13509624.97      2051211.84     13509882.32
      2050830.55     13511002.37      2050825.78     13511269.27
#Sta/Elev= 30
  3596.4  507.56  3687.9  504.72  3772.8  502.93  3980.9   499.9  4097.1  498.79
  4246.1  499.57  4303.6  499.32  4308.9  498.91  4414.1  499.36  4509.1  498.42
  4580.5  498.93  4653.8  496.54  4654.3  495.74  4659.7  495.74  4660.2  496.54
  4711.3  496.84  4737.3  497.83  4742.6  497.28  4768.7  498.22  4783.8  498.05
  4847.2  499.29  4920.2  498.82    4983  500.28  4988.2  500.15  4995.1  499.13
  5037.3  501.01  5058.4  500.07  5100.7  500.14  5232.8  502.95  5407.1  508.29
#Mann= 3 ,-1 , 0
  3596.4     .05       0  4653.8     .03       0  4660.2     .05       0
Bank Sta=4653.8,4660.2
XS Rating Curve= 0 ,0
Exp/Cntr=0.3,0.1

Type RM Length L Ch R = 1 ,6629    ,85,85,85
BEGIN DESCRIPTION:
Mapping XS 77eef218
END DESCRIPTION:
XS GIS Cut Line= 5
      2051169.71     13509717.92      2050865.01     13510246.59
      2050776.47     13510590.34       2050729.6     13510743.99
      2050721.78     13511017.38
#Sta/Elev= 30
  3874.2  502.47  3977.1  500.55  4212.7  498.43  4410.9  497.97  4416.7  498.51
  4432.5  498.01  4438.3  498.64  4462.4  498.62  4482.1  498.54  4587.9  497.93
  4606.7  496.33    4617  496.13  4669.3  498.13  4740.4  498.26  4745.5  498.86
  4877.6  498.15  4886.9  498.13  4931.6  498.65  4959.2  498.19  4964.4  499.12
  4980.1  498.49  4999.3  496.24  5037.8  495.85  5038.3  495.05  5043.7  495.05
  5044.2  495.85    5081  498.25  5121.1  499.24  5191.1  502.19  5273.5  502.48
#Mann= 7 ,-1 , 0
  3874.2     .05       0  4462.4     .08       0  4482.1     .05       0
  4877.6     .08       0  4886.9     .05       0  5037.8     .04       0
  5044.2     .05       0
Bank Sta=5037.8,5044.2
XS Rating Curve= 0 ,0
Exp/Cntr=0.3,0.1

Type RM Length L Ch R = 1 ,6544    ,262,262,262
BEGIN DESCRIPTION:
Mapping XS 7ebab1ca
END DESCRIPTION:
XS GIS Cut Line= 4
      2050901.47     13509595.54      2050841.57     13510009.62
      2050693.14     13510585.14      2050586.54     13510990.72
#Sta/Elev= 30
    3878  502.57  3930.2  501.56  4166.6  499.13  4171.6  498.27  4334.3  497.49
  4386.2  496.56  4421.8  497.48  4426.9  496.65  4477.5   497.1  4497.9  498.16
  4503.1  497.44  4536.4  497.58  4556.4   497.2    4620  498.09  4649.7  496.01
  4650.2  495.21    4656  495.21  4656.5  496.01  4684.1  497.64  4738.4  498.13
    4864  497.44  4940.5  498.34  5020.5  496.08  5060.8  499.55  5087.1  500.28
  5136.4  499.98  5141.5  499.15  5292.6  502.92  5297.8  502.15  5310.1   503.1
#Mann= 9 ,-1 , 0
    3878     .05       0  3930.2      .1       0  4334.3     .08       0
  4536.4     .05       0  4556.4      .1       0  4649.7     .04       0
  4656.5      .1       0  4738.4     .08       0  4940.5     .05       0
Bank Sta=4649.7,4656.5
XS Rating Curve= 0 ,0
Exp/Cntr=0.3,0.1

Type RM Length L Ch R = 1 ,6282    ,133,133,133
BEGIN DESCRIPTION:
Mapping XS 3865c3aa
END DESCRIPTION:
XS GIS Cut Line= 5
      2050849.61     13509553.46      2050692.33     13509791.76
      2050492.15     13510540.05      2050520.75     13510830.78
      2050558.47     13510981.67
#Sta/Elev= 30
  3998.7  502.11  4168.3   499.1  4532.6  494.93  4533.1  494.13  4538.9  494.13
  4539.4  494.93  4643.1  495.83  4691.3  495.68  4701.6  496.17    4718  495.34
  4743.1   496.2  4815.5  495.71  4846.6  496.46  4913.1  495.75    4948  497.03
  4960.4  496.89    4988  495.13  4993.2  495.53  5043.3  495.64  5073.9  497.34
    5114   497.2  5154.2  497.84  5184.4  497.68  5214.5  496.69  5284.9   497.4
    5315  496.75  5355.7  497.41  5429.8  499.65  5467.6  500.11  5506.5  501.68
#Mann= 4 ,-1 , 0
  3998.7      .1       0  4532.6     .07       0  4539.4      .1       0
  5429.8     .05       0
Bank Sta=4532.6,4539.4
XS Rating Curve= 0 ,0
Exp/Cntr=0.3,0.1

Type RM Length L Ch R = 1 ,6149    ,1045,1045,1045
BEGIN DESCRIPTION:
Mapping XS c9fec694
END DESCRIPTION:
XS GIS Cut Line= 4
      2050776.48     13509522.62      2050510.85     13509905.45
      2050385.85     13510548.68      2050531.68     13510986.19
#Sta/Elev= 30
  4045.1  501.38  4177.5  499.23  4620.6  494.07  4621.1  493.27  4626.9  493.27
  4627.4  494.07    4694  494.12  4734.7  495.42  4779.1  494.68    4806   495.6
  4836.6  495.38  4867.1  496.52  4877.3  495.38  4928.3  495.53  4948.6  496.46
  4979.2  495.01  4999.6  494.93  5037.5  495.16  5050.5  496.43  5070.9  496.58
  5140.8  496.05  5310.6  496.95  5362.7  496.24  5431.8  496.47  5485.8  497.79
  5541.9  498.99  5552.5  499.99  5563.6  499.41    5590  499.63  5627.5  500.76
#Mann= 4 ,-1 , 0
  4045.1      .1       0  4620.6     .07       0  4627.4      .1       0
  5485.8     .05       0
Bank Sta=4620.6,4627.4
XS Rating Curve= 0 ,0
Exp/Cntr=0.3,0.1

Type RM Length L Ch R = 1 ,5104    ,618,618,618
BEGIN DESCRIPTION:
Mapping XS 355db433
END DESCRIPTION:
XS GIS Cut Line= 4
      2050338.93     13509267.43      2050010.85     13509296.07
      2049585.67     13510236.71      2049598.69     13510734.15
#Sta/Elev= 30
  4293.9  504.08  4298.4  504.08  4317.9   500.6  4328.2  497.58    4348  496.36
  4414.6  495.17  4588.9  492.69  4649.5  492.99  4734.7  491.96    4863  491.89
  4943.3  490.99  4984.1  491.35  4995.2  490.77  5012.7  491.54  5156.9   491.2
    5301  492.83  5368.3  492.16  5422.1  492.74  5434.1  491.92  5467.1   491.8
  5496.9  492.89  5585.2  492.75  5663.8  492.64  5710.4  490.15  5710.9  489.35
  5716.7  489.35  5717.2  490.15  5753.8  492.63  5933.9  494.92  6153.1  500.97
#Mann= 6 ,-1 , 0
  4293.9      .1       0  4414.6     .05       0  4734.7      .1       0
  5585.2     .05       0  5710.4     .07       0  5717.2     .05       0
Bank Sta=5710.4,5717.2
XS Rating Curve= 0 ,0
Exp/Cntr=0.3,0.1

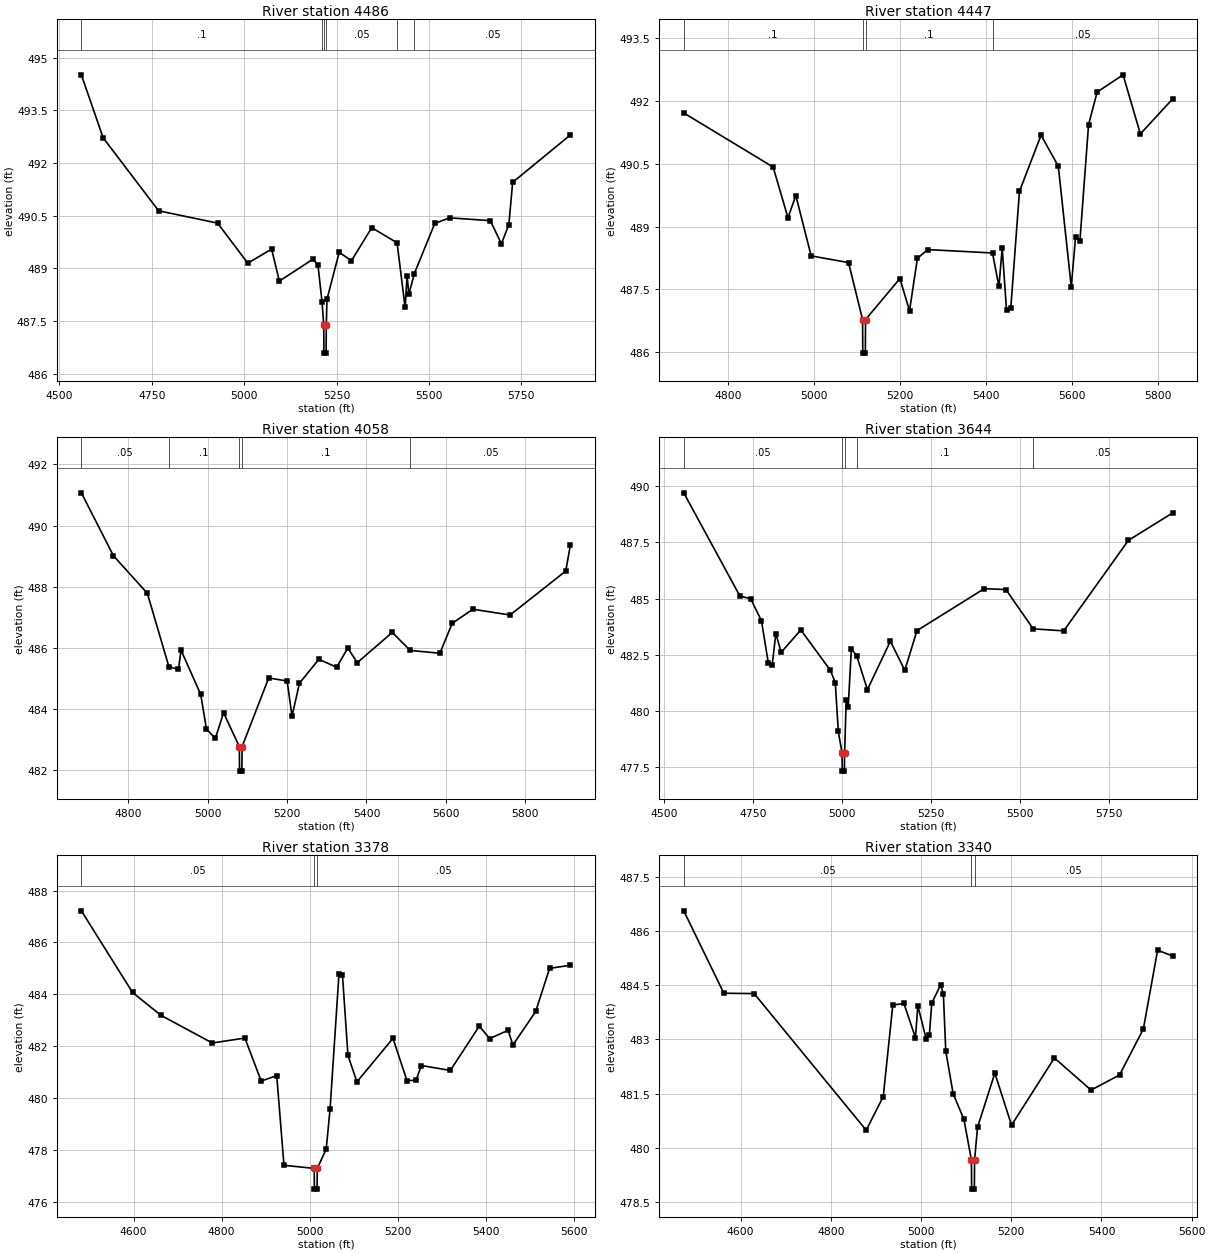
Type RM Length L Ch R = 1 ,4486    ,39,39,39
BEGIN DESCRIPTION:
Mapping XS dafa3996
END DESCRIPTION:
XS GIS Cut Line= 4
      2049610.77     13509077.56      2049376.39     13509251.17
      2049237.51     13509715.58      2049198.53     13510261.19
#Sta/Elev= 30
  4559.3  494.51  4618.1  492.72  4768.4  490.64    4928  490.29  5009.6  489.15
  5074.2  489.55    5095  488.64  5185.6  489.26  5199.4  489.11  5210.5  488.05
  5215.2  487.39  5215.7  486.59  5221.6  486.59  5222.1  487.39  5223.9  488.12
    5257  489.46  5290.1  489.22  5345.1  490.16  5413.6  489.73  5435.4  487.89
  5440.7  488.78  5445.7  488.27  5460.2  488.85  5515.6  490.28  5555.7  490.44
    5666  490.36    5696   489.7  5716.1  490.25  5726.4  491.45  5882.7   492.8
#Mann= 6 ,-1 , 0
  4559.3      .1       0  5210.5     .05       0  5215.2     .07       0
  5222.1     .05       0  5413.6      .1       0  5460.2     .05       0
Bank Sta=5215.2,5222.1
XS Rating Curve= 0 ,0
Exp/Cntr=0.3,0.1

Type RM Length L Ch R = 1 ,4447    ,389,389,389
BEGIN DESCRIPTION:
Mapping XS b5623ca9
END DESCRIPTION:
XS GIS Cut Line= 4
      2049479.59     13509132.01      2049356.33     13509248.33
       2049191.4     13509638.96      2049146.01     13510180.16
#Sta/Elev= 30
  4697.4  491.71  4905.1  490.42  4939.6  489.21  4957.9  489.74  4993.5   488.3
  5080.4  488.14    5113  486.78  5113.5  485.98  5119.4  485.98  5119.9  486.78
  5199.8  487.76  5222.1  486.99  5240.4  488.24  5264.1  488.45    5415  488.37
  5429.9  487.57  5437.5  488.49  5447.5  487.01  5457.5  487.06  5477.6  489.84
  5527.8  491.18  5567.9  490.44    5598  487.56    5608  488.75  5618.1  488.66
  5638.2  491.43  5658.2  492.21  5718.4  492.62  5758.6  491.21    5834  492.05
#Mann= 4 ,-1 , 0
  4697.4      .1       0    5113     .07       0  5119.9      .1       0
    5415     .05       0
Bank Sta=5113,5119.9
XS Rating Curve= 0 ,0
Exp/Cntr=0.3,0.1

Type RM Length L Ch R = 1 ,4058    ,414,414,414
BEGIN DESCRIPTION:
Mapping XS b781ba26
END DESCRIPTION:
XS GIS Cut Line= 4
      2049281.66      13508977.5      2049151.47      13509020.9
      2048866.75     13509250.07      2048666.76     13509951.18
#Sta/Elev= 30
  4681.9  491.07  4762.7  489.01  4848.1  487.78  4902.3  485.38  4926.5  485.29
  4932.9  485.92  4982.5  484.47  4996.9  483.34  5019.3  483.03  5040.1  483.87
  5079.8  482.76  5080.3  481.96  5086.2  481.96  5086.7  482.76  5153.7  485.01
  5200.1  484.91  5212.5  483.76  5231.3  484.84  5280.1  485.62  5324.9  485.36
    5353  485.99  5376.9  485.51  5464.9   486.5  5510.3  485.91  5584.9  485.82
  5616.1   486.8  5668.1  487.26  5761.7  487.07    5902  488.51  5913.7  489.37
#Mann= 5 ,-1 , 0
  4681.9     .05       0  4902.3      .1       0  5079.8     .07       0
  5086.7      .1       0  5510.3     .05       0
Bank Sta=5079.8,5086.7
XS Rating Curve= 0 ,0
Exp/Cntr=0.3,0.1

Type RM Length L Ch R = 1 ,3644    ,266,266,266
BEGIN DESCRIPTION:
Mapping XS 3827ac74
END DESCRIPTION:
XS GIS Cut Line= 4
       2049087.2     13508654.59      2048760.69     13508776.71
      2048666.94     13508957.26      2048529.84       13509767.
#Sta/Elev= 30
  4556.1  489.71  4713.8  485.11    4744  484.99  4774.3  484.01  4793.3  482.15
  4804.6  482.06  4814.7  483.44  4829.6   482.6  4884.8   483.6    4968   481.8
  4981.6  481.25  4990.1  479.08  5000.7  478.11  5001.2  477.31  5007.2  477.31
  5007.7  478.11  5012.3  480.47  5017.9  480.16  5026.7  482.75  5041.8  482.45
  5071.8  480.94  5136.3   483.1  5176.8   481.8    5211  483.57    5400  485.44
  5460.8   485.4  5537.3  483.65  5623.1  483.56  5804.6  487.59  5929.4  488.82
#Mann= 5 ,-1 , 0
  4556.1     .05       0  5000.7     .03       0  5007.7     .05       0
  5041.8      .1       0  5537.3     .05       0
Bank Sta=5000.7,5007.7
XS Rating Curve= 0 ,0
Exp/Cntr=0.3,0.1

Type RM Length L Ch R = 1 ,3378    ,38,38,38
BEGIN DESCRIPTION:
Mapping XS 9b9b76ef
END DESCRIPTION:
XS GIS Cut Line= 5
      2048879.05     13508470.24      2048520.24     13508683.83
      2048457.74     13508802.75      2048433.43     13508936.43
      2048310.55     13509340.26
#Sta/Elev= 30
  4481.6  487.22  4597.7  484.07  4661.9  483.19  4778.7  482.12  4852.7  482.31
  4889.7  480.65    4925  480.86  4941.4   477.4    5010  477.28  5010.5  476.48
  5016.5  476.48    5017  477.28  5037.2  478.02    5046  479.56  5066.3   484.8
  5074.1  484.76  5086.6  481.64    5107  480.62  5188.8   482.3  5220.5  480.67
  5241.1  480.68  5253.3  481.25    5319  481.06  5384.7  482.77  5408.3  482.29
  5450.1  482.61  5460.9  482.04  5512.8  483.34  5544.2     485  5591.5  485.12
#Mann= 3 ,-1 , 0
  4481.6     .05       0    5010     .03       0    5017     .05       0
Bank Sta=5010,5017
XS Rating Curve= 0 ,0
Exp/Cntr=0.3,0.1

Type RM Length L Ch R = 1 ,3340    ,27,27,27
BEGIN DESCRIPTION:
Mapping XS 986375ff
END DESCRIPTION:
XS GIS Cut Line= 5
      2048840.03     13508457.19      2048469.02     13508672.54
       2048412.6     13508832.26      2048416.07     13508906.92
      2048286.64       13509297.
#Sta/Elev= 30
  4474.1  486.56    4563  484.28  4630.2  484.27  4878.5  480.49  4916.3  481.42
  4937.5  483.95  4962.1     484  4987.7  483.05    4993  483.93  5011.7  483.01
  5018.6  483.13  5023.9  484.01  5043.6  484.51  5049.6  484.26  5054.9  482.68
  5071.3   481.5  5095.2  480.79  5111.8  479.66  5112.3  478.86  5118.3  478.86
  5118.8  479.66  5125.3  480.57  5163.7  482.07  5200.7  480.63  5295.7  482.49
    5377   481.6  5440.2  482.02  5492.9  483.29  5524.5  485.47  5558.2  485.31
#Mann= 3 ,-1 , 0
  4474.1     .05       0  5111.8     .03       0  5118.8     .05       0
Bank Sta=5111.8,5118.8
XS Rating Curve= 0 ,0
Exp/Cntr=0.3,0.1

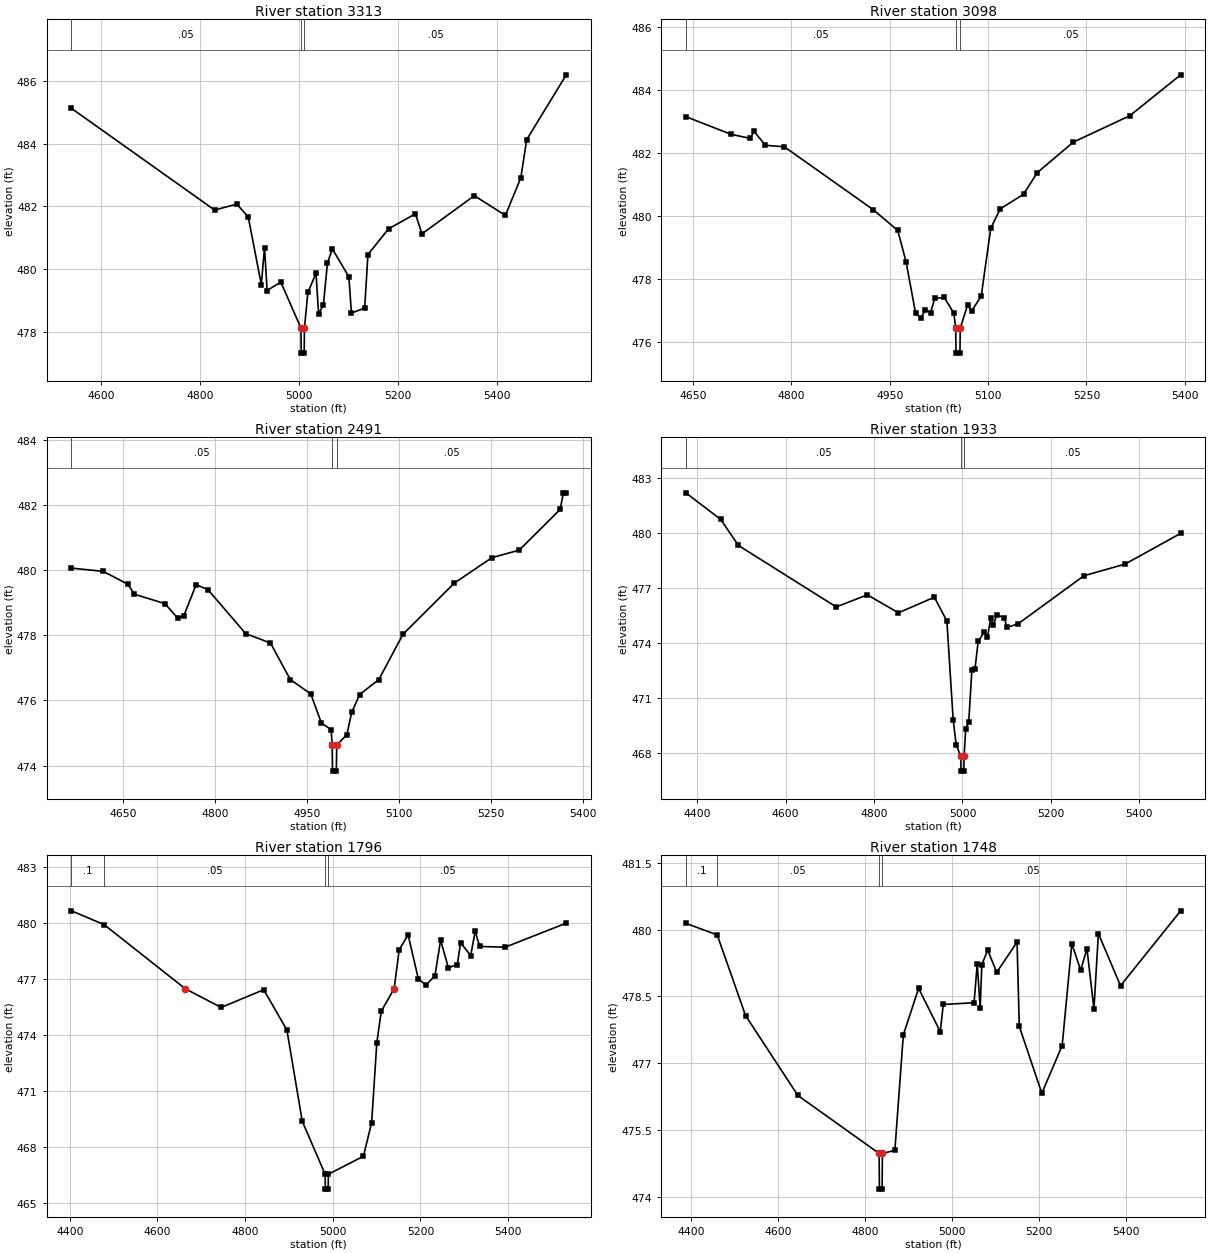
Type RM Length L Ch R = 1 ,3313    ,215,215,215
BEGIN DESCRIPTION:
Mapping XS bd8ae884
END DESCRIPTION:
XS GIS Cut Line= 5
      2048722.84     13508450.68      2048447.32     13508635.22
      2048392.64     13508815.77      2048358.24     13508932.46
      2048241.24     13509270.47
#Sta/Elev= 30
  4540.8  485.13  4830.1  481.88  4874.9  482.07    4898  481.66  4924.4   479.5
  4930.9  480.68  4936.1  479.31  4963.8  479.58  5004.5  478.11    5005  477.31
    5011  477.31  5011.5  478.11  5018.5  479.25  5034.9  479.86  5040.1  478.57
  5049.8  478.85    5058  480.19  5067.9  480.64  5101.2  479.75  5106.5  478.59
  5133.2  478.75  5139.8  480.46  5181.4  481.28  5235.7  481.76  5248.9  481.12
  5354.7  482.34  5417.4  481.71  5448.6  482.91  5460.5  484.13  5540.4   486.2
#Mann= 3 ,-1 , 0
  4540.8     .05       0  5004.5     .03       0  5011.5     .05       0
Bank Sta=5004.5,5011.5
XS Rating Curve= 0 ,0
Exp/Cntr=0.3,0.1

Type RM Length L Ch R = 1 ,3098    ,607,607,607
BEGIN DESCRIPTION:
Mapping XS ecfc963c
END DESCRIPTION:
XS GIS Cut Line= 4
      2048530.58     13508471.66      2048291.94     13508574.45
      2048113.12      13508812.3      2048074.85     13509005.54
#Sta/Elev= 30
  4639.3  483.16  4708.1   482.6  4737.1  482.47  4743.4  482.69  4760.6  482.25
  4789.6   482.2  4925.1   480.2  4962.4  479.54    4975  478.55  4989.6  476.91
  4997.9  476.75  5004.2  477.02  5012.4  476.93  5018.8  477.38  5033.3  477.41
  5047.9  476.91  5050.7  476.44  5051.2  475.64  5057.2  475.64  5057.7  476.44
  5068.8  477.16    5075  476.98  5089.6  477.45  5104.2  479.61  5118.7  480.23
  5154.1  480.69  5175.1  481.38    5230  482.35  5316.2  483.19  5393.7  484.49
#Mann= 3 ,-1 , 0
  4639.3     .05       0  5050.7     .03       0  5057.7     .05       0
Bank Sta=5050.7,5057.7
XS Rating Curve= 0 ,0
Exp/Cntr=0.3,0.1

Type RM Length L Ch R = 1 ,2491    ,558,558,558
BEGIN DESCRIPTION:
Mapping XS 433fc39d
END DESCRIPTION:
XS GIS Cut Line= 4
      2048236.33     13508177.38      2047899.58     13508226.36
      2047704.27     13508283.65      2047585.29      13508518.5
#Sta/Elev= 30
  4565.8  480.06  4617.7  479.96  4658.3  479.56  4668.2  479.26  4718.3  478.97
  4738.9  478.53    4749  478.59  4769.2  479.55  4788.4   479.4  4850.1  478.05
  4890.5  477.76  4922.8  476.64  4956.2   476.2  4973.4  475.31  4989.5   475.1
  4991.1  474.63  4991.7  473.83  4997.9  473.83  4998.5  474.63  5015.1  474.95
  5022.9  475.63  5035.9  476.18  5067.2  476.64  5106.6  478.03  5190.3   479.6
  5251.6  480.38  5296.1  480.61  5362.9  481.86  5368.2  482.37  5372.9  482.37
#Mann= 3 ,-1 , 0
  4565.8     .05       0  4991.1     .03       0  4998.5     .05       0
Bank Sta=4991.1,4998.5
XS Rating Curve= 0 ,0
Exp/Cntr=0.3,0.1

Type RM Length L Ch R = 1 ,1933    ,137,137,137
BEGIN DESCRIPTION:
Mapping XS 80bcc3d2
END DESCRIPTION:
XS GIS Cut Line= 4
      2048103.53     13507669.57      2047568.85     13507723.76
      2047458.61     13507839.21      2047317.06     13508237.24
#Sta/Elev= 30
  4374.2  482.18  4453.1  480.73  4493.3  479.31  4714.5  475.96  4784.8  476.62
  4855.2  475.64  4936.5  476.49  4964.8  475.19    4979  469.82  4985.9  468.45
  4996.3  467.81  4996.9  467.01  5003.2  467.01  5003.7  467.81  5007.3  469.29
  5014.2  469.69  5021.4  472.53  5028.3  472.57  5035.6  474.08  5049.7  474.61
  5056.6  474.32  5063.9  475.35  5070.2  474.98  5077.4  475.53  5095.1  475.37
  5100.4  474.84    5126  475.04  5274.9  477.66  5367.4  478.29  5493.7  479.97
#Mann= 3 ,-1 , 0
  4374.2     .05       0  4996.3     .03       0  5003.7     .05       0
Bank Sta=4996.3,5003.7
XS Rating Curve= 0 ,0
Exp/Cntr=0.3,0.1

Type RM Length L Ch R = 1 ,1796    ,48,48,48
BEGIN DESCRIPTION:
Mapping XS 7e0d54b4
END DESCRIPTION:
XS GIS Cut Line= 4
      2047968.04       13507555.      2047482.91     13507634.35
      2047370.07     13507727.23      2047272.76     13508208.67
#Sta/Elev= 30
  4403.9  480.64  4478.5   479.9 4663.69476.4626  4745.5  475.46  4842.7  476.41
  4895.5  474.25  4930.5  469.36  4982.7  466.52  4983.3  465.72  4989.6  465.72
  4990.2  466.52    5070  467.48  5088.8  469.28  5100.6  473.56  5110.8  475.26
 5140.11476.4619  5151.6  478.55    5172  479.35  5195.4  476.99  5212.8  476.66
  5233.2  477.16  5246.2  479.07  5263.8  477.59  5284.2  477.76  5291.8  478.93
  5314.8  478.24    5325  479.55  5335.2  478.73  5393.3  478.69  5532.8  479.98
#Mann= 4 ,-1 , 0
  4403.9      .1       0  4478.5     .05       0  4982.7     .03       0
  4990.2     .05       0
Bank Sta=4663.69,5140.11
XS Rating Curve= 0 ,0
Exp/Cntr=0.3,0.1

Type RM Length L Ch R = 1 ,1748    ,47,47,47
BEGIN DESCRIPTION:
Mapping XS 9af69c82
END DESCRIPTION:
XS GIS Cut Line= 4
      2047942.08     13507526.34      2047467.29     13507563.17
      2047324.93     13507715.08      2047239.09     13508160.88
#Sta/Elev= 30
  4387.6  480.14  4459.8  479.88  4525.1  478.07  4645.4  476.28  4832.3  474.98
  4832.9  474.18  4839.2  474.18  4839.8  474.98  4868.5  475.05    4888  477.64
  4923.2  478.68    4973  477.71  4979.8  478.32  5050.7  478.36    5058  479.23
  5064.8  478.24  5068.5  479.21  5082.1  479.54  5102.8  479.04  5149.6  479.72
  5154.7  477.83  5206.6  476.33  5253.4   477.4  5275.6  479.68    5296  479.09
  5310.4  479.57  5326.5  478.22  5336.7  479.91  5387.6  478.74    5526  480.42
#Mann= 4 ,-1 , 0
  4387.6      .1       0  4459.8     .05       0  4832.3     .03       0
  4839.8     .05       0
Bank Sta=4832.3,4839.8
XS Rating Curve= 0 ,0
Exp/Cntr=0.3,0.1