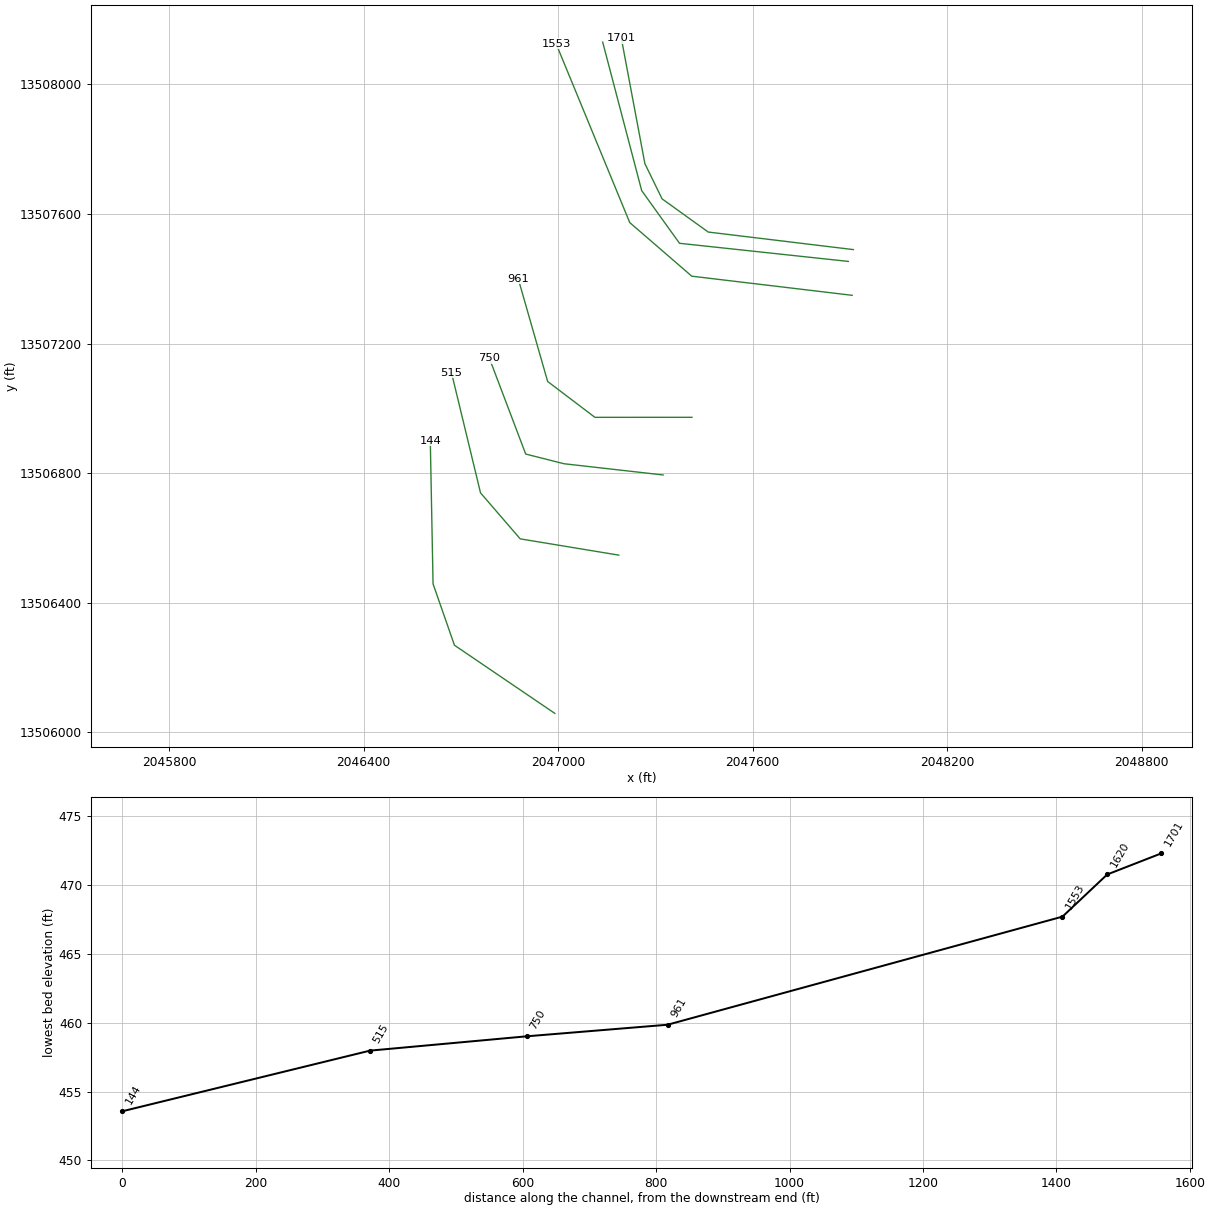
HEC-RAS study UNT 42 in Lagunillas Cr Wtrshd.prj: UNT 42 in Lagunillas Cr Wtrshd Base Level Engineering

--- UNT 42 in Lagunillas Cr Wtrshd.g01 (geometry) --- (continued)

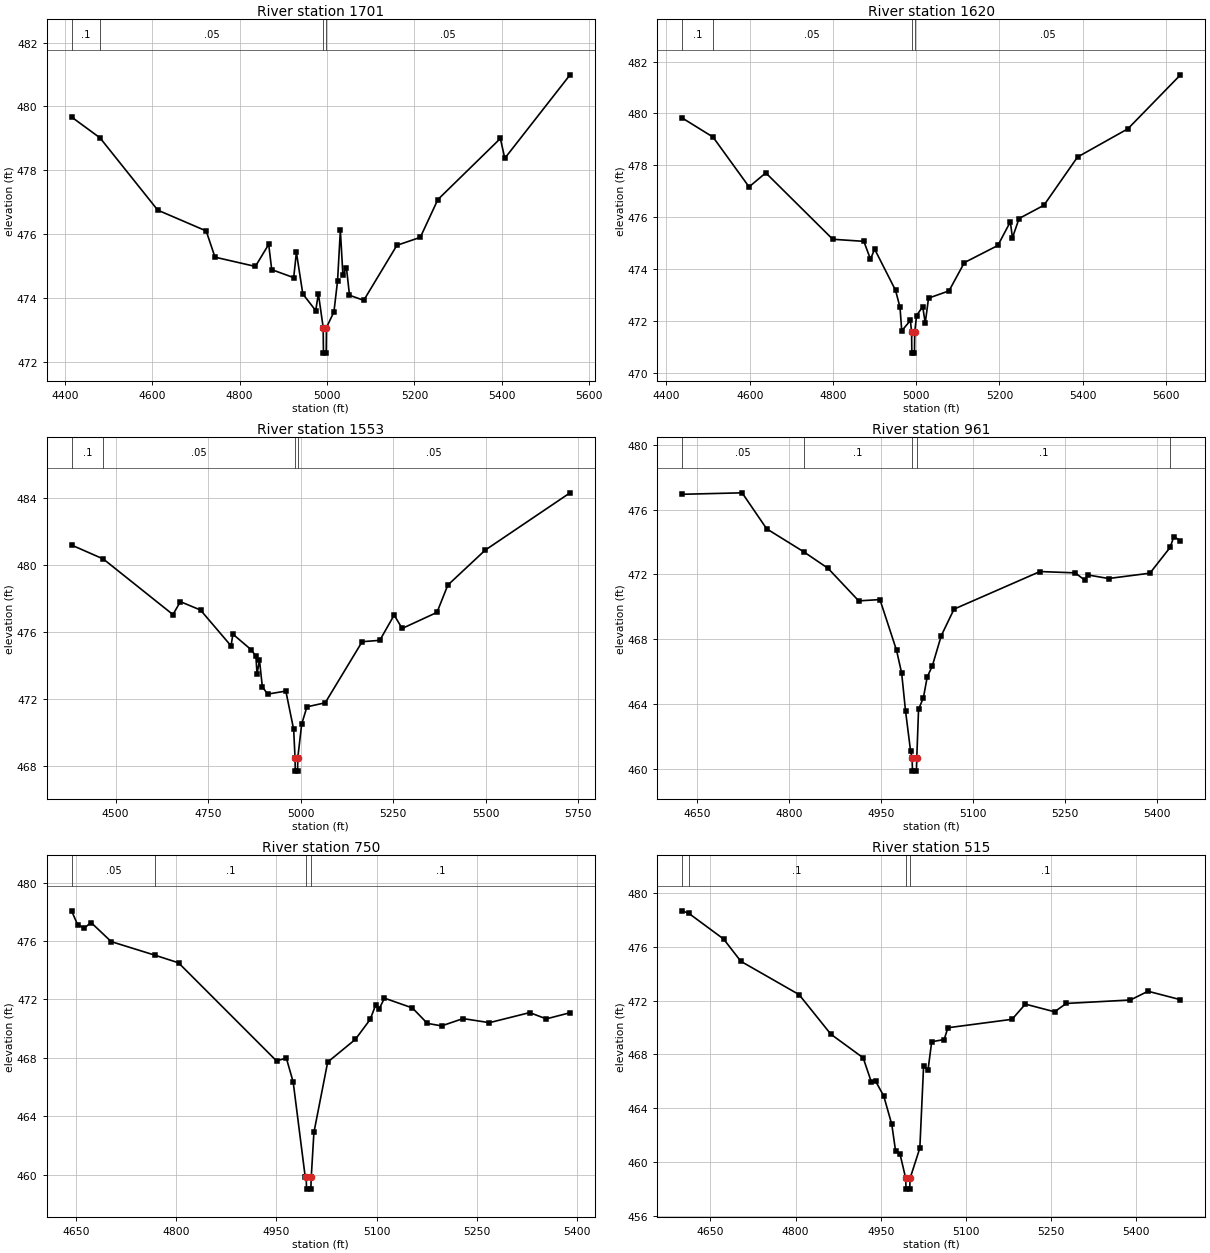
Type RM Length L Ch R = 1 ,1701    ,81,81,81
BEGIN DESCRIPTION:
Mapping XS 0a5aa8e9
END DESCRIPTION:
XS GIS Cut Line= 5
       2047910.8     13507489.88      2047462.95     13507544.07
      2047320.59      13507646.5      2047267.64     13507755.01
      2047194.97      13508141.8
#Sta/Elev= 30
  4415.5  479.67  4480.5  479.02  4612.7  476.76  4723.5  476.11  4743.7  475.29
  4836.1     475  4866.6  475.69  4873.5   474.9  4923.8  474.65    4930  475.44
  4944.7  474.14  4974.2  473.62  4980.3  474.15  4991.3  473.09  4991.9  472.29
  4998.2  472.29  4998.8  473.09  5015.9  473.58  5024.2  474.55  5030.6  476.13
  5036.4  474.74  5044.6  474.95  5051.5   474.1  5084.1  473.94    5160  475.66
  5213.6  475.91  5253.7  477.09  5396.8     479  5406.9  478.38  5556.3  480.99
#Mann= 4 ,-1 , 0
  4415.5      .1       0  4480.5     .05       0  4991.3     .03       0
  4998.8     .05       0
Bank Sta=4991.3,4998.8
XS Rating Curve= 0 ,0
Exp/Cntr=0.3,0.1

Type RM Length L Ch R = 1 ,1620    ,67,67,67
BEGIN DESCRIPTION:
Mapping XS 348c1057
END DESCRIPTION:
XS GIS Cut Line= 4
      2047895.17     13507453.43      2047374.41     13507509.35
      2047257.74     13507671.85      2047137.43     13508130.22
#Sta/Elev= 30
  4437.3  479.83  4511.8  479.09  4598.4  477.17  4638.6  477.71  4799.5  475.15
  4874.2  475.07  4890.1  474.38  4900.1  474.77  4950.4  473.18  4961.1  472.52
  4965.2  471.62  4986.1  472.02  4988.9  471.56  4989.5  470.76  4995.8  470.76
  4996.4  471.56  5000.9  472.21  5015.6  472.55  5021.7  471.92  5029.6  472.88
  5078.8  473.16  5115.7  474.25  5196.1  474.91  5226.1  475.82  5231.3  475.21
  5247.1  475.95  5306.8  476.46  5387.6  478.32  5508.7  479.41    5635  481.49
#Mann= 4 ,-1 , 0
  4437.3      .1       0  4511.8     .05       0  4988.9     .03       0
  4996.4     .05       0
Bank Sta=4988.9,4996.4
XS Rating Curve= 0 ,0
Exp/Cntr=0.3,0.1

Type RM Length L Ch R = 1 ,1553    ,592,592,592
BEGIN DESCRIPTION:
Mapping XS eab316db
END DESCRIPTION:
XS GIS Cut Line= 4
      2047907.05     13507348.81      2047412.28     13507407.83
      2047220.93     13507573.24      2046993.88     13508124.83
#Sta/Elev= 30
  4380.8   481.2  4466.4  480.37  4654.8  477.05  4674.9  477.82  4729.4  477.32
  4811.9  475.18  4816.9  475.88  4866.3  474.95  4879.1  474.56  4882.2   473.5
  4888.8  474.33  4896.5  472.74  4910.8   472.3  4960.1  472.48  4981.2  470.19
  4984.9   468.5  4985.5   467.7  4991.8   467.7  4992.4   468.5  5002.9  470.51
  5017.1  471.54  5066.5  471.78  5166.4  475.43  5214.1  475.51  5252.9  477.02
  5274.5  476.22  5368.7  477.18    5398  478.81  5499.2   480.9  5728.5  484.32
#Mann= 4 ,-1 , 0
  4380.8      .1       0  4466.4     .05       0  4984.9     .03       0
  4992.4     .05       0
Bank Sta=4984.9,4992.4
XS Rating Curve= 0 ,0
Exp/Cntr=0.3,0.1

Type RM Length L Ch R = 1 ,961     ,211,211,211
BEGIN DESCRIPTION:
Mapping XS 94999278
END DESCRIPTION:
XS GIS Cut Line= 4
      2047412.88     13506972.41      2047113.47     13506972.28
      2046967.64     13507082.96      2046876.89     13507399.94
#Sta/Elev= 30
  4625.7  476.94  4723.6  477.03  4763.6  474.81  4824.4  473.38  4863.6  472.37
  4913.6  470.36  4948.2  470.44  4975.3   467.3  4983.6  465.89  4989.9  463.56
  4998.1  461.09  5000.6  460.65  5001.2  459.85  5007.6  459.85  5008.2  460.65
  5011.1  463.67    5019  464.38  5025.2  465.66  5033.5  466.34  5048.1  468.21
  5068.9  469.85  5208.9  472.17  5266.3  472.09  5281.6  471.65  5287.1  471.96
  5320.6  471.74  5388.1  472.07    5421  473.66  5427.1  474.33  5437.9  474.06
#Mann= 5 ,-1 , 0
  4625.7     .05       0  4824.4      .1       0  5000.6     .07       0
  5008.2      .1       0    5421     .05       0
Bank Sta=5000.6,5008.2
XS Rating Curve= 0 ,0
Exp/Cntr=0.3,0.1

Type RM Length L Ch R = 1 ,750     ,235,235,235
BEGIN DESCRIPTION:
Mapping XS 5100bb47
END DESCRIPTION:
XS GIS Cut Line= 4
      2047323.95     13506794.46      2047018.42     13506829.05
      2046899.93       13506859.      2046787.92      13507154.7
#Sta/Elev= 30
  4643.4  478.07  4652.4  477.12  4662.5  476.89  4672.5  477.27  4702.7  475.96
  4768.9  475.02  4803.4  474.51  4950.1  467.79  4964.7  467.99    4975  466.34
    4993  459.84  4994.4  459.81    4995  459.01  5001.4  459.01    5002  459.81
    5006  462.89  5026.6  467.71  5067.9  469.26  5090.2  470.63  5098.3  471.61
  5103.7  471.36  5111.6  472.09  5153.3  471.42  5175.8  470.36  5197.1  470.19
  5229.2  470.69  5268.6  470.41  5328.9   471.1  5353.7  470.67  5389.3  471.09
#Mann= 4 ,-1 , 0
  4643.4     .05       0  4768.9      .1       0  4994.4     .07       0
    5002      .1       0
Bank Sta=4994.4,5002
XS Rating Curve= 0 ,0
Exp/Cntr=0.3,0.1

Type RM Length L Ch R = 1 ,515     ,371,371,371
BEGIN DESCRIPTION:
Mapping XS 927b8de5
END DESCRIPTION:
XS GIS Cut Line= 4
      2047187.19     13506547.07        2046883.     13506597.28
       2046760.6     13506739.21       2046670.9     13507110.61
#Sta/Elev= 30
  4599.9   478.7  4611.6  478.52  4673.1   476.6  4703.5  474.94    4806  472.46
    4862  469.51  4918.9  467.75  4933.2  465.96  4940.8  466.01  4955.1  464.91
  4969.3  462.79  4975.9  460.83  4983.6  460.62  4993.8  458.77  4994.4  457.97
  5000.8  457.97  5001.5  458.77  5018.7  461.03  5025.3  467.14    5033  466.82
  5039.6  468.95  5061.5  469.11  5068.1  469.99  5181.1  470.62  5204.5  471.75
  5255.9  471.18  5276.5   471.8  5389.6  472.06  5420.5  472.71  5477.7  472.08
#Mann= 4 ,-1 , 0
  4599.9     .05       0  4611.6      .1       0  4993.8     .07       0
  5001.5      .1       0
Bank Sta=4993.8,5001.5
XS Rating Curve= 0 ,0
Exp/Cntr=0.3,0.1

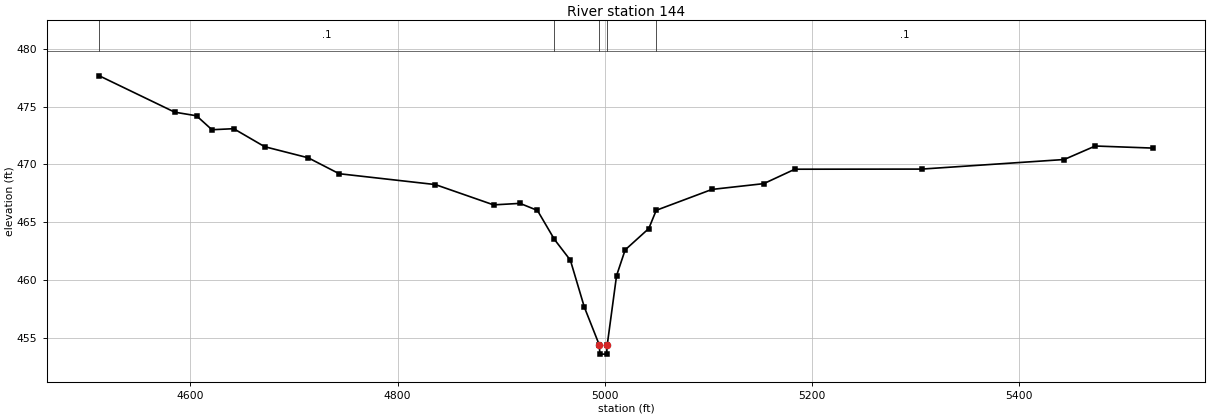
Type RM Length L Ch R = 1 ,144     ,0,0,0
BEGIN DESCRIPTION:
UNT 42 in Lagunillas Cr Wtrshd 1.0
END DESCRIPTION:
XS GIS Cut Line= 4
      2046989.76     13506058.77      2046680.16     13506269.08
      2046614.19     13506458.31      2046605.64     13506900.45
#Sta/Elev= 30
    4512  477.68  4584.8  474.53  4605.8  474.22  4620.7  473.01  4641.7   473.1
  4671.6  471.54  4713.6  470.58  4743.5   469.2  4836.3  468.26  4892.6   466.5
  4918.1  466.63  4934.9  466.02  4951.3  463.51  4966.7  461.71  4980.2  457.64
  4994.6  454.37  4995.2  453.57  5001.7  453.57  5002.3  454.37  5011.3  460.37
  5019.6   462.6  5042.4  464.45  5049.6  466.03  5103.4  467.84  5153.4  468.34
  5183.4  469.59  5305.8   469.6  5443.4  470.43  5473.4   471.6  5528.9  471.42
#Mann= 5 ,-1 , 0
    4512      .1       0  4951.3     .12       0  4994.6     .07       0
  5002.3     .12       0  5049.6      .1       0
Bank Sta=4994.6,5002.3
XS Rating Curve= 0 ,0
Exp/Cntr=0.3,0.1
LCMann Table=0

Chan Stop Cuts=-1
Use User Specified Reach Order=0
Composite Channel Slope=5