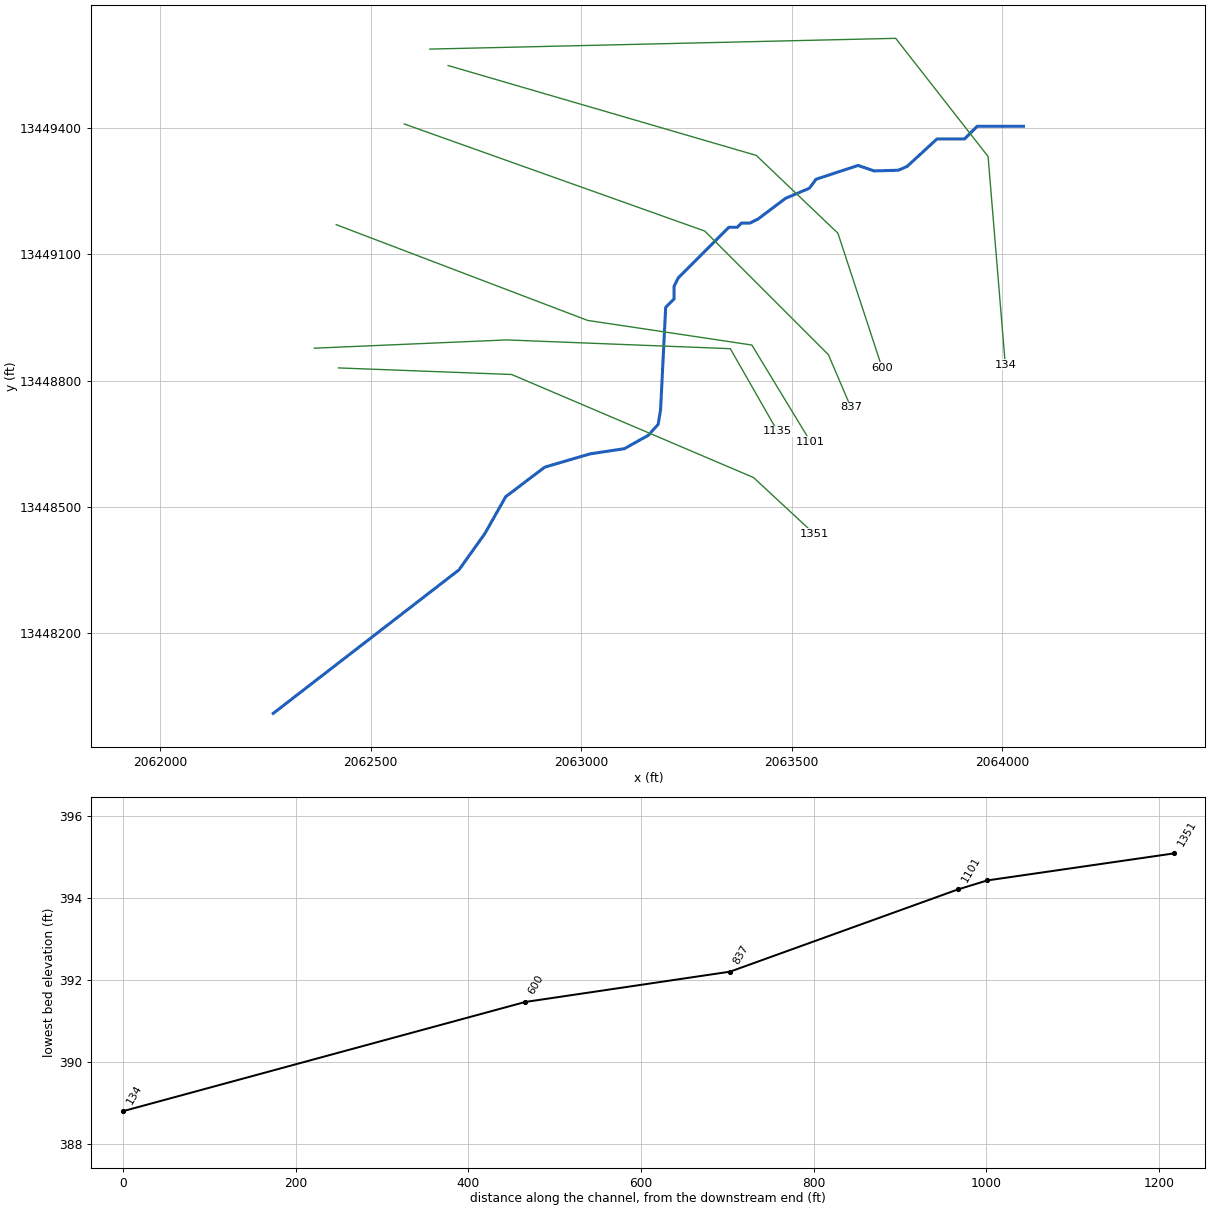
--- UNT 44 in Lagunillas Cr Wtrshd.prj (project) ---

Proj Title=UNT 44 in Lagunillas Cr Wtrshd Base Level Engineering
Current Plan=p01
Default Exp/Contr=0.3,0.1
English Units
Geom File=g01
Flow File=f01
Plan File=p01
BEGIN DESCRIPTION:
UNT 44 in Lagunillas Cr Wtrshd
END DESCRIPTION:

--- UNT 44 in Lagunillas Cr Wtrshd.p01 (plan) ---

Plan Title=Multiple Run
Short Identifier=Multiple
Geom File=g01
Flow File=f01
Subcritical Flow
K Sum by GR= 0
Std Step Tol= 0.01
Critical Tol= 0.01
Num of Std Step Trials= 20
Max Error Tol= 0.3
Flow Tol Ratio= 0.001
Split Flow NTrial= 30
Split Flow Tol= 0.02
Split Flow Ratio= 0.02
Log Output Level= 0
Friction Slope Method= 1
Unsteady Friction Slope Method= 2
Unsteady Bridges Friction Slope Method= 1
Parabolic Critical Depth
Global Vel Dist=  1 , 1 , 1
Global Log Level= 0
CheckData=True
Encroach Param= -1, 0, 0, 0
BEGIN DESCRIPTION:
Multiple Run
END DESCRIPTION:

--- UNT 44 in Lagunillas Cr Wtrshd.f01 (steady flow) ---

Flow Title=Multiple
Number of Profiles=7
Profile Names=10-year,25-year,50-year,1pct_min,100-year,1pct_plu,500-year
River Rch & RM= UNT 44 in Laguni,Reach-1,1351
     135     181     219     132     264     527     389
River Rch & RM= UNT 44 in Laguni,Reach-1,600
     221     306     377     232     464     925     710
Boundary for River Rch & Prof#=UNT 44 in Laguni,Reach-1,1
Up Type=0
Dn Type=3
Dn Slope=0.005
Boundary for River Rch & Prof#=UNT 44 in Laguni,Reach-1,2
Up Type=0
Dn Type=3
Dn Slope=0.005
Boundary for River Rch & Prof#=UNT 44 in Laguni,Reach-1,3
Up Type=0
Dn Type=3
Dn Slope=0.005
Boundary for River Rch & Prof#=UNT 44 in Laguni,Reach-1,4
Up Type=0
Dn Type=3
Dn Slope=0.005
Boundary for River Rch & Prof#=UNT 44 in Laguni,Reach-1,5
Up Type=0
Dn Type=3
Dn Slope=0.005
Boundary for River Rch & Prof#=UNT 44 in Laguni,Reach-1,6
Up Type=0
Dn Type=3
Dn Slope=0.005
Boundary for River Rch & Prof#=UNT 44 in Laguni,Reach-1,7
Up Type=0
Dn Type=3
Dn Slope=0.005

--- UNT 44 in Lagunillas Cr Wtrshd.g01 (geometry) ---

Geom Title=Existing Conditions

River Reach=UNT 44 in Laguni,Reach-1
Reach XY= 30
      2062268.54     13448009.78      2062709.68     13448350.64
      2062771.14     13448436.75      2062820.79     13448524.60
      2062913.50     13448594.74      2063021.14     13448626.33
      2063102.76     13448638.65      2063159.53     13448670.42
      2063182.97     13448696.47      2063188.70     13448730.84
      2063200.80     13448974.54      2063220.80     13448994.54
      2063220.80     13449024.54      2063230.80     13449044.54
      2063350.80     13449164.54      2063370.80     13449164.54
      2063380.80     13449174.54      2063400.80     13449174.54
      2063420.80     13449184.54      2063485.57     13449233.45
      2063542.34     13449257.40      2063557.97     13449278.76
      2063657.97     13449311.57      2063695.99     13449298.55
      2063753.28     13449300.11      2063774.12     13449308.97
      2063845.47     13449374.54      2063910.80     13449374.54
      2063940.80     13449404.54      2064050.80     13449404.54

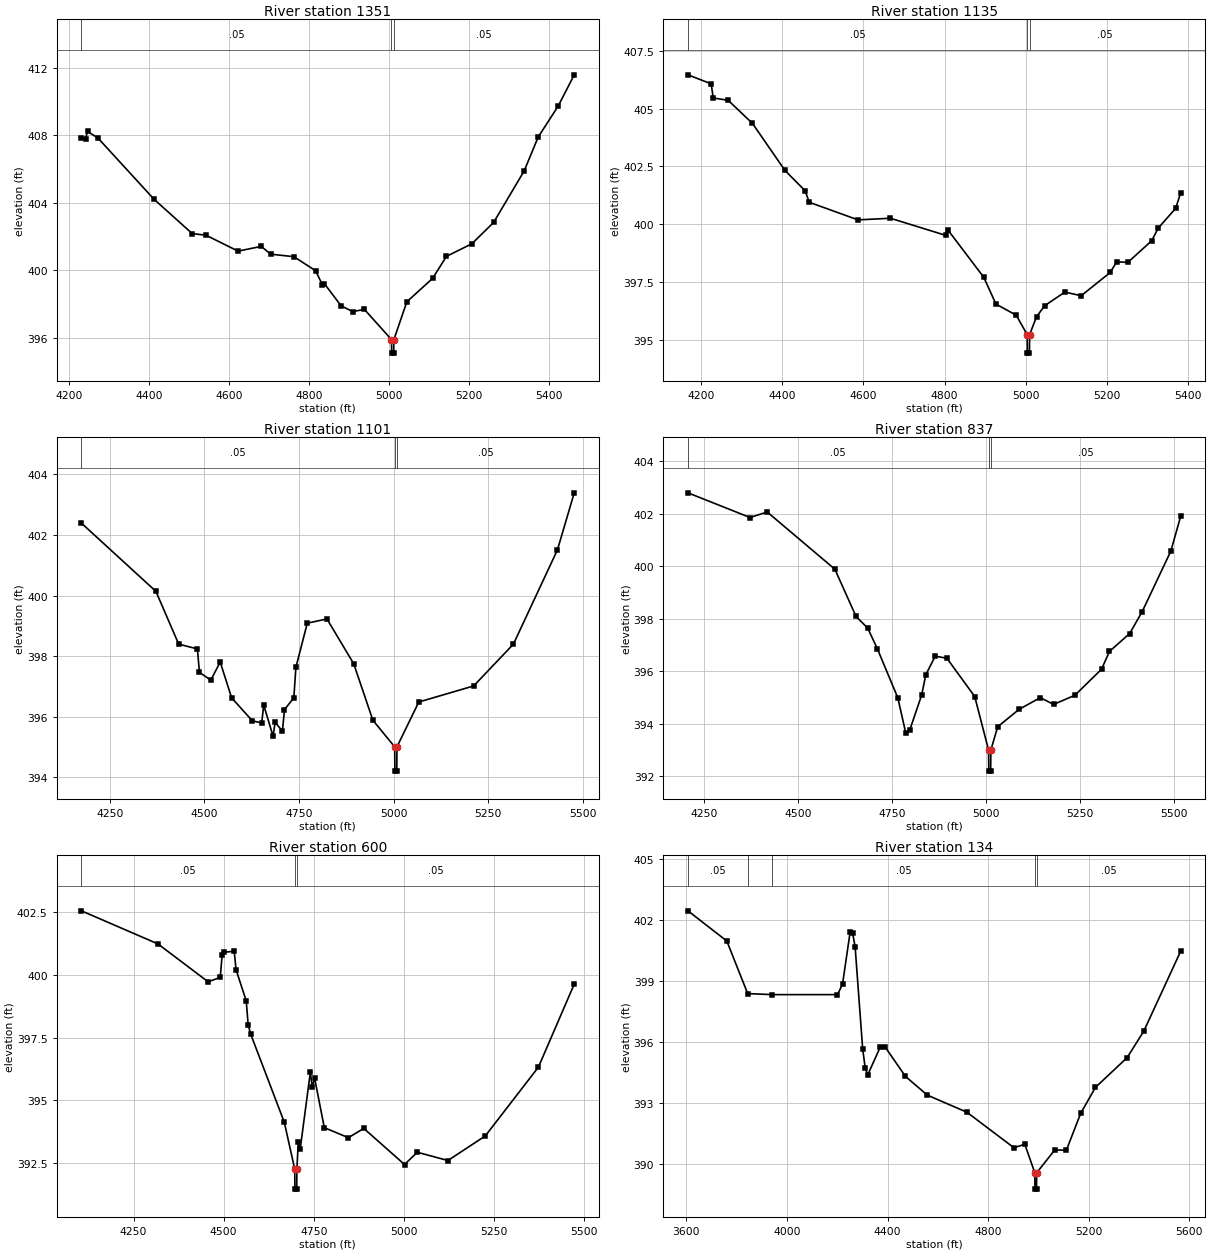
Type RM Length L Ch R = 1,1351,216,216,216
BEGIN DESCRIPTION:
UNT 44 in Lagunillas Cr Wtrshd 2.0
END DESCRIPTION:
XS GIS Cut Line= 4
      2062423.42     13448830.52      2062834.86     13448814.90
      2063409.51     13448570.11      2063553.60     13448436.43
#Sta/Elev= 30
  4231.0  407.81  4241.2  407.77  4246.2  408.22  4272.6  407.82  4412.7  404.20
  4508.1  402.17  4542.8  402.07  4622.9  401.13  4680.8  401.41  4704.5  400.95
  4762.6  400.80  4816.8  399.97  4833.5  399.15  4838.9  399.20  4880.7  397.89
  4909.8  397.55  4938.9  397.68  5006.7  395.89  5007.2  395.09  5012.2  395.09
  5012.7  395.89  5045.1  398.13  5109.7  399.52  5144.2  400.82  5208.1  401.57
  5262.2  402.83  5338.6  405.88  5373.8  407.89  5423.7  409.72  5463.9  411.57
#Mann=3,-1,0
  4231.0    0.05       0  5006.7    0.03       0  5012.7    0.05       0
Bank Sta=5006.7,5012.7
Exp/Cntr=0.3,0.1

Type RM Length L Ch R = 1,1135,34,34,34
BEGIN DESCRIPTION:
Mapping XS fb2a1695
END DESCRIPTION:
XS GIS Cut Line= 4
      2062366.09     13448877.40      2062823.15     13448897.04
      2063354.40     13448876.21      2063466.64     13448679.75
#Sta/Elev= 30
  4167.3  406.46  4224.6  406.07  4229.6  405.46  4266.3  405.36  4326.4  404.36
  4406.4  402.33  4456.1  401.45  4466.5  400.95  4586.6  400.19  4666.7  400.26
  4803.1  399.52  4808.1  399.76  4896.8  397.71  4926.9  396.55  4976.9  396.07
  5003.9  395.23  5004.4  394.43  5009.4  394.43  5009.9  395.23  5026.9  396.00
  5047.0  396.48  5097.0  397.07  5137.0  396.91  5208.9  397.92  5224.7  398.38
  5252.0  398.35  5311.1  399.29  5326.9  399.83  5370.1  400.69  5382.7  401.37
#Mann=3,-1,0
  4167.3    0.05       0  5003.9    0.03       0  5009.9    0.05       0
Bank Sta=5003.9,5009.9
Exp/Cntr=0.3,0.1

Type RM Length L Ch R = 1,1101,264,264,264
BEGIN DESCRIPTION:
Mapping XS 81d7bf77
END DESCRIPTION:
XS GIS Cut Line= 4
      2062418.16     13449170.81      2063015.41     13448943.37
      2063405.61     13448884.89      2063544.92     13448655.18
#Sta/Elev= 30
  4175.2  402.39  4372.0  400.14  4432.2  398.40  4481.7  398.24  4487.0  397.47
  4517.1  397.21  4541.9  397.81  4572.0  396.63  4626.8  395.87  4651.6  395.80
  4656.9  396.39  4681.7  395.36  4687.0  395.82  4706.4  395.53  4711.8  396.24
  4736.5  396.63  4741.9  397.63  4772.0  399.09  4824.0  399.23  4894.8  397.75
  4945.3  395.89  5003.0  395.01  5003.5  394.21  5008.5  394.21  5009.0  395.01
  5066.7  396.49  5211.7  397.02  5316.8  398.40  5433.1  401.51  5477.5  403.39
#Mann=3,-1,0
  4175.2    0.05       0  5003.0    0.03       0  5009.0    0.05       0
Bank Sta=5003,5009
Exp/Cntr=0.3,0.1

Type RM Length L Ch R = 1,837,237,237,237
BEGIN DESCRIPTION:
Mapping XS 773e8f63
END DESCRIPTION:
XS GIS Cut Line= 4
      2062579.77     13449410.05      2063293.63     13449155.72
      2063587.47     13448861.88      2063640.86     13448736.87
#Sta/Elev= 30
  4208.0  402.80  4372.8  401.86  4418.6  402.07  4598.3  399.89  4654.6  398.09
  4685.4  397.65  4710.9  396.87  4765.6  394.99  4786.8  393.64  4797.4  393.77
  4828.9  395.10  4839.9  395.87  4865.0  396.58  4895.9  396.50  4969.9  395.04
  5006.7  393.00  5007.2  392.20  5012.2  392.20  5012.7  393.00  5030.9  393.89
  5087.5  394.55  5144.1  395.00  5179.4  394.74  5236.0  395.09  5306.7  396.08
  5327.9  396.76  5381.4  397.44  5414.6  398.27  5490.9  400.58  5517.3  401.92
#Mann=3,-1,0
  4208.0    0.05       0  5006.7    0.03       0  5012.7    0.05       0
Bank Sta=5006.7,5012.7
Exp/Cntr=0.3,0.1

Type RM Length L Ch R = 1,600,466,466,466
BEGIN DESCRIPTION:
Mapping XS 3b59ecf8
END DESCRIPTION:
XS GIS Cut Line= 4
      2062683.95     13449548.93      2063416.03     13449335.41
      2063610.04     13449150.51      2063715.07     13448830.49
#Sta/Elev= 30
  4105.5  402.55  4318.0  401.23  4457.2  399.72  4490.7  399.90  4495.9  400.79
  4502.4  400.90  4529.4  400.94  4534.6  400.20  4562.8  398.96  4568.1  398.01
  4575.3  397.63  4668.5  394.12  4697.3  392.26  4697.8  391.46  4702.8  391.46
  4703.3  392.26  4707.2  393.32  4712.4  393.05  4740.7  396.12  4745.9  395.52
  4752.4  395.89  4779.4  393.91  4846.2  393.51  4888.9  393.88  5002.1  392.44
  5037.3  392.93  5122.3  392.60  5226.1  393.58  5373.4  396.32  5472.9  399.63
#Mann=3,-1,0
  4105.5    0.05       0  4697.3    0.03       0  4703.3    0.05       0
Bank Sta=4697.3,4703.3
Exp/Cntr=0.3,0.1

Type RM Length L Ch R = 1,134,0,0,0
BEGIN DESCRIPTION:
UNT 44 in Lagunillas Cr Wtrshd 1.0
END DESCRIPTION:
XS GIS Cut Line= 4
      2062640.63     13449587.98      2063747.30     13449613.54
      2063966.81     13449332.80      2064007.65     13448838.52
#Sta/Elev= 30
  3606.3  402.44  3760.7  400.96  3843.8  398.38  3942.1  398.33  4200.8  398.33
  4220.8  398.84  4250.8  401.38  4260.8  401.35  4270.8  400.69  4300.9  395.67
  4310.9  394.74  4320.9  394.39  4370.9  395.76  4390.9  395.75  4470.9  394.32
  4558.0  393.40  4715.5  392.56  4902.2  390.82  4945.6  390.99  4985.3  389.59
  4985.9  388.79  4992.1  388.79  4992.7  389.59  5065.1  390.72  5110.5  390.69
  5167.8  392.51  5226.4  393.78  5352.3  395.24  5418.6  396.54  5565.6  400.47
#Mann=5,-1,0
  3606.3    0.05       0  3843.8    0.07       0  3942.1    0.05       0
  4985.3    0.03       0  4992.7    0.05       0
Bank Sta=4985.3,4992.7
Exp/Cntr=0.3,0.1

Chan Stop Cuts=-1