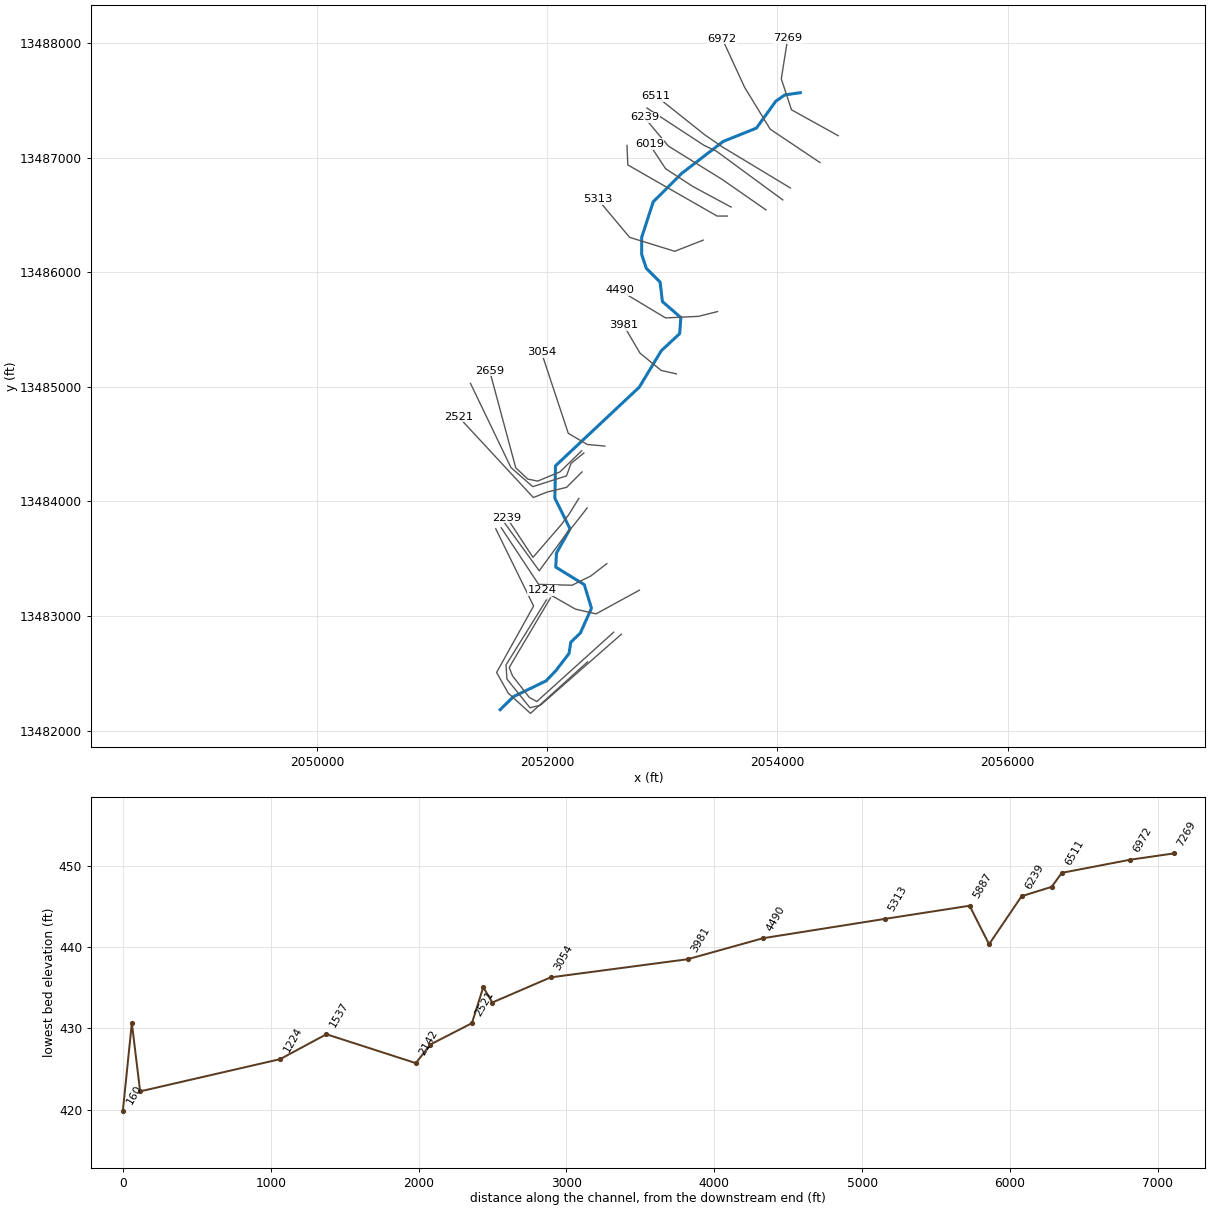
--- UNT 59 in Lagunillas Cr Wtrshd.prj (project) ---

Proj Title=UNT 59 in Lagunillas Cr Wtrshd Base Level Engineering
Current Plan=p01
Default Exp/Contr=0.3,0.1
English Units
Geom File=g01
Flow File=f01
Plan File=p01
BEGIN DESCRIPTION:
UNT 59 in Lagunillas Cr Wtrshd
END DESCRIPTION:

--- UNT 59 in Lagunillas Cr Wtrshd.p01 (plan) ---

Plan Title=Multiple Run
Short Identifier=Multiple
Geom File=g01
Flow File=f01
Subcritical Flow
K Sum by GR= 0
Std Step Tol= 0.01
Critical Tol= 0.01
Num of Std Step Trials= 20
Max Error Tol= 0.3
Flow Tol Ratio= 0.001
Split Flow NTrial= 30
Split Flow Tol= 0.02
Split Flow Ratio= 0.02
Log Output Level= 0
Friction Slope Method= 1
Unsteady Friction Slope Method= 2
Unsteady Bridges Friction Slope Method= 1
Parabolic Critical Depth
Global Vel Dist=  1 , 1 , 1
Global Log Level= 0
CheckData=True
Encroach Param= -1, 0, 0, 0
BEGIN DESCRIPTION:
Multiple Run
END DESCRIPTION:

--- UNT 59 in Lagunillas Cr Wtrshd.f01 (steady flow) ---

Flow Title=Multiple
Number of Profiles=7
Profile Names=10-year,25-year,50-year,1pct_min,100-year,1pct_plu,500-year
River Rch & RM= UNT 59 in Laguni,Reach-1,7269
     154     206     248     149     297     593     434
River Rch & RM= UNT 59 in Laguni,Reach-1,4490
     213     291     355     216     431     861     646
Boundary for River Rch & Prof#=UNT 59 in Laguni,Reach-1,1
Up Type=0
Dn Type=3
Dn Slope=0.005
Boundary for River Rch & Prof#=UNT 59 in Laguni,Reach-1,2
Up Type=0
Dn Type=3
Dn Slope=0.005
Boundary for River Rch & Prof#=UNT 59 in Laguni,Reach-1,3
Up Type=0
Dn Type=3
Dn Slope=0.005
Boundary for River Rch & Prof#=UNT 59 in Laguni,Reach-1,4
Up Type=0
Dn Type=3
Dn Slope=0.005
Boundary for River Rch & Prof#=UNT 59 in Laguni,Reach-1,5
Up Type=0
Dn Type=3
Dn Slope=0.005
Boundary for River Rch & Prof#=UNT 59 in Laguni,Reach-1,6
Up Type=0
Dn Type=3
Dn Slope=0.005
Boundary for River Rch & Prof#=UNT 59 in Laguni,Reach-1,7
Up Type=0
Dn Type=3
Dn Slope=0.005

--- UNT 59 in Lagunillas Cr Wtrshd.g01 (geometry) ---

Geom Title=Existing Conditions

River Reach=UNT 59 in Laguni,Reach-1
Reach XY= 30
      2054198.73     13487566.98      2054063.31     13487547.02
      2053986.06     13487492.33      2053817.65     13487257.96
      2053529.46     13487141.64      2053170.80     13486864.54
      2052920.80     13486614.54      2052820.80     13486304.54
      2052820.80     13486154.54      2052860.80     13486034.54
      2052980.80     13485914.54      2053000.80     13485744.54
      2053160.80     13485604.54      2053150.80     13485464.54
      2052990.80     13485314.54      2052799.87     13484997.44
      2052071.57     13484310.81      2052066.37     13484028.69
      2052198.31     13483760.46      2052080.25     13483549.52
      2052074.18     13483427.12      2052321.83     13483274.13
      2052384.33     13483068.40      2052287.97     13482852.26
      2052204.64     13482771.53      2052189.01     13482672.57
      2052074.43     13482522.83      2051989.80     13482434.29
      2051705.94     13482296.27      2051590.80     13482182.98

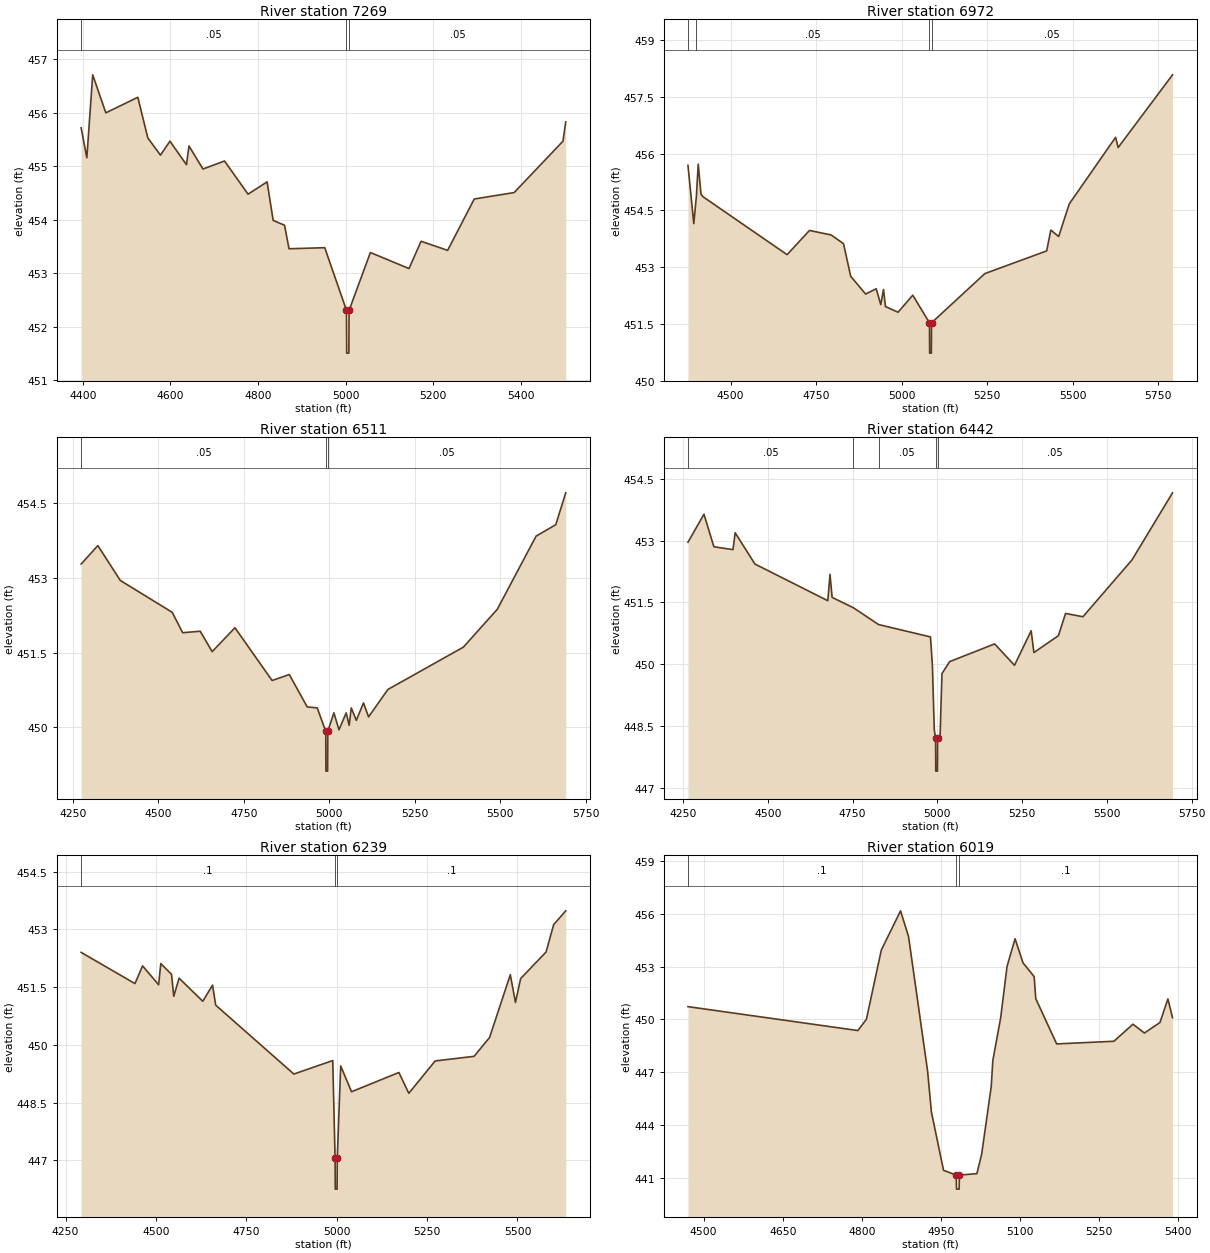
Type RM Length L Ch R = 1,7269,297,297,297
BEGIN DESCRIPTION:
UNT 59 in Lagunillas Cr Wtrshd 20.0
END DESCRIPTION:
XS GIS Cut Line= 4
      2054528.06     13487191.85      2054122.35     13487417.76
      2054033.84     13487687.89      2054089.81     13488041.26
#Sta/Elev= 30
  4396.0  455.72  4409.0  455.16  4422.4  456.71  4452.4  456.00  4525.4  456.29
  4548.3  455.53  4577.1  455.21  4598.8  455.47  4636.5  455.03  4642.2  455.38
  4674.2  454.95  4723.4  455.10  4777.1  454.48  4820.6  454.71  4834.4  453.99
  4860.4  453.90  4870.6  453.46  4952.2  453.48  5001.8  452.31  5002.3  451.51
  5007.3  451.51  5007.8  452.31  5056.4  453.39  5144.6  453.09  5172.1  453.60
  5232.8  453.43  5293.6  454.39  5384.7  454.51  5496.1  455.47  5502.4  455.83
#Mann=3,-1,0
  4396.0    0.05       0  5001.8    0.03       0  5007.8    0.05       0
Bank Sta=5001.8,5007.8
Exp/Cntr=0.3,0.1

Type RM Length L Ch R = 1,6972,461,461,461
BEGIN DESCRIPTION:
Mapping XS 389b48be
END DESCRIPTION:
XS GIS Cut Line= 4
      2054369.91     13486957.62      2053937.45     13487248.49
      2053714.80     13487614.38      2053519.84     13488039.63
#Sta/Elev= 30
  4375.2  455.69  4392.3  454.15  4400.0  454.89  4405.2  455.72  4413.3  454.93
  4419.3  454.86  4665.2  453.33  4730.6  453.97  4794.2  453.85  4830.2  453.62
  4851.2  452.76  4894.8  452.29  4925.8  452.43  4939.1  452.01  4947.1  452.41
  4952.9  451.96  4989.7  451.81  5032.8  452.26  5081.6  451.53  5082.1  450.73
  5087.1  450.73  5087.6  451.53  5243.5  452.83  5424.4  453.43  5436.5  453.98
  5459.5  453.81  5490.4  454.67  5626.0  456.43  5633.4  456.16  5792.5  458.08
#Mann=4,-1,0
  4375.2    0.08       0  4400.0    0.05       0  5081.6    0.03       0
  5087.6    0.05       0
Bank Sta=5081.6,5087.6
Exp/Cntr=0.3,0.1

Type RM Length L Ch R = 1,6511,69,69,69
BEGIN DESCRIPTION:
Mapping XS 783efd94
END DESCRIPTION:
XS GIS Cut Line= 4
      2054112.99     13486735.38      2053522.09     13487093.54
      2053371.05     13487197.71      2052946.36     13487537.43
#Sta/Elev= 30
  4273.7  453.28  4322.6  453.65  4388.3  452.95  4540.3  452.31  4570.8  451.90
  4622.2  451.93  4657.2  451.52  4723.9  452.00  4832.6  450.94  4883.0  451.06
  4935.3  450.41  4964.7  450.39  4989.6  449.92  4990.1  449.12  4995.1  449.12
  4995.6  449.92  5013.5  450.29  5028.4  449.95  5049.4  450.29  5058.2  450.04
  5064.3  450.39  5079.1  450.14  5100.1  450.49  5115.0  450.21  5171.5  450.76
  5392.4  451.61  5491.6  452.37  5605.3  453.84  5662.9  454.07  5692.0  454.71
#Mann=3,-1,0
  4273.7    0.05       0  4989.6    0.03       0  4995.6    0.05       0
Bank Sta=4989.6,4995.6
Exp/Cntr=0.3,0.1

Type RM Length L Ch R = 1,6442,203,203,203
BEGIN DESCRIPTION:
Mapping XS cd9a813b
END DESCRIPTION:
XS GIS Cut Line= 4
      2054047.02     13486631.21      2053471.31     13487055.78
      2053361.93     13487107.87      2052866.43     13487433.32
#Sta/Elev= 30
  4264.3  452.96  4311.5  453.64  4340.8  452.85  4397.2  452.78  4403.5  453.19
  4461.9  452.43  4676.8  451.54  4683.3  452.18  4689.5  451.62  4752.0  451.37
  4826.6  450.96  4979.6  450.66  4985.3  449.97  4990.8  448.41  4994.7  448.20
  4995.2  447.40  5000.2  447.40  5000.7  448.20  5008.0  448.26  5013.5  449.77
  5036.2  450.06  5168.9  450.49  5227.5  449.97  5276.6  450.81  5284.7  450.28
  5357.0  450.69  5378.1  451.23  5429.3  451.15  5574.0  452.53  5693.6  454.16
#Mann=5,-1,0
  4264.3    0.05       0  4752.0     0.1       0  4826.6    0.05       0
  4994.7    0.03       0  5000.7    0.05       0
Bank Sta=4994.7,5000.7
Exp/Cntr=0.3,0.1

Type RM Length L Ch R = 1,6239,220,220,220
BEGIN DESCRIPTION:
Mapping XS 7b1e740e
END DESCRIPTION:
XS GIS Cut Line= 4
      2053901.03     13486543.97      2053520.83     13486809.60
      2053052.08     13487101.26      2052844.26     13487350.64
#Sta/Elev= 30
  4293.0  452.40  4441.9  451.59  4462.9  452.05  4507.3  451.56  4513.4  452.11
  4543.1  451.83  4549.2  451.26  4564.0  451.73  4629.5  451.13  4656.5  451.55
  4665.2  451.03  4881.4  449.24  4989.0  449.59  4995.5  447.05  4996.0  446.25
  5001.0  446.25  5001.5  447.05  5011.0  449.45  5041.0  448.78  5172.0  449.28
  5199.4  448.74  5272.3  449.58  5380.0  449.70  5422.9  450.19  5480.2  451.82
  5494.5  451.10  5508.8  451.72  5579.1  452.41  5600.1  453.12  5633.5  453.48
#Mann=3,-1,0
  4293.0     0.1       0  4995.5    0.07       0  5001.5     0.1       0
Bank Sta=4995.5,5001.5
Exp/Cntr=0.3,0.1

Type RM Length L Ch R = 1,6019,132,132,132
BEGIN DESCRIPTION:
Mapping XS 865d2901
END DESCRIPTION:
XS GIS Cut Line= 4
      2053597.57     13486568.82      2053265.58     13486748.49
      2053028.60     13486903.44      2052886.68     13487119.58
#Sta/Elev= 30
  4470.2  450.73  4792.5  449.37  4808.7  450.01  4837.0  453.95  4873.5  456.18
  4888.6  454.72  4924.8  447.06  4932.0  444.74  4955.0  441.42  4979.1  441.15
  4979.6  440.35  4984.6  440.35  4985.1  441.15  5018.3  441.23  5027.4  442.35
  5045.5  446.19  5048.5  447.66  5063.4  450.10  5075.5  453.02  5090.7  454.59
  5105.8  453.22  5126.9  452.44  5130.0  451.18  5169.6  448.61  5278.1  448.76
  5314.3  449.73  5336.1  449.23  5365.6  449.83  5380.6  451.17  5389.4  450.10
#Mann=3,-1,0
  4470.2     0.1       0  4979.1    0.07       0  4985.1     0.1       0
Bank Sta=4979.1,4985.1
Exp/Cntr=0.3,0.1

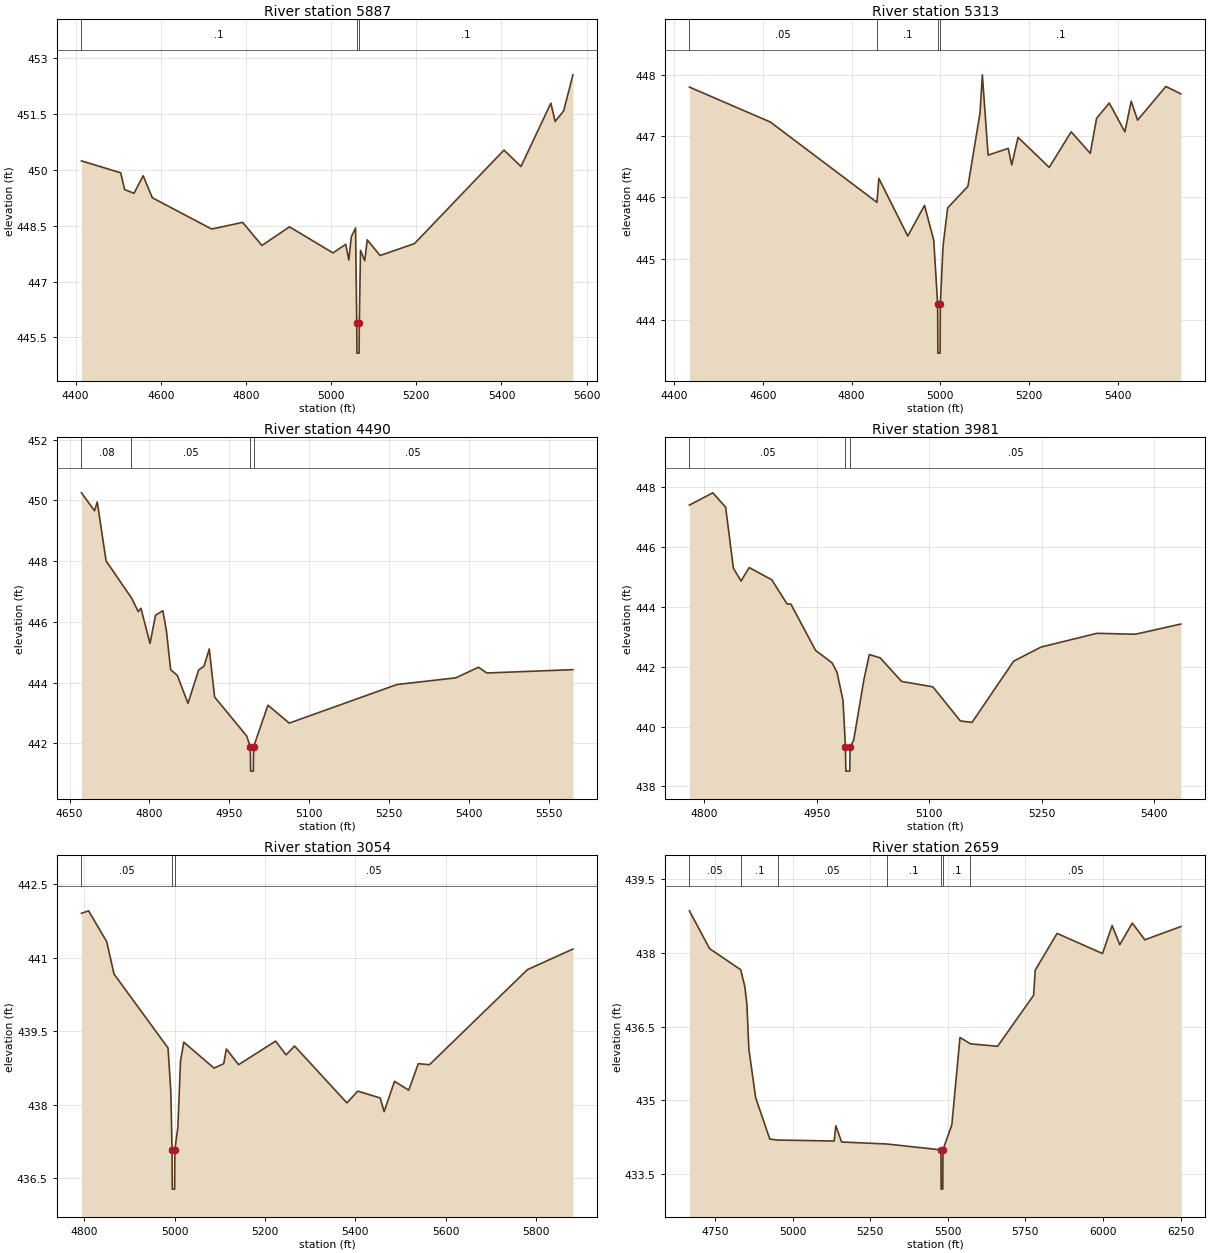
Type RM Length L Ch R = 1,5887,574,574,574
BEGIN DESCRIPTION:
Mapping XS 5fa5b970
END DESCRIPTION:
XS GIS Cut Line= 4
      2053564.73     13486490.45      2053476.17     13486490.45
      2052700.13     13486936.63      2052693.18     13487106.77
#Sta/Elev= 30
  4413.8  450.24  4505.9  449.92  4515.2  449.47  4537.1  449.37  4558.6  449.84
  4580.2  449.25  4719.6  448.41  4792.1  448.59  4837.5  447.97  4902.2  448.47
  5004.3  447.77  5034.3  448.00  5041.6  447.58  5047.4  448.20  5057.4  448.44
  5060.2  445.88  5060.7  445.08  5065.7  445.08  5066.2  445.88  5069.0  447.84
  5079.0  447.56  5084.8  448.12  5115.1  447.70  5195.8  448.02  5405.9  450.53
  5445.9  450.09  5516.0  451.79  5526.0  451.30  5546.0  451.58  5567.8  452.55
#Mann=3,-1,0
  4413.8     0.1       0  5060.2    0.07       0  5066.2     0.1       0
Bank Sta=5060.2,5066.2
Exp/Cntr=0.3,0.1

Type RM Length L Ch R = 1,5313,823,823,823
BEGIN DESCRIPTION:
Mapping XS c7158689
END DESCRIPTION:
XS GIS Cut Line= 4
      2053354.75     13486280.25      2053108.24     13486183.04
      2052715.88     13486304.57      2052439.02     13486636.80
#Sta/Elev= 30
  4434.1  447.80  4616.6  447.23  4857.1  445.92  4861.3  446.31  4926.5  445.37
  4964.3  445.87  4985.1  445.30  4993.9  444.26  4994.4  443.46  4999.4  443.46
  4999.9  444.26  5006.1  445.21  5016.5  445.83  5062.1  446.18  5089.5  447.38
  5094.7  448.00  5107.7  446.69  5153.1  446.80  5160.9  446.53  5175.2  446.98
  5245.5  446.49  5295.0  447.07  5338.0  446.72  5352.3  447.29  5380.9  447.54
  5416.1  447.07  5430.4  447.57  5444.7  447.26  5508.5  447.81  5542.3  447.69
#Mann=4,-1,0
  4434.1    0.05       0  4857.1     0.1       0  4993.9    0.07       0
  4999.9     0.1       0
Bank Sta=4993.9,4999.9
Exp/Cntr=0.3,0.1

Type RM Length L Ch R = 1,4490,509,509,509
BEGIN DESCRIPTION:
Mapping XS b7d2bd74
END DESCRIPTION:
XS GIS Cut Line= 4
      2053479.76     13485656.99      2053314.84     13485615.33
      2053028.38     13485601.44      2052629.56     13485842.47
#Sta/Elev= 30
  4672.5  450.25  4697.0  449.66  4702.1  449.95  4718.7  448.01  4766.4  446.79
  4779.1  446.34  4784.2  446.45  4801.2  445.29  4811.5  446.22  4825.3  446.37
  4832.1  445.70  4839.9  444.43  4852.5  444.24  4872.5  443.32  4892.5  444.42
  4902.5  444.54  4912.5  445.11  4922.5  443.53  4982.6  442.25  4989.6  441.89
  4990.1  441.09  4995.2  441.09  4995.7  441.89  5022.7  443.26  5062.7  442.67
  5264.8  443.94  5375.4  444.16  5418.1  444.51  5433.6  444.32  5595.4  444.43
#Mann=4,-1,0
  4672.5    0.08       0  4766.4    0.05       0  4989.6    0.03       0
  4995.7    0.05       0
Bank Sta=4989.6,4995.7
Exp/Cntr=0.3,0.1

Type RM Length L Ch R = 1,3981,927,927,927
BEGIN DESCRIPTION:
Mapping XS 135b8624
END DESCRIPTION:
XS GIS Cut Line= 4
      2053122.17     13485113.59      2052990.19     13485143.11
      2052806.16     13485294.15      2052663.80     13485537.21
#Sta/Elev= 30
  4780.2  447.41  4811.4  447.82  4828.5  447.34  4838.8  445.30  4849.0  444.87
  4859.9  445.32  4890.0  444.91  4910.4  444.10  4915.4  444.10  4948.3  442.55
  4970.5  442.13  4977.0  441.81  4984.9  440.88  4988.2  439.31  4988.7  438.51
  4993.9  438.51  4994.4  439.31  4999.2  439.55  5012.7  441.56  5020.0  442.41
  5034.4  442.30  5063.1  441.51  5104.7  441.33  5141.3  440.19  5156.9  440.14
  5212.4  442.19  5248.9  442.66  5323.3  443.12  5374.7  443.09  5435.2  443.43
#Mann=3,-1,0
  4780.2    0.05       0  4988.2    0.03       0  4994.4    0.05       0
Bank Sta=4988.2,4994.4
Exp/Cntr=0.3,0.1

Type RM Length L Ch R = 1,3054,395,395,395
BEGIN DESCRIPTION:
Mapping XS ad2e29de
END DESCRIPTION:
XS GIS Cut Line= 4
      2052500.64     13484483.38      2052347.83     13484497.27
      2052182.90     13484594.50      2051949.98     13485300.05
#Sta/Elev= 30
  4793.6  441.91  4809.3  441.96  4849.5  441.33  4865.6  440.67  4985.2  439.16
  4991.4  438.27  4994.1  437.08  4994.6  436.28  4999.8  436.28  5000.3  437.08
  5007.0  437.55  5012.8  438.89  5020.0  439.28  5087.0  438.75  5108.5  438.84
  5114.3  439.14  5141.4  438.82  5223.3  439.30  5246.5  439.02  5265.4  439.20
  5381.2  438.04  5405.3  438.28  5455.0  438.14  5463.5  437.86  5486.5  438.48
  5518.1  438.30  5539.2  438.84  5564.0  438.82  5780.9  440.76  5881.5  441.18
#Mann=3,-1,0
  4793.6    0.05       0  4994.1    0.03       0  5000.3    0.05       0
Bank Sta=4994.1,5000.3
Exp/Cntr=0.3,0.1

Type RM Length L Ch R = 1,2659,61,61,61
BEGIN DESCRIPTION:
Mapping XS 36a76b83
END DESCRIPTION:
XS GIS Cut Line= 6
      2052299.20     13484441.71      2052109.98     13484257.69
      2051917.27     13484177.83      2051830.47     13484195.19
      2051726.30     13484294.15      2051499.78     13485139.14
#Sta/Elev= 30
  4667.8  438.86  4732.8  438.09  4833.1  437.66  4846.5  437.31  4852.9  436.96
  4859.4  436.04  4881.3  435.05  4926.8  434.21  4952.8  434.19  5134.2  434.17
  5139.6  434.48  5158.2  434.15  5302.8  434.11  5478.3  433.99  5478.8  433.19
  5484.1  433.19  5484.6  433.99  5513.2  434.50  5539.5  436.28  5573.2  436.15
  5660.7  436.10  5776.7  437.14  5781.8  437.65  5852.3  438.40  5998.6  437.99
  6029.6  438.56  6054.2  438.17  6094.6  438.61  6135.0  438.27  6251.0  438.54
#Mann=7,-1,0
  4667.8    0.05       0  4833.1     0.1       0  4952.8    0.05       0
  5302.8     0.1       0  5478.3   0.033       0  5484.6     0.1       0
  5573.2    0.05       0
Bank Sta=5478.3,5484.6
Exp/Cntr=0.3,0.1

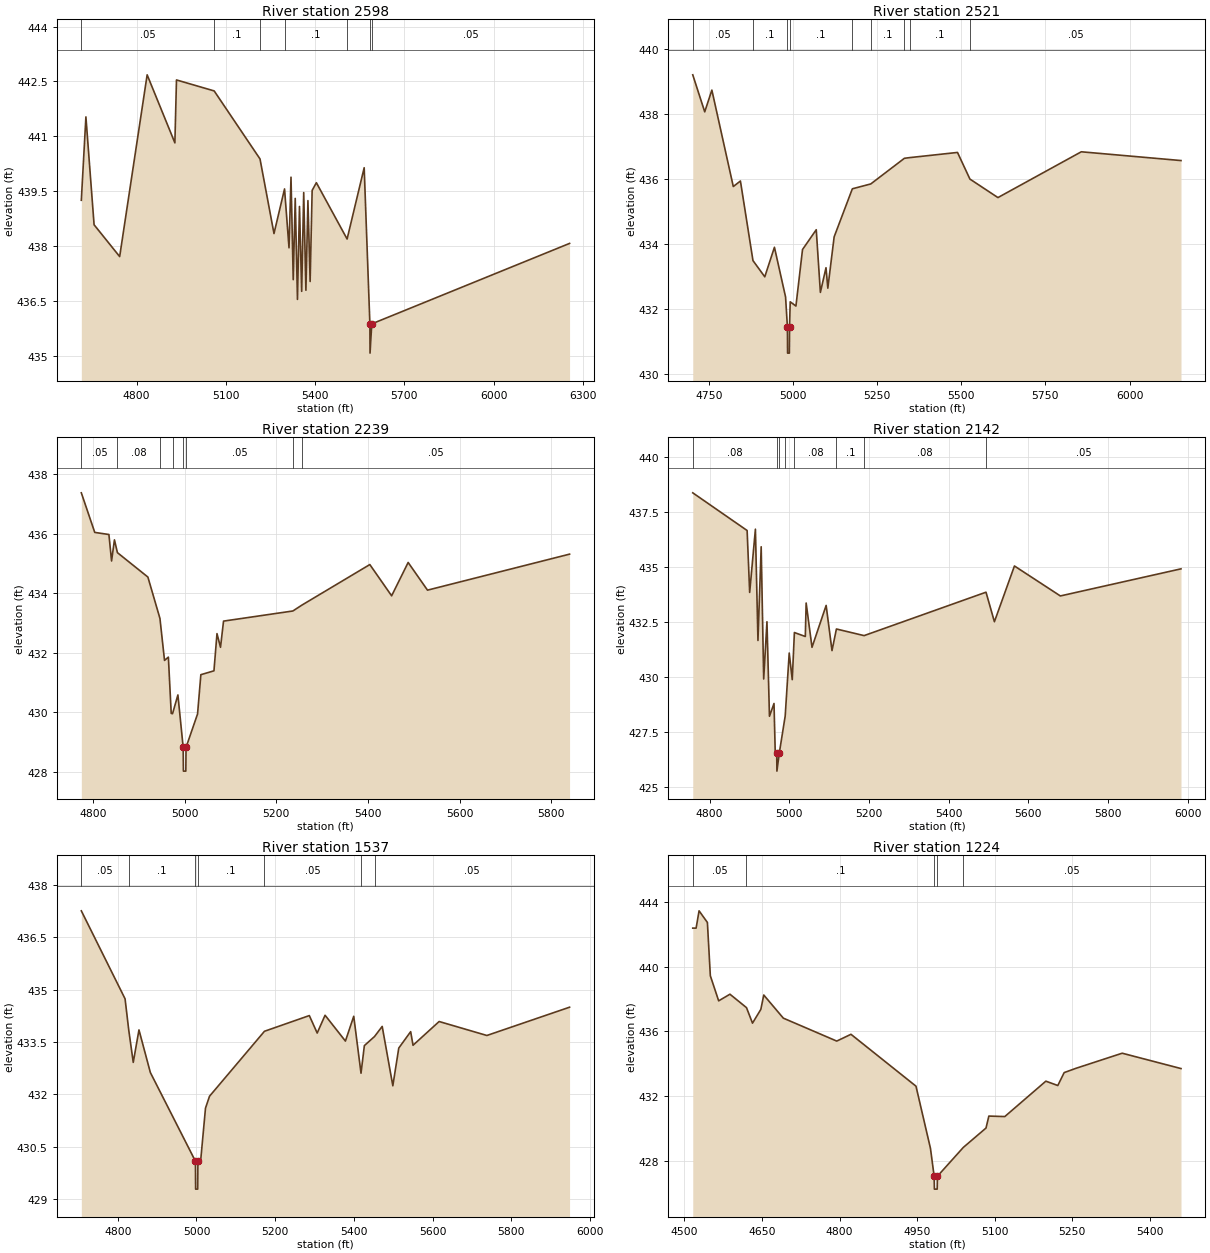
Type RM Length L Ch R = 1,2598,77,77,77
BEGIN DESCRIPTION:
Mapping XS 8bd8244d
END DESCRIPTION:
XS GIS Cut Line= 6
      2052318.33     13484422.63      2052207.20     13484332.34
      2052167.27     13484222.97      2051873.87     13484129.22
      2051684.63     13484295.89      2051333.03     13485030.30
#Sta/Elev= 30
  4614.2  439.25  4629.6  441.53  4657.1  438.58  4743.1  437.71  4835.5  442.68
  4928.7  440.82  4934.1  442.54  5060.8  442.24  5214.9  440.38  5261.9  438.34
  5297.4  439.56  5312.4  437.95  5319.1  439.88  5326.6  437.08  5333.3  439.30
  5340.8  436.54  5347.6  439.08  5355.0  436.76  5361.8  439.46  5369.2  436.79
  5376.0  439.24  5383.4  437.03  5390.2  439.52  5404.4  439.73  5507.7  438.19
  5565.1  440.14  5584.3  435.87  5584.8  435.07  5590.6  435.87  6255.6  438.07
#Mann=7,-1,0
  4614.2    0.05       0  5060.8     0.1       0  5214.9    0.05       0
  5297.4     0.1       0  5507.7    0.05       0  5584.3   0.033       0
  5590.6    0.05       0
Bank Sta=5584.3,5590.6
Exp/Cntr=0.3,0.1

Type RM Length L Ch R = 1,2521,282,282,282
BEGIN DESCRIPTION:
Mapping XS 6b1e3620
END DESCRIPTION:
XS GIS Cut Line= 5
      2052302.69     13484257.70      2052168.14     13484123.14
      2051998.87     13484081.91      2051879.51     13484034.17
      2051229.35     13484738.22
#Sta/Elev= 30
  4701.7  439.22  4737.3  438.08  4758.5  438.75  4822.2  435.78  4843.4  435.95
  4880.7  433.50  4915.8  433.00  4944.5  433.91  4977.6  432.38  4983.1  431.45
  4983.6  430.65  4988.9  430.65  4989.4  431.45  4991.4  432.23  5008.4  432.10
  5028.0  433.84  5068.8  434.45  5081.1  432.52  5097.8  433.28  5103.2  432.65
  5122.0  434.23  5176.1  435.71  5230.9  435.86  5330.9  436.65  5346.1  436.67
  5488.7  436.83  5525.6  436.01  5608.9  435.44  5856.7  436.85  6153.1  436.58
#Mann=9,-1,0
  4701.7    0.05       0  4880.7     0.1       0  4983.1    0.07       0
  4989.4     0.1       0  5176.1    0.05       0  5230.9     0.1       0
  5330.9    0.05       0  5346.1     0.1       0  5525.6    0.05       0
Bank Sta=4983.1,4989.4
Exp/Cntr=0.3,0.1

Type RM Length L Ch R = 1,2239,97,97,97
BEGIN DESCRIPTION:
Mapping XS 9900053a
END DESCRIPTION:
XS GIS Cut Line= 5
      2052274.28     13484026.67      2052189.67     13483888.68
      2052121.96     13483797.54      2051876.31     13483512.32
      2051649.24     13483858.33
#Sta/Elev= 30
  4774.3  437.37  4803.6  436.04  4834.5  435.97  4840.3  435.08  4846.6  435.79
  4853.1  435.36  4919.6  434.54  4945.9  433.15  4955.9  431.74  4964.3  431.85
  4970.5  429.96  4973.4  429.95  4985.1  430.58  4996.6  428.82  4997.1  428.02
  5002.4  428.02  5002.9  428.82  5028.0  429.94  5035.2  431.26  5063.8  431.39
  5070.4  432.64  5078.1  432.18  5084.7  433.06  5236.0  433.40  5256.0  433.60
  5404.0  434.96  5451.6  433.91  5487.7  435.03  5529.9  434.10  5840.0  435.31
#Mann=8,-1,0
  4774.3    0.05       0  4853.1    0.08       0  4945.9     0.1       0
  4973.4    0.05       0  4996.6    0.04       0  5002.9    0.05       0
  5236.0    0.08       0  5256.0    0.05       0
Bank Sta=4996.6,5002.9
Exp/Cntr=0.3,0.1

Type RM Length L Ch R = 1,2142,605,605,605
BEGIN DESCRIPTION:
Mapping XS 45ef453d
END DESCRIPTION:
XS GIS Cut Line= 5
      2052347.24     13483943.39      2052223.52     13483784.51
      2052170.14     13483723.32      2051930.57     13483395.13
      2051616.40     13483830.63
#Sta/Elev= 30
  4757.7  438.37  4894.2  436.66  4900.6  433.85  4915.0  436.72  4921.4  431.67
  4929.5  435.92  4935.8  429.92  4944.0  432.52  4950.3  428.23  4961.7  428.81
  4964.7  426.64  4968.5  426.54  4969.0  425.74  4974.8  426.54  4989.8  428.24
  4999.9  431.10  5007.5  429.89  5012.9  432.03  5040.3  431.85  5042.4  433.37
  5057.1  431.36  5092.6  433.26  5107.3  431.21  5118.4  432.19  5187.9  431.89
  5494.0  433.86  5515.1  432.52  5565.4  435.05  5680.7  433.69  5983.6  434.92
#Mann=8,-1,0
  4757.7    0.08       0  4968.5    0.07       0  4974.8    0.08       0
  4989.8     0.1       0  5012.9    0.08       0  5118.4     0.1       0
  5187.9    0.08       0  5494.0    0.05       0
Bank Sta=4968.5,4974.8
Exp/Cntr=0.3,0.1

Type RM Length L Ch R = 1,1537,313,313,313
BEGIN DESCRIPTION:
Mapping XS 82e5abbc
END DESCRIPTION:
XS GIS Cut Line= 5
      2052518.09     13483457.80      2052378.79     13483349.75
      2052216.03     13483269.02      2051925.33     13483276.47
      2051600.33     13483770.48
#Sta/Elev= 30
  4707.6  437.26  4818.7  434.74  4828.1  433.84  4839.5  432.92  4854.0  433.85
  4882.9  432.63  4997.4  430.09  4997.9  429.29  5003.2  429.29  5003.7  430.09
  5010.9  430.13  5023.0  431.61  5033.2  431.95  5172.7  433.81  5286.7  434.26
  5306.7  433.76  5326.7  434.27  5378.4  433.53  5399.5  434.24  5418.0  432.61
  5426.5  433.40  5452.3  433.66  5471.8  433.95  5498.8  432.25  5513.9  433.33
  5544.1  433.80  5550.1  433.41  5616.4  434.09  5737.7  433.69  5947.7  434.50
#Mann=7,-1,0
  4707.6    0.05       0  4828.1     0.1       0  4997.4    0.07       0
  5003.7     0.1       0  5172.7    0.05       0  5418.0    0.08       0
  5452.3    0.05       0
Bank Sta=4997.4,5003.7
Exp/Cntr=0.3,0.1

Type RM Length L Ch R = 1,1224,947,947,947
BEGIN DESCRIPTION:
Mapping XS fdb4e8d9
END DESCRIPTION:
XS GIS Cut Line= 4
      2052800.76     13483225.84      2052424.37     13483019.02
      2052244.68     13483060.69      2051958.34     13483224.87
#Sta/Elev= 30
  4516.1  442.38  4522.6  442.38  4528.3  443.45  4544.4  442.73  4550.1  439.43
  4566.2  437.88  4588.0  438.29  4620.0  437.46  4631.6  436.50  4647.7  437.35
  4653.4  438.24  4691.2  436.81  4794.5  435.39  4822.0  435.81  4947.7  432.60
  4975.7  428.75  4982.8  427.03  4983.3  426.23  4988.7  426.23  4989.2  427.03
  5039.2  428.81  5083.1  430.01  5088.6  430.75  5119.4  430.72  5198.8  432.91
  5221.9  432.64  5234.2  433.44  5256.5  433.70  5346.4  434.64  5460.1  433.69
#Mann=5,-1,0
  4516.1    0.05       0  4620.0     0.1       0  4982.8    0.07       0
  4989.2     0.1       0  5039.2    0.05       0
Bank Sta=4982.8,4989.2
Exp/Cntr=0.3,0.1

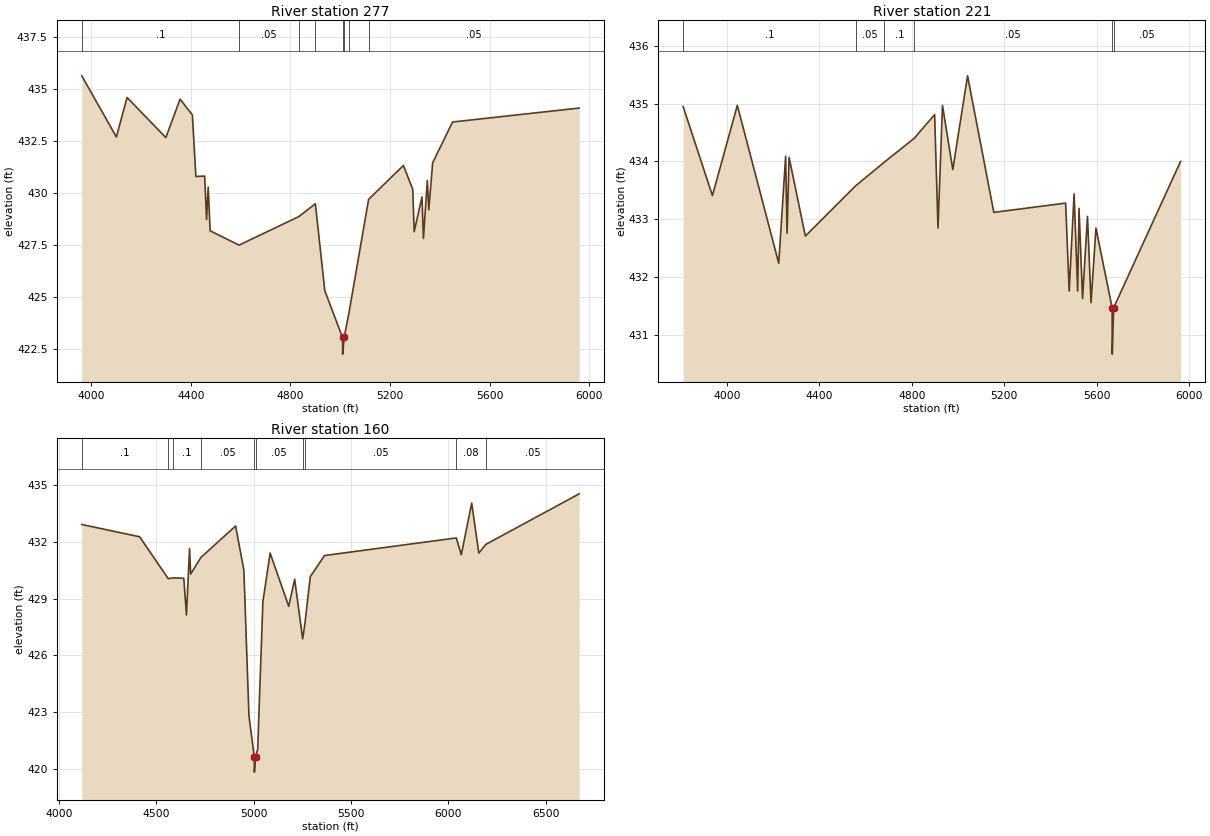
Type RM Length L Ch R = 1,277,56,56,56
BEGIN DESCRIPTION:
Mapping XS 2d835bb9
END DESCRIPTION:
XS GIS Cut Line= 6
      2052577.23     13482859.07      2051909.57     13482254.35
      2051844.07     13482290.29      2051697.80     13482479.09
      2051669.77     13482551.66      2052028.24     13483158.62
#Sta/Elev= 30
  3962.2  435.65  4101.2  432.71  4144.0  434.61  4299.9  432.68  4357.0  434.53
  4406.4  433.77  4420.6  430.81  4455.7  430.83  4463.4  428.74  4470.0  430.30
  4477.7  428.20  4594.0  427.51  4833.6  428.88  4900.5  429.50  4938.3  425.32
  5009.6  423.07  5010.1  422.27  5016.0  423.07  5034.9  424.22  5114.3  429.71
  5254.1  431.34  5291.6  430.19  5297.4  428.16  5328.7  429.83  5334.5  427.83
  5350.2  430.62  5356.0  429.21  5371.6  431.47  5451.6  433.43  5960.2  434.10
#Mann=8,-1,0
  3962.2     0.1       0  4594.0    0.05       0  4833.6     0.1       0
  4900.5    0.05       0  5009.6   0.033       0  5016.0    0.05       0
  5034.9    0.07       0  5114.3    0.05       0
Bank Sta=5009.6,5016
Exp/Cntr=0.3,0.1

Type RM Length L Ch R = 1,221,61,61,61
BEGIN DESCRIPTION:
Mapping XS 248e7e72
END DESCRIPTION:
XS GIS Cut Line= 6
      2052644.55     13482841.75      2051940.27     13482221.30
      2051850.00     13482200.00      2051650.00     13482450.00
      2051641.66     13482573.20      2051993.13     13483140.62
#Sta/Elev= 30
  3810.7  434.95  3937.5  433.41  4045.2  434.97  4224.5  432.24  4254.3  434.09
  4260.4  432.76  4269.3  434.07  4339.6  432.71  4557.5  433.58  4681.9  433.99
  4810.7  434.40  4899.1  434.81  4913.6  432.85  4933.0  434.97  4977.6  433.86
  5041.6  435.48  5155.2  433.12  5466.0  433.28  5481.3  431.76  5502.6  433.44
  5518.0  431.76  5523.9  433.19  5539.2  431.63  5560.5  433.05  5575.9  431.56
  5597.1  432.85  5667.2  431.47  5667.7  430.67  5673.6  431.47  5963.2  434.00
#Mann=6,-1,0
  3810.7     0.1       0  4557.5    0.05       0  4681.9     0.1       0
  4810.7    0.05       0  5667.2   0.033       0  5673.6    0.05       0
Bank Sta=5667.2,5673.6
Exp/Cntr=0.3,0.1

Type RM Length L Ch R = 1,160,0,0,0
BEGIN DESCRIPTION:
UNT 59 in Lagunillas Cr Wtrshd 1.0
END DESCRIPTION:
XS GIS Cut Line= 6
      2052350.00     13482600.00      2051854.52     13482150.78
      2051661.26     13482327.27      2051560.07     13482507.76
      2051881.59     13483087.62      2051552.72     13483761.24
#Sta/Elev= 30
  4117.2  432.91  4414.4  432.26  4561.2  430.05  4585.4  430.09  4641.2  430.07
  4654.9  428.13  4670.8  431.64  4676.5  430.29  4729.1  431.17  4907.3  432.83
  4949.8  430.51  4976.0  422.80  5003.4  420.63  5003.9  419.83  5009.8  420.63
  5020.8  421.03  5047.6  428.83  5084.8  431.40  5180.3  428.59  5210.9  430.02
  5251.9  426.87  5263.8  427.70  5291.1  430.15  5364.2  431.27  6041.4  432.20
  6066.8  431.31  6120.4  434.04  6156.9  431.40  6193.2  431.86  6672.6  434.53
#Mann=10,-1,0
  4117.2     0.1       0  4561.2    0.05       0  4585.4     0.1       0
  4729.1    0.05       0  5003.4    0.03       0  5009.8    0.05       0
  5251.9     0.1       0  5263.8    0.05       0  6041.4    0.08       0
  6193.2    0.05       0
Bank Sta=5003.4,5009.8
Exp/Cntr=0.3,0.1

Chan Stop Cuts=-1