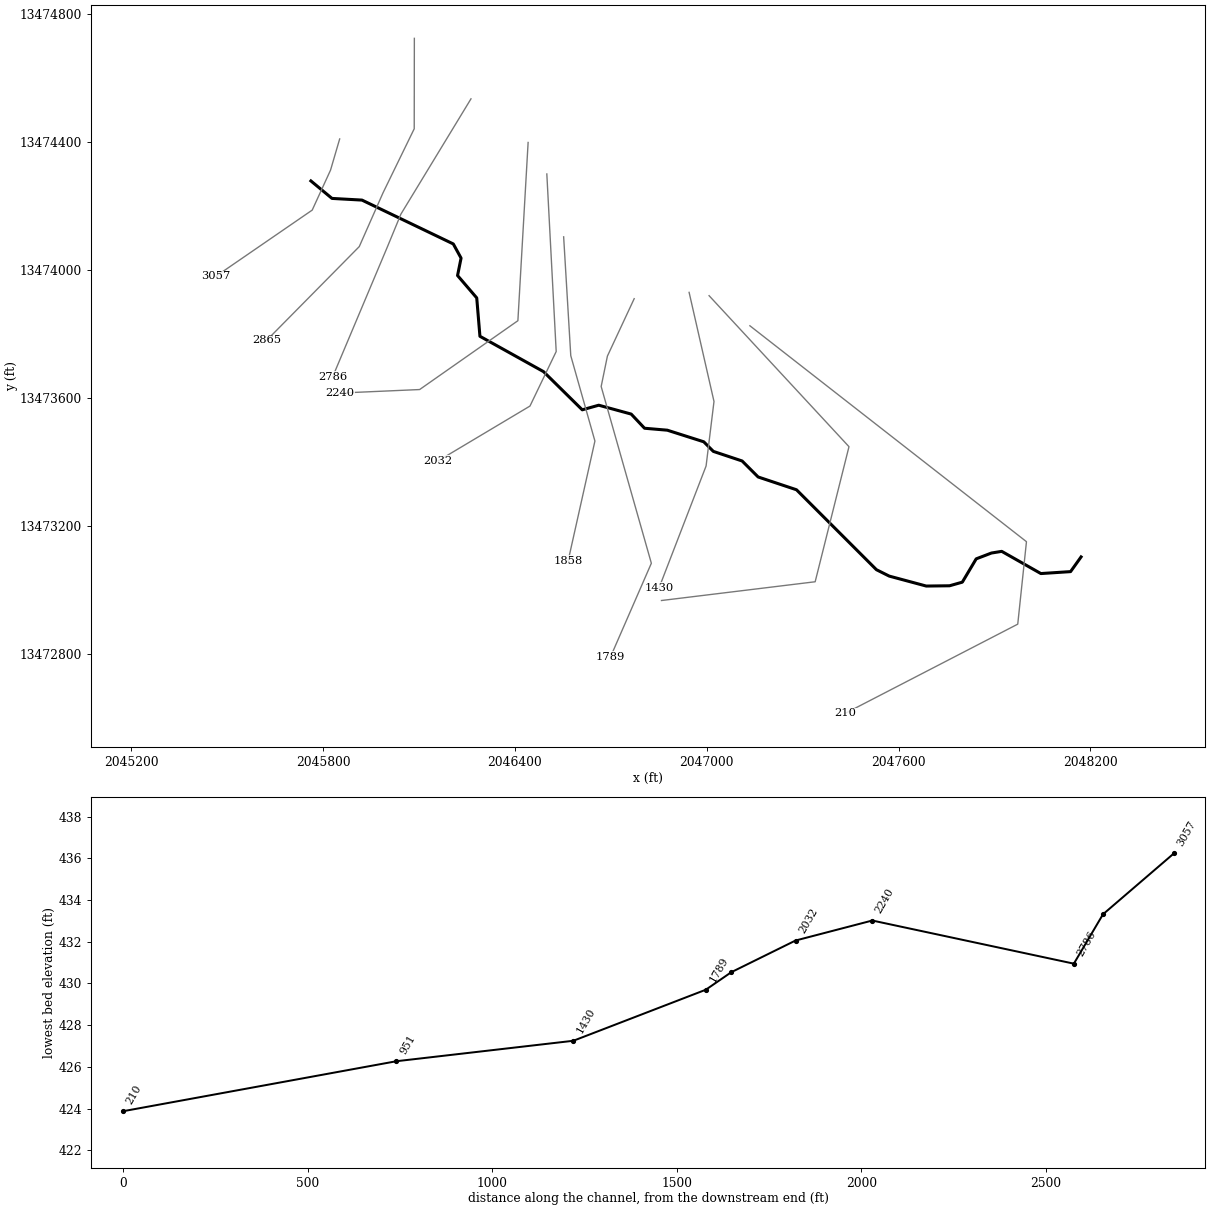
--- UNT 61 in Lagunillas Cr Wtrshd.prj (project) ---

Proj Title=UNT 61 in Lagunillas Cr Wtrshd Base Level Engineering
Current Plan=p01
Default Exp/Contr=0.3,0.1
English Units
Geom File=g01
Flow File=f01
Plan File=p01
Y Axis Title=Elevation
X Axis Title(PF)=Main Channel Distance
X Axis Title(XS)=Station
BEGIN DESCRIPTION:
UNT 61 in Lagunillas Cr Wtrshd
END DESCRIPTION:
DSS Export Rating Curves= 0
DSS Export Rating Curve Sorted= 0
DSS Export Volume Flow Curves= 0
DXF OffsetX= 0
DXF OffsetY= 0
DXF ScaleX= 1
DXF ScaleY= 10

--- UNT 61 in Lagunillas Cr Wtrshd.p01 (plan) ---

Plan Title=Multiple Run
Short Identifier=Multiple
Geom File=g01
Flow File=f01
Subcritical Flow
K Sum by GR= 0
Std Step Tol= 0.01
Critical Tol= 0.01
Num of Std Step Trials= 20
Max Error Tol= 0.3
Flow Tol Ratio= 0.001
Split Flow NTrial= 30
Split Flow Tol= 0.02
Split Flow Ratio= 0.02
Log Output Level= 0
Friction Slope Method= 1
Unsteady Friction Slope Method= 2
Unsteady Bridges Friction Slope Method= 1
Parabolic Critical Depth
Global Vel Dist=  1 , 1 , 1
Global Log Level= 0
CheckData=True
Encroach Param= -1, 0, 0, 0
BEGIN DESCRIPTION:
Multiple Run
END DESCRIPTION:

--- UNT 61 in Lagunillas Cr Wtrshd.f01 (steady flow) ---

Flow Title=Multiple
Program Version=5.05
Number of Profiles= 7
Profile Names=10-year,25-year,50-year,1pct_min,100-year,1pct_plu,500-year
River Rch & RM=UNT 61 in Laguni,Reach-1         ,3057
     189     259     317     194     388     773     586
River Rch & RM=UNT 61 in Laguni,Reach-1         ,1430
     265     371     460     285     568    1134     879
Boundary for River Rch & Prof#=UNT 61 in Laguni,Reach-1         , 1
Up Type= 0
Dn Type= 3
Dn Slope=0.00702
Boundary for River Rch & Prof#=UNT 61 in Laguni,Reach-1         , 2
Up Type= 0
Dn Type= 3
Dn Slope=0.00702
Boundary for River Rch & Prof#=UNT 61 in Laguni,Reach-1         , 3
Up Type= 0
Dn Type= 3
Dn Slope=0.00702
Boundary for River Rch & Prof#=UNT 61 in Laguni,Reach-1         , 4
Up Type= 0
Dn Type= 3
Dn Slope=0.00702
Boundary for River Rch & Prof#=UNT 61 in Laguni,Reach-1         , 5
Up Type= 0
Dn Type= 3
Dn Slope=0.00702
Boundary for River Rch & Prof#=UNT 61 in Laguni,Reach-1         , 6
Up Type= 0
Dn Type= 3
Dn Slope=0.00702
Boundary for River Rch & Prof#=UNT 61 in Laguni,Reach-1         , 7
Up Type= 0
Dn Type= 3
Dn Slope=0.00702
DSS Import GetInterval= 0
DSS Import GetPeak= 0
DSS Import FillOption= 0

--- UNT 61 in Lagunillas Cr Wtrshd.g01 (geometry) ---

Geom Title=Existing Conditions

River Reach=UNT 61 in Laguni,Reach-1
Reach XY= 30
      2045762.19     13474278.20      2045828.16     13474223.51
      2045921.91     13474218.30      2046207.50     13474081.15
      2046231.81     13474036.88      2046220.80     13473982.37
      2046280.80     13473912.37      2046290.80     13473792.37
      2046489.62     13473681.84      2046610.80     13473562.37
      2046662.36     13473576.81      2046763.93     13473549.03
      2046805.59     13473504.76      2046876.77     13473498.68
      2046990.80     13473462.37      2047020.80     13473432.37
      2047110.80     13473402.37      2047160.80     13473352.37
      2047280.80     13473312.37      2047530.80     13473062.37
      2047570.80     13473042.37      2047686.55     13473011.25
      2047759.47     13473012.11      2047799.40     13473023.40
      2047842.80     13473096.31      2047890.55     13473114.54
      2047922.67     13473119.75      2048045.06     13473050.31
      2048137.94     13473056.38      2048170.80     13473102.37

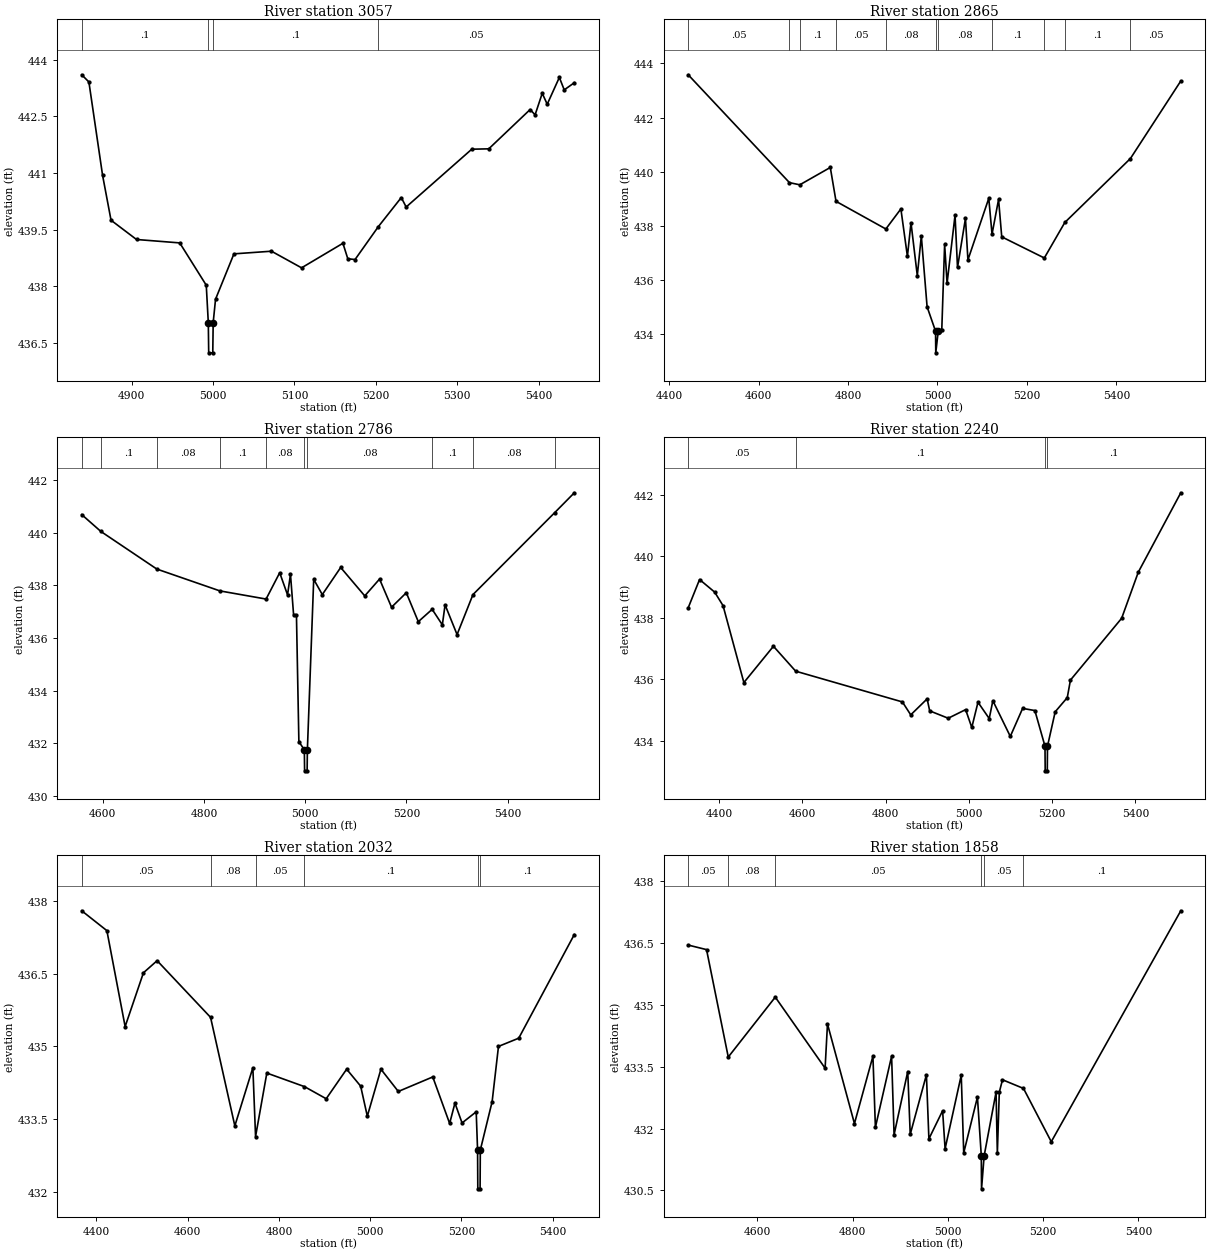
Type RM Length L Ch R = 1,3057,192,192,192
BEGIN DESCRIPTION:
UNT 61 in Lagunillas Cr Wtrshd 2.0
END DESCRIPTION:
XS GIS Cut Line= 4
      2045852.16     13474409.55      2045823.57     13474312.00
      2045766.28     13474187.00      2045464.62     13473979.68
#Sta/Elev= 30
  4838.7  443.60  4847.5  443.41  4864.3  440.94  4874.7  439.75  4906.0  439.24
  4959.1  439.15  4991.7  438.03  4994.2  437.04  4994.7  436.24  4999.7  436.24
  5000.2  437.04  5003.1  437.66  5025.7  438.86  5071.8  438.93  5108.8  438.49
  5159.6  439.14  5165.6  438.73  5174.5  438.71  5203.1  439.58  5231.3  440.35
  5237.3  440.10  5317.9  441.63  5338.8  441.64  5389.6  442.68  5395.7  442.54
  5404.5  443.11  5410.6  442.82  5425.5  443.53  5431.5  443.20  5443.9  443.39
#Mann=4,-1,0
  4838.7     0.1       0  4994.2    0.07       0  5000.2     0.1       0
  5203.1    0.05       0
Bank Sta=4994.2,5000.2
Exp/Cntr=0.3,0.1

Type RM Length L Ch R = 1,2865,79,79,79
BEGIN DESCRIPTION:
UNT 22 in Lagunillas Cr Wtrshd 12.0
END DESCRIPTION:
XS GIS Cut Line= 5
      2046085.71     13474724.16      2046085.29     13474441.34
      2045987.64     13474240.82      2045913.42     13474072.85
      2045624.04     13473779.86
#Sta/Elev= 30
  4442.8  443.58  4669.2  439.60  4692.3  439.52  4760.5  440.16  4773.3  438.91
  4884.7  437.89  4918.3  438.63  4932.9  436.88  4940.9  438.12  4955.0  436.17
  4964.0  437.63  4976.9  435.02  4995.8  434.12  4996.3  433.32  5001.8  434.12
  5009.7  434.15  5016.1  437.32  5021.6  435.89  5039.4  438.40  5044.9  436.47
  5062.7  438.28  5068.2  436.75  5114.8  439.02  5122.1  437.70  5136.7  438.98
  5143.8  437.60  5239.0  436.82  5284.8  438.13  5431.5  440.49  5544.1  443.35
#Mann=11,-1,0
  4442.8    0.05       0  4669.2    0.08       0  4692.3     0.1       0
  4773.3    0.05       0  4884.7    0.08       0  4995.8    0.07       0
  5001.8    0.08       0  5122.1     0.1       0  5239.0    0.05       0
  5284.8     0.1       0  5431.5    0.05       0
Bank Sta=4995.8,5001.8
Exp/Cntr=0.3,0.1

Type RM Length L Ch R = 1,2786,546,546,546
BEGIN DESCRIPTION:
Mapping XS c6f62354
END DESCRIPTION:
XS GIS Cut Line= 4
      2046262.80     13474534.95      2046043.63     13474174.41
      2046000.66     13474070.24      2045830.37     13473665.85
#Sta/Elev= 30
  4558.4  440.69  4596.2  440.05  4706.8  438.62  4831.4  437.79  4922.7  437.48
  4949.6  438.48  4965.1  437.64  4970.9  438.42  4977.1  436.87  4982.7  436.87
  4987.5  432.06  4998.3  431.75  4998.8  430.95  5003.8  430.95  5004.3  431.75
  5016.8  438.23  5033.8  437.65  5070.1  438.68  5117.7  437.60  5146.9  438.24
  5170.6  437.17  5199.8  437.72  5223.5  436.62  5250.9  437.09  5271.0  436.50
  5276.4  437.26  5300.1  436.13  5331.5  437.65  5493.3  440.77  5531.8  441.52
#Mann=10,-1,0
  4558.4    0.08       0  4596.2     0.1       0  4706.8    0.08       0
  4831.4     0.1       0  4922.7    0.08       0  4998.3    0.07       0
  5004.3    0.08       0  5250.9     0.1       0  5331.5    0.08       0
  5493.3     0.1       0
Bank Sta=4998.3,5004.3
Exp/Cntr=0.3,0.1

Type RM Length L Ch R = 1,2240,208,208,208
BEGIN DESCRIPTION:
Mapping XS f090032c
END DESCRIPTION:
XS GIS Cut Line= 4
      2046441.49     13474398.52      2046409.51     13473841.08
      2046102.22     13473625.80      2045853.12     13473614.80
#Sta/Elev= 30
  4325.9  438.32  4353.2  439.24  4389.5  438.83  4409.6  438.39  4459.6  435.89
  4530.6  437.07  4584.0  436.26  4840.3  435.26  4860.3  434.84  4899.7  435.36
  4905.8  434.97  4950.3  434.73  4992.1  435.01  5006.9  434.43  5021.8  435.25
  5048.8  434.72  5057.5  435.30  5099.4  434.14  5129.0  435.05  5158.4  434.98
  5182.7  433.82  5183.2  433.02  5188.2  433.02  5188.7  433.82  5207.2  434.94
  5236.2  435.40  5243.8  435.97  5366.8  437.98  5406.8  439.48  5508.8  442.06
#Mann=4,-1,0
  4325.9    0.05       0  4584.0     0.1       0  5182.7    0.07       0
  5188.7     0.1       0
Bank Sta=5182.7,5188.7
Exp/Cntr=0.3,0.1

Type RM Length L Ch R = 1,2032,174,174,174
BEGIN DESCRIPTION:
Mapping XS 074371d6
END DESCRIPTION:
XS GIS Cut Line= 4
      2046500.00     13474300.00      2046529.30     13473744.72
      2046447.27     13473574.15      2046160.37     13473402.99
#Sta/Elev= 30
  4367.9  437.80  4423.0  437.39  4463.0  435.41  4503.1  436.52  4533.1  436.77
  4650.2  435.60  4703.4  433.36  4742.9  434.56  4748.8  433.14  4773.5  434.45
  4856.0  434.17  4903.6  433.92  4948.4  434.53  4979.1  434.18  4993.7  433.56
  5023.5  434.53  5061.6  434.07  5137.1  434.37  5174.1  433.41  5185.7  433.83
  5201.3  433.42  5232.3  433.65  5235.3  432.86  5235.8  432.06  5240.8  432.06
  5241.3  432.86  5267.2  433.86  5281.1  435.00  5325.5  435.17  5447.3  437.31
#Mann=6,-1,0
  4367.9    0.05       0  4650.2    0.08       0  4748.8    0.05       0
  4856.0     0.1       0  5235.3    0.07       0  5241.3     0.1       0
Bank Sta=5235.3,5241.3
Exp/Cntr=0.3,0.1

Type RM Length L Ch R = 1,1858,69,69,69
BEGIN DESCRIPTION:
Mapping XS 9367eb19
END DESCRIPTION:
XS GIS Cut Line= 4
      2046552.60     13474103.39      2046574.88     13473731.70
      2046650.40     13473464.77      2046566.54     13473089.69
#Sta/Elev= 30
  4454.9  436.44  4493.4  436.33  4539.0  433.73  4637.7  435.18  4742.3  433.46
  4747.3  434.53  4803.9  432.12  4842.7  433.75  4847.9  432.03  4881.9  433.75
  4887.1  431.85  4915.8  433.38  4921.0  431.86  4955.0  433.30  4960.2  431.75
  4989.0  432.43  4994.2  431.51  5028.1  433.29  5033.3  431.41  5062.1  432.76
  5070.2  431.34  5070.7  430.54  5076.2  431.34  5101.2  432.88  5103.9  431.40
  5108.0  432.88  5114.7  433.18  5158.8  432.97  5217.1  431.68  5489.0  437.27
#Mann=6,-1,0
  4454.9    0.05       0  4539.0    0.08       0  4637.7    0.05       0
  5070.2    0.04       0  5076.2    0.05       0  5158.8     0.1       0
Bank Sta=5070.2,5076.2
Exp/Cntr=0.3,0.1

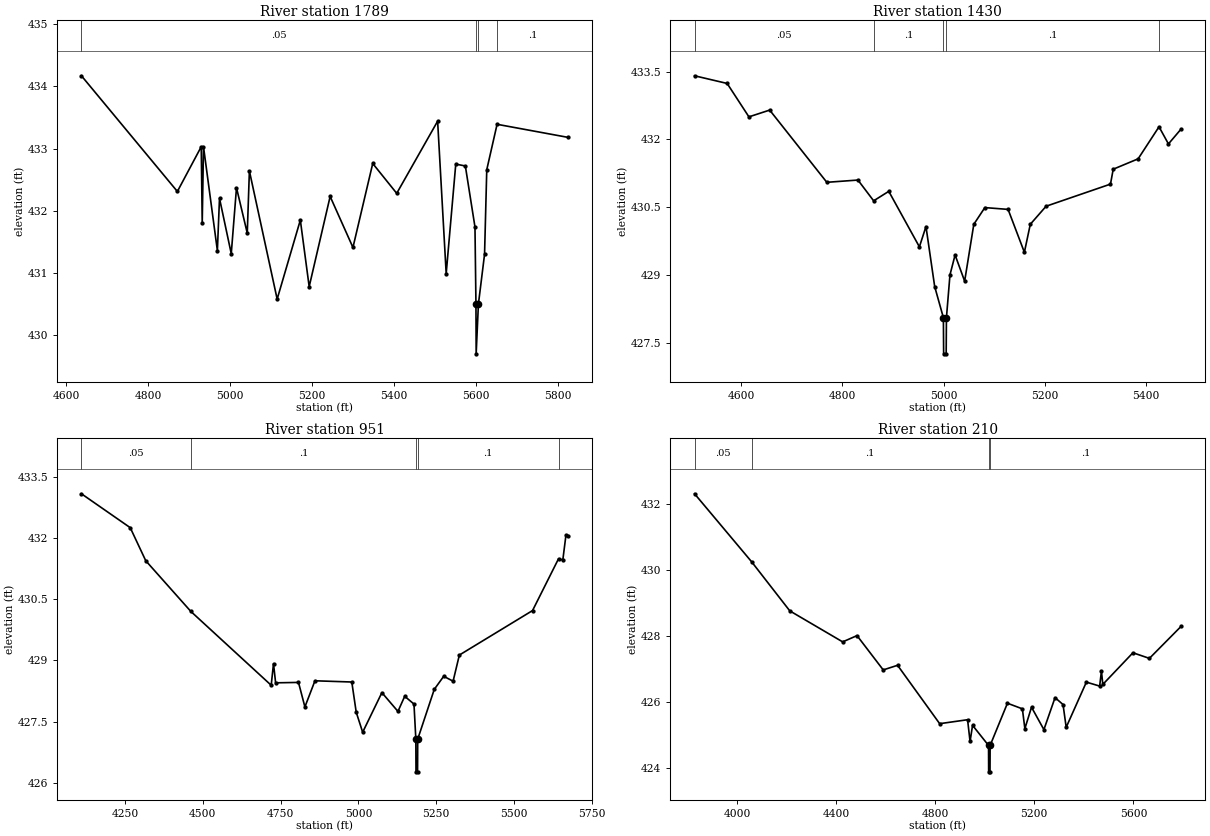
Type RM Length L Ch R = 1,1789,359,359,359
BEGIN DESCRIPTION:
Mapping XS c21261a5
END DESCRIPTION:
XS GIS Cut Line= 5
      2046773.23     13473909.97      2046689.46     13473730.40
      2046669.93     13473635.35      2046826.90     13473082.53
      2046699.68     13472790.72
#Sta/Elev= 30
  4636.5  434.17  4870.8  432.31  4929.1  433.03  4931.5  431.80  4934.6  433.03
  4968.5  431.36  4973.7  432.20  5002.4  431.31  5015.2  432.37  5041.5  431.64
  5046.7  432.64  5114.5  430.58  5171.1  431.85  5192.7  430.78  5243.9  432.23
  5299.6  431.41  5347.9  432.76  5406.5  432.28  5506.4  433.44  5527.3  430.99
  5550.7  432.75  5574.1  432.72  5597.6  431.74  5600.0  430.50  5600.5  429.70
  5606.0  430.50  5621.0  431.30  5626.4  432.66  5651.6  433.39  5824.7  433.18
#Mann=4,-1,0
  4636.5    0.05       0  5600.0    0.04       0  5606.0    0.05       0
  5651.6     0.1       0
Bank Sta=5600,5606
Exp/Cntr=0.3,0.1

Type RM Length L Ch R = 1,1430,479,479,479
BEGIN DESCRIPTION:
Mapping XS 9b224dc1
END DESCRIPTION:
XS GIS Cut Line= 4
      2046944.97     13473929.72      2047022.79     13473588.47
      2046998.05     13473386.65      2046851.21     13473006.14
#Sta/Elev= 30
  4508.1  433.41  4572.5  433.24  4615.5  432.50  4656.5  432.65  4769.4  431.05
  4830.9  431.10  4861.9  430.64  4891.8  430.85  4952.3  429.62  4965.3  430.07
  4982.5  428.74  4999.7  428.05  5000.2  427.25  5005.2  427.25  5005.7  428.05
  5012.7  429.00  5022.8  429.44  5041.7  428.86  5059.8  430.12  5081.6  430.49
  5127.5  430.45  5159.7  429.50  5171.4  430.12  5202.6  430.52  5329.8  431.01
  5335.2  431.34  5384.4  431.57  5425.7  432.28  5444.3  431.90  5469.3  432.23
#Mann=5,-1,0
  4508.1    0.05       0  4861.9     0.1       0  4999.7    0.07       0
  5005.7     0.1       0  5425.7    0.05       0
Bank Sta=4999.7,5005.7
Exp/Cntr=0.3,0.1

Type RM Length L Ch R = 1,951,741,741,741
BEGIN DESCRIPTION:
Mapping XS 3ab1764d
END DESCRIPTION:
XS GIS Cut Line= 4
      2047007.44     13473919.35      2047444.96     13473447.11
      2047339.20     13473024.67      2046858.61     13472966.02
#Sta/Elev= 30
  4109.8  433.08  4266.6  432.25  4316.5  431.44  4461.2  430.20  4719.6  428.39
  4727.0  428.92  4733.8  428.45  4807.3  428.46  4827.9  427.86  4860.2  428.50
  4978.6  428.47  4992.8  427.73  5013.5  427.24  5075.3  428.21  5126.9  427.75
  5148.6  428.12  5178.4  427.93  5184.4  427.07  5184.9  426.27  5189.9  426.27
  5190.4  427.07  5243.6  428.29  5273.9  428.61  5304.1  428.49  5324.2  429.13
  5559.4  430.22  5643.0  431.49  5656.7  431.46  5666.8  432.07  5673.2  432.04
#Mann=5,-1,0
  4109.8    0.05       0  4461.2     0.1       0  5184.4    0.07       0
  5190.4     0.1       0  5643.0    0.05       0
Bank Sta=5184.4,5190.4
Exp/Cntr=0.3,0.1

Type RM Length L Ch R = 1,210,0,0,0
BEGIN DESCRIPTION:
UNT 61 in Lagunillas Cr Wtrshd 1.0
END DESCRIPTION:
XS GIS Cut Line= 4
      2047135.09     13473825.21      2048000.00     13473150.00
      2047972.74     13472892.08      2047432.91     13472613.05
#Sta/Elev= 30
  3828.3  432.30  4058.5  430.24  4212.8  428.75  4426.3  427.81  4484.2  428.00
  4590.0  426.96  4647.9  427.10  4817.9  425.33  4930.6  425.45  4940.6  424.79
  4950.7  425.28  5015.2  424.67  5015.7  423.87  5021.1  423.87  5021.6  424.67
  5091.5  425.95  5151.8  425.78  5161.9  425.18  5188.7  425.83  5238.7  425.15
  5283.7  426.12  5316.0  425.91  5328.7  425.22  5410.2  426.59  5463.8  426.47
  5471.0  426.92  5476.6  426.52  5598.2  427.48  5664.7  427.31  5792.6  428.28
#Mann=4,-1,0
  3828.3    0.05       0  4058.5     0.1       0  5015.2    0.07       0
  5021.6     0.1       0
Bank Sta=5015.2,5021.6
Exp/Cntr=0.3,0.1

Chan Stop Cuts=-1