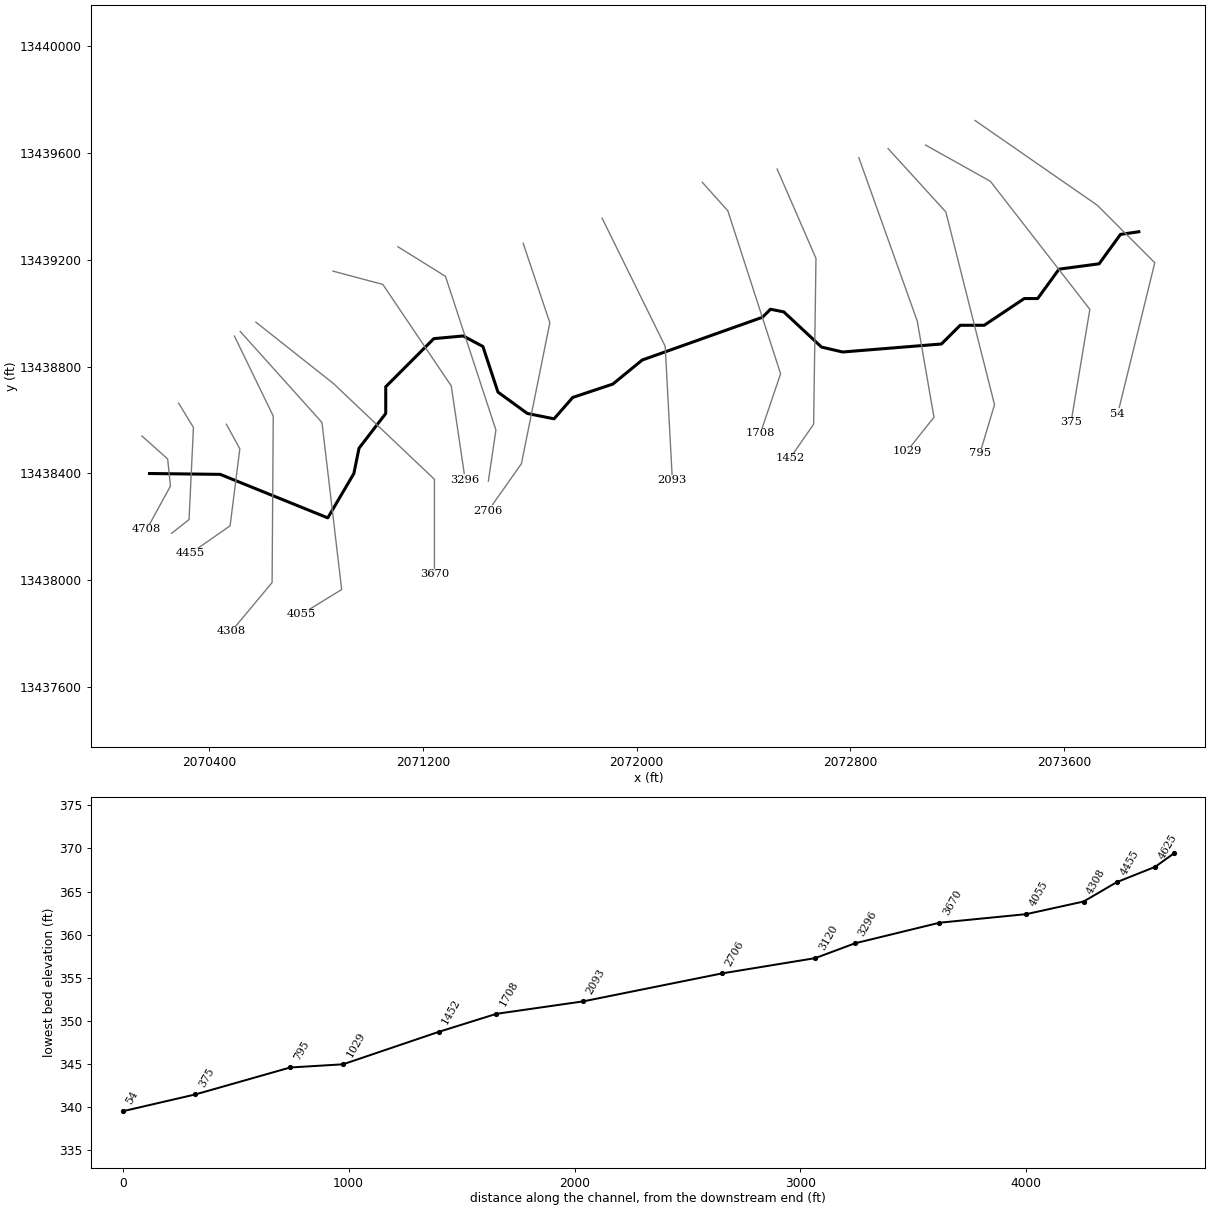
--- UNT 63 in Lagunillas Cr Wtrshd.prj (project) ---

Proj Title=UNT 63 in Lagunillas Cr Wtrshd Base Level Engineering
Current Plan=p01
Default Exp/Contr=0.3,0.1
English Units
Geom File=g01
Flow File=f01
Plan File=p01
BEGIN DESCRIPTION:
UNT 63 in Lagunillas Cr Wtrshd
END DESCRIPTION:

--- UNT 63 in Lagunillas Cr Wtrshd.p01 (plan) ---

Plan Title=Multiple Run
Short Identifier=Multiple
Geom File=g01
Flow File=f01
Subcritical Flow
K Sum by GR= 0
Std Step Tol= 0.01
Critical Tol= 0.01
Num of Std Step Trials= 20
Max Error Tol= 0.3
Flow Tol Ratio= 0.001
Split Flow NTrial= 30
Split Flow Tol= 0.02
Split Flow Ratio= 0.02
Log Output Level= 0
Friction Slope Method= 1
Unsteady Friction Slope Method= 2
Unsteady Bridges Friction Slope Method= 1
Parabolic Critical Depth
Global Vel Dist=  1 , 1 , 1
Global Log Level= 0
CheckData=True
Encroach Param= -1, 0, 0, 0
BEGIN DESCRIPTION:
Multiple Run
END DESCRIPTION:

--- UNT 63 in Lagunillas Cr Wtrshd.f01 (steady flow) ---

Flow Title=Multiple
Number of Profiles=7
Profile Names=10-year,25-year,50-year,1pct_min,100-year,1pct_plu,500-year
River Rch & RM= UNT 63 in Laguni,Reach-1,4708
     173     237     290     177     353     704     533
Boundary for River Rch & Prof#=UNT 63 in Laguni,Reach-1,1
Up Type=0
Dn Type=3
Dn Slope=0.005
Boundary for River Rch & Prof#=UNT 63 in Laguni,Reach-1,2
Up Type=0
Dn Type=3
Dn Slope=0.005
Boundary for River Rch & Prof#=UNT 63 in Laguni,Reach-1,3
Up Type=0
Dn Type=3
Dn Slope=0.005
Boundary for River Rch & Prof#=UNT 63 in Laguni,Reach-1,4
Up Type=0
Dn Type=3
Dn Slope=0.005
Boundary for River Rch & Prof#=UNT 63 in Laguni,Reach-1,5
Up Type=0
Dn Type=3
Dn Slope=0.005
Boundary for River Rch & Prof#=UNT 63 in Laguni,Reach-1,6
Up Type=0
Dn Type=3
Dn Slope=0.005
Boundary for River Rch & Prof#=UNT 63 in Laguni,Reach-1,7
Up Type=0
Dn Type=3
Dn Slope=0.005

--- UNT 63 in Lagunillas Cr Wtrshd.g01 (geometry) ---

Geom Title=Existing Conditions

River Reach=UNT 63 in Laguni,Reach-1
Reach XY= 30
      2070176.57     13438399.92      2070441.33     13438396.67
      2070843.89     13438233.90      2070941.54     13438399.92
      2070960.80     13438494.54      2071060.80     13438624.54
      2071060.80     13438724.54      2071240.80     13438904.54
      2071350.80     13438914.54      2071424.40     13438875.18
      2071480.80     13438704.54      2071590.80     13438624.54
      2071690.80     13438604.54      2071760.80     13438684.54
      2071910.80     13438734.54      2072020.80     13438824.54
      2072470.80     13438984.54      2072500.80     13439014.54
      2072550.80     13439004.54      2072691.76     13438873.01
      2072770.80     13438854.54      2073140.80     13438884.54
      2073210.80     13438954.54      2073300.80     13438954.54
      2073450.80     13439054.54      2073500.80     13439054.54
      2073580.80     13439164.54      2073730.80     13439184.54
      2073810.80     13439294.54      2073879.42     13439304.54

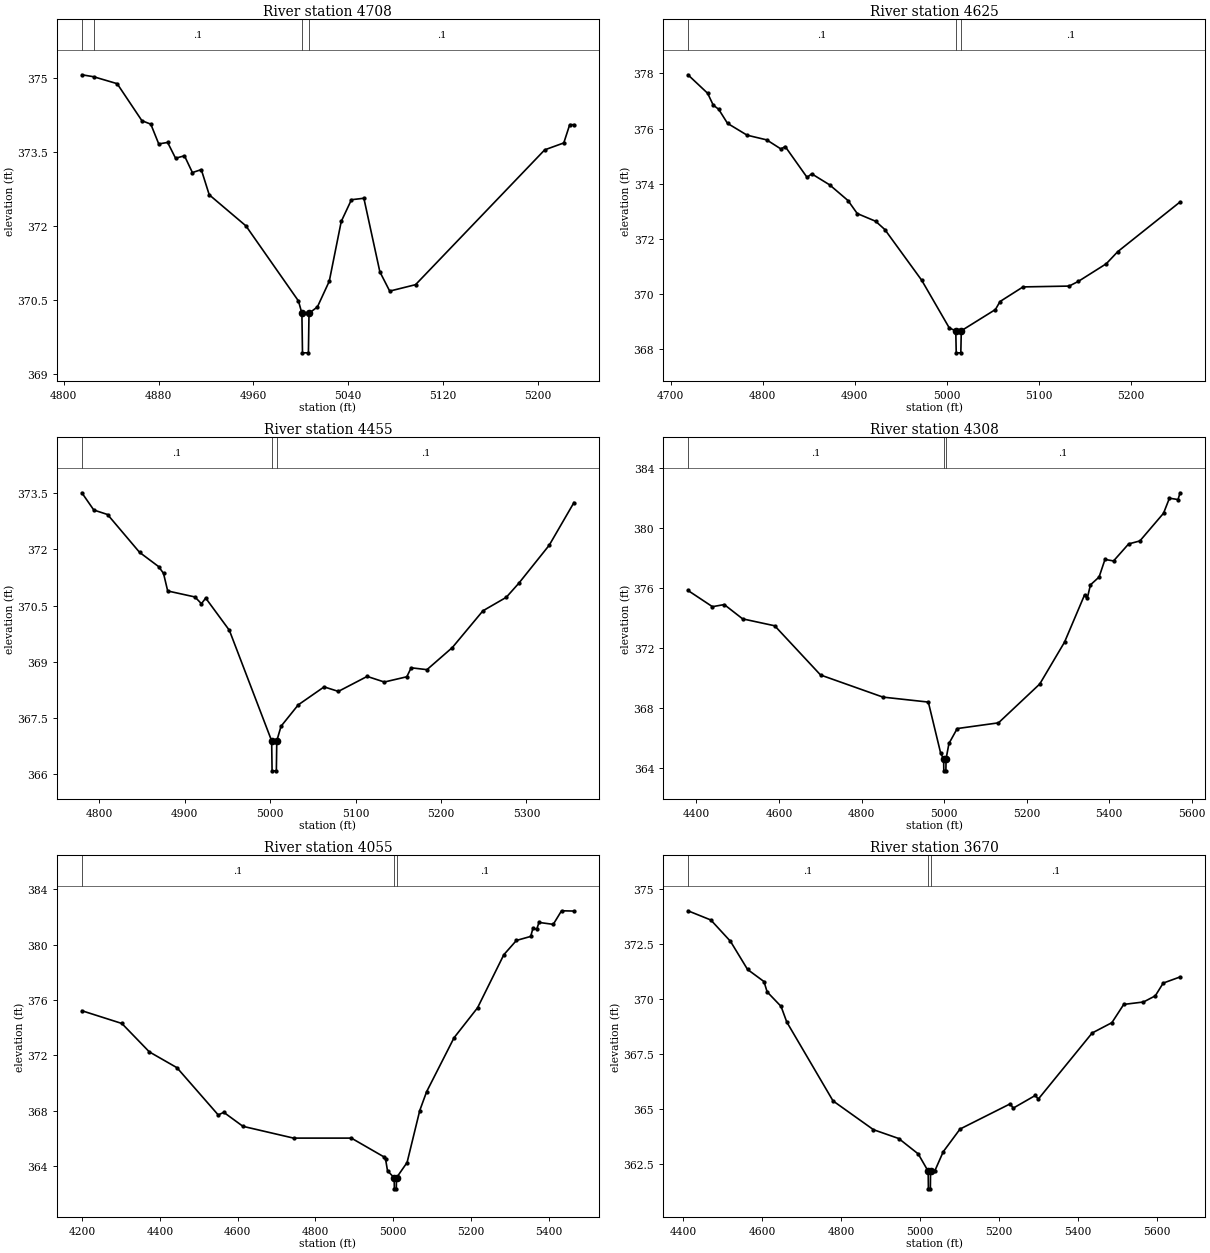
Type RM Length L Ch R = 1,4708,83,83,83
BEGIN DESCRIPTION:
UNT 63 in Lagunillas Cr Wtrshd 6.0
END DESCRIPTION:
XS GIS Cut Line= 4
      2070148.30     13438540.27      2070244.62     13438454.36
      2070255.03     13438352.80      2070166.49     13438191.34
#Sta/Elev= 30
  4815.3  375.06  4825.3  375.02  4845.1  374.88  4866.0  374.13  4873.5  374.06
  4880.2  373.66  4887.7  373.69  4894.4  373.37  4901.9  373.42  4908.6  373.08
  4916.1  373.14  4922.8  372.63  4953.8  372.00  4998.1  370.48  5001.0  370.23
  5001.5  369.43  5006.5  369.43  5007.0  370.23  5014.1  370.36  5024.1  370.88
  5034.2  372.09  5042.8  372.53  5053.3  372.56  5066.8  371.07  5075.1  370.68
  5096.9  370.81  5205.9  373.54  5222.0  373.68  5227.0  374.05  5230.6  374.05
#Mann=4,-1,0
  4815.3    0.05       0  4825.3     0.1       0  5001.0    0.07       0
  5007.0     0.1       0
Bank Sta=5001,5007
Exp/Cntr=0.3,0.1

Type RM Length L Ch R = 1,4625,170,170,170
BEGIN DESCRIPTION:
Mapping XS 0669d0a3
END DESCRIPTION:
XS GIS Cut Line= 4
      2070285.56     13438663.30      2070341.11     13438572.16
      2070324.62     13438227.54      2070259.36     13438176.02
#Sta/Elev= 30
  4718.9  377.95  4740.3  377.28  4746.4  376.85  4752.3  376.70  4761.9  376.19
  4783.2  375.76  4804.5  375.59  4820.0  375.26  4824.6  375.35  4848.4  374.23
  4853.4  374.36  4872.9  373.96  4892.9  373.39  4902.9  372.92  4922.9  372.64
  4932.9  372.34  4973.0  370.50  5003.0  368.77  5010.0  368.67  5010.5  367.87
  5015.5  367.87  5016.0  368.67  5053.1  369.44  5058.1  369.73  5083.1  370.26
  5133.2  370.29  5143.2  370.46  5173.6  371.10  5186.1  371.54  5253.8  373.34
#Mann=3,-1,0
  4718.9     0.1       0  5010.0    0.07       0  5016.0     0.1       0
Bank Sta=5010,5016
Exp/Cntr=0.3,0.1

Type RM Length L Ch R = 1,4455,147,147,147
BEGIN DESCRIPTION:
Mapping XS 05931c84
END DESCRIPTION:
XS GIS Cut Line= 4
      2070464.39     13438584.29      2070514.73     13438492.30
      2070478.27     13438204.11      2070329.91     13438100.86
#Sta/Elev= 30
  4779.6  373.51  4793.6  373.05  4809.7  372.93  4847.2  371.92  4869.5  371.54
  4875.2  371.36  4880.1  370.89  4912.0  370.73  4919.6  370.55  4924.6  370.70
  4952.3  369.84  5001.8  366.89  5002.3  366.09  5007.3  366.09  5007.8  366.89
  5012.8  367.28  5032.9  367.85  5063.2  368.33  5079.9  368.21  5113.6  368.61
  5133.7  368.46  5160.0  368.60  5165.1  368.84  5183.6  368.79  5213.3  369.38
  5249.1  370.36  5276.4  370.72  5290.9  371.09  5326.7  372.11  5355.7  373.25
#Mann=3,-1,0
  4779.6     0.1       0  5001.8    0.07       0  5007.8     0.1       0
Bank Sta=5001.8,5007.8
Exp/Cntr=0.3,0.1

Type RM Length L Ch R = 1,4308,253,253,253
BEGIN DESCRIPTION:
Mapping XS d8ee7470
END DESCRIPTION:
XS GIS Cut Line= 4
      2070494.43     13438914.15      2070639.82     13438614.69
      2070635.48     13437991.86      2070483.78     13437809.82
#Sta/Elev= 30
  4379.3  375.83  4438.7  374.75  4467.3  374.89  4511.9  373.94  4589.6  373.48
  4700.7  370.21  4851.9  368.74  4961.9  368.41  4991.9  365.00  4998.9  364.64
  4999.4  363.84  5004.4  363.84  5004.9  364.64  5011.9  365.66  5031.9  366.65
  5131.9  367.03  5231.9  369.61  5291.9  372.39  5340.5  375.53  5347.0  375.30
  5354.8  376.20  5375.7  376.72  5390.0  377.89  5410.8  377.79  5447.3  378.92
  5474.6  379.12  5531.9  380.96  5546.2  381.96  5567.0  381.87  5572.0  382.32
#Mann=3,-1,0
  4379.3     0.1       0  4998.9    0.07       0  5004.9     0.1       0
Bank Sta=4998.9,5004.9
Exp/Cntr=0.3,0.1

Type RM Length L Ch R = 1,4055,385,385,385
BEGIN DESCRIPTION:
Mapping XS 2c1cb32b
END DESCRIPTION:
XS GIS Cut Line= 4
      2070516.11     13438931.55      2070822.11     13438590.82
      2070895.90     13437965.82      2070743.98     13437872.50
#Sta/Elev= 30
  4199.4  375.23  4302.3  374.31  4373.0  372.26  4444.0  371.12  4550.2  367.71
  4564.4  367.90  4613.7  366.89  4743.8  366.04  4892.5  366.04  4975.4  364.70
  4980.5  364.52  4985.5  363.68  5002.6  363.18  5003.1  362.38  5008.1  362.38
  5008.6  363.18  5035.8  364.28  5068.4  368.03  5086.1  369.39  5156.6  373.28
  5217.0  375.44  5284.6  379.27  5317.0  380.30  5353.7  380.59  5359.6  381.19
  5369.1  381.10  5375.0  381.60  5411.7  381.46  5433.0  382.44  5465.0  382.42
#Mann=3,-1,0
  4199.4     0.1       0  5002.6    0.07       0  5008.6     0.1       0
Bank Sta=5002.6,5008.6
Exp/Cntr=0.3,0.1

Type RM Length L Ch R = 1,3670,374,374,374
BEGIN DESCRIPTION:
Mapping XS a7884ddd
END DESCRIPTION:
XS GIS Cut Line= 4
      2070574.73     13438966.25      2070865.52     13438736.22
      2071243.12     13438378.15      2071243.12     13438022.20
#Sta/Elev= 30
  4412.1  374.03  4470.2  373.61  4519.9  372.64  4563.2  371.36  4604.8  370.81
  4612.8  370.34  4648.1  369.68  4662.5  368.97  4779.8  365.38  4882.3  364.07
  4946.2  363.67  4995.6  362.97  5020.9  362.18  5021.4  361.38  5026.4  361.38
  5026.9  362.18  5038.0  362.21  5059.1  363.07  5101.6  364.10  5229.0  365.25
  5236.2  365.05  5292.5  365.63  5299.8  365.46  5436.4  368.47  5486.4  368.94
  5516.4  369.77  5566.4  369.88  5596.4  370.16  5616.4  370.74  5659.2  371.02
#Mann=3,-1,0
  4412.1     0.1       0  5020.9    0.07       0  5026.9     0.1       0
Bank Sta=5020.9,5026.9
Exp/Cntr=0.3,0.1

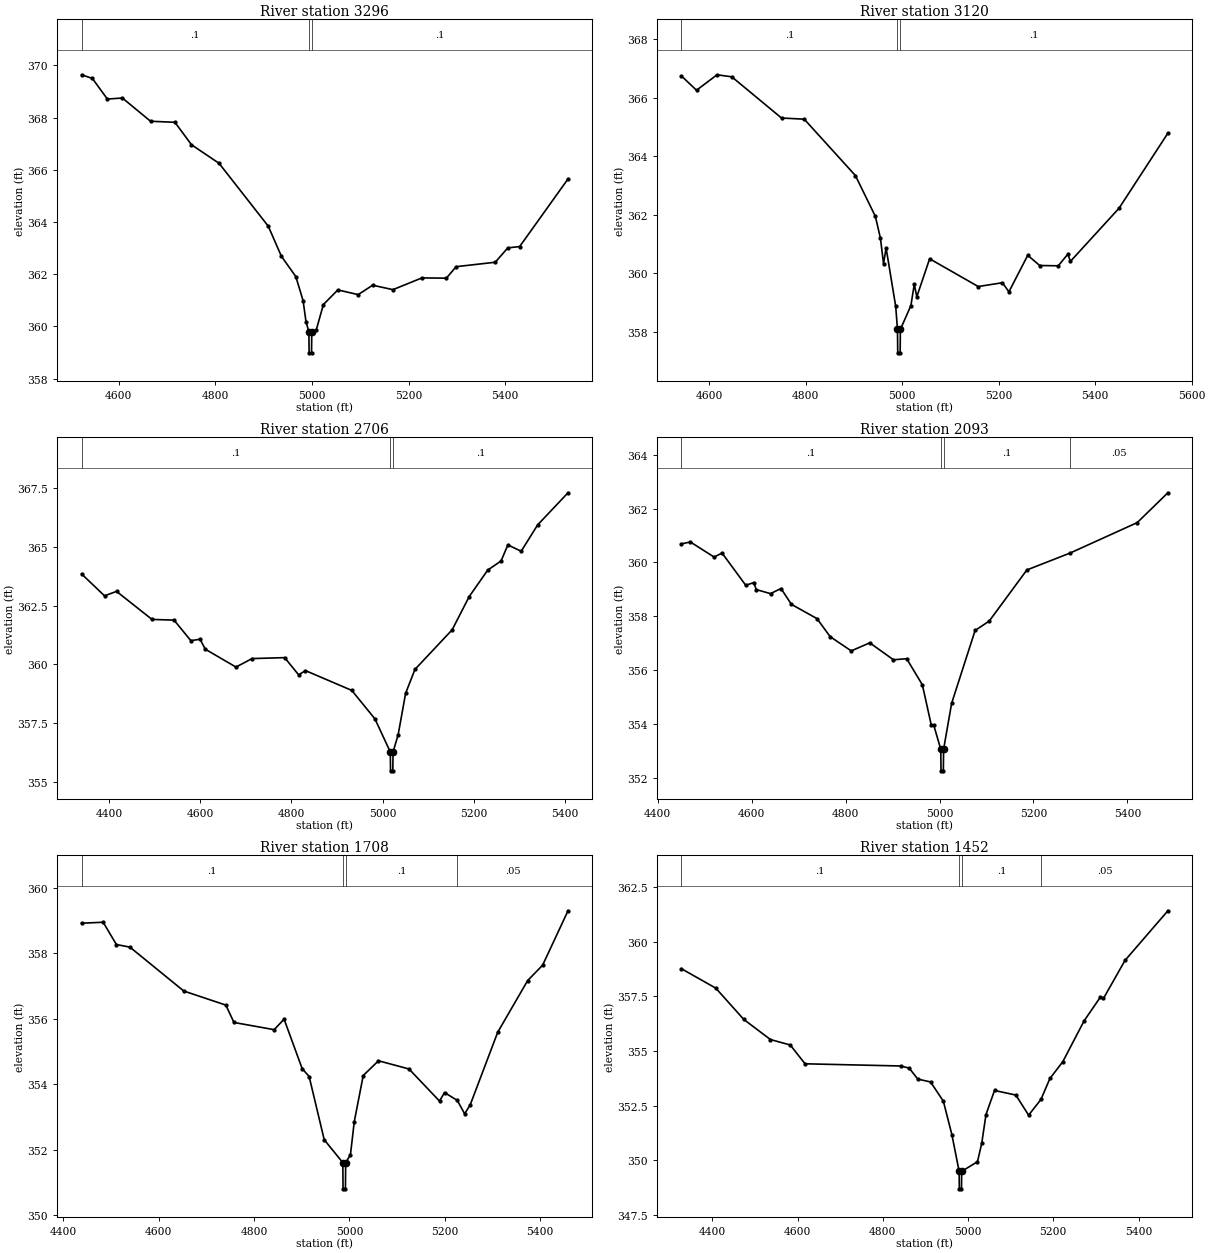
Type RM Length L Ch R = 1,3296,176,176,176
BEGIN DESCRIPTION:
Mapping XS 2cb6a291
END DESCRIPTION:
XS GIS Cut Line= 4
      2070863.37     13439157.22      2071049.98     13439107.31
      2071306.06     13438727.54      2071358.14     13438375.99
#Sta/Elev= 30
  4523.3  369.64  4545.7  369.50  4576.7  368.71  4607.8  368.75  4666.1  367.86
  4716.5  367.82  4750.8  366.96  4807.8  366.25  4909.7  363.84  4936.8  362.69
  4966.7  361.91  4981.7  360.99  4987.7  360.19  4993.7  359.79  4994.2  358.99
  4999.2  358.99  4999.7  359.79  5008.7  359.85  5023.7  360.84  5053.6  361.40
  5095.7  361.22  5125.6  361.58  5167.6  361.41  5227.6  361.86  5278.2  361.85
  5298.4  362.29  5379.3  362.46  5405.3  363.01  5429.8  363.06  5529.9  365.65
#Mann=3,-1,0
  4523.3     0.1       0  4993.7    0.07       0  4999.7     0.1       0
Bank Sta=4993.7,4999.7
Exp/Cntr=0.3,0.1

Type RM Length L Ch R = 1,3120,414,414,414
BEGIN DESCRIPTION:
Mapping XS fdf5cafd
END DESCRIPTION:
XS GIS Cut Line= 4
      2071106.39     13439248.38      2071284.35     13439137.70
      2071473.16     13438562.61      2071444.95     13438371.65
#Sta/Elev= 30
  4542.8  366.75  4574.1  366.26  4616.6  366.79  4647.2  366.72  4750.2  365.31
  4797.3  365.27  4903.3  363.34  4944.7  361.94  4955.2  361.19  4961.6  360.32
  4966.9  360.86  4986.8  358.86  4990.5  358.07  4991.0  357.27  4996.0  357.27
  4996.5  358.07  5018.3  358.89  5025.3  359.62  5030.5  359.19  5057.1  360.49
  5157.8  359.54  5207.8  359.67  5221.4  359.36  5260.4  360.61  5285.1  360.26
  5323.6  360.25  5343.5  360.65  5348.7  360.40  5449.5  362.22  5550.7  364.79
#Mann=3,-1,0
  4542.8     0.1       0  4990.5    0.07       0  4996.5     0.1       0
Bank Sta=4990.5,4996.5
Exp/Cntr=0.3,0.1

Type RM Length L Ch R = 1,2706,613,613,613
BEGIN DESCRIPTION:
Mapping XS 6ae320c0
END DESCRIPTION:
XS GIS Cut Line= 4
      2071575.15     13439261.39      2071674.98     13438964.09
      2071568.64     13438436.74      2071444.95     13438260.98
#Sta/Elev= 30
  4340.0  363.84  4390.4  362.91  4416.7  363.10  4494.4  361.91  4542.8  361.88
  4579.6  361.01  4599.9  361.07  4611.1  360.65  4678.5  359.89  4713.9  360.25
  4785.3  360.29  4815.9  359.56  4830.9  359.74  4932.5  358.90  4983.3  357.69
  5016.9  356.29  5017.4  355.49  5022.4  355.49  5022.9  356.29  5034.1  357.02
  5050.5  358.78  5070.9  359.79  5152.5  361.47  5189.9  362.88  5230.4  364.00
  5259.8  364.39  5274.6  365.07  5303.8  364.80  5340.0  365.92  5406.5  367.28
#Mann=3,-1,0
  4340.0     0.1       0  5016.9    0.07       0  5022.9     0.1       0
Bank Sta=5016.9,5022.9
Exp/Cntr=0.3,0.1

Type RM Length L Ch R = 1,2093,385,385,385
BEGIN DESCRIPTION:
Mapping XS 0caf6b5d
END DESCRIPTION:
XS GIS Cut Line= 3
      2071870.62     13439355.21      2072106.69     13438875.91
      2072133.52     13438375.21
#Sta/Elev= 30
  4450.5  360.69  4469.6  360.76  4520.1  360.20  4537.0  360.35  4587.5  359.15
  4604.4  359.25  4609.9  358.99  4640.2  358.84  4662.5  359.03  4684.8  358.44
  4739.2  357.91  4767.2  357.24  4812.1  356.71  4851.5  357.01  4902.0  356.38
  4930.1  356.42  4963.5  355.45  4982.5  353.95  4987.7  353.95  5002.7  353.05
  5003.2  352.25  5008.2  352.25  5008.7  353.05  5025.8  354.76  5075.8  357.47
  5105.9  357.82  5186.0  359.72  5278.2  360.35  5420.9  361.48  5486.2  362.59
#Mann=4,-1,0
  4450.5     0.1       0  5002.7    0.07       0  5008.7     0.1       0
  5278.2    0.05       0
Bank Sta=5002.7,5008.7
Exp/Cntr=0.3,0.1

Type RM Length L Ch R = 1,1708,256,256,256
BEGIN DESCRIPTION:
Mapping XS 4ebd4b6a
END DESCRIPTION:
XS GIS Cut Line= 4
      2072245.71     13439489.28      2072341.21     13439382.92
      2072538.69     13438773.11      2072462.81     13438549.79
#Sta/Elev= 30
  4438.3  358.91  4483.6  358.94  4511.3  358.26  4539.7  358.18  4652.6  356.84
  4740.8  356.41  4757.8  355.88  4842.0  355.66  4862.9  355.98  4900.8  354.47
  4915.4  354.23  4947.0  352.30  4986.0  351.60  4986.5  350.80  4991.5  350.80
  4992.0  351.60  5002.0  351.84  5010.0  352.85  5028.8  354.26  5060.8  354.71
  5124.7  354.46  5188.7  353.48  5199.2  353.74  5226.0  353.50  5241.4  353.09
  5253.2  353.37  5310.7  355.58  5373.5  357.16  5404.9  357.63  5458.1  359.29
#Mann=4,-1,0
  4438.3     0.1       0  4986.0    0.07       0  4992.0     0.1       0
  5226.0    0.05       0
Bank Sta=4986,4992
Exp/Cntr=0.3,0.1

Type RM Length L Ch R = 1,1452,423,423,423
BEGIN DESCRIPTION:
Mapping XS a92bad44
END DESCRIPTION:
XS GIS Cut Line= 4
      2072525.69     13439539.13      2072671.07     13439204.97
      2072662.39     13438584.31      2072573.44     13438456.31
#Sta/Elev= 30
  4327.7  358.77  4408.4  357.88  4474.0  356.45  4536.5  355.53  4583.0  355.28
  4617.7  354.42  4842.1  354.32  4862.1  354.22  4882.1  353.72  4912.1  353.59
  4942.1  352.71  4962.1  351.18  4979.1  349.50  4979.6  348.70  4984.6  348.70
  4985.1  349.50  5022.1  349.94  5032.1  350.78  5042.1  352.10  5062.1  353.20
  5112.1  352.99  5142.1  352.07  5171.0  352.79  5192.1  353.75  5222.1  354.51
  5272.1  356.38  5310.0  357.46  5317.6  357.41  5368.2  359.15  5468.7  361.42
#Mann=4,-1,0
  4327.7     0.1       0  4979.1    0.07       0  4985.1     0.1       0
  5171.0    0.05       0
Bank Sta=4979.1,4985.1
Exp/Cntr=0.3,0.1

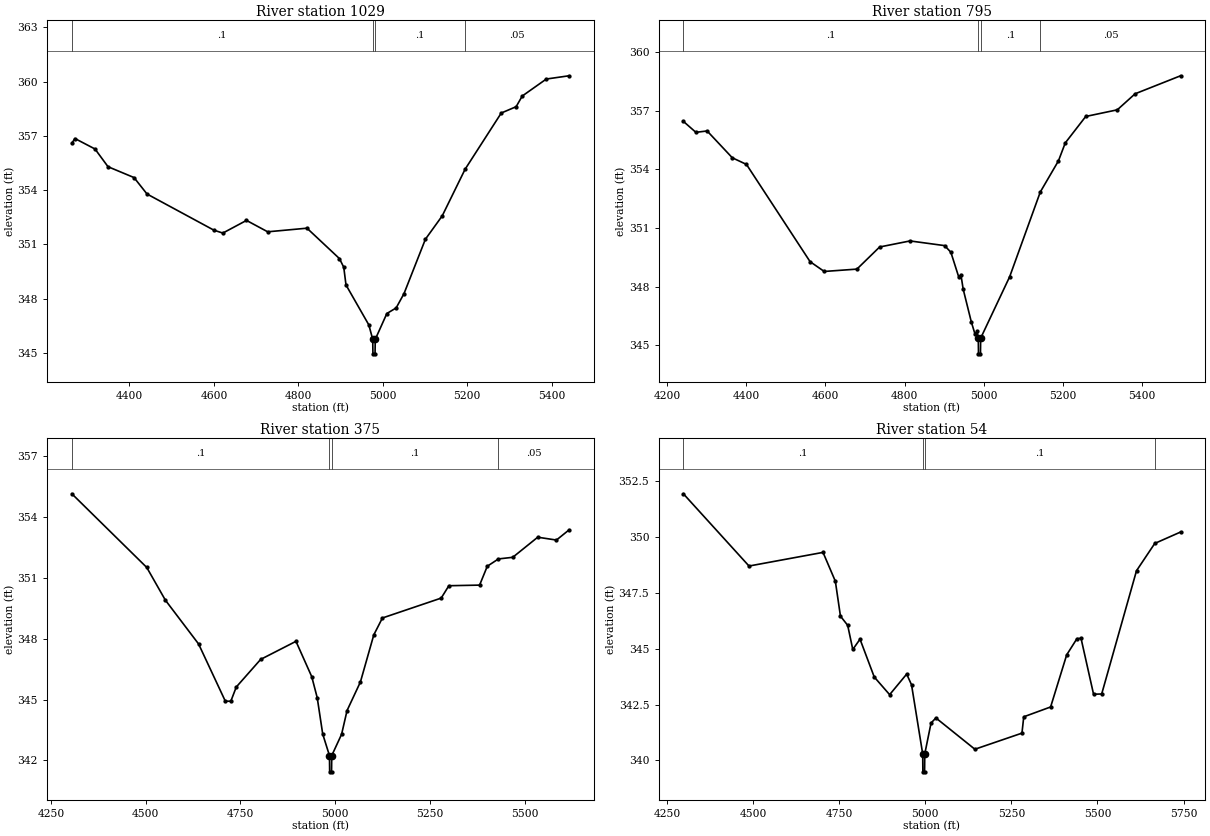
Type RM Length L Ch R = 1,1029,234,234,234
BEGIN DESCRIPTION:
Mapping XS 48a5b69b
END DESCRIPTION:
XS GIS Cut Line= 4
      2072831.55     13439581.84      2073050.29     13438969.88
      2073112.79     13438610.50      2073011.25     13438482.93
#Sta/Elev= 30
  4263.5  356.59  4270.8  356.85  4318.4  356.27  4349.2  355.29  4410.8  354.69
  4441.6  353.78  4600.0  351.78  4621.2  351.62  4677.2  352.32  4727.4  351.69
  4820.5  351.89  4897.3  350.21  4907.6  349.73  4912.9  348.75  4967.0  346.54
  4976.2  345.74  4976.7  344.94  4981.7  344.94  4982.2  345.74  5009.7  347.17
  5031.7  347.48  5050.3  348.27  5101.0  351.28  5140.8  352.57  5195.0  355.15
  5280.7  358.26  5315.9  358.61  5330.4  359.20  5387.4  360.14  5441.2  360.32
#Mann=4,-1,0
  4263.5     0.1       0  4976.2    0.07       0  4982.2     0.1       0
  5195.0    0.05       0
Bank Sta=4976.2,4982.2
Exp/Cntr=0.3,0.1

Type RM Length L Ch R = 1,795,420,420,420
BEGIN DESCRIPTION:
Mapping XS e13e365b
END DESCRIPTION:
XS GIS Cut Line= 4
      2072940.90     13439615.73      2073157.06     13439378.73
      2073339.35     13438657.38      2073284.67     13438475.10
#Sta/Elev= 30
  4241.7  356.45  4273.3  355.89  4301.7  355.96  4365.2  354.59  4401.0  354.25
  4561.6  349.28  4597.3  348.78  4679.8  348.90  4737.1  350.03  4813.9  350.34
  4901.3  350.10  4917.0  349.76  4937.1  348.48  4942.3  348.62  4948.0  347.88
  4968.6  346.20  4978.2  345.56  4983.3  345.74  4986.2  345.37  4986.7  344.57
  4991.7  344.57  4992.2  345.37  5065.4  348.51  5142.7  352.84  5188.5  354.43
  5205.8  355.35  5257.4  356.70  5337.1  357.04  5382.1  357.86  5496.8  358.78
#Mann=4,-1,0
  4241.7     0.1       0  4986.2    0.07       0  4992.2     0.1       0
  5142.7    0.05       0
Bank Sta=4986.2,4992.2
Exp/Cntr=0.3,0.1

Type RM Length L Ch R = 1,375,321,321,321
BEGIN DESCRIPTION:
Mapping XS e9c4e480
END DESCRIPTION:
XS GIS Cut Line= 4
      2073081.52     13439628.75      2073323.73     13439493.32
      2073696.12     13439014.15      2073625.80     13438592.23
#Sta/Elev= 30
  4305.0  355.14  4502.7  351.51  4551.8  349.90  4639.5  347.74  4710.1  344.92
  4724.6  344.92  4739.0  345.62  4803.3  346.98  4896.5  347.87  4938.1  346.13
  4952.6  345.09  4967.1  343.30  4984.9  342.24  4985.4  341.44  4990.4  341.44
  4990.9  342.24  5016.9  343.29  5031.3  344.46  5066.6  345.87  5101.9  348.19
  5124.6  349.02  5279.7  350.00  5300.0  350.61  5381.1  350.64  5401.4  351.57
  5430.8  351.93  5468.6  352.01  5534.5  353.00  5583.9  352.86  5617.1  353.36
#Mann=4,-1,0
  4305.0     0.1       0  4984.9    0.07       0  4990.9     0.1       0
  5430.8    0.05       0
Bank Sta=4984.9,4990.9
Exp/Cntr=0.3,0.1

Type RM Length L Ch R = 1,54,0,0,0
BEGIN DESCRIPTION:
UNT 63 in Lagunillas Cr Wtrshd 1.0
END DESCRIPTION:
XS GIS Cut Line= 4
      2073266.44     13439720.75      2073723.87     13439403.75
      2073939.15     13439188.47      2073800.29     13438622.65
#Sta/Elev= 30
  4297.7  351.92  4488.3  348.69  4703.2  349.30  4739.0  348.01  4753.8  346.45
  4774.8  346.04  4789.6  344.96  4810.6  345.42  4851.9  343.73  4896.6  342.94
  4946.1  343.86  4960.2  343.38  4992.6  340.29  4993.1  339.49  4998.1  339.49
  4998.6  340.29  5016.8  341.67  5030.9  341.90  5144.1  340.50  5280.8  341.22
  5286.0  341.95  5364.0  342.39  5410.7  344.72  5440.3  345.44  5452.3  345.46
  5488.7  342.96  5512.3  342.97  5613.4  348.48  5666.4  349.70  5741.3  350.21
#Mann=4,-1,0
  4297.7     0.1       0  4992.6    0.07       0  4998.6     0.1       0
  5666.4    0.05       0
Bank Sta=4992.6,4998.6
Exp/Cntr=0.3,0.1

Chan Stop Cuts=-1