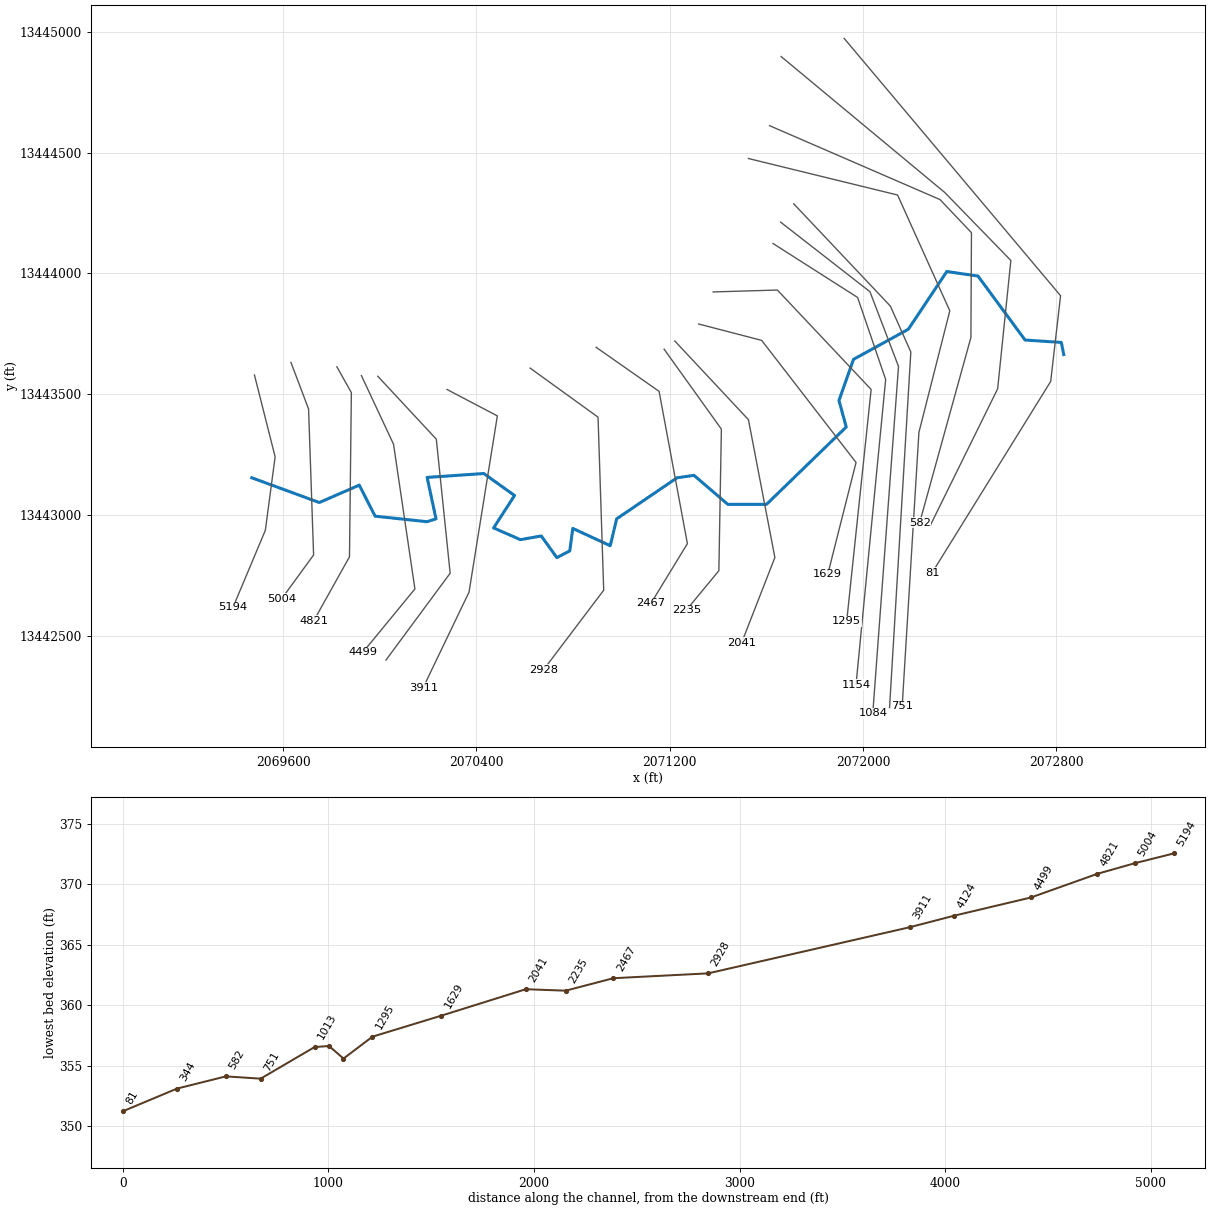
--- UNT 64 in Lagunillas Cr Wtrshd.prj (project) ---

Proj Title=UNT 64 in Lagunillas Cr Wtrshd Base Level Engineering
Current Plan=p01
Default Exp/Contr=0.3,0.1
English Units
Geom File=g01
Flow File=f01
Plan File=p01
BEGIN DESCRIPTION:
UNT 64 in Lagunillas Cr Wtrshd
END DESCRIPTION:

--- UNT 64 in Lagunillas Cr Wtrshd.p01 (plan) ---

Plan Title=Multiple Run
Short Identifier=Multiple
Geom File=g01
Flow File=f01
Subcritical Flow
K Sum by GR= 0
Std Step Tol= 0.01
Critical Tol= 0.01
Num of Std Step Trials= 20
Max Error Tol= 0.3
Flow Tol Ratio= 0.001
Split Flow NTrial= 30
Split Flow Tol= 0.02
Split Flow Ratio= 0.02
Log Output Level= 0
Friction Slope Method= 1
Unsteady Friction Slope Method= 2
Unsteady Bridges Friction Slope Method= 1
Parabolic Critical Depth
Global Vel Dist=  1 , 1 , 1
Global Log Level= 0
CheckData=True
Encroach Param= -1, 0, 0, 0
BEGIN DESCRIPTION:
Multiple Run
END DESCRIPTION:

--- UNT 64 in Lagunillas Cr Wtrshd.f01 (steady flow) ---

Flow Title=Multiple
Number of Profiles=7
Profile Names=10-year,25-year,50-year,1pct_min,100-year,1pct_plu,500-year
River Rch & RM= UNT 64 in Laguni,Reach-1,5194
     151     203     245     147     294     587     431
Boundary for River Rch & Prof#=UNT 64 in Laguni,Reach-1,1
Up Type=0
Dn Type=3
Dn Slope=0.005
Boundary for River Rch & Prof#=UNT 64 in Laguni,Reach-1,2
Up Type=0
Dn Type=3
Dn Slope=0.005
Boundary for River Rch & Prof#=UNT 64 in Laguni,Reach-1,3
Up Type=0
Dn Type=3
Dn Slope=0.005
Boundary for River Rch & Prof#=UNT 64 in Laguni,Reach-1,4
Up Type=0
Dn Type=3
Dn Slope=0.005
Boundary for River Rch & Prof#=UNT 64 in Laguni,Reach-1,5
Up Type=0
Dn Type=3
Dn Slope=0.005
Boundary for River Rch & Prof#=UNT 64 in Laguni,Reach-1,6
Up Type=0
Dn Type=3
Dn Slope=0.005
Boundary for River Rch & Prof#=UNT 64 in Laguni,Reach-1,7
Up Type=0
Dn Type=3
Dn Slope=0.005

--- UNT 64 in Lagunillas Cr Wtrshd.g01 (geometry) ---

Geom Title=Existing Conditions

River Reach=UNT 64 in Laguni,Reach-1
Reach XY= 30
      2069470.80     13443154.54      2069750.22     13443052.05
      2069915.59     13443124.09      2069981.10     13442995.65
      2070195.68     13442972.73      2070233.18     13442984.54
      2070196.37     13443156.07      2070431.10     13443172.04
      2070558.18     13443081.07      2070471.37     13442947.04
      2070582.48     13442898.43      2070668.60     13442913.71
      2070733.18     13442824.12      2070786.65     13442851.90
      2070799.15     13442944.96      2070954.01     13442873.43
      2070980.80     13442984.54      2071230.80     13443154.54
      2071300.80     13443164.54      2071440.80     13443044.54
      2071600.80     13443044.54      2071930.80     13443364.54
      2071900.80     13443474.54      2071960.80     13443644.54
      2072187.82     13443769.22      2072346.81     13444007.97
      2072476.08     13443989.26      2072670.80     13443724.54
      2072820.80     13443714.54      2072830.80     13443664.54

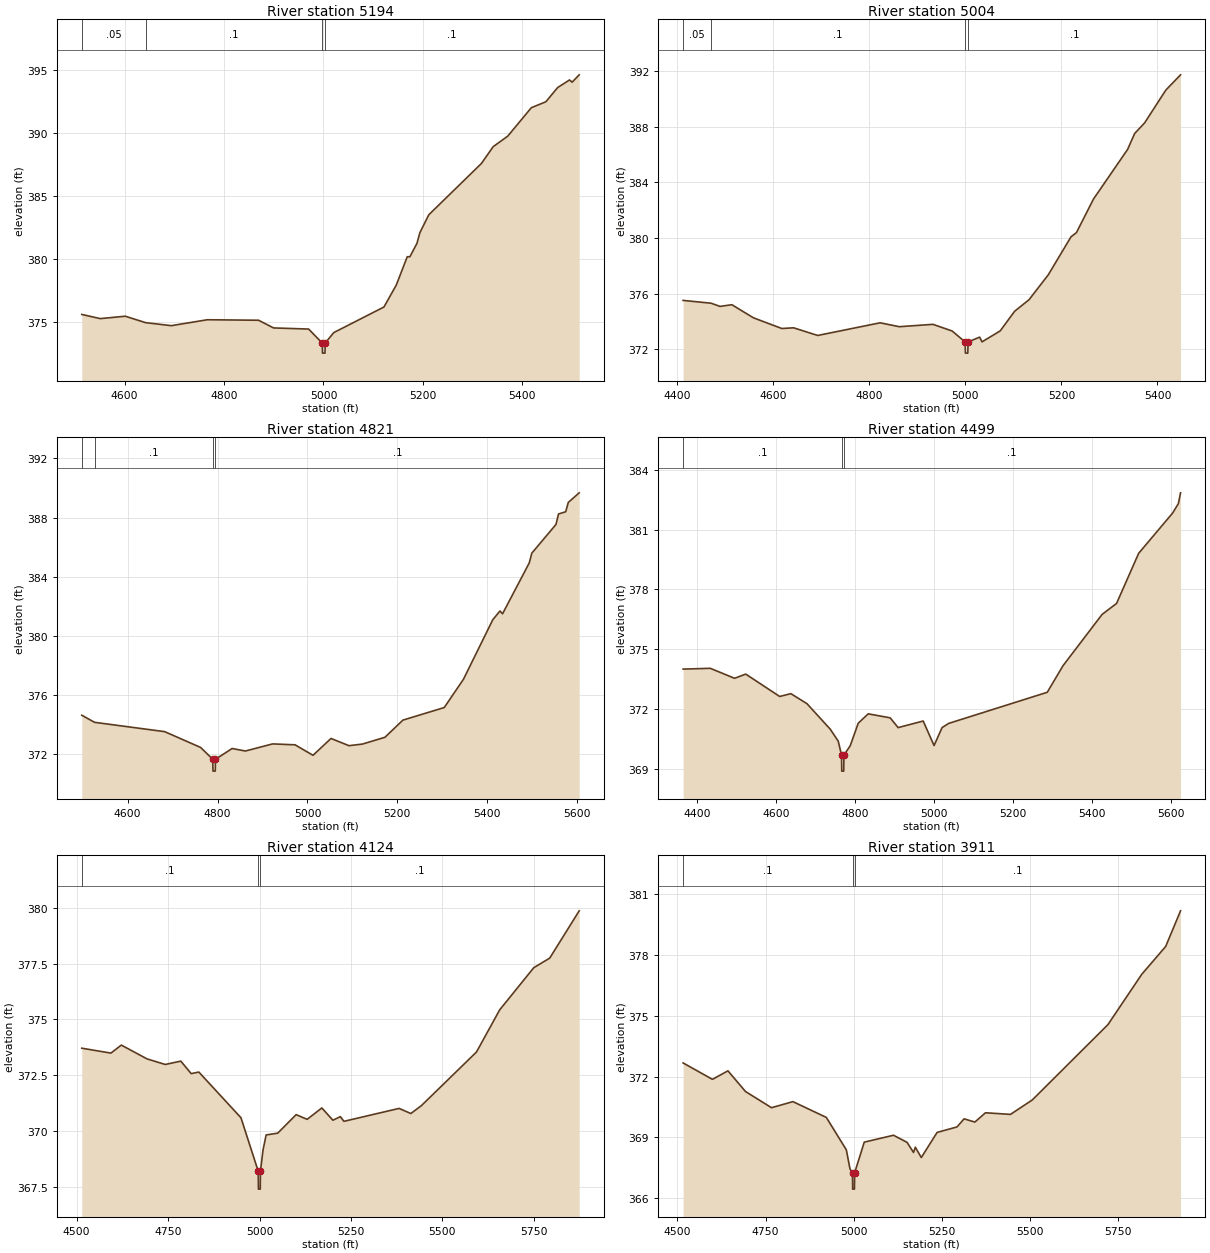
Type RM Length L Ch R = 1,5194,190,190,190
BEGIN DESCRIPTION:
UNT 64 in Lagunillas Cr Wtrshd 2.0
END DESCRIPTION:
XS GIS Cut Line= 4
      2069481.79     13443579.85      2069567.39     13443241.19
      2069526.81     13442937.03      2069393.47     13442619.45
#Sta/Elev= 30
  4513.8  375.61  4551.1  375.28  4601.3  375.47  4642.0  374.96  4694.1  374.72
  4766.3  375.19  4869.4  375.15  4899.6  374.54  4970.2  374.45  4997.5  373.34
  4998.0  372.54  5003.0  372.54  5003.5  373.34  5020.7  374.17  5121.6  376.20
  5146.3  377.93  5168.5  380.19  5173.8  380.19  5188.0  381.25  5193.9  382.10
  5211.8  383.52  5317.6  387.59  5341.4  388.93  5370.6  389.76  5418.1  392.02
  5447.3  392.49  5471.1  393.62  5494.8  394.22  5500.2  394.05  5514.4  394.63
#Mann=4,-1,0
  4513.8    0.05       0  4642.0     0.1       0  4997.5    0.07       0
  5003.5     0.1       0
Bank Sta=4997.5,5003.5
Exp/Cntr=0.3,0.1

Type RM Length L Ch R = 1,5004,183,183,183
BEGIN DESCRIPTION:
Mapping XS 8edaa31a
END DESCRIPTION:
XS GIS Cut Line= 4
      2069632.85     13443631.90      2069705.75     13443439.24
      2069726.58     13442835.07      2069593.74     13442652.75
#Sta/Elev= 30
  4412.0  375.52  4470.1  375.32  4488.8  375.09  4513.6  375.21  4558.4  374.27
  4617.6  373.50  4642.2  373.55  4692.3  373.00  4822.4  373.91  4862.4  373.63
  4932.4  373.80  4972.4  373.32  4999.5  372.53  5000.0  371.73  5005.0  371.73
  5005.5  372.53  5029.6  372.88  5034.6  372.54  5072.5  373.33  5102.5  374.74
  5132.5  375.57  5172.6  377.36  5220.1  380.10  5231.2  380.39  5266.8  382.81
  5337.9  386.38  5352.5  387.52  5373.4  388.29  5417.4  390.64  5448.1  391.74
#Mann=4,-1,0
  4412.0    0.05       0  4470.1     0.1       0  4999.5    0.07       0
  5005.5     0.1       0
Bank Sta=4999.5,5005.5
Exp/Cntr=0.3,0.1

Type RM Length L Ch R = 1,4821,322,322,322
BEGIN DESCRIPTION:
Mapping XS b1e6838d
END DESCRIPTION:
XS GIS Cut Line= 4
      2069822.92     13443613.74      2069882.83     13443506.94
      2069875.02     13442827.26      2069726.56     13442561.61
#Sta/Elev= 30
  4498.0  374.63  4526.5  374.15  4682.4  373.52  4762.4  372.45  4789.4  371.65
  4789.9  370.85  4794.9  370.85  4795.4  371.65  4832.4  372.38  4862.0  372.21
  4922.4  372.69  4972.4  372.63  5012.4  371.92  5052.4  373.06  5092.4  372.57
  5122.4  372.68  5172.4  373.14  5212.4  374.30  5304.3  375.15  5347.2  377.07
  5412.3  381.09  5428.3  381.68  5434.0  381.49  5493.4  384.93  5499.1  385.59
  5552.8  387.53  5558.5  388.24  5574.5  388.39  5580.2  389.02  5604.5  389.67
#Mann=4,-1,0
  4498.0    0.05       0  4526.5     0.1       0  4789.4    0.07       0
  4795.4     0.1       0
Bank Sta=4789.4,4795.4
Exp/Cntr=0.3,0.1

Type RM Length L Ch R = 1,4499,375,375,375
BEGIN DESCRIPTION:
Mapping XS 4c6a83dd
END DESCRIPTION:
XS GIS Cut Line= 4
      2069924.51     13443577.22      2070057.31     13443293.40
      2070145.85     13442694.44      2069929.87     13442431.62
#Sta/Elev= 30
  4364.5  374.01  4433.2  374.05  4494.7  373.55  4523.0  373.76  4608.9  372.64
  4637.2  372.78  4677.9  372.28  4736.9  371.00  4757.1  370.40  4765.5  369.70
  4766.0  368.90  4771.0  368.90  4771.5  369.70  4787.4  370.17  4807.7  371.30
  4833.0  371.77  4888.5  371.57  4908.7  371.08  4972.1  371.41  4999.7  370.18
  5019.9  371.08  5036.6  371.29  5286.2  372.85  5326.0  374.18  5425.0  376.75
  5461.6  377.30  5517.5  379.81  5603.6  381.83  5618.0  382.30  5623.5  382.84
#Mann=3,-1,0
  4364.5     0.1       0  4765.5    0.07       0  4771.5     0.1       0
Bank Sta=4765.5,4771.5
Exp/Cntr=0.3,0.1

Type RM Length L Ch R = 1,4124,213,213,213
BEGIN DESCRIPTION:
Mapping XS 64a261eb
END DESCRIPTION:
XS GIS Cut Line= 4
      2069992.22     13443574.64      2070234.39     13443314.24
      2070291.68     13442759.55      2070026.08     13442400.20
#Sta/Elev= 30
  4514.0  373.71  4593.7  373.49  4622.1  373.85  4692.4  373.23  4742.3  372.98
  4784.8  373.13  4813.1  372.57  4834.1  372.64  4949.3  370.59  4996.5  368.19
  4997.0  367.39  5002.0  367.39  5002.5  368.19  5009.6  369.15  5018.1  369.82
  5049.8  369.90  5100.1  370.73  5130.2  370.52  5170.4  371.03  5200.6  370.48
  5221.0  370.64  5230.8  370.43  5381.6  371.01  5413.8  370.78  5443.0  371.14
  5593.3  373.54  5656.7  375.43  5749.9  377.32  5793.5  377.75  5874.1  379.87
#Mann=3,-1,0
  4514.0     0.1       0  4996.5    0.07       0  5002.5     0.1       0
Bank Sta=4996.5,5002.5
Exp/Cntr=0.3,0.1

Type RM Length L Ch R = 1,3911,983,983,983
BEGIN DESCRIPTION:
Mapping XS bd44f95e
END DESCRIPTION:
XS GIS Cut Line= 4
      2070278.70     13443519.95      2070487.00     13443410.59
      2070369.81     13442681.42      2070179.83     13442285.86
#Sta/Elev= 30
  4516.0  372.68  4599.2  371.87  4643.3  372.29  4693.1  371.27  4767.0  370.47
  4827.8  370.77  4922.7  369.99  4979.5  368.39  4989.9  367.45  4997.0  367.25
  4997.5  366.45  5002.5  366.45  5003.0  367.25  5030.4  368.77  5113.5  369.11
  5151.9  368.76  5170.3  368.26  5175.4  368.52  5192.4  368.01  5237.3  369.25
  5293.7  369.52  5314.0  369.92  5344.4  369.76  5374.7  370.22  5445.6  370.14
  5507.4  370.85  5722.3  374.57  5818.6  377.06  5886.4  378.43  5928.6  380.19
#Mann=3,-1,0
  4516.0     0.1       0  4997.0    0.07       0  5003.0     0.1       0
Bank Sta=4997,5003
Exp/Cntr=0.3,0.1

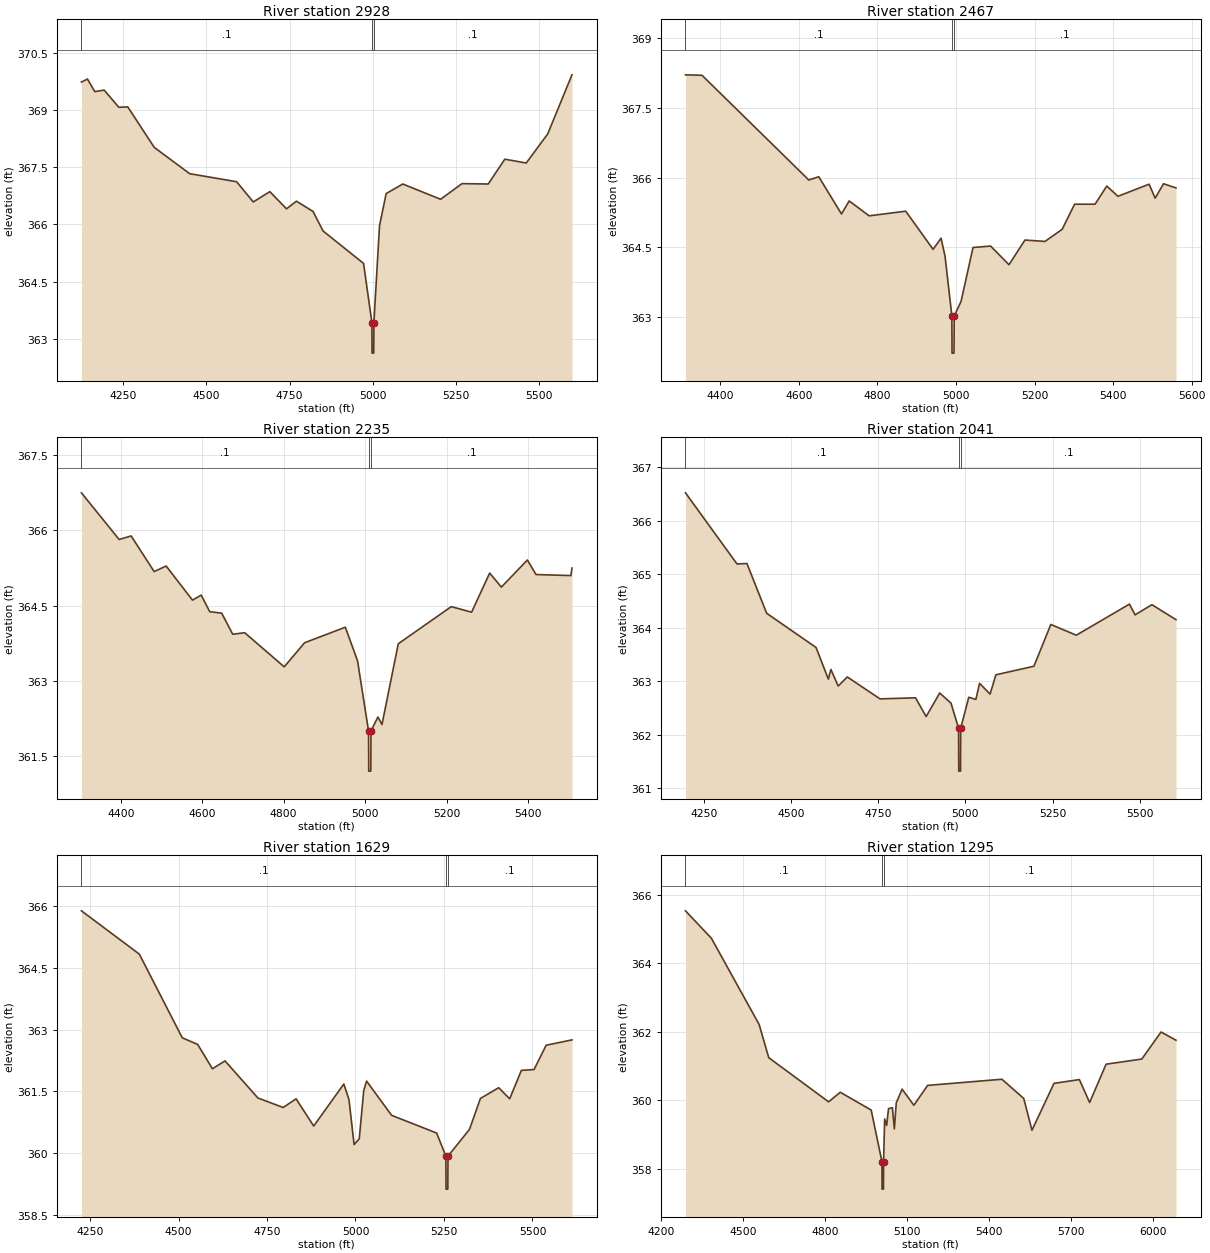
Type RM Length L Ch R = 1,2928,461,461,461
BEGIN DESCRIPTION:
Mapping XS 054d8148
END DESCRIPTION:
XS GIS Cut Line= 4
      2070622.45     13443608.48      2070903.66     13443405.38
      2070927.10     13442689.24      2070677.64     13442359.23
#Sta/Elev= 30
  4123.5  369.73  4141.6  369.81  4163.7  369.48  4191.9  369.52  4236.0  369.07
  4263.0  369.08  4342.7  368.02  4449.5  367.33  4590.8  367.12  4640.9  366.59
  4690.9  366.86  4740.9  366.41  4770.9  366.61  4821.0  366.34  4851.0  365.83
  4973.0  364.98  4998.1  363.43  4998.6  362.63  5003.6  362.63  5004.1  363.43
  5021.1  365.97  5041.1  366.81  5091.1  367.06  5204.9  366.66  5269.4  367.07
  5348.4  367.06  5398.4  367.71  5462.9  367.61  5527.4  368.37  5600.6  369.92
#Mann=3,-1,0
  4123.5     0.1       0  4998.1    0.07       0  5004.1     0.1       0
Bank Sta=4998.1,5004.1
Exp/Cntr=0.3,0.1

Type RM Length L Ch R = 1,2467,232,232,232
BEGIN DESCRIPTION:
Mapping XS c3da4014
END DESCRIPTION:
XS GIS Cut Line= 4
      2070895.86     13443694.44      2071156.27     13443512.15
      2071273.45     13442881.94      2071122.43     13442634.58
#Sta/Elev= 30
  4311.5  368.21  4353.6  368.20  4625.5  365.95  4650.8  366.02  4708.7  365.22
  4728.2  365.50  4779.0  365.18  4872.1  365.28  4941.8  364.46  4962.1  364.70
  4972.3  364.31  4989.6  363.03  4990.1  362.23  4995.1  362.23  4995.6  363.03
  5013.0  363.34  5043.5  364.50  5088.3  364.53  5135.0  364.13  5175.7  364.66
  5226.6  364.63  5270.4  364.89  5302.0  365.43  5354.2  365.43  5384.0  365.82
  5412.3  365.60  5491.7  365.86  5507.1  365.56  5528.4  365.87  5560.2  365.78
#Mann=3,-1,0
  4311.5     0.1       0  4989.6    0.07       0  4995.6     0.1       0
Bank Sta=4989.6,4995.6
Exp/Cntr=0.3,0.1

Type RM Length L Ch R = 1,2235,194,194,194
BEGIN DESCRIPTION:
Mapping XS c17f93da
END DESCRIPTION:
XS GIS Cut Line= 4
      2071177.11     13443686.62      2071414.08     13443355.90
      2071403.66     13442769.97      2071269.15     13442607.00
#Sta/Elev= 30
  4303.6  366.75  4396.1  365.82  4425.6  365.89  4482.1  365.18  4511.6  365.29
  4576.2  364.61  4597.6  364.71  4618.5  364.38  4647.9  364.35  4675.0  363.93
  4704.4  363.96  4801.4  363.28  4851.4  363.76  4951.4  364.07  4981.4  363.40
  5008.4  362.00  5008.9  361.20  5013.9  361.20  5014.4  362.00  5031.4  362.28
  5041.4  362.13  5081.4  363.74  5211.4  364.48  5261.4  364.37  5305.8  365.15
  5334.5  364.87  5398.3  365.41  5419.6  365.12  5505.2  365.10  5507.8  365.25
#Mann=3,-1,0
  4303.6     0.1       0  5008.4    0.07       0  5014.4     0.1       0
Bank Sta=5008.4,5014.4
Exp/Cntr=0.3,0.1

Type RM Length L Ch R = 1,2041,412,412,412
BEGIN DESCRIPTION:
Mapping XS 6dc34544
END DESCRIPTION:
XS GIS Cut Line= 4
      2071221.36     13443720.50      2071526.06     13443394.97
      2071635.43     13442824.65      2071497.41     13442470.49
#Sta/Elev= 30
  4197.3  366.52  4345.2  365.19  4373.5  365.20  4430.1  364.27  4571.8  363.63
  4607.0  363.04  4614.3  363.22  4635.3  362.91  4661.3  363.08  4755.2  362.67
  4857.0  362.69  4887.5  362.34  4926.4  362.78  4958.8  362.59  4980.5  362.12
  4981.0  361.32  4986.0  361.32  4986.5  362.12  5009.7  362.70  5030.1  362.66
  5040.6  362.96  5070.8  362.76  5087.5  363.12  5196.6  363.28  5245.0  364.06
  5318.1  363.86  5470.4  364.44  5486.6  364.24  5534.8  364.43  5604.0  364.15
#Mann=3,-1,0
  4197.3     0.1       0  4980.5    0.07       0  4986.5     0.1       0
Bank Sta=4980.5,4986.5
Exp/Cntr=0.3,0.1

Type RM Length L Ch R = 1,1629,334,334,334
BEGIN DESCRIPTION:
Mapping XS e698be5a
END DESCRIPTION:
XS GIS Cut Line= 4
      2071320.35     13443790.79      2071580.75     13443723.09
      2071971.37     13443217.88      2071854.18     13442754.33
#Sta/Elev= 30
  4225.8  365.88  4389.3  364.83  4510.7  362.80  4554.2  362.64  4595.8  362.05
  4631.5  362.24  4724.4  361.34  4795.8  361.11  4832.2  361.32  4882.0  360.66
  4967.1  361.68  4981.6  361.30  4996.1  360.21  5010.6  360.35  5023.3  361.52
  5031.4  361.75  5102.0  360.92  5229.3  360.49  5255.3  359.93  5255.8  359.13
  5260.8  359.13  5261.3  359.93  5322.1  360.58  5353.0  361.33  5404.6  361.59
  5435.6  361.32  5468.6  362.01  5504.4  362.03  5538.7  362.62  5611.6  362.75
#Mann=3,-1,0
  4225.8     0.1       0  5255.3    0.07       0  5261.3     0.1       0
Bank Sta=5255.3,5261.3
Exp/Cntr=0.3,0.1

Type RM Length L Ch R = 1,1295,141,141,141
BEGIN DESCRIPTION:
Mapping XS 068ad0e4
END DESCRIPTION:
XS GIS Cut Line= 4
      2071380.24     13443923.61      2071645.85     13443931.42
      2072033.87     13443519.97      2071932.63     13442560.47
#Sta/Elev= 30
  4289.8  365.53  4384.6  364.73  4559.5  362.21  4594.7  361.24  4814.0  359.95
  4856.5  360.23  4969.8  359.71  5009.2  358.20  5009.7  357.40  5014.7  357.40
  5015.2  358.20  5019.1  359.45  5026.4  359.26  5033.3  359.75  5047.4  359.78
  5054.7  359.16  5061.6  359.92  5083.0  360.32  5126.1  359.85  5176.4  360.43
  5448.4  360.61  5528.3  360.05  5558.5  359.12  5639.2  360.49  5732.1  360.60
  5769.6  359.93  5830.0  361.05  5960.7  361.20  6031.1  361.99  6085.9  361.75
#Mann=3,-1,0
  4289.8     0.1       0  5009.2    0.07       0  5015.2     0.1       0
Bank Sta=5009.2,5015.2
Exp/Cntr=0.3,0.1

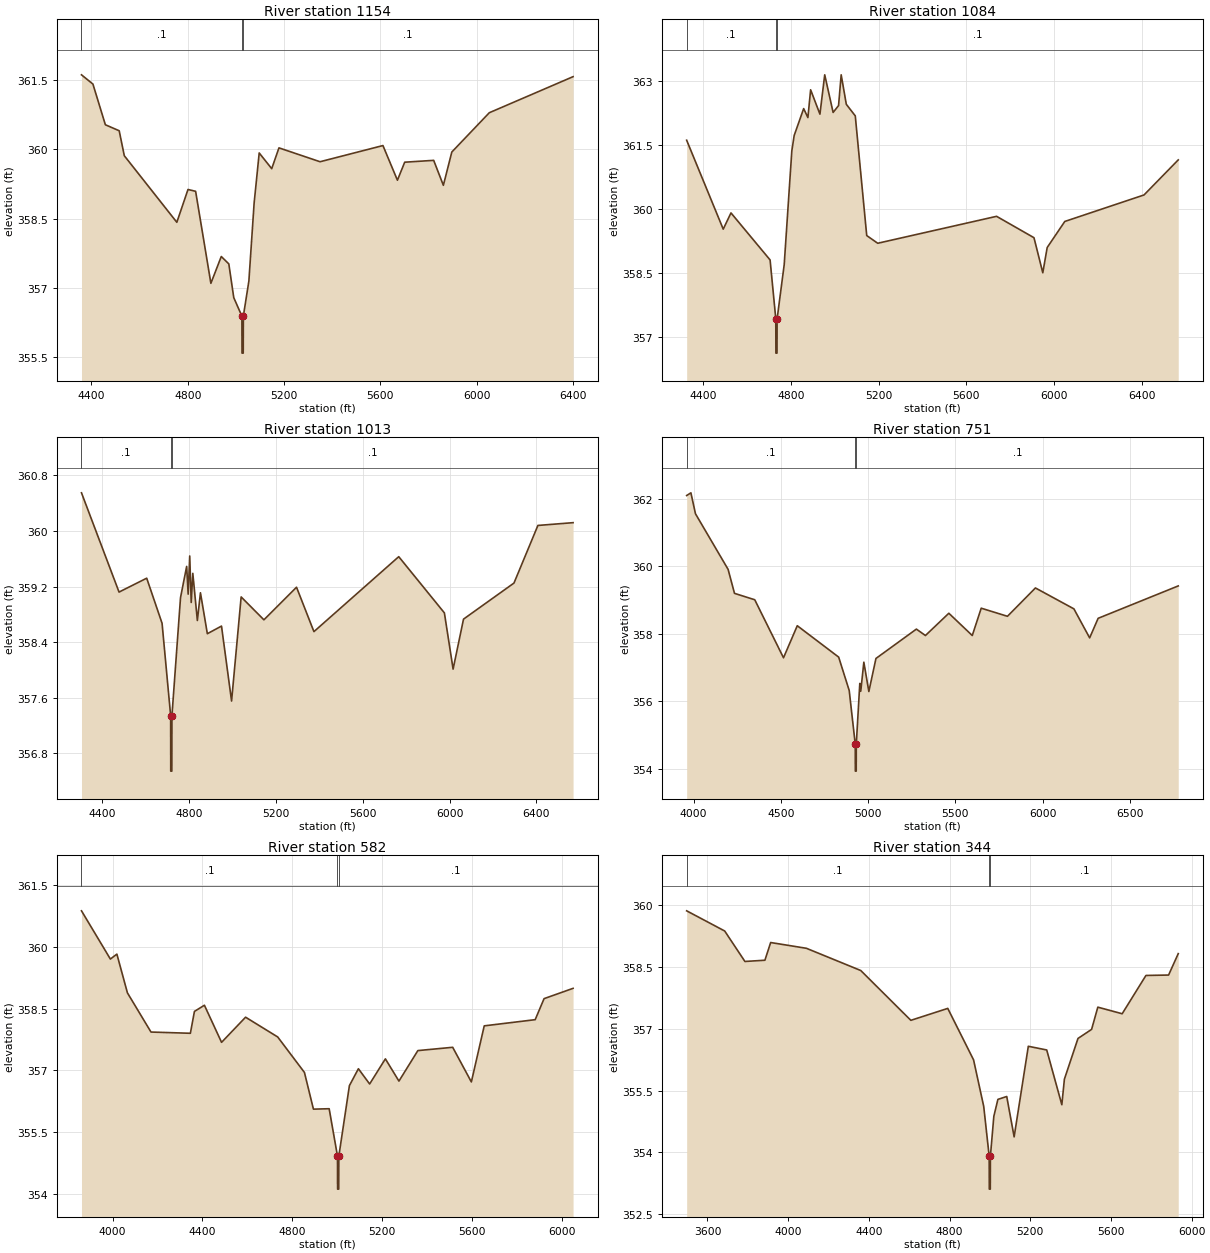
Type RM Length L Ch R = 1,1154,70,70,70
BEGIN DESCRIPTION:
Mapping XS d8f12b3c
END DESCRIPTION:
XS GIS Cut Line= 4
      2071627.64     13444124.12      2071977.84     13443900.74
      2072093.94     13443561.12      2071971.27     13442298.55
#Sta/Elev= 30
  4358.5  361.61  4406.0  361.41  4457.7  360.53  4515.2  360.40  4536.4  359.86
  4754.7  358.42  4801.1  359.13  4832.8  359.09  4896.2  357.10  4939.4  357.68
  4970.7  357.52  4991.3  356.79  5025.1  356.39  5025.6  355.59  5030.6  355.59
  5031.1  356.39  5054.1  357.15  5075.8  358.83  5097.0  359.92  5149.0  359.58
  5179.1  360.03  5349.9  359.73  5611.2  360.08  5671.4  359.33  5701.6  359.72
  5822.1  359.76  5862.3  359.22  5897.4  359.94  6053.2  360.79  6401.3  361.57
#Mann=3,-1,0
  4358.5     0.1       0  5025.1    0.07       0  5031.1     0.1       0
Bank Sta=5025.1,5031.1
Exp/Cntr=0.3,0.1

Type RM Length L Ch R = 1,1084,71,71,71
BEGIN DESCRIPTION:
Mapping XS c4b99185
END DESCRIPTION:
XS GIS Cut Line= 4
      2071658.90     13444212.65      2072028.84     13443924.61
      2072147.11     13443615.37      2072040.61     13442179.54
#Sta/Elev= 30
  4325.5  361.61  4492.1  359.53  4527.4  359.91  4705.6  358.81  4731.6  357.43
  4732.1  356.63  4737.1  356.63  4737.6  357.43  4769.9  358.70  4804.6  361.36
  4815.3  361.72  4858.6  362.35  4877.9  362.14  4890.3  362.79  4932.7  362.22
  4954.5  363.14  4992.8  362.26  5017.5  362.42  5029.5  363.14  5052.9  362.45
  5093.7  362.18  5145.9  359.38  5196.0  359.20  5737.5  359.83  5907.9  359.33
  5948.1  358.51  5968.1  359.10  6048.3  359.71  6409.3  360.33  6565.2  361.15
#Mann=3,-1,0
  4325.5     0.1       0  4731.6    0.07       0  4737.6     0.1       0
Bank Sta=4731.6,4737.6
Exp/Cntr=0.3,0.1

Type RM Length L Ch R = 1,1013,262,262,262
BEGIN DESCRIPTION:
Mapping XS 686e9c51
END DESCRIPTION:
XS GIS Cut Line= 4
      2071713.55     13444288.21      2072113.47     13443864.93
      2072198.11     13443675.05      2072110.01     13442203.30
#Sta/Elev= 30
  4304.1  360.55  4477.1  359.12  4604.5  359.32  4675.3  358.67  4714.8  357.34
  4715.3  356.54  4720.3  356.54  4720.8  357.34  4760.3  359.04  4788.6  359.49
  4795.5  359.09  4802.7  359.64  4809.6  358.97  4816.9  359.39  4837.9  358.71
  4852.1  359.11  4883.9  358.52  4949.1  358.63  4995.5  357.55  5039.6  359.05
  5144.5  358.72  5294.7  359.19  5374.9  358.55  5765.6  359.63  5975.9  358.82
  6016.0  358.01  6064.0  358.73  6296.5  359.25  6406.7  360.08  6568.7  360.12
#Mann=3,-1,0
  4304.1     0.1       0  4714.8    0.07       0  4720.8     0.1       0
Bank Sta=4714.8,4720.8
Exp/Cntr=0.3,0.1

Type RM Length L Ch R = 1,751,169,169,169
BEGIN DESCRIPTION:
Mapping XS d91a2749
END DESCRIPTION:
XS GIS Cut Line= 5
      2071526.08     13444475.69      2072143.25     13444324.65
      2072359.39     13443845.49      2072231.54     13443342.19
      2072162.20     13442208.43
#Sta/Elev= 30
  3960.4  362.10  3984.7  362.18  4010.8  361.56  4197.9  359.91  4234.4  359.20
  4350.5  359.01  4515.2  357.29  4594.1  358.24  4831.2  357.31  4891.6  356.32
  4926.2  354.73  4926.7  353.93  4931.7  353.93  4932.2  354.73  4952.3  356.53
  4957.8  356.30  4975.4  357.16  5004.1  356.29  5044.8  357.27  5276.5  358.14
  5328.3  357.95  5462.4  358.61  5596.6  357.95  5647.9  358.76  5798.2  358.52
  5958.5  359.36  6178.9  358.74  6269.1  357.88  6317.7  358.46  6776.6  359.42
#Mann=3,-1,0
  3960.4     0.1       0  4926.2    0.07       0  4932.2     0.1       0
Bank Sta=4926.2,4932.2
Exp/Cntr=0.3,0.1

Type RM Length L Ch R = 1,582,238,238,238
BEGIN DESCRIPTION:
Mapping XS 4b1d9358
END DESCRIPTION:
XS GIS Cut Line= 5
      2071613.42     13444611.67      2072318.85     13444305.76
      2072448.97     13444168.78      2072446.69     13443735.04
      2072234.67     13442969.02
#Sta/Elev= 30
  3862.0  360.87  3990.5  359.70  4019.4  359.82  4066.3  358.88  4171.1  357.93
  4346.3  357.90  4364.3  358.43  4408.7  358.58  4485.0  357.68  4591.8  358.29
  4734.8  357.81  4853.6  356.95  4893.6  356.06  4963.6  356.07  5000.6  354.92
  5001.1  354.12  5006.1  354.12  5006.6  354.92  5053.6  356.63  5093.6  357.04
  5143.6  356.67  5213.6  357.28  5273.9  356.74  5358.1  357.48  5513.0  357.56
  5596.0  356.72  5653.3  358.08  5879.9  358.23  5919.4  358.74  6048.4  358.99
#Mann=3,-1,0
  3862.0     0.1       0  5000.6    0.07       0  5006.6     0.1       0
Bank Sta=5000.6,5006.6
Exp/Cntr=0.3,0.1

Type RM Length L Ch R = 1,344,263,263,263
BEGIN DESCRIPTION:
Mapping XS a314da71
END DESCRIPTION:
XS GIS Cut Line= 5
      2071661.48     13444897.56      2072338.56     13444335.07
      2072612.00     13444053.82      2072557.31     13443522.57
      2072278.68     13442957.49
#Sta/Elev= 30
  3497.0  359.87  3685.5  359.38  3785.8  358.64  3884.8  358.67  3913.4  359.10
  4090.5  358.96  4360.0  358.42  4608.2  357.21  4791.2  357.50  4919.1  356.25
  4969.4  355.12  4996.5  353.91  4997.0  353.11  5002.0  353.11  5002.5  353.91
  5019.6  354.88  5039.7  355.29  5083.5  355.36  5120.2  354.38  5190.5  356.58
  5281.7  356.49  5356.6  355.16  5369.3  355.78  5436.7  356.77  5504.1  356.99
  5535.0  357.53  5655.7  357.37  5773.5  358.30  5885.8  358.31  5933.6  358.83
#Mann=3,-1,0
  3497.0     0.1       0  4996.5    0.07       0  5002.5     0.1       0
Bank Sta=4996.5,5002.5
Exp/Cntr=0.3,0.1

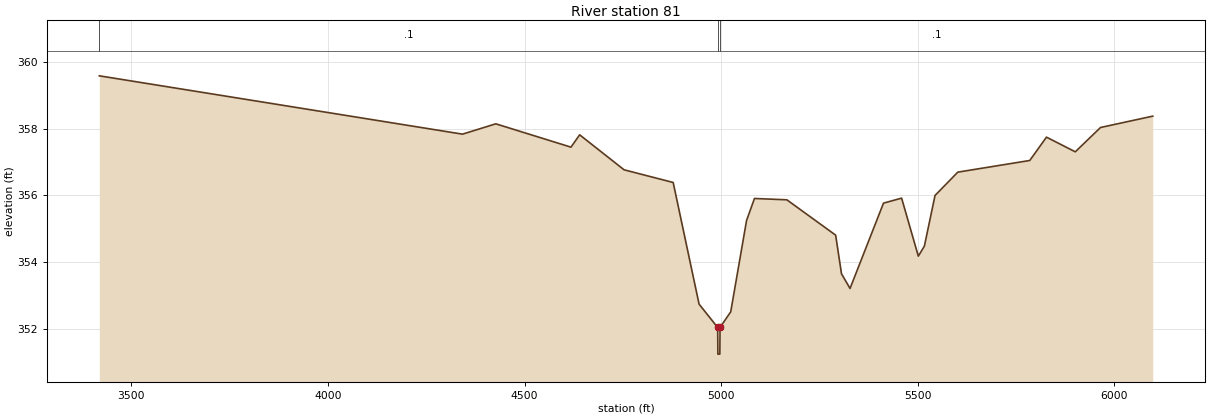
Type RM Length L Ch R = 1,81,0,0,0
BEGIN DESCRIPTION:
UNT 64 in Lagunillas Cr Wtrshd 1.0
END DESCRIPTION:
XS GIS Cut Line= 4
      2071921.92     13444973.05      2072817.72     13443907.99
      2072776.87     13443553.18      2072286.45     13442762.12
#Sta/Elev= 30
  3418.4  359.59  4342.3  357.84  4426.9  358.15  4618.1  357.45  4640.2  357.82
  4753.3  356.77  4878.1  356.39  4944.0  352.74  4991.3  352.04  4991.8  351.24
  4996.8  351.24  4997.3  352.04  5024.5  352.51  5064.8  355.25  5084.9  355.91
  5167.3  355.87  5291.4  354.81  5306.3  353.65  5328.0  353.21  5413.1  355.77
  5459.2  355.92  5501.7  354.18  5517.1  354.48  5544.2  356.00  5602.1  356.70
  5785.2  357.05  5827.7  357.75  5901.0  357.31  5965.2  358.04  6098.0  358.38
#Mann=3,-1,0
  3418.4     0.1       0  4991.3    0.07       0  4997.3     0.1       0
Bank Sta=4991.3,4997.3
Exp/Cntr=0.3,0.1

Chan Stop Cuts=-1