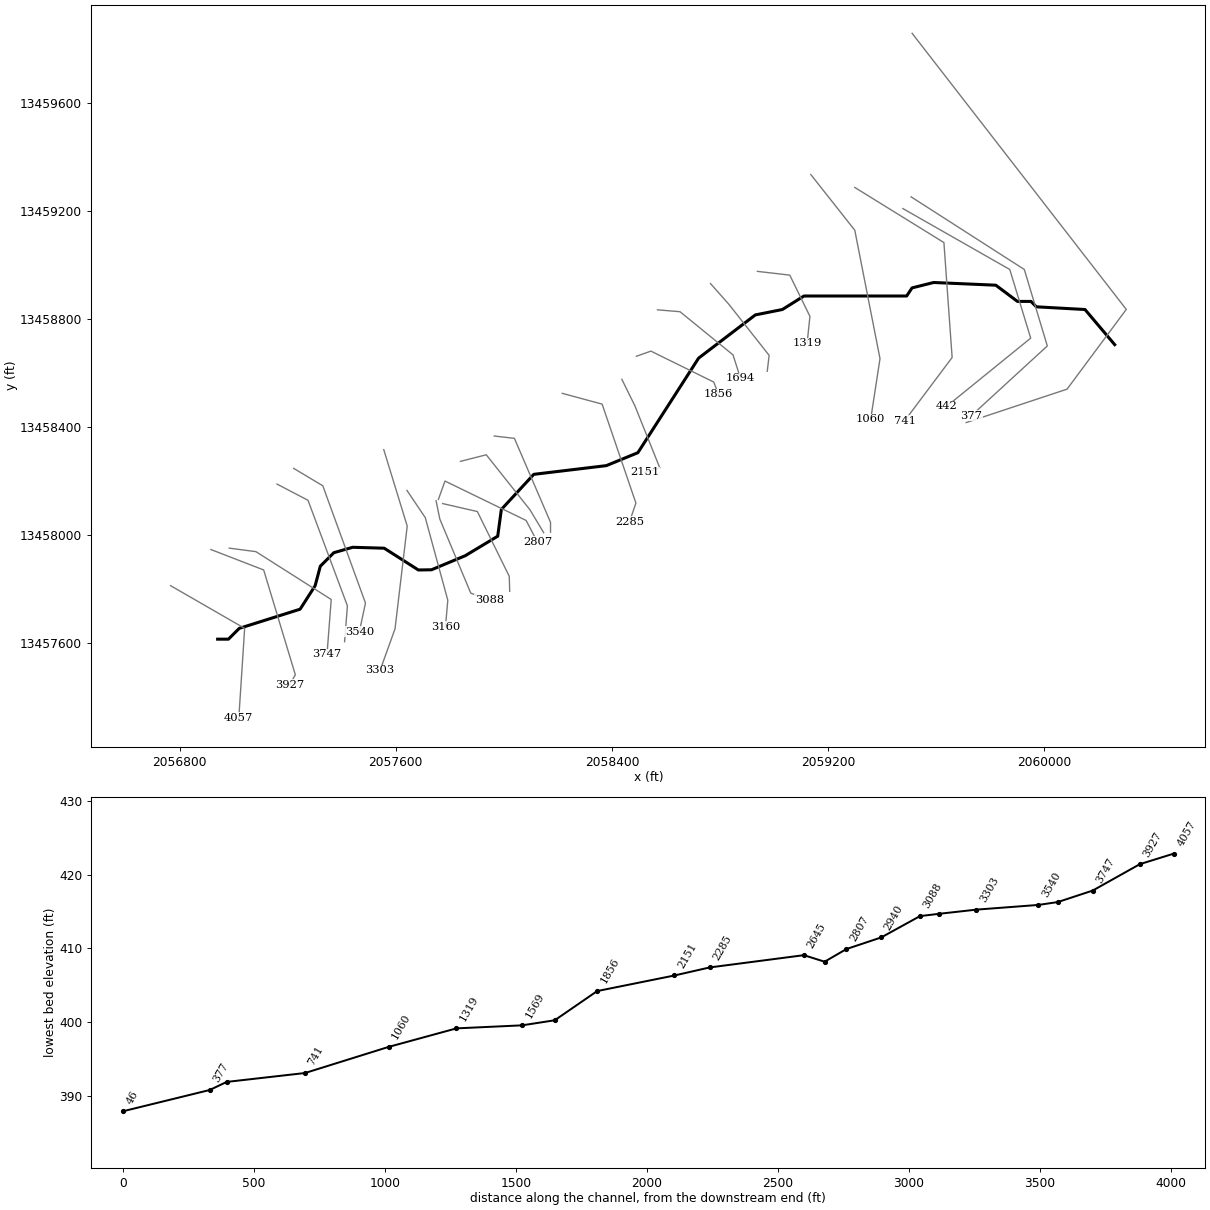
--- UNT 65 in Lagunillas Cr Wtrshd.prj (project) ---

Proj Title=UNT 65 in Lagunillas Cr Wtrshd Base Level Engineering
Current Plan=p01
Default Exp/Contr=0.3,0.1
English Units
Geom File=g01
Flow File=f01
Plan File=p01
BEGIN DESCRIPTION:
UNT 65 in Lagunillas Cr Wtrshd
END DESCRIPTION:

--- UNT 65 in Lagunillas Cr Wtrshd.p01 (plan) ---

Plan Title=Multiple Run
Short Identifier=Multiple
Geom File=g01
Flow File=f01
Subcritical Flow
K Sum by GR= 0
Std Step Tol= 0.01
Critical Tol= 0.01
Num of Std Step Trials= 20
Max Error Tol= 0.3
Flow Tol Ratio= 0.001
Split Flow NTrial= 30
Split Flow Tol= 0.02
Split Flow Ratio= 0.02
Log Output Level= 0
Friction Slope Method= 1
Unsteady Friction Slope Method= 2
Unsteady Bridges Friction Slope Method= 1
Parabolic Critical Depth
Global Vel Dist=  1 , 1 , 1
Global Log Level= 0
CheckData=True
Encroach Param= -1, 0, 0, 0
BEGIN DESCRIPTION:
Multiple Run
END DESCRIPTION:

--- UNT 65 in Lagunillas Cr Wtrshd.f01 (steady flow) ---

Flow Title=Multiple
Number of Profiles=7
Profile Names=10-year,25-year,50-year,1pct_min,100-year,1pct_plu,500-year
River Rch & RM= UNT 65 in Laguni,Reach-1,4057
      97     128     153      92     183     365     263
Boundary for River Rch & Prof#=UNT 65 in Laguni,Reach-1,1
Up Type=0
Dn Type=3
Dn Slope=0.005
Boundary for River Rch & Prof#=UNT 65 in Laguni,Reach-1,2
Up Type=0
Dn Type=3
Dn Slope=0.005
Boundary for River Rch & Prof#=UNT 65 in Laguni,Reach-1,3
Up Type=0
Dn Type=3
Dn Slope=0.005
Boundary for River Rch & Prof#=UNT 65 in Laguni,Reach-1,4
Up Type=0
Dn Type=3
Dn Slope=0.005
Boundary for River Rch & Prof#=UNT 65 in Laguni,Reach-1,5
Up Type=0
Dn Type=3
Dn Slope=0.005
Boundary for River Rch & Prof#=UNT 65 in Laguni,Reach-1,6
Up Type=0
Dn Type=3
Dn Slope=0.005
Boundary for River Rch & Prof#=UNT 65 in Laguni,Reach-1,7
Up Type=0
Dn Type=3
Dn Slope=0.005

--- UNT 65 in Lagunillas Cr Wtrshd.g01 (geometry) ---

Geom Title=Existing Conditions

River Reach=UNT 65 in Laguni,Reach-1
Reach XY= 30
      2056940.80     13457614.54      2056980.80     13457614.54
      2057020.80     13457654.54      2057246.09     13457725.47
      2057301.65     13457812.28      2057320.80     13457884.54
      2057370.80     13457934.54      2057440.80     13457954.54
      2057557.20     13457951.17      2057683.59     13457870.61
      2057732.20     13457871.30      2057857.20     13457923.39
      2057977.34     13457995.61      2057990.80     13458094.54
      2058110.80     13458224.54      2058379.19     13458256.73
      2058496.09     13458304.64      2058720.80     13458654.54
      2058930.80     13458814.54      2059030.80     13458834.54
      2059110.80     13458884.54      2059490.80     13458884.54
      2059510.80     13458914.54      2059590.80     13458934.54
      2059820.80     13458924.54      2059900.80     13458864.54
      2059950.80     13458864.54      2059970.80     13458844.54
      2060150.80     13458834.54      2060260.80     13458704.54

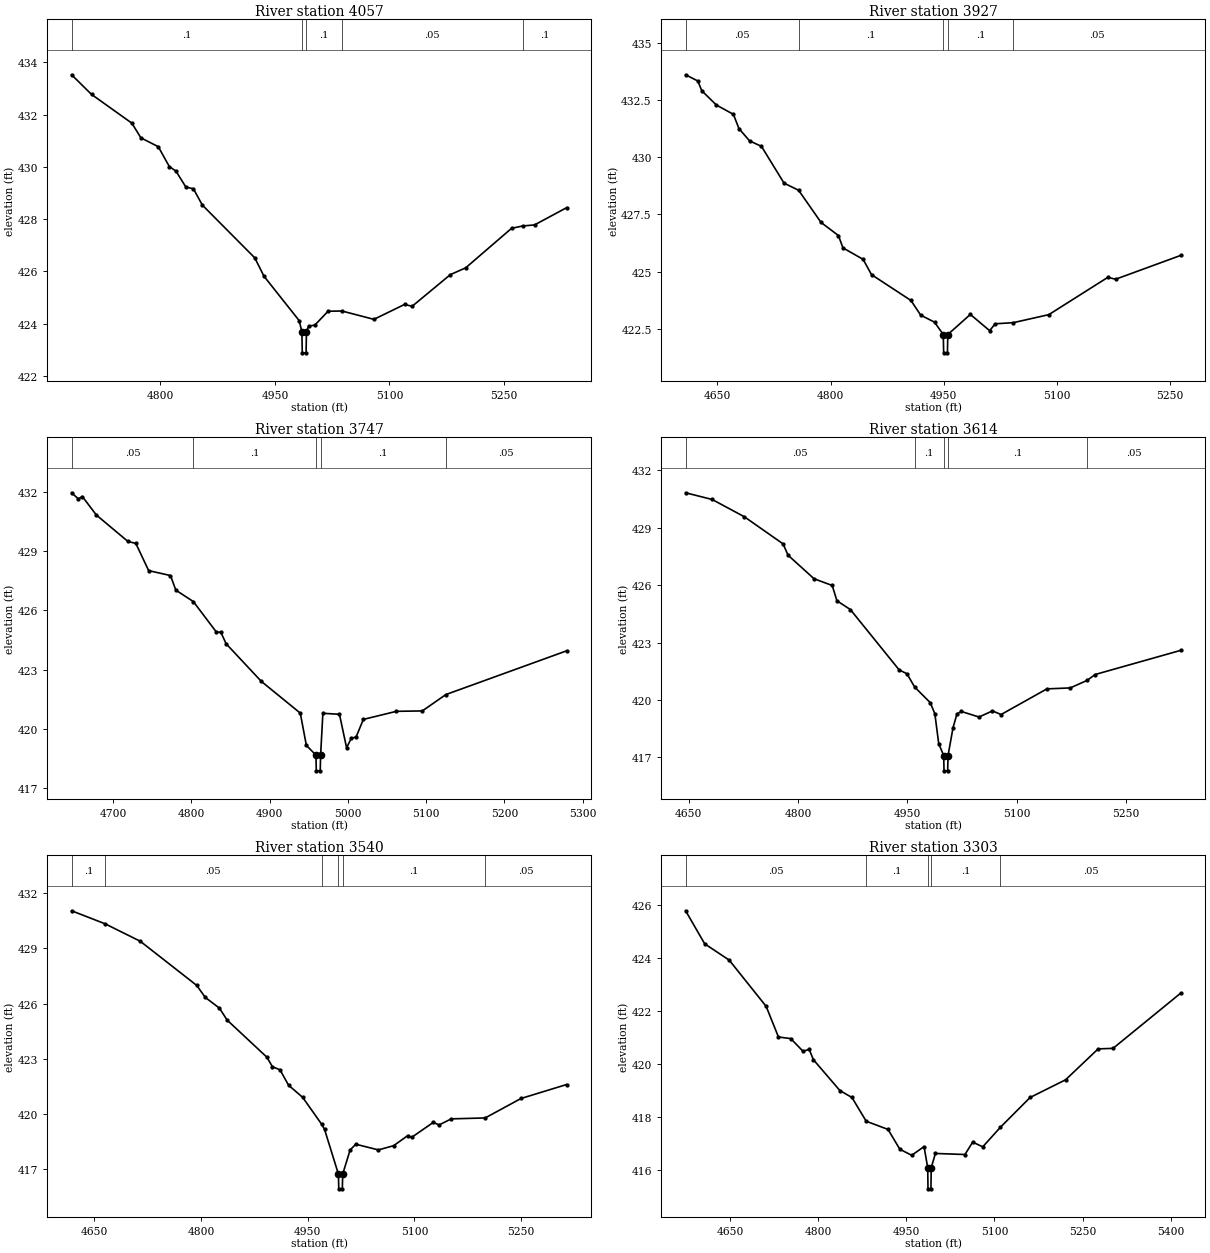
Type RM Length L Ch R = 1,4057,130,130,130
BEGIN DESCRIPTION:
UNT 65 in Lagunillas Cr Wtrshd 4.0
END DESCRIPTION:
XS GIS Cut Line= 3
      2056766.55     13457812.53      2057040.80     13457654.54
      2057019.16     13457322.94
#Sta/Elev= 30
  4683.5  433.52  4709.6  432.77  4762.5  431.67  4774.3  431.11  4797.1  430.77
  4811.6  430.01  4820.2  429.84  4833.2  429.23  4843.2  429.16  4854.8  428.54
  4923.6  426.52  4935.6  425.82  4981.8  424.12  4985.3  423.69  4985.8  422.89
  4990.8  422.89  4991.3  423.69  4994.1  423.91  5002.3  423.95  5019.6  424.48
  5037.7  424.49  5079.7  424.17  5119.8  424.74  5129.8  424.67  5179.9  425.88
  5200.0  426.14  5260.1  427.65  5274.7  427.74  5290.2  427.78  5332.3  428.44
#Mann=5,-1,0
  4683.5     0.1       0  4985.3    0.07       0  4991.3     0.1       0
  5037.7    0.05       0  5274.7     0.1       0
Bank Sta=4985.3,4991.3
Exp/Cntr=0.3,0.1

Type RM Length L Ch R = 1,3927,180,180,180
BEGIN DESCRIPTION:
Mapping XS 95e8825a
END DESCRIPTION:
XS GIS Cut Line= 4
      2056915.90     13457946.19      2057111.18     13457870.68
      2057228.37     13457482.66      2057207.53     13457446.20
#Sta/Elev= 30
  4607.8  433.61  4623.9  433.34  4629.3  432.91  4648.5  432.29  4671.2  431.88
  4678.5  431.26  4692.6  430.72  4708.4  430.48  4738.4  428.87  4757.7  428.56
  4787.5  427.15  4810.5  426.58  4816.5  426.04  4843.2  425.54  4854.4  424.87
  4906.7  423.74  4919.6  423.10  4938.0  422.79  4949.6  422.25  4950.1  421.45
  4955.1  421.45  4955.6  422.25  4985.5  423.13  5011.1  422.42  5018.5  422.72
  5042.5  422.77  5089.6  423.12  5167.8  424.75  5178.3  424.67  5264.5  425.71
#Mann=5,-1,0
  4607.8    0.05       0  4757.7     0.1       0  4949.6    0.07       0
  4955.6     0.1       0  5042.5    0.05       0
Bank Sta=4949.6,4955.6
Exp/Cntr=0.3,0.1

Type RM Length L Ch R = 1,3747,133,133,133
BEGIN DESCRIPTION:
Mapping XS 7547727f
END DESCRIPTION:
XS GIS Cut Line= 4
      2056983.59     13457951.41      2057082.53     13457938.39
      2057361.18     13457761.31      2057345.62     13457559.06
#Sta/Elev= 30
  4646.8  431.97  4655.4  431.66  4660.5  431.78  4678.5  430.84  4718.8  429.50
  4728.9  429.40  4745.3  428.02  4773.2  427.77  4780.0  427.03  4802.4  426.45
  4831.7  424.91  4837.6  424.89  4844.3  424.31  4889.3  422.40  4939.1  420.79
  4946.9  419.15  4959.1  418.66  4959.6  417.86  4964.6  417.86  4965.1  418.66
  4968.0  420.78  4989.2  420.73  4998.3  419.03  5004.4  419.52  5010.4  419.57
  5019.7  420.47  5062.0  420.88  5095.1  420.90  5125.2  421.73  5279.6  423.95
#Mann=5,-1,0
  4646.8    0.05       0  4802.4     0.1       0  4959.1    0.07       0
  4965.1     0.1       0  5125.2    0.05       0
Bank Sta=4959.1,4965.1
Exp/Cntr=0.3,0.1

Type RM Length L Ch R = 1,3614,74,74,74
BEGIN DESCRIPTION:
Mapping XS b72a7e10
END DESCRIPTION:
XS GIS Cut Line= 4
      2057160.67     13458188.38      2057275.24     13458128.49
      2057421.07     13457737.87      2057410.65     13457605.01
#Sta/Elev= 30
  4645.7  430.82  4682.1  430.47  4726.2  429.57  4779.5  428.15  4786.3  427.56
  4822.0  426.33  4846.9  425.98  4853.4  425.18  4871.9  424.72  4938.8  421.57
  4949.5  421.37  4960.0  420.68  4981.5  419.86  4987.8  419.28  4993.1  417.72
  4999.9  417.10  5000.4  416.30  5005.4  416.30  5005.9  417.10  5012.8  418.56
  5018.1  419.27  5024.2  419.40  5048.4  419.11  5066.9  419.43  5078.7  419.24
  5141.6  420.58  5173.7  420.63  5196.6  421.02  5207.8  421.33  5325.2  422.59
#Mann=5,-1,0
  4645.7    0.05       0  4960.0     0.1       0  4999.9    0.07       0
  5005.9     0.1       0  5196.6    0.05       0
Bank Sta=4999.9,5005.9
Exp/Cntr=0.3,0.1

Type RM Length L Ch R = 1,3540,237,237,237
BEGIN DESCRIPTION:
Mapping XS ebe37598
END DESCRIPTION:
XS GIS Cut Line= 4
      2057222.25     13458246.57      2057329.93     13458182.31
      2057487.91     13457748.29      2057465.34     13457642.34
#Sta/Elev= 30
  4618.2  431.05  4665.3  430.34  4714.7  429.39  4793.9  426.99  4806.1  426.33
  4825.9  425.75  4836.7  425.10  4892.5  423.08  4900.4  422.56  4911.0  422.39
  4923.1  421.55  4942.9  420.89  4969.5  419.43  4973.6  419.15  4993.1  416.71
  4993.6  415.91  4998.6  415.91  4999.1  416.71  5009.5  418.02  5017.4  418.34
  5049.3  418.03  5070.7  418.26  5090.6  418.81  5095.9  418.71  5126.5  419.53
  5134.5  419.39  5151.8  419.72  5199.3  419.77  5249.7  420.83  5313.8  421.59
#Mann=6,-1,0
  4618.2     0.1       0  4665.3    0.05       0  4969.5     0.1       0
  4993.1    0.07       0  4999.1     0.1       0  5199.3    0.05       0
Bank Sta=4993.1,4999.1
Exp/Cntr=0.3,0.1

Type RM Length L Ch R = 1,3303,143,143,143
BEGIN DESCRIPTION:
Mapping XS b5653cf3
END DESCRIPTION:
XS GIS Cut Line= 4
      2057555.64     13458315.95      2057642.43     13458033.01
      2057597.29     13457652.80      2057542.05     13457499.16
#Sta/Elev= 30
  4574.6  425.80  4607.0  424.55  4648.8  423.93  4711.6  422.18  4732.5  421.02
  4753.4  420.96  4774.3  420.48  4784.8  420.55  4792.0  420.16  4837.1  418.99
  4857.5  418.73  4881.8  417.83  4918.9  417.52  4939.0  416.77  4959.2  416.54
  4980.2  416.87  4986.4  416.07  4986.9  415.27  4991.9  415.27  4992.4  416.07
  4999.5  416.61  5049.8  416.57  5062.9  417.04  5080.0  416.86  5110.0  417.60
  5160.6  418.73  5221.0  419.40  5276.3  420.57  5301.7  420.59  5416.7  422.68
#Mann=5,-1,0
  4574.6    0.05       0  4881.8     0.1       0  4986.4    0.07       0
  4992.4     0.1       0  5110.0    0.05       0
Bank Sta=4986.4,4992.4
Exp/Cntr=0.3,0.1

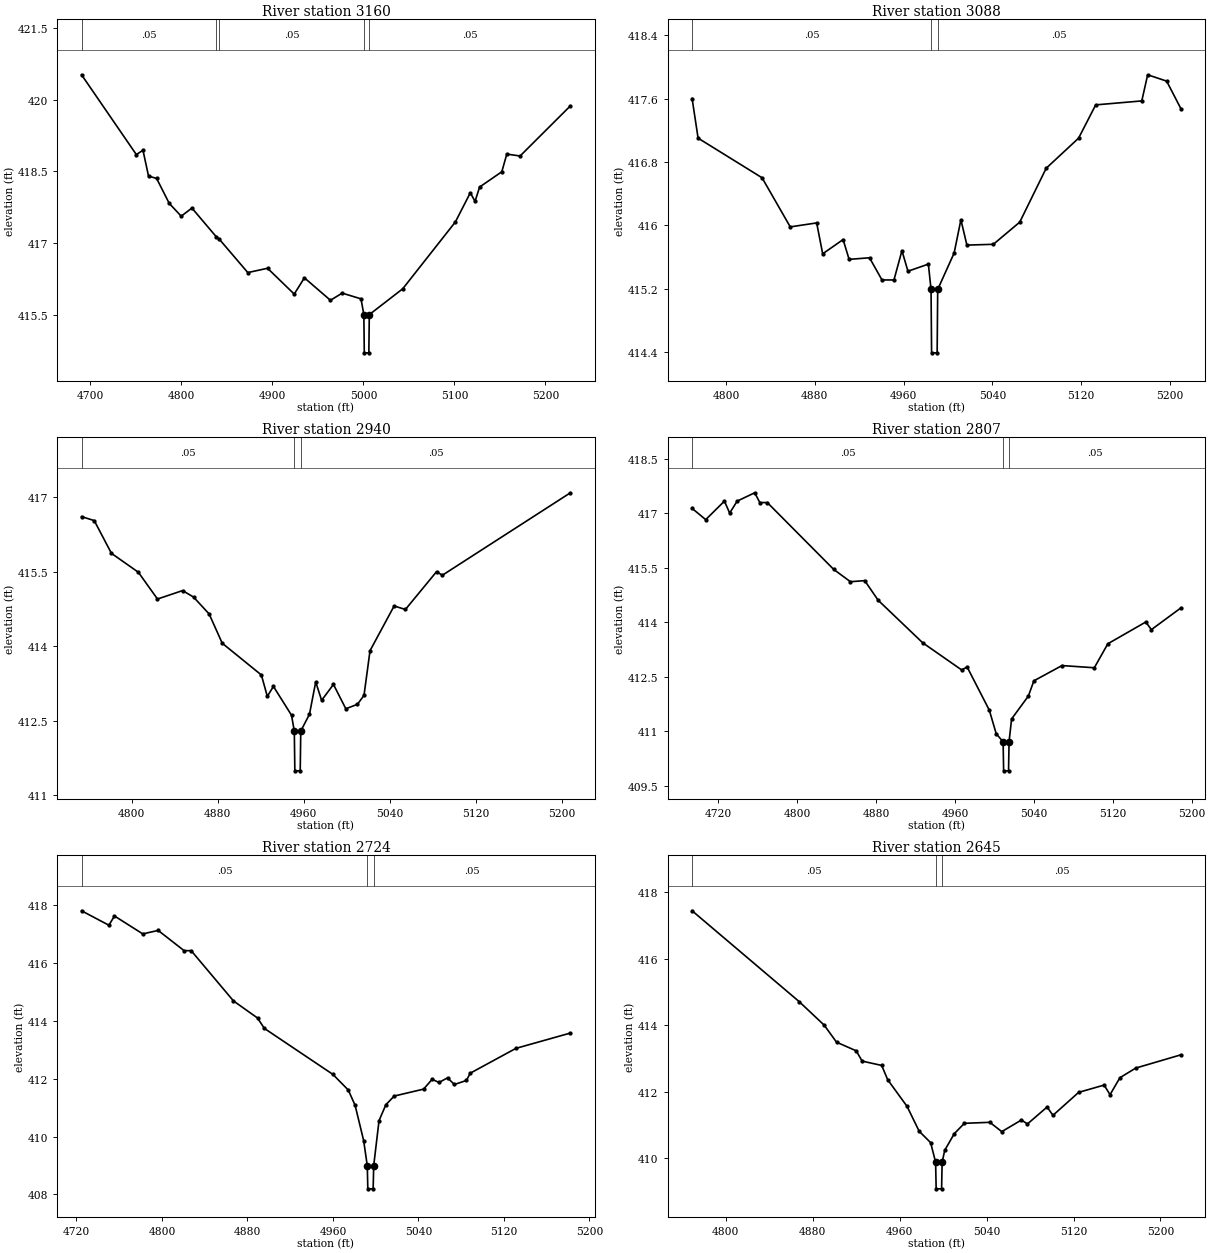
Type RM Length L Ch R = 1,3160,72,72,72
BEGIN DESCRIPTION:
Mapping XS 99345931
END DESCRIPTION:
XS GIS Cut Line= 4
      2057641.58     13458164.93      2057709.27     13458064.26
      2057792.60     13457758.70      2057783.94     13457659.91
#Sta/Elev= 30
  4690.2  420.52  4750.4  418.85  4757.7  418.94  4763.8  418.40  4772.7  418.35
  4786.5  417.83  4799.7  417.56  4811.5  417.73  4838.2  417.13  4841.5  417.08
  4872.9  416.38  4894.6  416.47  4923.9  415.93  4935.1  416.27  4963.7  415.80
  4976.6  415.95  4997.3  415.83  5000.4  415.50  5000.9  414.70  5005.9  414.70
  5006.4  415.50  5043.1  416.04  5101.0  417.44  5117.4  418.05  5122.6  417.87
  5127.6  418.17  5152.0  418.49  5157.5  418.86  5172.1  418.82  5227.4  419.87
#Mann=5,-1,0
  4690.2    0.05       0  4838.2     0.1       0  4841.5    0.05       0
  5000.4    0.03       0  5006.4    0.05       0
Bank Sta=5000.4,5006.4
Exp/Cntr=0.3,0.1

Type RM Length L Ch R = 1,3088,148,148,148
BEGIN DESCRIPTION:
Mapping XS 4c87eb3e
END DESCRIPTION:
XS GIS Cut Line= 4
      2057749.21     13458126.72      2057763.09     13458059.05
      2057877.67     13457784.74      2057947.12     13457759.34
#Sta/Elev= 30
  4769.5  417.60  4774.9  417.10  4832.5  416.60  4857.9  415.98  4881.7  416.03
  4887.1  415.64  4905.5  415.82  4910.9  415.57  4929.3  415.59  4940.5  415.31
  4951.3  415.31  4958.5  415.68  4963.9  415.42  4982.3  415.51  4984.7  415.19
  4985.2  414.39  4990.2  414.39  4990.7  415.19  5005.5  415.65  5011.6  416.07
  5017.0  415.75  5040.8  415.76  5064.6  416.04  5088.4  416.72  5117.6  417.10
  5133.0  417.52  5174.5  417.57  5179.8  417.90  5196.9  417.82  5209.8  417.47
#Mann=3,-1,0
  4769.5    0.05       0  4984.7    0.03       0  4990.7    0.05       0
Bank Sta=4984.7,4990.7
Exp/Cntr=0.3,0.1

Type RM Length L Ch R = 1,2940,133,133,133
BEGIN DESCRIPTION:
Mapping XS eb2d1cf6
END DESCRIPTION:
XS GIS Cut Line= 4
      2057773.50     13458116.34      2057901.98     13458086.83
      2058020.03     13457847.24      2058021.77     13457791.68
#Sta/Elev= 30
  4753.4  416.61  4765.2  416.53  4781.2  415.87  4806.2  415.49  4824.0  414.95
  4847.3  415.12  4857.5  414.99  4872.0  414.65  4884.2  414.06  4920.6  413.42
  4926.1  412.99  4931.8  413.19  4948.6  412.61  4951.2  412.29  4951.7  411.49
  4956.7  411.49  4957.2  412.29  4965.3  412.63  4971.1  413.28  4976.6  412.91
  4987.6  413.23  4999.1  412.74  5009.9  412.83  5016.0  413.01  5021.6  413.91
  5044.0  414.81  5054.5  414.74  5083.4  415.50  5088.9  415.43  5207.9  417.09
#Mann=3,-1,0
  4753.4    0.05       0  4951.2    0.03       0  4957.2    0.05       0
Bank Sta=4951.2,4957.2
Exp/Cntr=0.3,0.1

Type RM Length L Ch R = 1,2807,83,83,83
BEGIN DESCRIPTION:
Mapping XS 91b4aaab
END DESCRIPTION:
XS GIS Cut Line= 4
      2057757.89     13458131.99      2057782.18     13458199.67
      2058082.53     13458053.84      2058124.21     13457973.96
#Sta/Elev= 30
  4693.3  417.14  4707.1  416.83  4726.1  417.34  4731.4  417.01  4739.0  417.34
  4756.8  417.57  4762.0  417.30  4769.6  417.30  4836.9  415.46  4853.9  415.12
  4868.4  415.15  4882.0  414.61  4927.1  413.44  4966.7  412.69  4972.3  412.77
  4994.8  411.58  5001.8  410.93  5008.8  410.71  5009.3  409.91  5014.3  409.91
  5014.8  410.71  5017.4  411.34  5034.4  411.97  5040.0  412.39  5068.5  412.81
  5101.3  412.75  5115.0  413.41  5153.5  414.01  5159.2  413.80  5189.2  414.40
#Mann=3,-1,0
  4693.3    0.05       0  5008.8    0.03       0  5014.8    0.05       0
Bank Sta=5008.8,5014.8
Exp/Cntr=0.3,0.1

Type RM Length L Ch R = 1,2724,79,79,79
BEGIN DESCRIPTION:
Mapping XS 93296e7a
END DESCRIPTION:
XS GIS Cut Line= 4
      2057839.45     13458272.58      2057934.96     13458296.90
      2058096.42     13458093.77      2058147.60     13458008.48
#Sta/Elev= 30
  4724.8  417.81  4750.4  417.31  4755.6  417.63  4782.1  417.01  4796.5  417.13
  4820.8  416.43  4827.4  416.43  4867.0  414.69  4889.5  414.10  4895.9  413.74
  4960.0  412.15  4974.4  411.61  4980.8  411.08  4988.8  409.86  4992.2  408.99
  4992.7  408.19  4997.7  408.19  4998.2  408.99  5003.2  410.55  5009.6  411.10
  5017.4  411.40  5044.9  411.64  5052.9  411.98  5059.3  411.87  5067.3  412.03
  5073.7  411.80  5085.0  411.94  5088.5  412.19  5131.3  413.05  5182.3  413.58
#Mann=3,-1,0
  4724.8    0.05       0  4992.2    0.03       0  4998.2    0.05       0
Bank Sta=4992.2,4998.2
Exp/Cntr=0.3,0.1

Type RM Length L Ch R = 1,2645,360,360,360
BEGIN DESCRIPTION:
Mapping XS 5398be52
END DESCRIPTION:
XS GIS Cut Line= 4
      2057964.51     13458366.34      2058039.13     13458357.66
      2058172.81     13458046.90      2058172.81     13458010.41
#Sta/Elev= 30
  4769.0  417.44  4867.5  414.71  4890.6  414.00  4901.9  413.49  4920.0  413.23
  4925.5  412.92  4943.5  412.79  4949.0  412.36  4966.8  411.56  4978.0  410.81
  4988.5  410.47  4993.1  409.88  4993.6  409.08  4998.6  409.08  4999.1  409.88
  5001.5  410.24  5010.3  410.74  5019.6  411.05  5043.0  411.08  5054.0  410.80
  5072.1  411.15  5077.6  411.03  5095.7  411.54  5101.1  411.29  5124.7  411.98
  5148.2  412.20  5153.6  411.91  5162.7  412.42  5177.2  412.71  5218.9  413.11
#Mann=3,-1,0
  4769.0    0.05       0  4993.1    0.03       0  4999.1    0.05       0
Bank Sta=4993.1,4999.1
Exp/Cntr=0.3,0.1

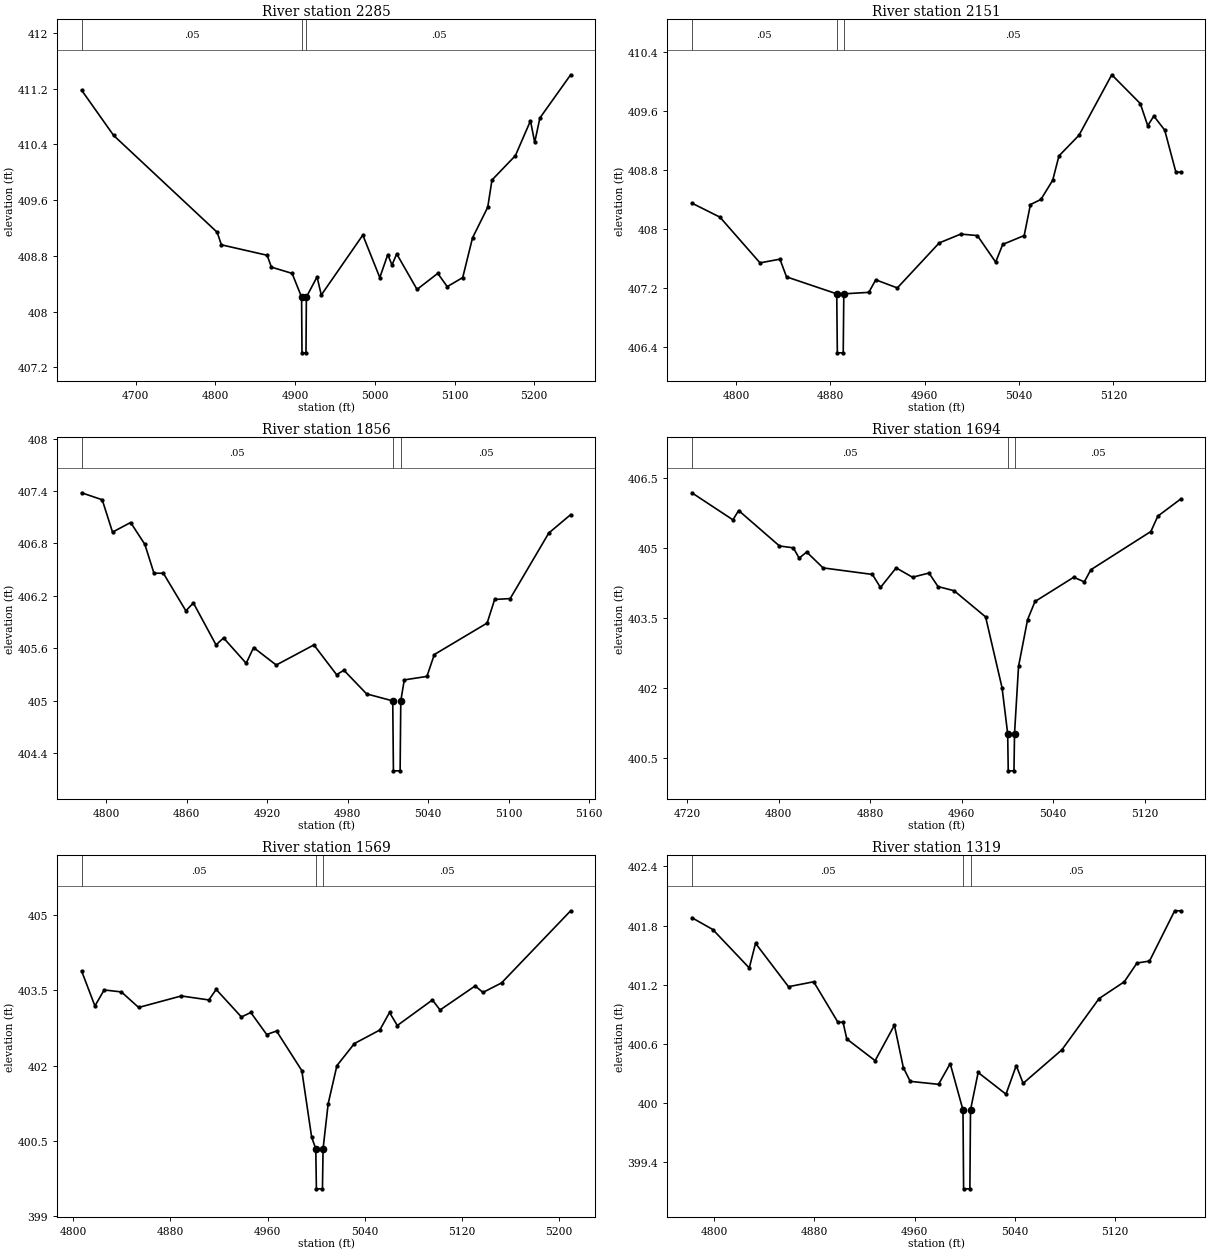
Type RM Length L Ch R = 1,2285,134,134,134
BEGIN DESCRIPTION:
Mapping XS 672b9d1d
END DESCRIPTION:
XS GIS Cut Line= 4
      2058216.22     13458524.33      2058363.78     13458484.40
      2058488.78     13458118.08      2058465.01     13458048.46
#Sta/Elev= 30
  4632.1  411.18  4672.3  410.53  4802.2  409.14  4807.5  408.96  4864.9  408.81
  4870.2  408.64  4896.2  408.55  4908.1  408.21  4908.6  407.41  4913.6  407.41
  4914.1  408.21  4927.5  408.50  4932.8  408.24  4984.9  409.10  5006.2  408.49
  5016.2  408.82  5021.5  408.67  5027.4  408.83  5052.9  408.32  5078.9  408.55
  5090.8  408.36  5110.2  408.49  5122.5  409.06  5141.6  409.50  5146.9  409.89
  5176.3  410.24  5195.2  410.74  5200.5  410.43  5207.0  410.78  5245.6  411.40
#Mann=3,-1,0
  4632.1    0.05       0  4908.1    0.03       0  4914.1    0.05       0
Bank Sta=4908.1,4914.1
Exp/Cntr=0.3,0.1

Type RM Length L Ch R = 1,2151,295,295,295
BEGIN DESCRIPTION:
Mapping XS 6123dc91
END DESCRIPTION:
XS GIS Cut Line= 4
      2058436.71     13458576.38      2058485.31     13458477.45
      2058577.32     13458248.29      2058521.75     13458232.65
#Sta/Elev= 30
  4762.4  408.35  4786.2  408.16  4820.2  407.54  4837.1  407.59  4842.7  407.35
  4885.3  407.12  4885.8  406.32  4890.8  406.32  4891.3  407.12  4912.5  407.14
  4918.4  407.31  4936.7  407.20  4972.2  407.81  4990.5  407.93  5004.6  407.91
  5020.1  407.55  5026.1  407.79  5044.3  407.91  5049.6  408.33  5058.5  408.40
  5068.5  408.66  5073.8  408.99  5090.8  409.27  5118.6  410.09  5142.8  409.70
  5149.1  409.40  5154.3  409.53  5163.5  409.34  5173.0  408.77  5177.3  408.77
#Mann=3,-1,0
  4762.4    0.05       0  4885.3    0.03       0  4891.3    0.05       0
Bank Sta=4885.3,4891.3
Exp/Cntr=0.3,0.1

Type RM Length L Ch R = 1,1856,162,162,162
BEGIN DESCRIPTION:
Mapping XS e1bbff9d
END DESCRIPTION:
XS GIS Cut Line= 4
      2058490.48     13458661.47      2058544.34     13458680.58
      2058776.98     13458565.99      2058794.32     13458520.89
#Sta/Elev= 30
  4781.5  407.38  4796.9  407.30  4804.6  406.93  4818.1  407.04  4828.7  406.79
  4835.5  406.46  4842.5  406.46  4859.3  406.03  4864.9  406.12  4881.8  405.64
  4887.4  405.72  4904.3  405.43  4909.8  405.61  4926.7  405.41  4954.8  405.64
  4971.7  405.30  4977.2  405.35  4994.1  405.08  5013.6  405.00  5014.1  404.20
  5019.1  404.20  5019.6  405.00  5022.2  405.24  5039.1  405.28  5044.6  405.53
  5084.0  405.89  5089.6  406.16  5101.2  406.17  5130.0  406.92  5146.3  407.13
#Mann=3,-1,0
  4781.5    0.05       0  5013.6    0.03       0  5019.6    0.05       0
Bank Sta=5013.6,5019.6
Exp/Cntr=0.3,0.1

Type RM Length L Ch R = 1,1694,125,125,125
BEGIN DESCRIPTION:
Mapping XS 0925ad94
END DESCRIPTION:
XS GIS Cut Line= 4
      2058568.68     13458833.35      2058651.98     13458826.41
      2058848.16     13458666.69      2058875.90     13458579.99
#Sta/Elev= 30
  4724.0  406.19  4759.9  405.61  4764.9  405.81  4800.6  405.05  4812.7  405.01
  4817.8  404.79  4824.4  404.92  4838.7  404.58  4881.8  404.44  4888.9  404.16
  4902.6  404.58  4916.9  404.38  4931.3  404.47  4939.2  404.18  4953.3  404.09
  4980.8  403.53  4995.2  402.01  5000.1  401.03  5000.6  400.23  5005.6  400.23
  5006.1  401.03  5009.6  402.47  5017.5  403.47  5024.0  403.86  5057.9  404.38
  5067.1  404.28  5072.8  404.54  5125.3  405.36  5131.4  405.69  5151.6  406.06
#Mann=3,-1,0
  4724.0    0.05       0  5000.1    0.03       0  5006.1    0.05       0
Bank Sta=5000.1,5006.1
Exp/Cntr=0.3,0.1

Type RM Length L Ch R = 1,1569,250,250,250
BEGIN DESCRIPTION:
Mapping XS ef4f0e52
END DESCRIPTION:
XS GIS Cut Line= 4
      2058764.79     13458930.61      2058832.53     13458854.19
      2058981.84     13458664.95      2058974.89     13458605.93
#Sta/Elev= 30
  4806.8  403.89  4817.8  403.19  4825.4  403.51  4839.6  403.47  4853.8  403.16
  4888.9  403.39  4911.6  403.31  4917.6  403.52  4938.4  402.97  4946.1  403.06
  4959.2  402.62  4967.3  402.69  4988.1  401.90  4996.2  400.57  4999.6  400.34
  5000.1  399.54  5005.1  399.54  5005.6  400.34  5009.8  401.24  5017.0  402.00
  5031.4  402.44  5052.3  402.71  5060.3  403.06  5066.7  402.80  5095.6  403.31
  5101.9  403.11  5130.8  403.59  5137.2  403.46  5152.5  403.65  5209.4  405.09
#Mann=3,-1,0
  4806.8    0.05       0  4999.6    0.03       0  5005.6    0.05       0
Bank Sta=4999.6,5005.6
Exp/Cntr=0.3,0.1

Type RM Length L Ch R = 1,1319,259,259,259
BEGIN DESCRIPTION:
Mapping XS 8be8bfb4
END DESCRIPTION:
XS GIS Cut Line= 4
      2058938.42     13458975.72      2059058.23     13458961.83
      2059132.88     13458809.05      2059122.46     13458710.05
#Sta/Elev= 30
  4782.3  401.88  4799.0  401.76  4828.1  401.37  4833.1  401.62  4859.4  401.18
  4879.5  401.23  4898.8  400.82  4902.9  400.82  4905.9  400.65  4928.5  400.43
  4943.9  400.79  4951.0  400.36  4956.5  400.22  4979.1  400.19  4988.4  400.40
  4998.6  399.93  4999.1  399.13  5004.1  399.13  5004.6  399.93  5010.7  400.31
  5032.9  400.09  5041.1  400.38  5046.6  400.20  5077.5  400.54  5107.2  401.06
  5127.3  401.23  5137.4  401.42  5147.4  401.44  5167.5  401.95  5172.5  401.95
#Mann=3,-1,0
  4782.3    0.05       0  4998.6    0.03       0  5004.6    0.05       0
Bank Sta=4998.6,5004.6
Exp/Cntr=0.3,0.1

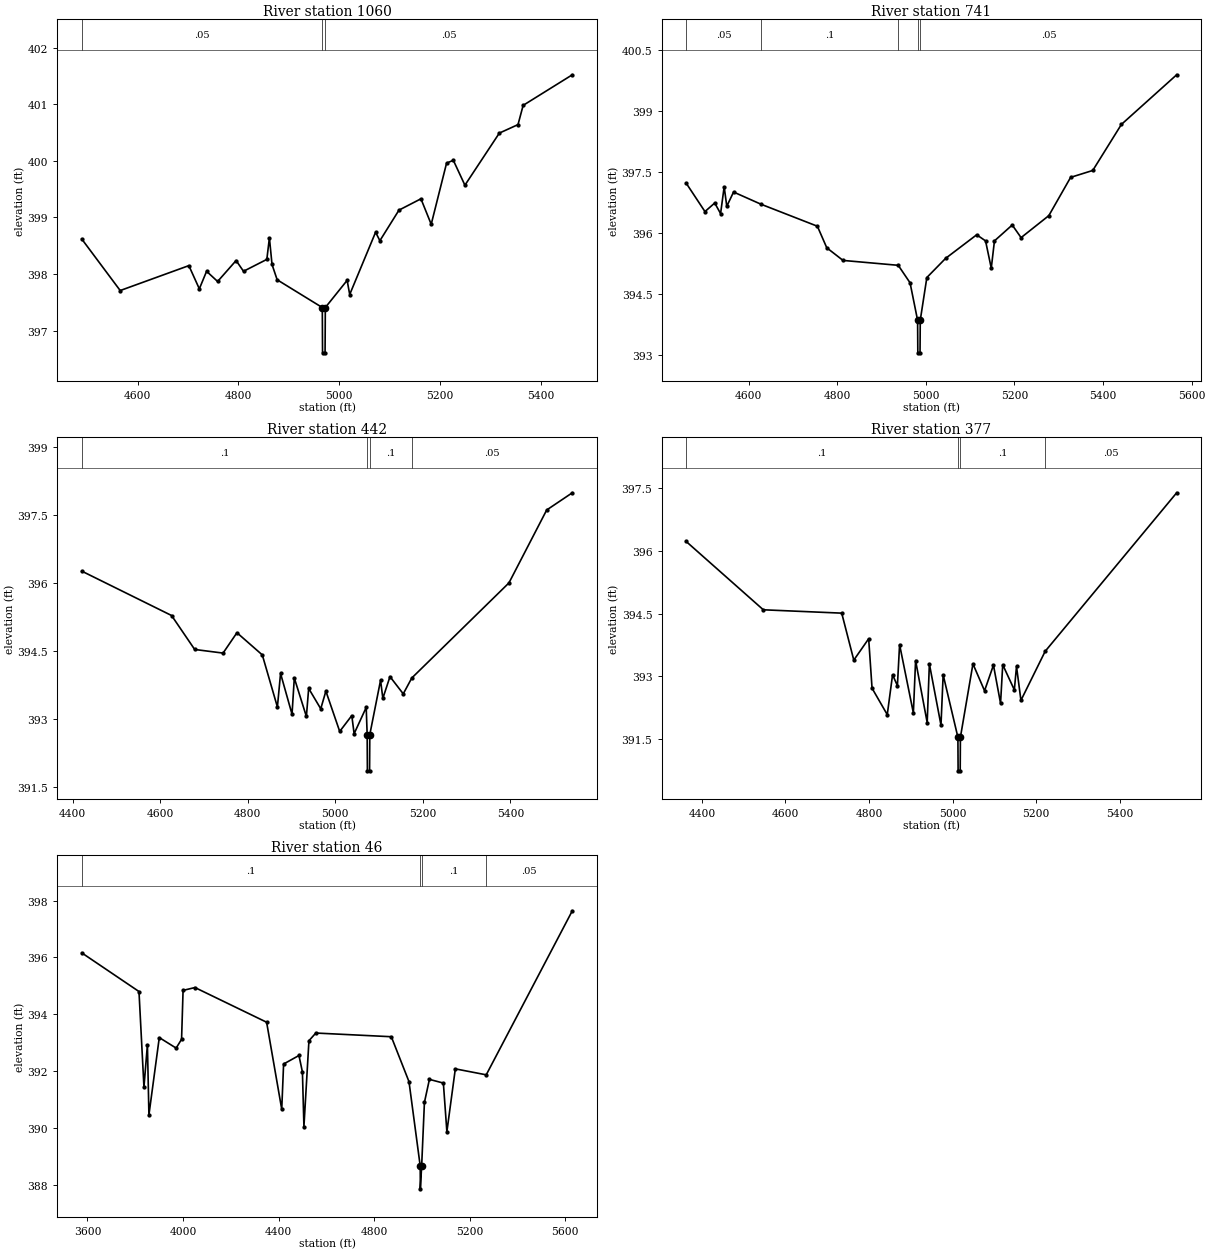
Type RM Length L Ch R = 1,1060,319,319,319
BEGIN DESCRIPTION:
Mapping XS acf56cc7
END DESCRIPTION:
XS GIS Cut Line= 4
      2059136.08     13459334.08      2059298.86     13459127.90
      2059392.18     13458652.64      2059357.69     13458428.50
#Sta/Elev= 30
  4489.3  398.62  4565.6  397.71  4701.9  398.15  4722.7  397.74  4737.1  398.05
  4759.0  397.87  4795.7  398.24  4810.4  398.05  4856.7  398.26  4861.8  398.64
  4867.0  398.17  4877.2  397.90  4966.8  397.41  4967.3  396.61  4972.3  396.61
  4972.8  397.41  5016.1  397.89  5021.2  397.64  5072.6  398.74  5081.1  398.59
  5119.0  399.13  5162.6  399.33  5183.0  398.88  5213.5  399.96  5226.9  400.01
  5249.9  399.57  5318.2  400.49  5355.3  400.64  5365.5  400.98  5463.1  401.52
#Mann=3,-1,0
  4489.3    0.05       0  4966.8    0.03       0  4972.8    0.05       0
Bank Sta=4966.8,4972.8
Exp/Cntr=0.3,0.1

Type RM Length L Ch R = 1,741,299,299,299
BEGIN DESCRIPTION:
Mapping XS 7e917638
END DESCRIPTION:
XS GIS Cut Line= 4
      2059298.83     13459286.33      2059628.72     13459082.33
      2059659.10     13458656.98      2059483.30     13458422.58
#Sta/Elev= 30
  4458.9  397.23  4501.4  396.53  4523.5  396.74  4536.7  396.48  4544.8  397.14
  4550.7  396.66  4566.0  397.01  4628.0  396.71  4755.2  396.17  4776.4  395.64
  4813.1  395.33  4937.7  395.21  4964.4  394.78  4981.4  393.86  4981.9  393.06
  4986.9  393.06  4987.4  393.86  5002.3  394.91  5044.6  395.38  5114.8  395.96
  5134.8  395.81  5147.7  395.14  5154.9  395.81  5195.0  396.20  5215.0  395.89
  5277.6  396.43  5326.8  397.37  5376.8  397.54  5441.4  398.67  5566.2  399.89
#Mann=5,-1,0
  4458.9    0.05       0  4628.0     0.1       0  4937.7    0.05       0
  4981.4    0.03       0  4987.4    0.05       0
Bank Sta=4981.4,4987.4
Exp/Cntr=0.3,0.1

Type RM Length L Ch R = 1,442,65,65,65
BEGIN DESCRIPTION:
Mapping XS fc8af61a
END DESCRIPTION:
XS GIS Cut Line= 4
      2059476.82     13459208.19      2059872.46     13458982.66
      2059949.90     13458728.59      2059639.81     13458477.05
#Sta/Elev= 30
  4421.1  396.26  4626.2  395.28  4679.0  394.53  4743.8  394.45  4775.5  394.90
  4833.4  394.41  4867.9  393.26  4875.1  394.00  4901.3  393.10  4906.5  393.90
  4934.1  393.05  4939.3  393.67  4966.9  393.22  4978.6  393.61  5010.2  392.72
  5037.8  393.07  5043.1  392.67  5070.7  393.25  5072.9  392.65  5073.4  391.85
  5078.4  391.85  5078.9  392.65  5103.5  393.85  5108.7  393.45  5125.0  393.93
  5155.3  393.55  5174.8  393.90  5396.7  396.00  5482.9  397.61  5541.4  397.99
#Mann=4,-1,0
  4421.1     0.1       0  5072.9    0.07       0  5078.9     0.1       0
  5174.8    0.05       0
Bank Sta=5072.9,5078.9
Exp/Cntr=0.3,0.1

Type RM Length L Ch R = 1,377,331,331,331
BEGIN DESCRIPTION:
Mapping XS 19c7fe6e
END DESCRIPTION:
XS GIS Cut Line= 4
      2059507.21     13459251.59      2059926.28     13458982.66
      2060011.35     13458699.67      2059730.74     13458442.16
#Sta/Elev= 30
  4362.3  396.22  4547.1  394.59  4734.8  394.51  4763.7  393.39  4799.3  393.90
  4807.4  392.72  4843.8  392.09  4856.5  393.04  4868.1  392.78  4873.3  393.76
  4906.3  392.13  4911.6  393.38  4939.4  391.90  4944.6  393.30  4972.4  391.84
  4977.6  393.04  5012.9  391.55  5013.4  390.75  5018.4  390.75  5018.9  391.55
  5048.9  393.30  5076.7  392.66  5098.0  393.27  5115.0  392.36  5120.2  393.28
  5148.0  392.68  5153.2  393.24  5163.8  392.43  5221.8  393.60  5536.6  397.38
#Mann=4,-1,0
  4362.3     0.1       0  5012.9    0.07       0  5018.9     0.1       0
  5221.8    0.05       0
Bank Sta=5012.9,5018.9
Exp/Cntr=0.3,0.1

Type RM Length L Ch R = 1,46,0,0,0
BEGIN DESCRIPTION:
UNT 65 in Lagunillas Cr Wtrshd 1.0
END DESCRIPTION:
XS GIS Cut Line= 4
      2059511.10     13459856.61      2060303.63     13458834.93
      2060084.45     13458539.79      2059711.17     13458416.09
#Sta/Elev= 30
  3576.0  396.16  3815.6  394.80  3836.4  391.44  3850.9  392.93  3857.2  390.46
  3900.6  393.18  3971.2  392.81  3993.9  393.12  4000.2  394.84  4050.0  394.94
  4350.0  393.72  4413.3  390.66  4421.1  392.25  4485.4  392.55  4499.9  391.97
  4506.2  390.05  4527.2  393.07  4556.0  393.34  4872.1  393.21  4946.1  391.63
  4993.1  388.66  4993.6  387.86  4999.1  388.66  5010.7  390.90  5031.6  391.71
  5090.0  391.58  5104.7  389.87  5140.1  392.08  5269.5  391.87  5629.9  397.64
#Mann=4,-1,0
  3576.0     0.1       0  4993.1    0.07       0  4999.1     0.1       0
  5269.5    0.05       0
Bank Sta=4993.1,4999.1
Exp/Cntr=0.3,0.1

Chan Stop Cuts=-1