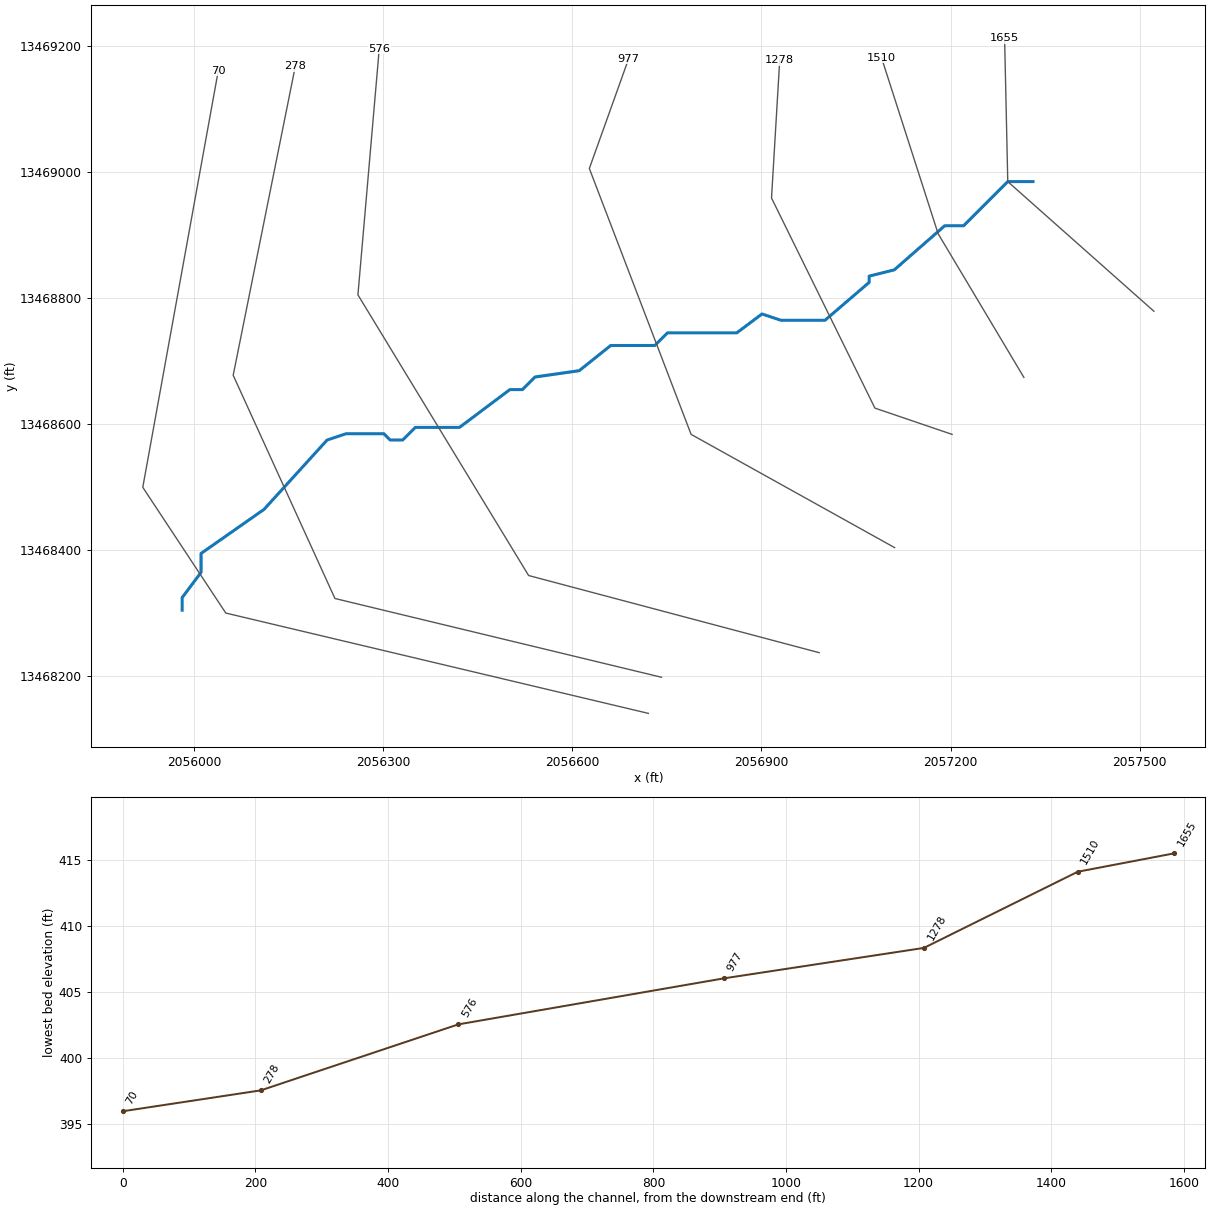
--- UNT 66 in Lagunillas Cr Wtrshd.prj (project) ---

Proj Title=UNT 66 in Lagunillas Cr Wtrshd Base Level Engineering
Current Plan=p01
Default Exp/Contr=0.3,0.1
English Units
Geom File=g01
Flow File=f01
Plan File=p01
BEGIN DESCRIPTION:
UNT 66 in Lagunillas Cr Wtrshd
END DESCRIPTION:

--- UNT 66 in Lagunillas Cr Wtrshd.p01 (plan) ---

Plan Title=Multiple Run
Short Identifier=Multiple
Geom File=g01
Flow File=f01
Subcritical Flow
K Sum by GR= 0
Std Step Tol= 0.01
Critical Tol= 0.01
Num of Std Step Trials= 20
Max Error Tol= 0.3
Flow Tol Ratio= 0.001
Split Flow NTrial= 30
Split Flow Tol= 0.02
Split Flow Ratio= 0.02
Log Output Level= 0
Friction Slope Method= 1
Unsteady Friction Slope Method= 2
Unsteady Bridges Friction Slope Method= 1
Parabolic Critical Depth
Global Vel Dist=  1 , 1 , 1
Global Log Level= 0
CheckData=True
Encroach Param= -1, 0, 0, 0
BEGIN DESCRIPTION:
Multiple Run
END DESCRIPTION:

--- UNT 66 in Lagunillas Cr Wtrshd.f01 (steady flow) ---

Flow Title=Multiple
Number of Profiles=7
Profile Names=10-year,25-year,50-year,1pct_min,100-year,1pct_plu,500-year
River Rch & RM= UNT 66 in Laguni,Reach-1,1655
      98     129     153      91     181     361     258
Boundary for River Rch & Prof#=UNT 66 in Laguni,Reach-1,1
Up Type=0
Dn Type=3
Dn Slope=0.005
Boundary for River Rch & Prof#=UNT 66 in Laguni,Reach-1,2
Up Type=0
Dn Type=3
Dn Slope=0.005
Boundary for River Rch & Prof#=UNT 66 in Laguni,Reach-1,3
Up Type=0
Dn Type=3
Dn Slope=0.005
Boundary for River Rch & Prof#=UNT 66 in Laguni,Reach-1,4
Up Type=0
Dn Type=3
Dn Slope=0.005
Boundary for River Rch & Prof#=UNT 66 in Laguni,Reach-1,5
Up Type=0
Dn Type=3
Dn Slope=0.005
Boundary for River Rch & Prof#=UNT 66 in Laguni,Reach-1,6
Up Type=0
Dn Type=3
Dn Slope=0.005
Boundary for River Rch & Prof#=UNT 66 in Laguni,Reach-1,7
Up Type=0
Dn Type=3
Dn Slope=0.005

--- UNT 66 in Lagunillas Cr Wtrshd.g01 (geometry) ---

Geom Title=Existing Conditions

River Reach=UNT 66 in Laguni,Reach-1
Reach XY= 30
      2057330.80     13468984.54      2057290.80     13468984.54
      2057220.80     13468914.54      2057190.80     13468914.54
      2057110.80     13468844.54      2057070.80     13468834.54
      2057070.80     13468824.54      2057000.80     13468764.54
      2056930.80     13468764.54      2056900.80     13468774.54
      2056860.80     13468744.54      2056750.80     13468744.54
      2056730.80     13468724.54      2056660.80     13468724.54
      2056610.80     13468684.54      2056540.80     13468674.54
      2056520.80     13468654.54      2056500.80     13468654.54
      2056420.80     13468594.54      2056350.80     13468594.54
      2056330.80     13468574.54      2056310.80     13468574.54
      2056300.80     13468584.54      2056240.80     13468584.54
      2056210.80     13468574.54      2056110.80     13468464.54
      2056010.80     13468394.54      2056010.80     13468364.54
      2055980.80     13468324.54      2055980.80     13468304.54

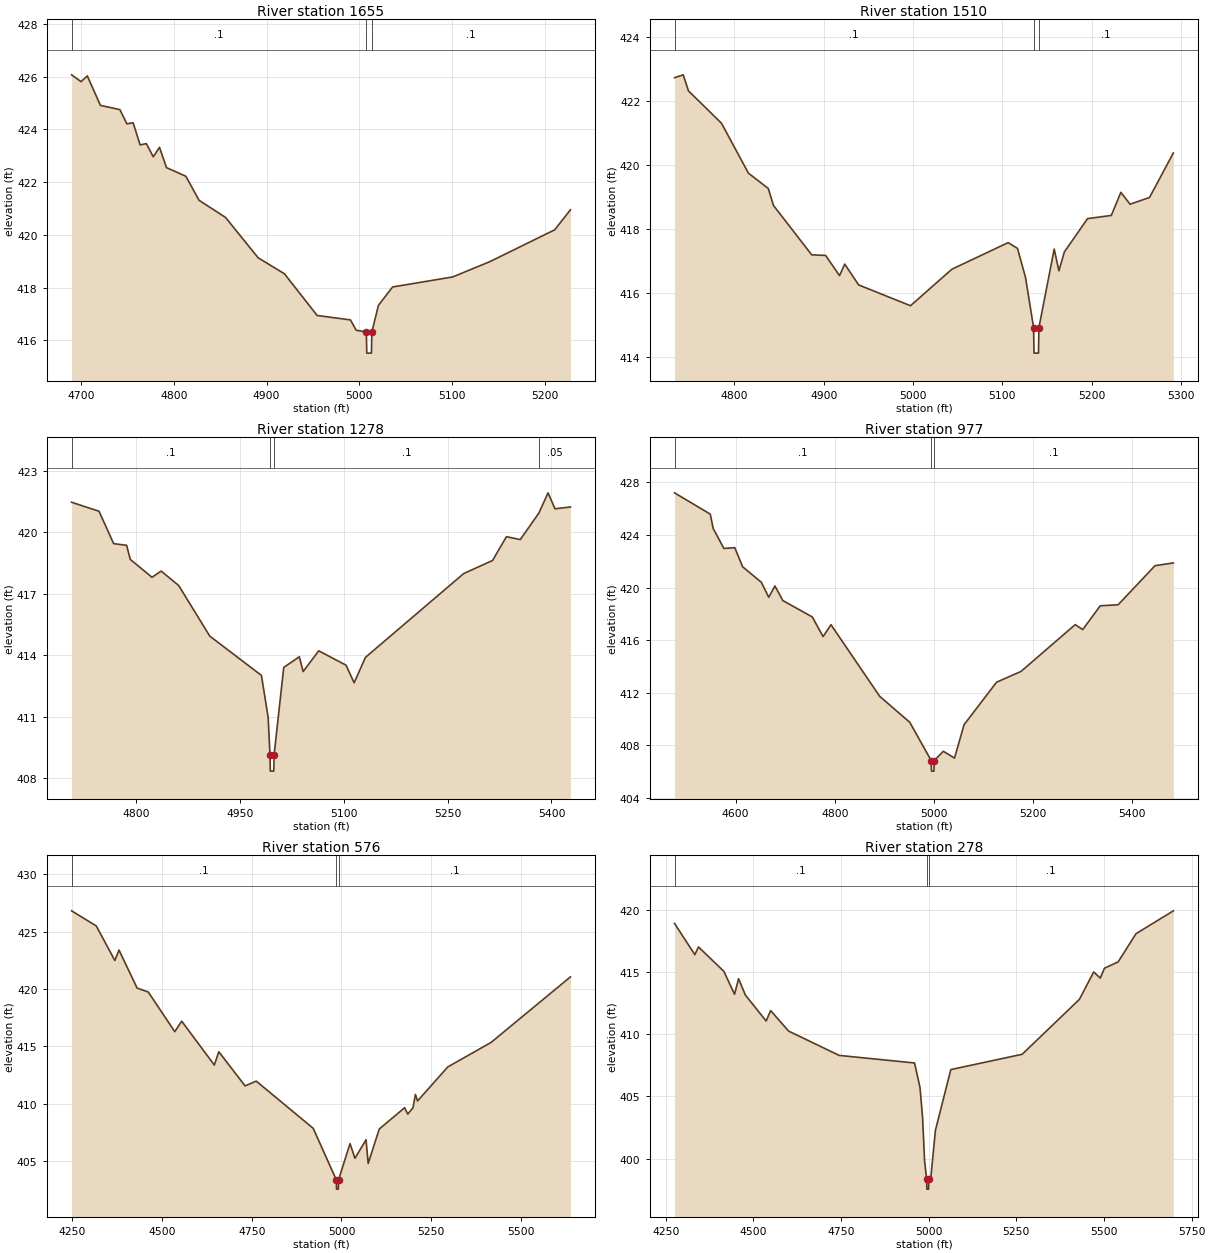
Type RM Length L Ch R = 1,1655,145,145,145
BEGIN DESCRIPTION:
UNT 66 in Lagunillas Cr Wtrshd 3.0
END DESCRIPTION:
XS GIS Cut Line= 3
      2057522.70     13468778.82      2057290.80     13468984.54
      2057285.77     13469211.88
#Sta/Elev= 30
  4690.0  426.07  4700.2  425.81  4706.9  426.03  4721.1  424.91  4742.0  424.75
  4749.6  424.21  4756.3  424.25  4763.8  423.41  4770.5  423.46  4778.0  422.96
  4784.7  423.32  4792.2  422.55  4813.1  422.22  4827.3  421.31  4855.8  420.66
  4890.9  419.13  4919.3  418.52  4954.5  416.94  4990.4  416.77  4996.6  416.38
  5007.5  416.31  5008.0  415.51  5013.0  415.51  5013.5  416.31  5020.5  417.32
  5035.8  418.02  5100.5  418.40  5140.5  418.98  5210.5  420.19  5227.4  420.95
#Mann=3,-1,0
  4690.0     0.1       0  5007.5    0.07       0  5013.5     0.1       0
Bank Sta=5007.5,5013.5
Exp/Cntr=0.3,0.1

Type RM Length L Ch R = 1,1510,232,232,232
BEGIN DESCRIPTION:
Mapping XS 2889de9c
END DESCRIPTION:
XS GIS Cut Line= 3
      2057316.36     13468673.90      2057180.25     13468901.96
      2057090.46     13469181.19
#Sta/Elev= 30
  4732.8  422.72  4742.6  422.81  4748.4  422.31  4785.4  421.30  4815.6  419.74
  4837.9  419.26  4843.7  418.73  4886.5  417.19  4902.1  417.17  4917.7  416.54
  4923.5  416.90  4939.1  416.25  4997.2  415.60  5043.6  416.74  5106.6  417.57
  5117.1  417.39  5126.1  416.48  5135.1  414.92  5135.6  414.12  5140.6  414.12
  5141.1  414.92  5158.2  417.37  5163.5  416.69  5169.6  417.28  5195.6  418.32
  5222.2  418.42  5232.9  419.14  5243.2  418.77  5265.0  418.98  5291.7  420.37
#Mann=3,-1,0
  4732.8     0.1       0  5135.1    0.07       0  5141.1     0.1       0
Bank Sta=5135.1,5141.1
Exp/Cntr=0.3,0.1

Type RM Length L Ch R = 1,1278,301,301,301
BEGIN DESCRIPTION:
Mapping XS 871ce02b
END DESCRIPTION:
XS GIS Cut Line= 4
      2057202.44     13468583.49      2057080.00     13468625.17
      2056915.94     13468958.50      2056928.96     13469177.25
#Sta/Elev= 30
  4707.4  421.47  4747.0  421.03  4768.1  419.45  4786.8  419.37  4792.1  418.68
  4823.4  417.81  4836.7  418.11  4861.9  417.41  4906.8  414.94  4981.4  413.02
  4991.1  410.97  4993.7  409.15  4994.2  408.35  4999.2  408.35  4999.7  409.15
  5013.6  413.41  5036.1  413.93  5041.6  413.21  5064.1  414.22  5103.5  413.52
  5115.2  412.66  5131.5  413.90  5273.3  417.99  5315.0  418.63  5335.0  419.79
  5355.0  419.65  5381.8  420.94  5395.1  421.93  5405.1  421.15  5427.4  421.24
#Mann=4,-1,0
  4707.4     0.1       0  4993.7    0.07       0  4999.7     0.1       0
  5381.8    0.05       0
Bank Sta=4993.7,4999.7
Exp/Cntr=0.3,0.1

Type RM Length L Ch R = 1,977,401,401,401
BEGIN DESCRIPTION:
Mapping XS 95fb4835
END DESCRIPTION:
XS GIS Cut Line= 4
      2057111.24     13468403.82      2056788.33     13468583.50
      2056626.87     13469005.38      2056689.38     13469179.87
#Sta/Elev= 30
  4476.7  427.21  4548.9  425.59  4554.7  424.50  4576.4  422.98  4598.3  423.04
  4614.1  421.59  4651.9  420.41  4666.9  419.27  4679.3  420.13  4695.3  419.02
  4754.8  417.77  4776.5  416.28  4792.5  417.18  4890.7  411.74  4951.5  409.76
  4994.7  406.85  4995.2  406.05  5000.2  406.05  5000.7  406.85  5019.2  407.56
  5041.7  407.04  5061.0  409.58  5126.5  412.81  5175.9  413.63  5285.3  417.19
  5300.4  416.81  5335.8  418.62  5371.9  418.70  5446.3  421.67  5483.3  421.88
#Mann=3,-1,0
  4476.7     0.1       0  4994.7    0.07       0  5000.7     0.1       0
Bank Sta=4994.7,5000.7
Exp/Cntr=0.3,0.1

Type RM Length L Ch R = 1,576,298,298,298
BEGIN DESCRIPTION:
Mapping XS f6eb66d5
END DESCRIPTION:
XS GIS Cut Line= 4
      2056991.50     13468237.13      2056530.52     13468359.54
      2056259.69     13468804.85      2056293.54     13469195.43
#Sta/Elev= 30
  4248.0  426.83  4316.8  425.51  4368.5  422.50  4380.1  423.41  4430.6  420.09
  4461.7  419.75  4535.6  416.29  4554.8  417.21  4645.8  413.38  4658.2  414.54
  4731.6  411.56  4762.5  411.98  4921.4  407.86  4985.8  403.36  4986.3  402.56
  4991.3  402.56  4991.8  403.36  5023.9  406.53  5037.7  405.25  5068.6  406.87
  5074.5  404.80  5105.4  407.80  5176.1  409.66  5184.9  409.10  5199.5  409.66
  5206.2  410.82  5212.1  410.25  5296.5  413.22  5416.9  415.35  5638.2  421.07
#Mann=3,-1,0
  4248.0     0.1       0  4985.8    0.07       0  4991.8     0.1       0
Bank Sta=4985.8,4991.8
Exp/Cntr=0.3,0.1

Type RM Length L Ch R = 1,278,208,208,208
BEGIN DESCRIPTION:
Mapping XS 55730702
END DESCRIPTION:
XS GIS Cut Line= 4
      2056741.42     13468198.09      2056223.23     13468323.08
      2056061.77     13468677.25      2056160.37     13469167.65
#Sta/Elev= 30
  4275.3  418.90  4333.3  416.39  4343.6  417.01  4416.1  415.05  4446.5  413.21
  4458.0  414.46  4477.3  413.15  4536.6  411.06  4549.4  411.90  4600.8  410.25
  4744.8  408.30  4959.8  407.69  4975.3  405.73  4982.8  403.30  4988.3  399.86
  4994.3  398.36  4994.8  397.56  4999.8  397.56  5000.3  398.36  5005.9  398.39
  5019.3  402.28  5063.2  407.16  5266.7  408.39  5429.9  412.80  5470.7  415.00
  5489.5  414.51  5501.3  415.30  5540.4  415.81  5591.2  418.07  5697.8  419.91
#Mann=3,-1,0
  4275.3     0.1       0  4994.3    0.07       0  5000.3     0.1       0
Bank Sta=4994.3,5000.3
Exp/Cntr=0.3,0.1

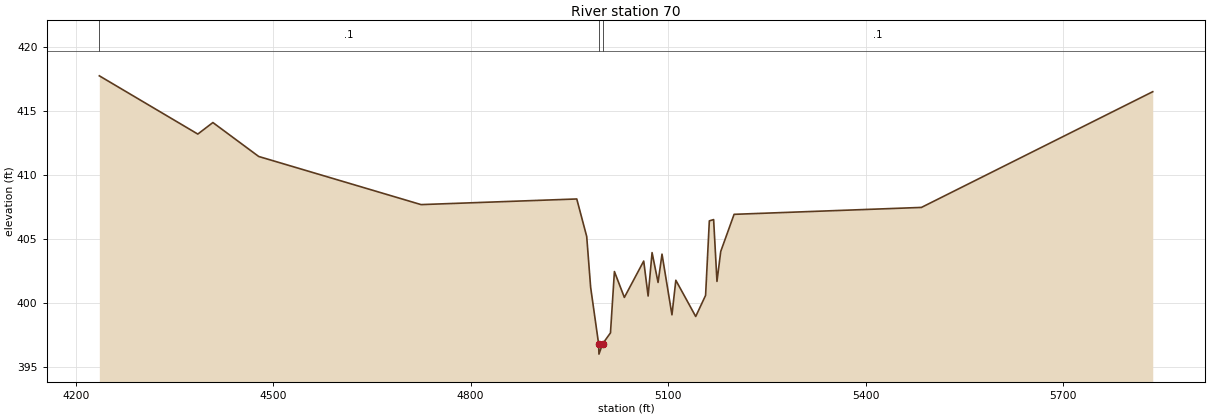
Type RM Length L Ch R = 1,70,0,0,0
BEGIN DESCRIPTION:
UNT 66 in Lagunillas Cr Wtrshd 1.0
END DESCRIPTION:
XS GIS Cut Line= 4
      2056720.58     13468140.80      2056050.00     13468300.00
      2055918.33     13468499.49      2056038.18     13469160.77
#Sta/Elev= 30
  4235.9  417.72  4385.5  413.17  4408.4  414.07  4478.0  411.42  4724.7  407.66
  4961.2  408.10  4976.3  405.17  4982.3  401.19  4994.4  396.78  4994.9  395.98
  5000.4  396.78  5012.4  397.64  5018.4  402.43  5033.5  400.41  5062.9  403.25
  5069.6  400.52  5075.6  403.91  5084.7  401.58  5090.7  403.79  5105.8  399.05
  5111.7  401.75  5141.9  398.92  5156.9  400.57  5162.6  406.39  5169.1  406.49
  5174.2  401.66  5179.9  404.00  5200.2  406.90  5484.8  407.44  5836.2  416.48
#Mann=3,-1,0
  4235.9     0.1       0  4994.4    0.07       0  5000.4     0.1       0
Bank Sta=4994.4,5000.4
Exp/Cntr=0.3,0.1

Chan Stop Cuts=-1