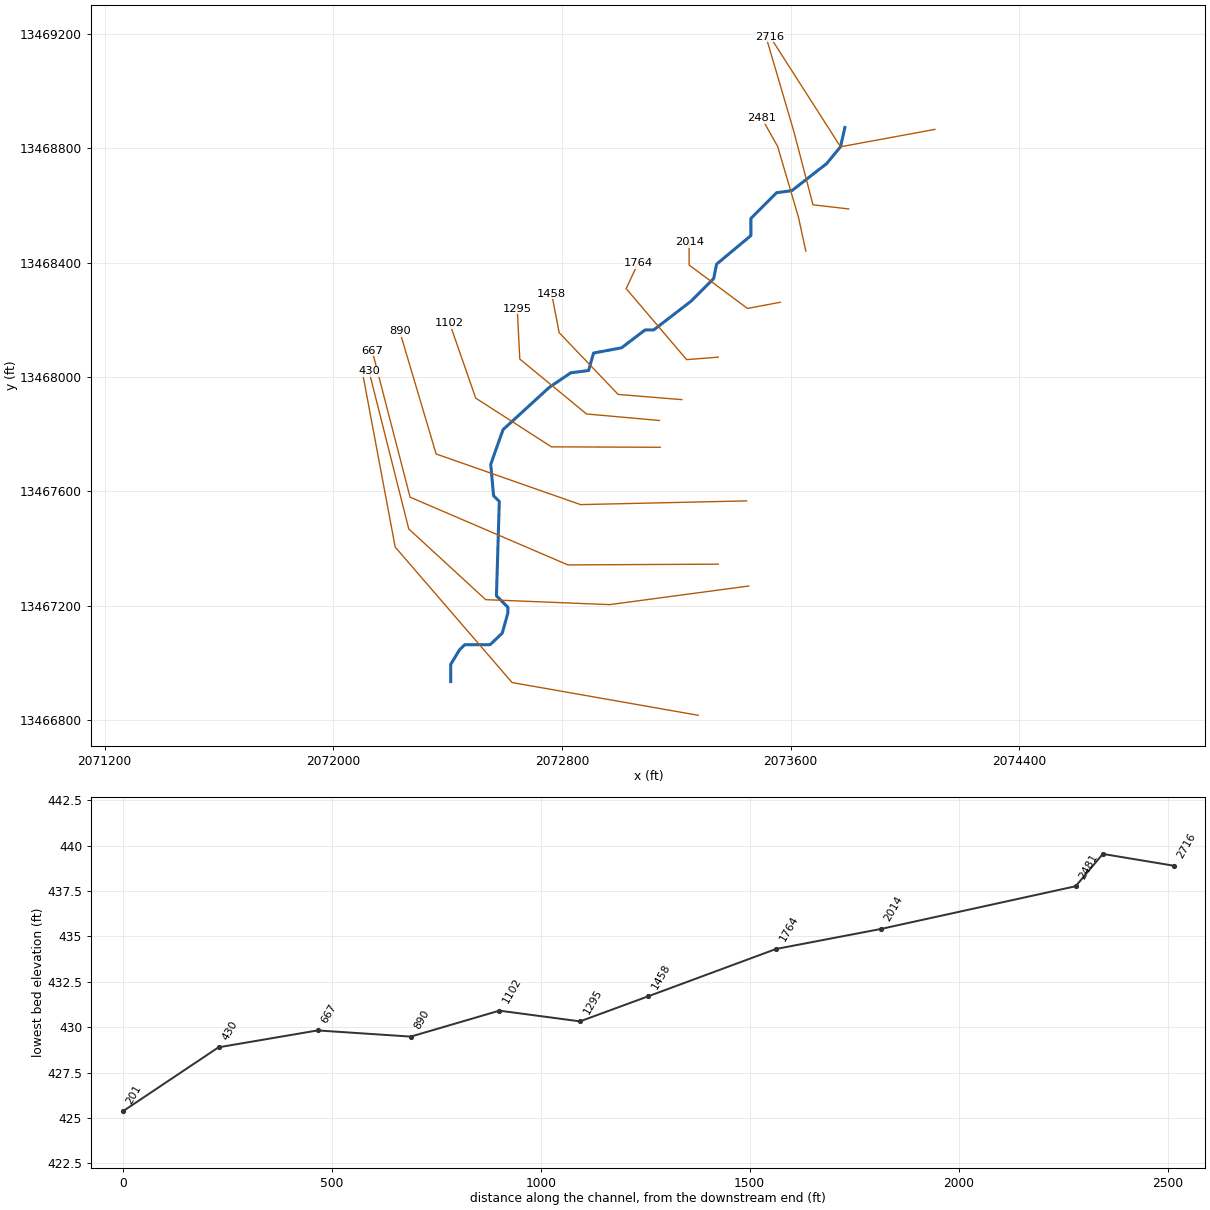
--- UNT 67 in Lagunillas Cr Wtrshd.prj (project) ---

Proj Title=UNT 67 in Lagunillas Cr Wtrshd Base Level Engineering
Current Plan=p01
Default Exp/Contr=0.3,0.1
English Units
Geom File=g01
Flow File=f01
Plan File=p01
BEGIN DESCRIPTION:
UNT 67 in Lagunillas Cr Wtrshd
END DESCRIPTION:

--- UNT 67 in Lagunillas Cr Wtrshd.p01 (plan) ---

Plan Title=Multiple Run
Short Identifier=Multiple
Geom File=g01
Flow File=f01
Subcritical Flow
K Sum by GR= 0
Std Step Tol= 0.01
Critical Tol= 0.01
Num of Std Step Trials= 20
Max Error Tol= 0.3
Flow Tol Ratio= 0.001
Split Flow NTrial= 30
Split Flow Tol= 0.02
Split Flow Ratio= 0.02
Log Output Level= 0
Friction Slope Method= 1
Unsteady Friction Slope Method= 2
Unsteady Bridges Friction Slope Method= 1
Parabolic Critical Depth
Global Vel Dist=  1 , 1 , 1
Global Log Level= 0
CheckData=True
Encroach Param= -1, 0, 0, 0
BEGIN DESCRIPTION:
Multiple Run
END DESCRIPTION:

--- UNT 67 in Lagunillas Cr Wtrshd.f01 (steady flow) ---

Flow Title=Multiple
Number of Profiles=7
Profile Names=10-year,25-year,50-year,1pct_min,100-year,1pct_plu,500-year
River Rch & RM= UNT 67 in Laguni,Reach-1,2716
     155     209     252     152     304     606     447
Boundary for River Rch & Prof#=UNT 67 in Laguni,Reach-1,1
Up Type=0
Dn Type=3
Dn Slope=0.005
Boundary for River Rch & Prof#=UNT 67 in Laguni,Reach-1,2
Up Type=0
Dn Type=3
Dn Slope=0.005
Boundary for River Rch & Prof#=UNT 67 in Laguni,Reach-1,3
Up Type=0
Dn Type=3
Dn Slope=0.005
Boundary for River Rch & Prof#=UNT 67 in Laguni,Reach-1,4
Up Type=0
Dn Type=3
Dn Slope=0.005
Boundary for River Rch & Prof#=UNT 67 in Laguni,Reach-1,5
Up Type=0
Dn Type=3
Dn Slope=0.005
Boundary for River Rch & Prof#=UNT 67 in Laguni,Reach-1,6
Up Type=0
Dn Type=3
Dn Slope=0.005
Boundary for River Rch & Prof#=UNT 67 in Laguni,Reach-1,7
Up Type=0
Dn Type=3
Dn Slope=0.005

--- UNT 67 in Lagunillas Cr Wtrshd.g01 (geometry) ---

Geom Title=Existing Conditions

River Reach=UNT 67 in Laguni,Reach-1
Reach XY= 30
      2073789.65     13468872.62      2073774.37     13468805.25
      2073725.76     13468746.23      2073604.23     13468651.78
      2073550.80     13468644.54      2073460.80     13468554.54
      2073460.80     13468494.54      2073340.80     13468394.54
      2073330.80     13468344.54      2073250.80     13468264.54
      2073120.80     13468164.54      2073090.80     13468164.54
      2073008.22     13468101.96      2072910.48     13468083.73
      2072893.12     13468022.62      2072830.80     13468014.54
      2072756.31     13467964.28      2072593.81     13467815.67
      2072550.80     13467694.54      2072560.80     13467584.54
      2072580.80     13467564.54      2072570.80     13467234.54
      2072610.80     13467194.54      2072610.80     13467174.54
      2072591.04     13467103.87      2072548.67     13467063.59
      2072459.82     13467063.56      2072440.80     13467044.54
      2072410.80     13466994.54      2072410.80     13466934.54

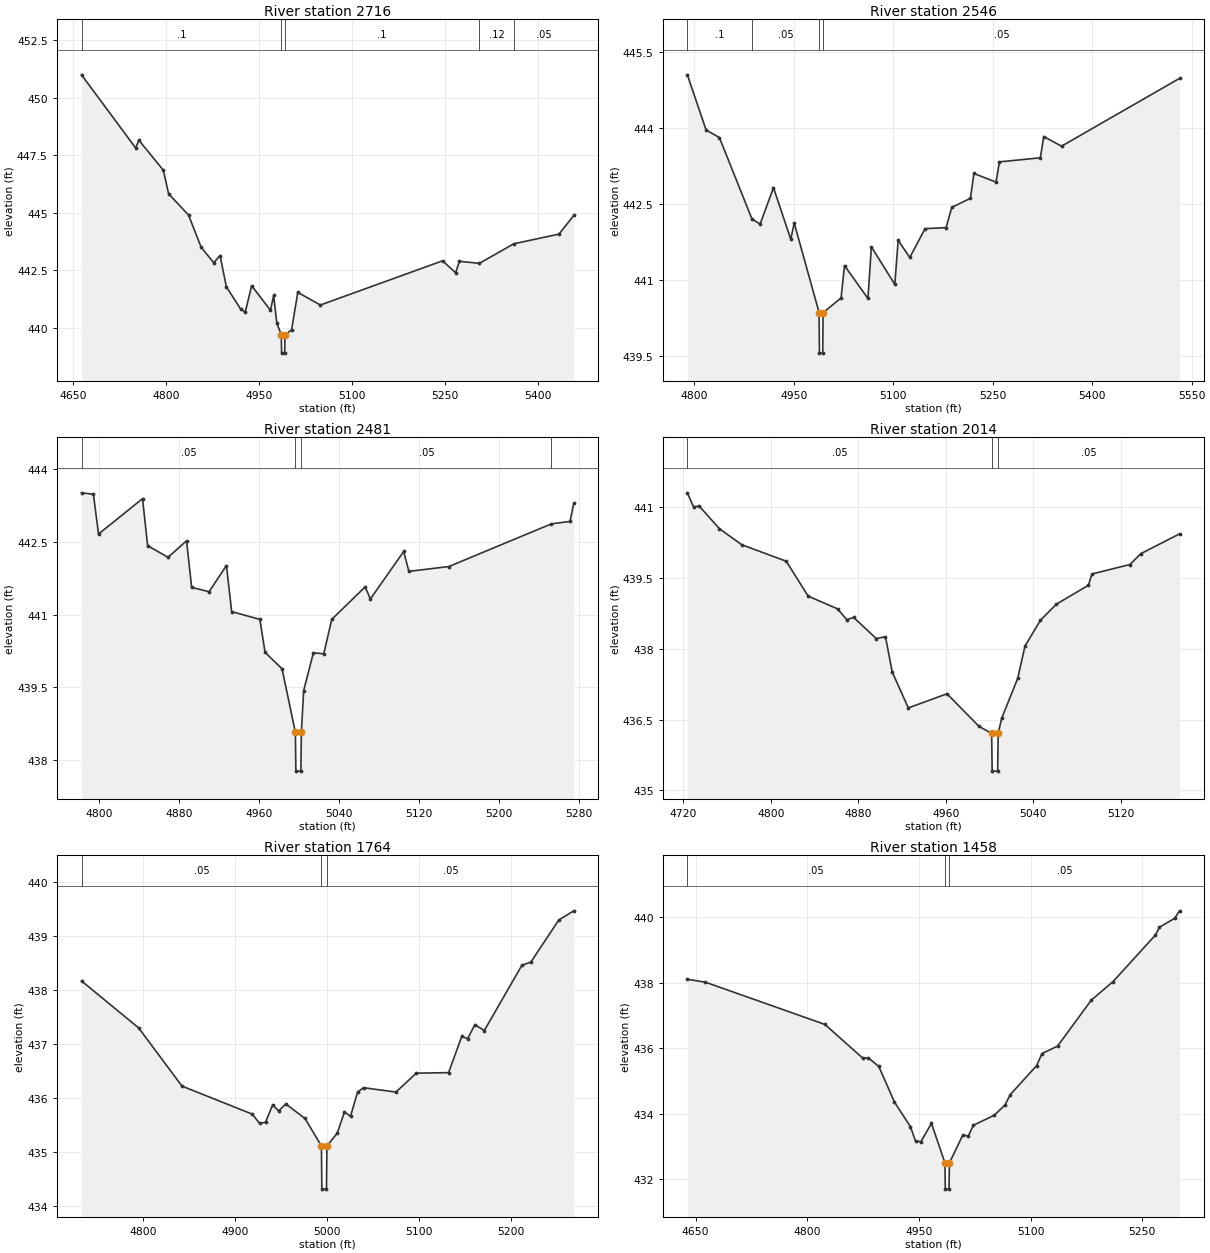
Type RM Length L Ch R = 1,2716,170,170,170
BEGIN DESCRIPTION:
UNT 67 in Lagunillas Cr Wtrshd 4.0
END DESCRIPTION:
XS GIS Cut Line= 3
      2074104.62     13468866.05      2073774.37     13468805.25
      2073527.71     13469190.68
#Sta/Elev= 30
  4664.2  450.99  4751.5  447.81  4756.6  448.15  4796.0  446.85  4804.6  445.82
  4836.7  444.90  4857.0  443.50  4877.3  442.83  4887.5  443.14  4897.7  441.78
  4920.8  440.81  4928.2  440.69  4938.4  441.83  4968.8  440.76  4973.9  441.41
  4979.0  440.20  4986.2  439.70  4986.7  438.90  4991.7  438.90  4992.2  439.70
  5002.8  439.91  5012.8  441.54  5049.2  440.99  5246.2  442.91  5267.3  442.39
  5273.3  442.89  5305.5  442.80  5361.0  443.65  5433.9  444.07  5457.6  444.88
#Mann=5,-1,0
  4664.2     0.1       0  4986.2    0.07       0  4992.2     0.1       0
  5305.5    0.12       0  5361.0    0.05       0
Bank Sta=4986.2,4992.2
Exp/Cntr=0.3,0.1

Type RM Length L Ch R = 1,2546,65,65,65
BEGIN DESCRIPTION:
Mapping XS 0d3dcf0c
END DESCRIPTION:
XS GIS Cut Line= 4
      2073802.98     13468587.77      2073677.98     13468602.35
      2073611.31     13468857.91      2073512.10     13469195.68
#Sta/Elev= 30
  4789.8  445.05  4818.0  443.96  4838.1  443.81  4887.2  442.20  4899.5  442.10
  4919.6  442.82  4945.7  441.80  4950.9  442.12  4988.4  440.35  4988.9  439.55
  4993.9  439.55  4994.4  440.35  5021.5  440.64  5026.7  441.28  5062.0  440.63
  5067.2  441.65  5102.5  440.91  5107.6  441.78  5125.1  441.44  5148.1  442.01
  5179.8  442.03  5188.4  442.43  5216.5  442.61  5221.8  443.10  5255.1  442.93
  5260.3  443.33  5321.9  443.41  5327.1  443.83  5353.9  443.64  5531.8  444.98
#Mann=4,-1,0
  4789.8     0.1       0  4887.2    0.05       0  4988.4    0.04       0
  4994.4    0.05       0
Bank Sta=4988.4,4994.4
Exp/Cntr=0.3,0.1

Type RM Length L Ch R = 1,2481,467,467,467
BEGIN DESCRIPTION:
Mapping XS ed3a3033
END DESCRIPTION:
XS GIS Cut Line= 4
      2073652.99     13468440.50      2073627.28     13468558.60
      2073554.37     13468806.52      2073499.05     13468904.85
#Sta/Elev= 30
  4782.6  443.51  4794.5  443.48  4799.6  442.66  4843.6  443.39  4848.7  442.42
  4869.1  442.18  4887.6  442.52  4892.7  441.56  4910.1  441.47  4927.5  442.01
  4932.7  441.06  4960.9  440.90  4966.1  440.22  4983.1  439.88  4996.4  438.57
  4996.9  437.77  5001.9  437.77  5002.4  438.57  5004.7  439.43  5014.4  440.21
  5024.8  440.19  5032.8  440.90  5066.2  441.57  5071.4  441.32  5104.7  442.30
  5109.9  441.89  5149.9  441.99  5252.4  442.87  5271.0  442.92  5274.7  443.29
#Mann=4,-1,0
  4782.6    0.05       0  4996.4    0.04       0  5002.4    0.05       0
  5252.4     0.1       0
Bank Sta=4996.4,5002.4
Exp/Cntr=0.3,0.1

Type RM Length L Ch R = 1,2014,250,250,250
BEGIN DESCRIPTION:
Mapping XS 526d0691
END DESCRIPTION:
XS GIS Cut Line= 4
      2073563.82     13468261.40      2073448.79     13468239.70
      2073244.79     13468391.61      2073244.79     13468470.41
#Sta/Elev= 30
  4723.7  441.31  4729.4  441.01  4734.5  441.03  4753.0  440.55  4773.4  440.21
  4814.1  439.86  4834.2  439.12  4861.1  438.85  4869.5  438.62  4875.7  438.67
  4896.5  438.22  4904.9  438.26  4911.1  437.51  4925.8  436.75  4961.2  437.05
  4990.4  436.36  5002.0  436.21  5002.5  435.41  5007.5  435.41  5008.0  436.21
  5011.2  436.53  5025.9  437.38  5032.5  438.06  5046.7  438.61  5061.3  438.95
  5090.5  439.35  5093.8  439.59  5128.5  439.79  5138.5  440.02  5173.9  440.44
#Mann=3,-1,0
  4723.7    0.05       0  5002.0    0.03       0  5008.0    0.05       0
Bank Sta=5002,5008
Exp/Cntr=0.3,0.1

Type RM Length L Ch R = 1,1764,306,306,306
BEGIN DESCRIPTION:
Mapping XS 8c7d6326
END DESCRIPTION:
XS GIS Cut Line= 4
      2073346.78     13468069.34      2073236.11     13468060.66
      2073024.53     13468309.14      2073065.78     13468397.07
#Sta/Elev= 30
  4733.5  438.17  4795.5  437.30  4842.6  436.22  4919.0  435.70  4926.8  435.53
  4933.3  435.55  4941.0  435.87  4947.6  435.76  4955.3  435.89  4976.2  435.62
  4994.0  435.11  4994.5  434.31  4999.5  434.31  5000.0  435.11  5011.3  435.35
  5019.0  435.74  5025.6  435.66  5033.3  436.11  5039.8  436.19  5075.0  436.11
  5097.0  436.46  5132.1  436.47  5146.4  437.14  5152.9  437.10  5160.6  437.36
  5170.9  437.25  5211.7  438.46  5221.5  438.52  5251.8  439.30  5268.0  439.47
#Mann=3,-1,0
  4733.5    0.05       0  4994.0    0.03       0  5000.0    0.05       0
Bank Sta=4994,5000
Exp/Cntr=0.3,0.1

Type RM Length L Ch R = 1,1458,163,163,163
BEGIN DESCRIPTION:
Mapping XS e9e53c6b
END DESCRIPTION:
XS GIS Cut Line= 4
      2073219.18     13467920.74      2072996.40     13467939.04
      2072790.23     13468154.97      2072763.79     13468291.55
#Sta/Elev= 30
  4638.9  438.11  4663.2  438.02  4823.7  436.73  4874.6  435.70  4881.9  435.71
  4896.0  435.45  4917.1  434.36  4938.5  433.61  4945.4  433.17  4952.7  433.15
  4966.8  433.71  4984.9  432.50  4985.4  431.70  4990.4  431.70  4990.9  432.50
  5008.9  433.35  5016.2  433.32  5023.1  433.65  5051.4  433.96  5065.6  434.27
  5072.8  434.59  5108.0  435.47  5115.3  435.84  5136.3  436.07  5181.4  437.47
  5210.8  438.04  5267.7  439.46  5273.1  439.70  5293.4  439.97  5300.1  440.20
#Mann=3,-1,0
  4638.9    0.05       0  4984.9    0.03       0  4990.9    0.05       0
Bank Sta=4984.9,4990.9
Exp/Cntr=0.3,0.1

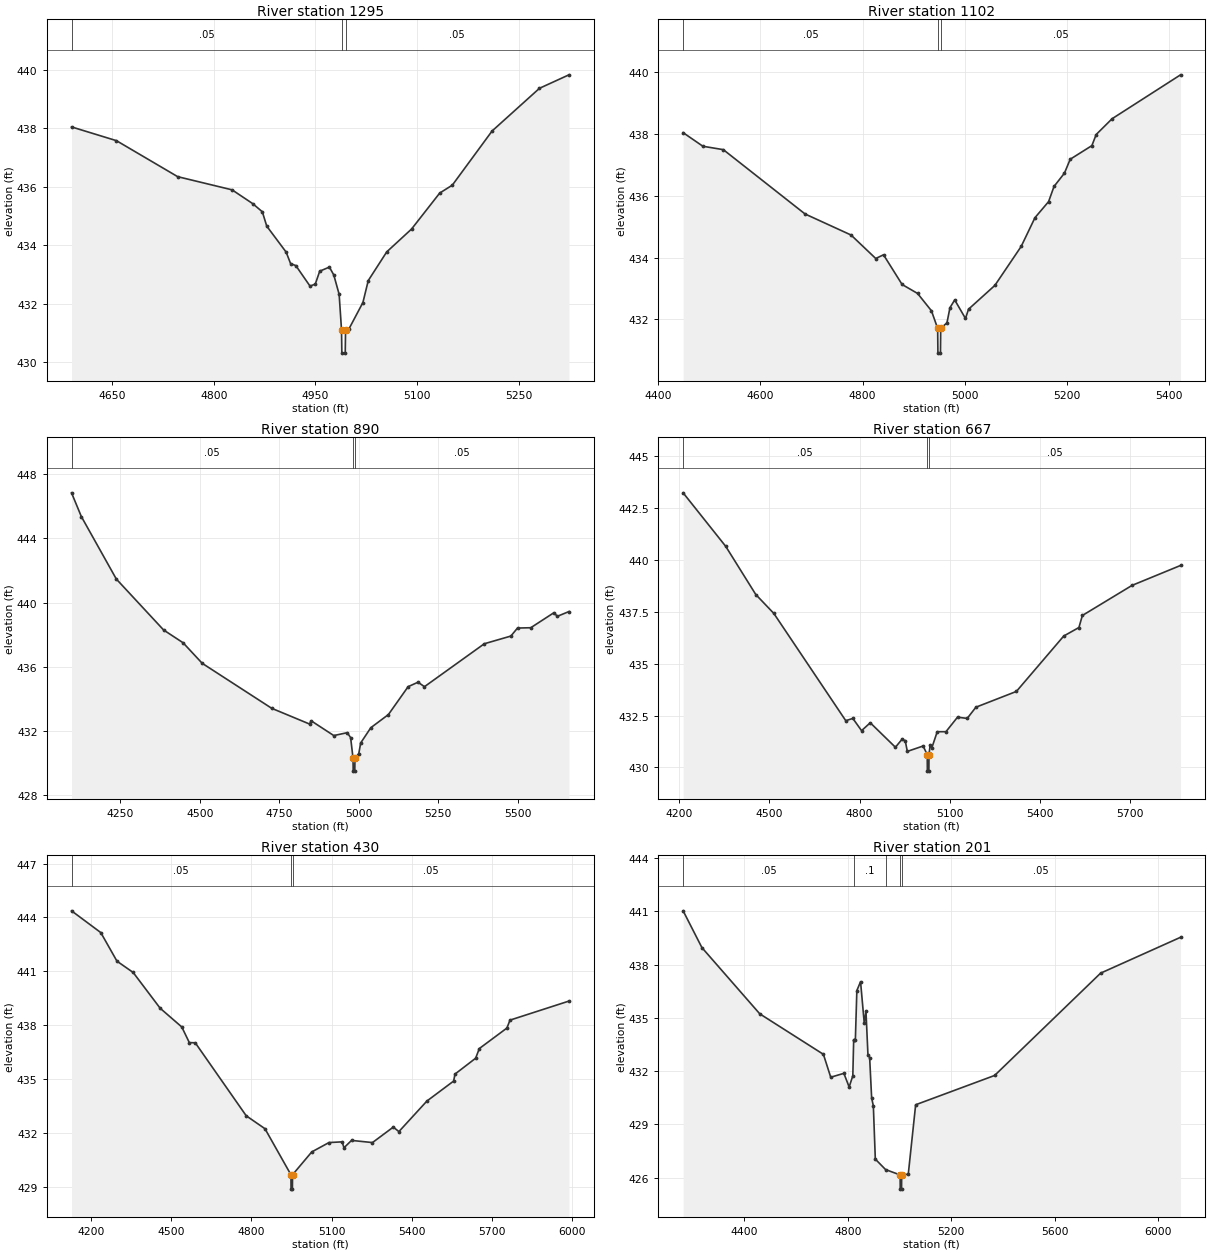
Type RM Length L Ch R = 1,1295,193,193,193
BEGIN DESCRIPTION:
Mapping XS d89d8f9e
END DESCRIPTION:
XS GIS Cut Line= 4
      2073141.05     13467847.82      2072885.72     13467870.68
      2072652.43     13468062.74      2072643.69     13468238.40
#Sta/Elev= 30
  4590.0  438.05  4656.3  437.58  4746.7  436.35  4827.0  435.90  4857.4  435.43
  4871.7  435.15  4878.2  434.66  4906.9  433.77  4913.4  433.38  4921.2  433.31
  4942.1  432.61  4949.9  432.68  4956.4  433.12  4970.7  433.26  4977.2  432.99
  4985.1  432.33  4988.6  431.12  4989.1  430.32  4994.1  430.32  4994.6  431.12
  4999.4  431.14  5020.2  432.05  5028.1  432.80  5055.4  433.78  5092.0  434.56
  5133.6  435.79  5152.2  436.06  5210.9  437.91  5280.9  439.37  5324.4  439.83
#Mann=3,-1,0
  4590.0    0.05       0  4988.6    0.03       0  4994.6    0.05       0
Bank Sta=4988.6,4994.6
Exp/Cntr=0.3,0.1

Type RM Length L Ch R = 1,1102,212,212,212
BEGIN DESCRIPTION:
Mapping XS 161ef3a7
END DESCRIPTION:
XS GIS Cut Line= 4
      2073143.65     13467754.07      2072763.11     13467755.66
      2072498.35     13467926.02      2072406.72     13468188.93
#Sta/Elev= 30
  4448.6  438.04  4487.3  437.60  4527.3  437.49  4687.3  435.41  4777.3  434.73
  4825.7  433.97  4840.9  434.09  4877.3  433.13  4907.6  432.84  4934.7  432.28
  4946.9  431.71  4947.4  430.91  4952.4  430.91  4952.9  431.71  4965.1  431.89
  4971.0  432.38  4980.3  432.63  5001.4  432.03  5007.3  432.33  5058.9  433.10
  5110.4  434.36  5137.4  435.29  5164.1  435.81  5174.7  436.30  5195.1  436.73
  5206.4  437.18  5248.8  437.62  5257.3  437.98  5288.4  438.49  5422.4  439.91
#Mann=3,-1,0
  4448.6    0.05       0  4946.9    0.03       0  4952.9    0.05       0
Bank Sta=4946.9,4952.9
Exp/Cntr=0.3,0.1

Type RM Length L Ch R = 1,890,223,223,223
BEGIN DESCRIPTION:
Mapping XS 68a42615
END DESCRIPTION:
XS GIS Cut Line= 4
      2073445.80     13467566.57      2072865.04     13467553.55
      2072359.84     13467730.63      2072232.28     13468160.14
#Sta/Elev= 30
  4096.7  446.85  4127.5  445.37  4237.5  441.47  4386.2  438.29  4447.6  437.49
  4507.6  436.21  4726.3  433.40  4845.1  432.42  4850.4  432.62  4921.4  431.70
  4963.8  431.88  4974.4  431.57  4982.0  430.28  4982.5  429.48  4987.5  429.48
  4988.0  430.28  5000.1  430.58  5006.1  431.24  5037.9  432.19  5093.2  433.01
  5155.2  434.75  5186.3  435.03  5206.6  434.75  5394.8  437.43  5478.3  437.91
  5499.2  438.41  5540.9  438.43  5613.9  439.37  5624.3  439.14  5661.0  439.44
#Mann=3,-1,0
  4096.7    0.05       0  4982.0    0.03       0  4988.0    0.05       0
Bank Sta=4982,4988
Exp/Cntr=0.3,0.1

Type RM Length L Ch R = 1,667,237,237,237
BEGIN DESCRIPTION:
Mapping XS 2381e1b0
END DESCRIPTION:
XS GIS Cut Line= 4
      2073346.82     13467345.22      2072820.77     13467342.61
      2072268.69     13467579.59      2072136.22     13468091.28
#Sta/Elev= 30
  4212.8  443.23  4354.6  440.65  4454.6  438.33  4514.6  437.42  4754.1  432.25
  4777.6  432.36  4806.6  431.77  4835.6  432.15  4919.3  430.97  4941.0  431.35
  4951.9  431.29  4958.9  430.77  5011.4  431.03  5025.1  430.62  5025.6  429.82
  5030.6  429.82  5031.1  430.62  5035.0  431.09  5040.4  430.94  5058.5  431.72
  5087.5  431.72  5126.0  432.42  5158.2  432.36  5187.2  432.90  5321.9  433.66
  5479.5  436.33  5530.0  436.74  5541.5  437.32  5706.8  438.77  5868.2  439.73
#Mann=3,-1,0
  4212.8    0.05       0  5025.1    0.03       0  5031.1    0.05       0
Bank Sta=5025.1,5031.1
Exp/Cntr=0.3,0.1

Type RM Length L Ch R = 1,430,229,229,229
BEGIN DESCRIPTION:
Mapping XS 8eb4c028
END DESCRIPTION:
XS GIS Cut Line= 5
      2073453.33     13467268.84      2072967.18     13467203.73
      2072533.15     13467221.09      2072264.05     13467468.48
      2072125.15     13468019.75
#Sta/Elev= 30
  4128.4  444.37  4237.7  443.16  4298.2  441.57  4358.8  440.94  4459.7  438.95
  4540.4  437.91  4568.6  437.04  4590.8  437.03  4781.2  432.97  4851.3  432.25
  4948.3  429.69  4948.8  428.89  4953.8  428.89  4954.3  429.69  5026.2  430.96
  5090.4  431.48  5139.7  431.52  5146.5  431.19  5174.8  431.60  5253.1  431.48
  5330.8  432.34  5351.8  432.09  5456.5  433.79  5556.3  434.90  5561.5  435.29
  5638.5  436.17  5652.4  436.71  5755.5  437.85  5766.9  438.29  5987.3  439.35
#Mann=3,-1,0
  4128.4    0.05       0  4948.3    0.03       0  4954.3    0.05       0
Bank Sta=4948.3,4954.3
Exp/Cntr=0.3,0.1

Type RM Length L Ch R = 1,201,0,0,0
BEGIN DESCRIPTION:
Mapping XS 1cbfb807
END DESCRIPTION:
XS GIS Cut Line= 4
      2073276.47     13466816.58      2072625.46     13466931.15
      2072216.61     13467405.11      2072099.72     13468028.49
#Sta/Elev= 30
  4164.1  441.03  4236.6  438.96  4460.1  435.23  4705.9  432.95  4734.2  431.66
  4785.0  431.88  4805.3  431.11  4819.5  431.74  4822.8  433.74  4824.7  433.74
  4829.3  433.74  4835.1  436.54  4849.4  437.04  4863.7  434.70  4870.3  435.38
  4877.9  432.94  4884.5  432.77  4892.2  430.49  4898.8  430.05  4906.4  427.05
  4946.1  426.46  5002.2  426.16  5002.7  425.36  5007.7  425.36  5008.2  426.16
  5033.7  426.20  5062.2  430.11  5367.2  431.76  5776.5  437.52  6085.3  439.54
#Mann=5,-1,0
  4164.1    0.05       0  4824.7     0.1       0  4946.1    0.05       0
  5002.2    0.03       0  5008.2    0.05       0
Bank Sta=5002.2,5008.2
Exp/Cntr=0.3,0.1

Chan Stop Cuts=-1