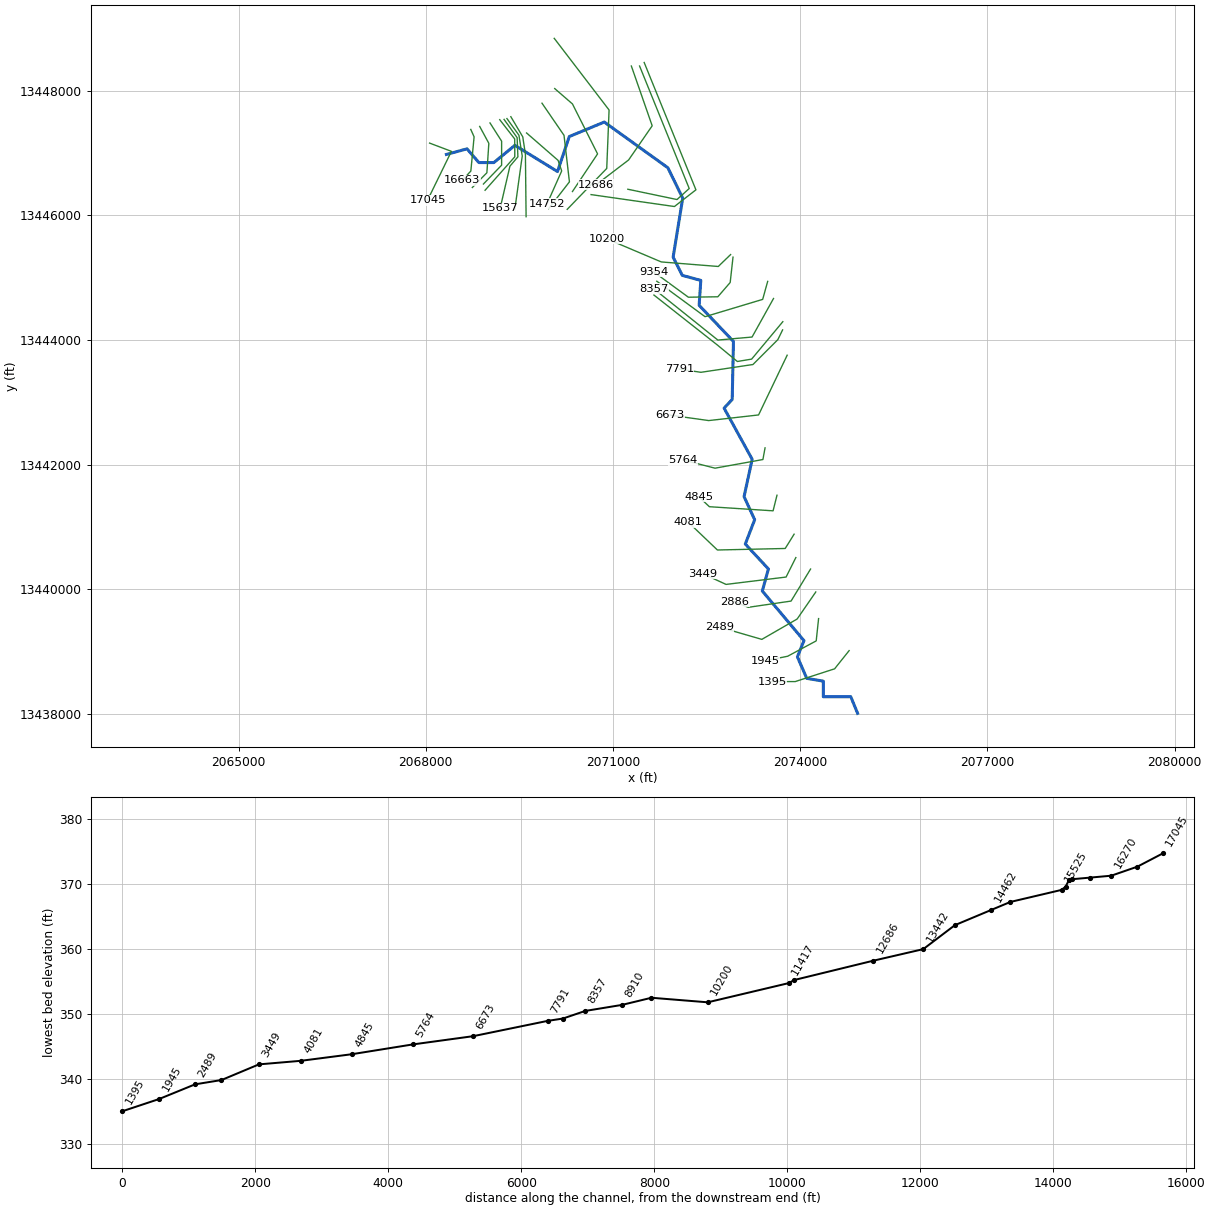
--- UNT 69 in Lagunillas Cr Wtrshd.prj (project) ---

Proj Title=UNT 69 in Lagunillas Cr Wtrshd Base Level Engineering
Current Plan=p01
Default Exp/Contr=0.3,0.1
English Units
Geom File=g01
Flow File=f01
Plan File=p01
BEGIN DESCRIPTION:
UNT 69 in Lagunillas Cr Wtrshd
END DESCRIPTION:

--- UNT 69 in Lagunillas Cr Wtrshd.p01 (plan) ---

Plan Title=Multiple Run
Short Identifier=Multiple
Geom File=g01
Flow File=f01
Subcritical Flow
K Sum by GR= 0
Std Step Tol= 0.01
Critical Tol= 0.01
Num of Std Step Trials= 20
Max Error Tol= 0.3
Flow Tol Ratio= 0.001
Split Flow NTrial= 30
Split Flow Tol= 0.02
Split Flow Ratio= 0.02
Log Output Level= 0
Friction Slope Method= 1
Unsteady Friction Slope Method= 2
Unsteady Bridges Friction Slope Method= 1
Parabolic Critical Depth
Global Vel Dist=  1 , 1 , 1
Global Log Level= 0
CheckData=True
Encroach Param= -1, 0, 0, 0
BEGIN DESCRIPTION:
Multiple Run
END DESCRIPTION:

--- UNT 69 in Lagunillas Cr Wtrshd.f01 (steady flow) ---

Flow Title=Multiple
Number of Profiles=7
Profile Names=10-year,25-year,50-year,1pct_min,100-year,1pct_plu,500-year
River Rch & RM= UNT 69 in Laguni,Reach-1,17045
     147     198     239     144     288     575     424
River Rch & RM= UNT 69 in Laguni,Reach-1,13918
     198     272     331     202     403     803     603
River Rch & RM= UNT 69 in Laguni,Reach-1,10200
     254     351     431     264     528    1053     801
River Rch & RM= UNT 69 in Laguni,Reach-1,7791
     377     532     661     409     817    1630    1266
River Rch & RM= UNT 69 in Laguni,Reach-1,1945
     454     645     806     502    1001    1998    1569
Boundary for River Rch & Prof#=UNT 69 in Laguni,Reach-1,1
Up Type=0
Dn Type=3
Dn Slope=0.005
Boundary for River Rch & Prof#=UNT 69 in Laguni,Reach-1,2
Up Type=0
Dn Type=3
Dn Slope=0.005
Boundary for River Rch & Prof#=UNT 69 in Laguni,Reach-1,3
Up Type=0
Dn Type=3
Dn Slope=0.005
Boundary for River Rch & Prof#=UNT 69 in Laguni,Reach-1,4
Up Type=0
Dn Type=3
Dn Slope=0.005
Boundary for River Rch & Prof#=UNT 69 in Laguni,Reach-1,5
Up Type=0
Dn Type=3
Dn Slope=0.005
Boundary for River Rch & Prof#=UNT 69 in Laguni,Reach-1,6
Up Type=0
Dn Type=3
Dn Slope=0.005
Boundary for River Rch & Prof#=UNT 69 in Laguni,Reach-1,7
Up Type=0
Dn Type=3
Dn Slope=0.005

--- UNT 69 in Lagunillas Cr Wtrshd.g01 (geometry) ---

Geom Title=Existing Conditions

River Reach=UNT 69 in Laguni,Reach-1
Reach XY= 30
      2068330.80     13446974.54      2068660.80     13447064.54
      2068850.80     13446844.54      2069091.09     13446844.54
      2069428.07     13447121.13      2070110.86     13446700.48
      2070299.40     13447261.92      2070860.80     13447494.54
      2071879.85     13446760.75      2072117.70     13446273.77
      2071964.05     13445326.72      2072110.80     13445034.54
      2072407.63     13444953.46      2072380.80     13444554.54
      2072930.80     13443974.54      2072910.80     13443044.54
      2072780.80     13442904.54      2073230.80     13442084.54
      2073100.80     13441484.54      2073270.80     13441114.54
      2073120.80     13440724.54      2073490.80     13440324.54
      2073393.48     13439970.67      2074060.80     13439174.54
      2073955.87     13438914.24      2074105.61     13438569.19
      2074370.80     13438524.54      2074370.80     13438274.54
      2074810.80     13438274.54      2074920.80     13438007.51

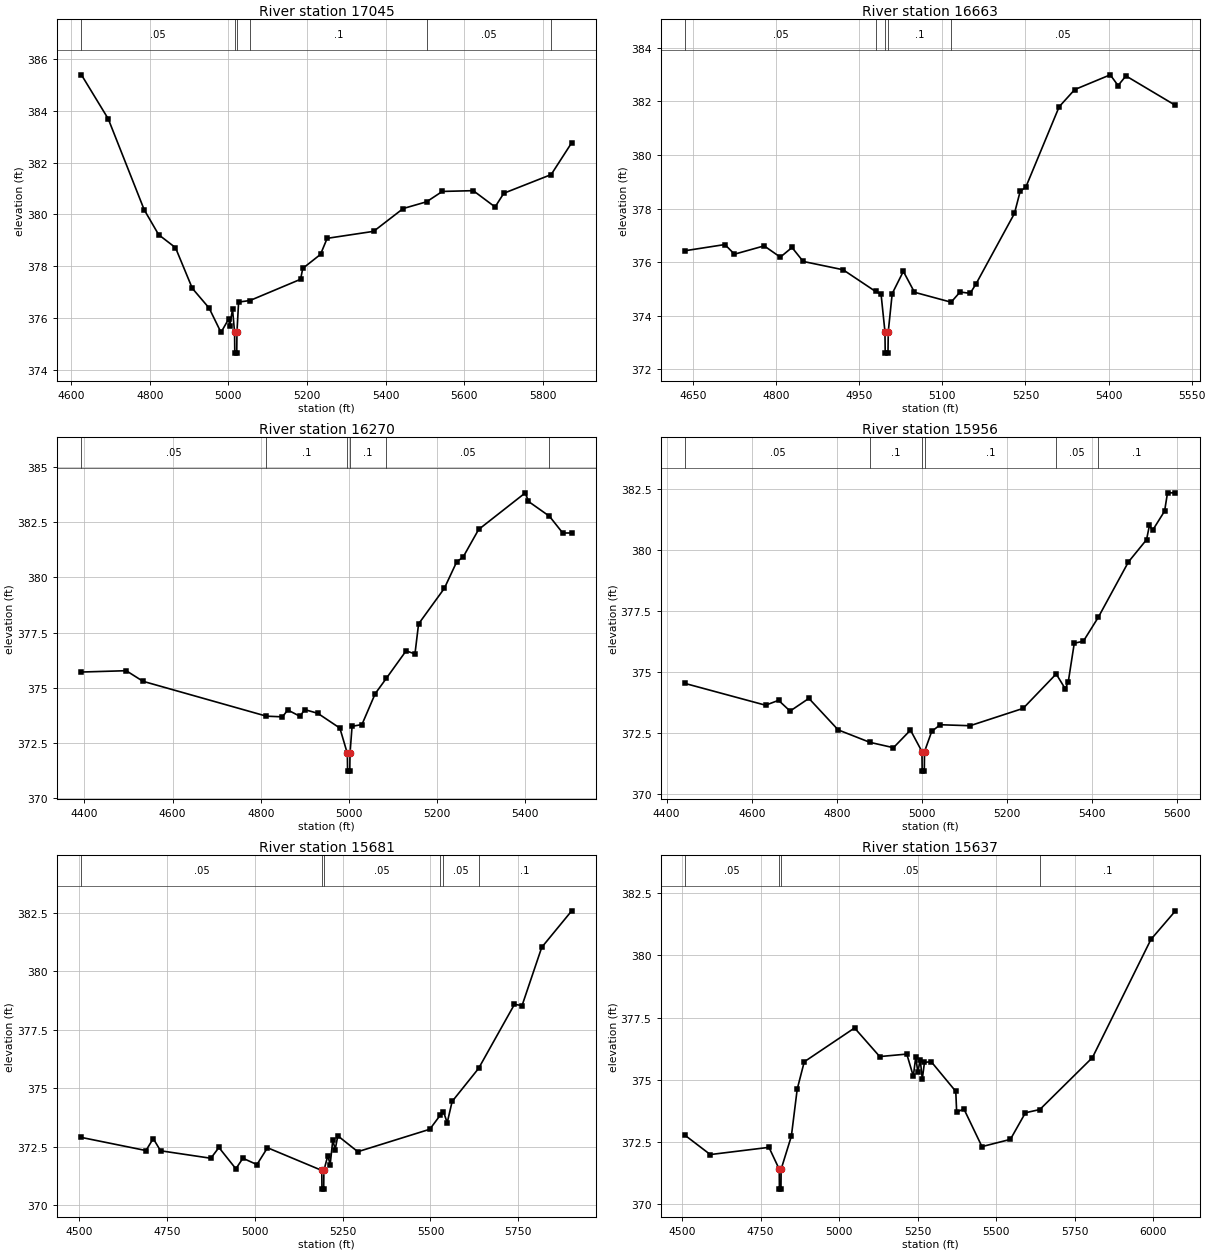
Type RM Length L Ch R = 1,17045,382,382,382
BEGIN DESCRIPTION:
UNT 69 in Lagunillas Cr Wtrshd 9.0
END DESCRIPTION:
XS GIS Cut Line= 3
      2068061.25     13447156.71      2068410.80     13447024.54
      2068027.77     13446239.83
#Sta/Elev= 30
  4626.3  385.39  4694.5  383.69  4786.0  380.18  4822.7  379.22  4865.5  378.72
  4908.3  377.15  4951.0  376.39  4981.2  375.45  5000.9  375.97  5003.4  375.71
  5010.6  376.34  5015.8  375.45  5016.3  374.65  5021.3  374.65  5021.8  375.45
  5026.0  376.62  5054.9  376.68  5183.6  377.50  5189.2  377.92  5234.3  378.46
  5251.2  379.08  5369.4  379.35  5444.6  380.23  5504.1  380.49  5544.1  380.89
  5622.8  380.92  5678.3  380.29  5700.5  380.82  5820.9  381.54  5873.2  382.77
#Mann=6,-1,0
  4626.3    0.05       0  5015.8    0.03       0  5021.8    0.05       0
  5054.9     0.1       0  5504.1    0.05       0  5820.9     0.1       0
Bank Sta=5015.8,5021.8
Exp/Cntr=0.3,0.1

Type RM Length L Ch R = 1,16663,393,393,393
BEGIN DESCRIPTION:
Mapping XS dc218a50
END DESCRIPTION:
XS GIS Cut Line= 4
      2068720.91     13447376.06      2068774.29     13447257.16
      2068722.20     13446708.55      2068583.67     13446559.63
#Sta/Elev= 30
  4636.0  376.43  4707.7  376.66  4724.9  376.30  4778.5  376.61  4807.7  376.19
  4828.8  376.55  4848.9  376.03  4920.9  375.72  4979.6  374.91  4989.5  374.81
  4996.5  373.41  4997.0  372.61  5002.0  372.61  5002.5  373.41  5009.6  374.83
  5029.7  375.66  5049.8  374.88  5115.9  374.51  5132.1  374.89  5150.2  374.84
  5160.3  375.17  5230.2  377.82  5240.6  378.65  5250.7  378.80  5310.9  381.80
  5339.0  382.44  5403.1  382.99  5417.2  382.59  5431.4  382.95  5520.8  381.85
#Mann=5,-1,0
  4636.0    0.05       0  4979.6     0.1       0  4996.5    0.07       0
  5002.5     0.1       0  5115.9    0.05       0
Bank Sta=4996.5,5002.5
Exp/Cntr=0.3,0.1

Type RM Length L Ch R = 1,16270,314,314,314
BEGIN DESCRIPTION:
Mapping XS 1c6f38eb
END DESCRIPTION:
XS GIS Cut Line= 4
      2068864.14     13447423.81      2069010.40     13447153.00
      2068979.15     13446680.77      2068746.52     13446444.67
#Sta/Elev= 30
  4393.1  375.71  4494.7  375.77  4532.8  375.29  4812.9  373.71  4849.2  373.68
  4861.3  373.99  4889.3  373.70  4899.3  374.01  4929.4  373.84  4979.5  373.17
  4996.5  372.02  4997.0  371.22  5002.0  371.22  5002.5  372.02  5007.2  373.25
  5029.6  373.33  5059.7  374.73  5084.8  375.42  5129.8  376.67  5149.9  376.53
  5158.1  377.89  5216.5  379.50  5244.8  380.71  5258.9  380.91  5294.4  382.17
  5400.4  383.83  5407.4  383.44  5455.0  382.77  5485.2  382.01  5505.6  382.01
#Mann=6,-1,0
  4393.1    0.05       0  4812.9     0.1       0  4996.5    0.07       0
  5002.5     0.1       0  5084.8    0.05       0  5455.0     0.1       0
Bank Sta=4996.5,5002.5
Exp/Cntr=0.3,0.1

Type RM Length L Ch R = 1,15956,275,275,275
BEGIN DESCRIPTION:
Mapping XS 23e42a6c
END DESCRIPTION:
XS GIS Cut Line= 4
      2069029.08     13447480.22      2069215.26     13447187.72
      2069215.26     13446802.30      2068923.56     13446500.19
#Sta/Elev= 30
  4443.6  374.52  4632.5  373.63  4663.0  373.83  4690.1  373.39  4734.3  373.91
  4803.0  372.62  4877.5  372.11  4933.0  371.89  4973.0  372.61  5000.0  371.73
  5000.5  370.93  5005.5  370.93  5006.0  371.73  5023.0  372.56  5043.0  372.83
  5113.0  372.79  5237.7  373.50  5315.4  374.91  5336.8  374.30  5343.7  374.58
  5357.9  376.17  5379.2  376.25  5414.3  377.23  5485.2  379.50  5527.7  380.41
  5534.6  381.00  5541.8  380.79  5570.1  381.58  5577.0  382.33  5595.7  382.33
#Mann=6,-1,0
  4443.6    0.05       0  4877.5     0.1       0  5000.0    0.07       0
  5006.0     0.1       0  5315.4    0.05       0  5414.3     0.1       0
Bank Sta=5000,5006
Exp/Cntr=0.3,0.1

Type RM Length L Ch R = 1,15681,44,44,44
BEGIN DESCRIPTION:
Mapping XS a4b2b22b
END DESCRIPTION:
XS GIS Cut Line= 4
      2069185.31     13447532.33      2069425.19     13447223.13
      2069426.28     13446936.67      2068950.02     13446400.03
#Sta/Elev= 30
  4506.6  372.89  4690.2  372.33  4711.0  372.84  4731.8  372.32  4874.9  372.00
  4897.9  372.46  4946.1  371.55  4966.1  372.00  5006.1  371.73  5036.1  372.45
  5190.6  371.48  5191.1  370.68  5196.1  370.68  5196.6  371.48  5207.8  372.11
  5214.5  371.73  5222.0  372.79  5228.7  372.37  5236.2  372.96  5293.1  372.28
  5498.0  373.24  5527.7  373.84  5536.9  373.99  5547.6  373.52  5561.6  374.43
  5636.8  375.84  5738.9  378.58  5760.6  378.53  5816.6  381.02  5901.9  382.58
#Mann=6,-1,0
  4506.6    0.05       0  5190.6    0.03       0  5196.6    0.05       0
  5527.7     0.1       0  5536.9    0.05       0  5636.8     0.1       0
Bank Sta=5190.6,5196.6
Exp/Cntr=0.3,0.1

Type RM Length L Ch R = 1,15637,53,53,53
BEGIN DESCRIPTION:
Mapping XS 91eff19e
END DESCRIPTION:
XS GIS Cut Line= 5
      2069254.75     13447536.68      2069464.25     13447243.74
      2069476.19     13446936.67      2069348.15     13446785.84
      2069191.19     13446108.89
#Sta/Elev= 30
  4510.3  372.76  4590.2  371.99  4776.9  372.28  4809.6  371.40  4810.1  370.60
  4815.1  370.60  4815.6  371.40  4848.2  372.73  4866.8  374.62  4889.2  375.72
  5049.3  377.08  5129.4  375.93  5215.5  376.03  5236.3  375.14  5244.0  375.91
  5250.6  375.31  5258.3  375.80  5264.9  375.03  5271.8  375.70  5293.5  375.72
  5371.4  374.53  5374.2  373.69  5397.0  373.83  5454.7  372.31  5545.2  372.60
  5593.0  373.67  5638.8  373.80  5806.3  375.89  5992.4  380.64  6070.5  381.79
#Mann=4,-1,0
  4510.3    0.05       0  4809.6    0.03       0  4815.6    0.05       0
  5638.8     0.1       0
Bank Sta=4809.6,4815.6
Exp/Cntr=0.3,0.1

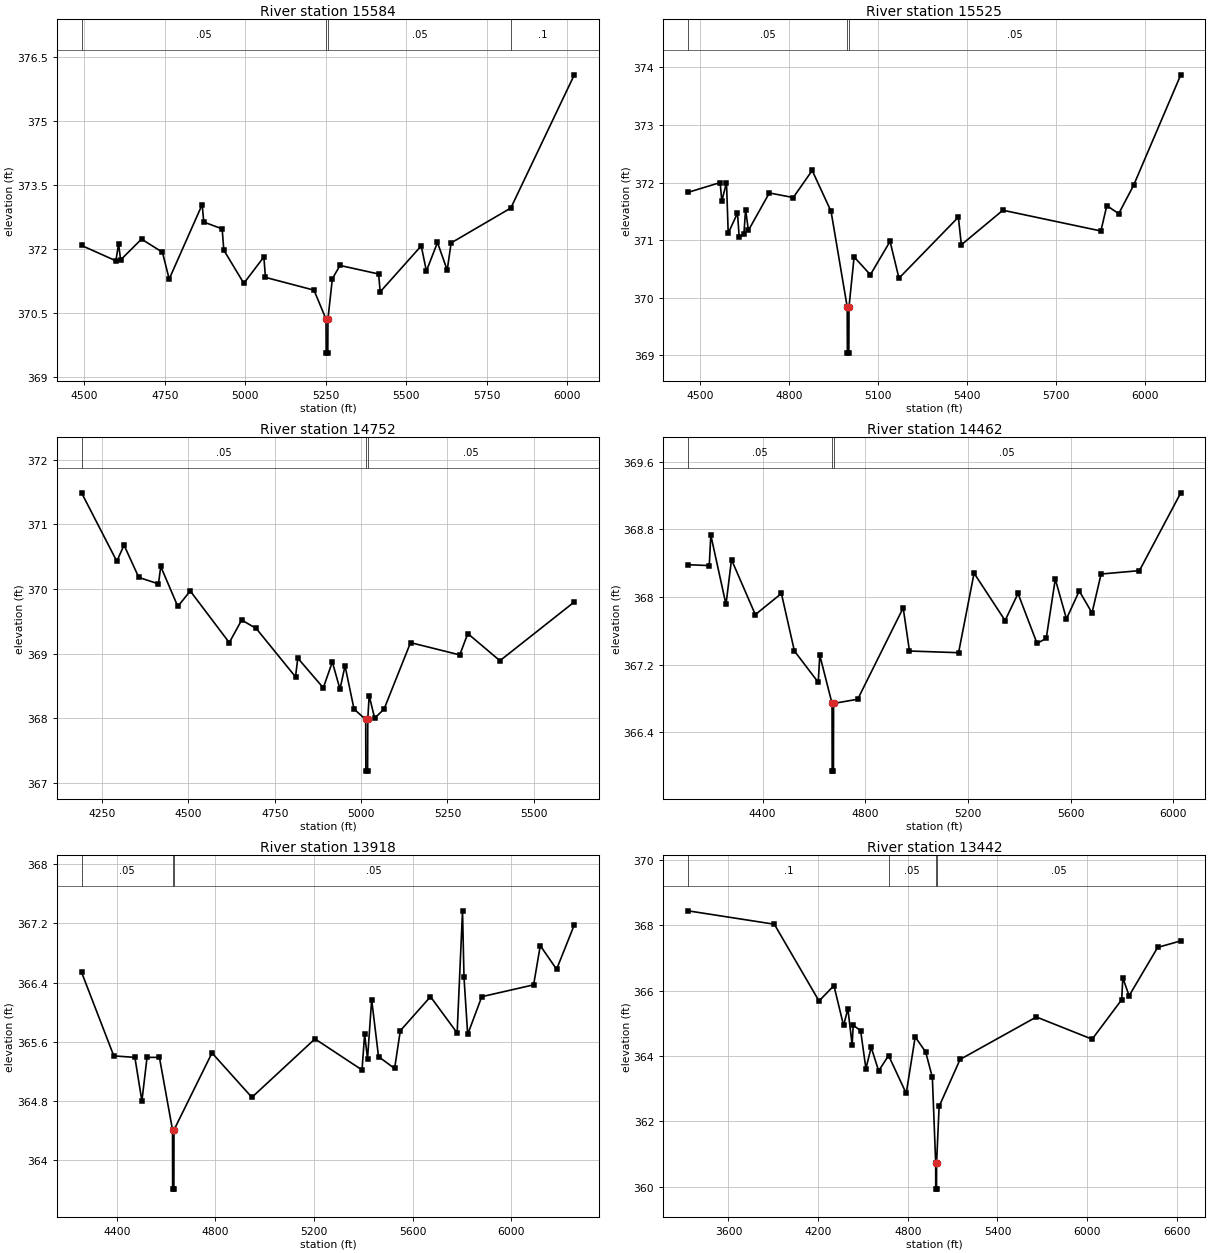
Type RM Length L Ch R = 1,15584,59,59,59
BEGIN DESCRIPTION:
Mapping XS 07f7d8da
END DESCRIPTION:
XS GIS Cut Line= 4
      2069300.40     13447550.26      2069492.47     13447283.89
      2069545.63     13446949.69      2069427.07     13446093.96
#Sta/Elev= 30
  4491.2  372.08  4597.8  371.72  4606.3  372.12  4612.5  371.74  4677.5  372.23
  4742.5  371.92  4763.4  371.29  4865.8  373.04  4870.9  372.63  4928.0  372.47
  4933.1  371.97  4995.3  371.19  5057.5  371.81  5062.5  371.33  5213.2  371.03
  5250.6  370.35  5251.1  369.55  5256.1  369.55  5256.6  370.35  5270.3  371.30
  5294.0  371.61  5413.9  371.41  5418.9  370.99  5546.4  372.07  5562.4  371.48
  5596.8  372.15  5627.1  371.50  5639.2  372.14  5824.7  372.96  6021.9  376.09
#Mann=4,-1,0
  4491.2    0.05       0  5250.6    0.03       0  5256.6    0.05       0
  5824.7     0.1       0
Bank Sta=5250.6,5256.6
Exp/Cntr=0.3,0.1

Type RM Length L Ch R = 1,15525,773,773,773
BEGIN DESCRIPTION:
Mapping XS c83833f5
END DESCRIPTION:
XS GIS Cut Line= 4
      2069363.24     13447580.11      2069554.31     13447256.76
      2069596.63     13446977.90      2069607.62     13445975.90
#Sta/Elev= 30
  4460.4  371.83  4568.5  372.00  4574.3  371.68  4590.0  372.00  4595.8  371.12
  4627.0  371.47  4632.8  371.05  4648.5  371.10  4654.3  371.53  4663.8  371.17
  4734.3  371.82  4814.8  371.74  4878.6  372.21  4942.2  371.50  4996.6  369.84
  4997.1  369.04  5002.1  369.04  5002.6  369.84  5019.8  370.71  5074.6  370.40
  5140.9  370.98  5170.9  370.34  5371.0  371.40  5381.0  370.92  5521.0  371.52
  5851.0  371.16  5871.0  371.60  5911.0  371.46  5961.0  371.95  6120.1  373.87
#Mann=3,-1,0
  4460.4    0.05       0  4996.6    0.03       0  5002.6    0.05       0
Bank Sta=4996.6,5002.6
Exp/Cntr=0.3,0.1

Type RM Length L Ch R = 1,14752,290,290,290
BEGIN DESCRIPTION:
Mapping XS c278da29
END DESCRIPTION:
XS GIS Cut Line= 4
      2069615.45     13447319.17      2070120.65     13446879.07
      2070177.94     13446709.80      2069943.18     13446181.63
#Sta/Elev= 30
  4190.7  371.49  4292.8  370.43  4313.7  370.68  4356.4  370.18  4413.4  370.08
  4420.0  370.35  4469.4  369.73  4505.4  369.97  4618.4  369.17  4654.3  369.52
  4696.3  369.39  4810.2  368.64  4816.8  368.93  4890.6  368.47  4916.8  368.87
  4938.9  368.45  4953.5  368.81  4979.7  368.14  5013.4  367.98  5013.9  367.18
  5018.9  367.18  5019.4  367.98  5023.4  368.35  5039.3  368.00  5066.5  368.14
  5143.2  369.17  5285.7  368.98  5309.0  369.31  5402.0  368.89  5617.4  369.80
#Mann=3,-1,0
  4190.7    0.05       0  5013.4    0.03       0  5019.4    0.05       0
Bank Sta=5013.4,5019.4
Exp/Cntr=0.3,0.1

Type RM Length L Ch R = 1,14462,544,544,544
BEGIN DESCRIPTION:
Mapping XS f46be642
END DESCRIPTION:
XS GIS Cut Line= 4
      2069862.42     13447797.06      2070215.26     13447281.47
      2070302.07     13446534.94      2069969.36     13446105.20
#Sta/Elev= 30
  4109.1  368.38  4191.9  368.37  4197.9  368.73  4257.0  367.91  4278.5  368.44
  4371.3  367.79  4472.9  368.04  4523.6  367.36  4616.4  366.99  4622.5  367.31
  4670.2  366.74  4670.7  365.94  4675.7  365.94  4676.2  366.74  4770.2  366.79
  4947.4  367.87  4971.9  367.36  5163.2  367.34  5223.6  368.28  5344.4  367.72
  5394.8  368.04  5468.9  367.45  5504.7  367.51  5540.0  368.21  5583.5  367.74
  5633.3  368.07  5683.1  367.81  5718.4  368.27  5867.8  368.31  6028.9  369.23
#Mann=3,-1,0
  4109.1    0.05       0  4670.2    0.03       0  4676.2    0.05       0
Bank Sta=4670.2,4676.2
Exp/Cntr=0.3,0.1

Type RM Length L Ch R = 1,13918,476,476,476
BEGIN DESCRIPTION:
Mapping XS 2c0a0b12
END DESCRIPTION:
XS GIS Cut Line= 4
      2070066.36     13448031.49      2070350.68     13447784.94
      2070753.03     13446983.30      2070350.52     13446379.54
#Sta/Elev= 30
  4257.2  366.54  4388.0  365.41  4473.5  365.39  4502.0  364.80  4522.8  365.39
  4573.1  365.39  4626.2  364.41  4626.7  363.61  4631.7  363.61  4632.2  364.41
  4786.3  365.45  4948.2  364.85  5204.1  365.64  5394.9  365.22  5405.5  365.70
  5417.3  365.37  5434.0  366.17  5461.9  365.40  5527.1  365.24  5550.2  365.75
  5672.7  366.21  5780.8  365.72  5802.6  367.37  5808.6  366.47  5823.6  365.70
  5880.7  366.21  6091.0  366.37  6118.1  366.90  6184.2  366.58  6256.1  367.18
#Mann=3,-1,0
  4257.2    0.05       0  4626.2    0.03       0  4632.2    0.05       0
Bank Sta=4626.2,4632.2
Exp/Cntr=0.3,0.1

Type RM Length L Ch R = 1,13442,756,756,756
BEGIN DESCRIPTION:
Mapping XS c9328395
END DESCRIPTION:
XS GIS Cut Line= 4
      2070058.56     13448837.50      2070937.48     13447687.72
      2070900.00     13446750.00      2070266.90     13446094.39
#Sta/Elev= 30
  3329.4  368.44  3906.7  368.03  4205.9  365.68  4305.7  366.15  4370.1  364.93
  4399.1  365.44  4427.6  364.33  4434.5  364.94  4484.3  364.77  4519.7  363.61
  4555.0  364.26  4604.9  363.54  4671.4  364.01  4789.4  362.85  4849.4  364.58
  4919.5  364.12  4964.3  363.34  4986.5  360.72  4987.0  359.92  4992.1  359.92
  4992.6  360.72  5009.5  362.45  5149.7  363.89  5660.1  365.19  6033.3  364.51
  6231.4  365.72  6238.4  366.39  6280.8  365.84  6471.9  367.32  6626.5  367.52
#Mann=4,-1,0
  3329.4     0.1       0  4671.4    0.05       0  4986.5    0.03       0
  4992.6    0.05       0
Bank Sta=4986.5,4992.6
Exp/Cntr=0.3,0.1

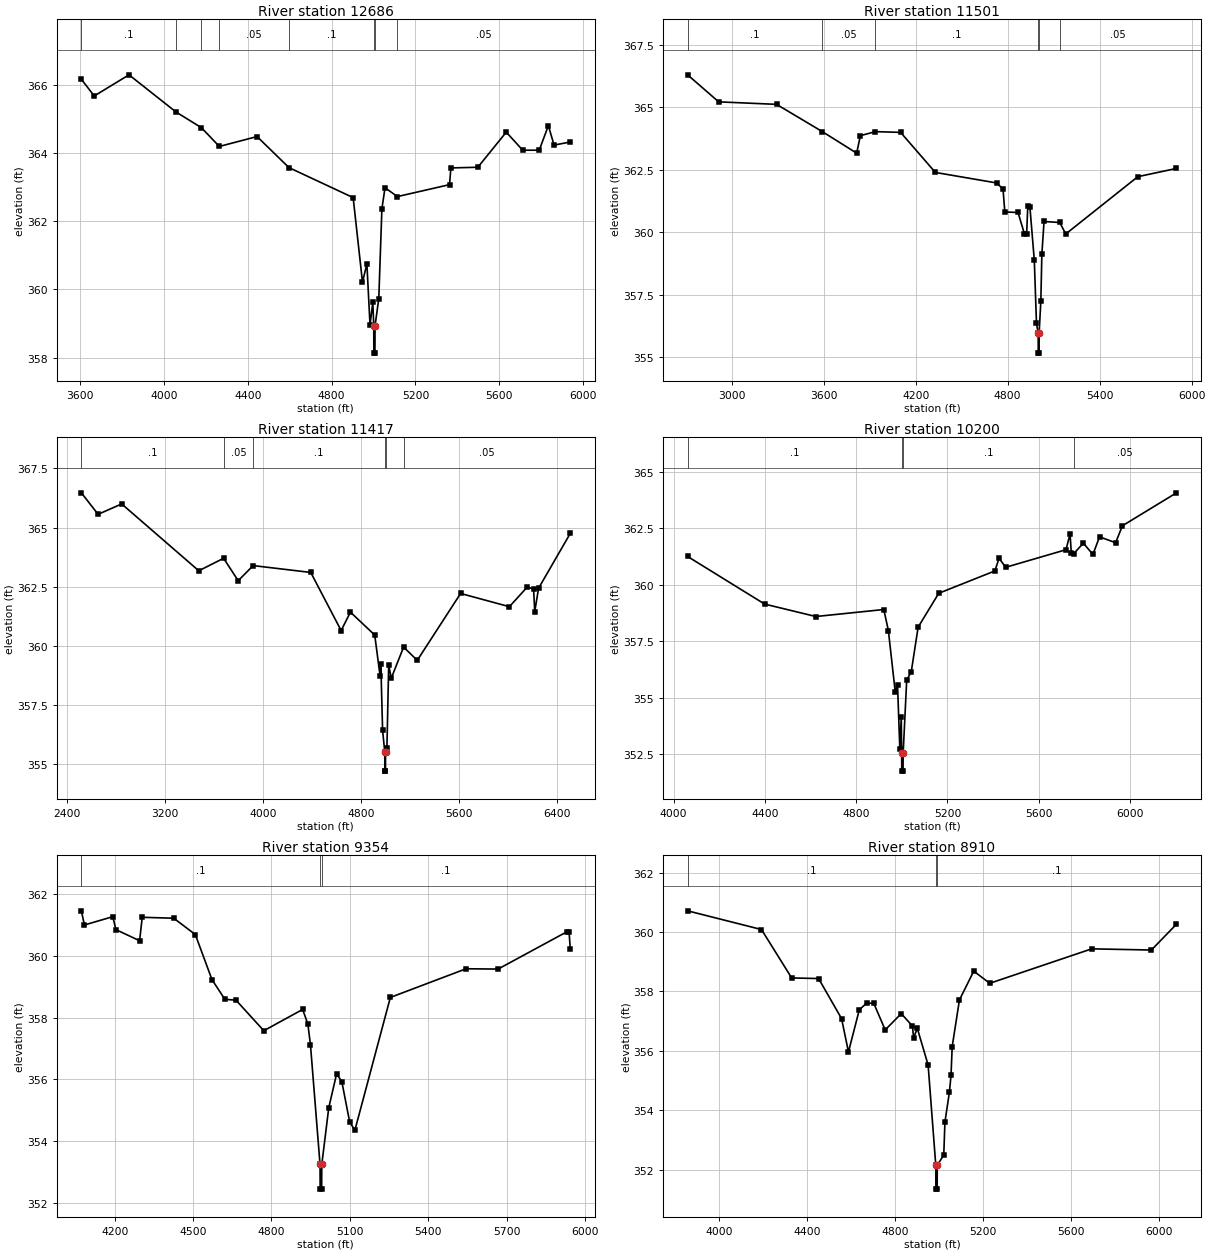
Type RM Length L Ch R = 1,12686,1185,1185,1185
BEGIN DESCRIPTION:
Mapping XS bc2e9536
END DESCRIPTION:
XS GIS Cut Line= 4
      2071294.71     13448392.99      2071628.45     13447434.25
      2071249.98     13446885.64      2070732.24     13446490.28
#Sta/Elev= 30
  3605.7  366.16  3667.1  365.67  3833.0  366.29  4057.5  365.20  4178.7  364.74
  4264.1  364.19  4444.2  364.48  4596.3  363.57  4902.7  362.69  4947.3  360.21
  4968.3  360.75  4983.2  358.96  4996.6  359.62  5001.1  358.93  5001.6  358.13
  5006.7  358.13  5007.2  358.93  5025.1  359.73  5039.9  362.36  5054.8  362.98
  5113.8  362.72  5362.7  363.07  5369.1  363.56  5497.8  363.58  5633.4  364.61
  5711.9  364.08  5790.8  364.08  5834.4  364.80  5861.5  364.23  5938.8  364.32
#Mann=8,-1,0
  3605.7     0.1       0  4057.5    0.05       0  4178.7    0.08       0
  4264.1    0.05       0  4596.3     0.1       0  5001.1    0.07       0
  5007.2     0.1       0  5113.8    0.05       0
Bank Sta=5001.1,5007.2
Exp/Cntr=0.3,0.1

Type RM Length L Ch R = 1,11501,84,84,84
BEGIN DESCRIPTION:
Mapping XS 8fc58f81
END DESCRIPTION:
XS GIS Cut Line= 4
      2071426.64     13448393.04      2072221.76     13446428.20
      2072026.45     13446251.12      2071238.06     13446416.47
#Sta/Elev= 30
  2712.4  366.29  2915.3  365.21  3292.8  365.11  3591.4  364.02  3815.2  363.16
  3839.3  363.86  3938.0  364.02  4101.9  363.99  4328.5  362.39  4727.6  361.97
  4769.7  361.73  4781.5  360.81  4867.7  360.79  4909.6  359.93  4923.8  359.93
  4931.2  361.04  4945.4  360.99  4973.8  358.88  4988.0  356.36  4999.1  355.97
  4999.6  355.17  5004.8  355.17  5005.3  355.97  5016.4  357.24  5023.1  359.12
  5037.3  360.43  5140.0  360.39  5178.9  359.93  5648.9  362.22  5901.2  362.55
#Mann=6,-1,0
  2712.4     0.1       0  3591.4    0.05       0  3938.0     0.1       0
  4999.1    0.07       0  5005.3     0.1       0  5140.0    0.05       0
Bank Sta=4999.1,5005.3
Exp/Cntr=0.3,0.1

Type RM Length L Ch R = 1,11417,1217,1217,1217
BEGIN DESCRIPTION:
Mapping XS b751a36b
END DESCRIPTION:
XS GIS Cut Line= 4
      2071500.01     13448449.98      2072329.42     13446406.91
      2071984.78     13446139.14      2070648.86     13446330.52
#Sta/Elev= 30
  2518.0  366.47  2654.6  365.56  2847.1  366.00  3476.8  363.17  3679.1  363.70
  3798.2  362.75  3920.5  363.39  4390.5  363.10  4638.7  360.64  4714.3  361.42
  4912.9  360.45  4956.3  358.73  4962.7  359.21  4977.1  356.42  4994.9  355.49
  4995.4  354.69  5000.6  354.69  5001.1  355.49  5012.4  355.67  5026.9  359.19
  5047.7  358.62  5148.5  359.94  5260.2  359.38  5613.8  362.21  6012.3  361.65
  6159.3  362.49  6209.8  362.39  6219.1  361.44  6250.2  362.43  6509.0  364.75
#Mann=6,-1,0
  2518.0     0.1       0  3679.1    0.05       0  3920.5     0.1       0
  4994.9    0.07       0  5001.1     0.1       0  5148.5    0.05       0
Bank Sta=4994.9,5001.1
Exp/Cntr=0.3,0.1

Type RM Length L Ch R = 1,10200,846,846,846
BEGIN DESCRIPTION:
Mapping XS 694d5c6d
END DESCRIPTION:
XS GIS Cut Line= 4
      2072885.40     13445368.28      2072687.48     13445177.30
      2071774.29     13445250.22      2070899.60     13445621.61
#Sta/Elev= 30
  4061.7  361.25  4399.4  359.14  4623.5  358.59  4921.1  358.90  4941.1  357.97
  4971.2  355.25  4981.3  355.54  4991.3  352.74  4997.6  354.14  4999.3  352.54
  4999.8  351.74  5005.4  351.74  5005.9  352.54  5021.4  355.77  5041.5  356.15
  5071.5  358.12  5161.8  359.62  5407.7  360.61  5425.9  361.17  5455.0  360.77
  5719.2  361.55  5737.0  362.25  5742.4  361.40  5752.4  361.37  5795.3  361.84
  5837.0  361.34  5866.1  362.12  5936.5  361.86  5966.2  362.61  6203.1  364.07
#Mann=4,-1,0
  4061.7     0.1       0  4999.3    0.07       0  5005.9     0.1       0
  5752.4    0.05       0
Bank Sta=4999.3,5005.9
Exp/Cntr=0.3,0.1

Type RM Length L Ch R = 1,9354,444,444,444
BEGIN DESCRIPTION:
Mapping XS 95381cb9
END DESCRIPTION:
XS GIS Cut Line= 5
      2072923.59     13445326.57      2072878.45     13444920.36
      2072680.54     13444691.19      2072208.32     13444684.25
      2071653.11     13445090.24
#Sta/Elev= 30
  4072.2  361.47  4083.8  361.01  4192.4  361.28  4204.6  360.86  4295.1  360.50
  4305.2  361.26  4425.9  361.23  4508.5  360.70  4572.1  359.24  4621.5  358.60
  4664.3  358.57  4770.7  357.58  4919.3  358.27  4939.3  357.80  4949.3  357.12
  4985.9  353.24  4986.4  352.44  4992.1  352.44  4992.6  353.24  5019.3  355.08
  5049.3  356.18  5069.3  355.93  5099.3  354.62  5119.3  354.35  5255.1  358.66
  5545.0  359.59  5667.5  359.58  5930.9  360.79  5939.3  360.79  5943.8  360.24
#Mann=3,-1,0
  4072.2     0.1       0  4985.9    0.07       0  4992.6     0.1       0
Bank Sta=4985.9,4992.6
Exp/Cntr=0.3,0.1

Type RM Length L Ch R = 1,8910,553,553,553
BEGIN DESCRIPTION:
Mapping XS 59eb6040
END DESCRIPTION:
XS GIS Cut Line= 4
      2073479.15     13444937.73      2073399.29     13444649.52
      2072475.68     13444371.75      2071702.18     13444940.60
#Sta/Elev= 30
  3855.2  360.71  4191.3  360.08  4328.6  358.45  4451.1  358.43  4555.6  357.08
  4586.9  355.96  4636.3  357.38  4669.3  357.60  4701.8  357.60  4754.0  356.70
  4827.1  357.25  4877.9  356.83  4883.1  356.44  4900.2  356.75  4949.2  355.52
  4984.1  352.14  4984.6  351.34  4990.3  351.34  4990.8  352.14  5020.4  352.49
  5025.7  353.60  5046.4  354.62  5053.5  355.19  5058.7  356.14  5091.7  357.71
  5156.8  358.68  5229.5  358.27  5693.2  359.43  5964.8  359.39  6078.9  360.26
#Mann=3,-1,0
  3855.2     0.1       0  4984.1    0.07       0  4990.8     0.1       0
Bank Sta=4984.1,4990.8
Exp/Cntr=0.3,0.1

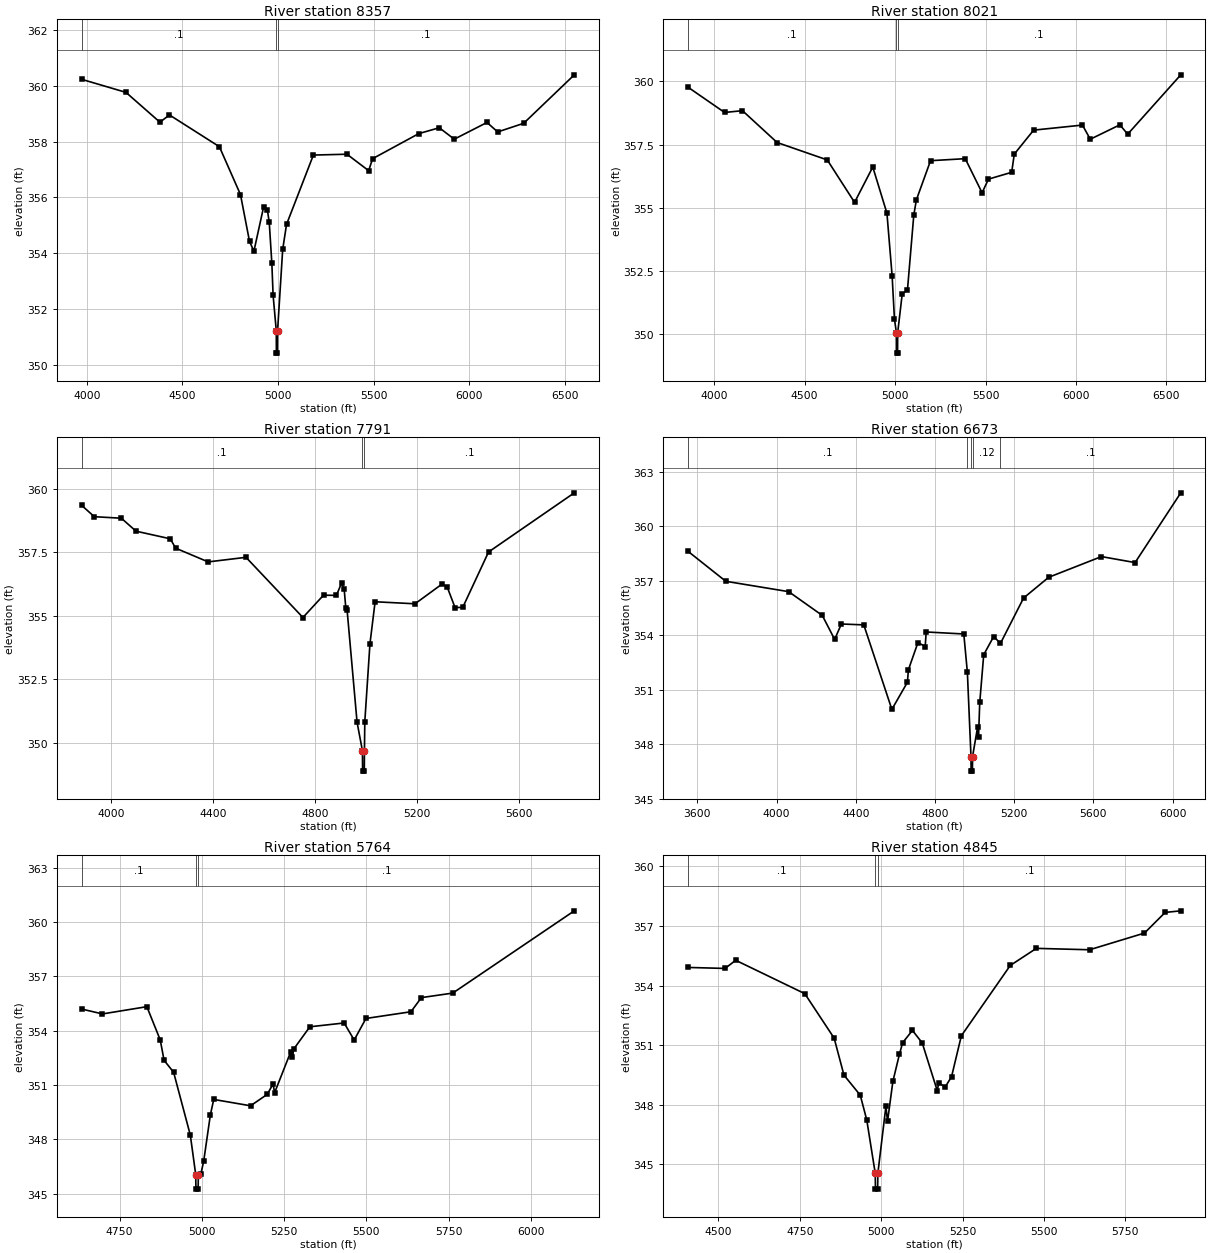
Type RM Length L Ch R = 1,8357,336,336,336
BEGIN DESCRIPTION:
Mapping XS 32280d74
END DESCRIPTION:
XS GIS Cut Line= 4
      2073572.90     13444663.41      2073229.15     13444045.36
      2072680.54     13443996.75      2071649.67     13444822.83
#Sta/Elev= 30
  3971.8  360.24  4204.3  359.77  4381.9  358.70  4431.9  358.96  4693.2  357.82
  4803.6  356.10  4850.9  354.42  4873.9  354.07  4924.1  355.64  4944.2  355.56
  4954.2  355.10  4967.8  353.63  4974.3  352.49  4991.0  351.21  4991.5  350.41
  4997.2  350.41  4997.7  351.21  5024.5  354.13  5044.6  355.03  5185.1  357.52
  5360.8  357.55  5474.4  356.96  5495.2  357.39  5736.9  358.29  5844.1  358.50
  5922.5  358.09  6093.8  358.69  6149.8  358.35  6285.8  358.66  6550.8  360.40
#Mann=3,-1,0
  3971.8     0.1       0  4991.0    0.07       0  4997.7     0.1       0
Bank Sta=4991,4997.7
Exp/Cntr=0.3,0.1

Type RM Length L Ch R = 1,8021,230,230,230
BEGIN DESCRIPTION:
Mapping XS 0e71f1d4
END DESCRIPTION:
XS GIS Cut Line= 5
      2073722.19     13444291.86      2073222.20     13443691.19
      2072993.04     13443653.00      2072673.59     13443916.89
      2071656.25     13444718.96
#Sta/Elev= 30
  3855.6  359.77  4057.7  358.77  4156.6  358.84  4348.0  357.58  4625.3  356.89
  4776.2  355.21  4876.9  356.61  4955.1  354.78  4983.7  352.31  4996.7  350.58
  5007.7  350.04  5008.2  349.24  5013.9  349.24  5014.4  350.04  5039.7  351.59
  5068.4  351.73  5103.6  354.71  5117.9  355.31  5196.1  356.86  5388.0  356.94
  5481.0  355.59  5516.3  356.13  5644.6  356.40  5659.0  357.12  5765.9  358.07
  6035.8  358.27  6079.1  357.71  6242.6  358.28  6285.9  357.91  6579.3  360.26
#Mann=3,-1,0
  3855.6     0.1       0  5007.7    0.07       0  5014.4     0.1       0
Bank Sta=5007.7,5014.4
Exp/Cntr=0.3,0.1

Type RM Length L Ch R = 1,7791,1118,1118,1118
BEGIN DESCRIPTION:
Mapping XS 498465c1
END DESCRIPTION:
XS GIS Cut Line= 5
      2073718.72     13444159.91      2073642.34     13444003.69
      2073243.04     13443604.39      2072409.70     13443479.39
      2072062.44     13443531.48
#Sta/Elev= 30
  3885.0  359.35  3935.0  358.90  4041.1  358.84  4098.5  358.33  4232.9  358.03
  4254.1  357.66  4381.4  357.12  4529.9  357.30  4753.1  354.93  4834.0  355.81
  4884.5  355.80  4904.7  356.29  4914.9  356.04  4921.4  355.30  4926.4  355.22
  4965.4  350.81  4986.5  349.68  4987.2  348.88  4993.8  348.88  4994.4  349.68
  4995.8  350.83  5016.0  353.90  5036.2  355.55  5192.7  355.47  5299.1  356.25
  5319.3  356.12  5349.7  355.32  5380.0  355.33  5481.1  357.51  5817.4  359.84
#Mann=3,-1,0
  3885.0     0.1       0  4986.5    0.07       0  4994.4     0.1       0
Bank Sta=4986.5,4994.4
Exp/Cntr=0.3,0.1

Type RM Length L Ch R = 1,6673,909,909,909
BEGIN DESCRIPTION:
Mapping XS c7f4deb5
END DESCRIPTION:
XS GIS Cut Line= 4
      2073791.63     13443753.65      2073333.32     13442795.36
      2072534.70     13442705.08      2071918.30     13442791.65
#Sta/Elev= 30
  3552.8  358.63  3743.6  356.98  4061.1  356.41  4230.9  355.10  4293.3  353.78
  4327.2  354.63  4440.5  354.58  4582.2  349.93  4660.7  351.42  4665.7  352.11
  4714.0  353.61  4750.5  353.39  4755.5  354.19  4945.5  354.08  4963.5  351.97
  4981.8  347.33  4982.4  346.53  4989.0  346.53  4989.7  347.33  5014.9  348.94
  5019.9  348.43  5026.0  350.31  5046.1  352.94  5096.4  353.94  5130.5  353.56
  5247.4  356.06  5374.1  357.20  5640.6  358.34  5810.4  358.01  6041.2  361.85
#Mann=5,-1,0
  3552.8     0.1       0  4963.5    0.12       0  4981.8    0.07       0
  4989.7    0.12       0  5130.5     0.1       0
Bank Sta=4981.8,4989.7
Exp/Cntr=0.3,0.1

Type RM Length L Ch R = 1,5764,919,919,919
BEGIN DESCRIPTION:
Mapping XS b09aa806
END DESCRIPTION:
XS GIS Cut Line= 4
      2073437.47     13442267.54      2073402.76     13442080.08
      2072635.40     13441941.19      2072124.95     13442073.14
#Sta/Elev= 30
  4634.6  355.20  4698.2  354.93  4833.1  355.33  4873.8  353.49  4885.4  352.37
  4914.4  351.71  4965.2  348.24  4981.6  346.06  4982.2  345.26  4988.9  345.26
  4989.6  346.06  4997.5  346.12  5005.9  346.81  5026.2  349.37  5036.4  350.21
  5148.2  349.86  5199.0  350.49  5216.5  351.06  5221.6  350.59  5270.0  352.82
  5275.0  352.58  5280.3  353.01  5328.5  354.22  5432.7  354.43  5463.2  353.49
  5499.1  354.68  5635.8  355.05  5667.5  355.83  5762.9  356.08  6132.3  360.62
#Mann=3,-1,0
  4634.6     0.1       0  4981.6    0.07       0  4989.6     0.1       0
Bank Sta=4981.6,4989.6
Exp/Cntr=0.3,0.1

Type RM Length L Ch R = 1,4845,764,764,764
BEGIN DESCRIPTION:
Mapping XS 122581cb
END DESCRIPTION:
XS GIS Cut Line= 4
      2073628.44     13441507.12      2073565.95     13441257.16
      2072545.12     13441323.14      2072374.96     13441482.88
#Sta/Elev= 30
  4406.5  354.91  4520.3  354.86  4553.0  355.27  4765.3  353.59  4855.5  351.35
  4885.6  349.49  4935.7  348.48  4955.7  347.23  4981.7  344.55  4982.4  343.75
  4989.1  343.75  4989.8  344.55  5014.5  347.91  5019.5  347.16  5035.9  349.17
  5055.9  350.53  5065.9  351.12  5096.0  351.74  5126.1  351.11  5172.2  348.71
  5177.2  349.11  5196.2  348.88  5216.2  349.41  5246.3  351.47  5396.6  355.01
  5476.8  355.87  5640.3  355.80  5808.9  356.64  5872.5  357.68  5920.5  357.76
#Mann=3,-1,0
  4406.5     0.1       0  4981.7    0.07       0  4989.8     0.1       0
Bank Sta=4981.7,4989.8
Exp/Cntr=0.3,0.1

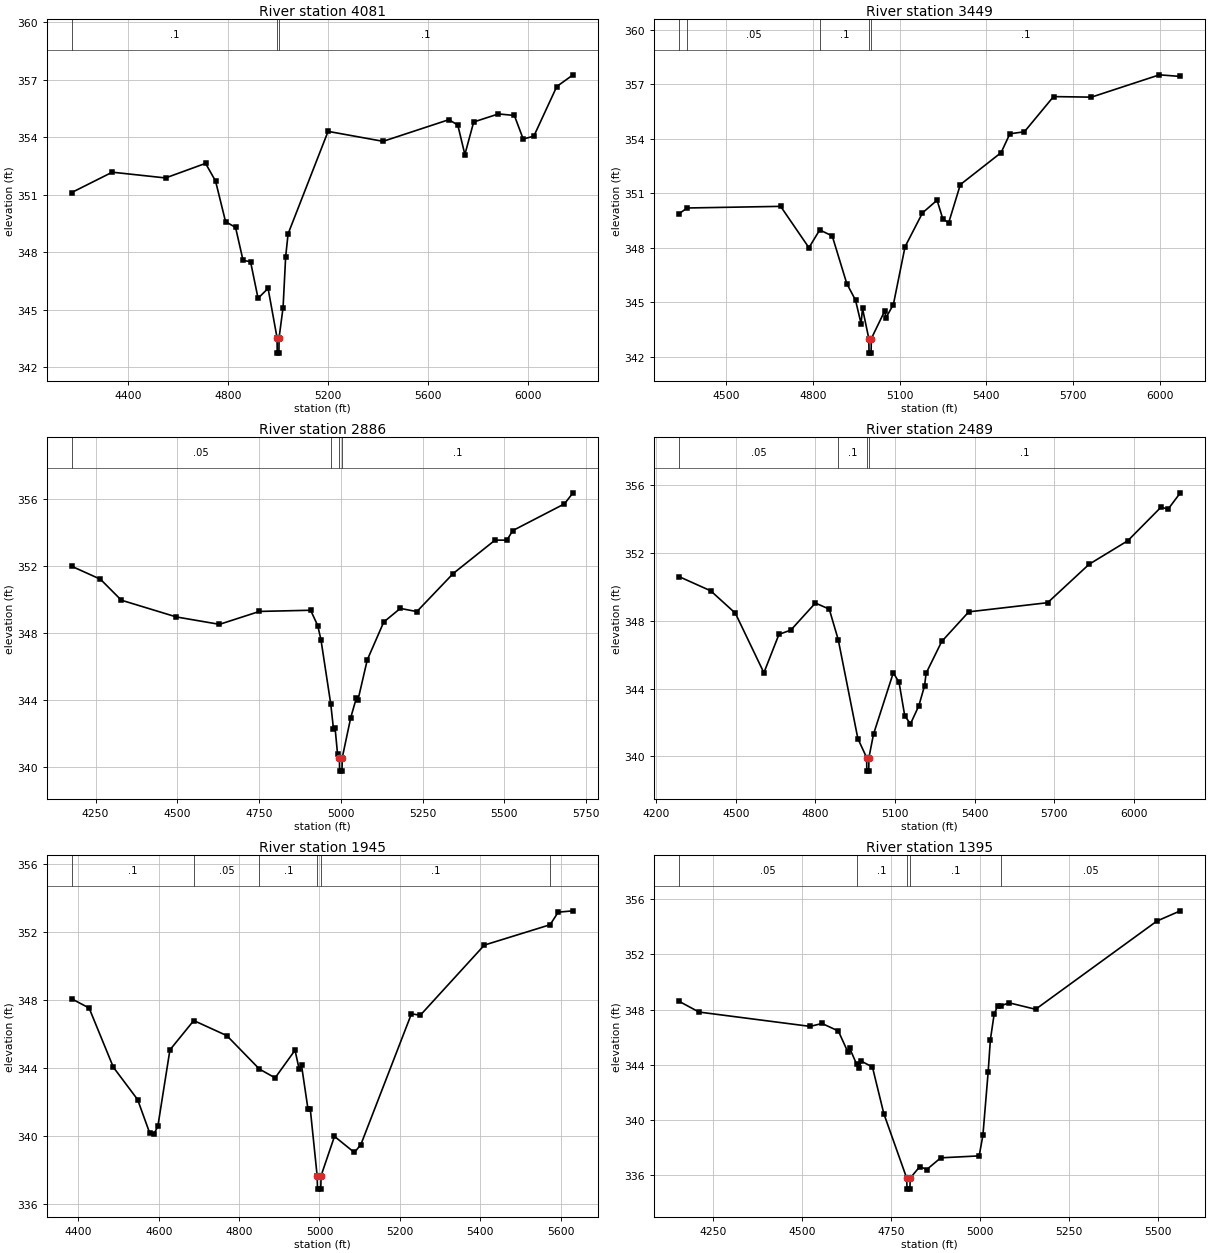
Type RM Length L Ch R = 1,4081,632,632,632
BEGIN DESCRIPTION:
Mapping XS 9b08e154
END DESCRIPTION:
XS GIS Cut Line= 4
      2073902.78     13440882.20      2073760.40     13440653.00
      2072673.59     13440628.69      2072204.81     13441076.64
#Sta/Elev= 30
  4174.4  351.12  4336.5  352.18  4549.7  351.88  4709.7  352.64  4749.7  351.72
  4789.7  349.60  4829.7  349.30  4859.7  347.58  4889.7  347.51  4919.7  345.60
  4959.8  346.12  4995.7  343.54  4996.4  342.74  5003.1  342.74  5003.8  343.54
  5019.8  345.12  5030.1  347.76  5039.8  348.96  5199.8  354.31  5419.9  353.79
  5683.2  354.92  5718.7  354.64  5747.0  353.10  5782.3  354.80  5881.3  355.22
  5944.9  355.14  5980.4  353.91  6022.9  354.06  6114.7  356.65  6179.7  357.26
#Mann=3,-1,0
  4174.4     0.1       0  4995.7    0.07       0  5003.8     0.1       0
Bank Sta=4995.7,5003.8
Exp/Cntr=0.3,0.1

Type RM Length L Ch R = 1,3449,563,563,563
BEGIN DESCRIPTION:
Mapping XS e5649da8
END DESCRIPTION:
XS GIS Cut Line= 4
      2073930.52     13440507.13      2073774.29     13440194.66
      2072812.48     13440076.61      2072434.25     13440250.11
#Sta/Elev= 30
  4336.7  349.87  4364.4  350.19  4688.2  350.28  4786.1  348.00  4823.4  348.98
  4866.7  348.65  4917.1  346.02  4947.3  345.11  4966.5  343.81  4971.5  344.65
  4993.3  342.99  4994.1  342.19  5001.2  342.19  5002.0  342.99  5047.8  344.50
  5052.9  344.15  5078.3  344.87  5118.6  348.05  5179.0  349.92  5229.4  350.62
  5249.5  349.58  5269.7  349.38  5310.0  351.48  5451.0  353.24  5481.3  354.28
  5531.6  354.39  5632.4  356.33  5763.5  356.30  5998.9  357.53  6071.2  357.44
#Mann=5,-1,0
  4336.7     0.1       0  4364.4    0.05       0  4823.4     0.1       0
  4993.3    0.07       0  5002.0     0.1       0
Bank Sta=4993.3,5002
Exp/Cntr=0.3,0.1

Type RM Length L Ch R = 1,2886,397,397,397
BEGIN DESCRIPTION:
Mapping XS 704c589a
END DESCRIPTION:
XS GIS Cut Line= 4
      2074166.65     13440323.14      2073854.15     13439809.25
      2073166.65     13439708.55      2072948.99     13439801.84
#Sta/Elev= 30
  4177.2  351.99  4264.9  351.22  4328.9  349.97  4497.4  348.97  4629.1  348.53
  4751.3  349.30  4907.8  349.37  4929.4  348.46  4939.5  347.60  4969.5  343.76
  4977.7  342.29  4982.7  342.33  4990.0  340.82  4995.8  340.58  4996.5  339.78
  5003.7  339.78  5004.5  340.58  5030.5  342.97  5047.5  344.13  5052.6  344.02
  5081.0  346.41  5131.5  348.67  5182.1  349.48  5232.6  349.29  5343.8  351.56
  5471.8  353.55  5508.0  353.55  5526.1  354.12  5683.8  355.71  5710.3  356.37
#Mann=4,-1,0
  4177.2    0.05       0  4969.5     0.1       0  4995.8    0.07       0
  5004.5     0.1       0
Bank Sta=4995.8,5004.5
Exp/Cntr=0.3,0.1

Type RM Length L Ch R = 1,2489,544,544,544
BEGIN DESCRIPTION:
Mapping XS 0d27fcf0
END DESCRIPTION:
XS GIS Cut Line= 4
      2074249.99     13439955.08      2073951.37     13439521.05
      2073385.40     13439194.66      2072704.87     13439392.57
#Sta/Elev= 30
  4286.4  350.61  4405.8  349.77  4498.5  348.45  4606.1  344.93  4662.9  347.20
  4707.5  347.45  4800.2  349.05  4852.4  348.69  4886.3  346.88  4960.2  341.04
  4993.2  339.92  4993.9  339.12  5001.1  339.12  5001.9  339.92  5019.1  341.30
  5093.7  344.93  5115.3  344.37  5136.8  342.39  5158.4  341.91  5189.9  342.98
  5211.5  344.16  5217.3  344.90  5276.2  346.78  5378.1  348.53  5675.3  349.07
  5831.5  351.34  5977.3  352.73  6102.3  354.71  6129.3  354.60  6175.3  355.56
#Mann=4,-1,0
  4286.4    0.05       0  4886.3     0.1       0  4993.2    0.07       0
  5001.9     0.1       0
Bank Sta=4993.2,5001.9
Exp/Cntr=0.3,0.1

Type RM Length L Ch R = 1,1945,550,550,550
BEGIN DESCRIPTION:
Mapping XS f690d2b0
END DESCRIPTION:
XS GIS Cut Line= 4
      2074295.12     13439527.96      2074256.93     13439170.36
      2073798.59     13438923.83      2073438.72     13438851.16
#Sta/Elev= 30
  4383.6  348.07  4426.8  347.53  4487.1  344.04  4547.5  342.13  4577.7  340.15
  4587.7  340.08  4597.8  340.55  4627.9  345.06  4687.2  346.79  4769.5  345.90
  4850.5  343.93  4889.6  343.41  4939.1  345.04  4949.6  343.91  4955.3  344.15
  4971.5  341.55  4977.2  341.55  4994.1  337.65  4995.1  336.85  5003.1  336.85
  5004.1  337.65  5037.3  339.96  5086.8  339.01  5103.0  339.48  5228.8  347.19
  5250.7  347.10  5410.2  351.24  5573.8  352.44  5593.8  353.18  5630.8  353.26
#Mann=6,-1,0
  4383.6     0.1       0  4687.2    0.05       0  4850.5     0.1       0
  4994.1    0.07       0  5004.1     0.1       0  5573.8    0.05       0
Bank Sta=4994.1,5004.1
Exp/Cntr=0.3,0.1

Type RM Length L Ch R = 1,1395,608,608,608
BEGIN DESCRIPTION:
Mapping XS cf6b5f30
END DESCRIPTION:
XS GIS Cut Line= 4
      2074784.73     13439014.14      2074552.07     13438722.44
      2073920.12     13438517.58      2073549.27     13438517.58
#Sta/Elev= 30
  4155.2  348.60  4211.3  347.82  4523.5  346.78  4556.8  346.99  4602.6  346.45
  4629.3  344.93  4634.6  345.19  4654.4  344.02  4661.3  343.74  4666.6  344.27
  4698.5  343.83  4730.5  340.45  4794.7  335.78  4795.7  334.98  4803.7  334.98
  4804.7  335.78  4831.7  336.62  4851.1  336.40  4890.4  337.25  4998.3  337.39
  5008.8  338.88  5023.6  343.48  5029.8  345.81  5040.3  347.65  5050.3  348.27
  5060.3  348.28  5082.3  348.49  5156.8  348.02  5497.8  354.42  5563.5  355.16
#Mann=5,-1,0
  4155.2    0.05       0  4654.4     0.1       0  4794.7    0.07       0
  4804.7     0.1       0  5060.3    0.05       0
Bank Sta=4794.7,4804.7
Exp/Cntr=0.3,0.1