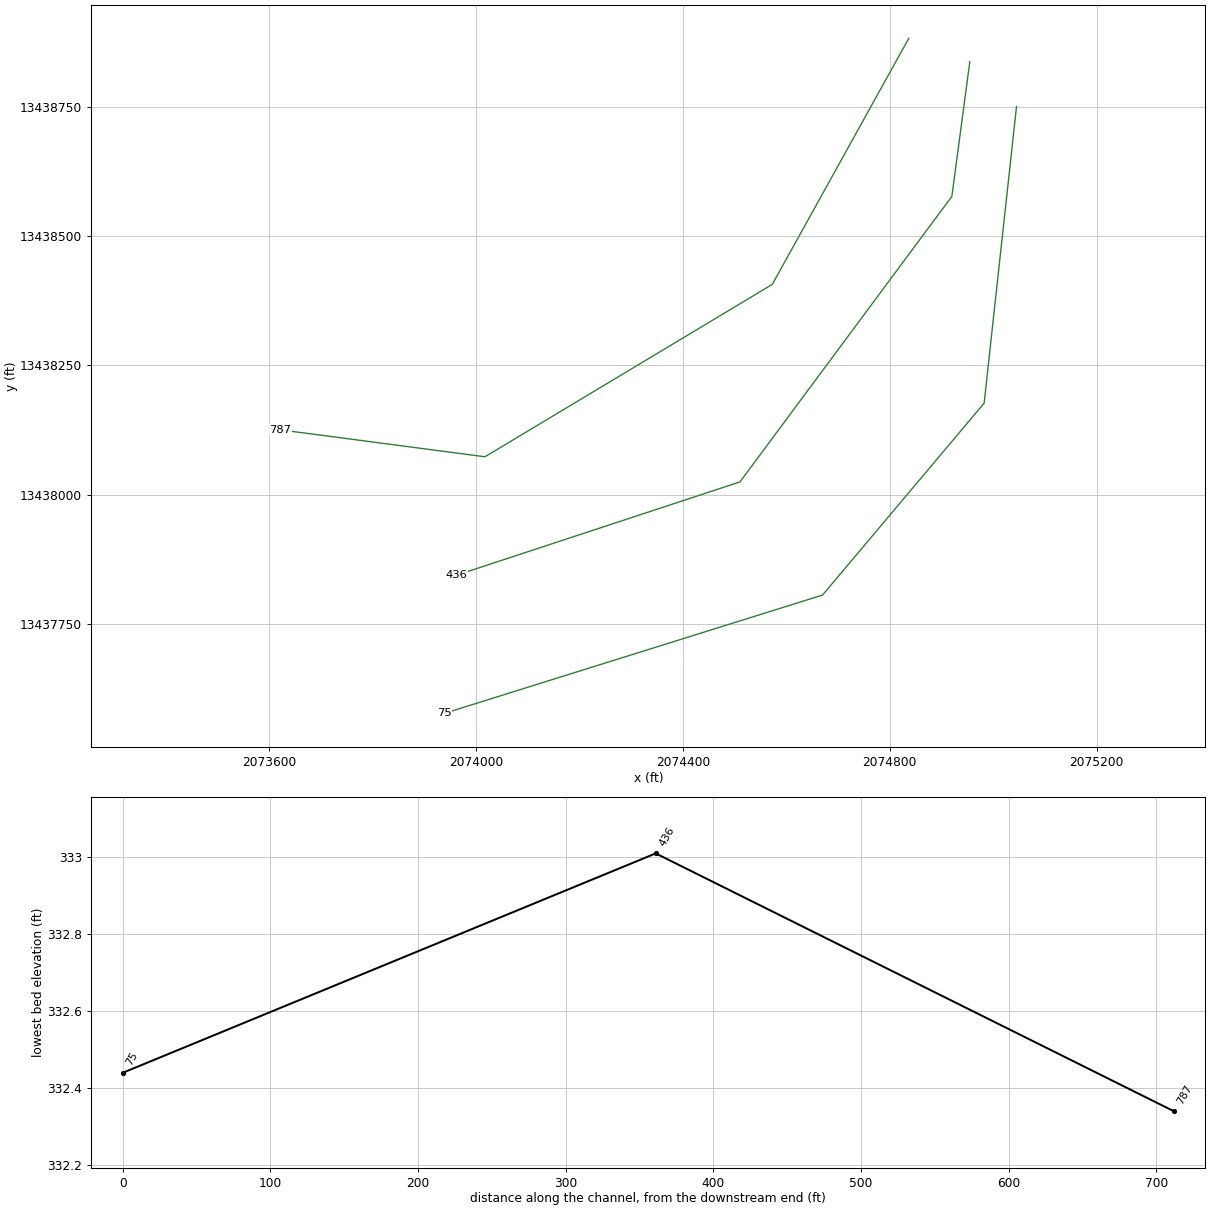
HEC-RAS study UNT 69 in Lagunillas Cr Wtrshd.prj: UNT 69 in Lagunillas Cr Wtrshd Base Level Engineering

--- UNT 69 in Lagunillas Cr Wtrshd.g01 (geometry) --- (continued)

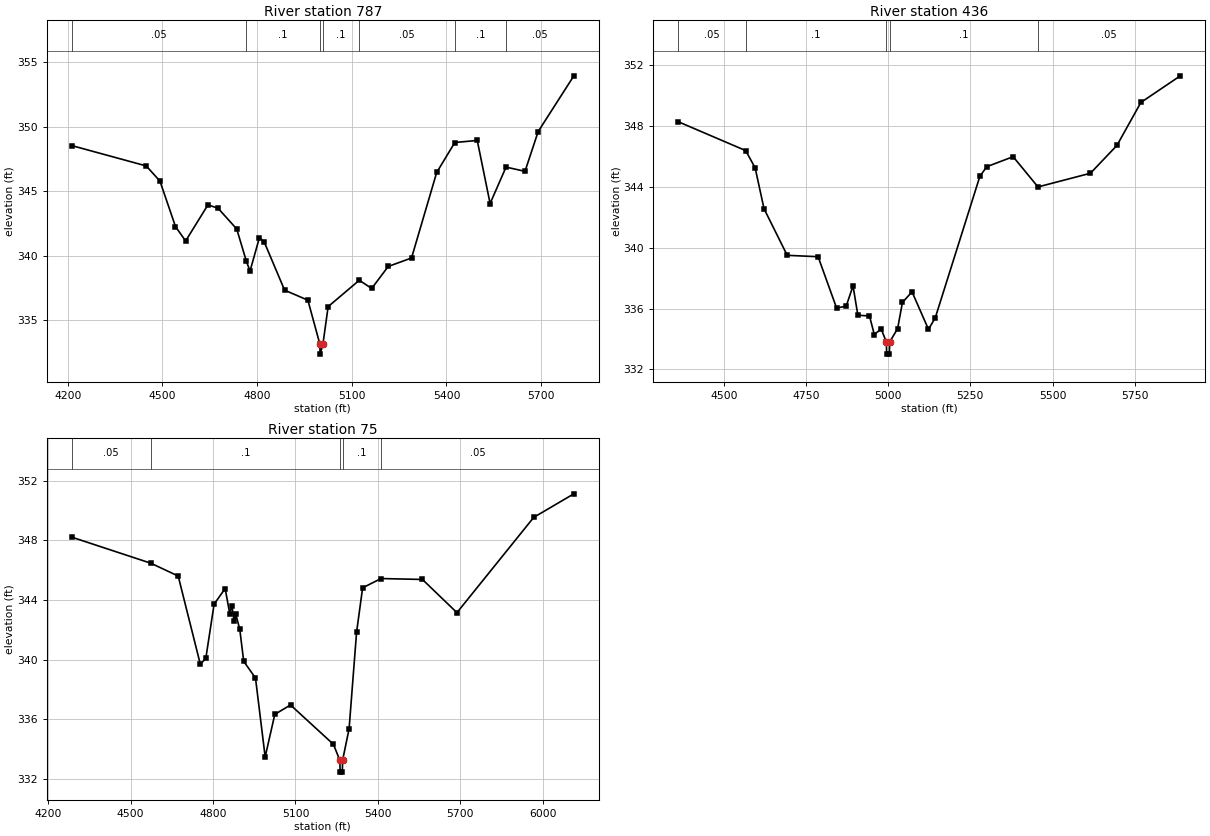
Type RM Length L Ch R = 1,787,351,351,351
BEGIN DESCRIPTION:
Mapping XS 1439dbb9
END DESCRIPTION:
XS GIS Cut Line= 4
      2074836.81     13438882.20      2074572.90     13438406.47
      2074017.34     13438073.14      2073621.47     13438125.22
#Sta/Elev= 30
  4212.5  348.54  4448.5  346.96  4492.0  345.78  4541.2  342.25  4573.3  341.13
  4644.2  343.94  4676.2  343.67  4735.3  342.06  4765.3  339.60  4777.4  338.79
  4807.3  341.40  4822.8  341.03  4887.0  337.31  4960.8  336.53  4998.5  333.14
  4999.5  332.34  5008.6  333.14  5025.0  336.03  5123.8  338.08  5163.0  337.44
  5215.4  339.15  5289.3  339.81  5369.0  346.45  5426.4  348.78  5497.6  348.94
  5538.3  344.04  5588.8  346.87  5648.9  346.54  5690.6  349.63  5803.7  353.96
#Mann=7,-1,0
  4212.5    0.05       0  4765.3     0.1       0  4998.5    0.07       0
  5008.6     0.1       0  5123.8    0.05       0  5426.4     0.1       0
  5588.8    0.05       0
Bank Sta=4998.5,5008.6
Exp/Cntr=0.3,0.1

Type RM Length L Ch R = 1,436,361,361,361
BEGIN DESCRIPTION:
Mapping XS 3e485c1a
END DESCRIPTION:
XS GIS Cut Line= 4
      2074954.85     13438837.04      2074920.12     13438576.61
      2074510.40     13438024.52      2073961.79     13437843.97
#Sta/Elev= 30
  4361.1  348.30  4566.4  346.40  4595.2  345.26  4622.1  342.58  4692.7  339.51
  4786.7  339.42  4843.0  336.04  4872.2  336.17  4893.0  337.50  4907.7  335.57
  4943.1  335.52  4957.7  334.30  4978.6  334.67  4994.4  333.81  4995.4  333.01
  5003.5  333.01  5004.5  333.81  5028.7  334.69  5043.3  336.41  5072.5  337.11
  5122.6  334.64  5143.4  335.41  5279.0  344.71  5299.9  345.34  5380.2  346.00
  5455.8  344.01  5615.4  344.91  5696.0  346.74  5769.0  349.57  5888.9  351.32
#Mann=5,-1,0
  4361.1    0.05       0  4566.4     0.1       0  4994.4    0.07       0
  5004.5     0.1       0  5455.8    0.05       0
Bank Sta=4994.4,5004.5
Exp/Cntr=0.3,0.1

Type RM Length L Ch R = 1,75,0,0,0
BEGIN DESCRIPTION:
UNT 69 in Lagunillas Cr Wtrshd 1.0
END DESCRIPTION:
XS GIS Cut Line= 4
      2075045.12     13438750.21      2074982.56     13438176.83
      2074670.12     13437805.77      2073938.72     13437577.00
#Sta/Elev= 30
  4285.5  348.22  4573.4  346.47  4673.0  345.61  4753.5  339.69  4773.6  340.08
  4803.8  343.72  4844.0  344.77  4860.7  343.09  4868.7  343.62  4876.5  342.56
  4883.0  343.03  4897.3  342.02  4911.6  339.88  4954.5  338.76  4989.7  333.46
  5024.8  336.32  5082.0  336.95  5238.1  334.31  5261.6  333.24  5262.6  332.44
  5270.7  332.44  5271.7  333.24  5295.3  335.35  5322.6  341.84  5344.6  344.82
  5411.7  345.44  5562.3  345.38  5688.0  343.15  5967.7  349.55  6113.7  351.13
#Mann=5,-1,0
  4285.5    0.05       0  4573.4     0.1       0  5261.6    0.07       0
  5271.7     0.1       0  5411.7    0.05       0
Bank Sta=5261.6,5271.7
Exp/Cntr=0.3,0.1

Chan Stop Cuts=-1