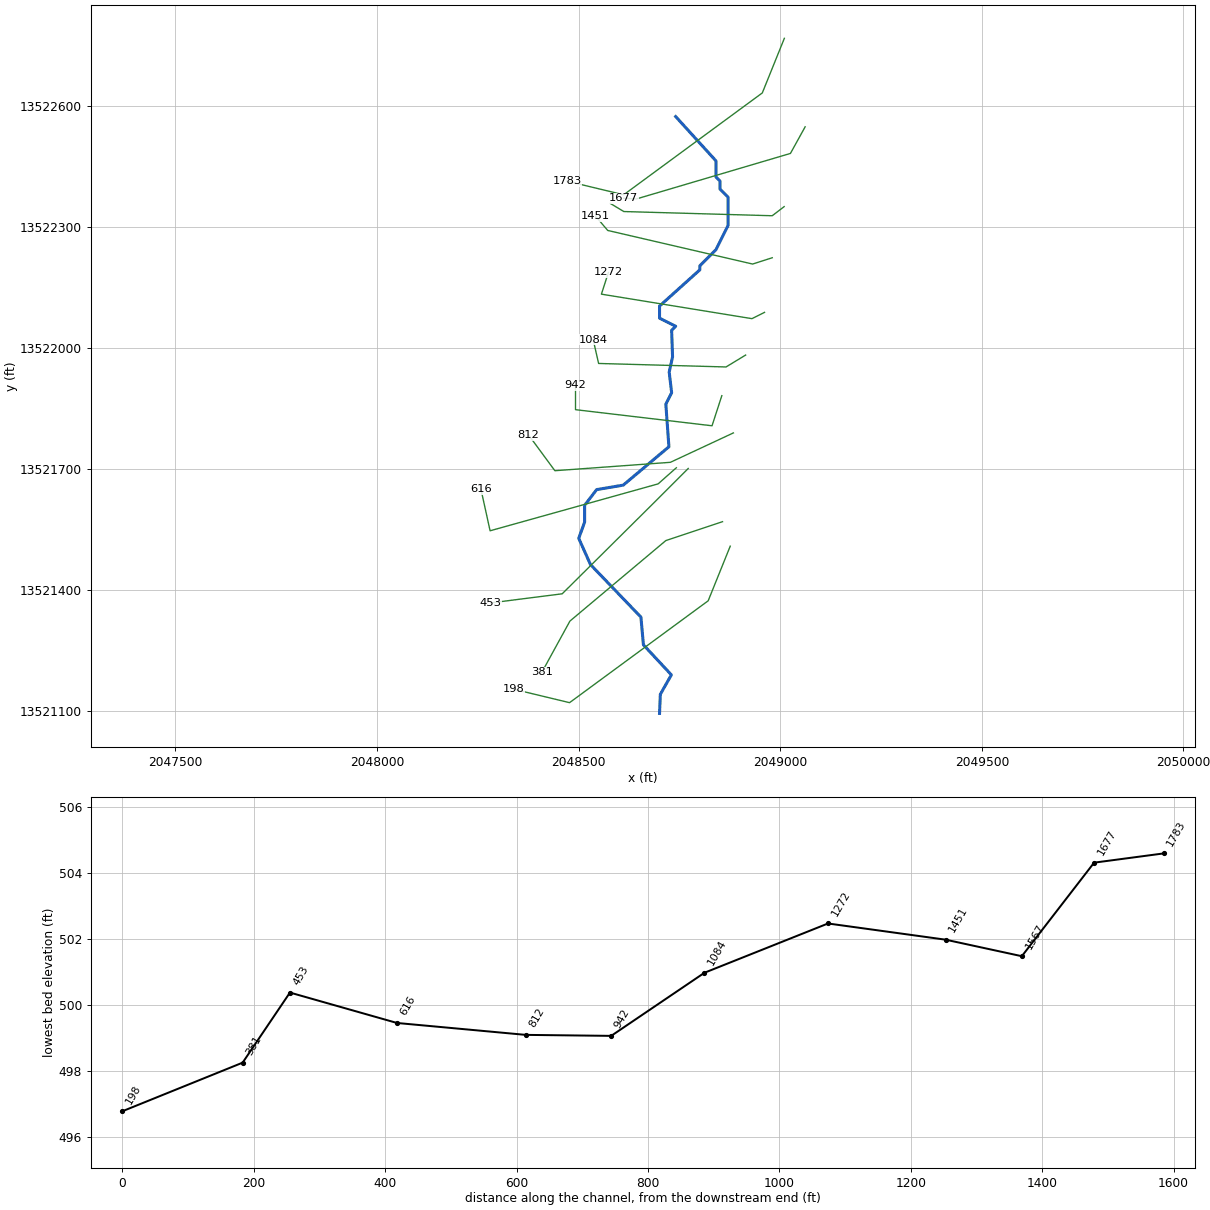
--- UNT 7 in Lagunillas Cr Wtrshd.prj (project) ---

Proj Title=UNT 7 in Lagunillas Cr Wtrshd Base Level Engineering
Current Plan=p01
Default Exp/Contr=0.3,0.1
English Units
Geom File=g01
Flow File=f01
Plan File=p01
BEGIN DESCRIPTION:
UNT 7 in Lagunillas Cr Wtrshd
END DESCRIPTION:

--- UNT 7 in Lagunillas Cr Wtrshd.p01 (plan) ---

Plan Title=Multiple Run
Short Identifier=Multiple
Geom File=g01
Flow File=f01
Subcritical Flow
K Sum by GR= 0
Std Step Tol= 0.01
Critical Tol= 0.01
Num of Std Step Trials= 20
Max Error Tol= 0.3
Flow Tol Ratio= 0.001
Split Flow NTrial= 30
Split Flow Tol= 0.02
Split Flow Ratio= 0.02
Log Output Level= 0
Friction Slope Method= 1
Unsteady Friction Slope Method= 2
Unsteady Bridges Friction Slope Method= 1
Parabolic Critical Depth
Global Vel Dist=  1 , 1 , 1
Global Log Level= 0
CheckData=True
Encroach Param= -1, 0, 0, 0
BEGIN DESCRIPTION:
Multiple Run
END DESCRIPTION:

--- UNT 7 in Lagunillas Cr Wtrshd.f01 (steady flow) ---

Flow Title=Multiple
Number of Profiles=7
Profile Names=10-year,25-year,50-year,1pct_min,100-year,1pct_plu,500-year
River Rch & RM= UNT 7 in Lagunil,Reach-1,1783
     176     238     288     174     346     691     509
Boundary for River Rch & Prof#=UNT 7 in Lagunil,Reach-1,1
Up Type=0
Dn Type=3
Dn Slope=0.005
Boundary for River Rch & Prof#=UNT 7 in Lagunil,Reach-1,2
Up Type=0
Dn Type=3
Dn Slope=0.005
Boundary for River Rch & Prof#=UNT 7 in Lagunil,Reach-1,3
Up Type=0
Dn Type=3
Dn Slope=0.005
Boundary for River Rch & Prof#=UNT 7 in Lagunil,Reach-1,4
Up Type=0
Dn Type=3
Dn Slope=0.005
Boundary for River Rch & Prof#=UNT 7 in Lagunil,Reach-1,5
Up Type=0
Dn Type=3
Dn Slope=0.005
Boundary for River Rch & Prof#=UNT 7 in Lagunil,Reach-1,6
Up Type=0
Dn Type=3
Dn Slope=0.005
Boundary for River Rch & Prof#=UNT 7 in Lagunil,Reach-1,7
Up Type=0
Dn Type=3
Dn Slope=0.005

--- UNT 7 in Lagunillas Cr Wtrshd.g01 (geometry) ---

Geom Title=Existing Conditions

River Reach=UNT 7 in Lagunil,Reach-1
Reach XY= 30
      2048740.80     13522574.54      2048840.80     13522464.54
      2048840.80     13522424.54      2048850.80     13522414.54
      2048850.80     13522394.54      2048870.80     13522374.54
      2048870.80     13522304.54      2048840.80     13522244.54
      2048800.80     13522204.54      2048800.80     13522194.54
      2048700.80     13522104.54      2048700.80     13522074.54
      2048740.80     13522054.54      2048730.80     13522044.54
      2048733.08     13521978.61      2048724.75     13521941.11
      2048730.80     13521889.72      2048716.42     13521861.25
      2048724.06     13521755.70      2048610.86     13521660.56
      2048544.89     13521649.45      2048515.03     13521610.56
      2048515.03     13521568.89      2048500.44     13521528.61
      2048529.61     13521463.48      2048654.61     13521333.27
      2048660.80     13521264.54      2048730.13     13521190.04
      2048702.79     13521141.86      2048700.80     13521094.54

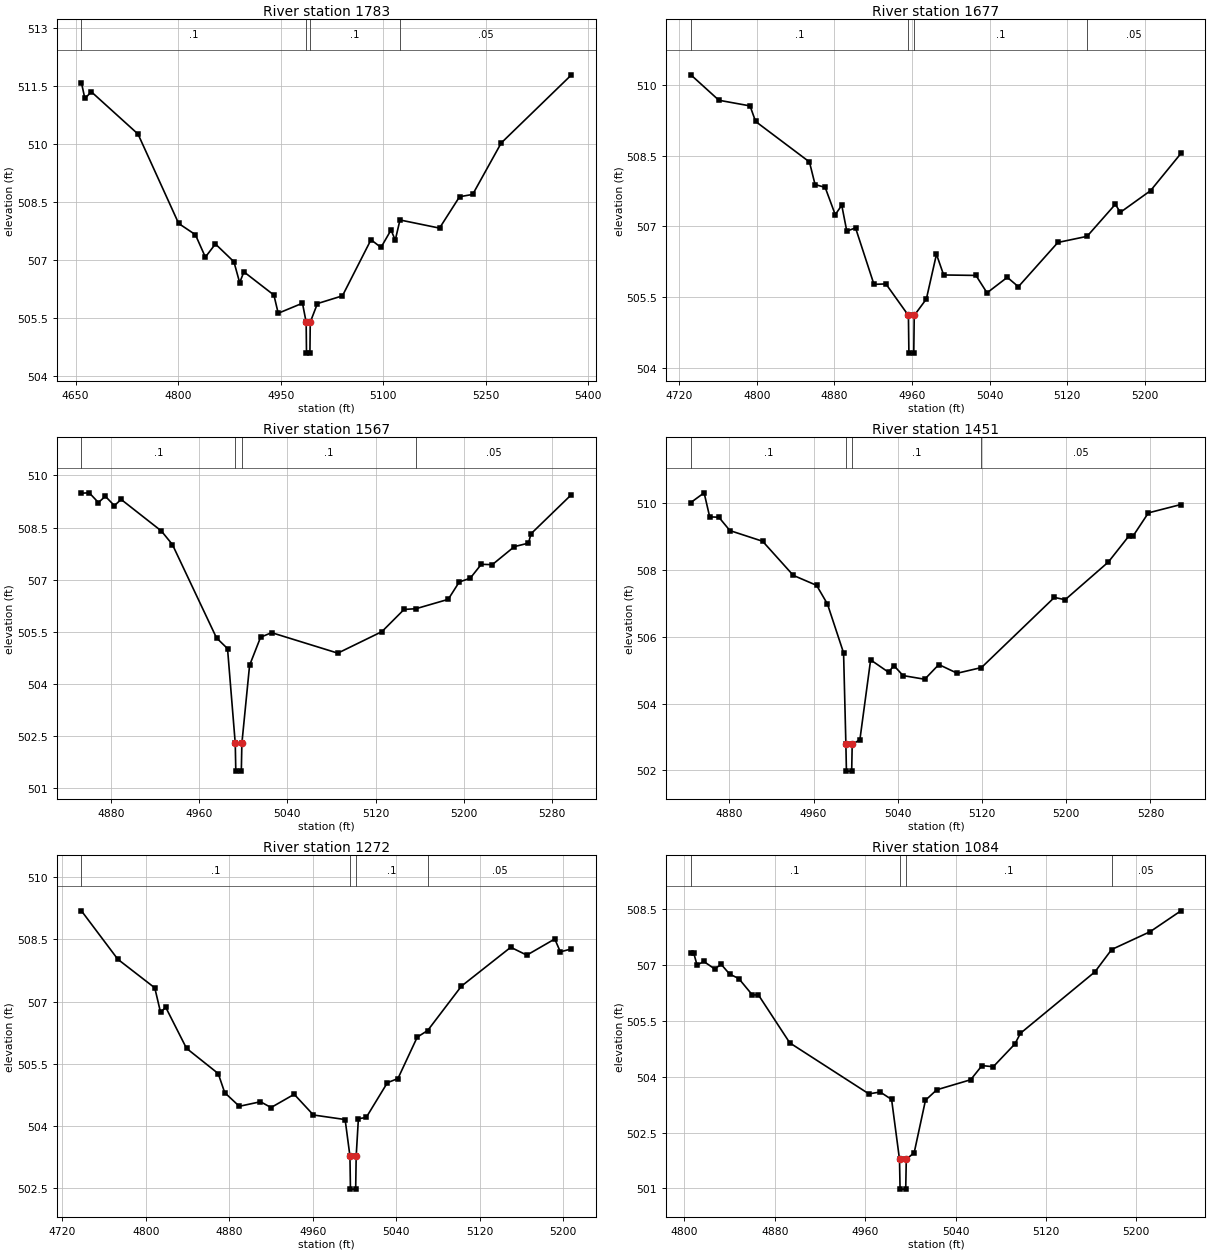
Type RM Length L Ch R = 1,1783,106,106,106
BEGIN DESCRIPTION:
UNT 7 in Lagunillas Cr Wtrshd 20.0
END DESCRIPTION:
XS GIS Cut Line= 4
      2049010.32     13522768.51      2048955.64     13522633.13
      2048611.89     13522380.53      2048471.30     13522414.37
#Sta/Elev= 30
  4658.4  511.58  4663.4  511.17  4673.0  511.34  4741.2  510.25  4800.7  507.94
  4825.2  507.65  4839.8  507.07  4854.5  507.41  4881.6  506.95  4890.0  506.41
  4896.2  506.69  4940.1  506.09  4946.4  505.62  4981.9  505.88  4987.3  505.39
  4987.8  504.59  4992.8  504.59  4993.3  505.39  5003.8  505.87  5040.4  506.07
  5082.2  507.52  5096.8  507.32  5111.5  507.77  5117.7  507.51  5124.6  508.03
  5182.5  507.82  5211.8  508.63  5231.0  508.69  5272.8  510.02  5375.6  511.78
#Mann=4,-1,0
  4658.4     0.1       0  4987.3    0.07       0  4993.3     0.1       0
  5124.6    0.05       0
Bank Sta=4987.3,4993.3
Exp/Cntr=0.3,0.1

Type RM Length L Ch R = 1,1677,110,110,110
BEGIN DESCRIPTION:
Mapping XS 77fcc1f2
END DESCRIPTION:
XS GIS Cut Line= 4
      2049061.88     13522549.08      2049025.41     13522483.09
      2048643.47     13522370.24      2048612.18     13522371.98
#Sta/Elev= 30
  4732.1  510.22  4761.0  509.68  4793.1  509.56  4798.8  509.23  4854.3  508.37
  4860.1  507.89  4870.5  507.83  4880.9  507.25  4887.6  507.45  4892.8  506.90
  4901.8  506.97  4920.8  505.77  4933.1  505.78  4956.3  505.11  4956.8  504.31
  4961.8  504.31  4962.3  505.11  4974.8  505.46  4985.2  506.41  4992.6  505.97
  5025.9  505.96  5037.3  505.59  5058.2  505.92  5069.6  505.72  5110.3  506.66
  5140.4  506.79  5169.5  507.47  5174.7  507.30  5205.8  507.76  5237.1  508.55
#Mann=4,-1,0
  4732.1     0.1       0  4956.3    0.07       0  4962.3     0.1       0
  5140.4    0.05       0
Bank Sta=4956.3,4962.3
Exp/Cntr=0.3,0.1

Type RM Length L Ch R = 1,1567,116,116,116
BEGIN DESCRIPTION:
Mapping XS f3b6af93
END DESCRIPTION:
XS GIS Cut Line= 4
      2049009.81     13522351.16      2048980.27     13522328.58
      2048612.22     13522338.99      2048578.76     13522359.07
#Sta/Elev= 30
  4853.3  509.49  4860.4  509.50  4868.7  509.22  4875.0  509.40  4883.2  509.13
  4889.3  509.31  4925.8  508.40  4935.8  508.01  4975.8  505.32  4985.8  505.01
  4992.8  502.28  4993.3  501.48  4998.3  501.48  4998.8  502.28  5005.8  504.53
  5015.8  505.34  5025.8  505.47  5085.8  504.88  5125.8  505.50  5145.9  506.14
  5156.6  506.16  5185.9  506.43  5195.9  506.93  5205.9  507.04  5215.9  507.44
  5225.9  507.43  5245.9  507.95  5258.7  508.05  5261.0  508.32  5297.7  509.45
#Mann=4,-1,0
  4853.3     0.1       0  4992.8    0.07       0  4998.8     0.1       0
  5156.6    0.05       0
Bank Sta=4992.8,4998.8
Exp/Cntr=0.3,0.1

Type RM Length L Ch R = 1,1451,179,179,179
BEGIN DESCRIPTION:
Mapping XS a85836cf
END DESCRIPTION:
XS GIS Cut Line= 4
      2048980.30     13522224.42      2048931.66     13522208.78
      2048572.29     13522292.12      2048542.75     13522326.86
#Sta/Elev= 30
  4843.4  510.02  4856.0  510.31  4861.3  509.59  4870.0  509.58  4880.5  509.18
  4911.6  508.86  4940.7  507.84  4962.9  507.54  4973.2  506.98  4988.5  505.52
  4990.7  502.78  4991.2  501.98  4996.2  501.98  4996.7  502.78  5004.0  502.92
  5014.2  505.31  5031.2  504.94  5036.3  505.14  5045.0  504.84  5065.6  504.73
  5079.0  505.17  5096.4  504.91  5119.5  505.08  5188.8  507.18  5199.0  507.11
  5240.1  508.24  5259.4  509.01  5263.4  509.01  5278.1  509.71  5309.0  509.96
#Mann=4,-1,0
  4843.4     0.1       0  4990.7    0.07       0  4996.7     0.1       0
  5119.5    0.05       0
Bank Sta=4990.7,4996.7
Exp/Cntr=0.3,0.1

Type RM Length L Ch R = 1,1272,188,188,188
BEGIN DESCRIPTION:
Mapping XS 40c31325
END DESCRIPTION:
XS GIS Cut Line= 4
      2048961.14     13522088.97      2048929.93     13522073.37
      2048556.66     13522134.13      2048574.02     13522187.93
#Sta/Elev= 30
  4738.3  509.19  4773.2  508.02  4808.6  507.33  4814.1  506.74  4819.1  506.86
  4839.0  505.87  4869.4  505.26  4875.6  504.80  4889.6  504.47  4909.9  504.58
  4920.0  504.44  4942.2  504.76  4960.6  504.26  4991.0  504.15  4995.6  503.27
  4996.1  502.47  5001.1  502.47  5001.6  503.27  5003.7  504.17  5011.2  504.20
  5031.5  505.04  5041.6  505.14  5060.1  506.14  5070.1  506.30  5102.4  507.37
  5149.7  508.31  5165.1  508.12  5191.9  508.51  5197.2  508.20  5207.9  508.27
#Mann=4,-1,0
  4738.3     0.1       0  4995.6    0.07       0  5001.6     0.1       0
  5070.1    0.05       0
Bank Sta=4995.6,5001.6
Exp/Cntr=0.3,0.1

Type RM Length L Ch R = 1,1084,142,142,142
BEGIN DESCRIPTION:
Mapping XS 7e82b567
END DESCRIPTION:
XS GIS Cut Line= 4
      2048914.34     13521983.11      2048865.69     13521953.58
      2048549.72     13521962.26      2048536.17     13522021.52
#Sta/Elev= 30
  4805.7  507.32  4808.3  507.32  4811.2  507.00  4817.1  507.10  4826.7  506.90
  4832.6  507.02  4840.0  506.76  4848.1  506.64  4860.1  506.20  4865.5  506.20
  4893.3  504.91  4963.3  503.54  4973.3  503.59  4983.4  503.39  4990.4  501.78
  4990.9  500.98  4995.9  500.98  4996.4  501.78  5003.4  501.96  5013.4  503.37
  5023.4  503.65  5053.4  503.92  5063.4  504.30  5073.4  504.27  5092.5  504.88
  5097.5  505.17  5163.4  506.82  5178.2  507.42  5212.3  507.90  5239.5  508.46
#Mann=4,-1,0
  4805.7     0.1       0  4990.4    0.07       0  4996.4     0.1       0
  5178.2    0.05       0
Bank Sta=4990.4,4996.4
Exp/Cntr=0.3,0.1

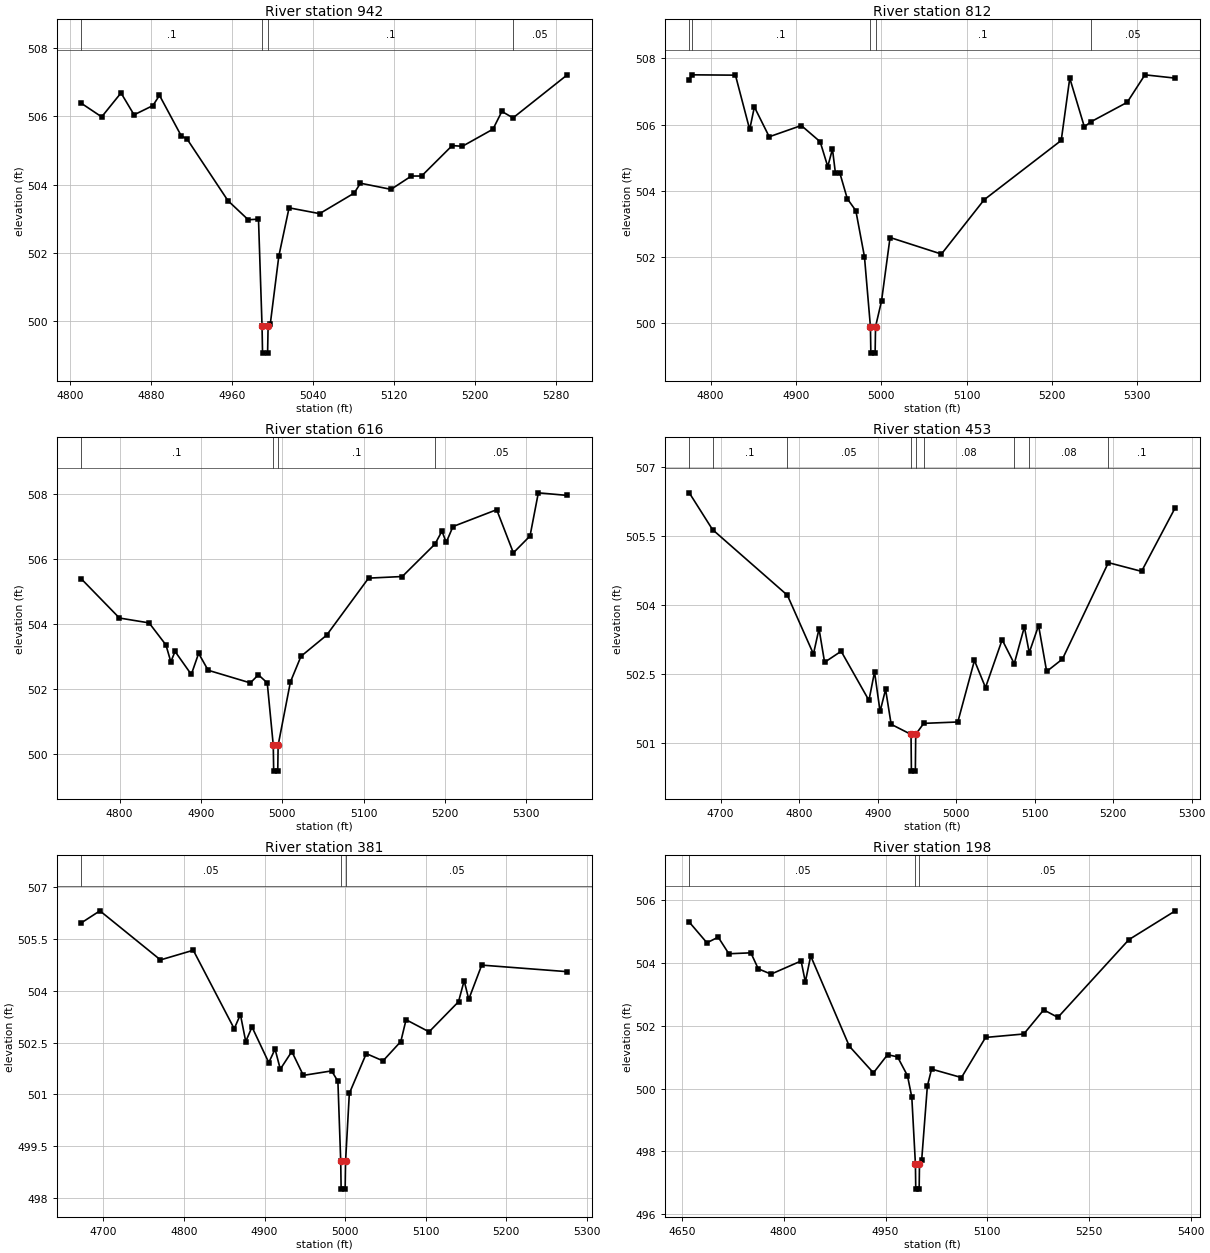
Type RM Length L Ch R = 1,942,130,130,130
BEGIN DESCRIPTION:
Mapping XS 29b1ee0f
END DESCRIPTION:
XS GIS Cut Line= 4
      2048855.26     13521882.35      2048830.97     13521807.74
      2048492.43     13521847.67      2048492.43     13521908.42
#Sta/Elev= 30
  4811.3  506.38  4831.5  505.98  4850.6  506.68  4863.5  506.04  4882.1  506.31
  4888.6  506.61  4910.0  505.43  4915.9  505.33  4956.2  503.53  4976.3  502.97
  4986.4  502.99  4989.9  499.87  4990.4  499.07  4995.4  499.07  4995.9  499.87
  4998.0  499.91  5006.5  501.91  5016.6  503.32  5046.8  503.15  5080.9  503.75
  5087.1  504.04  5117.3  503.86  5137.4  504.25  5147.5  504.25  5177.7  505.14
  5187.8  505.12  5218.0  505.62  5226.8  506.14  5237.8  505.95  5291.4  507.21
#Mann=4,-1,0
  4811.3     0.1       0  4989.9    0.07       0  4995.9     0.1       0
  5237.8    0.05       0
Bank Sta=4989.9,4995.9
Exp/Cntr=0.3,0.1

Type RM Length L Ch R = 1,812,196,196,196
BEGIN DESCRIPTION:
Mapping XS 69d62e4d
END DESCRIPTION:
XS GIS Cut Line= 4
      2048883.99     13521790.04      2048727.73     13521717.12
      2048441.27     13521696.28      2048376.14     13521784.86
#Sta/Elev= 30
  4775.0  507.34  4778.1  507.50  4829.1  507.49  4845.8  505.85  4851.3  506.53
  4868.7  505.63  4906.3  505.97  4928.4  505.48  4937.3  504.73  4942.8  505.26
  4946.2  504.55  4951.3  504.55  4960.2  503.76  4970.2  503.40  4980.3  502.01
  4987.3  499.90  4987.8  499.10  4992.8  499.10  4993.3  499.90  5000.3  500.67
  5010.3  502.59  5070.5  502.09  5120.6  503.73  5210.9  505.52  5220.9  507.40
  5238.0  505.93  5245.5  506.08  5288.2  506.67  5309.0  507.50  5344.6  507.40
#Mann=5,-1,0
  4775.0    0.05       0  4778.1     0.1       0  4987.3    0.07       0
  4993.3     0.1       0  5245.5    0.05       0
Bank Sta=4987.3,4993.3
Exp/Cntr=0.3,0.1

Type RM Length L Ch R = 1,616,163,163,163
BEGIN DESCRIPTION:
Mapping XS b3c9ca37
END DESCRIPTION:
XS GIS Cut Line= 4
      2048742.46     13521703.61      2048697.29     13521663.65
      2048280.62     13521547.33      2048258.05     13521649.76
#Sta/Elev= 30
  4752.7  505.39  4799.7  504.18  4836.2  504.03  4856.9  503.35  4862.9  502.83
  4868.1  503.15  4888.1  502.44  4897.1  503.09  4908.8  502.57  4960.7  502.18
  4970.6  502.43  4981.5  502.18  4988.9  500.26  4989.4  499.46  4994.4  499.46
  4994.9  500.26  5010.0  502.21  5023.0  503.00  5054.5  503.65  5106.1  505.41
  5147.6  505.46  5187.8  506.46  5196.4  506.86  5201.6  506.51  5209.9  507.00
  5263.7  507.52  5284.2  506.19  5304.7  506.71  5314.9  508.04  5350.5  507.96
#Mann=4,-1,0
  4752.7     0.1       0  4988.9    0.07       0  4994.9     0.1       0
  5187.8    0.05       0
Bank Sta=4988.9,4994.9
Exp/Cntr=0.3,0.1

Type RM Length L Ch R = 1,453,72,72,72
BEGIN DESCRIPTION:
Mapping XS 967dcb8a
END DESCRIPTION:
XS GIS Cut Line= 4
      2048771.93     13521701.83      2048686.87     13521616.77
      2048459.44     13521391.08      2048282.37     13521368.51
#Sta/Elev= 30
  4660.0  506.44  4689.6  505.64  4785.0  504.21  4818.2  502.93  4825.3  503.48
  4832.4  502.75  4853.5  502.99  4888.9  501.92  4896.0  502.54  4903.1  501.68
  4910.1  502.16  4917.2  501.40  4942.5  501.18  4943.0  500.38  4948.0  500.38
  4948.5  501.18  4958.7  501.42  5002.1  501.45  5023.3  502.79  5037.4  502.20
  5058.6  503.24  5074.0  502.72  5086.9  503.52  5093.1  502.96  5105.0  503.55
  5115.3  502.55  5135.4  502.82  5193.9  504.92  5236.2  504.73  5279.2  506.12
#Mann=9,-1,0
  4660.0    0.08       0  4689.6     0.1       0  4785.0    0.05       0
  4942.5    0.07       0  4948.5    0.05       0  4958.7    0.08       0
  5074.0    0.05       0  5093.1    0.08       0  5193.9     0.1       0
Bank Sta=4942.5,4948.5
Exp/Cntr=0.3,0.1

Type RM Length L Ch R = 1,381,183,183,183
BEGIN DESCRIPTION:
Mapping XS 358544fe
END DESCRIPTION:
XS GIS Cut Line= 4
      2048857.00     13521569.89      2048716.38     13521523.02
      2048478.54     13521323.37      2048409.08     13521196.60
#Sta/Elev= 30
  4672.5  505.96  4695.7  506.31  4770.9  504.89  4811.6  505.17  4862.4  502.90
  4870.1  503.31  4876.7  502.53  4884.5  502.95  4905.3  501.92  4913.1  502.31
  4919.6  501.73  4933.9  502.24  4948.2  501.55  4983.3  501.68  4991.1  501.38
  4994.6  499.06  4995.1  498.26  5000.1  498.26  5000.6  499.06  5005.3  501.03
  5026.3  502.18  5047.1  501.97  5069.2  502.53  5075.7  503.16  5104.3  502.81
  5140.8  503.68  5147.8  504.29  5153.5  503.75  5169.6  504.74  5275.8  504.55
#Mann=3,-1,0
  4672.5    0.05       0  4994.6    0.03       0  5000.6    0.05       0
Bank Sta=4994.6,5000.6
Exp/Cntr=0.3,0.1

Type RM Length L Ch R = 1,198,0,0,0
BEGIN DESCRIPTION:
UNT 7 in Lagunillas Cr Wtrshd 19.0
END DESCRIPTION:
XS GIS Cut Line= 4
      2048876.09     13521509.10      2048821.42     13521373.72
      2048477.67     13521121.11      2048338.54     13521154.61
#Sta/Elev= 30
  4661.0  505.31  4687.0  504.65  4703.6  504.83  4719.3  504.30  4751.7  504.33
  4762.6  503.82  4781.4  503.65  4825.7  504.07  4831.9  503.40  4839.8  504.23
  4896.7  501.35  4932.2  500.50  4953.0  501.08  4967.7  501.01  4982.3  500.41
  4988.7  499.72  4994.0  497.59  4994.5  496.79  4999.5  496.79  5000.0  497.59
  5003.2  497.71  5011.6  500.08  5017.8  500.62  5061.8  500.35  5097.3  501.63
  5153.6  501.74  5182.9  502.51  5203.8  502.27  5308.3  504.75  5376.7  505.67
#Mann=3,-1,0
  4661.0    0.05       0  4994.0    0.03       0  5000.0    0.05       0
Bank Sta=4994,5000
Exp/Cntr=0.3,0.1

Chan Stop Cuts=-1