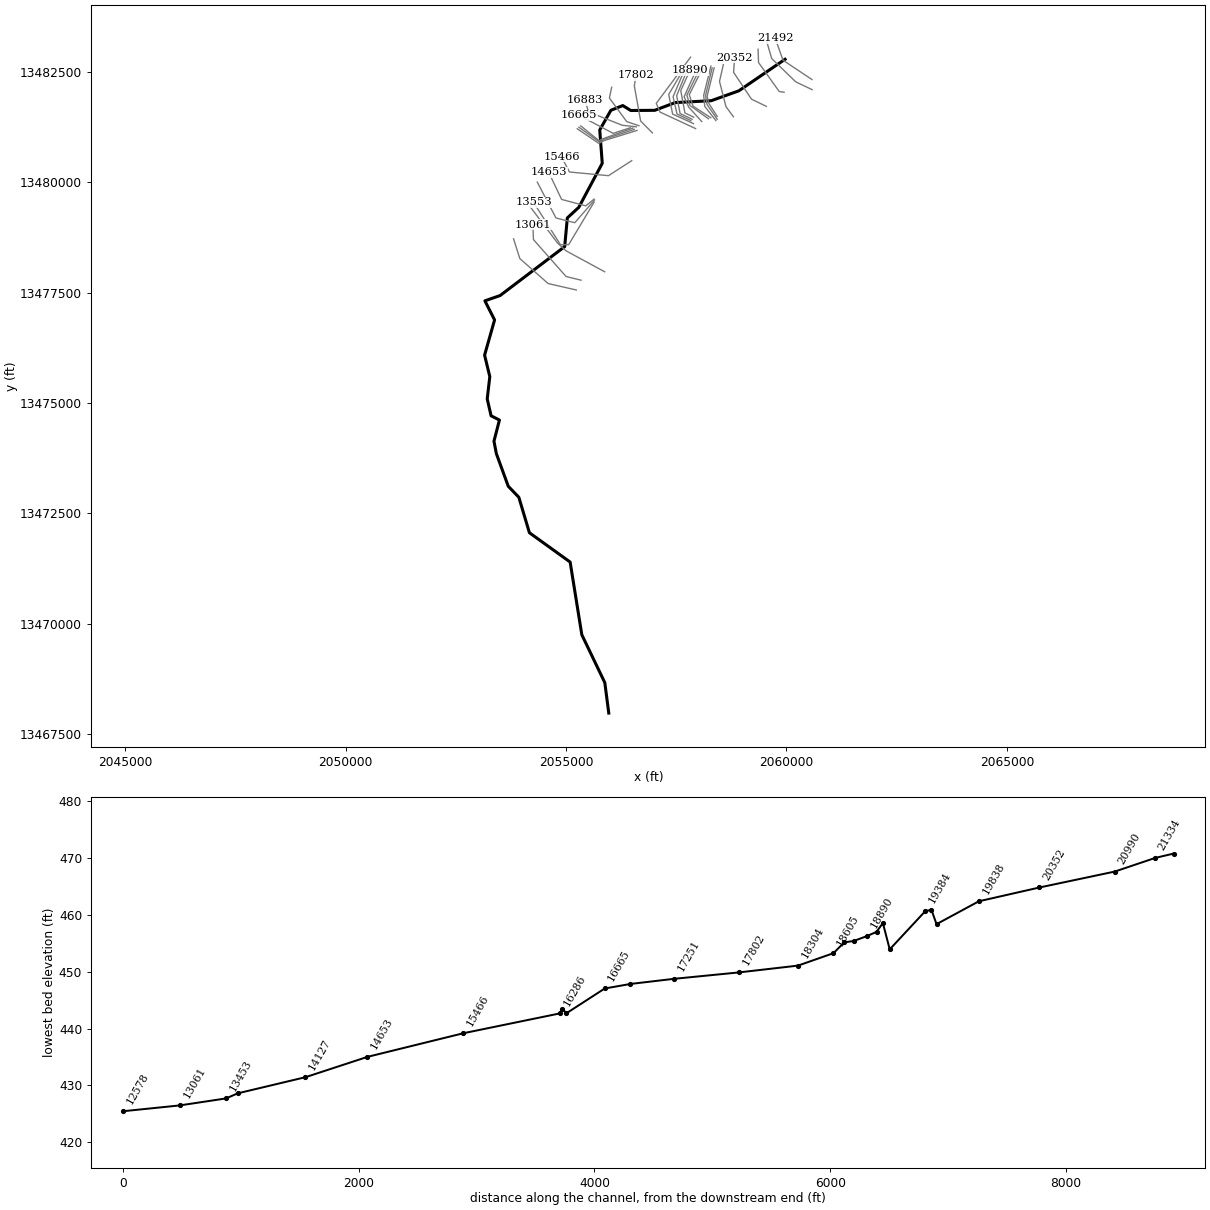
--- UNT 71 in Lagunillas Cr Wtrshd.prj (project) ---

Proj Title=UNT 71 in Lagunillas Cr Wtrshd Base Level Engineering
Current Plan=p01
Default Exp/Contr=0.3,0.1
English Units
Geom File=g01
Flow File=f01
Plan File=p01
BEGIN DESCRIPTION:
UNT 71 in Lagunillas Cr Wtrshd
END DESCRIPTION:

--- UNT 71 in Lagunillas Cr Wtrshd.p01 (plan) ---

Plan Title=Multiple Run
Short Identifier=Multiple
Geom File=g01
Flow File=f01
Subcritical Flow
K Sum by GR= 0
Std Step Tol= 0.01
Critical Tol= 0.01
Num of Std Step Trials= 20
Max Error Tol= 0.3
Flow Tol Ratio= 0.001
Split Flow NTrial= 30
Split Flow Tol= 0.02
Split Flow Ratio= 0.02
Log Output Level= 0
Friction Slope Method= 1
Unsteady Friction Slope Method= 2
Unsteady Bridges Friction Slope Method= 1
Parabolic Critical Depth
Global Vel Dist=  1 , 1 , 1
Global Log Level= 0
CheckData=True
Encroach Param= -1, 0, 0, 0
BEGIN DESCRIPTION:
Multiple Run
END DESCRIPTION:

--- UNT 71 in Lagunillas Cr Wtrshd.f01 (steady flow) ---

Flow Title=Multiple
Number of Profiles=7
Profile Names=10-year,25-year,50-year,1pct_min,100-year,1pct_plu,500-year
River Rch & RM= UNT 71 in Laguni,Reach-1,21492
      80     104     122      72     143     285     199
River Rch & RM= UNT 71 in Laguni,Reach-1,17802
     134     179     215     129     256     512     371
River Rch & RM= UNT 71 in Laguni,Reach-1,13453
     258     355     435     265     529    1056     797
River Rch & RM= UNT 71 in Laguni,Reach-1,6827
     324     449     552     338     675    1346    1023
River Rch & RM= UNT 71 in Laguni,Reach-1,245
     358     499     615     378     754    1505    1151
Boundary for River Rch & Prof#=UNT 71 in Laguni,Reach-1,1
Up Type=0
Dn Type=3
Dn Slope=0.005
Boundary for River Rch & Prof#=UNT 71 in Laguni,Reach-1,2
Up Type=0
Dn Type=3
Dn Slope=0.005
Boundary for River Rch & Prof#=UNT 71 in Laguni,Reach-1,3
Up Type=0
Dn Type=3
Dn Slope=0.005
Boundary for River Rch & Prof#=UNT 71 in Laguni,Reach-1,4
Up Type=0
Dn Type=3
Dn Slope=0.005
Boundary for River Rch & Prof#=UNT 71 in Laguni,Reach-1,5
Up Type=0
Dn Type=3
Dn Slope=0.005
Boundary for River Rch & Prof#=UNT 71 in Laguni,Reach-1,6
Up Type=0
Dn Type=3
Dn Slope=0.005
Boundary for River Rch & Prof#=UNT 71 in Laguni,Reach-1,7
Up Type=0
Dn Type=3
Dn Slope=0.005

--- UNT 71 in Lagunillas Cr Wtrshd.g01 (geometry) ---

Geom Title=Existing Conditions

River Reach=UNT 71 in Laguni,Reach-1
Reach XY= 30
      2059968.82     13482789.28      2058920.80     13482074.54
      2058296.20     13481850.69      2057477.22     13481807.82
      2057014.25     13481632.63      2056470.02     13481628.67
      2056288.77     13481740.48      2056018.63     13481633.53
      2055765.85     13481187.70      2055822.79     13480432.14
      2055290.80     13479434.54      2055030.80     13479194.54
      2054970.80     13478544.54      2053505.43     13477435.44
      2053160.93     13477316.22      2053380.80     13476883.58
      2053154.09     13476084.96      2053272.36     13475598.85
      2053213.77     13475094.30      2053301.66     13474711.27
      2053490.80     13474614.70      2053366.76     13474136.18
      2053420.80     13473854.54      2053690.80     13473114.54
      2053930.80     13472864.54      2054170.91     13472061.15
      2055094.52     13471397.08      2055359.28     13469749.95
      2055880.80     13468664.54      2055970.80     13467974.54

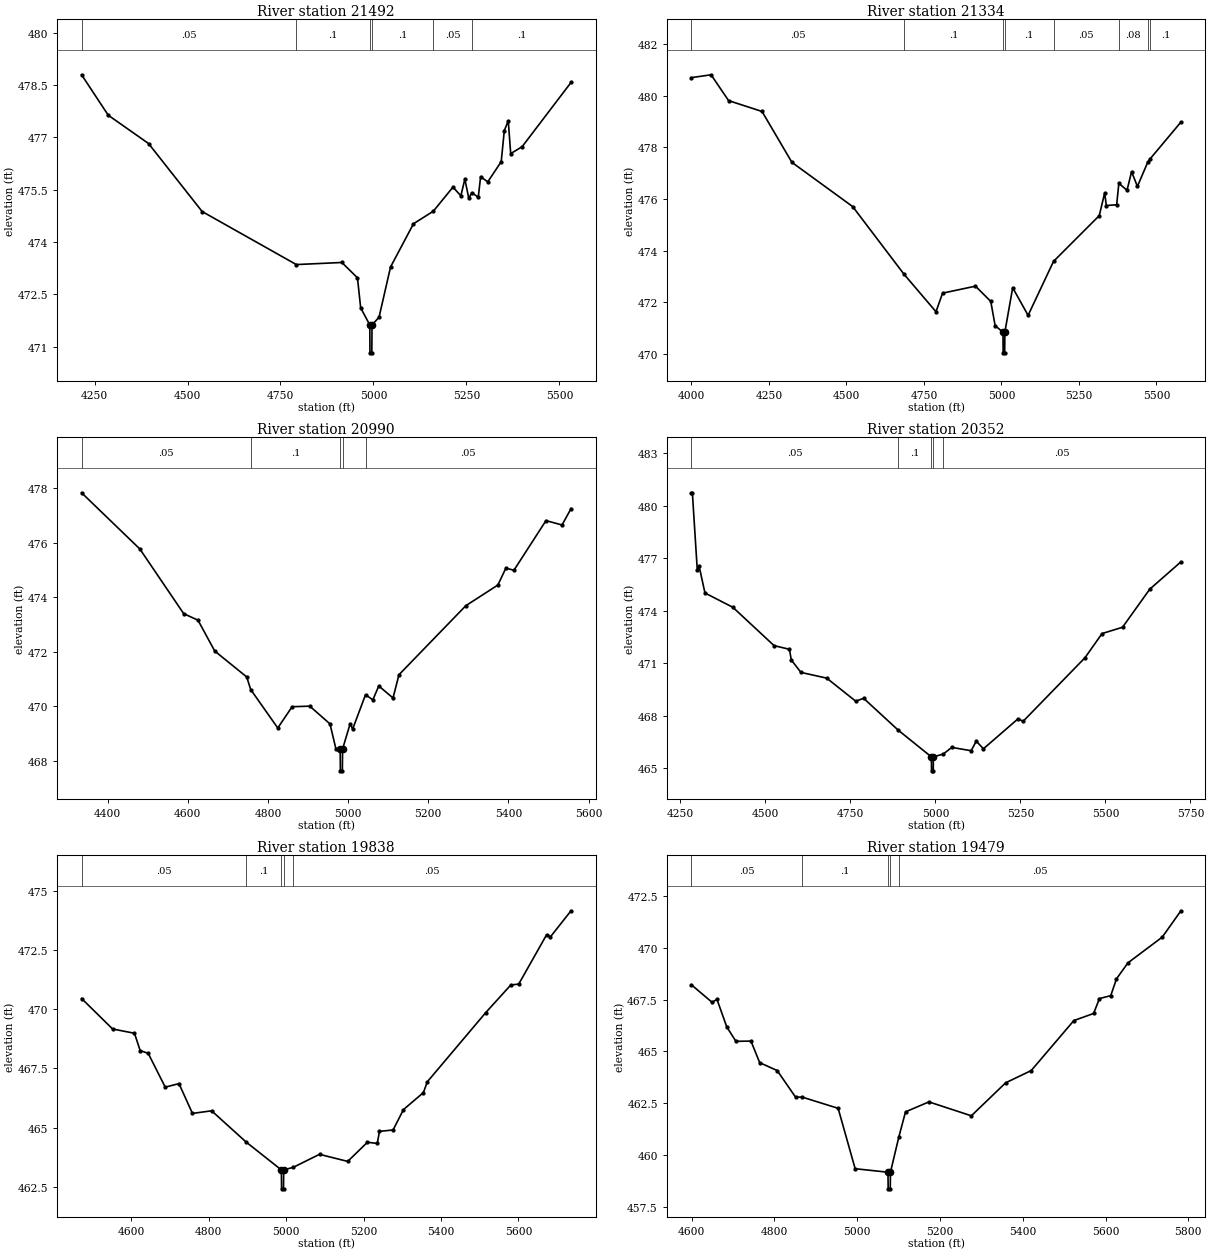
Type RM Length L Ch R = 1,21492,158,158,158
BEGIN DESCRIPTION:
UNT 71 in Lagunillas Cr Wtrshd 4.0
END DESCRIPTION:
XS GIS Cut Line= 3
      2060579.34     13482329.89      2059922.82     13482767.60
      2059745.97     13483263.98
#Sta/Elev= 30
  4215.2  478.79  4287.0  477.63  4395.2  476.82  4539.4  474.87  4792.6  473.35
  4915.0  473.41  4957.0  472.97  4965.6  472.11  4990.1  471.62  4990.6  470.82
  4995.6  470.82  4996.1  471.62  5015.0  471.84  5045.9  473.28  5107.6  474.52
  5161.0  474.88  5213.8  475.57  5235.0  475.32  5245.7  475.80  5256.3  475.25
  5264.5  475.41  5281.8  475.28  5288.1  475.87  5307.3  475.72  5343.5  476.30
  5351.8  477.19  5362.4  477.47  5369.0  476.53  5399.8  476.73  5531.2  478.57
#Mann=6,-1,0
  4215.2    0.05       0  4792.6     0.1       0  4990.1    0.07       0
  4996.1     0.1       0  5161.0    0.05       0  5264.5     0.1       0
Bank Sta=4990.1,4996.1
Exp/Cntr=0.3,0.1

Type RM Length L Ch R = 1,21334,344,344,344
BEGIN DESCRIPTION:
Mapping XS cab50810
END DESCRIPTION:
XS GIS Cut Line= 4
      2060582.74     13482100.77      2060211.26     13482277.83
      2059666.12     13482805.60      2059551.55     13483197.93
#Sta/Elev= 30
  4000.0  480.70  4063.2  480.81  4119.7  479.81  4227.6  479.39  4324.0  477.42
  4520.0  475.71  4685.1  473.10  4788.8  471.64  4810.0  472.36  4916.1  472.63
  4965.5  472.04  4979.6  471.10  5004.9  470.85  5005.4  470.05  5010.4  470.05
  5010.9  470.85  5036.2  472.57  5085.9  471.50  5168.0  473.59  5315.5  475.36
  5333.0  476.24  5338.2  475.75  5371.6  475.78  5378.7  476.61  5405.1  476.34
  5419.7  477.06  5438.6  476.49  5472.0  477.43  5480.5  477.57  5579.0  478.98
#Mann=8,-1,0
  4000.0    0.05       0  4685.1     0.1       0  5004.9    0.07       0
  5010.9     0.1       0  5168.0    0.05       0  5378.7    0.08       0
  5472.0    0.05       0  5480.5     0.1       0
Bank Sta=5004.9,5010.9
Exp/Cntr=0.3,0.1

Type RM Length L Ch R = 1,20990,638,638,638
BEGIN DESCRIPTION:
Mapping XS 787897c5
END DESCRIPTION:
XS GIS Cut Line= 4
      2059947.37     13482041.72      2059836.26     13482059.08
      2059367.51     13482715.33      2059357.09     13483017.42
#Sta/Elev= 30
  4334.9  477.83  4480.3  475.77  4589.7  473.40  4625.4  473.16  4667.1  472.03
  4747.0  471.08  4756.8  470.62  4824.4  469.21  4860.2  469.99  4904.3  470.01
  4954.7  469.36  4969.4  468.45  4980.1  468.44  4980.6  467.64  4985.6  467.64
  4986.1  468.44  5005.1  469.37  5011.2  469.17  5043.4  470.43  5061.6  470.24
  5076.4  470.75  5112.0  470.31  5126.7  471.16  5293.5  473.69  5373.6  474.45
  5393.6  475.07  5413.6  474.99  5493.6  476.81  5533.7  476.65  5556.1  477.25
#Mann=5,-1,0
  4334.9    0.05       0  4756.8     0.1       0  4980.1    0.07       0
  4986.1     0.1       0  5043.4    0.05       0
Bank Sta=4980.1,4986.1
Exp/Cntr=0.3,0.1

Type RM Length L Ch R = 1,20352,514,514,514
BEGIN DESCRIPTION:
Mapping XS 02c6d084
END DESCRIPTION:
XS GIS Cut Line= 4
      2059544.63     13481722.26      2059207.79     13481885.47
      2058801.54     13482493.10      2058825.84     13482826.39
#Sta/Elev= 30
  4282.5  480.74  4285.1  480.74  4299.5  476.33  4305.1  476.53  4322.1  475.01
  4404.3  474.19  4525.3  472.00  4570.5  471.79  4576.0  471.18  4604.3  470.47
  4680.3  470.14  4765.6  468.82  4788.6  468.99  4890.8  467.16  4987.9  465.64
  4988.4  464.84  4993.4  464.84  4993.9  465.64  5023.1  465.80  5047.9  466.18
  5105.0  465.99  5120.0  466.54  5141.0  466.10  5243.1  467.82  5257.7  467.67
  5439.8  471.31  5489.9  472.69  5550.1  473.05  5630.3  475.23  5721.9  476.79
#Mann=5,-1,0
  4282.5    0.05       0  4890.8     0.1       0  4987.9    0.07       0
  4993.9     0.1       0  5023.1    0.05       0
Bank Sta=4987.9,4993.9
Exp/Cntr=0.3,0.1

Type RM Length L Ch R = 1,19838,359,359,359
BEGIN DESCRIPTION:
Mapping XS e85210eb
END DESCRIPTION:
XS GIS Cut Line= 4
      2058798.04     13481486.20      2058627.93     13481718.80
      2058482.09     13482288.24      2058568.90     13482666.73
#Sta/Elev= 30
  4471.5  470.46  4551.7  469.17  4608.1  468.99  4622.8  468.26  4643.6  468.14
  4687.6  466.71  4723.1  466.86  4757.9  465.60  4807.4  465.71  4896.5  464.39
  4987.6  463.21  4988.1  462.41  4993.1  462.41  4993.6  463.21  5018.3  463.32
  5086.1  463.87  5158.9  463.57  5209.9  464.38  5235.4  464.33  5240.9  464.84
  5276.2  464.90  5302.9  465.76  5354.4  466.48  5364.7  466.94  5515.3  469.86
  5580.1  471.03  5600.7  471.07  5672.5  473.15  5682.7  473.07  5735.8  474.17
#Mann=5,-1,0
  4471.5    0.05       0  4896.5     0.1       0  4987.6    0.07       0
  4993.6     0.1       0  5018.3    0.05       0
Bank Sta=4987.6,4993.6
Exp/Cntr=0.3,0.1

Type RM Length L Ch R = 1,19479,43,43,43
BEGIN DESCRIPTION:
Mapping XS 19939731
END DESCRIPTION:
XS GIS Cut Line= 4
      2058430.01     13481493.11      2058241.61     13481788.00
      2058200.82     13481950.33      2058360.28     13482596.13
#Sta/Elev= 30
  4599.7  468.21  4649.4  467.37  4661.3  467.51  4685.0  466.18  4707.0  465.49
  4743.4  465.50  4764.5  464.46  4806.8  464.08  4851.1  462.80  4867.3  462.80
  4954.0  462.26  4995.1  459.35  5074.4  459.18  5074.9  458.38  5079.9  458.38
  5080.4  459.18  5100.4  460.86  5116.8  462.09  5173.3  462.57  5275.8  461.90
  5358.7  463.49  5420.5  464.08  5523.5  466.49  5571.2  466.83  5585.3  467.55
  5612.6  467.69  5626.5  468.50  5654.1  469.27  5737.0  470.51  5782.2  471.78
#Mann=5,-1,0
  4599.7    0.05       0  4867.3     0.1       0  5074.4    0.07       0
  5080.4     0.1       0  5100.4    0.05       0
Bank Sta=5074.4,5080.4
Exp/Cntr=0.3,0.1

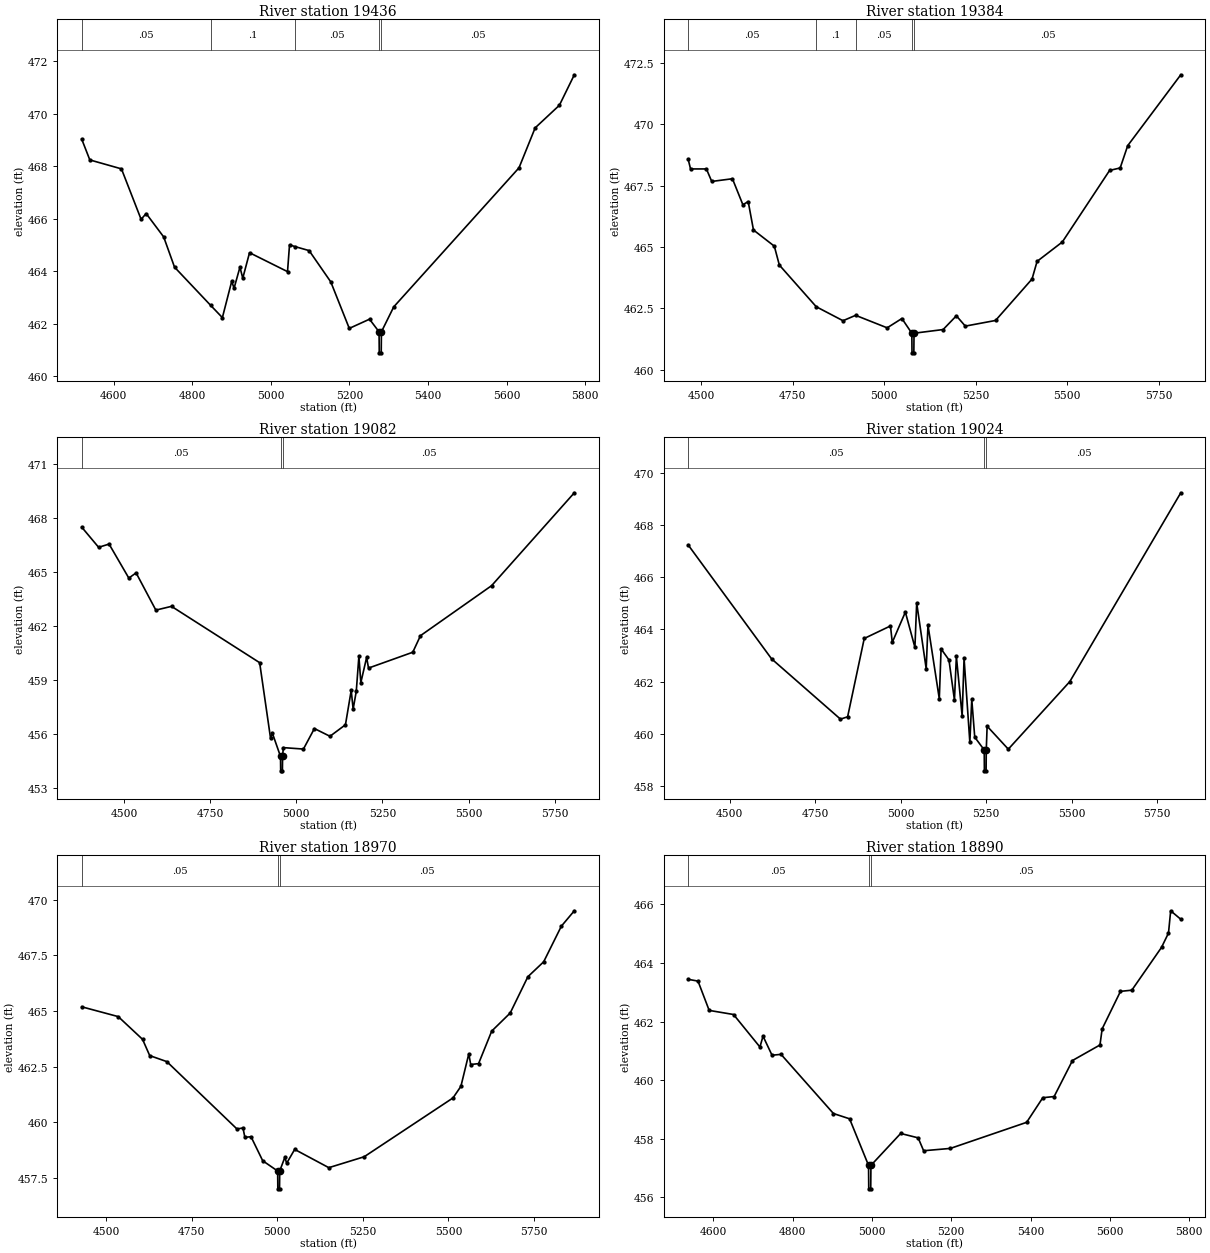
Type RM Length L Ch R = 1,19436,52,52,52
BEGIN DESCRIPTION:
Mapping XS cbe1282a
END DESCRIPTION:
XS GIS Cut Line= 4
      2058430.03     13481430.58      2058197.34     13481768.04
      2058166.09     13481972.03      2058314.98     13482591.93
#Sta/Elev= 30
  4518.7  469.03  4539.3  468.24  4619.8  467.90  4669.8  465.98  4682.7  466.20
  4727.3  465.31  4754.9  464.16  4846.6  462.71  4876.7  462.24  4900.4  463.62
  4906.5  463.36  4921.4  464.16  4928.6  463.74  4945.8  464.71  5042.5  463.99
  5047.6  465.01  5062.1  464.94  5097.5  464.79  5152.6  463.60  5199.7  461.83
  5251.2  462.18  5275.5  461.70  5276.0  460.90  5281.0  460.90  5281.5  461.70
  5312.9  462.65  5631.7  467.94  5672.8  469.46  5734.5  470.32  5772.5  471.48
#Mann=5,-1,0
  4518.7    0.05       0  4846.6     0.1       0  5062.1    0.05       0
  5275.5    0.07       0  5281.5    0.05       0
Bank Sta=5275.5,5281.5
Exp/Cntr=0.3,0.1

Type RM Length L Ch R = 1,19384,302,302,302
BEGIN DESCRIPTION:
Mapping XS d2d28bf0
END DESCRIPTION:
XS GIS Cut Line= 4
      2058400.01     13481399.99      2058146.87     13481723.16
      2058123.25     13481975.24      2058287.65     13482635.48
#Sta/Elev= 30
  4465.4  468.57  4471.8  468.18  4515.1  468.18  4529.6  467.67  4586.1  467.78
  4614.6  466.72  4629.1  466.85  4643.5  465.69  4700.4  465.03  4714.1  464.26
  4814.8  462.56  4887.8  461.99  4922.2  462.21  5008.3  461.70  5048.5  462.08
  5075.6  461.48  5076.1  460.68  5081.1  460.68  5081.6  461.48  5161.0  461.63
  5197.1  462.19  5221.6  461.77  5304.0  462.00  5403.6  463.69  5417.4  464.41
  5486.2  465.20  5615.3  468.12  5644.1  468.22  5664.7  469.13  5809.5  472.02
#Mann=5,-1,0
  4465.4    0.05       0  4814.8     0.1       0  4922.2    0.05       0
  5075.6    0.03       0  5081.6    0.05       0
Bank Sta=5075.6,5081.6
Exp/Cntr=0.3,0.1

Type RM Length L Ch R = 1,19082,58,58,58
BEGIN DESCRIPTION:
Mapping XS 8c7d17ec
END DESCRIPTION:
XS GIS Cut Line= 4
      2058284.19     13481465.32      2057881.59     13481727.33
      2057796.17     13481986.35      2058099.99     13482590.01
#Sta/Elev= 30
  4377.7  467.48  4426.7  466.36  4457.0  466.54  4514.3  464.65  4535.4  464.94
  4592.7  462.87  4638.1  463.08  4893.8  459.95  4925.5  455.74  4930.8  456.03
  4954.3  454.74  4954.8  453.94  4959.8  453.94  4960.3  454.74  4962.5  455.23
  5020.8  455.15  5052.6  456.29  5097.8  455.86  5142.7  456.50  5159.4  458.41
  5165.0  457.37  5174.1  458.36  5181.7  460.31  5187.3  458.84  5204.1  460.24
  5209.6  459.65  5338.0  460.53  5360.3  461.45  5566.7  464.23  5806.6  469.39
#Mann=3,-1,0
  4377.7    0.05       0  4954.3    0.03       0  4960.3    0.05       0
Bank Sta=4954.3,4960.3
Exp/Cntr=0.3,0.1

Type RM Length L Ch R = 1,19024,54,54,54
BEGIN DESCRIPTION:
Mapping XS 456bff55
END DESCRIPTION:
XS GIS Cut Line= 4
      2058232.11     13481441.01      2057812.84     13481741.21
      2057742.00     13481977.33      2058040.57     13482585.74
#Sta/Elev= 30
  4378.6  467.23  4622.3  462.87  4823.7  460.56  4844.6  460.65  4893.2  463.65
  4969.9  464.13  4975.1  463.50  5013.4  464.66  5041.3  463.31  5046.5  465.01
  5074.3  462.49  5079.5  464.16  5112.6  461.34  5117.8  463.25  5140.8  462.83
  5156.9  461.29  5162.5  462.96  5179.4  460.68  5185.0  462.89  5201.9  459.67
  5207.5  461.32  5216.2  459.87  5243.9  459.38  5244.4  458.58  5249.4  458.58
  5249.9  459.38  5252.4  460.29  5314.3  459.41  5494.2  462.00  5818.5  469.23
#Mann=3,-1,0
  4378.6    0.05       0  5243.9    0.03       0  5249.9    0.05       0
Bank Sta=5243.9,5249.9
Exp/Cntr=0.3,0.1

Type RM Length L Ch R = 1,18970,80,80,80
BEGIN DESCRIPTION:
Mapping XS 978e5af8
END DESCRIPTION:
XS GIS Cut Line= 4
      2058079.33     13481378.51      2057783.67     13481704.41
      2057679.50     13481940.52      2057985.55     13482614.61
#Sta/Elev= 30
  4429.3  465.19  4535.9  464.75  4606.9  463.73  4627.8  463.00  4677.8  462.73
  4882.4  459.71  4900.2  459.75  4905.7  459.33  4923.6  459.36  4957.8  458.28
  5001.4  457.82  5001.9  457.02  5006.9  457.02  5007.4  457.82  5022.3  458.43
  5027.8  458.17  5051.1  458.79  5150.8  457.97  5254.1  458.46  5513.4  461.10
  5536.5  461.62  5559.6  463.08  5565.1  462.60  5588.1  462.64  5626.5  464.10
  5680.4  464.91  5732.1  466.54  5778.2  467.21  5829.9  468.81  5867.7  469.50
#Mann=3,-1,0
  4429.3    0.05       0  5001.4    0.03       0  5007.4    0.05       0
Bank Sta=5001.4,5007.4
Exp/Cntr=0.3,0.1

Type RM Length L Ch R = 1,18890,113,113,113
BEGIN DESCRIPTION:
Mapping XS 7489f21f
END DESCRIPTION:
XS GIS Cut Line= 4
      2057898.01     13481477.25      2057697.47     13481573.62
      2057603.72     13482078.82      2057812.08     13482539.80
#Sta/Elev= 30
  4536.5  463.44  4561.2  463.38  4589.4  462.38  4650.8  462.24  4717.4  461.13
  4725.2  461.50  4747.9  460.85  4770.6  460.88  4902.8  458.86  4943.5  458.68
  4991.3  457.09  4991.8  456.29  4996.8  456.29  4997.3  457.09  5072.3  458.18
  5116.4  458.03  5130.2  457.59  5197.7  457.67  5390.0  458.56  5430.7  459.40
  5459.3  459.44  5505.6  460.67  5574.9  461.20  5580.4  461.75  5626.6  463.03
  5655.2  463.07  5730.1  464.53  5747.7  465.02  5753.2  465.78  5778.7  465.49
#Mann=3,-1,0
  4536.5    0.05       0  4991.3    0.03       0  4997.3    0.05       0
Bank Sta=4991.3,4997.3
Exp/Cntr=0.3,0.1

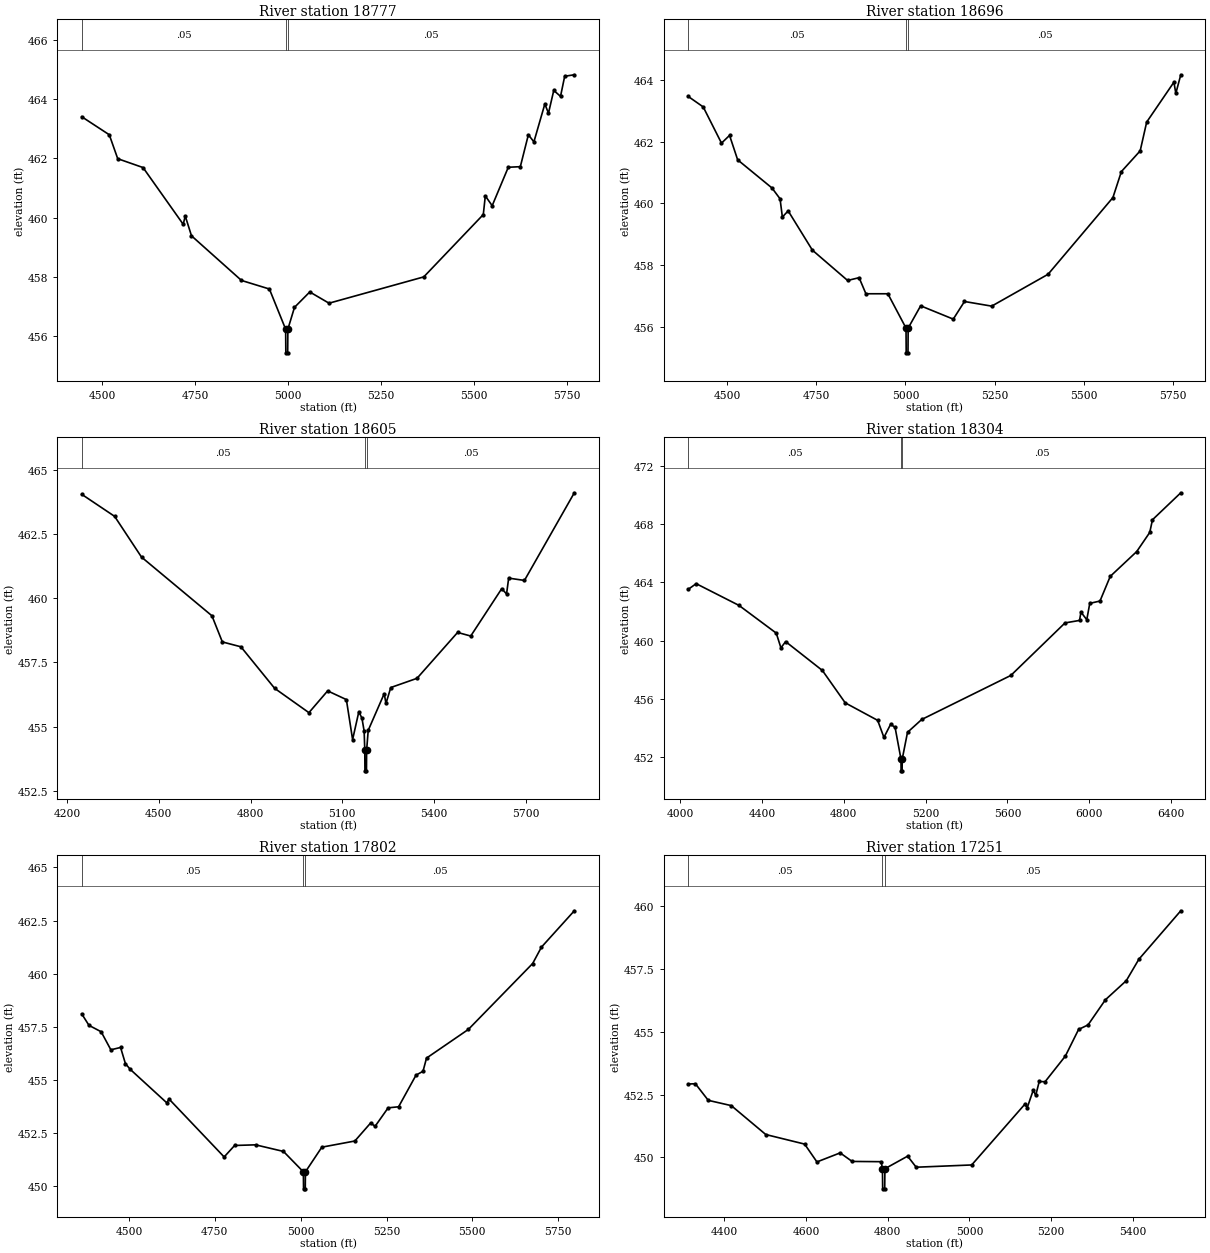
Type RM Length L Ch R = 1,18777,81,81,81
BEGIN DESCRIPTION:
Mapping XS 83b3eb36
END DESCRIPTION:
XS GIS Cut Line= 4
      2057861.56     13481430.38      2057588.10     13481560.60
      2057509.97     13481964.24      2057741.74     13482529.34
#Sta/Elev= 30
  4444.3  463.41  4518.4  462.80  4541.1  461.99  4609.2  461.69  4717.2  459.77
  4722.7  460.05  4739.5  459.38  4873.9  457.87  4949.0  457.58  4992.7  456.22
  4993.2  455.42  4998.2  455.42  4998.7  456.22  5016.5  456.96  5057.6  457.48
  5109.4  457.10  5364.2  457.99  5524.3  460.10  5529.7  460.73  5548.2  460.40
  5591.5  461.70  5623.9  461.72  5645.5  462.80  5660.4  462.56  5689.8  463.84
  5699.6  463.53  5713.8  464.30  5732.0  464.10  5743.2  464.78  5769.1  464.83
#Mann=3,-1,0
  4444.3    0.05       0  4992.7    0.03       0  4998.7    0.05       0
Bank Sta=4992.7,4998.7
Exp/Cntr=0.3,0.1

Type RM Length L Ch R = 1,18696,91,91,91
BEGIN DESCRIPTION:
Mapping XS 64560b0f
END DESCRIPTION:
XS GIS Cut Line= 4
      2057832.93     13481399.12      2057517.79     13481550.18
      2057429.24     13481940.80      2057676.31     13482520.76
#Sta/Elev= 30
  4391.4  463.46  4433.5  463.12  4484.7  461.95  4507.3  462.20  4530.0  461.41
  4626.2  460.50  4648.8  460.15  4655.3  459.56  4671.5  459.76  4739.4  458.49
  4838.1  457.51  4870.3  457.60  4889.4  457.08  4950.9  457.08  5001.8  455.97
  5002.3  455.17  5007.3  455.17  5007.8  455.97  5042.8  456.69  5134.2  456.26
  5165.6  456.83  5241.9  456.68  5399.9  457.71  5581.6  460.19  5605.3  461.03
  5658.0  461.70  5676.2  462.63  5752.5  463.92  5757.9  463.56  5771.8  464.16
#Mann=3,-1,0
  4391.4    0.05       0  5001.8    0.03       0  5007.8    0.05       0
Bank Sta=5001.8,5007.8
Exp/Cntr=0.3,0.1

Type RM Length L Ch R = 1,18605,301,301,301
BEGIN DESCRIPTION:
Mapping XS 3cc63d82
END DESCRIPTION:
XS GIS Cut Line= 4
      2057892.82     13481331.41      2057418.83     13481547.57
      2057330.29     13481992.89      2057653.21     13482539.77
#Sta/Elev= 30
  4248.2  464.06  4355.7  463.20  4443.6  461.61  4673.8  459.32  4707.8  458.30
  4768.5  458.11  4878.7  456.49  4990.8  455.54  5052.0  456.39  5113.2  456.05
  5133.6  454.49  5154.0  455.58  5164.2  455.32  5171.3  454.82  5173.4  454.07
  5173.9  453.27  5178.9  453.27  5179.4  454.07  5184.6  454.85  5236.9  456.28
  5242.7  455.90  5258.3  456.52  5344.1  456.88  5476.8  458.67  5519.7  458.53
  5621.1  460.38  5636.8  460.17  5643.7  460.79  5695.3  460.70  5858.3  464.12
#Mann=3,-1,0
  4248.2    0.05       0  5173.4    0.03       0  5179.4    0.05       0
Bank Sta=5173.4,5179.4
Exp/Cntr=0.3,0.1

Type RM Length L Ch R = 1,18304,502,502,502
BEGIN DESCRIPTION:
Mapping XS fbba95f5
END DESCRIPTION:
XS GIS Cut Line= 4
      2057940.38     13481218.82      2057133.67     13481592.60
      2057047.56     13481789.83      2057825.84     13482836.85
#Sta/Elev= 30
  4039.0  463.52  4078.0  463.91  4287.4  462.42  4469.6  460.52  4492.5  459.51
  4515.4  459.94  4695.2  457.96  4806.9  455.74  4965.6  454.54  4996.2  453.37
  5028.9  454.27  5050.7  454.06  5079.6  451.88  5080.1  451.08  5085.1  451.08
  5085.6  451.88  5111.5  453.72  5180.9  454.60  5616.9  457.62  5881.8  461.22
  5952.7  461.39  5959.7  461.96  5988.2  461.44  6002.8  462.56  6052.8  462.72
  6102.9  464.41  6232.3  466.11  6296.1  467.42  6309.4  468.29  6447.9  470.14
#Mann=3,-1,0
  4039.0    0.05       0  5079.6    0.03       0  5085.6    0.05       0
Bank Sta=5079.6,5085.6
Exp/Cntr=0.3,0.1

Type RM Length L Ch R = 1,17802,551,551,551
BEGIN DESCRIPTION:
Mapping XS 66407243
END DESCRIPTION:
XS GIS Cut Line= 4
      2056960.41     13481120.54      2056693.03     13481391.39
      2056550.67     13482186.53      2056588.86     13482429.57
#Sta/Elev= 30
  4362.5  458.11  4383.6  457.57  4419.0  457.27  4447.3  456.42  4475.6  456.53
  4489.7  455.77  4503.8  455.50  4609.9  453.93  4617.0  454.10  4777.2  451.38
  4807.7  451.92  4868.7  451.95  4949.9  451.64  5007.9  450.68  5008.4  449.88
  5013.4  449.88  5013.9  450.68  5061.7  451.84  5157.8  452.13  5203.9  452.98
  5216.7  452.82  5254.7  453.69  5285.2  453.74  5336.0  455.23  5356.3  455.41
  5366.5  456.03  5488.4  457.38  5675.6  460.48  5701.2  461.25  5796.9  462.96
#Mann=3,-1,0
  4362.5    0.05       0  5007.9    0.03       0  5013.9    0.05       0
Bank Sta=5007.9,5013.9
Exp/Cntr=0.3,0.1

Type RM Length L Ch R = 1,17251,368,368,368
BEGIN DESCRIPTION:
Mapping XS 7c475e69
END DESCRIPTION:
XS GIS Cut Line= 4
      2056654.83     13481283.75      2056377.06     13481377.50
      2055984.70     13481912.22      2056036.79     13482155.31
#Sta/Elev= 30
  4312.1  452.92  4329.7  452.93  4361.2  452.27  4417.5  452.06  4501.9  450.91
  4596.9  450.53  4627.0  449.82  4683.8  450.18  4713.1  449.84  4784.1  449.83
  4787.3  449.55  4787.8  448.75  4792.8  448.75  4793.3  449.55  4848.9  450.05
  4869.8  449.61  5005.6  449.70  5135.3  452.11  5141.5  451.98  5156.1  452.67
  5162.3  452.47  5170.8  453.02  5185.1  453.01  5234.7  454.03  5267.1  455.09
  5290.2  455.27  5332.7  456.27  5383.8  457.03  5414.5  457.88  5517.1  459.81
#Mann=3,-1,0
  4312.1    0.05       0  4787.3    0.03       0  4793.3    0.05       0
Bank Sta=4787.3,4793.3
Exp/Cntr=0.3,0.1

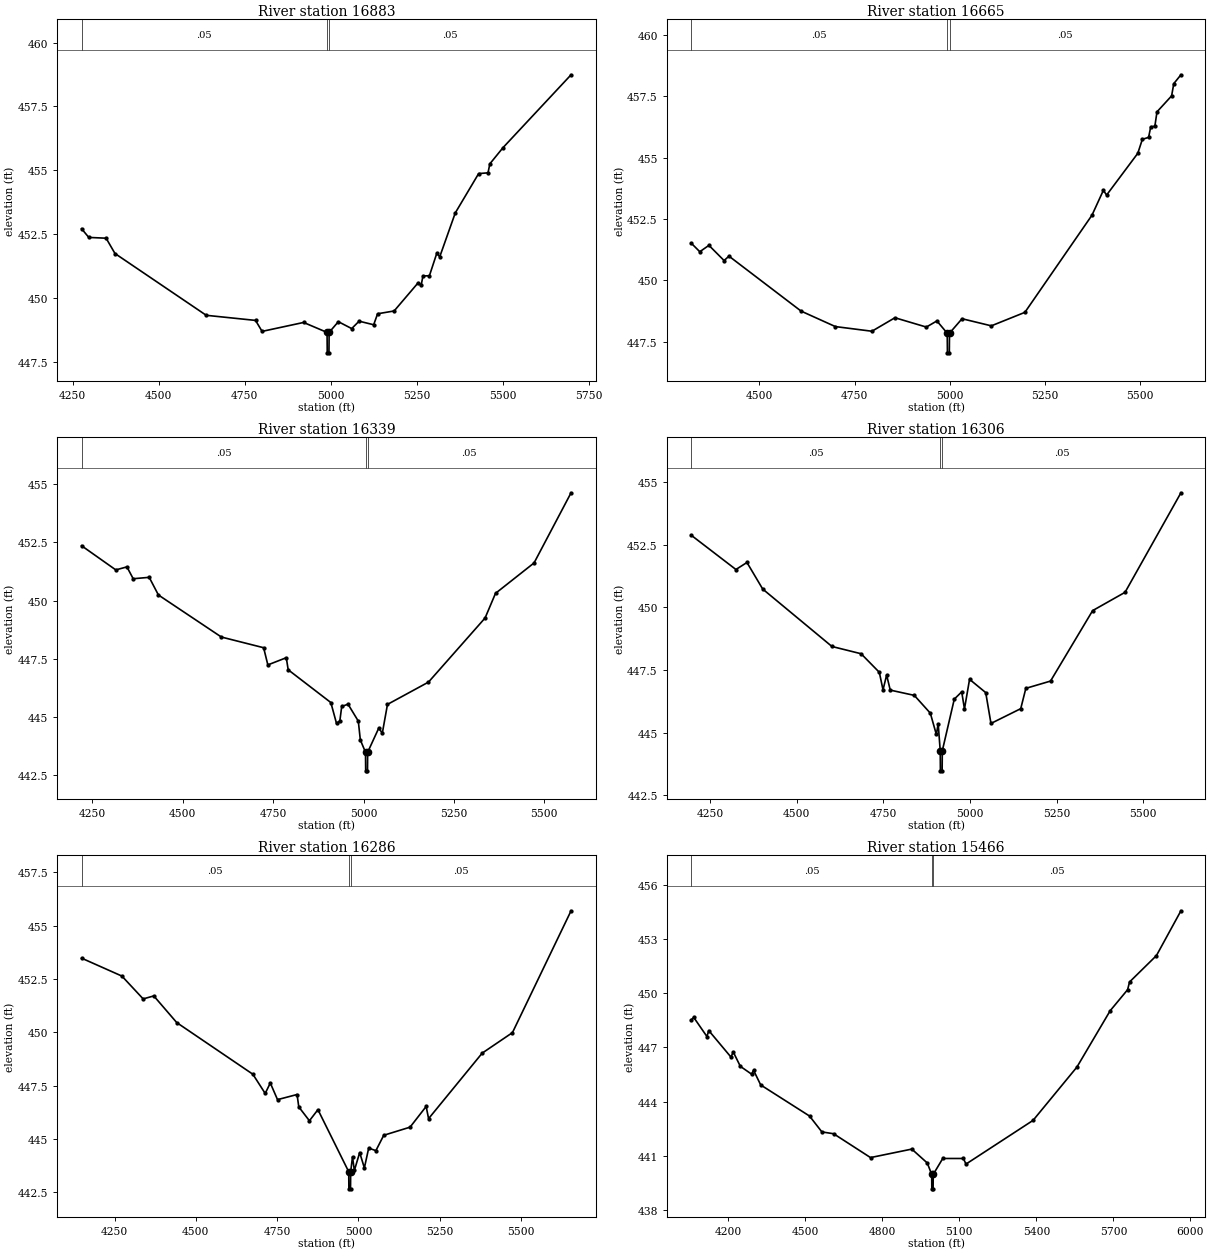
Type RM Length L Ch R = 1,16883,218,218,218
BEGIN DESCRIPTION:
Mapping XS a78136e7
END DESCRIPTION:
XS GIS Cut Line= 4
      2056595.85     13481259.44      2056276.36     13481294.17
      2055512.48     13481596.25      2055429.13     13481863.65
#Sta/Elev= 30
  4276.2  452.71  4297.2  452.37  4347.5  452.34  4373.3  451.74  4638.6  449.32
  4781.9  449.12  4800.9  448.69  4921.6  449.04  4989.8  448.65  4990.3  447.85
  4995.3  447.85  4995.8  448.65  5022.6  449.07  5061.4  448.80  5082.9  449.09
  5125.3  448.95  5136.7  449.38  5184.8  449.49  5255.0  450.60  5263.2  450.49
  5268.6  450.86  5287.3  450.87  5308.8  451.75  5317.3  451.61  5362.5  453.33
  5430.4  454.87  5457.7  454.90  5462.9  455.25  5501.5  455.89  5699.1  458.74
#Mann=3,-1,0
  4276.2    0.05       0  4989.8    0.03       0  4995.8    0.05       0
Bank Sta=4989.8,4995.8
Exp/Cntr=0.3,0.1

Type RM Length L Ch R = 1,16665,326,326,326
BEGIN DESCRIPTION:
Mapping XS d1d71dcf
END DESCRIPTION:
XS GIS Cut Line= 3
      2056458.61     13481237.54      2056070.71     13481110.77
      2055294.79     13481519.54
#Sta/Elev= 30
  4321.5  451.51  4343.4  451.17  4367.4  451.43  4407.2  450.81  4420.0  450.99
  4609.4  448.75  4699.3  448.12  4795.3  447.93  4855.7  448.48  4938.2  448.10
  4965.9  448.35  4993.0  447.85  4993.5  447.05  4998.5  447.05  4999.0  447.85
  5031.9  448.44  5108.8  448.15  5196.9  448.70  5373.1  452.66  5402.9  453.67
  5411.5  453.48  5493.3  455.18  5505.3  455.75  5521.7  455.83  5527.3  456.26
  5538.1  456.28  5543.7  456.87  5582.1  457.52  5587.8  458.02  5606.6  458.38
#Mann=3,-1,0
  4321.5    0.05       0  4993.0    0.03       0  4999.0    0.05       0
Bank Sta=4993,4999
Exp/Cntr=0.3,0.1

Type RM Length L Ch R = 1,16339,33,33,33
BEGIN DESCRIPTION:
Mapping XS 7a41d43d
END DESCRIPTION:
XS GIS Cut Line= 4
      2056519.46     13481231.68      2055849.50     13480992.78
      2055747.42     13480945.56      2055335.56     13481280.14
#Sta/Elev= 30
  4219.8  452.36  4314.5  451.32  4345.3  451.45  4362.6  450.94  4406.9  451.00
  4432.4  450.24  4606.6  448.43  4723.5  447.97  4735.2  447.23  4786.2  447.54
  4791.5  447.02  4909.5  445.61  4925.2  444.71  4934.4  444.82  4939.6  445.44
  4957.0  445.54  4985.5  444.81  4991.1  444.00  5005.4  443.47  5005.9  442.67
  5010.9  442.67  5011.4  443.47  5042.1  444.51  5051.9  444.29  5066.2  445.53
  5179.7  446.49  5336.3  449.25  5365.1  450.31  5471.8  451.62  5574.2  454.64
#Mann=3,-1,0
  4219.8    0.05       0  5005.4    0.03       0  5011.4    0.05       0
Bank Sta=5005.4,5011.4
Exp/Cntr=0.3,0.1

Type RM Length L Ch R = 1,16306,20,20,20
BEGIN DESCRIPTION:
Mapping XS 0cd0c9b3
END DESCRIPTION:
XS GIS Cut Line= 5
      2056550.62     13481200.40      2055850.19     13480971.25
      2055787.69     13480926.11      2055752.28     13480921.25
      2055293.70     13481249.05
#Sta/Elev= 30
  4195.8  452.87  4324.2  451.51  4356.1  451.79  4401.6  450.73  4601.5  448.44
  4685.7  448.15  4738.3  447.41  4749.0  446.71  4759.4  447.30  4769.9  446.70
  4839.3  446.49  4885.6  445.78  4903.0  444.93  4908.3  445.36  4914.2  444.28
  4914.7  443.48  4919.7  443.48  4920.2  444.28  4954.8  446.34  4976.2  446.63
  4984.2  445.95  4998.9  447.13  5045.6  446.60  5060.7  445.37  5146.7  445.96
  5161.4  446.77  5232.7  447.06  5354.3  449.87  5447.9  450.60  5609.3  454.57
#Mann=3,-1,0
  4195.8    0.05       0  4914.2    0.03       0  4920.2    0.05       0
Bank Sta=4914.2,4920.2
Exp/Cntr=0.3,0.1

Type RM Length L Ch R = 1,16286,820,820,820
BEGIN DESCRIPTION:
Mapping XS 1eb5de64
END DESCRIPTION:
XS GIS Cut Line= 4
      2056609.74     13481176.13      2055867.55     13480947.64
      2055745.33     13480883.75      2055255.52     13481214.31
#Sta/Elev= 30
  4148.7  453.48  4272.7  452.64  4338.1  451.57  4370.8  451.71  4441.4  450.46
  4675.5  448.04  4713.4  447.14  4729.1  447.63  4751.3  446.85  4811.4  447.09
  4816.7  446.51  4849.4  445.86  4875.6  446.38  4970.3  443.47  4970.8  442.67
  4975.8  442.67  4976.3  443.47  4981.9  444.17  4987.6  443.53  5004.0  444.37
  5018.4  443.65  5031.7  444.58  5053.8  444.46  5078.0  445.18  5158.9  445.56
  5208.4  446.53  5215.9  445.96  5380.8  449.03  5473.8  449.99  5654.1  455.70
#Mann=3,-1,0
  4148.7    0.05       0  4970.3    0.03       0  4976.3    0.05       0
Bank Sta=4970.3,4976.3
Exp/Cntr=0.3,0.1

Type RM Length L Ch R = 1,15466,813,813,813
BEGIN DESCRIPTION:
Mapping XS 8941ae1e
END DESCRIPTION:
XS GIS Cut Line= 4
      2056491.62     13480492.07      2055963.86     13480151.81
      2055078.45     13480235.14      2054897.92     13480578.85
#Sta/Elev= 30
  4057.3  448.53  4066.1  448.66  4117.6  447.60  4124.7  447.93  4211.3  446.46
  4219.9  446.75  4247.6  445.95  4291.2  445.52  4299.1  445.73  4326.9  444.92
  4516.9  443.20  4565.1  442.32  4610.6  442.22  4754.4  440.90  4915.1  441.37
  4975.4  440.60  4992.5  439.97  4993.0  439.17  4998.0  439.17  4998.5  439.97
  5035.6  440.85  5116.0  440.85  5126.0  440.54  5387.2  442.96  5557.9  445.91
  5687.4  449.03  5755.1  450.19  5762.8  450.62  5867.4  452.08  5962.8  454.56
#Mann=3,-1,0
  4057.3    0.05       0  4992.5    0.03       0  4998.5    0.05       0
Bank Sta=4992.5,4998.5
Exp/Cntr=0.3,0.1

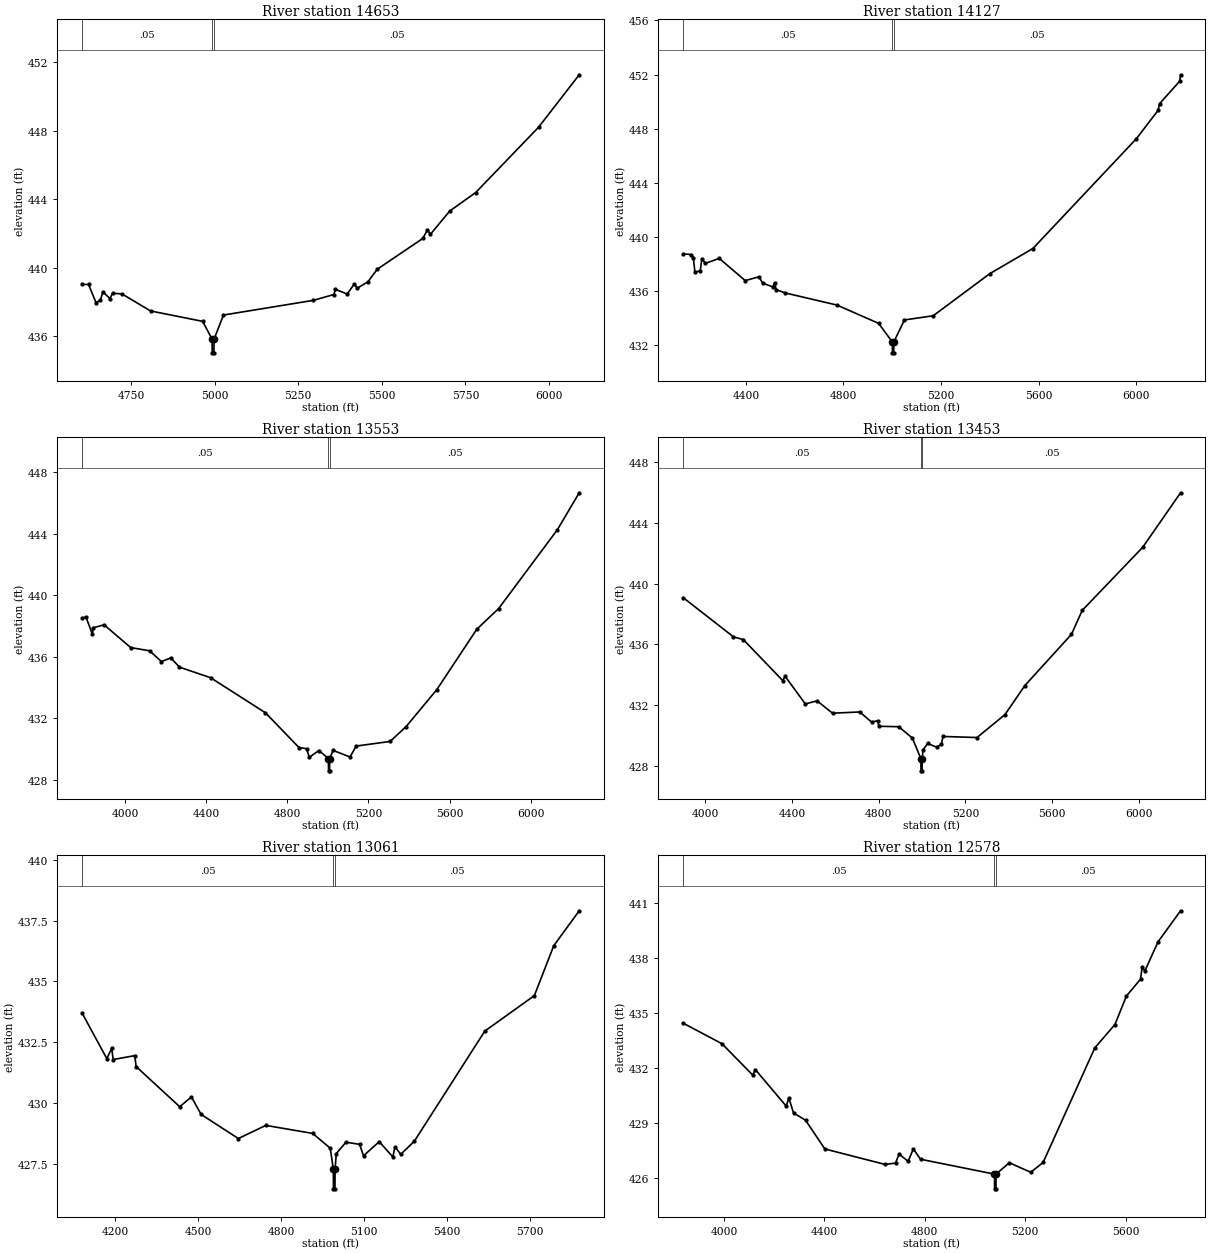
Type RM Length L Ch R = 1,14653,526,526,526
BEGIN DESCRIPTION:
Mapping XS 4f3acae3
END DESCRIPTION:
XS GIS Cut Line= 4
      2055637.46     13479620.54      2055449.98     13479467.78
      2054901.36     13479613.61      2054609.85     13480224.41
#Sta/Elev= 30
  4603.8  439.01  4623.4  439.01  4645.7  437.95  4658.6  438.08  4666.5  438.58
  4687.3  438.18  4695.2  438.49  4723.1  438.46  4808.7  437.46  4964.6  436.85
  4992.7  435.81  4993.2  435.01  4998.2  435.01  4998.7  435.81  5026.7  437.22
  5295.7  438.08  5356.5  438.42  5361.6  438.72  5396.6  438.45  5418.4  439.05
  5425.9  438.78  5458.3  439.16  5486.5  439.90  5622.6  441.70  5636.5  442.20
  5645.3  441.94  5702.9  443.30  5780.5  444.38  5968.5  448.20  6090.1  451.27
#Mann=3,-1,0
  4603.8    0.05       0  4992.7    0.03       0  4998.7    0.05       0
Bank Sta=4992.7,4998.7
Exp/Cntr=0.3,0.1

Type RM Length L Ch R = 1,14127,574,574,574
BEGIN DESCRIPTION:
Mapping XS 974c3ec7
END DESCRIPTION:
XS GIS Cut Line= 4
      2055647.92     13479599.75      2055199.98     13479085.83
      2054772.89     13479193.47      2054349.64     13480005.29
#Sta/Elev= 30
  4143.8  438.75  4177.2  438.69  4184.8  438.47  4191.4  437.39  4213.3  437.50
  4219.9  438.40  4234.1  438.04  4291.1  438.41  4397.4  436.77  4454.4  437.05
  4468.5  436.59  4510.4  436.30  4518.0  436.61  4524.6  436.10  4560.7  435.86
  4773.4  434.96  4944.1  433.61  5000.5  432.23  5001.0  431.43  5006.0  431.43
  5006.5  432.23  5049.8  433.86  5167.9  434.17  5399.7  437.28  5576.4  439.14
  6000.7  447.26  6089.8  449.36  6095.4  449.84  6178.1  451.51  6181.5  451.98
#Mann=3,-1,0
  4143.8    0.05       0  5000.5    0.03       0  5006.5    0.05       0
Bank Sta=5000.5,5006.5
Exp/Cntr=0.3,0.1

Type RM Length L Ch R = 1,13553,100,100,100
BEGIN DESCRIPTION:
Mapping XS bc981e6a
END DESCRIPTION:
XS GIS Cut Line= 4
      2055637.45     13479551.07      2055062.00     13478589.65
      2054875.19     13478585.49      2054262.82     13479550.57
#Sta/Elev= 30
  3788.3  438.50  3807.8  438.60  3839.0  437.49  3844.8  437.89  3897.3  438.08
  4028.5  436.60  4121.7  436.39  4180.0  435.69  4226.0  435.93  4268.7  435.33
  4422.4  434.64  4692.7  432.36  4858.0  430.10  4895.0  430.03  4908.6  429.47
  4955.8  429.91  5002.8  429.39  5003.3  428.59  5008.3  428.59  5008.8  429.39
  5025.8  429.92  5109.1  429.49  5139.6  430.20  5306.5  430.50  5385.3  431.46
  5536.9  433.87  5734.3  437.80  5841.2  439.13  6131.6  444.27  6238.6  446.66
#Mann=3,-1,0
  3788.3    0.05       0  5002.8    0.03       0  5008.8    0.05       0
Bank Sta=5002.8,5008.8
Exp/Cntr=0.3,0.1

Type RM Length L Ch R = 1,13453,392,392,392
BEGIN DESCRIPTION:
Mapping XS 1eead2a2
END DESCRIPTION:
XS GIS Cut Line= 4
      2055878.12     13477974.18      2055000.00     13478450.00
      2054810.79     13478622.37      2054185.97     13479450.25
#Sta/Elev= 30
  3899.5  439.07  4130.5  436.50  4176.0  436.32  4358.1  433.62  4368.6  433.91
  4461.8  432.09  4516.0  432.29  4587.3  431.48  4712.8  431.56  4767.0  430.90
  4794.6  430.98  4801.6  430.62  4892.6  430.59  4955.0  429.85  4994.5  428.49
  4995.0  427.69  5000.2  427.69  5000.7  428.49  5004.3  429.06  5025.9  429.49
  5067.8  429.24  5089.5  429.45  5096.2  429.95  5253.3  429.88  5382.3  431.39
  5473.9  433.30  5688.3  436.66  5738.3  438.24  6017.2  442.39  6191.4  445.97
#Mann=3,-1,0
  3899.5    0.05       0  4994.5    0.03       0  5000.7    0.05       0
Bank Sta=4994.5,5000.7
Exp/Cntr=0.3,0.1

Type RM Length L Ch R = 1,13061,483,483,483
BEGIN DESCRIPTION:
Mapping XS a668718c
END DESCRIPTION:
XS GIS Cut Line= 4
      2055342.30     13477783.76      2055002.06     13477867.08
      2054262.48     13478703.89      2054248.59     13479037.21
#Sta/Elev= 30
  4078.6  433.70  4168.5  431.82  4186.4  432.24  4191.6  431.78  4269.6  431.94
  4274.8  431.49  4432.4  429.84  4475.1  430.24  4510.2  429.52  4644.9  428.53
  4744.4  429.07  4914.2  428.74  4977.8  428.13  4988.9  427.26  4989.4  426.46
  4994.7  426.46  4995.2  427.26  4999.6  427.91  5034.7  428.38  5084.0  428.29
  5098.2  427.82  5155.1  428.40  5204.5  427.77  5212.0  428.19  5232.9  427.88
  5282.3  428.42  5537.4  432.95  5716.9  434.41  5787.0  436.46  5879.3  437.90
#Mann=3,-1,0
  4078.6    0.05       0  4988.9    0.03       0  4995.2    0.05       0
Bank Sta=4988.9,4995.2
Exp/Cntr=0.3,0.1

Type RM Length L Ch R = 1,12578,401,401,401
BEGIN DESCRIPTION:
Mapping XS 528041f7
END DESCRIPTION:
XS GIS Cut Line= 4
      2055234.74     13477561.52      2054595.81     13477707.36
      2053953.45     13478273.33      2053811.30     13478720.59
#Sta/Elev= 30
  3837.9  434.44  3991.5  433.33  4114.6  431.62  4124.8  431.92  4247.9  429.93
  4258.2  430.38  4277.0  429.56  4325.1  429.16  4401.8  427.60  4641.0  426.76
  4683.2  426.83  4697.4  427.32  4733.4  426.93  4754.3  427.60  4782.8  427.04
  5077.5  426.23  5078.0  425.43  5083.3  425.43  5083.8  426.23  5136.7  426.85
  5222.0  426.33  5271.4  426.87  5477.1  433.10  5557.3  434.37  5603.0  435.92
  5659.3  436.84  5665.9  437.51  5676.4  437.28  5729.0  438.87  5818.7  440.56
#Mann=3,-1,0
  3837.9    0.05       0  5077.5    0.03       0  5083.8    0.05       0
Bank Sta=5077.5,5083.8
Exp/Cntr=0.3,0.1