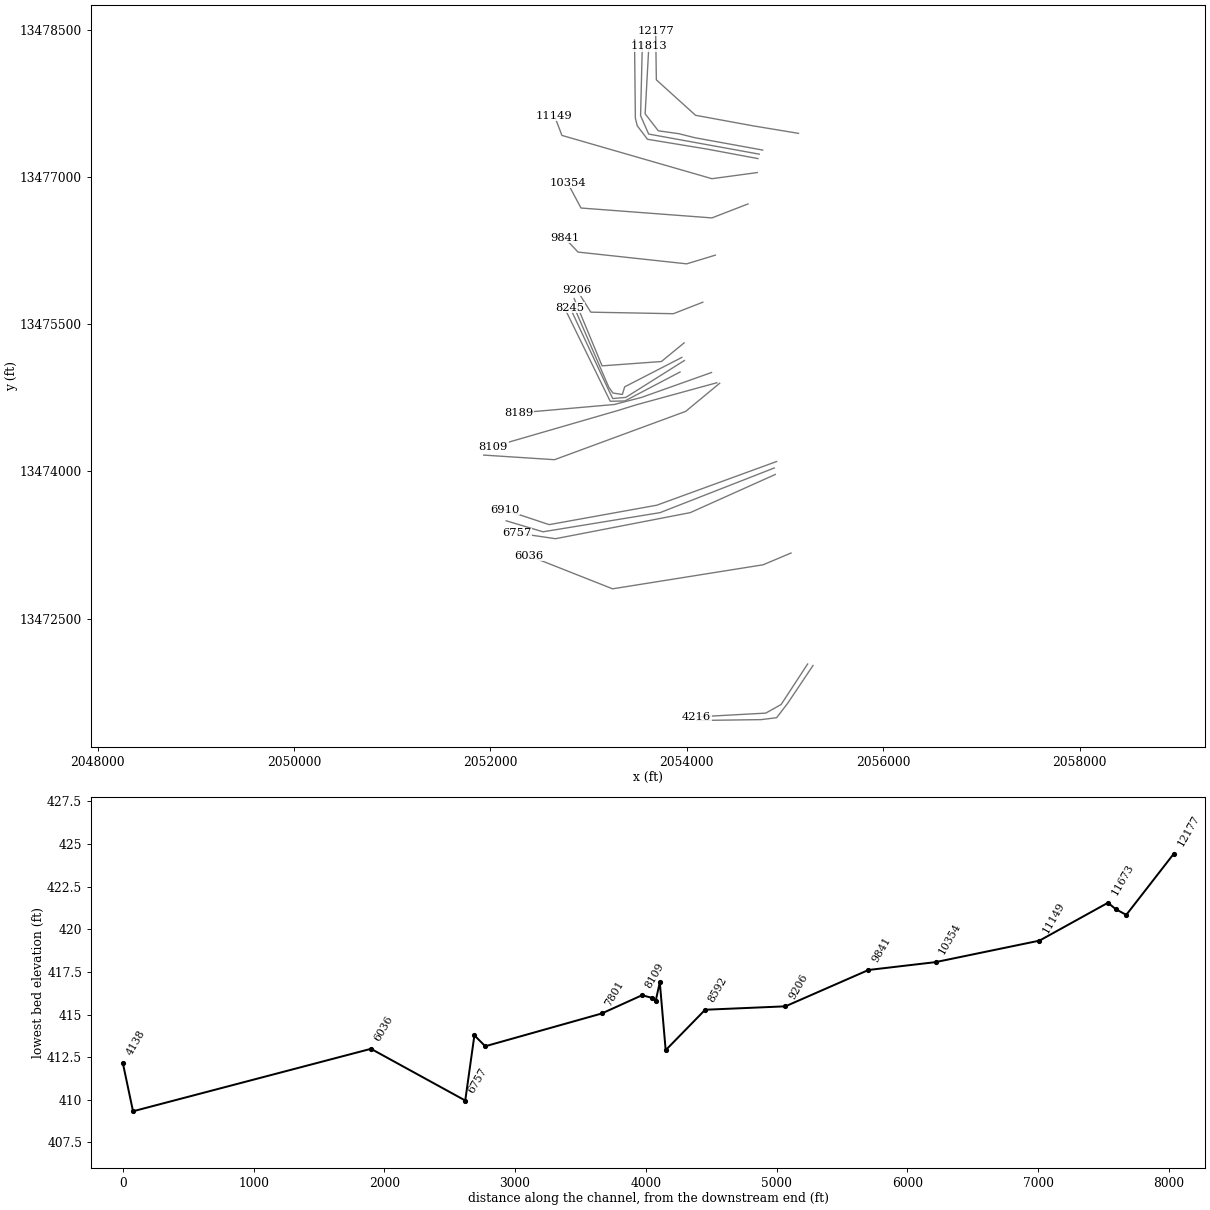
HEC-RAS study UNT 71 in Lagunillas Cr Wtrshd.prj: UNT 71 in Lagunillas Cr Wtrshd Base Level Engineering

--- UNT 71 in Lagunillas Cr Wtrshd.g01 (geometry) --- (continued)

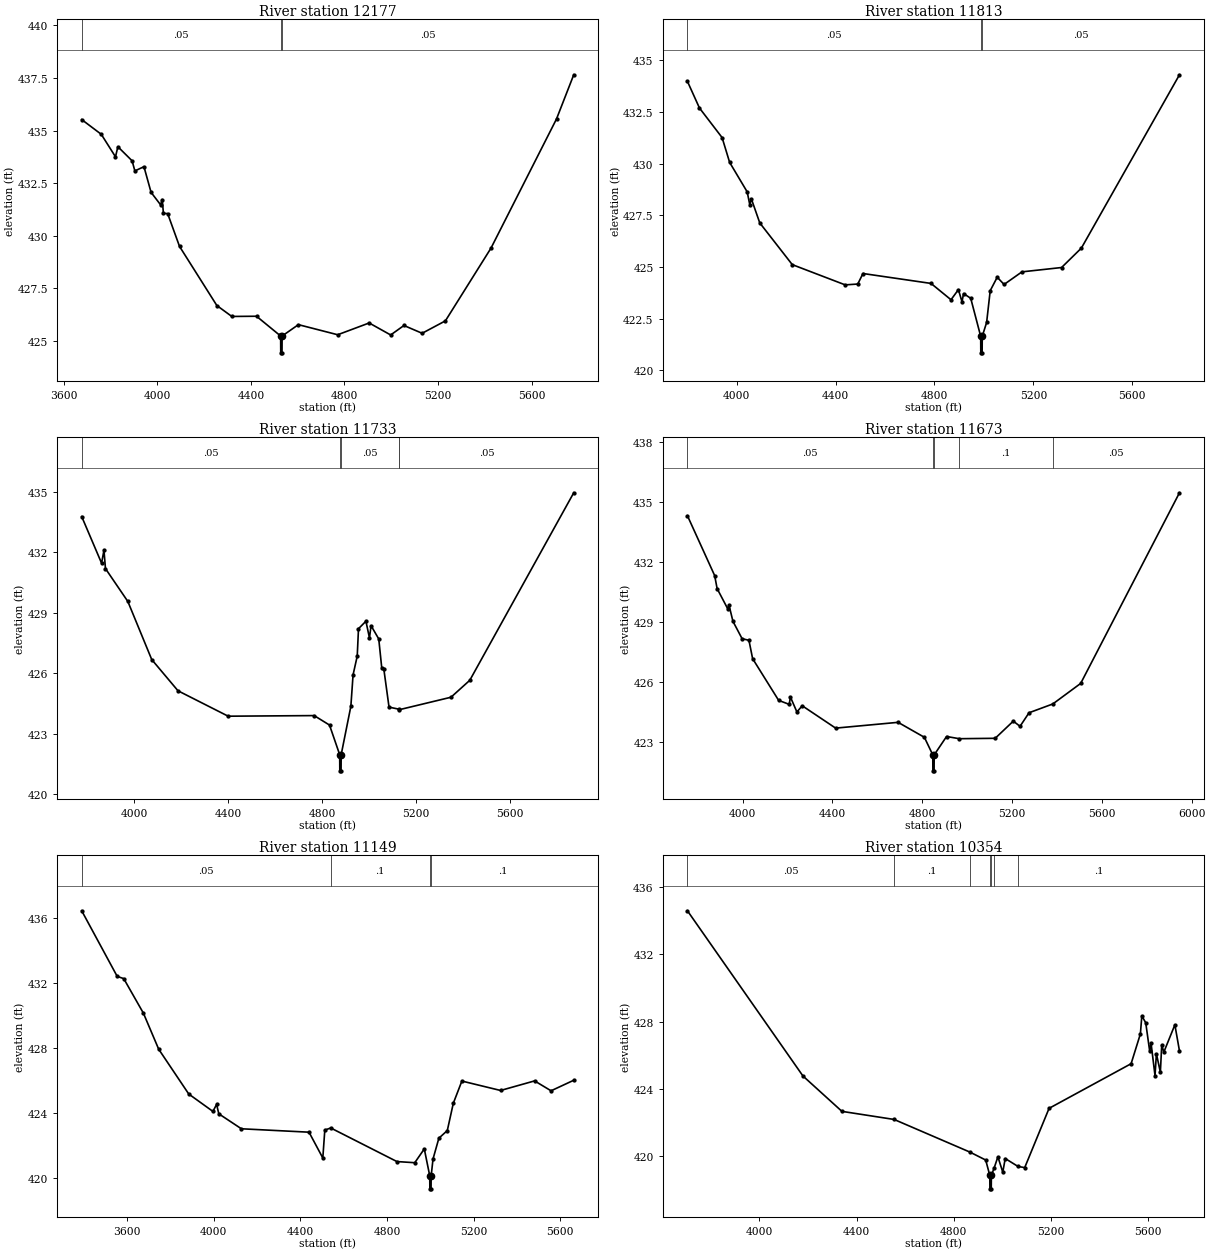
Type RM Length L Ch R = 1,12177,364,364,364
BEGIN DESCRIPTION:
Mapping XS 11b9b024
END DESCRIPTION:
XS GIS Cut Line= 5
      2055137.51     13477443.47      2054675.67     13477519.86
      2054088.86     13477627.50      2053689.56     13477988.61
      2053682.61     13478488.58
#Sta/Elev= 30
  3676.8  435.52  3760.4  434.82  3821.2  433.75  3831.4  434.23  3892.2  433.56
  3904.0  433.08  3942.9  433.28  3973.3  432.06  4013.8  431.47  4021.0  431.72
  4026.1  431.06  4044.2  431.05  4094.9  429.49  4254.4  426.68  4318.4  426.16
  4424.0  426.17  4527.1  425.23  4527.6  424.43  4532.9  424.43  4533.4  425.23
  4603.1  425.77  4771.0  425.29  4905.5  425.85  4997.4  425.28  5054.2  425.73
  5131.9  425.36  5231.3  425.95  5426.3  429.41  5706.3  435.55  5779.9  437.65
#Mann=3,-1,0
  3676.8    0.05       0  4527.1    0.03       0  4533.4    0.05       0
Bank Sta=4527.1,4533.4
Exp/Cntr=0.3,0.1

Type RM Length L Ch R = 1,11813,80,80,80
BEGIN DESCRIPTION:
Mapping XS 6a09b334
END DESCRIPTION:
XS GIS Cut Line= 6
      2054772.90     13477273.33      2054085.39     13477398.33
      2053918.73     13477440.00      2053709.31     13477469.69
      2053575.45     13477642.60      2053613.11     13478331.22
#Sta/Elev= 30
  3800.8  433.98  3849.5  432.69  3941.0  431.26  3971.5  430.06  4042.6  428.63
  4052.8  428.02  4059.8  428.28  4093.4  427.13  4224.9  425.11  4439.0  424.13
  4489.8  424.17  4510.9  424.68  4786.2  424.20  4867.0  423.41  4897.0  423.90
  4911.5  423.31  4917.8  423.71  4946.8  423.48  4987.1  421.64  4987.6  420.84
  4992.9  420.84  4993.4  421.64  5011.1  422.31  5025.6  423.85  5054.0  424.50
  5081.7  424.15  5154.0  424.76  5314.3  424.97  5394.4  425.91  5791.2  434.30
#Mann=3,-1,0
  3800.8    0.05       0  4987.1    0.03       0  4993.4    0.05       0
Bank Sta=4987.1,4993.4
Exp/Cntr=0.3,0.1

Type RM Length L Ch R = 1,11733,60,60,60
BEGIN DESCRIPTION:
Mapping XS 013b94ca
END DESCRIPTION:
XS GIS Cut Line= 4
      2054738.15     13477231.67      2053611.39     13477436.35
      2053529.10     13477623.33      2053547.20     13478367.13
#Sta/Elev= 30
  3777.4  433.78  3861.9  431.47  3872.1  432.11  3878.5  431.20  3973.7  429.57
  4075.3  426.69  4187.1  425.14  4400.6  423.88  4766.5  423.91  4831.8  423.44
  4875.1  421.97  4875.6  421.17  4880.9  421.17  4881.4  421.97  4922.6  424.37
  4932.0  425.93  4949.7  426.86  4955.1  428.22  4986.7  428.59  5001.8  427.76
  5008.5  428.37  5041.3  427.71  5053.9  426.29  5063.1  426.20  5085.0  424.33
  5126.2  424.23  5127.9  424.20  5348.6  424.82  5428.6  425.66  5870.9  434.96
#Mann=5,-1,0
  3777.4    0.05       0  4875.1    0.03       0  4881.4    0.05       0
  5126.2     0.1       0  5127.9    0.05       0
Bank Sta=4875.1,4881.4
Exp/Cntr=0.3,0.1

Type RM Length L Ch R = 1,11673,524,524,524
BEGIN DESCRIPTION:
Mapping XS e7a2d835
END DESCRIPTION:
XS GIS Cut Line= 6
      2054724.26     13477186.53      2054203.45     13477283.75
      2053599.41     13477383.23      2053495.25     13477520.21
      2053475.97     13477596.77      2053467.34     13478394.91
#Sta/Elev= 30
  3754.6  434.33  3875.9  431.33  3886.8  430.68  3934.4  429.66  3939.5  429.86
  3957.3  429.04  3998.0  428.17  4028.5  428.09  4044.9  427.17  4160.8  425.08
  4208.0  424.88  4213.1  425.25  4242.1  424.50  4265.8  424.81  4414.6  423.69
  4692.7  423.98  4809.8  423.23  4847.2  422.35  4847.7  421.55  4853.0  421.55
  4853.5  422.35  4908.6  423.27  4965.5  423.16  5125.2  423.18  5205.8  424.04
  5235.8  423.78  5275.9  424.46  5381.7  424.90  5505.9  425.93  5945.8  435.48
#Mann=5,-1,0
  3754.6    0.05       0  4847.2    0.07       0  4853.5    0.05       0
  4965.5     0.1       0  5381.7    0.05       0
Bank Sta=4847.2,4853.5
Exp/Cntr=0.3,0.1

Type RM Length L Ch R = 1,11149,795,795,795
BEGIN DESCRIPTION:
Mapping XS 546cdbfe
END DESCRIPTION:
XS GIS Cut Line= 4
      2054717.33     13477044.17      2054255.53     13476981.67
      2052727.75     13477422.64      2052651.38     13477623.99
#Sta/Elev= 30
  3390.8  436.46  3554.6  432.42  3584.9  432.28  3675.7  430.15  3746.3  427.93
  3885.1  425.17  3996.5  424.10  4013.5  424.53  4023.9  423.95  4128.0  423.03
  4440.2  422.82  4503.9  421.23  4513.1  422.95  4540.5  423.08  4846.1  421.01
  4928.4  420.94  4972.4  421.79  4997.6  420.13  4998.1  419.33  5003.6  419.33
  5004.1  420.13  5012.7  421.17  5039.7  422.45  5078.6  422.92  5106.3  424.60
  5145.9  425.97  5324.5  425.39  5481.6  425.98  5557.6  425.37  5662.3  426.02
#Mann=4,-1,0
  3390.8    0.05       0  4540.5     0.1       0  4997.6    0.07       0
  5004.1     0.1       0
Bank Sta=4997.6,5004.1
Exp/Cntr=0.3,0.1

Type RM Length L Ch R = 1,10354,513,513,513
BEGIN DESCRIPTION:
Mapping XS 521173fe
END DESCRIPTION:
XS GIS Cut Line= 4
      2054623.58     13476724.72      2054255.53     13476582.36
      2052922.20     13476683.06      2052784.25     13476941.71
#Sta/Elev= 30
  3703.8  434.58  4179.2  424.77  4339.6  422.67  4554.3  422.19  4866.6  420.25
  4931.3  419.78  4948.1  418.87  4948.6  418.07  4954.1  418.07  4954.6  418.87
  4965.4  419.28  4981.5  419.97  5001.6  419.06  5011.6  419.87  5064.2  419.40
  5091.8  419.33  5192.1  422.85  5529.7  425.50  5567.9  427.27  5573.8  428.34
  5589.9  427.93  5606.2  426.24  5611.8  426.72  5628.1  424.79  5633.8  426.09
  5650.1  424.99  5655.7  426.61  5664.4  426.19  5709.8  427.81  5728.7  426.26
#Mann=7,-1,0
  3703.8    0.05       0  4554.3     0.1       0  4866.6    0.12       0
  4948.1    0.07       0  4954.6    0.12       0  4965.4    0.07       0
  5064.2     0.1       0
Bank Sta=4948.1,4954.6
Exp/Cntr=0.3,0.1

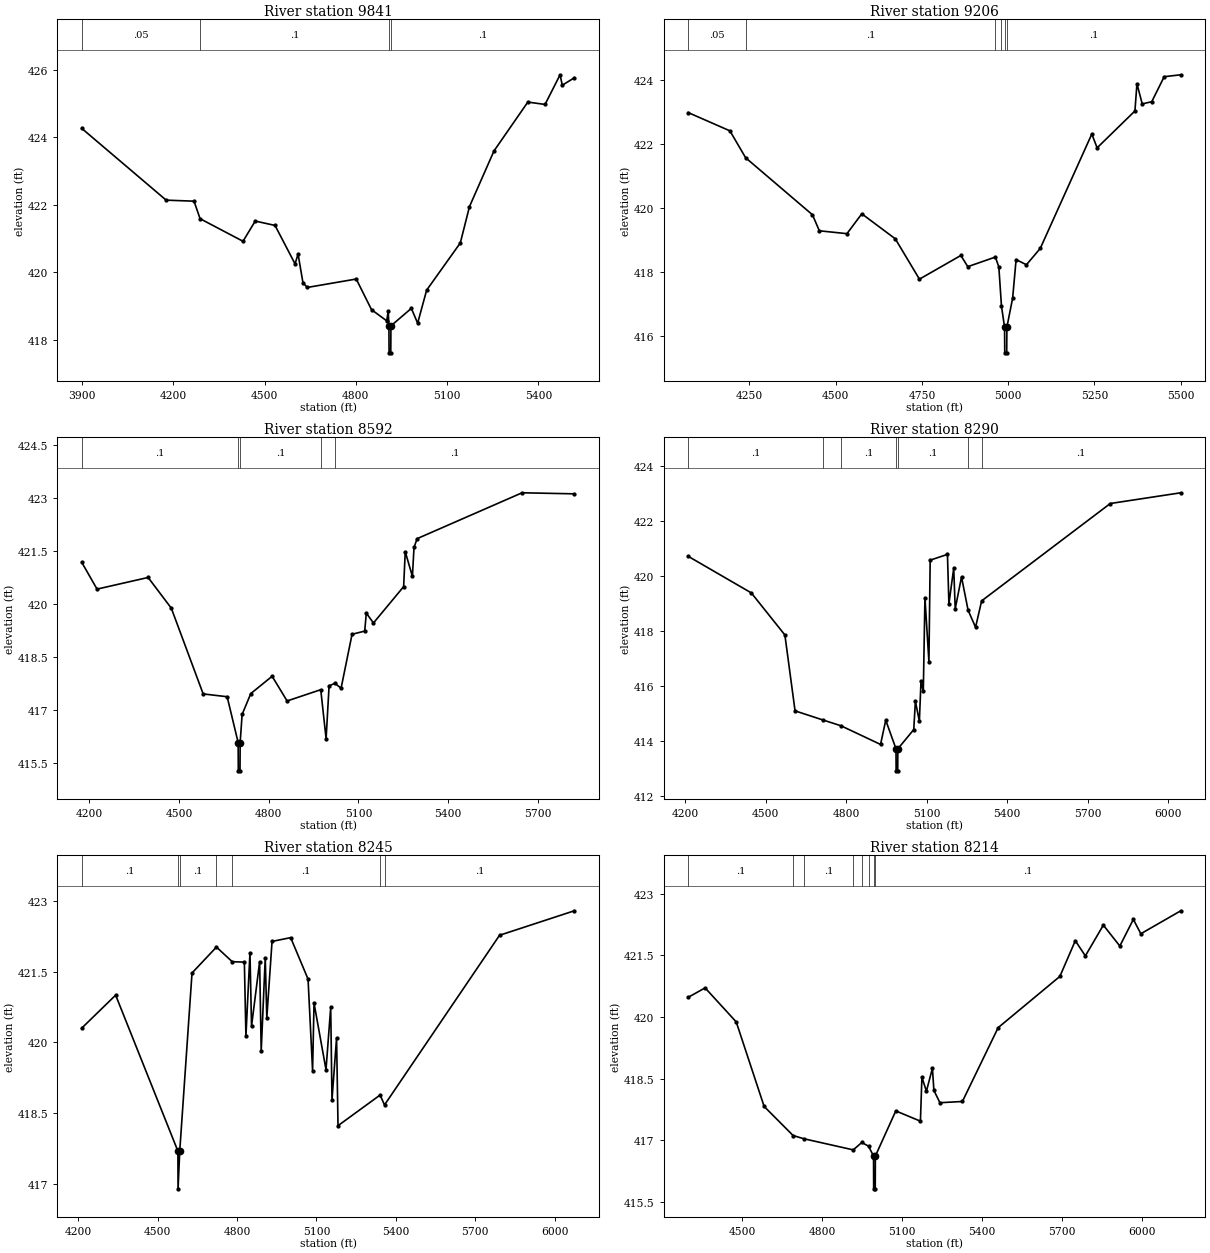
Type RM Length L Ch R = 1,9841,635,635,635
BEGIN DESCRIPTION:
Mapping XS fab22a56
END DESCRIPTION:
XS GIS Cut Line= 4
      2054290.52     13476203.02      2053998.85     13476114.48
      2052892.08     13476234.27      2052754.08     13476380.07
#Sta/Elev= 30
  3899.2  424.27  4176.7  422.14  4268.2  422.11  4288.1  421.59  4429.2  420.92
  4469.4  421.52  4534.4  421.39  4600.2  420.25  4610.2  420.54  4626.2  419.69
  4640.4  419.55  4801.3  419.80  4851.6  418.89  4901.4  418.56  4906.4  418.85
  4908.7  418.41  4909.2  417.61  4914.8  417.61  4915.3  418.41  4982.4  418.93
  5003.1  418.49  5032.7  419.47  5143.3  420.87  5173.5  421.95  5254.0  423.60
  5365.2  425.05  5421.8  424.98  5471.2  425.86  5478.4  425.55  5518.0  425.77
#Mann=4,-1,0
  3899.2    0.05       0  4288.1     0.1       0  4908.7    0.07       0
  4915.3     0.1       0
Bank Sta=4908.7,4915.3
Exp/Cntr=0.3,0.1

Type RM Length L Ch R = 1,9206,614,614,614
BEGIN DESCRIPTION:
Mapping XS ea861c99
END DESCRIPTION:
XS GIS Cut Line= 4
      2054162.88     13475723.84      2053863.43     13475606.67
      2053022.28     13475622.29      2052881.66     13475846.26
#Sta/Elev= 30
  4072.9  422.98  4193.7  422.41  4239.3  421.57  4432.9  419.79  4452.9  419.29
  4532.9  419.20  4575.9  419.82  4672.9  419.04  4742.9  417.78  4863.0  418.52
  4883.0  418.17  4963.0  418.47  4973.0  418.16  4980.6  416.94  4989.6  416.28
  4990.1  415.48  4995.8  415.48  4996.3  416.28  5013.0  417.19  5023.0  418.39
  5053.0  418.23  5093.0  418.74  5242.4  422.31  5257.8  421.88  5367.3  423.03
  5373.2  423.88  5388.5  423.25  5416.1  423.32  5452.1  424.10  5500.2  424.16
#Mann=6,-1,0
  4072.9    0.05       0  4239.3     0.1       0  4963.0    0.07       0
  4980.6     0.1       0  4989.6    0.07       0  4996.3     0.1       0
Bank Sta=4989.6,4996.3
Exp/Cntr=0.3,0.1

Type RM Length L Ch R = 1,8592,302,302,302
BEGIN DESCRIPTION:
Mapping XS ab9db093
END DESCRIPTION:
XS GIS Cut Line= 4
      2053972.82     13475309.80      2053741.03     13475119.69
      2053136.87     13475075.42      2052852.70     13475760.56
#Sta/Elev= 30
  4174.8  421.19  4226.0  420.43  4396.8  420.76  4474.3  419.89  4580.9  417.46
  4661.1  417.38  4697.9  416.08  4698.4  415.28  4704.1  415.28  4704.6  416.08
  4711.2  416.88  4740.2  417.47  4811.5  417.96  4861.6  417.26  4974.1  417.58
  4992.0  416.19  5002.0  417.69  5021.7  417.76  5042.1  417.62  5078.8  419.15
  5121.1  419.24  5126.5  419.75  5150.4  419.47  5251.3  420.50  5256.7  421.49
  5280.6  420.79  5286.0  421.61  5296.4  421.86  5647.4  423.16  5822.1  423.13
#Mann=5,-1,0
  4174.8     0.1       0  4697.9    0.07       0  4704.6     0.1       0
  4974.1    0.07       0  5021.7     0.1       0
Bank Sta=4697.9,4704.6
Exp/Cntr=0.3,0.1

Type RM Length L Ch R = 1,8290,45,45,45
BEGIN DESCRIPTION:
Mapping XS a92059f1
END DESCRIPTION:
XS GIS Cut Line= 6
      2053949.33     13475161.33      2053367.12     13474861.87
      2053343.51     13474784.10      2053247.68     13474798.68
      2053205.32     13474857.71      2052835.68     13475711.17
#Sta/Elev= 30
  4210.9  420.71  4446.1  419.38  4571.3  417.85  4609.2  415.09  4712.8  414.76
  4779.9  414.55  4927.8  413.87  4947.2  414.75  4985.4  413.71  4985.9  412.91
  4991.8  412.91  4992.3  413.71  5051.6  414.41  5057.7  415.44  5072.5  414.71
  5078.6  416.17  5087.2  415.80  5093.3  419.21  5108.1  416.88  5112.8  420.57
  5177.2  420.78  5182.6  418.98  5200.6  420.28  5206.1  418.80  5229.6  419.96
  5254.1  418.75  5282.0  418.13  5304.6  419.09  5784.2  422.63  6046.9  423.02
#Mann=7,-1,0
  4210.9     0.1       0  4712.8    0.07       0  4779.9     0.1       0
  4985.4    0.07       0  4992.3     0.1       0  5254.1    0.07       0
  5304.6     0.1       0
Bank Sta=4985.4,4992.3
Exp/Cntr=0.3,0.1

Type RM Length L Ch R = 1,8245,31,31,31
BEGIN DESCRIPTION:
Mapping XS 94c0b339
END DESCRIPTION:
XS GIS Cut Line= 5
      2053975.39     13475130.09      2053378.23     13474754.24
      2053245.59     13474742.43      2053202.54     13474831.32
      2052810.84     13475667.27
#Sta/Elev= 30
  4213.4  420.30  4341.5  421.00  4576.7  417.69  4577.2  416.89  4583.6  417.69
  4630.0  421.47  4722.3  422.02  4781.8  421.71  4827.7  421.70  4833.6  420.13
  4848.9  421.90  4854.8  420.34  4885.4  421.71  4891.3  419.81  4906.6  421.79
  4912.5  420.52  4932.3  422.14  5002.6  422.22  5068.3  421.34  5085.4  419.40
  5090.9  420.83  5136.1  419.42  5153.9  420.74  5158.7  418.78  5176.0  420.09
  5181.5  418.23  5340.4  418.88  5357.1  418.67  5791.6  422.27  6074.1  422.79
#Mann=7,-1,0
  4213.4     0.1       0  4576.7    0.07       0  4583.6     0.1       0
  4722.3    0.07       0  4781.8     0.1       0  5340.4    0.07       0
  5357.1     0.1       0
Bank Sta=4576.7,4583.6
Exp/Cntr=0.3,0.1

Type RM Length L Ch R = 1,8214,25,25,25
BEGIN DESCRIPTION:
Mapping XS 20f3d67e
END DESCRIPTION:
XS GIS Cut Line= 4
      2053931.11     13475012.90      2053369.20     13474718.12
      2053219.90     13474714.65      2052751.99     13475670.38
#Sta/Elev= 30
  4297.3  420.48  4360.7  420.71  4477.5  419.88  4582.1  417.82  4690.8  417.11
  4732.0  417.03  4916.5  416.76  4948.6  416.94  4973.8  416.85  4992.6  416.61
  4993.1  415.81  4999.0  415.81  4999.5  416.61  5076.1  417.71  5168.5  417.46
  5174.1  418.53  5191.0  418.19  5213.5  418.75  5219.1  418.21  5241.6  417.91
  5326.0  417.94  5460.1  419.74  5691.7  420.99  5749.6  421.86  5787.3  421.49
  5854.8  422.24  5916.6  421.73  5967.3  422.38  5995.4  422.03  6145.3  422.59
#Mann=8,-1,0
  4297.3     0.1       0  4690.8    0.08       0  4732.0     0.1       0
  4916.5    0.08       0  4948.6    0.05       0  4973.8     0.1       0
  4992.6    0.07       0  4999.5     0.1       0
Bank Sta=4992.6,4999.5
Exp/Cntr=0.3,0.1

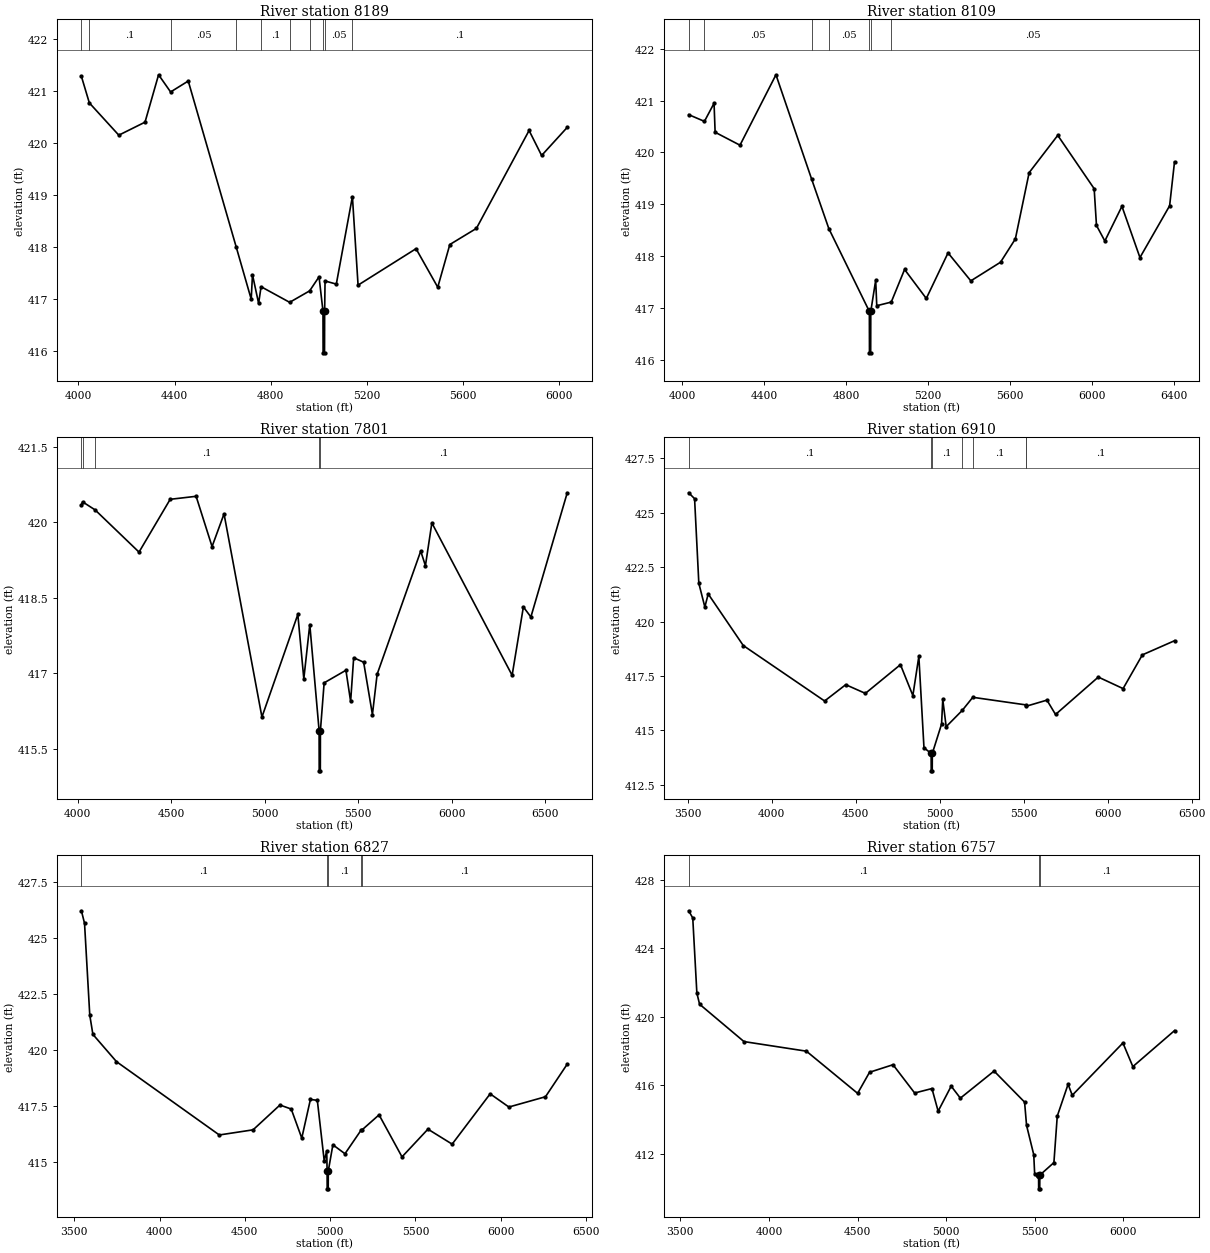
Type RM Length L Ch R = 1,8189,80,80,80
BEGIN DESCRIPTION:
Mapping XS 6b64e6cf
END DESCRIPTION:
XS GIS Cut Line= 4
      2054251.49     13475007.72      2053538.65     13474754.24
      2053260.87     13474682.01      2052288.93     13474596.34
#Sta/Elev= 30
  4013.0  421.28  4046.0  420.77  4168.5  420.15  4277.4  420.40  4333.8  421.31
  4383.8  420.98  4457.1  421.19  4656.6  418.00  4718.8  417.00  4724.1  417.47
  4749.6  416.92  4759.8  417.24  4878.6  416.94  4961.6  417.16  5000.7  417.43
  5017.1  416.77  5017.6  415.97  5023.5  415.97  5024.0  416.77  5025.7  417.35
  5072.5  417.29  5139.4  418.97  5162.9  417.27  5403.8  417.97  5494.1  417.23
  5544.3  418.05  5654.8  418.36  5873.7  420.24  5925.8  419.76  6032.3  420.30
#Mann=10,-1,0
  4013.0    0.05       0  4046.0     0.1       0  4383.8    0.05       0
  4656.6    0.08       0  4759.8     0.1       0  4878.6    0.08       0
  4961.6    0.05       0  5017.1    0.04       0  5024.0    0.05       0
  5139.4     0.1       0
Bank Sta=5017.1,5024
Exp/Cntr=0.3,0.1

Type RM Length L Ch R = 1,8109,308,308,308
BEGIN DESCRIPTION:
Mapping XS 300503b4
END DESCRIPTION:
XS GIS Cut Line= 4
      2054306.18     13474903.55      2053484.48     13474678.54
      2053301.15     13474621.60      2052028.72     13474252.86
#Sta/Elev= 30
  4032.5  420.73  4109.3  420.60  4156.2  420.95  4161.4  420.39  4282.6  420.14
  4458.0  421.50  4631.5  419.49  4715.7  418.53  4913.4  416.93  4913.9  416.13
  4919.8  416.13  4920.3  416.93  4944.2  417.53  4949.5  417.04  5020.1  417.11
  5085.1  417.74  5191.0  417.18  5297.0  418.06  5408.1  417.52  5552.9  417.88
  5625.2  418.33  5692.4  419.61  5831.9  420.33  6009.4  419.30  6020.7  418.59
  6061.5  418.29  6144.8  418.96  6232.6  417.97  6377.3  418.97  6401.2  419.82
#Mann=7,-1,0
  4032.5    0.08       0  4109.3    0.05       0  4631.5     0.1       0
  4715.7    0.05       0  4913.4    0.07       0  4920.3    0.05       0
  5020.1    0.05       0
Bank Sta=4913.4,4920.3
Exp/Cntr=0.3,0.1

Type RM Length L Ch R = 1,7801,891,891,891
BEGIN DESCRIPTION:
Mapping XS e3b78df7
END DESCRIPTION:
XS GIS Cut Line= 4
      2054334.79     13474898.34      2053988.43     13474611.88
      2052652.49     13474119.69      2051931.10     13474166.57
#Sta/Elev= 30
  4020.2  420.35  4026.4  420.41  4093.3  420.25  4328.1  419.41  4494.6  420.46
  4633.2  420.52  4718.4  419.52  4782.4  420.17  4984.9  416.13  5176.7  418.17
  5208.7  416.89  5240.6  417.97  5290.4  415.86  5290.9  415.06  5296.9  415.06
  5297.4  415.86  5317.3  416.81  5433.7  417.06  5458.8  416.44  5475.1  417.31
  5528.4  417.22  5575.3  416.18  5600.4  416.98  5833.4  419.43  5858.5  419.14
  5892.9  419.99  6321.8  416.96  6381.9  418.32  6422.0  418.12  6616.3  420.59
#Mann=5,-1,0
  4020.2    0.05       0  4026.4    0.08       0  4093.3     0.1       0
  5290.4    0.07       0  5297.4     0.1       0
Bank Sta=5290.4,5297.4
Exp/Cntr=0.3,0.1

Type RM Length L Ch R = 1,6910,83,83,83
BEGIN DESCRIPTION:
Mapping XS 0f721b1b
END DESCRIPTION:
XS GIS Cut Line= 4
      2054914.98     13474101.30      2053694.16     13473656.15
      2052597.81     13473458.23      2052144.64     13473609.28
#Sta/Elev= 30
  3506.9  425.92  3542.0  425.65  3567.3  421.76  3603.1  420.67  3623.1  421.27
  3831.7  418.90  4315.8  416.35  4441.5  417.10  4558.4  416.70  4767.1  418.02
  4841.0  416.60  4876.6  418.40  4907.1  414.20  4949.7  413.94  4950.2  413.14
  4956.2  413.14  4956.7  413.94  5011.8  415.29  5018.9  416.42  5039.2  415.17
  5135.1  415.92  5197.6  416.52  5514.4  416.17  5515.8  416.11  5638.8  416.39
  5690.0  415.73  5944.5  417.45  6092.0  416.92  6206.7  418.47  6398.1  419.12
#Mann=7,-1,0
  3506.9     0.1       0  4949.7    0.07       0  4956.7     0.1       0
  5135.1    0.08       0  5197.6     0.1       0  5514.4    0.08       0
  5515.8     0.1       0
Bank Sta=4949.7,4956.7
Exp/Cntr=0.3,0.1

Type RM Length L Ch R = 1,6827,70,70,70
BEGIN DESCRIPTION:
Mapping XS 4f3a3dd0
END DESCRIPTION:
XS GIS Cut Line= 4
      2054890.69     13474035.33      2053728.01     13473580.63
      2052535.31     13473385.31      2052160.29     13473497.30
#Sta/Elev= 30
  3541.6  426.22  3560.0  425.66  3590.7  421.55  3609.0  420.69  3747.4  419.47
  4350.1  416.19  4548.2  416.42  4705.7  417.53  4771.8  417.35  4833.6  416.05
  4884.3  417.78  4924.8  417.74  4965.3  415.03  4980.0  415.48  4982.1  414.58
  4982.6  413.78  4988.6  413.78  4989.1  414.58  5016.0  415.75  5086.9  415.35
  5180.9  416.40  5184.4  416.40  5286.7  417.09  5421.3  415.21  5573.3  416.45
  5715.2  415.78  5938.1  418.03  6047.9  417.44  6262.4  417.90  6390.0  419.36
#Mann=5,-1,0
  3541.6     0.1       0  4982.1    0.07       0  4989.1     0.1       0
  5180.9    0.08       0  5184.4     0.1       0
Bank Sta=4982.1,4989.1
Exp/Cntr=0.3,0.1

Type RM Length L Ch R = 1,6757,721,721,721
BEGIN DESCRIPTION:
Mapping XS 3e1cffa6
END DESCRIPTION:
XS GIS Cut Line= 4
      2054901.13     13473969.37      2054035.31     13473580.63
      2052662.91     13473315.00      2052272.25     13473372.30
#Sta/Elev= 30
  3546.9  426.18  3569.9  425.76  3593.1  421.38  3608.4  420.73  3858.9  418.55
  4211.3  417.99  4500.3  415.53  4567.6  416.76  4700.0  417.20  4822.2  415.55
  4919.7  415.81  4954.7  414.49  5028.3  415.95  5080.1  415.25  5270.4  416.83
  5442.5  415.02  5453.7  413.66  5494.3  411.95  5499.4  410.82  5521.5  410.76
  5522.0  409.96  5528.0  409.96  5528.6  410.76  5608.0  411.49  5626.9  414.20
  5688.0  416.06  5711.6  415.42  5997.5  418.47  6053.5  417.09  6288.7  419.19
#Mann=3,-1,0
  3546.9     0.1       0  5521.5    0.07       0  5528.6     0.1       0
Bank Sta=5521.5,5528.6
Exp/Cntr=0.3,0.1

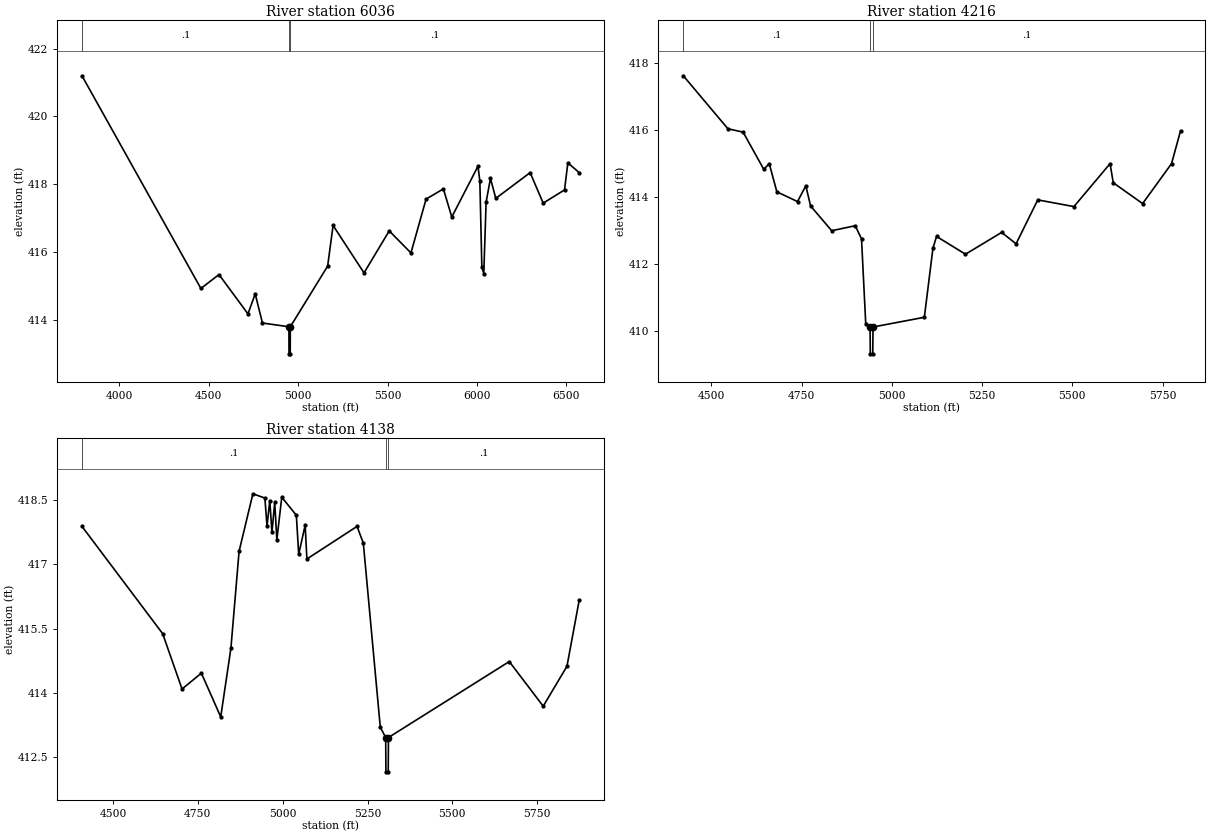
Type RM Length L Ch R = 1,6036,1820,1820,1820
BEGIN DESCRIPTION:
Mapping XS 1e2705ce
END DESCRIPTION:
XS GIS Cut Line= 4
      2055061.33     13473169.16      2054777.49     13473049.38
      2053243.64     13472804.58      2052388.61     13473142.43
#Sta/Elev= 30
  3791.1  421.20  4456.1  414.92  4557.4  415.33  4719.4  414.17  4759.9  414.76
  4800.4  413.90  4948.4  413.79  4949.0  412.99  4955.6  412.99  4956.3  413.79
  5165.0  415.58  5195.4  416.78  5368.4  415.38  5509.3  416.62  5630.8  415.97
  5715.5  417.56  5812.3  417.86  5859.2  417.03  6005.8  418.53  6016.1  418.09
  6027.3  415.56  6038.1  415.36  6051.2  417.47  6075.5  418.17  6105.3  417.58
  6297.3  418.34  6370.4  417.44  6489.7  417.83  6508.3  418.63  6571.8  418.34
#Mann=3,-1,0
  3791.1     0.1       0  4948.4    0.07       0  4956.3     0.1       0
Bank Sta=4948.4,4956.3
Exp/Cntr=0.3,0.1

Type RM Length L Ch R = 1,4216,78,78,78
BEGIN DESCRIPTION:
Mapping XS 19325cde
END DESCRIPTION:
XS GIS Cut Line= 4
      2055230.60     13472038.93      2054960.12     13471625.86
      2054803.87     13471538.62      2054100.03     13471500.00
#Sta/Elev= 30
  4422.3  417.62  4545.9  416.04  4588.0  415.94  4645.3  414.83  4660.4  415.00
  4681.5  414.16  4738.7  413.87  4761.7  414.34  4774.9  413.74  4833.4  413.00
  4898.6  413.15  4916.0  412.76  4927.8  410.21  4939.7  410.13  4940.4  409.33
  4947.2  409.33  4947.9  410.13  5090.1  410.42  5113.9  412.48  5123.9  412.83
  5204.0  412.30  5304.2  412.95  5344.2  412.61  5404.3  413.92  5504.5  413.72
  5604.6  415.00  5613.5  414.43  5694.8  413.81  5774.9  415.00  5799.9  415.98
#Mann=3,-1,0
  4422.3     0.1       0  4939.7    0.07       0  4947.9     0.1       0
Bank Sta=4939.7,4947.9
Exp/Cntr=0.3,0.1

Type RM Length L Ch R = 1,4138,64,64,64
BEGIN DESCRIPTION:
Mapping XS 14423604
END DESCRIPTION:
XS GIS Cut Line= 5
      2055285.30     13472023.32      2055026.53     13471637.58
      2054914.55     13471491.74      2054757.00     13471472.21
      2054098.88     13471463.45
#Sta/Elev= 30
  4408.5  417.88  4646.3  415.38  4703.4  414.09  4760.4  414.46  4817.4  413.44
  4847.4  415.04  4871.5  417.30  4912.2  418.64  4947.5  418.54  4953.8  417.89
  4962.0  418.48  4968.3  417.74  4976.5  418.44  4982.8  417.57  4997.3  418.56
  5040.2  418.14  5047.2  417.23  5066.2  417.91  5071.3  417.12  5219.1  417.88
  5237.6  417.49  5287.6  413.20  5303.5  412.96  5304.2  412.16  5311.0  412.16
  5311.7  412.96  5667.7  414.73  5767.7  413.69  5837.7  414.62  5873.8  416.16
#Mann=3,-1,0
  4408.5     0.1       0  5303.5    0.07       0  5311.7     0.1       0
Bank Sta=5303.5,5311.7
Exp/Cntr=0.3,0.1