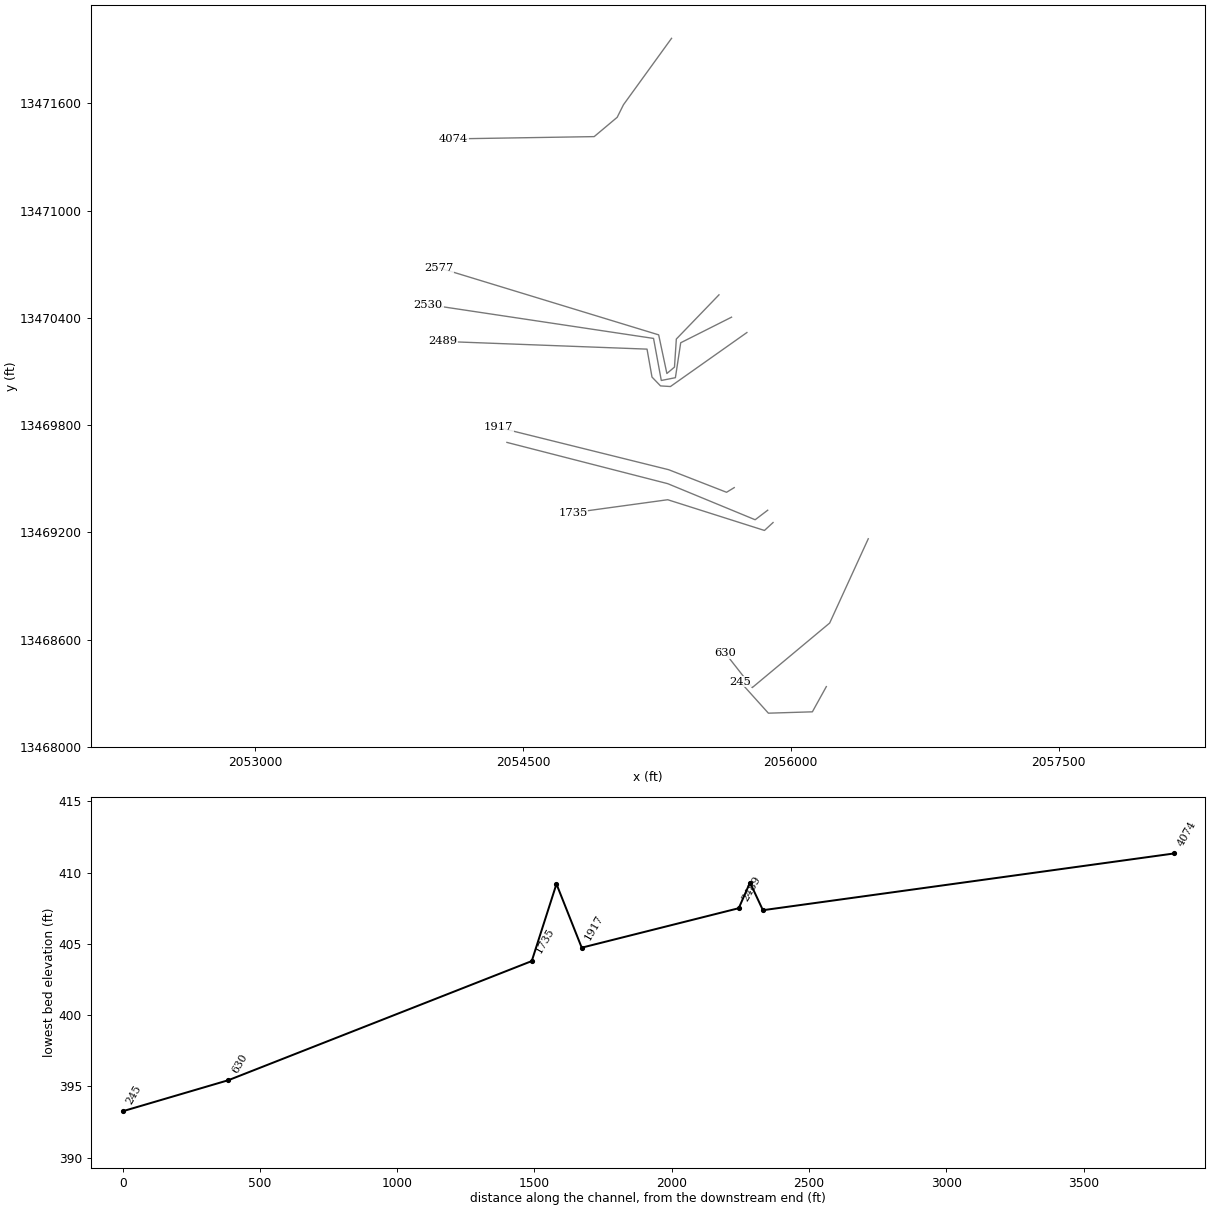
HEC-RAS study UNT 71 in Lagunillas Cr Wtrshd.prj: UNT 71 in Lagunillas Cr Wtrshd Base Level Engineering

--- UNT 71 in Lagunillas Cr Wtrshd.g01 (geometry) --- (continued)

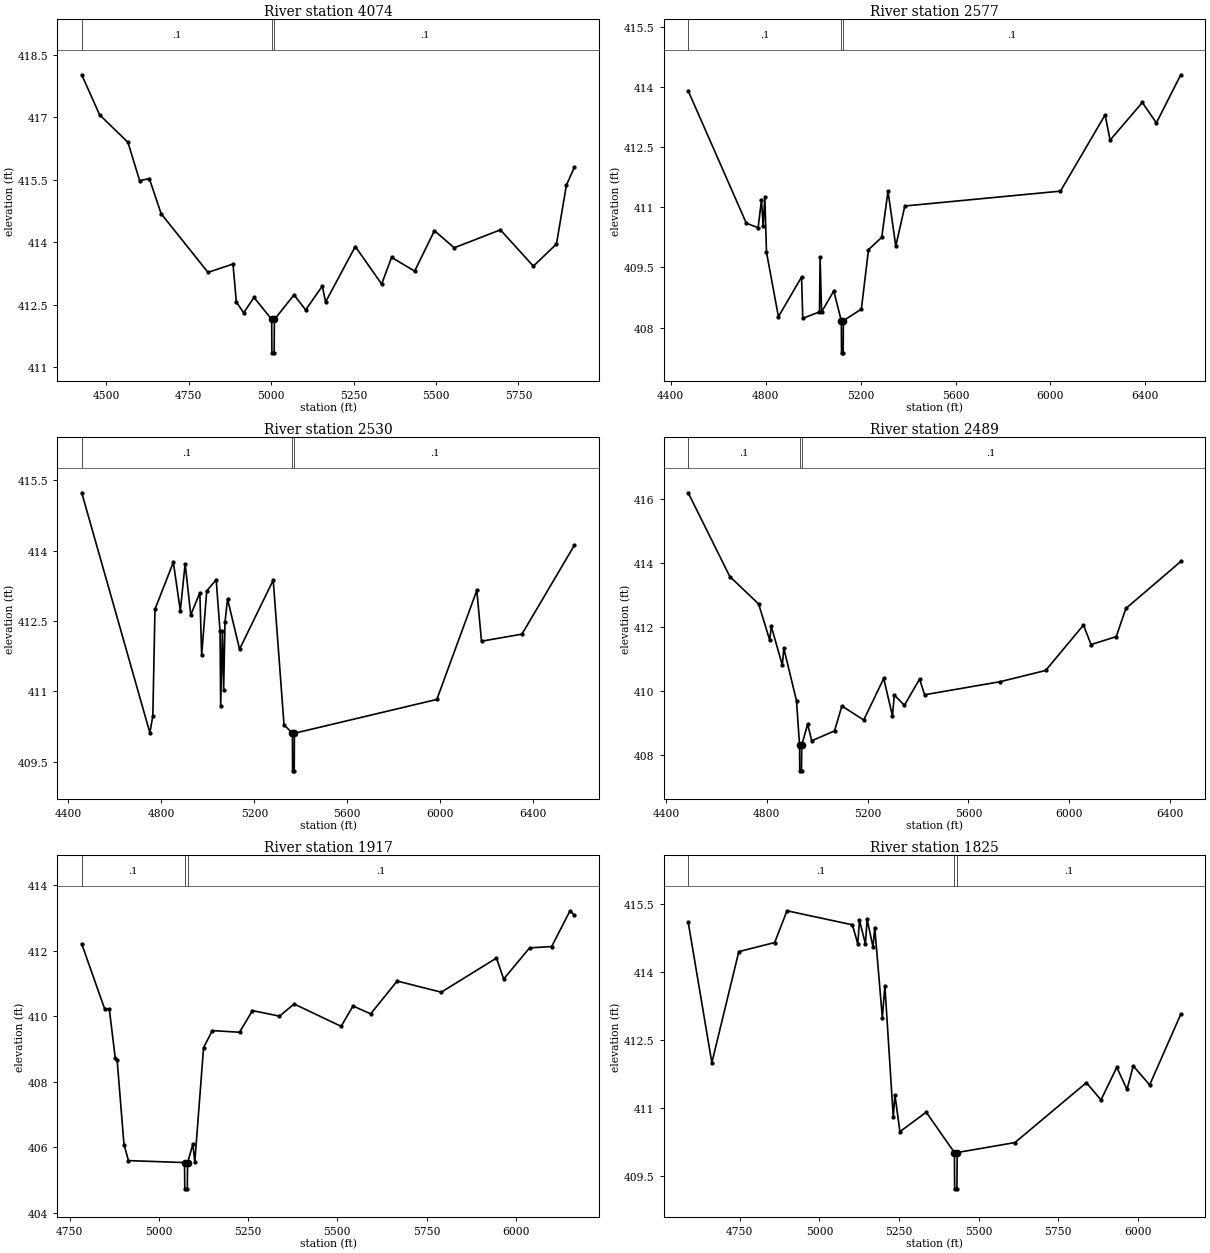
Type RM Length L Ch R = 1,4074,1497,1497,1497
BEGIN DESCRIPTION:
Mapping XS ea8af860
END DESCRIPTION:
XS GIS Cut Line= 5
      2055332.17     13471963.43      2055062.99     13471592.00
      2055027.83     13471521.69      2054898.93     13471413.62
      2054110.87     13471400.94
#Sta/Elev= 30
  4425.8  418.02  4480.0  417.06  4565.9  416.40  4601.4  415.48  4630.8  415.53
  4666.4  414.69  4808.6  413.28  4884.5  413.48  4894.6  412.57  4916.9  412.31
  4948.2  412.68  5001.8  412.15  5002.5  411.35  5009.3  411.35  5010.0  412.15
  5069.7  412.74  5104.8  412.38  5155.3  412.95  5165.3  412.57  5255.3  413.90
  5335.3  413.00  5365.3  413.64  5435.3  413.31  5495.3  414.28  5555.3  413.87
  5695.3  414.30  5795.3  413.43  5865.4  413.96  5895.4  415.37  5919.5  415.80
#Mann=3,-1,0
  4425.8     0.1       0  5001.8    0.07       0  5010.0     0.1       0
Bank Sta=5001.8,5010
Exp/Cntr=0.3,0.1

Type RM Length L Ch R = 1,2577,47,47,47
BEGIN DESCRIPTION:
Mapping XS c8739893
END DESCRIPTION:
XS GIS Cut Line= 6
      2055597.81     13470528.55      2055359.00     13470281.24
      2055348.58     13470124.12      2055306.04     13470088.53
      2055260.04     13470304.68      2054030.08     13470679.59
#Sta/Elev= 30
  4473.9  413.90  4718.8  410.60  4768.4  410.49  4782.6  411.18  4789.5  410.53
  4796.7  411.25  4803.7  409.88  4854.0  408.27  4951.5  409.26  4956.5  408.23
  5026.9  408.39  5029.5  409.75  5035.8  408.39  5087.1  408.91  5119.0  408.17
  5119.8  407.37  5126.8  407.37  5127.5  408.17  5203.4  408.46  5233.4  409.94
  5289.3  410.25  5315.6  411.40  5348.4  410.03  5386.5  411.03  6042.1  411.40
  6230.2  413.30  6251.1  412.67  6387.0  413.61  6446.0  413.10  6549.0  414.30
#Mann=3,-1,0
  4473.9     0.1       0  5119.0    0.07       0  5127.5     0.1       0
Bank Sta=5119,5127.5
Exp/Cntr=0.3,0.1

Type RM Length L Ch R = 1,2530,41,41,41
BEGIN DESCRIPTION:
Mapping XS 91e3bb18
END DESCRIPTION:
XS GIS Cut Line= 6
      2055668.15     13470403.56      2055383.47     13470260.37
      2055353.79     13470065.10      2055274.79     13470049.47
      2055231.39     13470284.71      2053970.21     13470473.85
#Sta/Elev= 30
  4457.6  415.23  4750.7  410.12  4763.4  410.48  4772.6  412.75  4851.6  413.75
  4881.6  412.72  4902.4  413.72  4926.5  412.63  4965.6  413.10  4973.4  411.77
  4995.2  413.14  5035.9  413.38  5052.5  412.28  5055.2  410.69  5062.5  412.28
  5068.0  411.04  5073.7  412.47  5084.7  412.97  5136.4  411.90  5281.2  413.37
  5327.6  410.29  5363.8  410.11  5364.5  409.31  5371.5  409.31  5372.3  410.11
  5984.9  410.83  6156.8  413.15  6177.0  412.07  6350.9  412.22  6576.2  414.11
#Mann=3,-1,0
  4457.6     0.1       0  5363.8    0.07       0  5372.3     0.1       0
Bank Sta=5363.8,5372.3
Exp/Cntr=0.3,0.1

Type RM Length L Ch R = 1,2489,572,572,572
BEGIN DESCRIPTION:
Mapping XS 43edeb1c
END DESCRIPTION:
XS GIS Cut Line= 6
      2055754.09     13470317.63      2055326.01     13470015.62
      2055270.45     13470019.09      2055222.71     13470068.57
      2055194.93     13470224.82      2054049.12     13470268.10
#Sta/Elev= 30
  4488.0  416.21  4653.1  413.59  4767.6  412.73  4811.4  411.60  4817.6  412.03
  4861.4  410.82  4867.6  411.34  4917.8  409.70  4929.9  408.31  4930.7  407.51
  4937.7  407.51  4938.4  408.31  4961.9  408.97  4978.3  408.45  5068.6  408.76
  5097.9  409.54  5184.5  409.10  5263.9  410.40  5298.5  409.23  5306.0  409.88
  5346.0  409.56  5406.1  410.38  5426.1  409.89  5726.3  410.30  5906.4  410.65
  6056.5  412.07  6086.6  411.46  6186.6  411.71  6224.9  412.59  6442.7  414.06
#Mann=3,-1,0
  4488.0     0.1       0  4929.9    0.07       0  4938.4     0.1       0
Bank Sta=4929.9,4938.4
Exp/Cntr=0.3,0.1

Type RM Length L Ch R = 1,1917,92,92,92
BEGIN DESCRIPTION:
Mapping XS 3a269376
END DESCRIPTION:
XS GIS Cut Line= 4
      2055683.15     13469450.06      2055640.22     13469424.04
      2055316.00     13469550.34      2054363.39     13469786.49
#Sta/Elev= 30
  4784.1  412.20  4848.0  410.23  4861.4  410.21  4877.9  408.73  4883.2  408.67
  4902.4  406.09  4915.0  405.60  5072.0  405.54  5072.7  404.74  5079.8  404.74
  5080.6  405.54  5095.4  406.10  5100.8  405.56  5125.3  409.04  5149.8  409.56
  5226.0  409.51  5262.3  410.17  5337.8  410.00  5379.0  410.37  5510.6  409.69
  5543.9  410.31  5593.3  410.07  5667.5  411.07  5791.1  410.73  5945.7  411.77
  5965.8  411.13  6038.4  412.08  6100.3  412.12  6151.7  413.21  6163.7  413.08
#Mann=3,-1,0
  4784.1     0.1       0  5072.0    0.07       0  5080.6     0.1       0
Bank Sta=5072,5080.6
Exp/Cntr=0.3,0.1

Type RM Length L Ch R = 1,1825,90,90,90
BEGIN DESCRIPTION:
Mapping XS 7f83ee87
END DESCRIPTION:
XS GIS Cut Line= 4
      2055870.68     13469323.77      2055800.37     13469270.39
      2055310.79     13469472.21      2054410.33     13469703.02
#Sta/Elev= 30
  4587.8  415.09  4662.1  411.99  4746.8  414.44  4859.5  414.64  4898.2  415.34
  5103.7  415.03  5120.5  414.61  5125.9  415.13  5144.5  414.61  5149.9  415.15
  5168.4  414.54  5173.8  414.97  5197.7  412.98  5205.6  413.69  5232.0  410.79
  5237.2  411.28  5252.9  410.47  5335.5  410.90  5424.1  410.01  5424.8  409.21
  5431.9  409.21  5432.7  410.01  5614.2  410.23  5838.6  411.55  5884.6  411.17
  5934.2  411.89  5966.2  411.40  5985.9  411.92  6037.4  411.50  6135.2  413.06
#Mann=3,-1,0
  4587.8     0.1       0  5424.1    0.07       0  5432.7     0.1       0
Bank Sta=5424.1,5432.7
Exp/Cntr=0.3,0.1

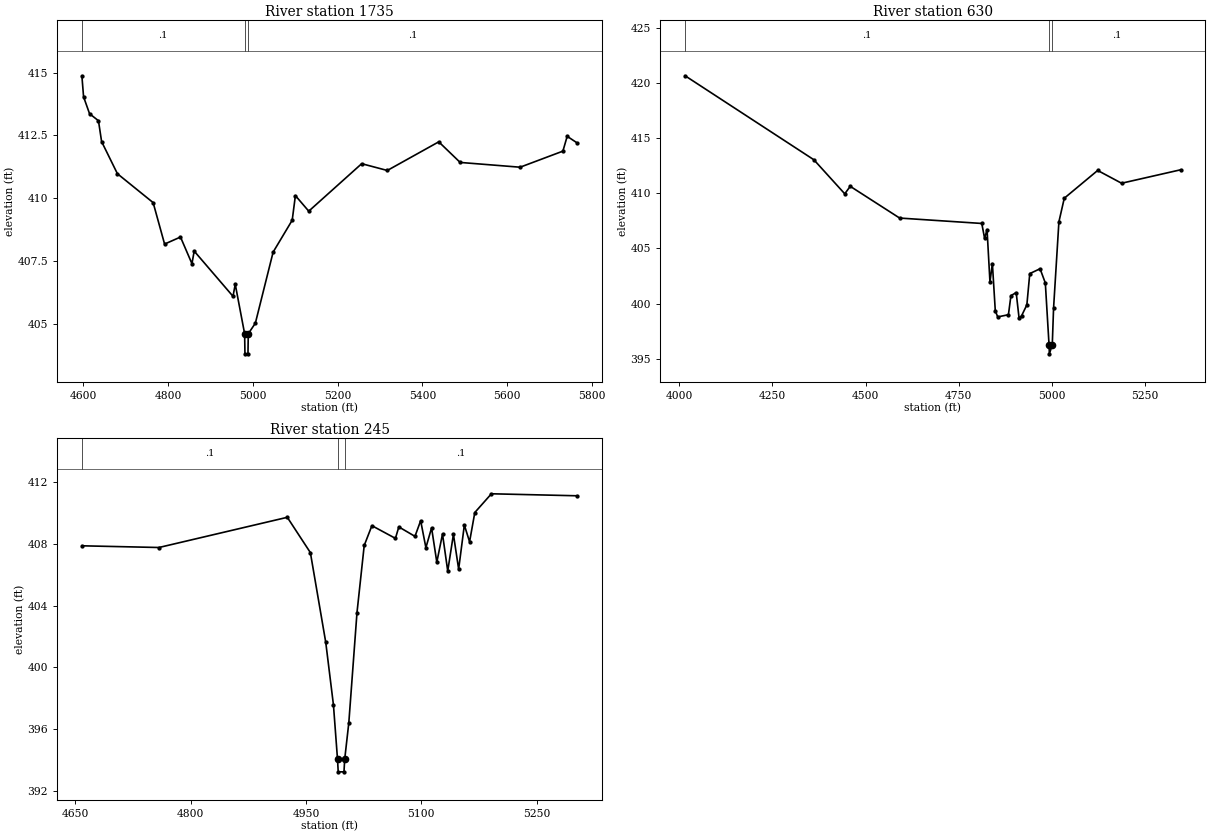
Type RM Length L Ch R = 1,1735,1105,1105,1105
BEGIN DESCRIPTION:
Mapping XS e1572e69
END DESCRIPTION:
XS GIS Cut Line= 4
      2055900.64     13469254.77      2055852.46     13469210.49
      2055310.79     13469382.37      2054781.15     13469309.85
#Sta/Elev= 30
  4597.1  414.87  4601.1  414.03  4615.2  413.36  4636.2  413.08  4643.6  412.25
  4680.9  410.97  4765.1  409.82  4792.1  408.17  4829.6  408.45  4856.6  407.39
  4861.9  407.89  4953.4  406.09  4958.7  406.57  4980.8  404.60  4981.6  403.80
  4988.7  403.80  4989.4  404.60  5006.1  405.02  5048.0  407.85  5093.0  409.12
  5100.5  410.10  5132.0  409.48  5256.8  411.37  5317.2  411.10  5438.5  412.24
  5489.0  411.42  5630.3  411.23  5731.2  411.87  5741.3  412.46  5765.4  412.19
#Mann=3,-1,0
  4597.1     0.1       0  4980.8    0.07       0  4989.4     0.1       0
Bank Sta=4980.8,4989.4
Exp/Cntr=0.3,0.1

Type RM Length L Ch R = 1,630,385,385,385
BEGIN DESCRIPTION:
UNT 71 in Lagunillas Cr Wtrshd 35.0
END DESCRIPTION:
XS GIS Cut Line= 4
      2056433.73     13469163.94      2056217.60     13468692.61
      2055784.31     13468331.59      2055632.42     13468524.71
#Sta/Elev= 30
  4016.5  420.67  4361.6  413.05  4444.4  409.96  4459.1  410.64  4591.5  407.76
  4811.7  407.27  4819.3  405.91  4825.8  406.72  4833.6  401.96  4840.1  403.63
  4847.9  399.34  4854.4  398.79  4883.1  398.99  4889.8  400.72  4903.9  401.00
  4911.7  398.66  4918.2  398.88  4932.5  399.88  4940.3  402.72  4967.9  403.16
  4982.0  401.87  4992.0  396.24  4992.8  395.44  5000.6  396.24  5004.1  399.59
  5018.4  407.42  5032.8  409.56  5122.3  412.08  5186.4  410.92  5344.7  412.14
#Mann=3,-1,0
  4016.5     0.1       0  4992.0    0.07       0  5000.6     0.1       0
Bank Sta=4992,5000.6
Exp/Cntr=0.3,0.1

Type RM Length L Ch R = 1,245,0,0,0
BEGIN DESCRIPTION:
UNT 71 in Lagunillas Cr Wtrshd 36.0
END DESCRIPTION:
XS GIS Cut Line= 4
      2056198.90     13468336.96      2056120.79     13468195.92
      2055874.48     13468188.33      2055716.05     13468364.12
#Sta/Elev= 30
  4658.7  407.86  4758.9  407.75  4925.8  409.70  4955.8  407.42  4975.8  401.62
  4985.8  397.58  4991.1  394.06  4992.0  393.26  4999.5  393.26  5000.4  394.06
  5005.8  396.44  5016.4  403.54  5025.8  407.88  5035.8  409.16  5066.4  408.34
  5070.8  409.08  5091.8  408.47  5099.2  409.48  5106.0  407.74  5113.4  409.02
  5120.2  406.80  5127.6  408.62  5134.4  406.23  5141.8  408.60  5148.6  406.35
  5156.0  409.20  5162.8  408.12  5169.6  410.01  5191.2  411.22  5303.0  411.09
#Mann=3,-1,0
  4658.7     0.1       0  4991.1    0.07       0  5000.4     0.1       0
Bank Sta=4991.1,5000.4
Exp/Cntr=0.3,0.1

Chan Stop Cuts=-1