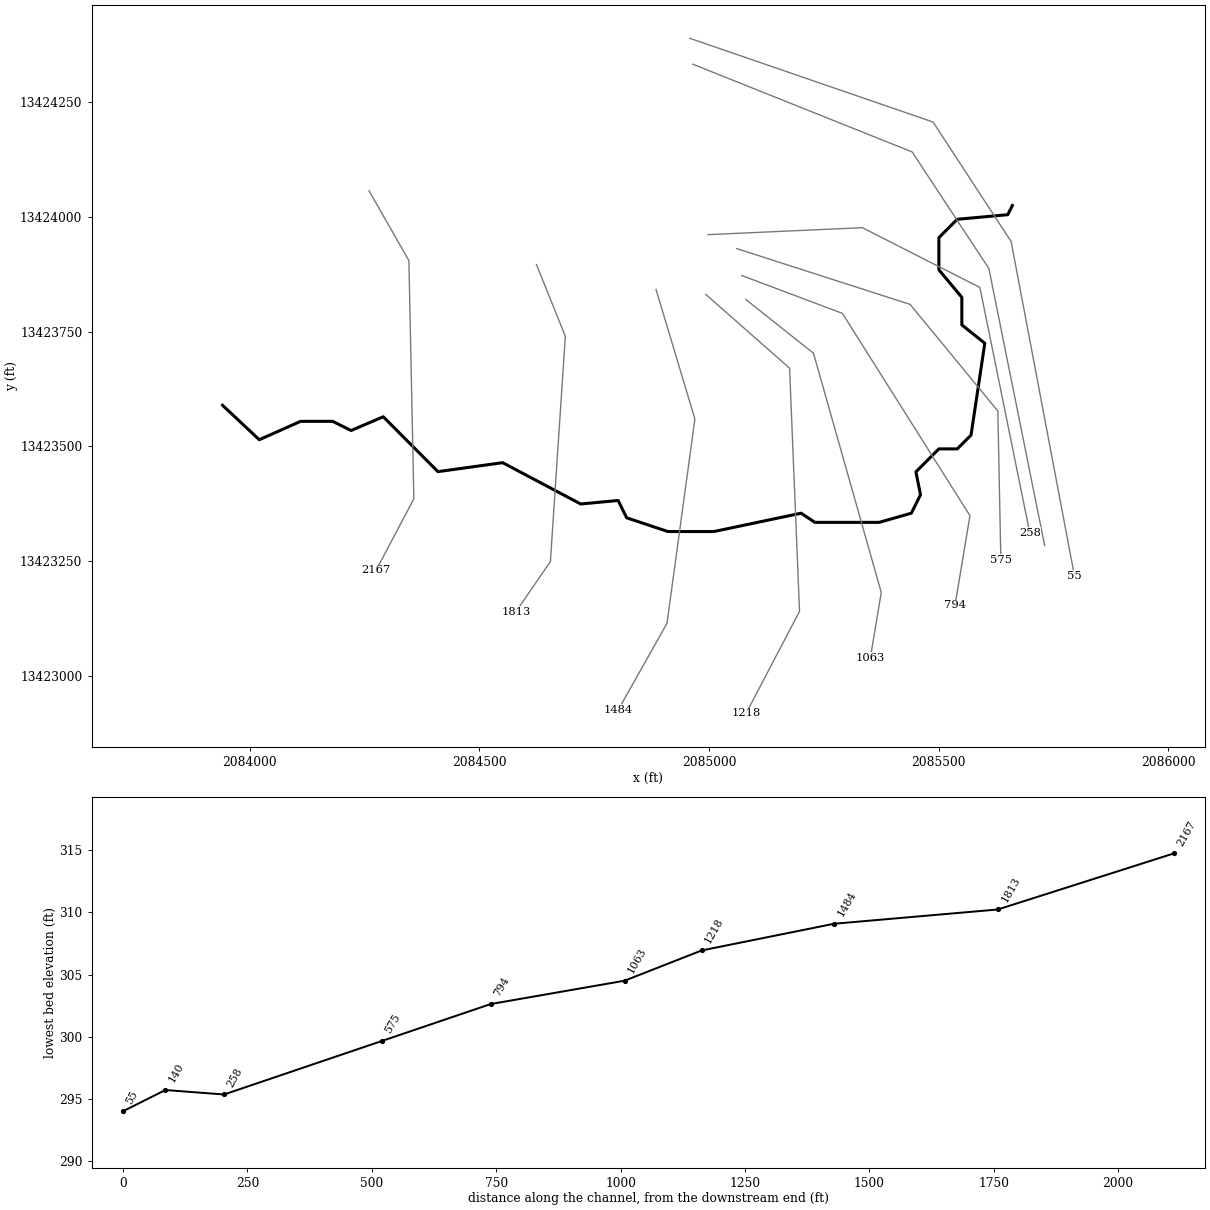
--- UNT 75 in Lagunillas Cr Wtrshd.prj (project) ---

Proj Title=UNT 75 in Lagunillas Cr Wtrshd Base Level Engineering
Current Plan=p01
Default Exp/Contr=0.3,0.1
English Units
Geom File=g01
Flow File=f01
Plan File=p01
BEGIN DESCRIPTION:
UNT 75 in Lagunillas Cr Wtrshd
END DESCRIPTION:

--- UNT 75 in Lagunillas Cr Wtrshd.p01 (plan) ---

Plan Title=Multiple Run
Short Identifier=Multiple
Geom File=g01
Flow File=f01
Subcritical Flow
K Sum by GR= 0
Std Step Tol= 0.01
Critical Tol= 0.01
Num of Std Step Trials= 20
Max Error Tol= 0.3
Flow Tol Ratio= 0.001
Split Flow NTrial= 30
Split Flow Tol= 0.02
Split Flow Ratio= 0.02
Log Output Level= 0
Friction Slope Method= 1
Unsteady Friction Slope Method= 2
Unsteady Bridges Friction Slope Method= 1
Parabolic Critical Depth
Global Vel Dist=  1 , 1 , 1
Global Log Level= 0
CheckData=True
Encroach Param= -1, 0, 0, 0
BEGIN DESCRIPTION:
Multiple Run
END DESCRIPTION:

--- UNT 75 in Lagunillas Cr Wtrshd.f01 (steady flow) ---

Flow Title=Multiple
Number of Profiles=7
Profile Names=10-year,25-year,50-year,1pct_min,100-year,1pct_plu,500-year
River Rch & RM= UNT 75 in Laguni,Reach-1,2167
      56      71      82      48      95     190     130
Boundary for River Rch & Prof#=UNT 75 in Laguni,Reach-1,1
Up Type=0
Dn Type=3
Dn Slope=0.005
Boundary for River Rch & Prof#=UNT 75 in Laguni,Reach-1,2
Up Type=0
Dn Type=3
Dn Slope=0.005
Boundary for River Rch & Prof#=UNT 75 in Laguni,Reach-1,3
Up Type=0
Dn Type=3
Dn Slope=0.005
Boundary for River Rch & Prof#=UNT 75 in Laguni,Reach-1,4
Up Type=0
Dn Type=3
Dn Slope=0.005
Boundary for River Rch & Prof#=UNT 75 in Laguni,Reach-1,5
Up Type=0
Dn Type=3
Dn Slope=0.005
Boundary for River Rch & Prof#=UNT 75 in Laguni,Reach-1,6
Up Type=0
Dn Type=3
Dn Slope=0.005
Boundary for River Rch & Prof#=UNT 75 in Laguni,Reach-1,7
Up Type=0
Dn Type=3
Dn Slope=0.005

--- UNT 75 in Lagunillas Cr Wtrshd.g01 (geometry) ---

Geom Title=Existing Conditions

River Reach=UNT 75 in Laguni,Reach-1
Reach XY= 30
      2083940.80     13423589.54      2084020.80     13423514.54
      2084110.80     13423554.54      2084180.80     13423554.54
      2084220.80     13423534.54      2084290.80     13423564.54
      2084409.90     13423445.00      2084550.80     13423464.54
      2084720.80     13423374.54      2084802.32     13423382.18
      2084820.80     13423344.54      2084910.80     13423314.54
      2085010.80     13423314.54      2085200.80     13423354.54
      2085230.80     13423334.54      2085370.80     13423334.54
      2085440.80     13423354.54      2085460.80     13423394.54
      2085450.80     13423444.54      2085500.80     13423494.54
      2085540.80     13423494.54      2085570.80     13423524.54
      2085600.80     13423724.54      2085550.80     13423764.54
      2085550.80     13423824.54      2085500.80     13423884.54
      2085500.80     13423954.54      2085540.80     13423994.54
      2085650.80     13424004.54      2085660.80     13424024.54

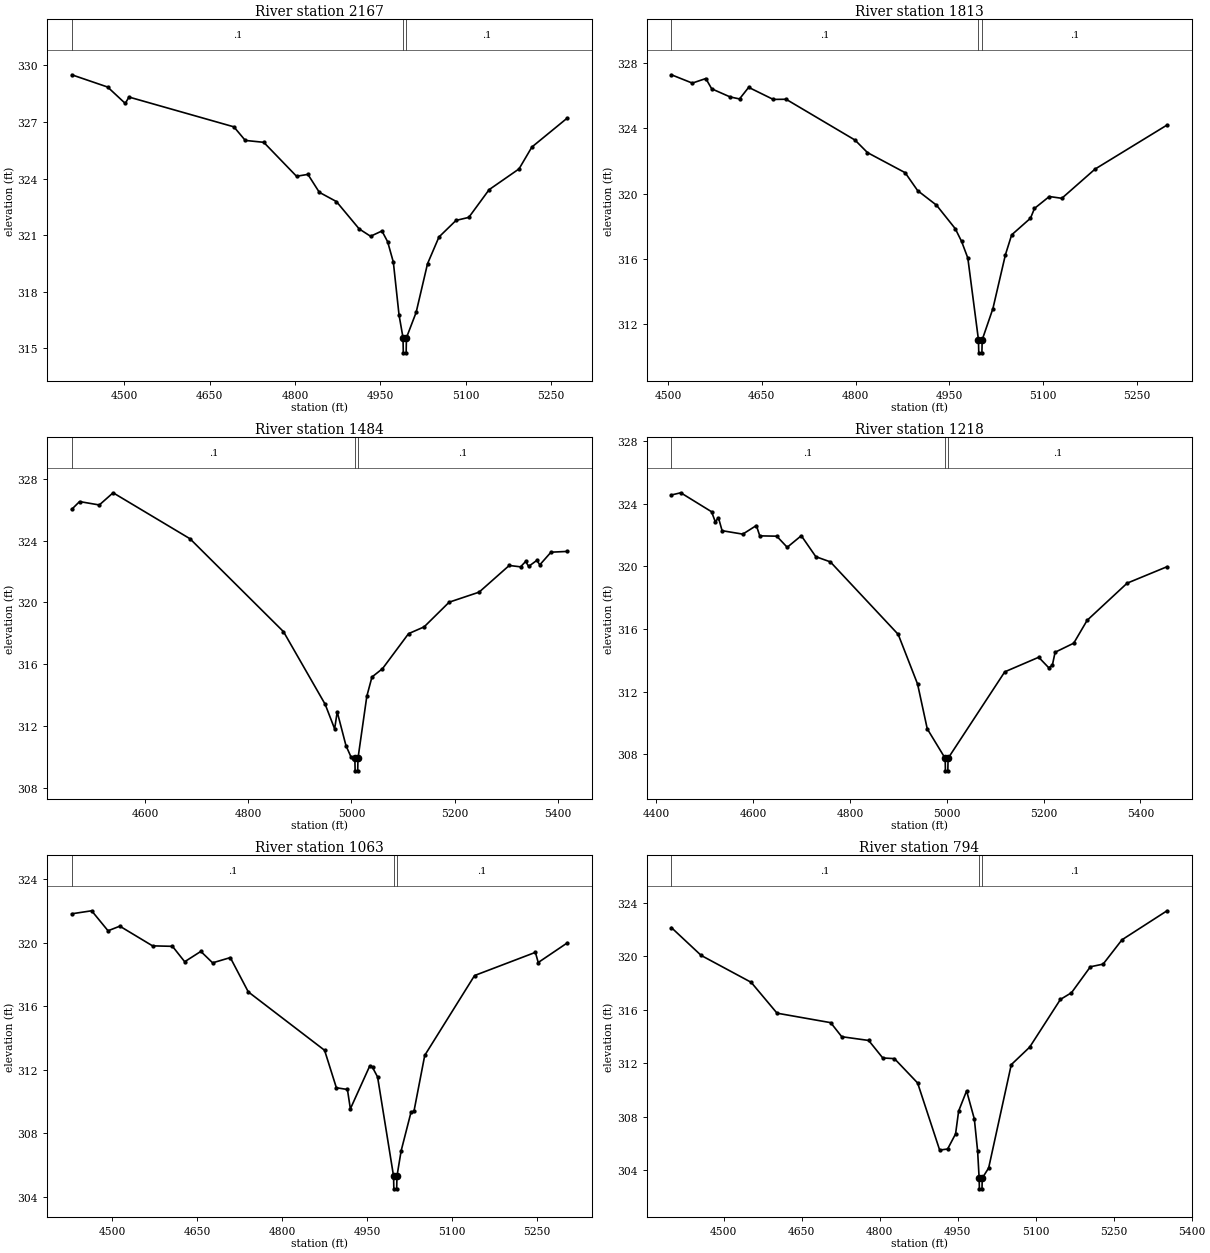
Type RM Length L Ch R = 1,2167,354,354,354
BEGIN DESCRIPTION:
Mapping XS f5d1c7ee
END DESCRIPTION:
XS GIS Cut Line= 4
      2084259.85     13424056.59      2084346.66     13423904.67
      2084357.51     13423386.00      2084275.11     13423229.87
#Sta/Elev= 30
  4407.9  329.50  4470.9  328.85  4501.9  327.98  4508.3  328.32  4692.6  326.74
  4712.6  326.02  4745.0  325.92  4802.6  324.12  4822.6  324.22  4842.6  323.27
  4872.6  322.78  4912.6  321.33  4932.6  320.94  4952.6  321.22  4962.6  320.65
  4972.6  319.57  4982.6  316.77  4989.6  315.56  4990.1  314.76  4995.1  314.76
  4995.6  315.56  5012.6  316.90  5032.6  319.48  5052.7  320.90  5082.7  321.78
  5105.1  321.94  5140.8  323.41  5193.3  324.51  5215.9  325.67  5278.2  327.21
#Mann=3,-1,0
  4407.9     0.1       0  4989.6    0.07       0  4995.6     0.1       0
Bank Sta=4989.6,4995.6
Exp/Cntr=0.3,0.1

Type RM Length L Ch R = 1,1813,329,329,329
BEGIN DESCRIPTION:
Mapping XS 46da2472
END DESCRIPTION:
XS GIS Cut Line= 4
      2084624.43     13423896.02      2084687.37     13423739.74
      2084654.82     13423249.28      2084579.91     13423140.13
#Sta/Elev= 30
  4505.6  327.28  4539.0  326.77  4560.6  327.05  4570.0  326.42  4599.6  325.92
  4614.5  325.80  4629.1  326.51  4668.4  325.77  4688.9  325.78  4799.1  323.28
  4819.1  322.51  4879.3  321.28  4899.3  320.18  4929.4  319.29  4959.4  317.85
  4969.5  317.07  4979.5  316.05  4996.5  311.04  4997.0  310.24  5002.0  310.24
  5002.5  311.04  5019.6  312.95  5039.6  316.25  5049.6  317.47  5079.7  318.49
  5086.1  319.09  5109.8  319.82  5129.8  319.71  5182.9  321.50  5298.0  324.20
#Mann=3,-1,0
  4505.6     0.1       0  4996.5    0.07       0  5002.5     0.1       0
Bank Sta=4996.5,5002.5
Exp/Cntr=0.3,0.1

Type RM Length L Ch R = 1,1484,266,266,266
BEGIN DESCRIPTION:
Mapping XS a835b719
END DESCRIPTION:
XS GIS Cut Line= 4
      2084884.86     13423841.74      2084969.49     13423559.61
      2084908.73     13423114.74      2084802.41     13422925.97
#Sta/Elev= 30
  4458.1  326.04  4473.2  326.54  4511.5  326.32  4538.2  327.11  4687.2  324.13
  4868.3  318.11  4949.1  313.40  4967.4  311.81  4972.4  312.91  4989.4  310.72
  4999.5  309.96  5006.6  309.89  5007.1  309.09  5012.1  309.09  5012.6  309.89
  5029.8  313.93  5039.7  315.17  5060.1  315.71  5110.6  317.98  5140.8  318.42
  5189.3  320.02  5247.3  320.67  5305.7  322.40  5327.6  322.31  5337.5  322.66
  5343.3  322.34  5359.2  322.73  5364.9  322.44  5386.6  323.26  5418.3  323.31
#Mann=3,-1,0
  4458.1     0.1       0  5006.6    0.07       0  5012.6     0.1       0
Bank Sta=5006.6,5012.6
Exp/Cntr=0.3,0.1

Type RM Length L Ch R = 1,1218,155,155,155
BEGIN DESCRIPTION:
Mapping XS 2f6f9d48
END DESCRIPTION:
XS GIS Cut Line= 4
      2084993.34     13423830.90      2085175.66     13423670.29
      2085197.36     13423140.78      2085080.87     13422918.59
#Sta/Elev= 30
  4431.0  324.55  4450.3  324.69  4513.9  323.48  4521.5  322.85  4528.2  323.09
  4535.7  322.27  4578.4  322.05  4606.5  322.60  4613.5  321.94  4648.6  321.92
  4670.2  321.21  4699.3  321.95  4729.3  320.61  4759.3  320.28  4899.5  315.65
  4939.5  312.48  4959.5  309.62  4996.5  307.74  4997.0  306.94  5002.0  306.94
  5002.5  307.74  5119.6  313.26  5189.7  314.19  5210.5  313.52  5217.9  313.68
  5223.6  314.51  5262.1  315.09  5289.8  316.55  5372.4  318.92  5454.8  319.97
#Mann=3,-1,0
  4431.0     0.1       0  4996.5    0.07       0  5002.5     0.1       0
Bank Sta=4996.5,5002.5
Exp/Cntr=0.3,0.1

Type RM Length L Ch R = 1,1063,269,269,269
BEGIN DESCRIPTION:
Mapping XS 02ce9cdb
END DESCRIPTION:
XS GIS Cut Line= 4
      2085080.20     13423820.00      2085227.74     13423702.84
      2085375.31     13423182.01      2085351.54     13423039.41
#Sta/Elev= 30
  4428.8  321.83  4463.9  322.02  4492.8  320.76  4513.6  321.05  4571.3  319.81
  4606.5  319.78  4628.0  318.81  4656.5  319.46  4677.3  318.74  4708.5  319.07
  4740.2  316.91  4874.8  313.23  4895.6  310.87  4915.1  310.76  4920.3  309.54
  4954.2  312.22  4959.4  312.15  4968.3  311.55  4996.5  305.30  4997.0  304.50
  5002.0  304.50  5002.5  305.30  5009.9  306.90  5027.3  309.33  5032.5  309.39
  5051.5  312.91  5139.4  317.94  5246.7  319.40  5251.7  318.76  5303.1  320.00
#Mann=3,-1,0
  4428.8     0.1       0  4996.5    0.07       0  5002.5     0.1       0
Bank Sta=4996.5,5002.5
Exp/Cntr=0.3,0.1

Type RM Length L Ch R = 1,794,219,219,219
BEGIN DESCRIPTION:
Mapping XS 209e06b6
END DESCRIPTION:
XS GIS Cut Line= 4
      2085071.49     13423872.12      2085290.67     13423789.65
      2085568.45     13423349.11      2085535.90     13423153.79
#Sta/Elev= 30
  4399.5  322.16  4456.7  320.08  4552.8  318.07  4602.6  315.76  4705.8  315.05
  4727.0  314.00  4778.8  313.72  4805.9  312.41  4828.3  312.36  4872.9  310.54
  4915.3  305.52  4930.6  305.60  4945.9  306.73  4951.8  308.44  4967.1  309.95
  4982.0  307.84  4988.3  305.44  4991.2  303.42  4991.7  302.62  4996.7  302.62
  4997.2  303.42  5009.5  304.18  5053.0  311.91  5088.4  313.22  5147.5  316.79
  5168.8  317.29  5205.1  319.23  5229.6  319.43  5265.9  321.25  5352.5  323.42
#Mann=3,-1,0
  4399.5     0.1       0  4991.2    0.07       0  4997.2     0.1       0
Bank Sta=4991.2,4997.2
Exp/Cntr=0.3,0.1

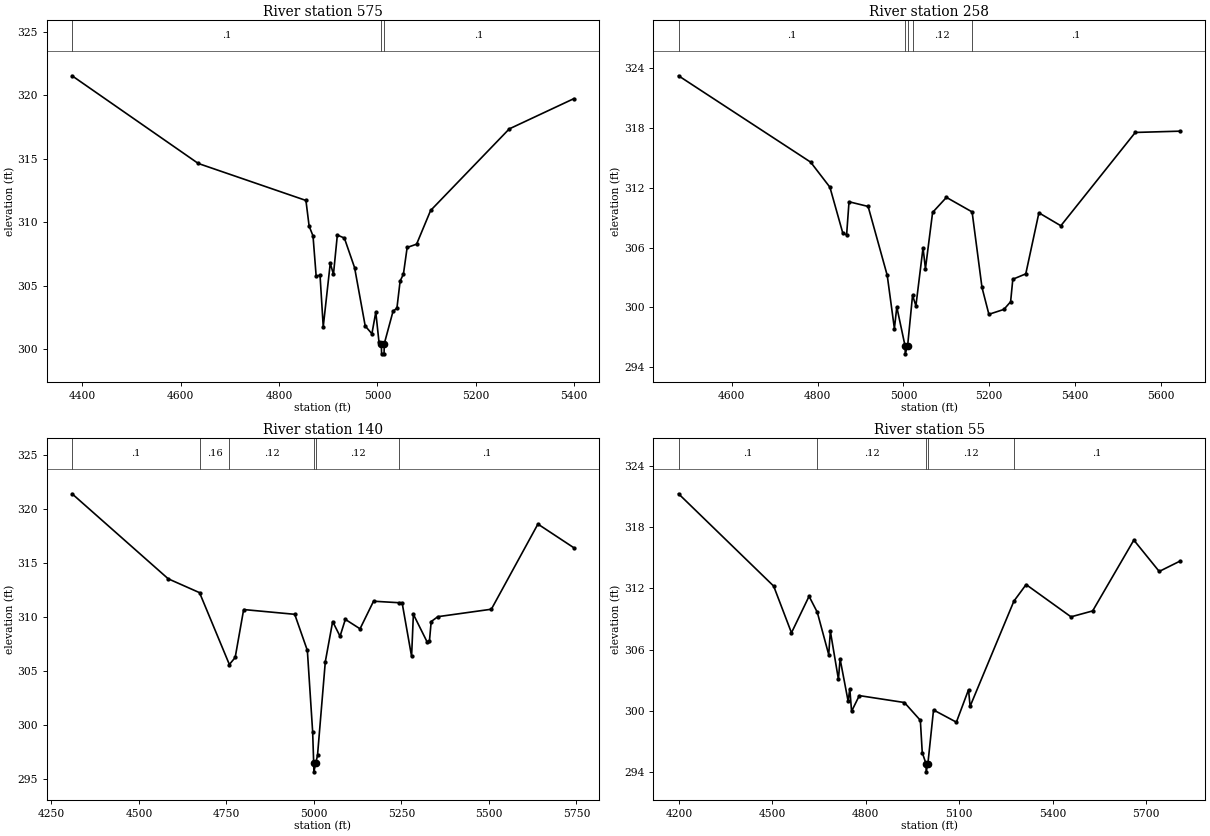
Type RM Length L Ch R = 1,575,317,317,317
BEGIN DESCRIPTION:
Mapping XS fa2409f9
END DESCRIPTION:
XS GIS Cut Line= 4
      2085060.64     13423930.71      2085438.24     13423809.18
      2085629.22     13423576.98      2085635.72     13423253.66
#Sta/Elev= 30
  4378.9  321.52  4635.6  314.62  4854.6  311.71  4861.1  309.69  4869.0  308.92
  4875.4  305.76  4883.3  305.82  4889.8  301.77  4904.1  306.77  4910.6  305.90
  4918.5  308.99  4932.8  308.75  4953.6  306.42  4975.2  301.83  4988.8  301.22
  4996.7  302.92  5003.2  300.57  5008.0  300.44  5008.5  299.64  5013.5  299.64
  5014.0  300.44  5031.8  302.99  5039.7  303.24  5046.2  305.37  5052.9  305.91
  5060.5  308.01  5079.7  308.27  5108.2  310.92  5268.2  317.34  5399.6  319.72
#Mann=3,-1,0
  4378.9     0.1       0  5008.0    0.07       0  5014.0     0.1       0
Bank Sta=5008,5014
Exp/Cntr=0.3,0.1

Type RM Length L Ch R = 1,258,118,118,118
BEGIN DESCRIPTION:
Mapping XS 81e35d32
END DESCRIPTION:
XS GIS Cut Line= 4
      2084997.66     13423961.09      2085334.08     13423976.28
      2085590.15     13423846.07      2085698.66     13423312.23
#Sta/Elev= 30
  4476.2  323.25  4783.9  314.58  4828.8  312.06  4858.9  307.44  4867.7  307.27
  4873.3  310.60  4917.8  310.13  4962.3  303.21  4979.0  297.87  4984.6  300.03
  5003.8  296.13  5004.3  295.33  5009.8  296.13  5021.3  301.21  5029.1  300.15
  5045.7  305.98  5051.3  303.88  5068.0  309.53  5100.2  311.04  5160.0  309.58
  5183.0  302.00  5199.1  299.30  5234.0  299.79  5249.7  300.56  5254.8  302.82
  5285.0  303.36  5315.6  309.49  5366.7  308.19  5540.1  317.56  5645.0  317.69
#Mann=5,-1,0
  4476.2     0.1       0  5003.8    0.07       0  5009.8     0.1       0
  5021.3    0.12       0  5160.0     0.1       0
Bank Sta=5003.8,5009.8
Exp/Cntr=0.3,0.1

Type RM Length L Ch R = 1,140,85,85,85
BEGIN DESCRIPTION:
Mapping XS 4fbe1d30
END DESCRIPTION:
XS GIS Cut Line= 4
      2084965.17     13424332.18      2085442.58     13424141.21
      2085609.68     13423887.31      2085731.22     13423283.98
#Sta/Elev= 30
  4309.0  321.39  4583.8  313.53  4673.2  312.25  4758.4  305.61  4775.0  306.26
  4799.2  310.69  4945.1  310.25  4981.2  306.91  4996.3  299.41  4999.3  296.49
  4999.8  295.69  5005.3  296.49  5010.2  297.21  5032.5  305.87  5053.5  309.58
  5074.6  308.22  5089.7  309.78  5131.7  308.91  5170.3  311.46  5243.5  311.32
  5251.9  311.32  5279.0  306.36  5284.1  310.25  5323.3  307.70  5329.9  307.74
  5335.0  309.58  5353.9  310.03  5506.9  310.72  5639.9  318.59  5742.6  316.40
#Mann=6,-1,0
  4309.0     0.1       0  4673.2    0.16       0  4758.4    0.12       0
  4999.3    0.07       0  5005.3    0.12       0  5243.5     0.1       0
Bank Sta=4999.3,5005.3
Exp/Cntr=0.3,0.1

Type RM Length L Ch R = 1,55,0,0,0
BEGIN DESCRIPTION:
UNT 75 in Lagunillas Cr Wtrshd 1.0
END DESCRIPTION:
XS GIS Cut Line= 4
      2084958.66     13424388.60      2085488.16     13424206.32
      2085658.11     13423946.12      2085796.01     13423218.34
#Sta/Elev= 30
  4199.0  321.30  4504.5  312.23  4561.7  307.64  4618.2  311.23  4644.6  309.66
  4681.3  305.50  4686.6  307.79  4712.5  303.07  4717.8  305.08  4743.7  300.91
  4749.0  302.15  4754.7  299.93  4779.6  301.47  4924.4  300.79  4975.6  299.04
  4981.7  295.87  4993.8  294.78  4994.3  293.98  4999.8  294.78  5017.9  300.06
  5091.3  298.86  5130.3  302.05  5135.4  300.42  5276.0  310.75  5315.2  312.38
  5459.4  309.21  5528.9  309.79  5661.2  316.75  5742.7  313.67  5810.5  314.70
#Mann=5,-1,0
  4199.0     0.1       0  4644.6    0.12       0  4993.8    0.07       0
  4999.8    0.12       0  5276.0     0.1       0
Bank Sta=4993.8,4999.8
Exp/Cntr=0.3,0.1

Chan Stop Cuts=-1