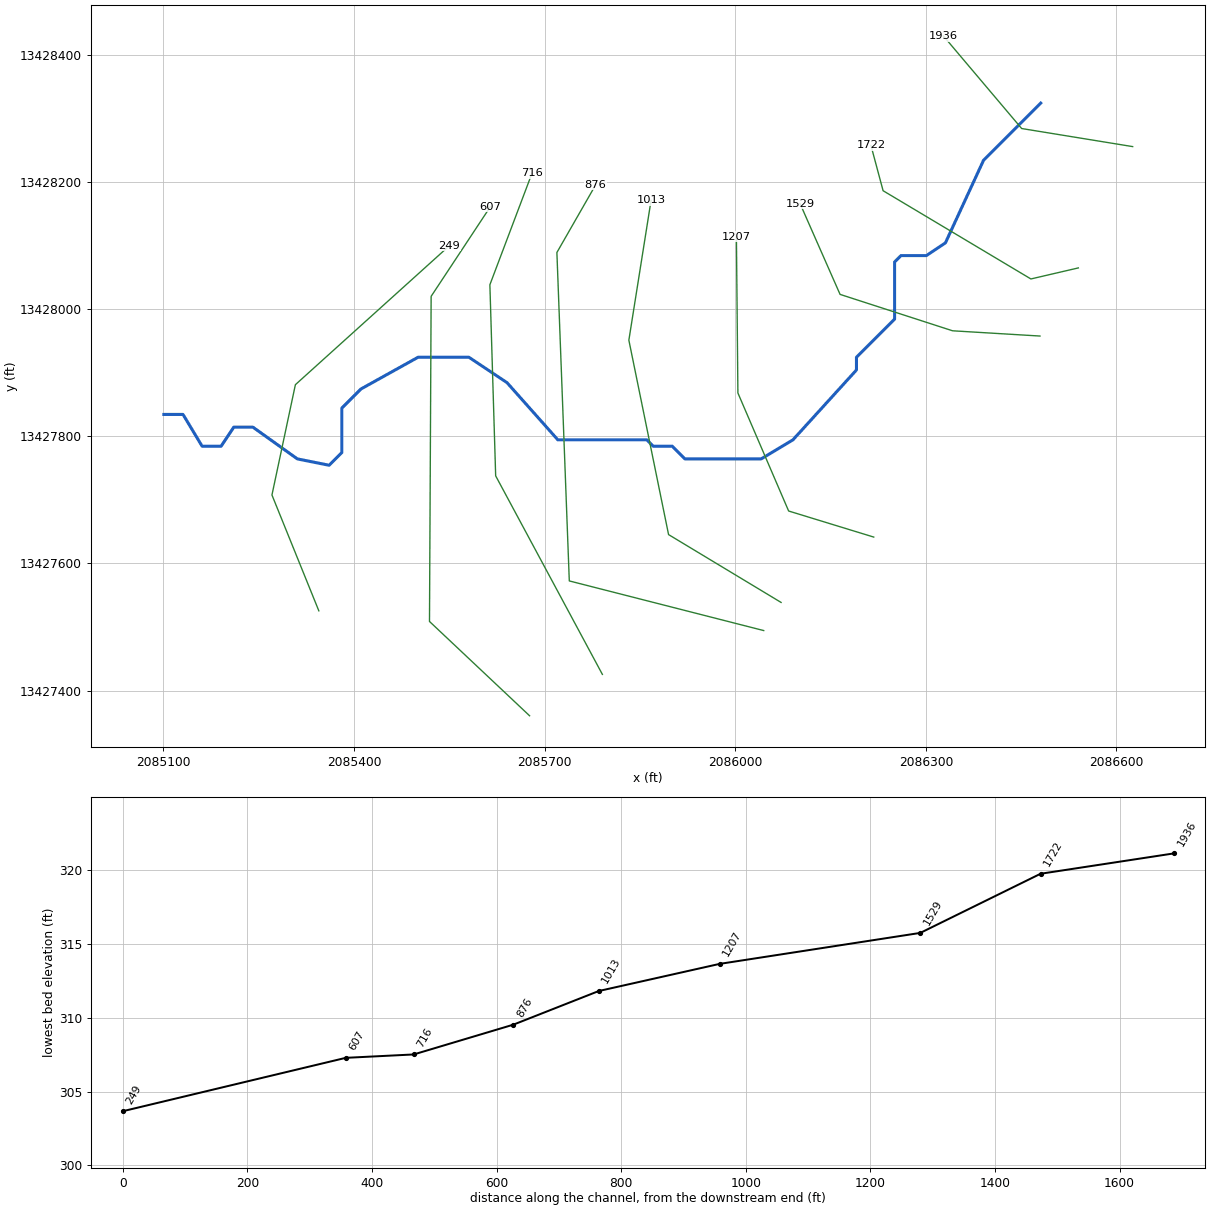
--- UNT 76 in Lagunillas Cr Wtrshd.prj (project) ---

Proj Title=UNT 76 in Lagunillas Cr Wtrshd Base Level Engineering
Current Plan=p01
Default Exp/Contr=0.3,0.1
English Units
Geom File=g01
Flow File=f01
Plan File=p01
BEGIN DESCRIPTION:
UNT 76 in Lagunillas Cr Wtrshd
END DESCRIPTION:

--- UNT 76 in Lagunillas Cr Wtrshd.p01 (plan) ---

Plan Title=Multiple Run
Short Identifier=Multiple
Geom File=g01
Flow File=f01
Subcritical Flow
K Sum by GR= 0
Std Step Tol= 0.01
Critical Tol= 0.01
Num of Std Step Trials= 20
Max Error Tol= 0.3
Flow Tol Ratio= 0.001
Split Flow NTrial= 30
Split Flow Tol= 0.02
Split Flow Ratio= 0.02
Log Output Level= 0
Friction Slope Method= 1
Unsteady Friction Slope Method= 2
Unsteady Bridges Friction Slope Method= 1
Parabolic Critical Depth
Global Vel Dist=  1 , 1 , 1
Global Log Level= 0
CheckData=True
Encroach Param= -1, 0, 0, 0
BEGIN DESCRIPTION:
Multiple Run
END DESCRIPTION:

--- UNT 76 in Lagunillas Cr Wtrshd.f01 (steady flow) ---

Flow Title=Multiple
Number of Profiles=7
Profile Names=10-year,25-year,50-year,1pct_min,100-year,1pct_plu,500-year
River Rch & RM= UNT 76 in Laguni,Reach-1,1936
     128     171     205     123     246     491     359
Boundary for River Rch & Prof#=UNT 76 in Laguni,Reach-1,1
Up Type=0
Dn Type=3
Dn Slope=0.005
Boundary for River Rch & Prof#=UNT 76 in Laguni,Reach-1,2
Up Type=0
Dn Type=3
Dn Slope=0.005
Boundary for River Rch & Prof#=UNT 76 in Laguni,Reach-1,3
Up Type=0
Dn Type=3
Dn Slope=0.005
Boundary for River Rch & Prof#=UNT 76 in Laguni,Reach-1,4
Up Type=0
Dn Type=3
Dn Slope=0.005
Boundary for River Rch & Prof#=UNT 76 in Laguni,Reach-1,5
Up Type=0
Dn Type=3
Dn Slope=0.005
Boundary for River Rch & Prof#=UNT 76 in Laguni,Reach-1,6
Up Type=0
Dn Type=3
Dn Slope=0.005
Boundary for River Rch & Prof#=UNT 76 in Laguni,Reach-1,7
Up Type=0
Dn Type=3
Dn Slope=0.005

--- UNT 76 in Lagunillas Cr Wtrshd.g01 (geometry) ---

Geom Title=Existing Conditions

River Reach=UNT 76 in Laguni,Reach-1
Reach XY= 30
      2086480.80     13428324.54      2086390.80     13428234.54
      2086330.80     13428104.54      2086300.80     13428084.54
      2086260.80     13428084.54      2086250.80     13428074.54
      2086250.80     13427984.54      2086190.80     13427924.54
      2086190.80     13427904.54      2086090.80     13427794.54
      2086040.80     13427764.54      2085920.80     13427764.54
      2085900.80     13427784.54      2085870.80     13427784.54
      2085860.80     13427794.54      2085720.80     13427794.54
      2085640.80     13427884.54      2085580.80     13427924.54
      2085500.80     13427924.54      2085410.80     13427874.54
      2085380.80     13427844.54      2085380.80     13427774.54
      2085360.80     13427754.54      2085310.80     13427764.54
      2085240.80     13427814.54      2085210.80     13427814.54
      2085190.80     13427784.54      2085160.80     13427784.54
      2085130.80     13427834.54      2085100.80     13427834.54

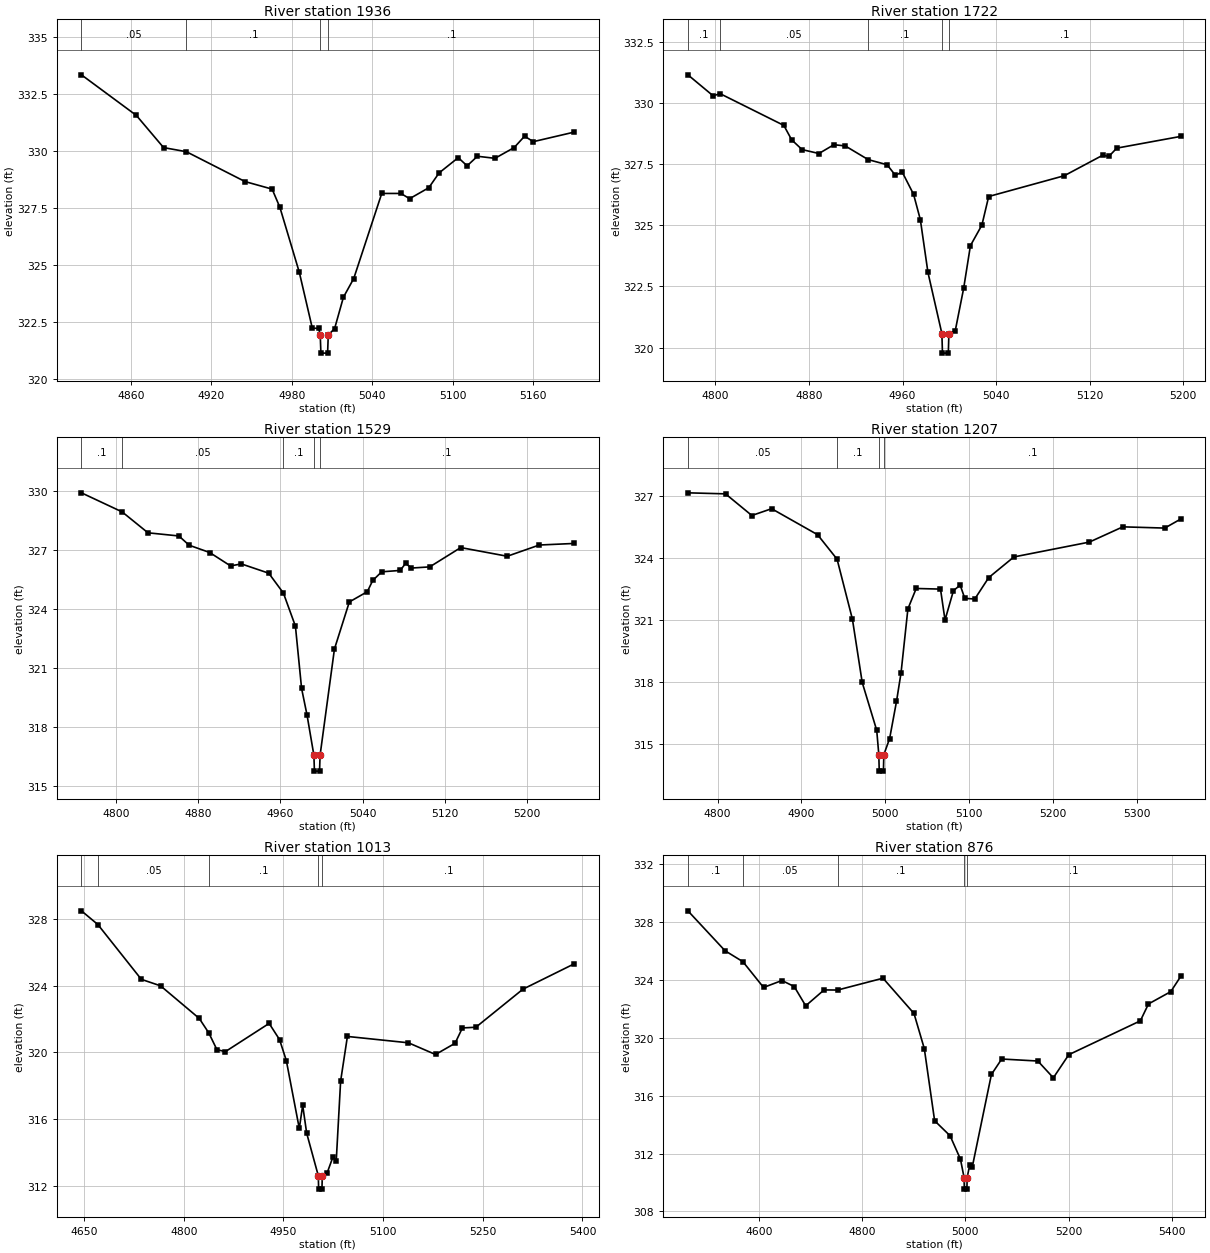
Type RM Length L Ch R = 1,1936,214,214,214
BEGIN DESCRIPTION:
UNT 76 in Lagunillas Cr Wtrshd 3.0
END DESCRIPTION:
XS GIS Cut Line= 3
      2086625.50     13428256.09      2086450.80     13428284.54
      2086327.62     13428430.25
#Sta/Elev= 30
  4823.0  333.35  4864.0  331.57  4884.3  330.16  4901.3  329.98  4945.1  328.67
  4965.3  328.34  4971.1  327.54  4985.6  324.69  4995.3  322.24  5000.0  322.24
  5001.2  321.95  5001.7  321.15  5006.7  321.15  5007.2  321.95  5011.9  322.22
  5018.5  323.60  5026.2  324.42  5047.1  328.15  5061.4  328.15  5067.9  327.92
  5082.2  328.40  5089.9  329.05  5104.2  329.72  5110.8  329.36  5118.5  329.78
  5131.6  329.69  5145.9  330.16  5153.7  330.66  5160.2  330.42  5190.8  330.84
#Mann=4,-1,0
  4823.0    0.05       0  4901.3     0.1       0  5001.2    0.07       0
  5007.2     0.1       0
Bank Sta=5001.2,5007.2
Exp/Cntr=0.3,0.1

Type RM Length L Ch R = 1,1722,193,193,193
BEGIN DESCRIPTION:
Mapping XS bcdf175e
END DESCRIPTION:
XS GIS Cut Line= 4
      2086540.04     13428065.15      2086465.35     13428047.77
      2086232.71     13428186.66      2086213.62     13428257.82
#Sta/Elev= 30
  4776.5  331.16  4798.1  330.30  4804.0  330.39  4858.5  329.09  4865.2  328.50
  4874.1  328.10  4888.5  327.94  4901.3  328.30  4911.0  328.25  4930.6  327.69
  4946.8  327.48  4953.8  327.05  4959.7  327.18  4969.4  326.27  4975.2  325.23
  4981.7  323.07  4993.6  320.57  4994.1  319.77  4999.1  319.77  4999.6  320.57
  5005.0  320.68  5012.2  322.42  5018.0  324.17  5027.8  325.01  5033.6  326.18
  5098.2  327.03  5131.1  327.87  5136.3  327.82  5143.1  328.16  5197.8  328.64
#Mann=5,-1,0
  4776.5     0.1       0  4804.0    0.05       0  4930.6     0.1       0
  4993.6    0.07       0  4999.6     0.1       0
Bank Sta=4993.6,4999.6
Exp/Cntr=0.3,0.1

Type RM Length L Ch R = 1,1529,322,322,322
BEGIN DESCRIPTION:
Mapping XS 982bda1f
END DESCRIPTION:
XS GIS Cut Line= 4
      2086479.69     13427957.91      2086342.09     13427966.18
      2086165.00     13428023.47      2086102.09     13428166.25
#Sta/Elev= 30
  4766.2  329.89  4805.9  328.92  4831.0  327.86  4861.1  327.70  4871.1  327.23
  4891.1  326.86  4911.4  326.18  4922.0  326.28  4948.6  325.81  4962.9  324.80
  4974.6  323.12  4980.6  319.96  4985.9  318.61  4992.6  316.56  4993.1  315.76
  4998.1  315.76  4998.6  316.56  5012.6  321.96  5027.1  324.35  5044.6  324.87
  5049.9  325.44  5058.6  325.88  5076.7  325.95  5081.9  326.31  5087.5  326.07
  5105.4  326.13  5135.6  327.11  5180.9  326.67  5212.1  327.24  5246.2  327.32
#Mann=5,-1,0
  4766.2     0.1       0  4805.9    0.05       0  4962.9     0.1       0
  4992.6    0.07       0  4998.6     0.1       0
Bank Sta=4992.6,4998.6
Exp/Cntr=0.3,0.1

Type RM Length L Ch R = 1,1207,194,194,194
BEGIN DESCRIPTION:
Mapping XS 78c3ab5b
END DESCRIPTION:
XS GIS Cut Line= 4
      2086217.96     13427641.51      2086084.04     13427682.54
      2086004.18     13427868.30      2086001.84     13428114.13
#Sta/Elev= 30
  4764.6  327.16  4809.5  327.11  4840.9  326.06  4864.5  326.39  4919.3  325.13
  4942.6  323.94  4960.9  321.03  4972.6  317.96  4989.9  315.64  4992.4  314.46
  4992.9  313.66  4997.9  313.66  4998.4  314.46  5005.3  315.24  5013.5  317.04
  5018.9  318.42  5027.1  321.53  5037.0  322.52  5066.0  322.49  5071.4  320.99
  5081.5  322.42  5089.5  322.68  5095.0  322.04  5106.9  322.01  5123.6  323.05
  5153.6  324.05  5243.6  324.77  5283.6  325.51  5333.6  325.45  5352.7  325.89
#Mann=4,-1,0
  4764.6    0.05       0  4942.6     0.1       0  4992.4    0.07       0
  4998.4     0.1       0
Bank Sta=4992.4,4998.4
Exp/Cntr=0.3,0.1

Type RM Length L Ch R = 1,1013,137,137,137
BEGIN DESCRIPTION:
Mapping XS a019ffa2
END DESCRIPTION:
XS GIS Cut Line= 4
      2086072.15     13427538.64      2085895.07     13427645.41
      2085832.57     13427951.40      2085867.50     13428171.36
#Sta/Elev= 30
  4645.9  328.48  4670.6  327.66  4736.0  324.38  4765.0  323.99  4823.2  322.04
  4837.6  321.17  4849.8  320.17  4862.5  320.05  4928.4  321.74  4944.1  320.77
  4954.3  319.51  4973.8  315.45  4978.9  316.84  4984.9  315.17  5002.4  312.62
  5002.9  311.82  5007.9  311.82  5008.4  312.62  5015.6  312.78  5024.3  313.73
  5029.4  313.51  5036.0  318.29  5046.2  320.96  5138.0  320.58  5178.8  319.88
  5208.2  320.55  5219.3  321.47  5239.5  321.51  5310.4  323.79  5387.7  325.31
#Mann=5,-1,0
  4645.9     0.1       0  4670.6    0.05       0  4837.6     0.1       0
  5002.4    0.07       0  5008.4     0.1       0
Bank Sta=5002.4,5008.4
Exp/Cntr=0.3,0.1

Type RM Length L Ch R = 1,876,160,160,160
BEGIN DESCRIPTION:
Mapping XS 601aa7b8
END DESCRIPTION:
XS GIS Cut Line= 4
      2086044.80     13427494.37      2085738.82     13427572.49
      2085719.29     13428089.42      2085780.26     13428195.79
#Sta/Elev= 30
  4462.0  328.79  4534.0  326.03  4568.7  325.27  4608.7  323.49  4644.4  323.97
  4668.2  323.55  4690.4  322.22  4726.1  323.32  4752.2  323.31  4840.3  324.13
  4900.4  321.69  4920.4  319.26  4940.4  314.27  4970.4  313.23  4990.5  311.61
  4997.5  310.34  4998.0  309.54  5003.0  309.54  5003.5  310.34  5008.4  311.21
  5013.4  311.07  5050.5  317.47  5070.5  318.54  5140.6  318.40  5170.6  317.24
  5200.6  318.84  5339.3  321.18  5355.1  322.35  5398.3  323.20  5417.7  324.26
#Mann=5,-1,0
  4462.0     0.1       0  4568.7    0.05       0  4752.2     0.1       0
  4997.5    0.07       0  5003.5     0.1       0
Bank Sta=4997.5,5003.5
Exp/Cntr=0.3,0.1

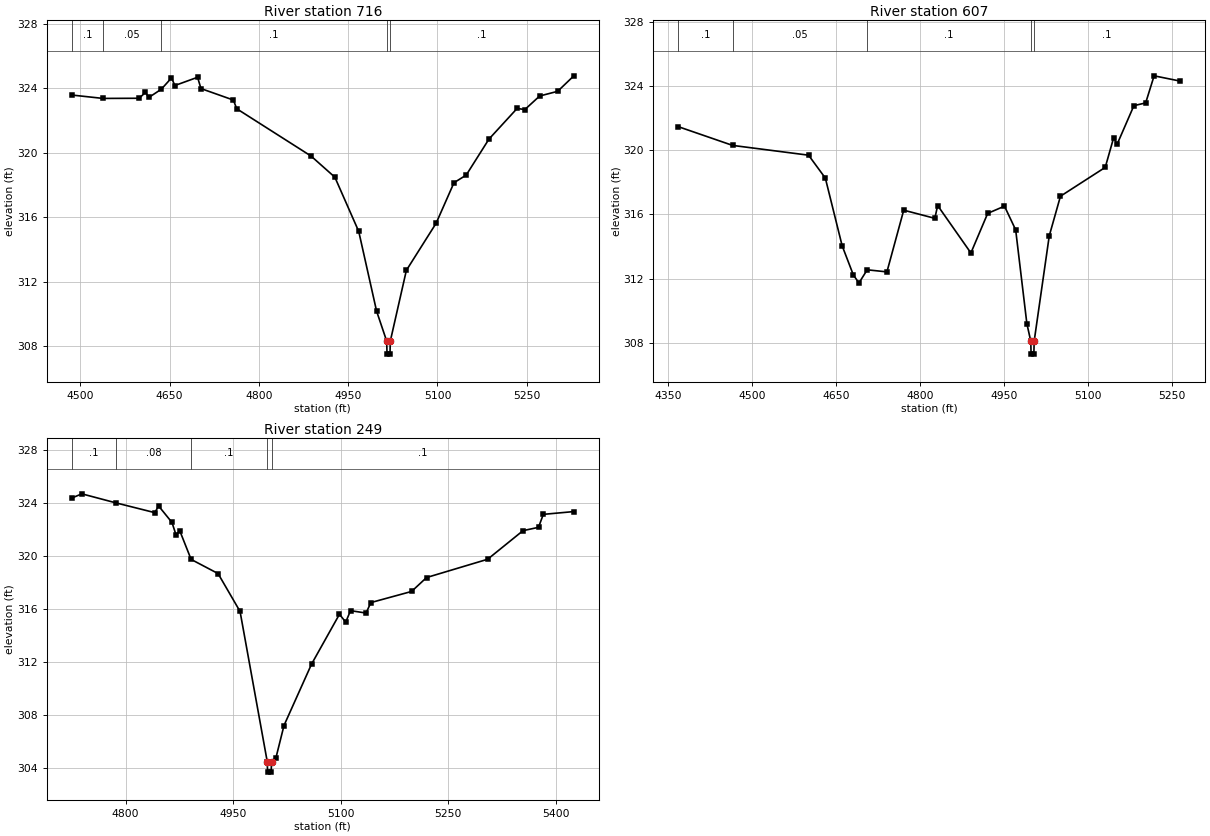
Type RM Length L Ch R = 1,716,109,109,109
BEGIN DESCRIPTION:
Mapping XS 8303fc79
END DESCRIPTION:
XS GIS Cut Line= 4
      2085790.89     13427425.38      2085622.93     13427737.86
      2085613.82     13428038.64      2085680.13     13428214.16
#Sta/Elev= 30
  4485.8  323.57  4538.4  323.36  4598.9  323.37  4609.5  323.73  4615.2  323.42
  4636.2  323.93  4653.3  324.63  4659.0  324.16  4697.1  324.67  4702.8  323.97
  4757.2  323.26  4762.9  322.72  4887.7  319.79  4927.7  318.48  4967.8  315.12
  4997.8  310.18  5014.8  308.32  5015.3  307.52  5020.3  307.52  5020.8  308.32
  5047.8  312.71  5097.8  315.63  5127.8  318.14  5148.3  318.61  5186.5  320.84
  5233.8  322.74  5246.8  322.67  5271.7  323.51  5301.9  323.80  5329.1  324.76
#Mann=5,-1,0
  4485.8     0.1       0  4538.4    0.05       0  4636.2     0.1       0
  5014.8    0.07       0  5020.8     0.1       0
Bank Sta=5014.8,5020.8
Exp/Cntr=0.3,0.1

Type RM Length L Ch R = 1,607,358,358,358
BEGIN DESCRIPTION:
Mapping XS 715ad062
END DESCRIPTION:
XS GIS Cut Line= 4
      2085676.31     13427360.26      2085518.77     13427508.69
      2085521.37     13428020.41      2085614.37     13428161.19
#Sta/Elev= 30
  4367.7  321.48  4464.8  320.31  4600.5  319.70  4630.5  318.27  4660.5  314.05
  4680.5  312.23  4690.5  311.73  4705.3  312.55  4740.5  312.42  4770.5  316.27
  4826.1  315.76  4831.1  316.56  4890.5  313.60  4920.5  316.07  4950.5  316.52
  4970.5  315.04  4990.5  309.19  4997.5  308.09  4998.0  307.29  5003.0  307.29
  5003.5  308.09  5030.5  314.67  5050.5  317.14  5130.5  318.94  5145.6  320.80
  5151.6  320.37  5181.7  322.79  5202.7  322.96  5217.8  324.65  5264.6  324.32
#Mann=5,-1,0
  4367.7     0.1       0  4464.8    0.05       0  4705.3     0.1       0
  4997.5    0.07       0  5003.5     0.1       0
Bank Sta=4997.5,5003.5
Exp/Cntr=0.3,0.1

Type RM Length L Ch R = 1,249,0,0,0
BEGIN DESCRIPTION:
UNT 76 in Lagunillas Cr Wtrshd 1.0
END DESCRIPTION:
XS GIS Cut Line= 4
      2085344.60     13427525.42      2085270.81     13427707.73
      2085307.70     13427881.34      2085549.97     13428099.97
#Sta/Elev= 30
  4724.8  324.36  4738.8  324.68  4786.2  324.00  4840.6  323.26  4846.0  323.76
  4864.6  322.52  4870.2  321.59  4875.5  321.89  4891.3  319.73  4928.9  318.66
  4959.6  315.80  4997.5  304.47  4998.0  303.67  5003.0  303.67  5003.5  304.47
  5009.7  304.76  5020.9  307.19  5059.3  311.82  5098.3  315.59  5107.0  314.99
  5113.7  315.86  5135.4  315.68  5142.1  316.47  5198.9  317.31  5219.8  318.36
  5305.0  319.74  5354.4  321.90  5376.0  322.15  5382.7  323.13  5425.3  323.34
#Mann=5,-1,0
  4724.8     0.1       0  4786.2    0.08       0  4891.3     0.1       0
  4997.5    0.07       0  5003.5     0.1       0
Bank Sta=4997.5,5003.5
Exp/Cntr=0.3,0.1

Chan Stop Cuts=-1