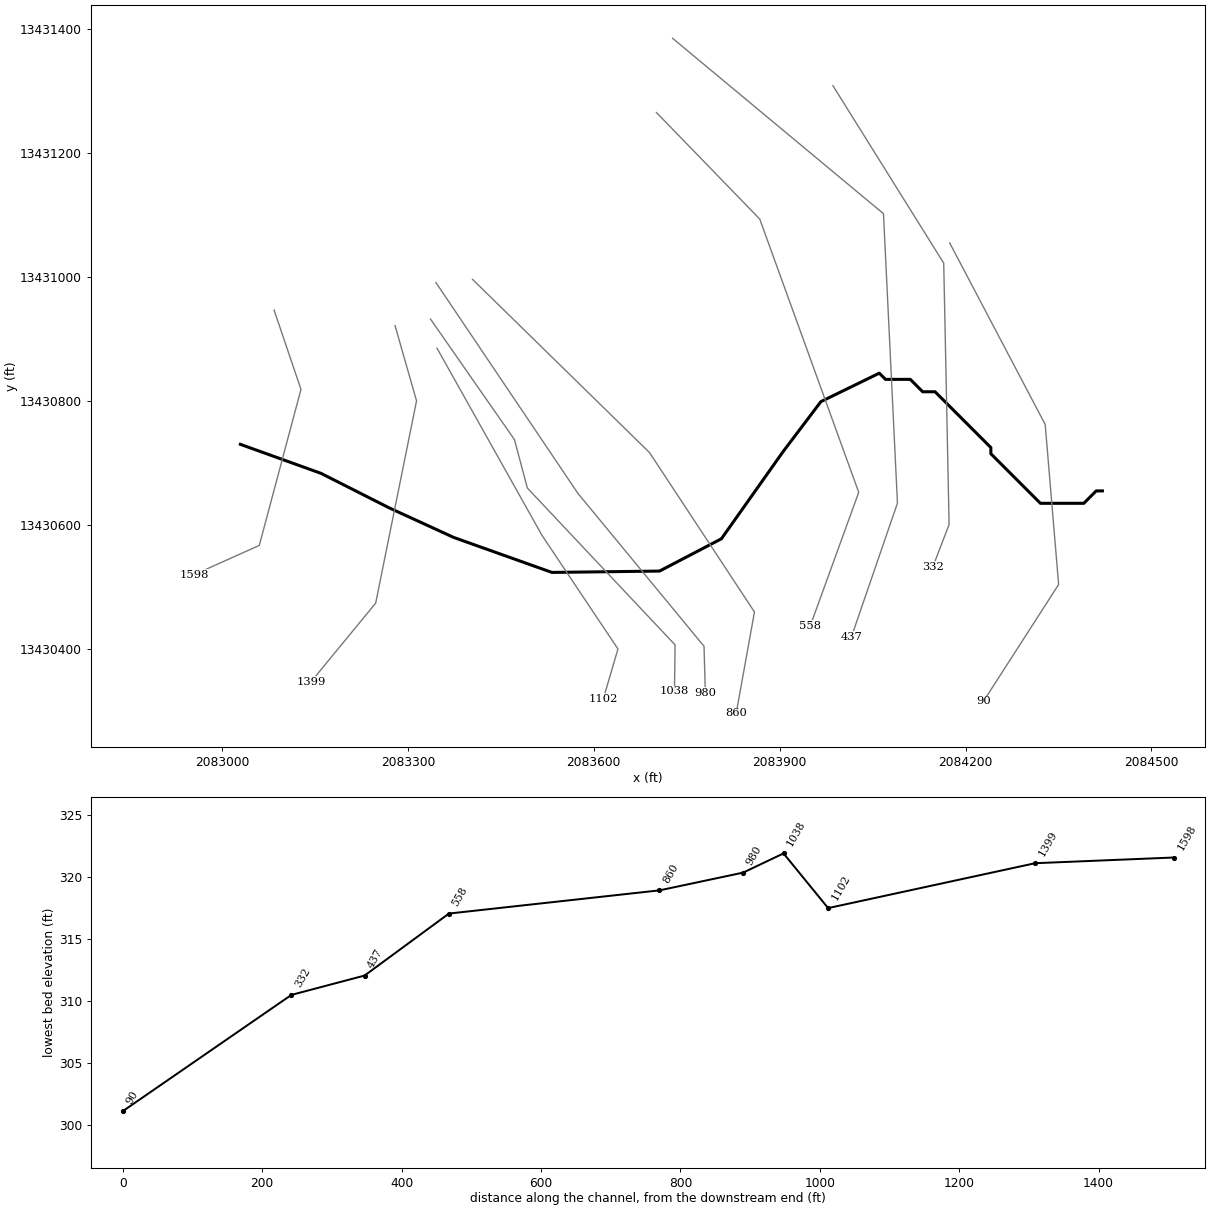
--- UNT 83 in Lagunillas Cr Wtrshd.prj (project) ---

Proj Title=UNT 83 in Lagunillas Cr Wtrshd Base Level Engineering
Current Plan=p01
Default Exp/Contr=0.3,0.1
English Units
Geom File=g01
Flow File=f01
Plan File=p01
BEGIN DESCRIPTION:
UNT 83 in Lagunillas Cr Wtrshd
END DESCRIPTION:

--- UNT 83 in Lagunillas Cr Wtrshd.p01 (plan) ---

Plan Title=Multiple Run
Short Identifier=Multiple
Geom File=g01
Flow File=f01
Subcritical Flow
K Sum by GR= 0
Std Step Tol= 0.01
Critical Tol= 0.01
Num of Std Step Trials= 20
Max Error Tol= 0.3
Flow Tol Ratio= 0.001
Split Flow NTrial= 30
Split Flow Tol= 0.02
Split Flow Ratio= 0.02
Log Output Level= 0
Friction Slope Method= 1
Unsteady Friction Slope Method= 2
Unsteady Bridges Friction Slope Method= 1
Parabolic Critical Depth
Global Vel Dist=  1 , 1 , 1
Global Log Level= 0
CheckData=True
Encroach Param= -1, 0, 0, 0
BEGIN DESCRIPTION:
Multiple Run
END DESCRIPTION:

--- UNT 83 in Lagunillas Cr Wtrshd.f01 (steady flow) ---

Flow Title=Multiple
Number of Profiles=7
Profile Names=10-year,25-year,50-year,1pct_min,100-year,1pct_plu,500-year
River Rch & RM= UNT 83 in Laguni,Reach-1,1598
      31      37      41      23      46      93      59
Boundary for River Rch & Prof#=UNT 83 in Laguni,Reach-1,1
Up Type=0
Dn Type=3
Dn Slope=0.005
Boundary for River Rch & Prof#=UNT 83 in Laguni,Reach-1,2
Up Type=0
Dn Type=3
Dn Slope=0.005
Boundary for River Rch & Prof#=UNT 83 in Laguni,Reach-1,3
Up Type=0
Dn Type=3
Dn Slope=0.005
Boundary for River Rch & Prof#=UNT 83 in Laguni,Reach-1,4
Up Type=0
Dn Type=3
Dn Slope=0.005
Boundary for River Rch & Prof#=UNT 83 in Laguni,Reach-1,5
Up Type=0
Dn Type=3
Dn Slope=0.005
Boundary for River Rch & Prof#=UNT 83 in Laguni,Reach-1,6
Up Type=0
Dn Type=3
Dn Slope=0.005
Boundary for River Rch & Prof#=UNT 83 in Laguni,Reach-1,7
Up Type=0
Dn Type=3
Dn Slope=0.005

--- UNT 83 in Lagunillas Cr Wtrshd.g01 (geometry) ---

Geom Title=Existing Conditions

River Reach=UNT 83 in Laguni,Reach-1
Reach XY= 20
      2083029.73     13430729.72      2083159.94     13430682.85
      2083269.95     13430627.17      2083374.12     13430579.43
      2083532.54     13430523.01      2083706.15     13430525.18
      2083805.98     13430577.26      2083905.80     13430718.32
      2083966.57     13430798.62      2084060.80     13430844.54
      2084070.80     13430834.54      2084110.80     13430834.54
      2084130.80     13430814.54      2084150.80     13430814.54
      2084240.80     13430724.54      2084240.80     13430714.54
      2084320.80     13430634.54      2084390.80     13430634.54
      2084410.80     13430654.54      2084420.80     13430654.54

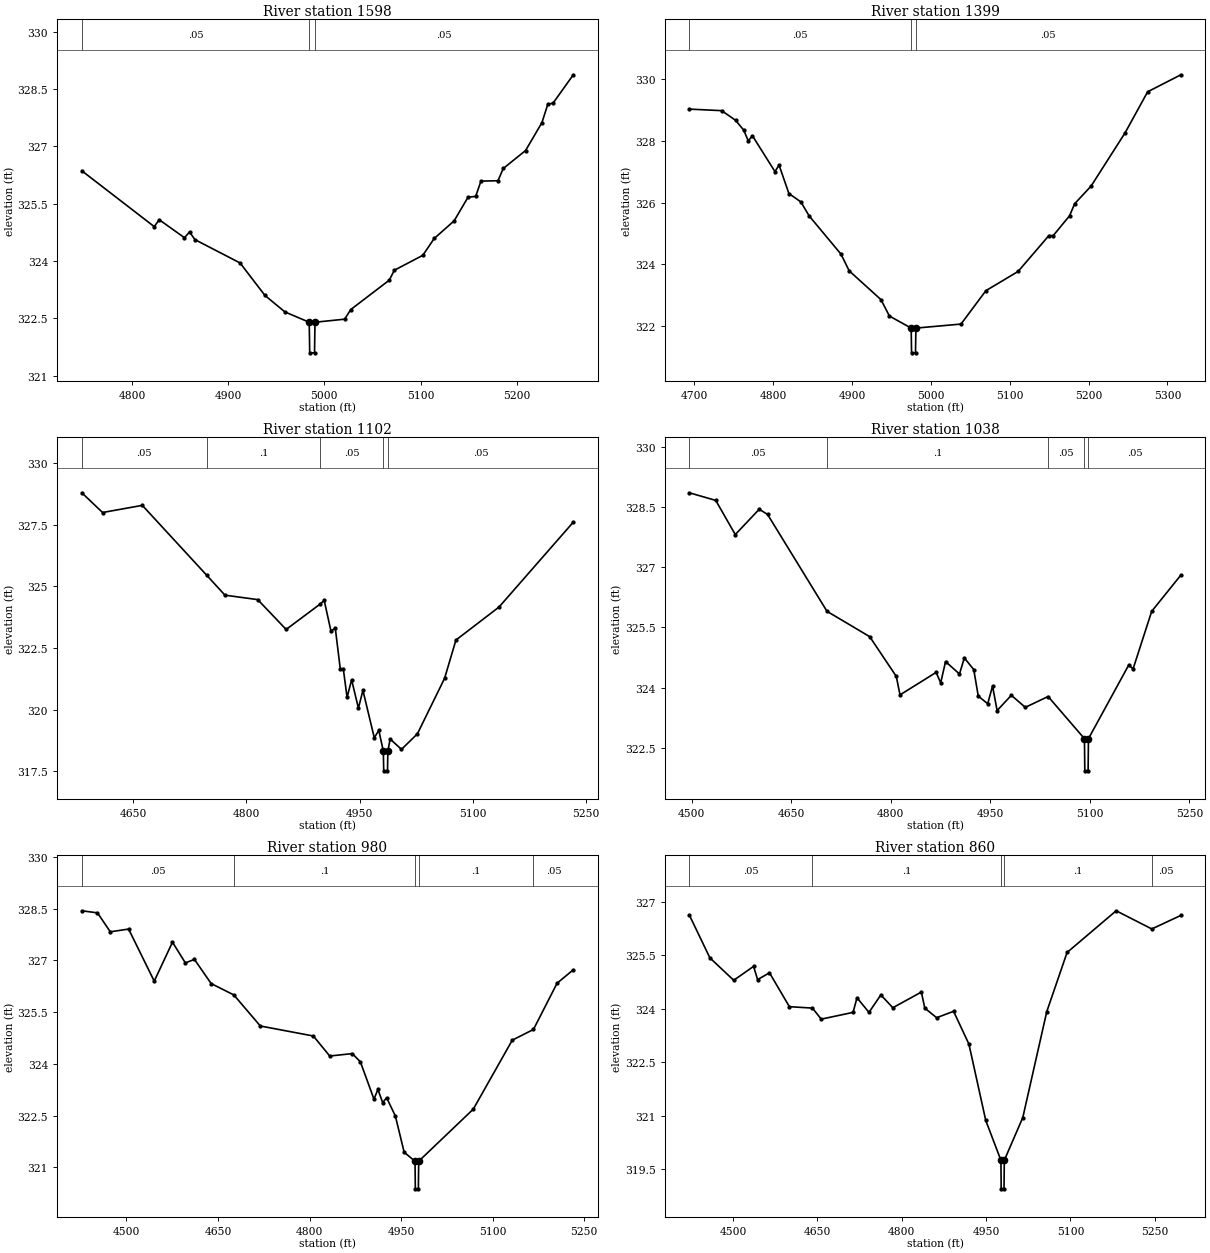
Type RM Length L Ch R = 1,1598,199,199,199
BEGIN DESCRIPTION:
UNT 83 in Lagunillas Cr Wtrshd 2.0
END DESCRIPTION:
XS GIS Cut Line= 4
      2083084.17     13430946.35      2083127.56     13430818.34
      2083060.29     13430566.60      2082955.23     13430519.43
#Sta/Elev= 30
  4747.9  326.36  4823.2  324.90  4828.4  325.08  4854.6  324.61  4859.9  324.76
  4865.5  324.56  4912.4  323.95  4938.3  323.10  4959.0  322.67  4984.3  322.40
  4984.8  321.60  4989.8  321.60  4990.3  322.40  5021.1  322.48  5027.4  322.73
  5067.5  323.50  5072.8  323.76  5102.4  324.15  5114.2  324.59  5134.9  325.05
  5149.4  325.67  5157.3  325.69  5162.8  326.09  5180.5  326.10  5186.0  326.42
  5209.2  326.89  5226.2  327.62  5232.3  328.10  5237.8  328.13  5258.8  328.87
#Mann=3,-1,0
  4747.9    0.05       0  4984.3    0.03       0  4990.3    0.05       0
Bank Sta=4984.3,4990.3
Exp/Cntr=0.3,0.1

Type RM Length L Ch R = 1,1399,297,297,297
BEGIN DESCRIPTION:
Mapping XS ecdc3e23
END DESCRIPTION:
XS GIS Cut Line= 4
      2083279.32     13430921.38      2083314.05     13430799.82
      2083248.08     13430473.43      2083143.89     13430346.67
#Sta/Elev= 30
  4693.5  329.02  4734.5  328.97  4752.1  328.66  4762.5  328.34  4768.3  327.99
  4773.5  328.16  4802.1  327.00  4807.3  327.21  4819.8  326.29  4835.0  326.02
  4845.4  325.57  4885.9  324.33  4896.3  323.79  4936.6  322.86  4947.3  322.33
  4974.9  321.94  4975.4  321.14  4980.4  321.14  4980.9  321.94  5038.1  322.07
  5069.7  323.15  5110.5  323.77  5149.6  324.93  5155.1  324.93  5175.8  325.57
  5182.3  325.96  5203.1  326.53  5246.2  328.25  5274.9  329.58  5317.0  330.13
#Mann=3,-1,0
  4693.5    0.05       0  4974.9    0.03       0  4980.9    0.05       0
Bank Sta=4974.9,4980.9
Exp/Cntr=0.3,0.1

Type RM Length L Ch R = 1,1102,64,64,64
BEGIN DESCRIPTION:
Mapping XS 35f7b326
END DESCRIPTION:
XS GIS Cut Line= 4
      2083347.06     13430884.85      2083516.45     13430582.88
      2083639.06     13430399.50      2083615.46     13430319.02
#Sta/Elev= 30
  4582.1  328.79  4609.6  327.99  4662.2  328.28  4747.4  325.45  4771.6  324.64
  4815.0  324.46  4852.6  323.25  4898.1  324.29  4903.0  324.43  4911.9  323.19
  4917.7  323.30  4924.3  321.65  4928.3  321.65  4933.3  320.50  4939.3  321.21
  4948.3  320.06  4954.3  320.78  4969.3  318.86  4975.3  319.16  4981.3  318.32
  4981.8  317.52  4986.8  317.52  4987.3  318.32  4990.3  318.81  5005.3  318.39
  5026.4  319.02  5062.4  321.27  5077.4  322.82  5134.5  324.16  5232.8  327.60
#Mann=5,-1,0
  4582.1    0.05       0  4747.4     0.1       0  4898.1    0.05       0
  4981.3    0.03       0  4987.3    0.05       0
Bank Sta=4981.3,4987.3
Exp/Cntr=0.3,0.1

Type RM Length L Ch R = 1,1038,58,58,58
BEGIN DESCRIPTION:
Mapping XS f4c8ca32
END DESCRIPTION:
XS GIS Cut Line= 5
      2083336.60     13430931.79      2083472.04     13430737.32
      2083492.87     13430659.19      2083731.29     13430406.01
      2083730.21     13430331.13
#Sta/Elev= 30
  4496.6  328.85  4536.4  328.66  4565.8  327.81  4601.9  328.44  4614.5  328.31
  4704.0  325.90  4768.3  325.27  4808.4  324.28  4814.0  323.82  4868.4  324.38
  4875.3  324.12  4882.6  324.65  4903.6  324.34  4910.9  324.74  4925.1  324.45
  4931.9  323.79  4946.1  323.60  4953.4  324.04  4960.3  323.43  4981.7  323.81
  5002.8  323.51  5037.1  323.78  5091.9  322.73  5092.4  321.93  5097.4  321.93
  5097.9  322.73  5158.5  324.56  5165.2  324.47  5193.2  325.90  5237.1  326.80
#Mann=5,-1,0
  4496.6    0.05       0  4704.0     0.1       0  5037.1    0.05       0
  5091.9    0.07       0  5097.9    0.05       0
Bank Sta=5091.9,5097.9
Exp/Cntr=0.3,0.1

Type RM Length L Ch R = 1,980,120,120,120
BEGIN DESCRIPTION:
Mapping XS 09c0f462
END DESCRIPTION:
XS GIS Cut Line= 4
      2083345.29     13430990.81      2083574.47     13430650.51
      2083777.95     13430403.84      2083780.08     13430328.41
#Sta/Elev= 30
  4426.8  328.44  4452.5  328.38  4473.5  327.83  4503.5  327.91  4545.5  326.40
  4575.4  327.53  4596.5  326.93  4611.4  327.03  4638.8  326.33  4676.0  326.00
  4719.4  325.10  4806.3  324.81  4833.1  324.23  4870.1  324.30  4883.4  324.06
  4905.6  322.98  4912.1  323.26  4919.9  322.88  4926.4  323.02  4940.7  322.49
  4955.1  321.44  4972.9  321.18  4973.4  320.38  4978.4  320.38  4978.9  321.18
  5068.4  322.69  5132.3  324.69  5167.0  325.00  5205.7  326.34  5232.3  326.73
#Mann=5,-1,0
  4426.8    0.05       0  4676.0     0.1       0  4972.9    0.07       0
  4978.9     0.1       0  5167.0    0.05       0
Bank Sta=4972.9,4978.9
Exp/Cntr=0.3,0.1

Type RM Length L Ch R = 1,860,302,302,302
BEGIN DESCRIPTION:
Mapping XS 267e4f72
END DESCRIPTION:
XS GIS Cut Line= 4
      2083404.36     13430995.96      2083690.06     13430716.34
      2083859.33     13430459.18      2083829.85     13430295.55
#Sta/Elev= 30
  4422.4  326.63  4458.9  325.43  4501.3  324.80  4536.6  325.19  4543.8  324.82
  4564.9  325.01  4600.3  324.06  4641.3  324.02  4656.9  323.71  4713.5  323.90
  4720.5  324.31  4741.8  323.90  4762.9  324.39  4784.2  324.03  4835.0  324.47
  4841.0  324.02  4862.1  323.75  4892.2  323.93  4919.5  323.01  4949.4  320.87
  4976.4  319.75  4976.9  318.95  4981.9  318.95  4982.4  319.75  5015.3  320.95
  5057.9  323.92  5094.0  325.58  5181.3  326.75  5244.7  326.24  5296.3  326.62
#Mann=5,-1,0
  4422.4    0.05       0  4641.3     0.1       0  4976.4    0.07       0
  4982.4     0.1       0  5244.7    0.05       0
Bank Sta=4976.4,4982.4
Exp/Cntr=0.3,0.1

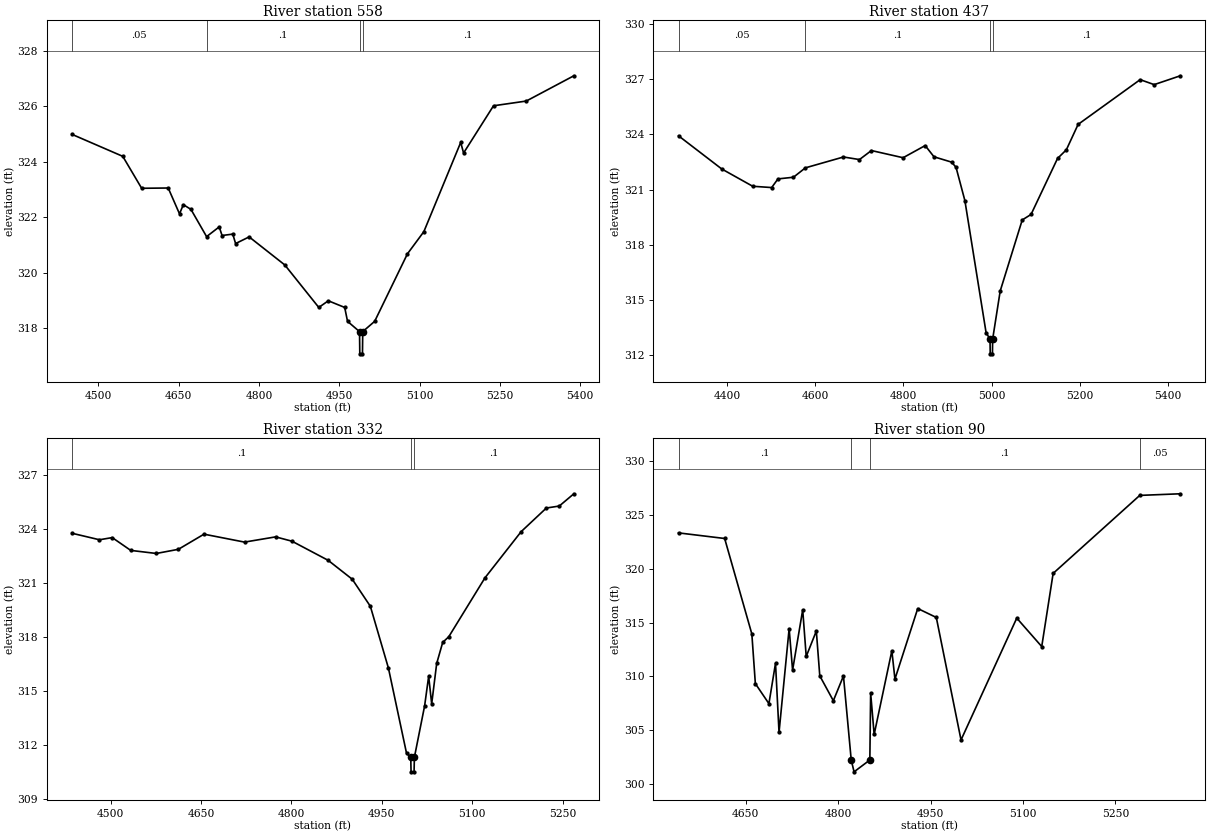
Type RM Length L Ch R = 1,558,121,121,121
BEGIN DESCRIPTION:
Mapping XS dd5db418
END DESCRIPTION:
XS GIS Cut Line= 4
      2083701.22     13431265.08      2083867.87     13431093.22
      2084027.59     13430652.25      2083949.48     13430436.99
#Sta/Elev= 30
  4450.8  324.98  4545.5  324.19  4580.8  323.04  4630.4  323.05  4651.5  322.12
  4658.7  322.45  4672.9  322.28  4702.1  321.30  4725.7  321.65  4731.0  321.34
  4751.0  321.39  4756.3  321.05  4781.6  321.29  4848.2  320.28  4911.7  318.75
  4929.5  318.99  4960.1  318.75  4965.4  318.25  4987.8  317.88  4988.3  317.08
  4993.3  317.08  4993.8  317.88  5016.1  318.25  5077.3  320.68  5108.0  321.48
  5176.8  324.69  5182.2  324.31  5238.1  326.01  5299.3  326.18  5388.2  327.09
#Mann=4,-1,0
  4450.8    0.05       0  4702.1     0.1       0  4987.8    0.07       0
  4993.8     0.1       0
Bank Sta=4987.8,4993.8
Exp/Cntr=0.3,0.1

Type RM Length L Ch R = 1,437,105,105,105
BEGIN DESCRIPTION:
Mapping XS 982a1109
END DESCRIPTION:
XS GIS Cut Line= 4
      2083727.28     13431384.86      2084067.52     13431101.90
      2084090.09     13430634.89      2084015.79     13430418.89
#Sta/Elev= 30
  4289.8  323.92  4387.8  322.12  4458.1  321.18  4501.1  321.11  4515.4  321.58
  4550.5  321.67  4577.6  322.18  4664.0  322.77  4700.3  322.63  4727.4  323.12
  4799.3  322.73  4849.4  323.39  4869.4  322.78  4909.4  322.49  4919.4  322.21
  4939.5  320.40  4987.6  313.23  4996.5  312.88  4997.0  312.08  5002.0  312.08
  5002.5  312.88  5019.6  315.49  5069.6  319.35  5089.6  319.65  5149.7  322.69
  5169.7  323.16  5196.4  324.54  5337.2  326.97  5369.0  326.70  5428.3  327.18
#Mann=4,-1,0
  4289.8    0.05       0  4577.6     0.1       0  4996.5    0.07       0
  5002.5     0.1       0
Bank Sta=4996.5,5002.5
Exp/Cntr=0.3,0.1

Type RM Length L Ch R = 1,332,242,242,242
BEGIN DESCRIPTION:
Mapping XS df9ed04d
END DESCRIPTION:
XS GIS Cut Line= 4
      2083985.95     13431308.46      2084164.75     13431022.04
      2084173.43     13430600.16      2084147.37     13430532.42
#Sta/Elev= 30
  4436.2  323.75  4481.6  323.39  4502.8  323.51  4533.5  322.80  4575.9  322.63
  4612.5  322.86  4655.0  323.70  4722.2  323.26  4773.8  323.55  4800.9  323.31
  4860.9  322.25  4900.9  321.20  4930.9  319.70  4960.9  316.27  4990.9  311.55
  4997.9  311.32  4998.4  310.52  5003.4  310.52  5003.9  311.32  5020.9  314.18
  5027.6  315.82  5032.6  314.29  5040.9  316.53  5050.9  317.70  5060.9  318.01
  5121.0  321.28  5181.0  323.84  5222.8  325.15  5244.2  325.26  5268.4  325.94
#Mann=3,-1,0
  4436.2     0.1       0  4997.9    0.07       0  5003.9     0.1       0
Bank Sta=4997.9,5003.9
Exp/Cntr=0.3,0.1

Type RM Length L Ch R = 1,90,0,0,0
BEGIN DESCRIPTION:
UNT 83 in Lagunillas Cr Wtrshd 1.0
END DESCRIPTION:
XS GIS Cut Line= 4
      2084174.39     13431054.74      2084328.48     13430761.77
      2084350.18     13430503.52      2084229.11     13430315.39
#Sta/Elev= 30
  4541.3  323.32  4616.1  322.80  4660.2  313.94  4665.9  309.33  4687.9  307.47
  4698.6  311.22  4704.3  304.80  4720.7  314.43  4726.3  310.58  4742.7  316.18
  4748.4  311.85  4764.8  314.21  4770.4  310.05  4792.4  307.74  4808.8  310.04
  4821.4  302.24  4826.0  301.14  4851.6  302.24  4852.9  308.45  4858.6  304.61
  4887.3  312.38  4892.3  309.75  4929.3  316.30  4959.4  315.47  4999.5  304.10
  5089.9  315.41  5130.4  312.77  5148.9  319.56  5289.4  326.80  5355.2  326.95
#Mann=4,-1,0
  4541.3     0.1       0  4821.4    0.07       0  4851.6     0.1       0
  5289.4    0.05       0
Bank Sta=4821.4,4851.6
Exp/Cntr=0.3,0.1

Chan Stop Cuts=-1