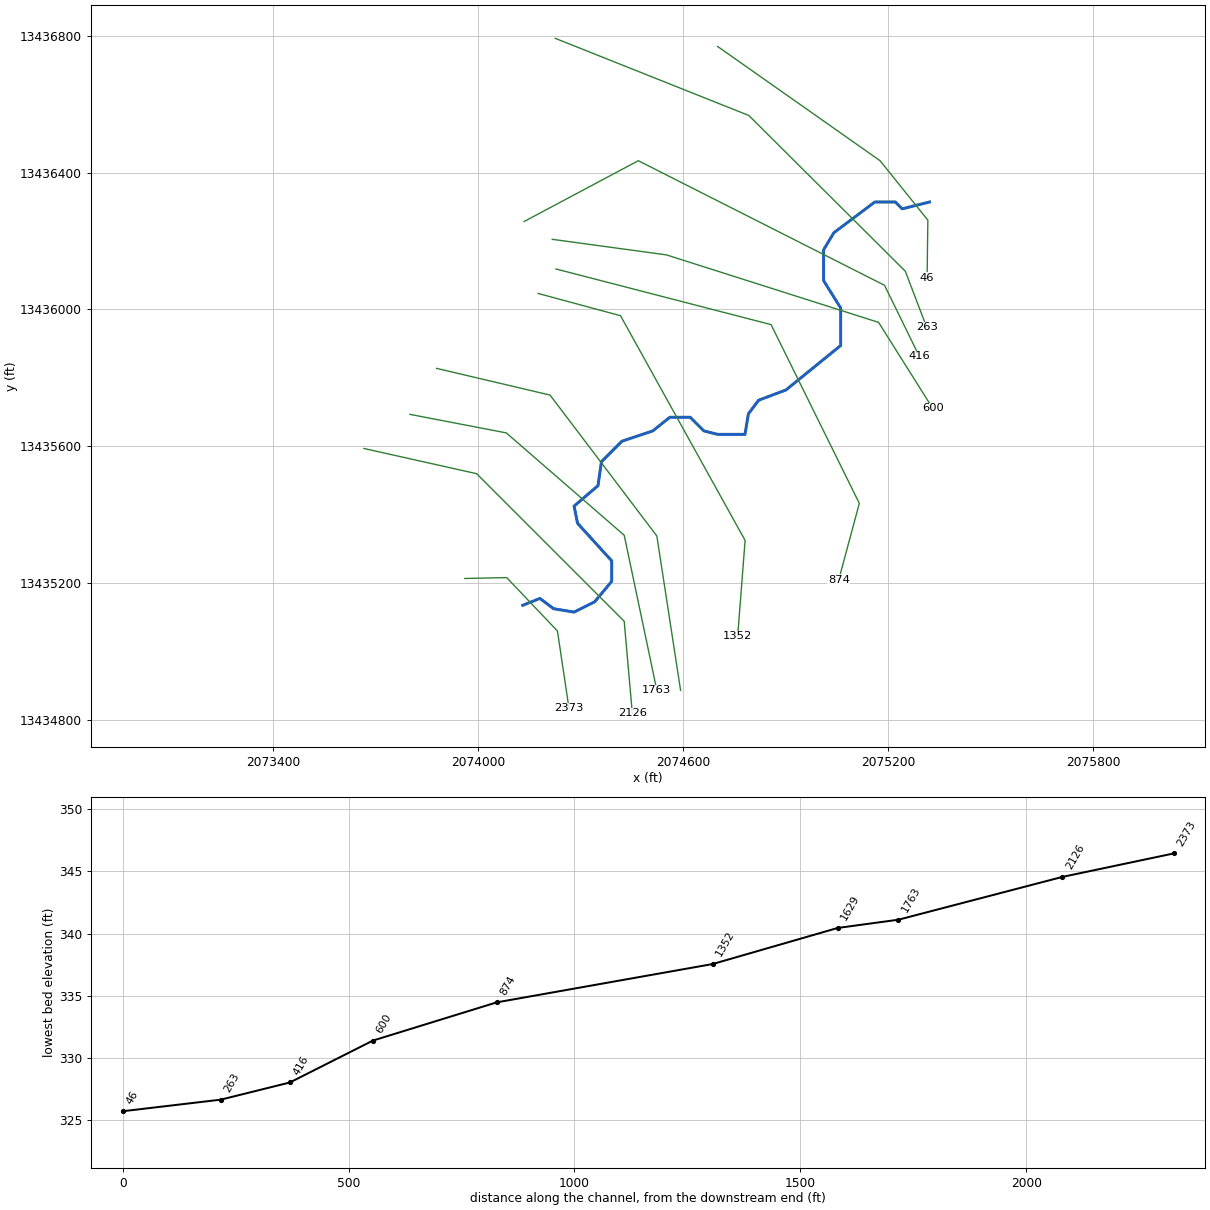
--- UNT 84 in Lagunillas Cr Wtrshd.prj (project) ---

Proj Title=UNT 84 in Lagunillas Cr Wtrshd Base Level Engineering
Current Plan=p01
Default Exp/Contr=0.3,0.1
English Units
Geom File=g01
Flow File=f01
Plan File=p01
BEGIN DESCRIPTION:
UNT 84 in Lagunillas Cr Wtrshd
END DESCRIPTION:

--- UNT 84 in Lagunillas Cr Wtrshd.p01 (plan) ---

Plan Title=Multiple Run
Short Identifier=Multiple
Geom File=g01
Flow File=f01
Subcritical Flow
K Sum by GR= 0
Std Step Tol= 0.01
Critical Tol= 0.01
Num of Std Step Trials= 20
Max Error Tol= 0.3
Flow Tol Ratio= 0.001
Split Flow NTrial= 30
Split Flow Tol= 0.02
Split Flow Ratio= 0.02
Log Output Level= 0
Friction Slope Method= 1
Unsteady Friction Slope Method= 2
Unsteady Bridges Friction Slope Method= 1
Parabolic Critical Depth
Global Vel Dist=  1 , 1 , 1
Global Log Level= 0
CheckData=True
Encroach Param= -1, 0, 0, 0
BEGIN DESCRIPTION:
Multiple Run
END DESCRIPTION:

--- UNT 84 in Lagunillas Cr Wtrshd.f01 (steady flow) ---

Flow Title=Multiple
Number of Profiles=7
Profile Names=10-year,25-year,50-year,1pct_min,100-year,1pct_plu,500-year
River Rch & RM= UNT 84 in Laguni,Reach-1,2373
     186     257     316     194     388     774     592
Boundary for River Rch & Prof#=UNT 84 in Laguni,Reach-1,1
Up Type=0
Dn Type=3
Dn Slope=0.005
Boundary for River Rch & Prof#=UNT 84 in Laguni,Reach-1,2
Up Type=0
Dn Type=3
Dn Slope=0.005
Boundary for River Rch & Prof#=UNT 84 in Laguni,Reach-1,3
Up Type=0
Dn Type=3
Dn Slope=0.005
Boundary for River Rch & Prof#=UNT 84 in Laguni,Reach-1,4
Up Type=0
Dn Type=3
Dn Slope=0.005
Boundary for River Rch & Prof#=UNT 84 in Laguni,Reach-1,5
Up Type=0
Dn Type=3
Dn Slope=0.005
Boundary for River Rch & Prof#=UNT 84 in Laguni,Reach-1,6
Up Type=0
Dn Type=3
Dn Slope=0.005
Boundary for River Rch & Prof#=UNT 84 in Laguni,Reach-1,7
Up Type=0
Dn Type=3
Dn Slope=0.005

--- UNT 84 in Lagunillas Cr Wtrshd.g01 (geometry) ---

Geom Title=Existing Conditions

River Reach=UNT 84 in Laguni,Reach-1
Reach XY= 30
      2074130.80     13435134.54      2074180.80     13435154.54
      2074220.80     13435124.54      2074280.80     13435114.54
      2074340.80     13435144.54      2074390.80     13435204.54
      2074390.80     13435264.54      2074290.80     13435374.54
      2074280.80     13435424.54      2074350.80     13435484.54
      2074360.80     13435554.54      2074420.80     13435614.54
      2074510.80     13435644.54      2074560.80     13435684.54
      2074620.80     13435684.54      2074660.80     13435644.54
      2074700.80     13435634.54      2074780.80     13435634.54
      2074790.80     13435694.54      2074820.80     13435734.54
      2074900.80     13435764.54      2075060.80     13435894.54
      2075060.80     13436004.54      2075010.80     13436084.54
      2075010.80     13436174.54      2075040.80     13436224.54
      2075160.80     13436314.54      2075220.80     13436314.54
      2075240.80     13436294.54      2075320.80     13436314.54

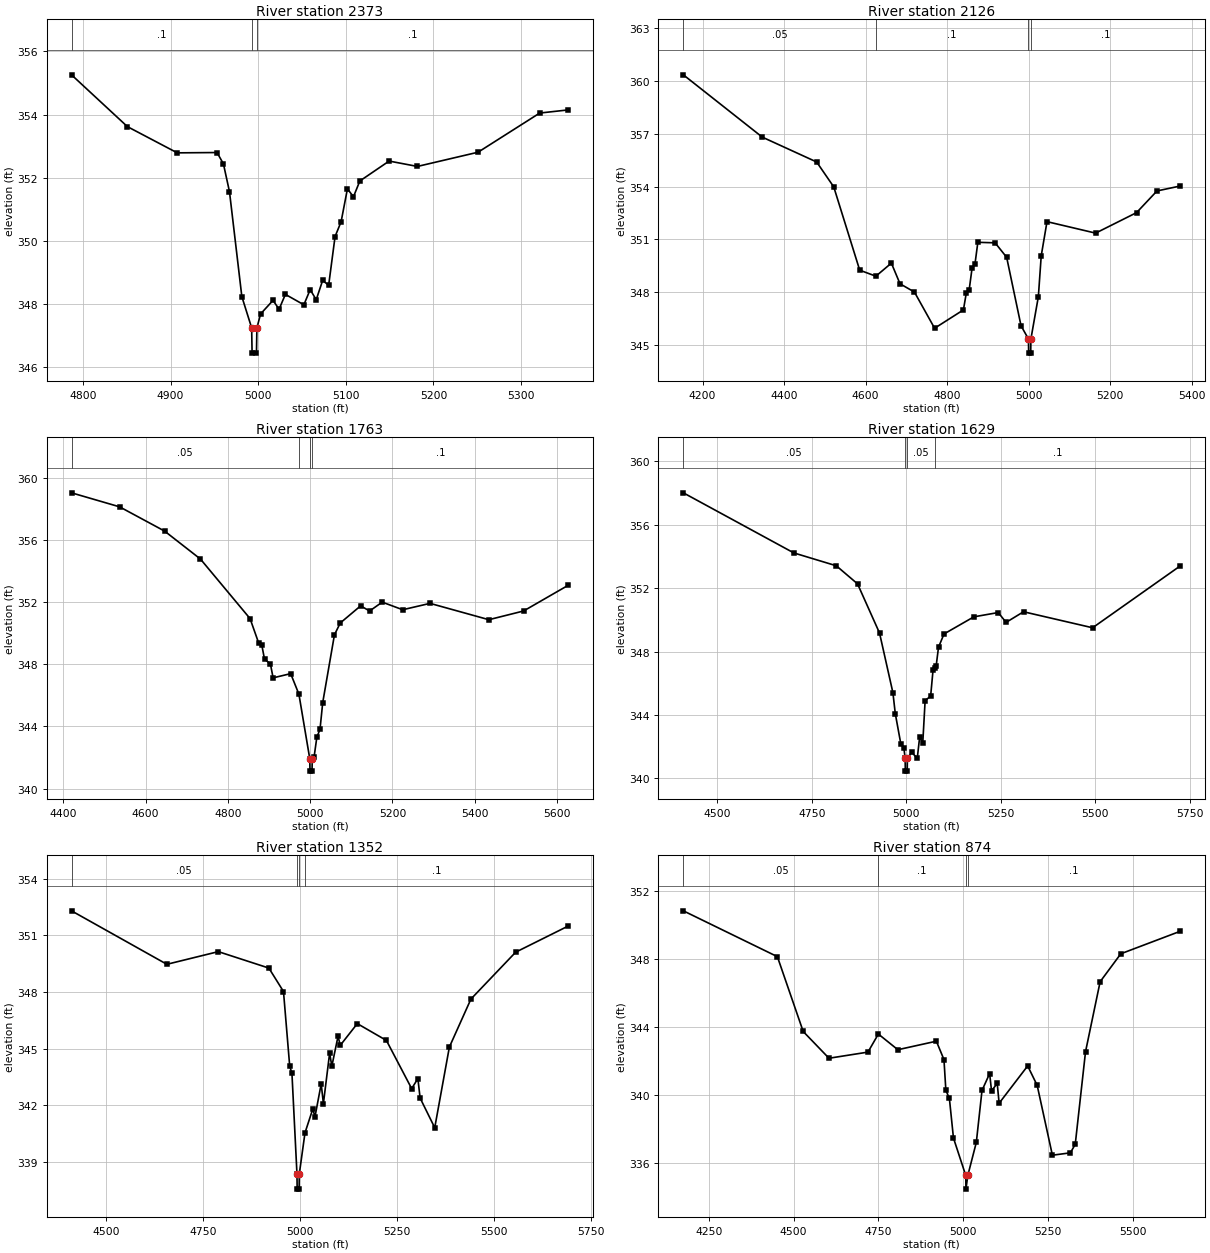
Type RM Length L Ch R = 1,2373,247,247,247
BEGIN DESCRIPTION:
UNT 84 in Lagunillas Cr Wtrshd 2.0
END DESCRIPTION:
XS GIS Cut Line= 4
      2073961.19     13435212.90      2074083.63     13435215.50
      2074232.07     13435059.25      2074265.93     13434832.65
#Sta/Elev= 30
  4786.9  355.26  4850.7  353.62  4907.6  352.79  4953.0  352.80  4960.3  352.44
  4967.2  351.56  4981.3  348.24  4992.5  347.25  4993.0  346.45  4998.0  346.45
  4998.5  347.25  5002.7  347.69  5016.9  348.12  5023.8  347.84  5031.0  348.31
  5052.1  347.98  5059.3  348.46  5066.2  348.14  5073.5  348.75  5080.4  348.60
  5087.7  350.14  5094.6  350.61  5101.8  351.65  5108.7  351.40  5116.0  351.90
  5149.4  352.53  5181.7  352.36  5250.9  352.81  5321.3  354.05  5354.0  354.15
#Mann=3,-1,0
  4786.9     0.1       0  4992.5    0.07       0  4998.5     0.1       0
Bank Sta=4992.5,4998.5
Exp/Cntr=0.3,0.1

Type RM Length L Ch R = 1,2126,363,363,363
BEGIN DESCRIPTION:
Mapping XS fe21fcb3
END DESCRIPTION:
XS GIS Cut Line= 4
      2073665.73     13435593.35      2073995.61     13435519.56
      2074427.46     13435087.70      2074451.18     13434818.21
#Sta/Elev= 30
  4152.7  360.33  4346.4  356.80  4479.9  355.39  4521.8  353.98  4585.5  349.26
  4625.2  348.92  4663.2  349.66  4684.4  348.49  4719.8  348.02  4769.3  345.97
  4840.0  347.01  4847.1  347.97  4854.2  348.16  4861.2  349.37  4868.3  349.60
  4875.4  350.84  4917.8  350.81  4946.1  349.99  4981.4  346.11  4999.6  345.36
  5000.1  344.56  5005.1  344.56  5005.6  345.36  5023.9  347.76  5030.9  350.07
  5045.1  352.01  5164.4  351.36  5264.8  352.52  5315.0  353.75  5372.0  354.03
#Mann=4,-1,0
  4152.7    0.05       0  4625.2     0.1       0  4999.6    0.07       0
  5005.6     0.1       0
Bank Sta=4999.6,5005.6
Exp/Cntr=0.3,0.1

Type RM Length L Ch R = 1,1763,134,134,134
BEGIN DESCRIPTION:
Mapping XS ef809ce1
END DESCRIPTION:
XS GIS Cut Line= 4
      2073800.28     13435693.17      2074082.41     13435638.92
      2074427.46     13435339.44      2074522.95     13434885.87
#Sta/Elev= 30
  4420.1  359.02  4536.9  358.12  4646.3  356.56  4733.5  354.76  4854.1  350.93
  4875.0  349.36  4882.6  349.23  4889.2  348.32  4903.5  348.02  4910.1  347.12
  4952.8  347.39  4972.8  346.07  4999.2  341.92  4999.7  341.12  5004.7  341.12
  5005.2  341.92  5009.8  342.05  5016.4  343.30  5024.1  343.81  5030.7  345.53
  5059.2  349.89  5073.4  350.65  5122.8  351.75  5144.7  351.42  5175.3  351.99
  5225.1  351.50  5291.5  351.91  5434.5  350.86  5518.9  351.42  5627.8  353.08
#Mann=4,-1,0
  4420.1    0.05       0  4972.8     0.1       0  4999.2    0.07       0
  5005.2     0.1       0
Bank Sta=4999.2,5005.2
Exp/Cntr=0.3,0.1

Type RM Length L Ch R = 1,1629,277,277,277
BEGIN DESCRIPTION:
Mapping XS b99596a0
END DESCRIPTION:
XS GIS Cut Line= 4
      2073878.43     13435827.71      2074210.45     13435749.59
      2074522.95     13435337.27      2074592.40     13434885.83
#Sta/Elev= 30
  4410.0  358.01  4702.5  354.22  4814.9  353.41  4871.1  352.27  4929.3  349.17
  4964.7  345.41  4971.0  344.09  4985.6  342.19  4993.8  341.93  4997.1  341.26
  4997.6  340.46  5002.6  340.46  5003.1  341.26  5014.7  341.64  5029.2  341.27
  5035.5  342.60  5043.8  342.26  5050.0  344.91  5064.6  345.19  5070.9  346.82
  5075.6  346.96  5079.1  347.07  5085.4  348.27  5100.0  349.11  5179.0  350.19
  5243.5  350.46  5264.3  349.84  5310.5  350.51  5493.3  349.50  5725.2  353.40
#Mann=4,-1,0
  4410.0    0.05       0  4997.1    0.03       0  5003.1    0.05       0
  5075.6     0.1       0
Bank Sta=4997.1,5003.1
Exp/Cntr=0.3,0.1

Type RM Length L Ch R = 1,1352,478,478,478
BEGIN DESCRIPTION:
Mapping XS 29cb1af6
END DESCRIPTION:
XS GIS Cut Line= 4
      2074175.75     13436046.90      2074416.61     13435981.80
      2074781.20     13435324.25      2074759.49     13435044.25
#Sta/Elev= 30
  4410.6  352.29  4656.7  349.46  4789.4  350.13  4919.9  349.26  4957.6  348.02
  4973.7  344.06  4979.4  343.70  4992.4  338.36  4992.9  337.56  4997.9  337.56
  4998.4  338.36  5013.1  340.54  5033.2  341.80  5038.9  341.39  5054.9  343.13
  5060.6  342.09  5076.7  344.76  5082.4  344.07  5098.4  345.65  5104.1  345.17
  5148.1  346.32  5223.2  345.43  5288.4  342.88  5304.4  343.41  5310.2  342.38
  5347.9  340.81  5385.7  345.08  5441.3  347.62  5556.7  350.10  5692.8  351.49
#Mann=4,-1,0
  4410.6    0.05       0  4992.4    0.03       0  4998.4    0.05       0
  5013.1     0.1       0
Bank Sta=4992.4,4998.4
Exp/Cntr=0.3,0.1

Type RM Length L Ch R = 1,874,274,274,274
BEGIN DESCRIPTION:
Mapping XS 3c842dc1
END DESCRIPTION:
XS GIS Cut Line= 4
      2074227.81     13436118.52      2074857.15     13435955.76
      2075115.40     13435432.75      2075055.04     13435208.57
#Sta/Elev= 30
  4174.6  350.81  4452.0  348.12  4528.1  343.73  4604.2  342.16  4719.1  342.52
  4749.8  343.58  4807.3  342.66  4920.9  343.16  4943.3  342.08  4948.9  340.28
  4959.3  339.80  4971.3  337.48  5007.6  335.28  5008.1  334.48  5013.6  335.28
  5038.7  337.22  5055.5  340.27  5078.0  341.26  5083.6  340.25  5100.4  340.68
  5106.0  339.52  5190.2  341.71  5218.2  340.57  5263.1  336.47  5316.2  336.61
  5330.5  337.11  5360.8  342.54  5403.9  346.65  5464.9  348.29  5640.1  349.61
#Mann=4,-1,0
  4174.6    0.05       0  4749.8     0.1       0  5007.6    0.07       0
  5013.6     0.1       0
Bank Sta=5007.6,5013.6
Exp/Cntr=0.3,0.1

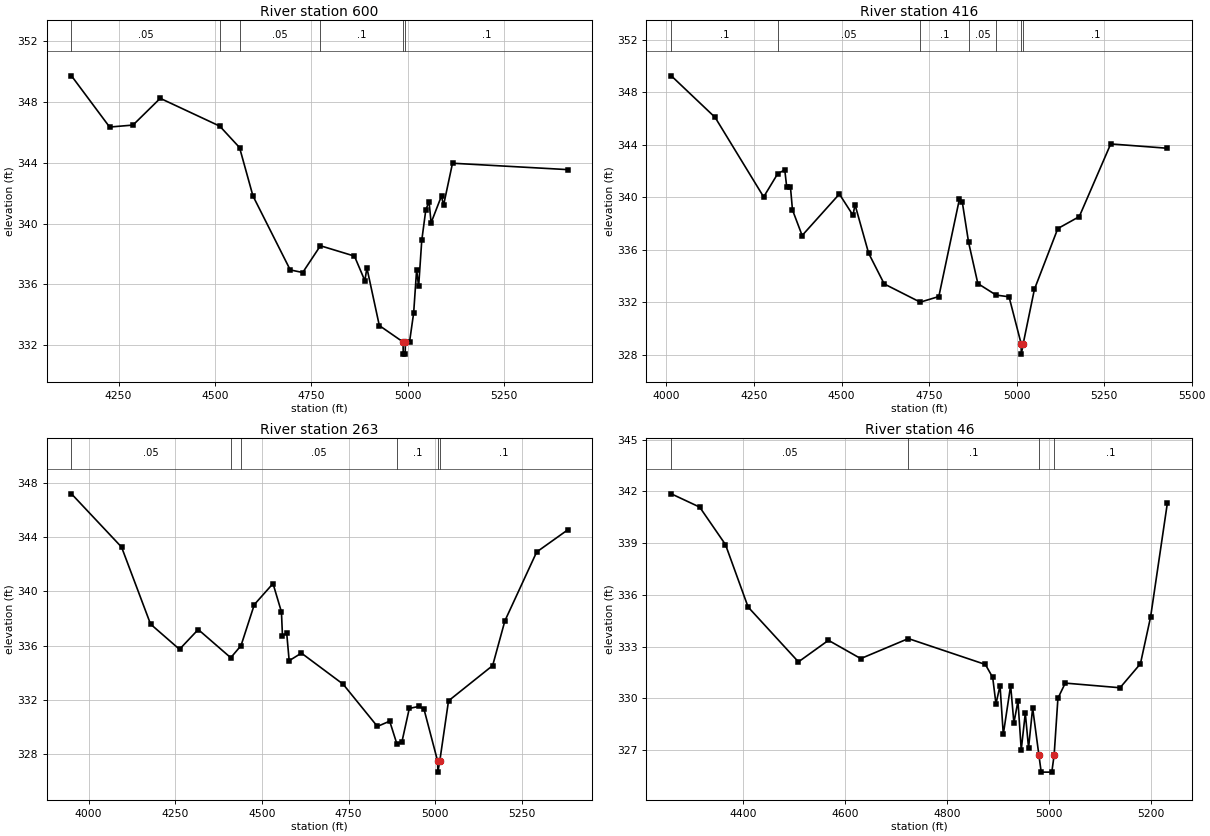
Type RM Length L Ch R = 1,600,184,184,184
BEGIN DESCRIPTION:
Mapping XS 2b1a348e
END DESCRIPTION:
XS GIS Cut Line= 4
      2074216.97     13436205.32      2074551.16     13436159.75
      2075171.82     13435962.27      2075330.11     13435710.74
#Sta/Elev= 30
  4127.9  349.72  4226.8  346.35  4287.4  346.48  4358.0  348.24  4512.3  346.41
  4563.6  345.00  4598.3  341.82  4695.0  336.95  4727.3  336.78  4773.2  338.54
  4861.4  337.86  4888.4  336.24  4893.7  337.08  4925.9  333.29  4987.4  332.21
  4987.9  331.41  4992.9  331.41  4993.4  332.21  5004.4  332.24  5014.9  334.12
  5022.6  336.96  5027.8  335.86  5035.9  338.89  5046.4  340.90  5054.8  341.45
  5060.1  340.05  5087.1  341.82  5092.3  341.19  5115.6  343.97  5413.7  343.55
#Mann=6,-1,0
  4127.9    0.05       0  4512.3     0.1       0  4563.6    0.05       0
  4773.2     0.1       0  4987.4    0.07       0  4993.4     0.1       0
Bank Sta=4987.4,4993.4
Exp/Cntr=0.3,0.1

Type RM Length L Ch R = 1,416,153,153,153
BEGIN DESCRIPTION:
Mapping XS c35dbf9a
END DESCRIPTION:
XS GIS Cut Line= 4
      2074134.48     13436257.40      2074468.70     13436435.36
      2075189.18     13436070.77      2075290.57     13435863.68
#Sta/Elev= 30
  4013.8  349.25  4139.0  346.08  4277.6  340.02  4317.7  341.79  4337.9  342.08
  4343.5  340.76  4354.2  340.75  4359.9  339.03  4387.5  337.08  4493.8  340.24
  4532.8  338.62  4538.4  339.44  4577.4  335.73  4621.9  333.39  4724.8  332.00
  4777.9  332.43  4836.6  339.84  4844.7  339.66  4862.9  336.56  4889.3  333.42
  4941.5  332.54  4978.4  332.41  5012.9  328.84  5013.4  328.04  5018.9  328.84
  5050.9  332.98  5117.7  337.61  5179.0  338.52  5268.8  344.06  5430.5  343.73
#Mann=7,-1,0
  4013.8     0.1       0  4317.7    0.05       0  4724.8     0.1       0
  4862.9    0.05       0  4941.5     0.1       0  5012.9    0.07       0
  5018.9     0.1       0
Bank Sta=5012.9,5018.9
Exp/Cntr=0.3,0.1

Type RM Length L Ch R = 1,263,217,217,217
BEGIN DESCRIPTION:
Mapping XS 004c6ce5
END DESCRIPTION:
XS GIS Cut Line= 4
      2074225.64     13436793.43      2074792.05     13436567.74
      2075249.95     13436112.01      2075312.32     13435948.55
#Sta/Elev= 30
  3950.5  347.19  4095.0  343.26  4178.6  337.58  4262.1  335.72  4316.1  337.18
  4409.9  335.10  4439.5  335.99  4477.9  339.02  4531.8  340.57  4556.1  338.48
  4559.1  336.72  4571.3  336.91  4578.4  334.88  4613.7  335.44  4733.9  333.15
  4832.9  330.03  4868.3  330.42  4889.1  328.74  4903.6  328.89  4924.9  331.36
  4953.1  331.51  4967.3  331.30  5006.7  327.46  5007.2  326.66  5012.7  327.46
  5038.0  331.92  5165.3  334.52  5200.6  337.82  5292.3  342.90  5381.2  344.52
#Mann=6,-1,0
  3950.5    0.05       0  4409.9     0.1       0  4439.5    0.05       0
  4889.1     0.1       0  5006.7    0.07       0  5012.7     0.1       0
Bank Sta=5006.7,5012.7
Exp/Cntr=0.3,0.1

Type RM Length L Ch R = 1,46,0,0,0
BEGIN DESCRIPTION:
UNT 84 in Lagunillas Cr Wtrshd 1.0
END DESCRIPTION:
XS GIS Cut Line= 4
      2074700.87     13436769.58      2075176.16     13436435.36
      2075315.92     13436261.46      2075313.75     13436092.21
#Sta/Elev= 30
  4258.6  341.86  4314.3  341.09  4364.9  338.92  4409.3  335.30  4508.1  332.12
  4567.0  333.37  4630.4  332.31  4723.8  333.47  4874.9  331.97  4889.3  331.22
  4895.7  329.69  4903.7  330.74  4910.1  327.92  4924.5  330.75  4930.9  328.58
  4938.9  329.85  4945.3  327.02  4953.3  329.15  4959.7  327.13  4967.7  329.45
  4979.9  326.73  4984.5  325.73  5005.3  325.73  5009.9  326.73  5017.3  330.01
  5031.7  330.89  5139.2  330.62  5179.2  332.01  5199.2  334.73  5232.0  341.31
#Mann=4,-1,0
  4258.6    0.05       0  4723.8     0.1       0  4979.9    0.07       0
  5009.9     0.1       0
Bank Sta=4979.9,5009.9
Exp/Cntr=0.3,0.1

Chan Stop Cuts=-1