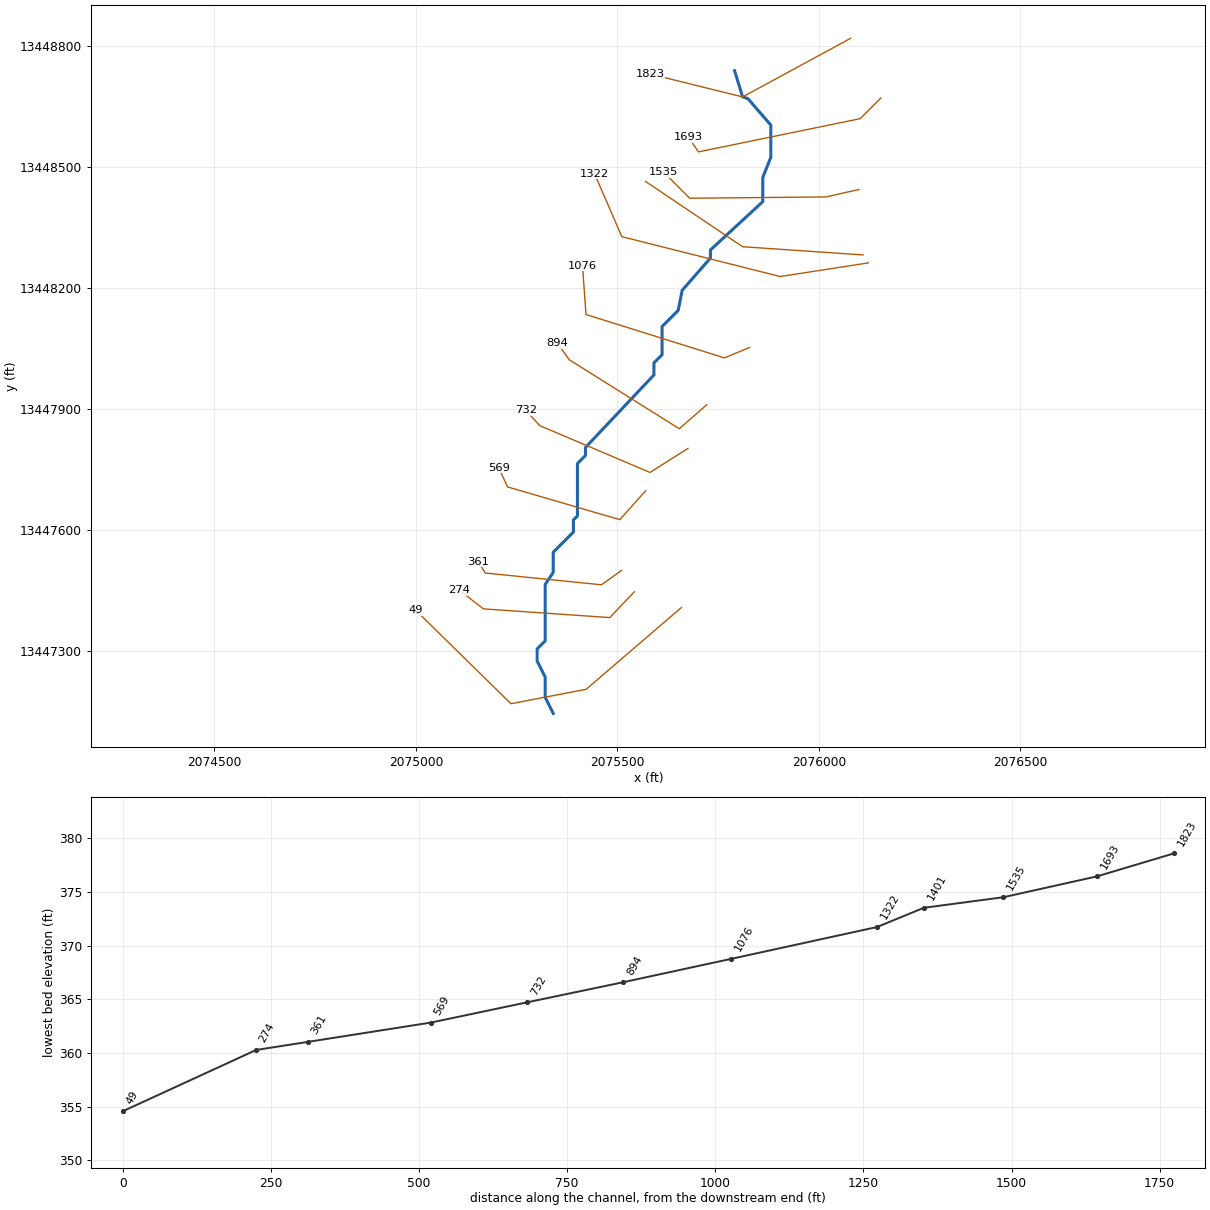
--- UNT 87 in Lagunillas Cr Wtrshd.prj (project) ---

Proj Title=UNT 87 in Lagunillas Cr Wtrshd Base Level Engineering
Current Plan=p01
Default Exp/Contr=0.3,0.1
English Units
Geom File=g01
Flow File=f01
Plan File=p01
BEGIN DESCRIPTION:
UNT 87 in Lagunillas Cr Wtrshd
END DESCRIPTION:

--- UNT 87 in Lagunillas Cr Wtrshd.p01 (plan) ---

Plan Title=Multiple Run
Short Identifier=Multiple
Geom File=g01
Flow File=f01
Subcritical Flow
K Sum by GR= 0
Std Step Tol= 0.01
Critical Tol= 0.01
Num of Std Step Trials= 20
Max Error Tol= 0.3
Flow Tol Ratio= 0.001
Split Flow NTrial= 30
Split Flow Tol= 0.02
Split Flow Ratio= 0.02
Log Output Level= 0
Friction Slope Method= 1
Unsteady Friction Slope Method= 2
Unsteady Bridges Friction Slope Method= 1
Parabolic Critical Depth
Global Vel Dist=  1 , 1 , 1
Global Log Level= 0
CheckData=True
Encroach Param= -1, 0, 0, 0
BEGIN DESCRIPTION:
Multiple Run
END DESCRIPTION:

--- UNT 87 in Lagunillas Cr Wtrshd.f01 (steady flow) ---

Flow Title=Multiple
Number of Profiles=7
Profile Names=10-year,25-year,50-year,1pct_min,100-year,1pct_plu,500-year
River Rch & RM= UNT 87 in Laguni,Reach-1,1823
      51      64      74      43      85     170     116
Boundary for River Rch & Prof#=UNT 87 in Laguni,Reach-1,1
Up Type=0
Dn Type=3
Dn Slope=0.005
Boundary for River Rch & Prof#=UNT 87 in Laguni,Reach-1,2
Up Type=0
Dn Type=3
Dn Slope=0.005
Boundary for River Rch & Prof#=UNT 87 in Laguni,Reach-1,3
Up Type=0
Dn Type=3
Dn Slope=0.005
Boundary for River Rch & Prof#=UNT 87 in Laguni,Reach-1,4
Up Type=0
Dn Type=3
Dn Slope=0.005
Boundary for River Rch & Prof#=UNT 87 in Laguni,Reach-1,5
Up Type=0
Dn Type=3
Dn Slope=0.005
Boundary for River Rch & Prof#=UNT 87 in Laguni,Reach-1,6
Up Type=0
Dn Type=3
Dn Slope=0.005
Boundary for River Rch & Prof#=UNT 87 in Laguni,Reach-1,7
Up Type=0
Dn Type=3
Dn Slope=0.005

--- UNT 87 in Lagunillas Cr Wtrshd.g01 (geometry) ---

Geom Title=Existing Conditions

River Reach=UNT 87 in Laguni,Reach-1
Reach XY= 30
      2075790.80     13448739.54      2075810.80     13448674.54
      2075823.99     13448670.20      2075880.80     13448604.54
      2075880.80     13448524.54      2075860.80     13448474.54
      2075860.80     13448414.54      2075730.80     13448294.54
      2075730.80     13448274.54      2075660.80     13448194.54
      2075650.80     13448144.54      2075610.80     13448104.54
      2075610.80     13448034.54      2075590.80     13448014.54
      2075590.80     13447984.54      2075420.80     13447804.54
      2075420.80     13447784.54      2075400.80     13447764.54
      2075400.80     13447634.54      2075390.80     13447624.54
      2075390.80     13447594.54      2075340.80     13447544.54
      2075340.80     13447494.54      2075320.80     13447464.54
      2075320.80     13447324.54      2075300.80     13447304.54
      2075300.80     13447274.54      2075320.80     13447234.54
      2075320.80     13447184.54      2075340.80     13447144.54

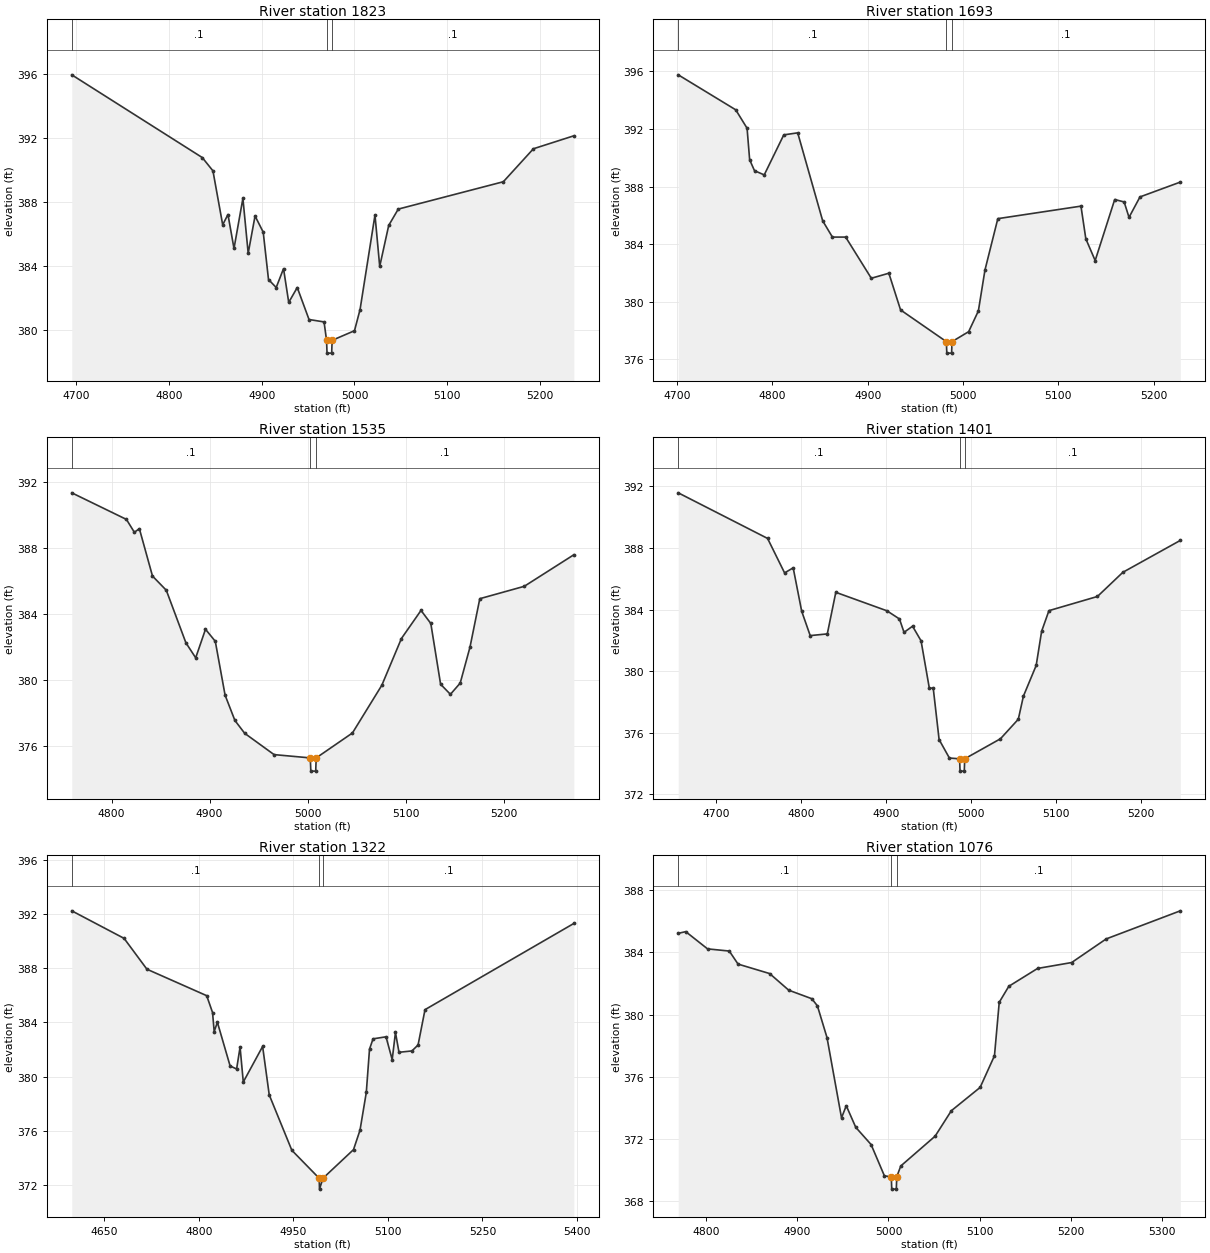
Type RM Length L Ch R = 1,1823,130,130,130
BEGIN DESCRIPTION:
UNT 87 in Lagunillas Cr Wtrshd 4.0
END DESCRIPTION:
XS GIS Cut Line= 3
      2076078.70     13448819.90      2075810.80     13448674.54
      2075581.22     13448731.35
#Sta/Elev= 30
  4695.2  395.96  4835.9  390.79  4847.4  389.96  4857.9  386.59  4863.6  387.23
  4870.1  385.11  4879.7  388.24  4885.4  384.81  4892.8  387.14  4901.6  386.13
  4907.3  383.17  4915.6  382.67  4923.5  383.85  4929.1  381.74  4938.3  382.67
  4951.0  380.67  4967.2  380.52  4969.9  379.37  4970.4  378.57  4975.4  378.57
  4975.9  379.37  5000.0  379.97  5006.0  381.29  5022.1  387.20  5027.2  383.99
  5036.9  386.55  5047.2  387.57  5160.5  389.28  5192.9  391.34  5236.5  392.15
#Mann=3,-1,0
  4695.2     0.1       0  4969.9    0.07       0  4975.9     0.1       0
Bank Sta=4969.9,4975.9
Exp/Cntr=0.3,0.1

Type RM Length L Ch R = 1,1693,158,158,158
BEGIN DESCRIPTION:
Mapping XS 0d6e47bf
END DESCRIPTION:
XS GIS Cut Line= 4
      2076153.73     13448671.58      2076102.70     13448620.55
      2075701.22     13448538.08      2075676.25     13448575.00
#Sta/Elev= 30
  4701.3  395.76  4761.6  393.33  4773.5  392.05  4776.2  389.86  4781.3  389.10
  4791.5  388.81  4812.0  391.59  4826.6  391.73  4852.8  385.62  4863.0  384.49
  4876.9  384.49  4903.8  381.63  4922.2  381.98  4934.5  379.43  4982.5  377.23
  4983.0  376.43  4988.0  376.43  4988.5  377.23  5005.9  377.92  5016.1  379.36
  5023.0  382.20  5036.5  385.77  5123.7  386.64  5128.8  384.37  5138.6  382.86
  5159.1  387.10  5169.0  386.93  5174.1  385.86  5185.6  387.28  5227.9  388.31
#Mann=3,-1,0
  4701.3     0.1       0  4982.5    0.07       0  4988.5     0.1       0
Bank Sta=4982.5,4988.5
Exp/Cntr=0.3,0.1

Type RM Length L Ch R = 1,1535,134,134,134
BEGIN DESCRIPTION:
Mapping XS 5263277d
END DESCRIPTION:
XS GIS Cut Line= 4
      2076099.43     13448444.76      2076018.06     13448426.32
      2075679.52     13448423.06      2075615.52     13448487.07
#Sta/Elev= 30
  4759.3  391.34  4815.1  389.73  4823.2  388.95  4828.3  389.17  4841.7  386.30
  4855.8  385.44  4875.8  382.26  4885.8  381.35  4895.8  383.08  4905.8  382.35
  4915.8  379.09  4925.8  377.56  4935.8  376.78  4965.8  375.49  5002.8  375.29
  5003.3  374.49  5008.3  374.49  5008.8  375.29  5045.8  376.80  5075.8  379.69
  5095.8  382.52  5115.8  384.22  5125.8  383.43  5135.8  379.75  5145.8  379.14
  5155.8  379.82  5165.8  382.00  5175.8  384.93  5221.2  385.68  5271.8  387.59
#Mann=3,-1,0
  4759.3     0.1       0  5002.8    0.07       0  5008.8     0.1       0
Bank Sta=5002.8,5008.8
Exp/Cntr=0.3,0.1

Type RM Length L Ch R = 1,1401,79,79,79
BEGIN DESCRIPTION:
Mapping XS 28f3f4fa
END DESCRIPTION:
XS GIS Cut Line= 3
      2076109.76     13448282.34      2075810.75     13448302.73
      2075569.78     13448464.79
#Sta/Elev= 30
  4655.8  391.58  4760.8  388.62  4780.8  386.38  4790.9  386.71  4800.9  383.89
  4810.9  382.31  4831.0  382.42  4841.0  385.12  4901.1  383.92  4915.8  383.39
  4921.2  382.52  4931.2  382.92  4941.2  381.97  4950.9  378.90  4955.5  378.90
  4962.4  375.56  4974.5  374.36  4986.5  374.31  4987.0  373.51  4992.0  373.51
  4992.5  374.31  5034.5  375.61  5055.5  376.88  5061.5  378.38  5076.5  380.37
  5082.9  382.59  5091.5  383.93  5148.5  384.85  5178.4  386.42  5245.9  388.49
#Mann=3,-1,0
  4655.8     0.1       0  4986.5    0.07       0  4992.5     0.1       0
Bank Sta=4986.5,4992.5
Exp/Cntr=0.3,0.1

Type RM Length L Ch R = 1,1322,246,246,246
BEGIN DESCRIPTION:
Mapping XS a0f58a23
END DESCRIPTION:
XS GIS Cut Line= 4
      2076122.90     13448262.58      2075904.18     13448228.73
      2075510.96     13448327.69      2075443.25     13448483.94
#Sta/Elev= 30
  4598.1  392.22  4681.2  390.19  4717.4  387.92  4812.3  385.97  4821.6  384.73
  4824.2  383.33  4829.3  384.01  4849.5  380.79  4859.8  380.57  4865.3  382.18
  4870.4  379.61  4901.1  382.23  4911.6  378.66  4947.5  374.58  4990.9  372.52
  4991.4  371.72  4996.9  372.52  5045.4  374.63  5055.7  376.06  5065.7  378.84
  5070.8  382.03  5076.4  382.79  5097.0  382.94  5106.8  381.26  5112.0  383.26
  5117.6  381.80  5138.2  381.90  5147.9  382.34  5158.9  384.94  5395.2  391.29
#Mann=3,-1,0
  4598.1     0.1       0  4990.9    0.07       0  4996.9     0.1       0
Bank Sta=4990.9,4996.9
Exp/Cntr=0.3,0.1

Type RM Length L Ch R = 1,1076,182,182,182
BEGIN DESCRIPTION:
Mapping XS 73c95cc9
END DESCRIPTION:
XS GIS Cut Line= 4
      2075828.36     13448052.86      2075765.82     13448026.80
      2075422.07     13448134.43      2075413.39     13448255.96
#Sta/Elev= 30
  4769.8  385.23  4778.0  385.34  4801.9  384.23  4825.7  384.09  4835.3  383.25
  4869.9  382.64  4890.8  381.57  4916.1  381.02  4922.2  380.56  4932.7  378.52
  4948.6  373.35  4953.8  374.13  4964.2  372.74  4981.0  371.63  4995.6  369.61
  5003.1  369.56  5003.6  368.76  5008.6  368.76  5009.1  369.56  5013.5  370.25
  5051.1  372.17  5068.9  373.81  5100.4  375.31  5116.1  377.35  5121.3  380.79
  5131.8  381.82  5163.3  382.97  5200.6  383.35  5238.4  384.87  5319.6  386.68
#Mann=3,-1,0
  4769.8     0.1       0  5003.1    0.07       0  5009.1     0.1       0
Bank Sta=5003.1,5009.1
Exp/Cntr=0.3,0.1

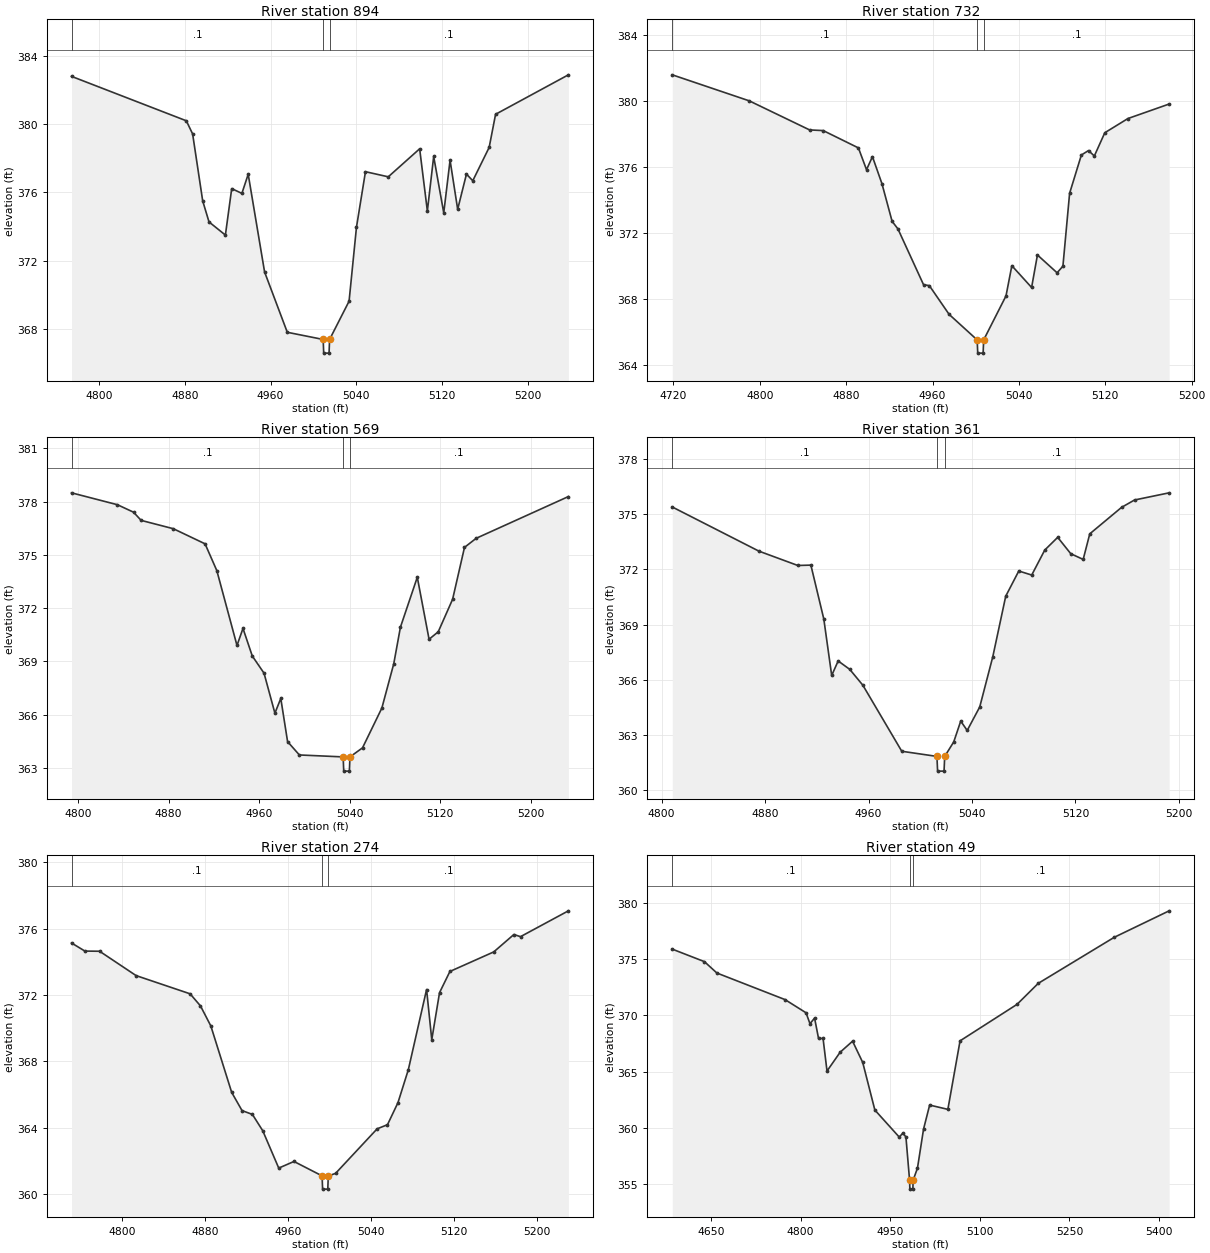
Type RM Length L Ch R = 1,894,162,162,162
BEGIN DESCRIPTION:
Mapping XS 2b8c6ee1
END DESCRIPTION:
XS GIS Cut Line= 4
      2075721.96     13447910.67      2075653.62     13447851.01
      2075380.19     13448022.45      2075350.91     13448063.66
#Sta/Elev= 30
  4774.1  382.79  4881.3  380.19  4887.2  379.42  4896.6  375.50  4902.5  374.27
  4917.8  373.50  4923.7  376.22  4933.2  375.94  4939.1  377.06  4954.4  371.34
  4975.6  367.81  5009.1  367.39  5009.6  366.59  5014.6  366.59  5015.1  367.39
  5033.3  369.63  5040.2  373.96  5048.6  377.21  5069.9  376.91  5099.2  378.55
  5106.4  374.91  5112.3  378.10  5121.7  374.80  5127.6  377.88  5134.7  375.01
  5142.9  377.07  5148.8  376.68  5164.1  378.63  5170.1  380.57  5238.1  382.88
#Mann=3,-1,0
  4774.1     0.1       0  5009.1    0.07       0  5015.1     0.1       0
Bank Sta=5009.1,5015.1
Exp/Cntr=0.3,0.1

Type RM Length L Ch R = 1,732,163,163,163
BEGIN DESCRIPTION:
Mapping XS e84469f8
END DESCRIPTION:
XS GIS Cut Line= 4
      2075675.32     13447802.19      2075580.92     13447742.51
      2075307.49     13447858.61      2075272.77     13447896.58
#Sta/Elev= 30
  4718.9  381.59  4790.3  380.01  4846.1  378.25  4858.7  378.21  4891.3  377.16
  4898.8  375.84  4904.3  376.63  4913.1  374.99  4922.5  372.71  4927.9  372.25
  4951.6  368.87  4957.0  368.81  4975.3  367.07  5001.3  365.52  5001.8  364.72
  5006.8  364.72  5007.3  365.52  5028.0  368.19  5033.4  370.02  5051.7  368.70
  5057.1  370.67  5075.3  369.59  5080.7  369.99  5086.9  374.41  5097.8  376.73
  5104.4  377.00  5109.8  376.67  5119.5  378.08  5140.9  378.94  5179.1  379.82
#Mann=3,-1,0
  4718.9     0.1       0  5001.3    0.07       0  5007.3     0.1       0
Bank Sta=5001.3,5007.3
Exp/Cntr=0.3,0.1

Type RM Length L Ch R = 1,569,208,208,208
BEGIN DESCRIPTION:
Mapping XS 4043f4f1
END DESCRIPTION:
XS GIS Cut Line= 4
      2075570.07     13447696.93      2075506.05     13447625.32
      2075227.19     13447706.70      2075205.49     13447754.45
#Sta/Elev= 30
  4794.3  378.49  4834.9  377.82  4849.1  377.40  4855.8  376.94  4884.3  376.47
  4912.3  375.62  4922.7  374.11  4940.5  369.90  4945.8  370.86  4954.0  369.31
  4964.4  368.34  4974.0  366.09  4979.2  366.92  4985.2  364.49  4995.6  363.74
  5034.3  363.63  5034.8  362.83  5039.8  362.83  5040.3  363.63  5051.4  364.14
  5068.5  366.38  5079.0  368.87  5084.9  370.93  5099.8  373.74  5110.2  370.25
  5118.3  370.67  5131.0  372.50  5141.5  375.42  5151.8  375.93  5233.3  378.28
#Mann=3,-1,0
  4794.3     0.1       0  5034.3    0.07       0  5040.3     0.1       0
Bank Sta=5034.3,5040.3
Exp/Cntr=0.3,0.1

Type RM Length L Ch R = 1,361,87,87,87
BEGIN DESCRIPTION:
Mapping XS db9f46ad
END DESCRIPTION:
XS GIS Cut Line= 4
      2075510.41     13447499.46      2075460.48     13447463.64
      2075171.85     13447492.94      2075155.16     13447521.11
#Sta/Elev= 30
  4808.2  375.39  4875.2  372.99  4905.3  372.21  4915.4  372.23  4925.4  369.30
  4931.5  366.23  4936.5  367.02  4945.5  366.56  4955.6  365.70  4985.7  362.11
  5012.9  361.83  5013.4  361.03  5018.4  361.03  5018.9  361.83  5025.9  362.62
  5031.3  363.75  5036.3  363.24  5046.0  364.52  5056.1  367.25  5066.1  370.54
  5076.2  371.91  5086.2  371.69  5096.3  373.05  5106.3  373.74  5116.4  372.85
  5126.0  372.54  5131.1  373.93  5155.7  375.37  5165.7  375.77  5192.5  376.16
#Mann=3,-1,0
  4808.2     0.1       0  5012.9    0.07       0  5018.9     0.1       0
Bank Sta=5012.9,5018.9
Exp/Cntr=0.3,0.1

Type RM Length L Ch R = 1,274,225,225,225
BEGIN DESCRIPTION:
Mapping XS 45fb535a
END DESCRIPTION:
XS GIS Cut Line= 4
      2075541.83     13447446.25      2075481.10     13447382.26
      2075167.51     13447403.97      2075106.76     13447450.86
#Sta/Elev= 30
  4751.1  375.14  4764.0  374.65  4778.2  374.64  4813.4  373.17  4865.5  372.07
  4875.5  371.34  4885.5  370.13  4905.6  366.12  4915.6  365.02  4925.6  364.79
  4935.6  363.80  4951.0  361.55  4965.7  361.95  4992.8  361.08  4993.3  360.28
  4998.3  360.28  4998.8  361.08  5005.8  361.23  5045.9  363.92  5055.9  364.17
  5066.0  365.50  5076.0  367.49  5093.6  372.33  5098.6  369.30  5106.1  372.14
  5116.1  373.42  5158.4  374.60  5177.8  375.65  5184.2  375.52  5230.4  377.08
#Mann=3,-1,0
  4751.1     0.1       0  4992.8    0.07       0  4998.8     0.1       0
Bank Sta=4992.8,4998.8
Exp/Cntr=0.3,0.1

Type RM Length L Ch R = 1,49,0,0,0
BEGIN DESCRIPTION:
UNT 87 in Lagunillas Cr Wtrshd 1.0
END DESCRIPTION:
XS GIS Cut Line= 4
      2075658.58     13447406.98      2075422.50     13447204.31
      2075235.87     13447168.51      2074999.98     13447400.02
#Sta/Elev= 30
  4585.3  375.88  4639.1  374.77  4660.0  373.76  4774.1  371.40  4809.2  370.23
  4815.8  369.26  4823.5  369.76  4830.1  367.96  4837.7  367.95  4844.3  365.06
  4866.3  366.73  4887.1  367.71  4904.1  365.82  4924.4  361.60  4965.2  359.20
  4971.3  359.55  4976.4  359.21  4982.5  355.38  4983.0  354.58  4988.0  354.58
  4988.5  355.38  4995.7  356.44  5005.9  359.91  5016.1  362.04  5046.6  361.66
  5067.0  367.74  5162.4  370.98  5197.8  372.84  5325.1  376.93  5417.0  379.28
#Mann=3,-1,0
  4585.3     0.1       0  4982.5    0.07       0  4988.5     0.1       0
Bank Sta=4982.5,4988.5
Exp/Cntr=0.3,0.1

Chan Stop Cuts=-1