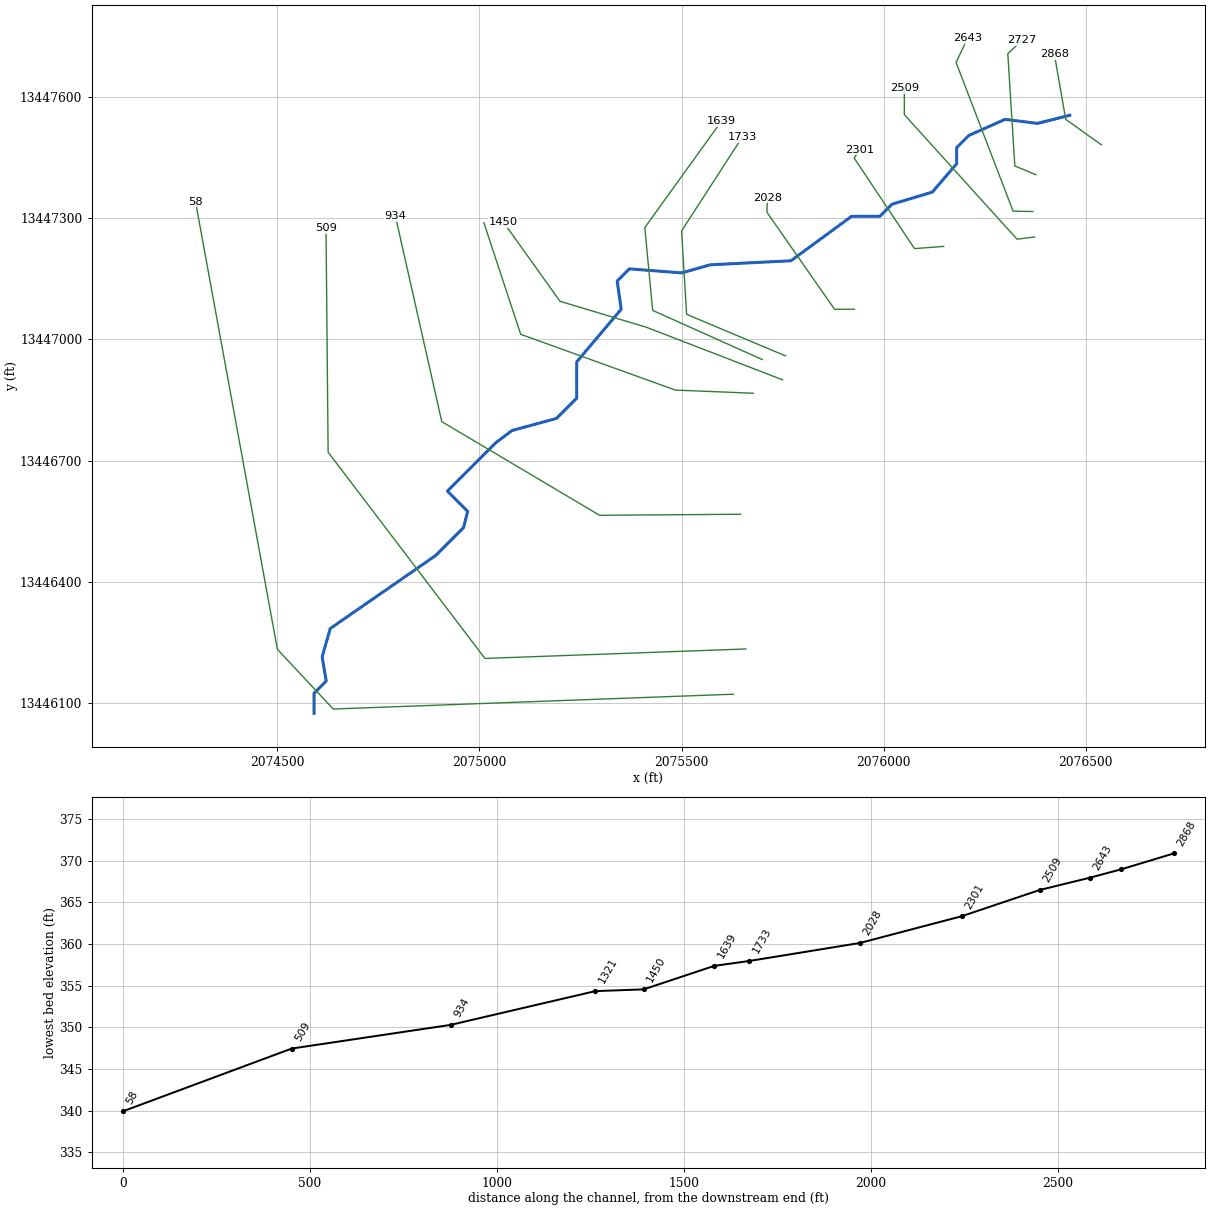
--- UNT 88 in Lagunillas Cr Wtrshd.prj (project) ---

Proj Title=UNT 88 in Lagunillas Cr Wtrshd Base Level Engineering
Current Plan=p01
Default Exp/Contr=0.3,0.1
English Units
Geom File=g01
Flow File=f01
Plan File=p01
BEGIN DESCRIPTION:
UNT 88 in Lagunillas Cr Wtrshd
END DESCRIPTION:

--- UNT 88 in Lagunillas Cr Wtrshd.p01 (plan) ---

Plan Title=Multiple Run
Short Identifier=Multiple
Geom File=g01
Flow File=f01
Subcritical Flow
K Sum by GR= 0
Std Step Tol= 0.01
Critical Tol= 0.01
Num of Std Step Trials= 20
Max Error Tol= 0.3
Flow Tol Ratio= 0.001
Split Flow NTrial= 30
Split Flow Tol= 0.02
Split Flow Ratio= 0.02
Log Output Level= 0
Friction Slope Method= 1
Unsteady Friction Slope Method= 2
Unsteady Bridges Friction Slope Method= 1
Parabolic Critical Depth
Global Vel Dist=  1 , 1 , 1
Global Log Level= 0
CheckData=True
Encroach Param= -1, 0, 0, 0
BEGIN DESCRIPTION:
Multiple Run
END DESCRIPTION:

--- UNT 88 in Lagunillas Cr Wtrshd.f01 (steady flow) ---

Flow Title=Multiple
Number of Profiles=7
Profile Names=10-year,25-year,50-year,1pct_min,100-year,1pct_plu,500-year
River Rch & RM= UNT 88 in Laguni,Reach-1,2868
      71      92     108      63     126     252     176
River Rch & RM= UNT 88 in Laguni,Reach-1,1639
     123     165     198     120     239     476     350
Boundary for River Rch & Prof#=UNT 88 in Laguni,Reach-1,1
Up Type=0
Dn Type=3
Dn Slope=0.005
Boundary for River Rch & Prof#=UNT 88 in Laguni,Reach-1,2
Up Type=0
Dn Type=3
Dn Slope=0.005
Boundary for River Rch & Prof#=UNT 88 in Laguni,Reach-1,3
Up Type=0
Dn Type=3
Dn Slope=0.005
Boundary for River Rch & Prof#=UNT 88 in Laguni,Reach-1,4
Up Type=0
Dn Type=3
Dn Slope=0.005
Boundary for River Rch & Prof#=UNT 88 in Laguni,Reach-1,5
Up Type=0
Dn Type=3
Dn Slope=0.005
Boundary for River Rch & Prof#=UNT 88 in Laguni,Reach-1,6
Up Type=0
Dn Type=3
Dn Slope=0.005
Boundary for River Rch & Prof#=UNT 88 in Laguni,Reach-1,7
Up Type=0
Dn Type=3
Dn Slope=0.005

--- UNT 88 in Lagunillas Cr Wtrshd.g01 (geometry) ---

Geom Title=Existing Conditions

River Reach=UNT 88 in Laguni,Reach-1
Reach XY= 30
      2076460.80     13447554.54      2076380.80     13447534.54
      2076300.80     13447544.54      2076210.80     13447504.54
      2076180.80     13447474.54      2076180.80     13447434.54
      2076120.80     13447364.54      2076020.80     13447334.54
      2075990.80     13447304.54      2075920.80     13447304.54
      2075770.80     13447194.54      2075570.80     13447184.54
      2075500.80     13447164.54      2075370.80     13447174.54
      2075340.80     13447144.54      2075350.80     13447074.54
      2075240.80     13446944.54      2075240.80     13446854.54
      2075190.80     13446804.54      2075080.80     13446774.54
      2075040.80     13446744.54      2074920.80     13446624.54
      2074970.80     13446574.54      2074960.80     13446534.54
      2074890.80     13446464.54      2074630.80     13446284.54
      2074610.80     13446214.54      2074620.80     13446154.54
      2074590.80     13446124.54      2074590.80     13446074.54

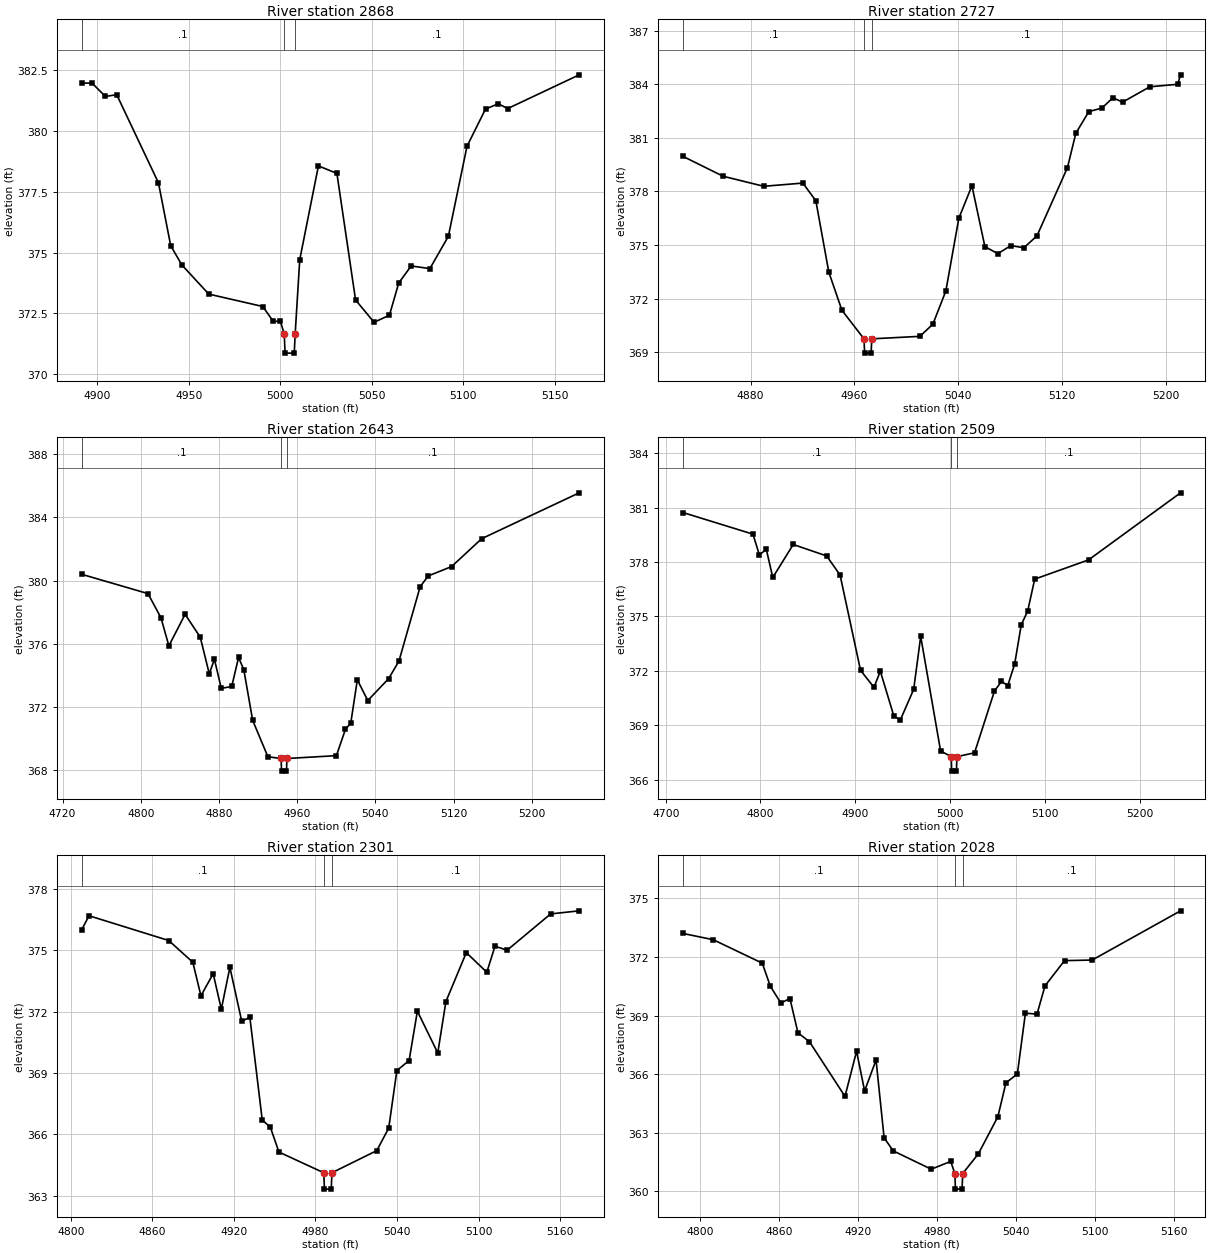
Type RM Length L Ch R = 1,2868,141,141,141
BEGIN DESCRIPTION:
UNT 88 in Lagunillas Cr Wtrshd 8.0
END DESCRIPTION:
XS GIS Cut Line= 3
      2076539.09     13447481.47      2076450.80     13447544.54
      2076422.74     13447705.41
#Sta/Elev= 30
  4891.5  381.98  4897.1  381.98  4904.4  381.43  4910.6  381.50  4933.4  377.87
  4940.1  375.28  4946.2  374.49  4960.9  373.29  4990.4  372.78  4996.1  372.17
  5000.0  372.17  5002.1  371.66  5002.6  370.86  5007.6  370.86  5008.1  371.66
  5010.6  374.71  5020.8  378.57  5030.9  378.26  5041.1  373.05  5051.2  372.13
  5059.6  372.42  5064.7  373.75  5071.5  374.45  5081.7  374.34  5091.8  375.67
  5102.0  379.38  5112.1  380.91  5119.1  381.13  5124.2  380.93  5163.3  382.32
#Mann=3,-1,0
  4891.5     0.1       0  5002.1    0.07       0  5008.1     0.1       0
Bank Sta=5002.1,5008.1
Exp/Cntr=0.3,0.1

Type RM Length L Ch R = 1,2727,84,84,84
BEGIN DESCRIPTION:
Mapping XS 1f39d74a
END DESCRIPTION:
XS GIS Cut Line= 4
      2076376.96     13447407.49      2076324.86     13447429.20
      2076307.50     13447706.98      2076342.96     13447740.28
#Sta/Elev= 30
  4828.0  379.96  4858.9  378.85  4890.2  378.29  4920.3  378.47  4930.3  377.48
  4940.3  373.48  4950.4  371.35  4967.4  369.75  4967.9  368.95  4972.9  368.95
  4973.4  369.75  5010.5  369.89  5020.5  370.57  5030.5  372.43  5040.5  376.50
  5050.6  378.32  5060.6  374.91  5070.6  374.52  5080.6  374.97  5090.6  374.85
  5100.7  375.51  5124.2  379.33  5130.7  381.26  5140.7  382.47  5150.8  382.67
  5159.3  383.25  5166.7  383.00  5187.7  383.86  5209.2  384.00  5211.4  384.53
#Mann=3,-1,0
  4828.0     0.1       0  4967.4    0.07       0  4973.4     0.1       0
Bank Sta=4967.4,4973.4
Exp/Cntr=0.3,0.1

Type RM Length L Ch R = 1,2643,134,134,134
BEGIN DESCRIPTION:
Mapping XS 70396c57
END DESCRIPTION:
XS GIS Cut Line= 4
      2076369.40     13447316.35      2076320.52     13447317.44
      2076179.46     13447685.27      2076207.69     13447744.99
#Sta/Elev= 30
  4739.7  380.40  4807.4  379.18  4820.7  377.65  4828.8  375.87  4845.4  377.87
  4860.9  376.42  4870.1  374.11  4875.4  375.02  4882.4  373.18  4893.1  373.30
  4900.1  375.14  4905.5  374.35  4914.5  371.16  4930.1  368.85  4943.6  368.74
  4944.1  367.94  4949.1  367.94  4949.6  368.74  5000.2  368.92  5009.5  370.60
  5014.9  370.98  5021.6  373.72  5032.3  372.41  5053.7  373.80  5064.2  374.91
  5085.9  379.62  5094.2  380.30  5118.0  380.89  5148.9  382.66  5248.6  385.56
#Mann=3,-1,0
  4739.7     0.1       0  4943.6    0.07       0  4949.6     0.1       0
Bank Sta=4943.6,4949.6
Exp/Cntr=0.3,0.1

Type RM Length L Ch R = 1,2509,208,208,208
BEGIN DESCRIPTION:
Mapping XS b8393e20
END DESCRIPTION:
XS GIS Cut Line= 4
      2076373.64     13447253.41      2076330.29     13447247.99
      2076051.42     13447556.15      2076051.42     13447621.76
#Sta/Elev= 30
  4718.4  380.73  4792.1  379.54  4798.8  378.40  4806.2  378.70  4813.0  377.15
  4834.6  378.97  4869.8  378.34  4884.0  377.29  4905.6  372.03  4919.8  371.09
  4926.5  371.98  4940.7  369.52  4947.5  369.28  4961.7  370.98  4969.1  373.90
  4990.1  367.58  5001.3  367.27  5001.8  366.47  5006.8  366.47  5007.3  367.27
  5025.9  367.48  5046.9  370.88  5054.3  371.42  5061.0  371.19  5068.3  372.39
  5075.2  374.54  5082.0  375.30  5089.4  377.06  5146.2  378.12  5243.3  381.82
#Mann=3,-1,0
  4718.4     0.1       0  5001.3    0.07       0  5007.3     0.1       0
Bank Sta=5001.3,5007.3
Exp/Cntr=0.3,0.1

Type RM Length L Ch R = 1,2301,273,273,273
BEGIN DESCRIPTION:
Mapping XS ba95c9e4
END DESCRIPTION:
XS GIS Cut Line= 4
      2076148.82     13447230.14      2076076.55     13447224.58
      2075927.25     13447448.88      2075940.80     13447468.89
#Sta/Elev= 30
  4808.0  376.00  4813.3  376.68  4872.0  375.47  4889.7  374.41  4895.7  372.77
  4904.7  373.85  4910.7  372.12  4917.0  374.16  4925.7  371.53  4931.7  371.72
  4940.8  366.71  4946.8  366.35  4953.1  365.14  4986.1  364.13  4986.6  363.33
  4991.6  363.33  4992.1  364.13  5025.1  365.21  5033.9  366.31  5039.9  369.12
  5048.9  369.61  5055.0  372.02  5070.0  369.98  5076.0  372.49  5091.0  374.88
  5106.1  373.92  5112.1  375.19  5121.1  375.00  5153.1  376.77  5174.1  376.92
#Mann=3,-1,0
  4808.0     0.1       0  4986.1    0.07       0  4992.1     0.1       0
Bank Sta=4986.1,4992.1
Exp/Cntr=0.3,0.1

Type RM Length L Ch R = 1,2028,295,295,295
BEGIN DESCRIPTION:
Mapping XS 9d8205ab
END DESCRIPTION:
XS GIS Cut Line= 4
      2075927.90     13447074.58      2075878.64     13447074.58
      2075711.28     13447314.85      2075712.65     13447350.45
#Sta/Elev= 30
  4787.1  373.20  4810.0  372.88  4847.2  371.68  4853.3  370.50  4861.3  369.64
  4868.2  369.87  4874.3  368.11  4883.0  367.66  4910.0  364.86  4918.8  367.17
  4924.9  365.14  4933.6  366.72  4939.7  362.74  4946.6  362.07  4975.5  361.13
  4990.3  361.53  4993.4  360.91  4993.9  360.11  4998.9  360.11  4999.4  360.91
  5011.3  361.92  5026.1  363.82  5032.2  365.55  5040.9  366.01  5047.0  369.12
  5055.8  369.07  5061.9  370.52  5076.7  371.81  5097.7  371.84  5164.8  374.36
#Mann=3,-1,0
  4787.1     0.1       0  4993.4    0.07       0  4999.4     0.1       0
Bank Sta=4993.4,4999.4
Exp/Cntr=0.3,0.1

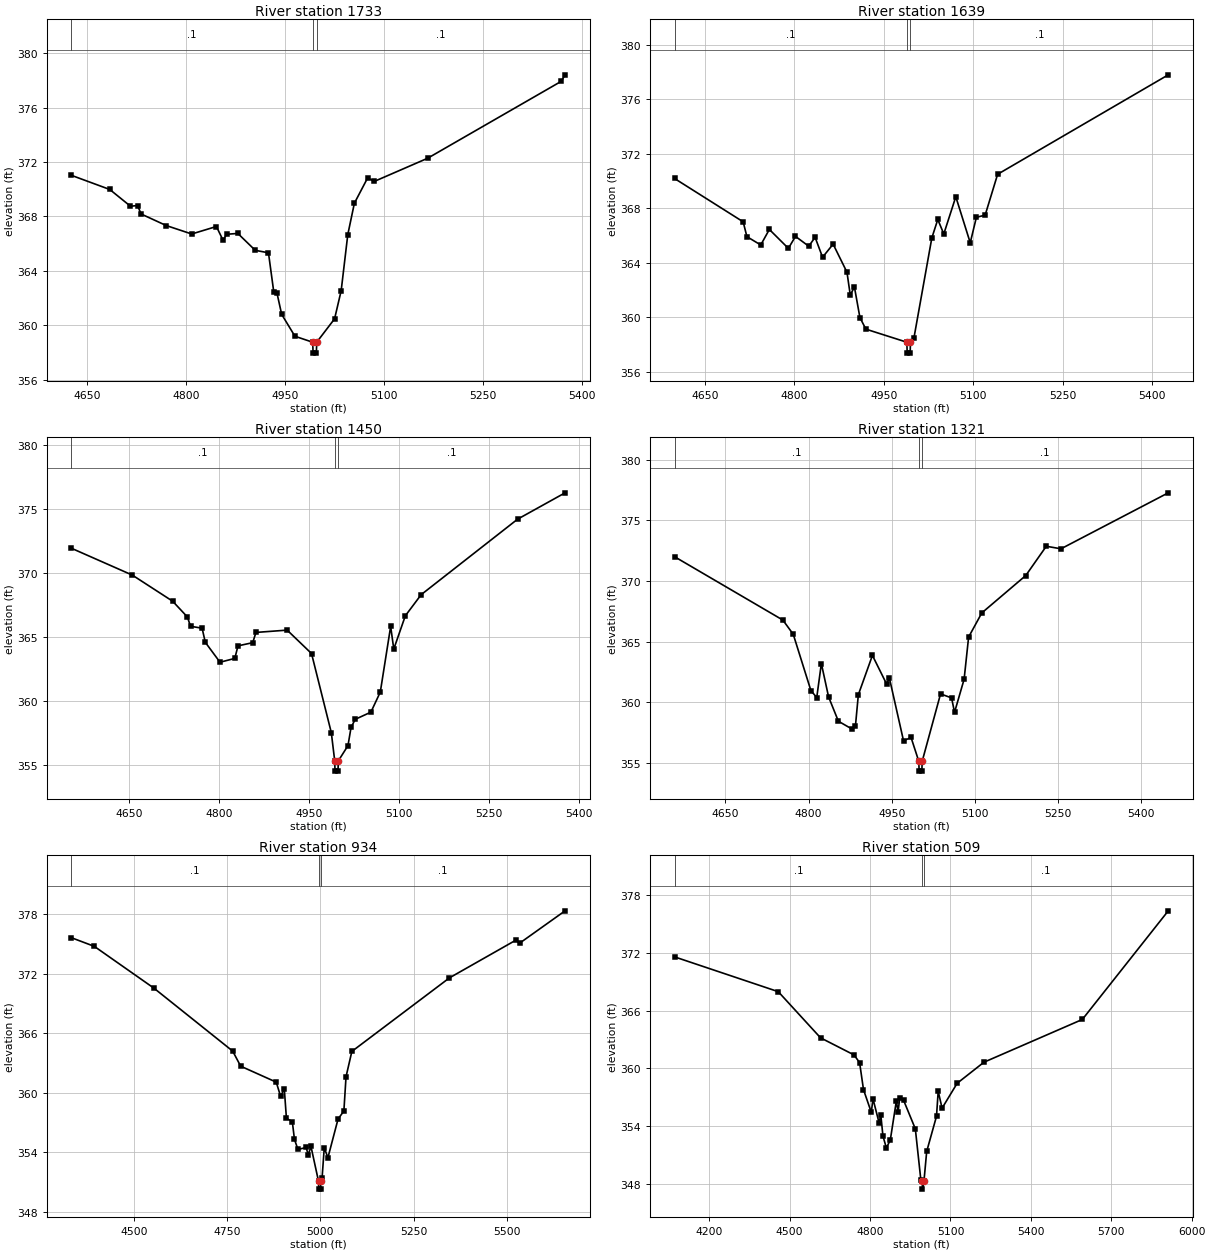
Type RM Length L Ch R = 1,1733,94,94,94
BEGIN DESCRIPTION:
Mapping XS 3f1644ff
END DESCRIPTION:
XS GIS Cut Line= 4
      2075757.59     13446959.06      2075512.67     13447062.08
      2075500.17     13447268.33      2075649.98     13447499.97
#Sta/Elev= 30
  4626.3  371.02  4684.5  369.98  4715.9  368.75  4726.6  368.80  4732.0  368.18
  4770.1  367.33  4808.7  366.71  4846.1  367.26  4856.2  366.25  4861.6  366.69
  4878.6  366.75  4905.0  365.51  4925.0  365.33  4933.0  362.47  4938.0  362.35
  4945.0  360.81  4965.1  359.20  4992.1  358.76  4992.6  357.96  4997.6  357.96
  4998.1  358.76  5025.2  360.48  5035.2  362.55  5045.2  366.66  5055.2  368.97
  5075.3  370.83  5085.3  370.57  5166.1  372.27  5368.6  377.92  5374.5  378.40
#Mann=3,-1,0
  4626.3     0.1       0  4992.1    0.07       0  4998.1     0.1       0
Bank Sta=4992.1,4998.1
Exp/Cntr=0.3,0.1

Type RM Length L Ch R = 1,1639,189,189,189
BEGIN DESCRIPTION:
Mapping XS c6ef8b4a
END DESCRIPTION:
XS GIS Cut Line= 4
      2075699.96     13446950.02      2075428.64     13447071.80
      2075409.19     13447276.66      2075598.72     13447539.84
#Sta/Elev= 30
  4599.4  370.19  4714.4  367.01  4720.7  365.92  4743.9  365.31  4758.3  366.45
  4790.2  365.06  4802.1  365.94  4824.3  365.22  4835.0  365.87  4847.5  364.41
  4865.2  365.37  4888.4  363.31  4893.9  361.64  4900.9  362.22  4910.1  359.98
  4920.1  359.13  4988.8  358.17  4989.3  357.37  4994.3  357.37  4994.8  358.17
  5000.5  358.45  5030.6  365.82  5040.6  367.18  5050.7  366.12  5070.8  368.85
  5095.0  365.47  5105.3  367.34  5120.0  367.50  5140.9  370.50  5426.9  377.80
#Mann=3,-1,0
  4599.4     0.1       0  4988.8    0.07       0  4994.8     0.1       0
Bank Sta=4988.8,4994.8
Exp/Cntr=0.3,0.1

Type RM Length L Ch R = 1,1450,129,129,129
BEGIN DESCRIPTION:
Mapping XS 6c8a7f29
END DESCRIPTION:
XS GIS Cut Line= 4
      2075750.01     13446899.99      2075413.88     13447029.74
      2075199.30     13447094.33      2075059.83     13447289.53
#Sta/Elev= 30
  4553.1  371.97  4654.9  369.87  4722.2  367.83  4746.8  366.60  4752.1  365.87
  4771.4  365.72  4776.7  364.62  4801.3  363.06  4826.0  363.36  4831.3  364.34
  4855.9  364.59  4861.3  365.39  4913.4  365.57  4954.1  363.74  4987.1  357.56
  4992.8  355.35  4993.3  354.55  4998.3  354.55  4998.8  355.35  5014.9  356.54
  5020.1  357.97  5027.1  358.60  5053.2  359.16  5068.9  360.73  5086.2  365.86
  5091.4  364.09  5110.7  366.69  5137.1  368.34  5298.1  374.24  5377.4  376.30
#Mann=3,-1,0
  4553.1     0.1       0  4992.8    0.07       0  4998.8     0.1       0
Bank Sta=4992.8,4998.8
Exp/Cntr=0.3,0.1

Type RM Length L Ch R = 1,1321,387,387,387
BEGIN DESCRIPTION:
Mapping XS 7128a7e2
END DESCRIPTION:
XS GIS Cut Line= 4
      2075677.59     13446866.75      2075484.91     13446874.56
      2075102.10     13447012.58      2075010.94     13447288.66
#Sta/Elev= 30
  4558.3  372.00  4753.7  366.78  4772.4  365.61  4804.2  360.98  4814.8  360.40
  4823.1  363.20  4836.1  360.46  4853.8  358.45  4878.6  357.80  4884.5  358.02
  4889.8  360.63  4915.2  363.87  4940.6  361.53  4945.9  361.99  4971.3  356.84
  4984.9  357.11  4998.9  355.14  4999.4  354.34  5004.4  354.34  5004.9  355.14
  5038.1  360.70  5058.0  360.37  5063.3  359.18  5080.6  361.91  5088.7  365.38
  5112.5  367.37  5191.8  370.45  5228.8  372.86  5255.3  372.65  5448.8  377.26
#Mann=3,-1,0
  4558.3     0.1       0  4998.9    0.07       0  5004.9     0.1       0
Bank Sta=4998.9,5004.9
Exp/Cntr=0.3,0.1

Type RM Length L Ch R = 1,934,425,425,425
BEGIN DESCRIPTION:
Mapping XS c2b819f2
END DESCRIPTION:
XS GIS Cut Line= 4
      2075646.37     13446567.27      2075297.41     13446564.67
      2074906.79     13446796.44      2074792.19     13447304.30
#Sta/Elev= 30
  4332.5  375.65  4393.9  374.78  4553.9  370.56  4765.1  364.21  4786.5  362.69
  4881.9  361.08  4893.6  359.64  4903.4  360.42  4909.2  357.42  4924.9  357.11
  4930.7  355.31  4940.1  354.29  4961.9  354.49  4967.7  353.76  4975.0  354.59
  4995.2  351.09  4995.7  350.29  5000.7  350.29  5001.2  351.09  5004.8  351.44
  5010.6  354.46  5020.4  353.46  5047.6  357.36  5063.2  358.17  5069.0  361.63
  5084.6  364.18  5346.3  371.60  5523.8  375.39  5534.6  375.10  5656.3  378.36
#Mann=3,-1,0
  4332.5     0.1       0  4995.2    0.07       0  5001.2     0.1       0
Bank Sta=4995.2,5001.2
Exp/Cntr=0.3,0.1

Type RM Length L Ch R = 1,509,451,451,451
BEGIN DESCRIPTION:
Mapping XS d5fc1fa0
END DESCRIPTION:
XS GIS Cut Line= 4
      2075659.36     13446233.94      2075013.56     13446210.50
      2074625.54     13446720.92      2074620.33     13447275.60
#Sta/Elev= 30
  4070.6  371.61  4457.6  367.99  4615.3  363.19  4740.3  361.41  4761.1  360.61
  4775.6  357.80  4804.7  355.44  4811.0  356.85  4833.8  354.34  4840.1  355.21
  4848.1  352.98  4860.9  351.74  4875.5  352.54  4898.3  356.64  4904.5  355.47
  4910.9  356.95  4925.4  356.68  4969.0  353.72  4989.8  348.35  4995.1  348.25
  4995.6  347.45  5001.1  348.25  5011.4  351.37  5048.0  355.03  5054.3  357.63
  5068.8  355.87  5125.0  358.46  5224.9  360.65  5592.1  365.10  5912.7  376.40
#Mann=3,-1,0
  4070.6     0.1       0  4995.1    0.07       0  5001.1     0.1       0
Bank Sta=4995.1,5001.1
Exp/Cntr=0.3,0.1

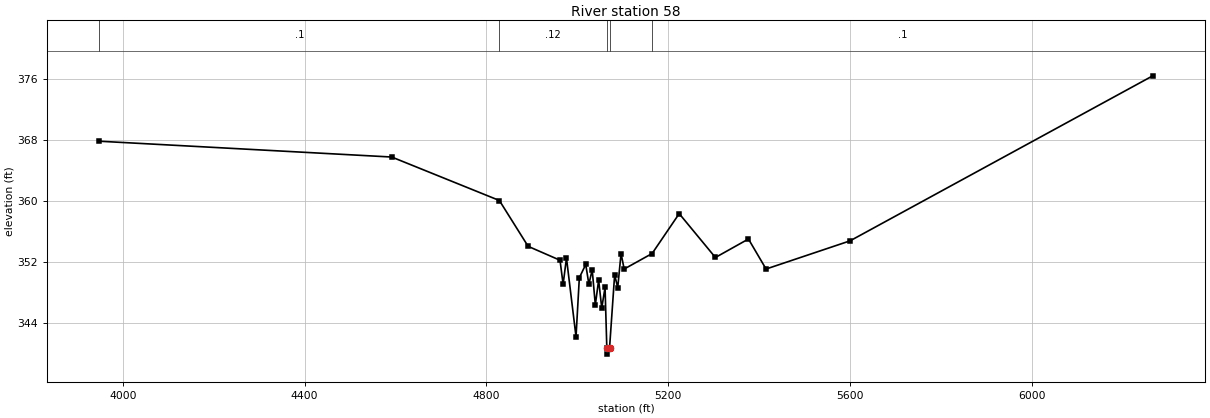
Type RM Length L Ch R = 1,58,0,0,0
BEGIN DESCRIPTION:
UNT 88 in Lagunillas Cr Wtrshd 1.0
END DESCRIPTION:
XS GIS Cut Line= 4
      2075628.12     13446121.96      2074638.19     13446085.30
      2074499.98     13446232.97      2074297.48     13447340.34
#Sta/Elev= 30
  3948.1  367.80  4591.7  365.73  4828.6  360.04  4891.9  354.04  4962.1  352.22
  4968.9  349.07  4976.3  352.51  4997.3  342.20  5004.6  349.93  5018.7  351.67
  5025.6  349.08  5032.9  350.97  5039.8  346.37  5047.1  349.62  5053.9  345.96
  5061.2  348.66  5065.1  340.73  5065.6  339.93  5071.1  340.73  5082.3  350.31
  5089.1  348.63  5096.4  353.09  5103.3  351.07  5164.8  353.10  5224.4  358.32
  5304.1  352.58  5376.8  355.00  5415.6  351.07  5600.5  354.76  6266.7  376.36
#Mann=5,-1,0
  3948.1     0.1       0  4828.6    0.12       0  5065.1    0.07       0
  5071.1    0.12       0  5164.8     0.1       0
Bank Sta=5065.1,5071.1
Exp/Cntr=0.3,0.1

Chan Stop Cuts=-1