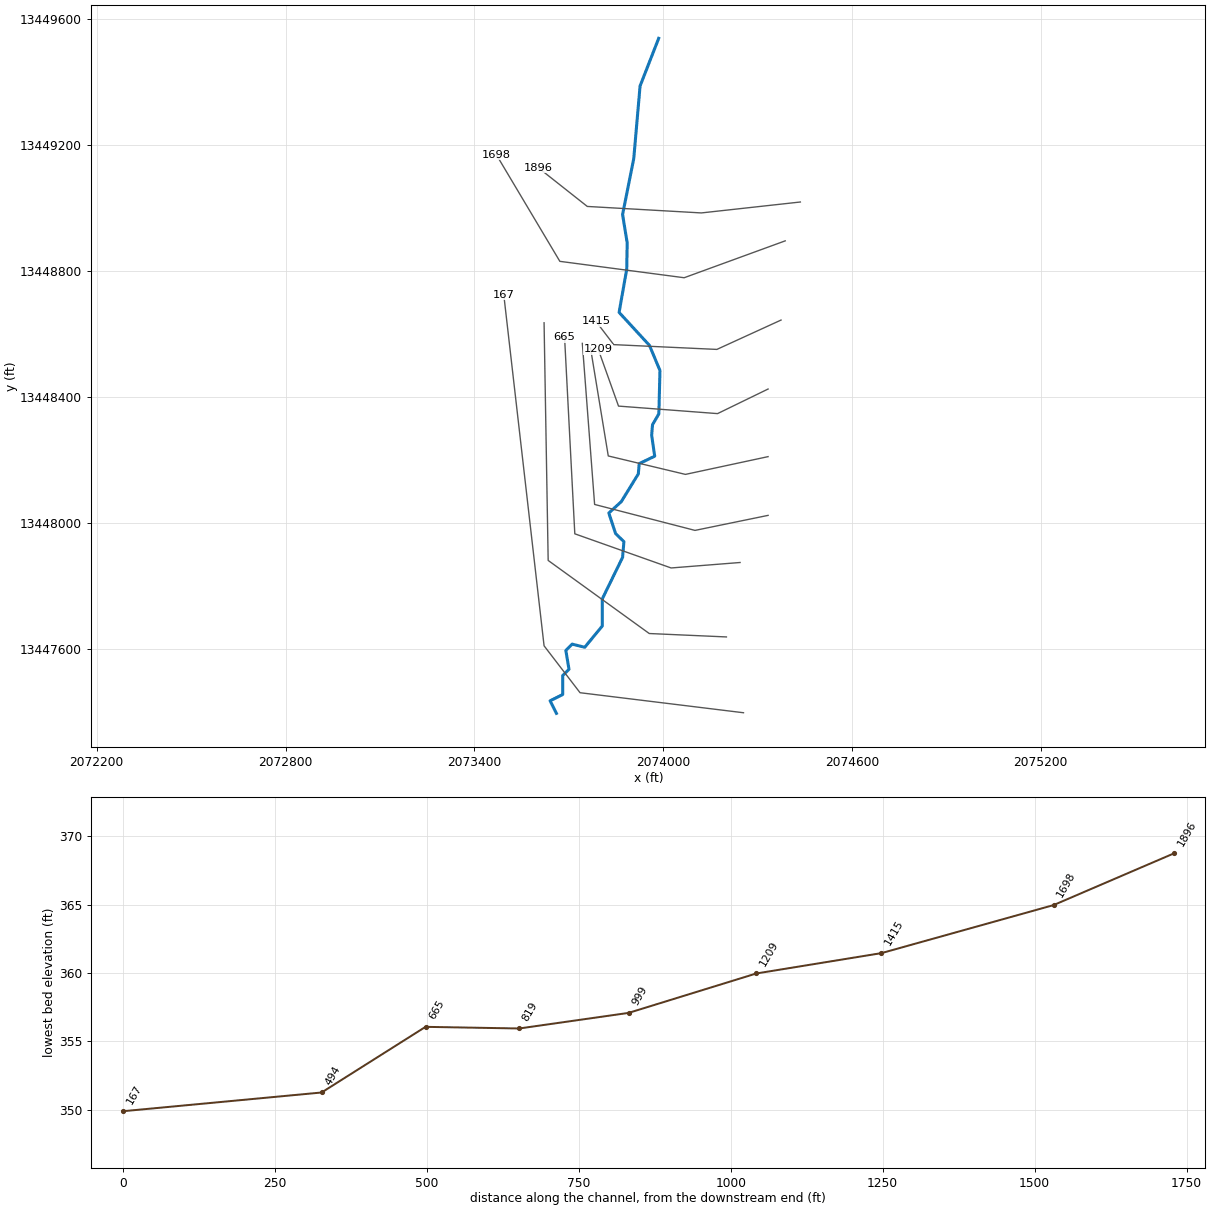
--- UNT 89 in Lagunillas Cr Wtrshd.prj (project) ---

Proj Title=UNT 89 in Lagunillas Cr Wtrshd Base Level Engineering
Current Plan=p01
Default Exp/Contr=0.3,0.1
English Units
Geom File=g01
Flow File=f01
Plan File=p01
BEGIN DESCRIPTION:
UNT 89 in Lagunillas Cr Wtrshd
END DESCRIPTION:

--- UNT 89 in Lagunillas Cr Wtrshd.p01 (plan) ---

Plan Title=Multiple Run
Short Identifier=Multiple
Geom File=g01
Flow File=f01
Subcritical Flow
K Sum by GR= 0
Std Step Tol= 0.01
Critical Tol= 0.01
Num of Std Step Trials= 20
Max Error Tol= 0.3
Flow Tol Ratio= 0.001
Split Flow NTrial= 30
Split Flow Tol= 0.02
Split Flow Ratio= 0.02
Log Output Level= 0
Friction Slope Method= 1
Unsteady Friction Slope Method= 2
Unsteady Bridges Friction Slope Method= 1
Parabolic Critical Depth
Global Vel Dist=  1 , 1 , 1
Global Log Level= 0
CheckData=True
Encroach Param= -1, 0, 0, 0
BEGIN DESCRIPTION:
Multiple Run
END DESCRIPTION:

--- UNT 89 in Lagunillas Cr Wtrshd.f01 (steady flow) ---

Flow Title=Multiple
Number of Profiles=7
Profile Names=10-year,25-year,50-year,1pct_min,100-year,1pct_plu,500-year
River Rch & RM= UNT 89 in Laguni,Reach-1,1896
      72      93     109      64     128     255     179
Boundary for River Rch & Prof#=UNT 89 in Laguni,Reach-1,1
Up Type=0
Dn Type=3
Dn Slope=0.005
Boundary for River Rch & Prof#=UNT 89 in Laguni,Reach-1,2
Up Type=0
Dn Type=3
Dn Slope=0.005
Boundary for River Rch & Prof#=UNT 89 in Laguni,Reach-1,3
Up Type=0
Dn Type=3
Dn Slope=0.005
Boundary for River Rch & Prof#=UNT 89 in Laguni,Reach-1,4
Up Type=0
Dn Type=3
Dn Slope=0.005
Boundary for River Rch & Prof#=UNT 89 in Laguni,Reach-1,5
Up Type=0
Dn Type=3
Dn Slope=0.005
Boundary for River Rch & Prof#=UNT 89 in Laguni,Reach-1,6
Up Type=0
Dn Type=3
Dn Slope=0.005
Boundary for River Rch & Prof#=UNT 89 in Laguni,Reach-1,7
Up Type=0
Dn Type=3
Dn Slope=0.005

--- UNT 89 in Lagunillas Cr Wtrshd.g01 (geometry) ---

Geom Title=Existing Conditions

River Reach=UNT 89 in Laguni,Reach-1
Reach XY= 30
      2073985.80     13449539.54      2073926.64     13449388.13
      2073906.50     13449156.88      2073871.08     13448979.80
      2073885.66     13448889.52      2073884.28     13448806.19
      2073859.97     13448668.69      2073956.50     13448563.83
      2073989.83     13448483.97      2073986.36     13448346.47
      2073966.22     13448311.75      2073963.44     13448277.72
      2073973.16     13448211.75      2073923.86     13448188.13
      2073921.08     13448155.50      2073866.91     13448067.30
      2073827.33     13448031.19      2073848.86     13447965.91
      2073875.25     13447940.22      2073871.08     13447890.22
      2073806.50     13447758.27      2073806.50     13447672.16
      2073750.80     13447604.54      2073710.80     13447614.54
      2073690.80     13447594.54      2073700.80     13447534.54
      2073680.80     13447514.54      2073680.80     13447454.54
      2073640.80     13447434.54      2073660.80     13447394.54

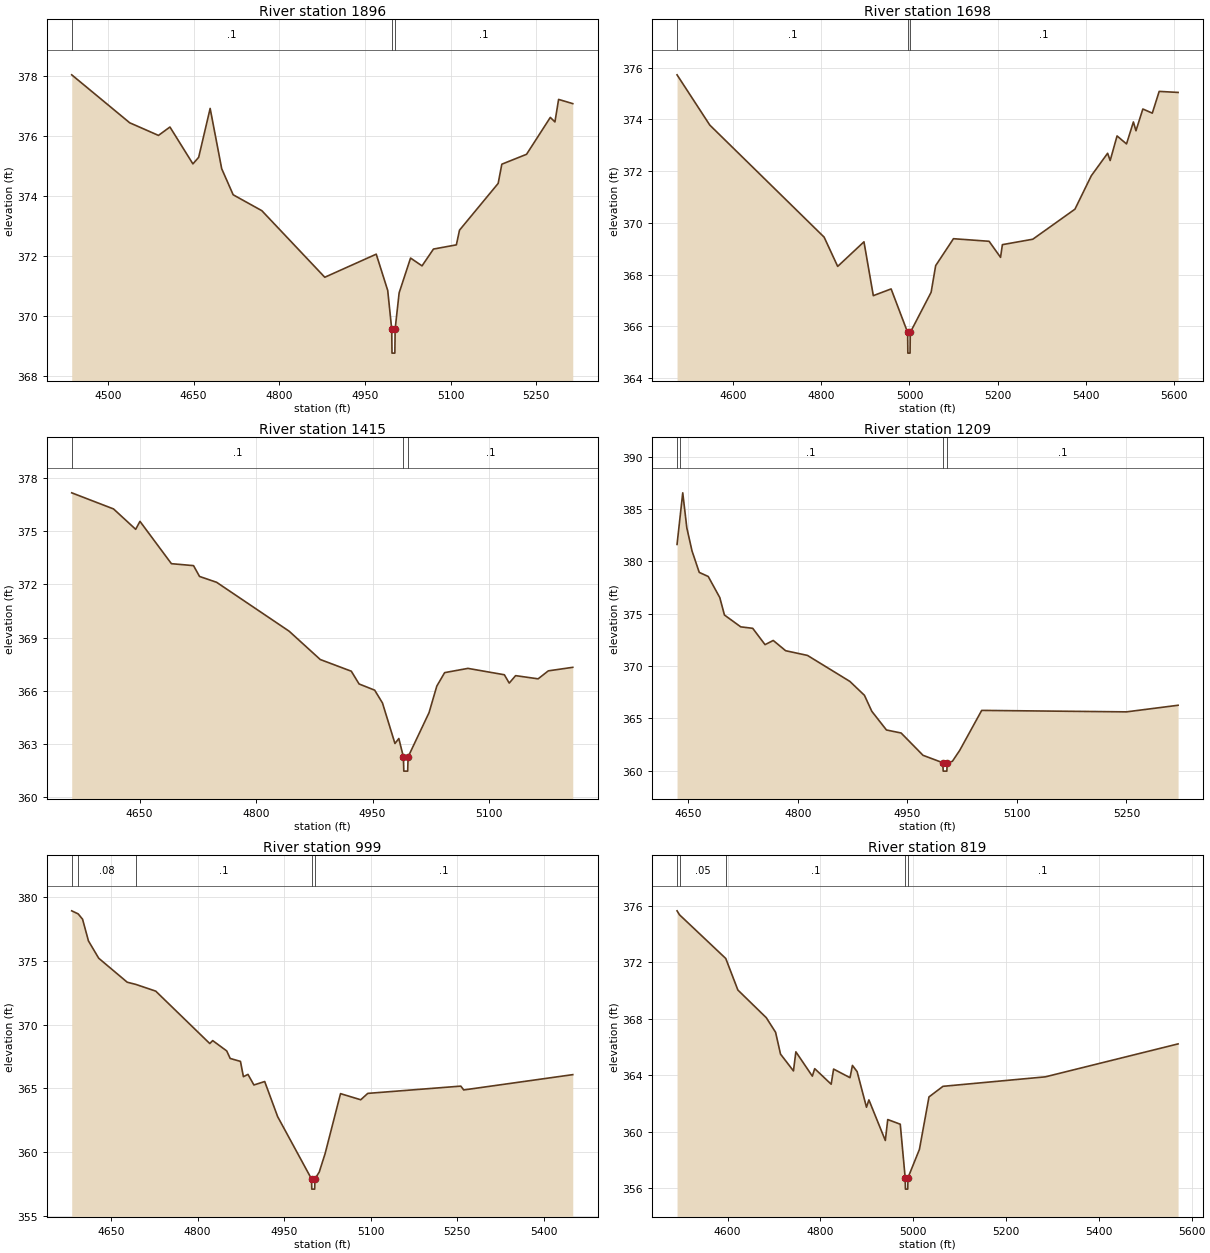
Type RM Length L Ch R = 1,1896,198,198,198
BEGIN DESCRIPTION:
Mapping XS 1c2fad4b
END DESCRIPTION:
XS GIS Cut Line= 4
      2074435.97     13449019.48      2074121.31     13448984.76
      2073758.90     13449005.37      2073603.76     13449127.97
#Sta/Elev= 30
  4436.6  378.03  4538.2  376.43  4588.5  376.01  4608.6  376.29  4648.8  375.06
  4658.9  375.28  4679.0  376.91  4699.2  374.90  4719.3  374.03  4769.5  373.50
  4879.7  371.28  4969.8  372.05  4989.9  370.84  4996.9  369.55  4997.4  368.75
  5002.4  368.75  5002.9  369.55  5009.9  370.76  5029.9  371.92  5050.0  371.66
  5070.0  372.22  5110.1  372.36  5115.6  372.85  5183.3  374.41  5189.7  375.05
  5233.0  375.38  5274.6  376.61  5282.7  376.46  5289.1  377.21  5313.9  377.07
#Mann=3,-1,0
  4436.6     0.1       0  4996.9    0.07       0  5002.9     0.1       0
Bank Sta=4996.9,5002.9
Exp/Cntr=0.3,0.1

Type RM Length L Ch R = 1,1698,283,283,283
BEGIN DESCRIPTION:
Mapping XS f67f010c
END DESCRIPTION:
XS GIS Cut Line= 4
      2074387.88     13448896.03      2074066.69     13448778.83
      2073671.72     13448830.92      2073469.92     13449169.79
#Sta/Elev= 30
  4473.6  375.72  4547.7  373.78  4806.7  369.45  4837.4  368.32  4896.9  369.27
  4918.1  367.19  4958.4  367.45  4995.8  365.77  4996.3  364.97  5001.3  364.97
  5001.8  365.77  5049.0  367.32  5059.3  368.35  5099.6  369.39  5180.3  369.29
  5206.2  368.67  5210.4  369.16  5279.3  369.37  5374.7  370.53  5411.7  371.82
  5448.7  372.69  5454.5  372.41  5470.1  373.36  5491.5  373.05  5507.1  373.90
  5512.9  373.56  5528.5  374.40  5549.9  374.24  5565.5  375.08  5608.3  375.04
#Mann=3,-1,0
  4473.6     0.1       0  4995.8    0.07       0  5001.8     0.1       0
Bank Sta=4995.8,5001.8
Exp/Cntr=0.3,0.1

Type RM Length L Ch R = 1,1415,206,206,206
BEGIN DESCRIPTION:
Mapping XS f241f090
END DESCRIPTION:
XS GIS Cut Line= 4
      2074374.65     13448644.38      2074170.64     13448551.06
      2073842.94     13448566.25      2073786.50     13448640.06
#Sta/Elev= 30
  4562.5  377.17  4616.4  376.26  4644.9  375.11  4650.4  375.56  4690.9  373.17
  4719.4  373.06  4727.1  372.45  4749.1  372.12  4842.5  369.36  4882.6  367.76
  4922.6  367.10  4932.6  366.38  4952.7  366.03  4962.7  365.31  4978.8  363.02
  4983.8  363.30  4989.7  362.26  4990.2  361.46  4995.2  361.46  4995.7  362.26
  5022.7  364.76  5032.7  366.26  5042.8  367.02  5072.8  367.26  5119.7  366.90
  5126.0  366.43  5134.2  366.85  5163.2  366.67  5176.3  367.12  5207.8  367.32
#Mann=3,-1,0
  4562.5     0.1       0  4989.7    0.07       0  4995.7     0.1       0
Bank Sta=4989.7,4995.7
Exp/Cntr=0.3,0.1

Type RM Length L Ch R = 1,1209,210,210,210
BEGIN DESCRIPTION:
Mapping XS 37194d33
END DESCRIPTION:
XS GIS Cut Line= 4
      2074333.40     13448425.19      2074172.81     13448347.07
      2073858.14     13448370.94      2073793.61     13448551.60
#Sta/Elev= 30
  4634.8  381.62  4638.2  383.77  4642.6  386.55  4648.2  383.20  4655.3  381.00
  4665.2  378.95  4677.5  378.56  4693.3  376.55  4699.7  374.88  4722.0  373.75
  4738.4  373.61  4755.3  372.05  4766.5  372.45  4783.5  371.47  4813.4  371.02
  4871.4  368.54  4891.4  367.21  4901.4  365.69  4921.5  363.90  4941.6  363.61
  4971.6  361.48  4998.7  360.77  4999.2  359.97  5004.2  359.97  5004.7  360.77
  5011.8  360.91  5021.8  361.95  5051.9  365.77  5250.1  365.63  5320.8  366.26
#Mann=4,-1,0
  4634.8    0.05       0  4638.2     0.1       0  4998.7    0.07       0
  5004.7     0.1       0
Bank Sta=4998.7,5004.7
Exp/Cntr=0.3,0.1

Type RM Length L Ch R = 1,999,180,180,180
BEGIN DESCRIPTION:
Mapping XS 38fc7236
END DESCRIPTION:
XS GIS Cut Line= 4
      2074333.40     13448210.35      2074070.81     13448153.92
      2073825.58     13448212.52      2073769.16     13448555.39
#Sta/Elev= 30
  4582.0  378.92  4593.2  378.68  4600.8  378.26  4611.0  376.56  4628.8  375.20
  4678.2  373.32  4693.0  373.15  4727.6  372.62  4821.2  368.51  4826.3  368.74
  4850.6  367.93  4856.6  367.34  4874.4  367.11  4879.5  365.91  4887.4  366.09
  4897.7  365.26  4916.4  365.53  4938.8  362.78  4997.5  357.89  4998.0  357.09
  5003.0  357.09  5003.5  357.89  5010.9  358.43  5021.1  359.88  5047.8  364.58
  5082.8  364.10  5095.0  364.60  5256.2  365.17  5261.3  364.87  5450.2  366.07
#Mann=5,-1,0
  4582.0    0.05       0  4593.2    0.08       0  4693.0     0.1       0
  4997.5    0.07       0  5003.5     0.1       0
Bank Sta=4997.5,5003.5
Exp/Cntr=0.3,0.1

Type RM Length L Ch R = 1,819,154,154,154
BEGIN DESCRIPTION:
Mapping XS 064d839d
END DESCRIPTION:
XS GIS Cut Line= 4
      2074333.43     13448023.72      2074101.19     13447975.97
      2073782.18     13448058.44      2073743.14     13448570.25
#Sta/Elev= 30
  4490.9  375.63  4496.2  375.35  4595.9  372.26  4622.0  370.03  4683.3  368.07
  4703.3  367.04  4713.9  365.50  4741.8  364.31  4747.0  365.66  4782.5  363.94
  4787.6  364.47  4823.1  363.37  4828.3  364.44  4863.7  363.83  4868.9  364.70
  4879.0  364.26  4899.2  361.74  4904.4  362.26  4939.8  359.39  4945.0  360.87
  4972.0  360.54  4982.6  356.75  4983.1  355.95  4988.1  355.95  4988.6  356.75
  5013.3  358.76  5033.9  362.47  5064.1  363.22  5284.7  363.89  5570.8  366.22
#Mann=5,-1,0
  4490.9    0.08       0  4496.2    0.05       0  4595.9     0.1       0
  4982.6    0.07       0  4988.6     0.1       0
Bank Sta=4982.6,4988.6
Exp/Cntr=0.3,0.1

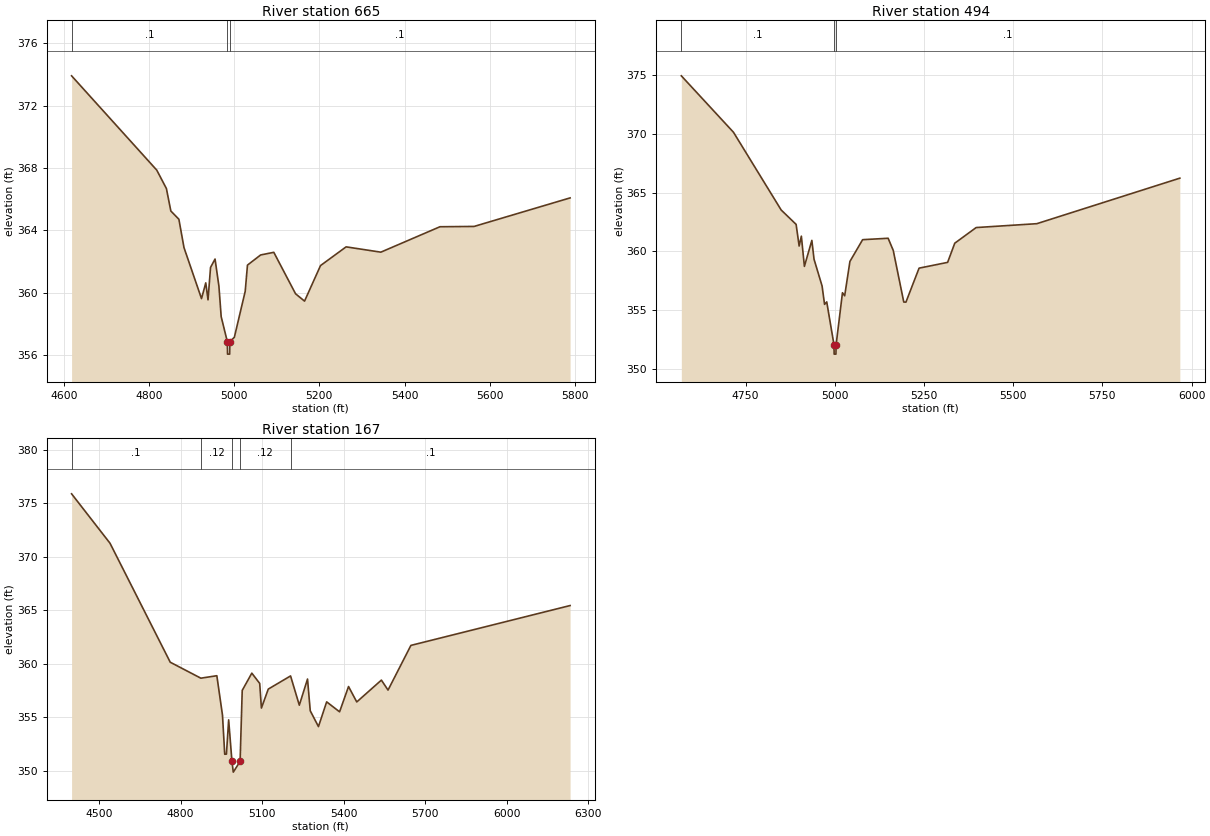
Type RM Length L Ch R = 1,665,171,171,171
BEGIN DESCRIPTION:
Mapping XS 1502ba1b
END DESCRIPTION:
XS GIS Cut Line= 4
      2074244.40     13447873.97      2074025.24     13447856.61
      2073719.25     13447965.12      2073686.70     13448590.07
#Sta/Elev= 30
  4618.4  373.92  4818.4  367.87  4841.0  366.69  4851.4  365.25  4870.3  364.72
  4882.3  362.90  4923.4  359.63  4933.4  360.64  4938.7  359.55  4944.6  361.63
  4955.2  362.17  4964.3  360.42  4969.6  358.47  4984.0  356.87  4984.5  356.07
  4989.5  356.07  4990.0  356.87  5000.5  357.15  5026.0  360.10  5031.3  361.78
  5062.2  362.43  5093.1  362.60  5144.2  359.94  5165.3  359.47  5202.8  361.75
  5262.9  362.95  5344.4  362.61  5483.2  364.24  5563.3  364.26  5788.7  366.09
#Mann=3,-1,0
  4618.4     0.1       0  4984.0    0.07       0  4990.0     0.1       0
Bank Sta=4984,4990
Exp/Cntr=0.3,0.1

Type RM Length L Ch R = 1,494,327,327,327
BEGIN DESCRIPTION:
Mapping XS a9aa2796
END DESCRIPTION:
XS GIS Cut Line= 4
      2074201.02     13447637.43      2073955.79     13447648.28
      2073634.61     13447880.49      2073621.59     13448635.67
#Sta/Elev= 30
  4569.9  374.93  4716.1  370.13  4849.8  363.52  4891.6  362.30  4900.1  360.46
  4906.3  361.30  4914.8  358.73  4935.7  360.94  4941.8  359.34  4964.4  357.06
  4971.3  355.50  4977.4  355.71  4997.7  352.07  4998.2  351.27  5003.2  351.27
  5003.7  352.07  5021.5  356.49  5027.7  356.23  5042.4  359.15  5078.0  361.00
  5149.5  361.12  5163.8  360.09  5193.3  355.70  5199.4  355.69  5236.2  358.58
  5316.2  359.07  5336.2  360.70  5396.2  362.03  5566.3  362.36  5967.0  366.23
#Mann=3,-1,0
  4569.9     0.1       0  4997.7    0.07       0  5003.7     0.1       0
Bank Sta=4997.7,5003.7
Exp/Cntr=0.3,0.1

Type RM Length L Ch R = 1,167,0,0,0
BEGIN DESCRIPTION:
Mapping XS 45c3bcf9
END DESCRIPTION:
XS GIS Cut Line= 4
      2074255.25     13447396.55      2073735.90     13447460.19
      2073621.59     13447609.22      2073493.56     13448724.64
#Sta/Elev= 30
  4398.7  375.88  4540.0  371.27  4761.6  360.16  4874.2  358.67  4933.0  358.90
  4953.8  355.22  4962.0  351.57  4968.3  351.58  4976.5  354.78  4988.6  350.90
  4993.5  349.90  5018.6  350.90  5026.4  357.53  5061.7  359.14  5090.7  358.18
  5097.0  355.88  5122.2  357.65  5204.2  358.88  5236.4  356.15  5266.6  358.59
  5276.6  355.63  5306.8  354.15  5337.0  356.46  5384.5  355.53  5417.5  357.89
  5447.7  356.45  5538.3  358.49  5562.8  357.56  5646.9  361.73  6232.5  365.45
#Mann=5,-1,0
  4398.7     0.1       0  4874.2    0.12       0  4988.6    0.07       0
  5018.6    0.12       0  5204.2     0.1       0
Bank Sta=4988.6,5018.6
Exp/Cntr=0.3,0.1

Chan Stop Cuts=-1