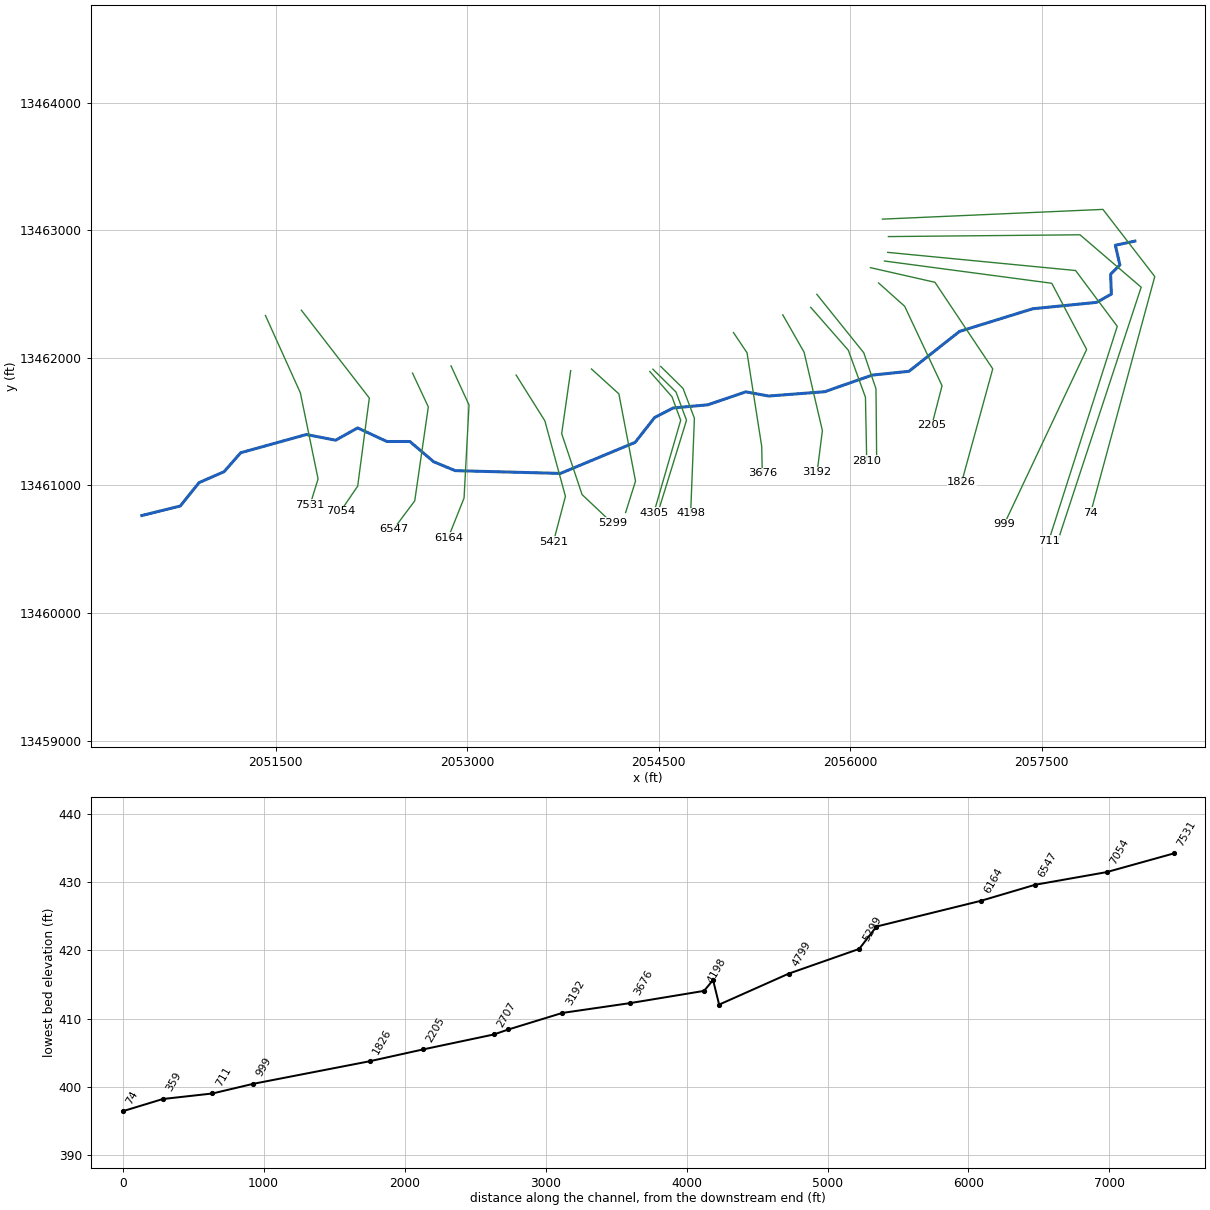
--- UNT 9 in Lagunillas Cr Wtrshd.prj (project) ---

Proj Title=UNT 9 in Lagunillas Cr Wtrshd Base Level Engineering
Current Plan=p01
Default Exp/Contr=0.3,0.1
English Units
Geom File=g01
Flow File=f01
Plan File=p01
BEGIN DESCRIPTION:
UNT 9 in Lagunillas Cr Wtrshd
END DESCRIPTION:

--- UNT 9 in Lagunillas Cr Wtrshd.p01 (plan) ---

Plan Title=Multiple Run
Short Identifier=Multiple
Geom File=g01
Flow File=f01
Subcritical Flow
K Sum by GR= 0
Std Step Tol= 0.01
Critical Tol= 0.01
Num of Std Step Trials= 20
Max Error Tol= 0.3
Flow Tol Ratio= 0.001
Split Flow NTrial= 30
Split Flow Tol= 0.02
Split Flow Ratio= 0.02
Log Output Level= 0
Friction Slope Method= 1
Unsteady Friction Slope Method= 2
Unsteady Bridges Friction Slope Method= 1
Parabolic Critical Depth
Global Vel Dist=  1 , 1 , 1
Global Log Level= 0
CheckData=True
Encroach Param= -1, 0, 0, 0
BEGIN DESCRIPTION:
Multiple Run
END DESCRIPTION:

--- UNT 9 in Lagunillas Cr Wtrshd.f01 (steady flow) ---

Flow Title=Multiple
Number of Profiles=7
Profile Names=10-year,25-year,50-year,1pct_min,100-year,1pct_plu,500-year
River Rch & RM= UNT 9 in Lagunil,Reach-1,7531
     224     312     386     238     476     949     733
River Rch & RM= UNT 9 in Lagunil,Reach-1,6547
     314     444     554     344     687    1370    1073
Boundary for River Rch & Prof#=UNT 9 in Lagunil,Reach-1,1
Up Type=0
Dn Type=3
Dn Slope=0.005
Boundary for River Rch & Prof#=UNT 9 in Lagunil,Reach-1,2
Up Type=0
Dn Type=3
Dn Slope=0.005
Boundary for River Rch & Prof#=UNT 9 in Lagunil,Reach-1,3
Up Type=0
Dn Type=3
Dn Slope=0.005
Boundary for River Rch & Prof#=UNT 9 in Lagunil,Reach-1,4
Up Type=0
Dn Type=3
Dn Slope=0.005
Boundary for River Rch & Prof#=UNT 9 in Lagunil,Reach-1,5
Up Type=0
Dn Type=3
Dn Slope=0.005
Boundary for River Rch & Prof#=UNT 9 in Lagunil,Reach-1,6
Up Type=0
Dn Type=3
Dn Slope=0.005
Boundary for River Rch & Prof#=UNT 9 in Lagunil,Reach-1,7
Up Type=0
Dn Type=3
Dn Slope=0.005

--- UNT 9 in Lagunillas Cr Wtrshd.g01 (geometry) ---

Geom Title=Existing Conditions

River Reach=UNT 9 in Lagunil,Reach-1
Reach XY= 30
      2050450.80     13460764.54      2050752.11     13460839.16
      2050899.34     13461022.49      2051095.17     13461107.91
      2051225.73     13461256.52      2051740.22     13461399.23
      2051969.39     13461354.78      2052141.61     13461451.03
      2052370.80     13461344.54      2052550.80     13461344.54
      2052737.70     13461185.64      2052906.11     13461116.20
      2053730.80     13461094.54      2054315.74     13461337.77
      2054468.35     13461532.56      2054614.70     13461607.56
      2054885.01     13461632.04      2055182.93     13461733.60
      2055361.58     13461700.79      2055800.80     13461734.54
      2056172.43     13461864.54      2056460.80     13461894.54
      2056856.80     13462206.91      2057430.80     13462384.54
      2057930.80     13462434.54      2058046.39     13462499.10
      2058040.80     13462654.54      2058113.27     13462727.01
      2058077.83     13462881.90      2058230.80     13462914.54

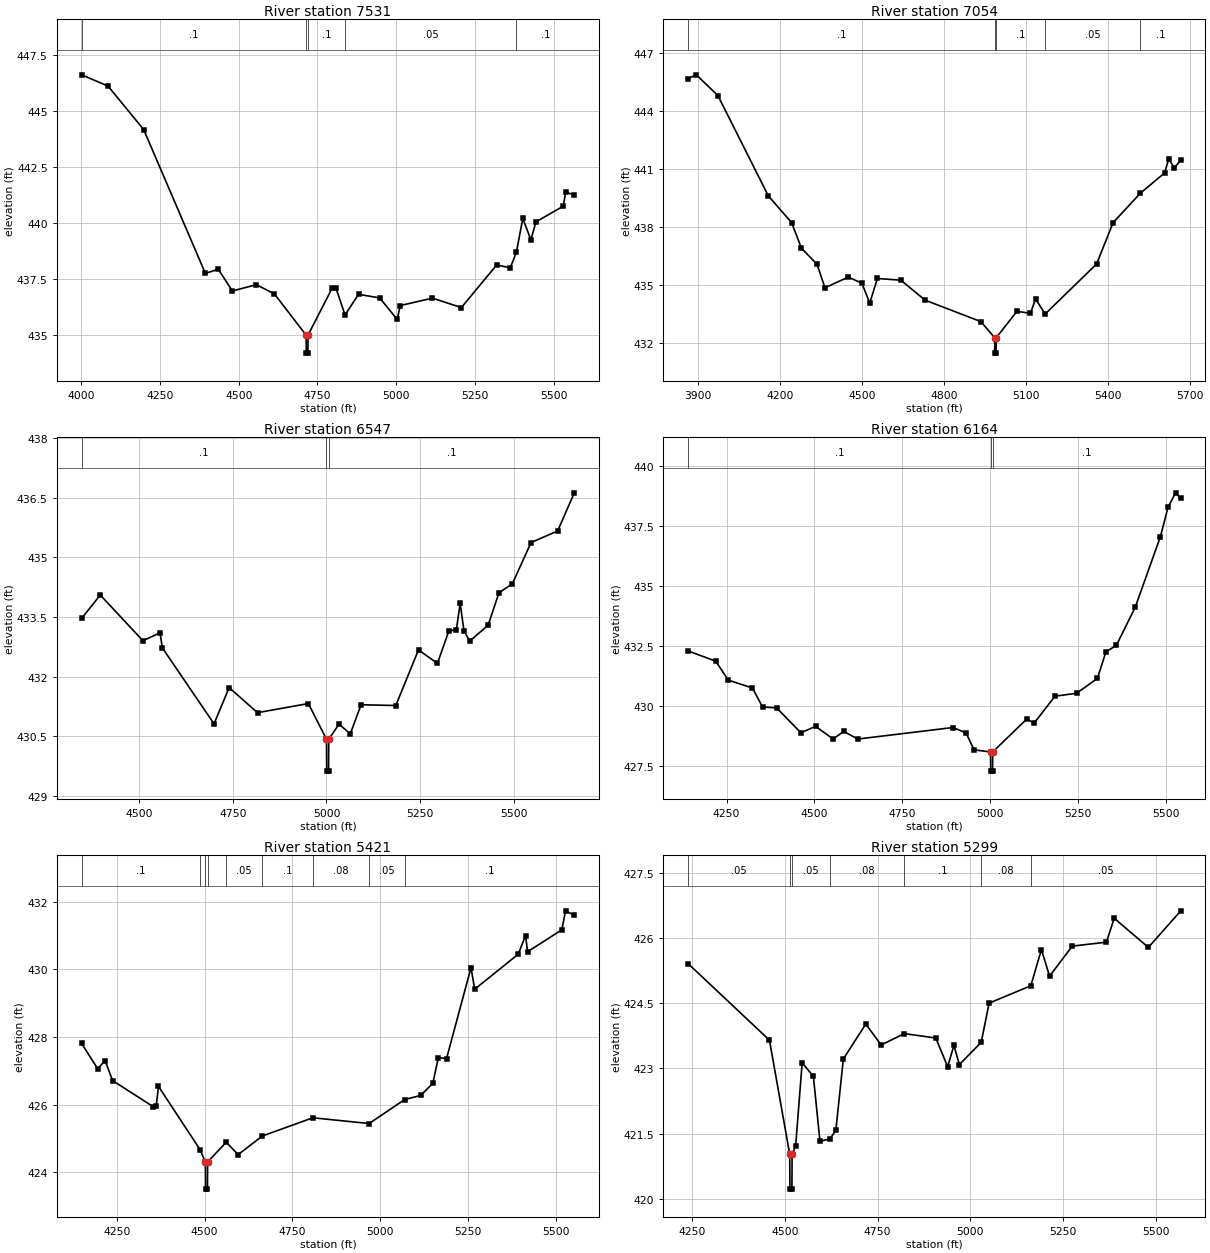
Type RM Length L Ch R = 1,7531,477,477,477
BEGIN DESCRIPTION:
Mapping XS 48c4e331
END DESCRIPTION:
XS GIS Cut Line= 4
      2051419.46     13462331.52      2051692.77     13461726.18
      2051831.65     13461051.26      2051769.14     13460848.63
#Sta/Elev= 30
  4000.8  446.61  4084.8  446.11  4198.2  444.17  4394.2  437.76  4435.0  437.95
  4479.8  436.98  4556.1  437.26  4613.3  436.85  4714.2  435.01  4714.7  434.21
  4719.7  434.21  4720.2  435.01  4797.0  437.11  4809.1  437.10  4837.8  435.91
  4880.6  436.83  4947.9  436.67  5003.4  435.71  5013.3  436.33  5115.4  436.66
  5207.3  436.24  5319.6  438.14  5362.7  438.01  5382.0  438.70  5402.5  440.21
  5428.1  439.26  5444.3  440.06  5531.3  440.76  5538.5  441.38  5566.1  441.26
#Mann=5,-1,0
  4000.8     0.1       0  4714.2    0.03       0  4720.2     0.1       0
  4837.8    0.05       0  5382.0     0.1       0
Bank Sta=4714.2,4720.2
Exp/Cntr=0.3,0.1

Type RM Length L Ch R = 1,7054,507,507,507
BEGIN DESCRIPTION:
Mapping XS 54ca8905
END DESCRIPTION:
XS GIS Cut Line= 4
      2051700.69     13462373.22      2052233.13     13461684.94
      2052141.98     13460994.84      2052008.36     13460798.71
#Sta/Elev= 30
  3863.9  445.67  3894.4  445.86  3973.1  444.79  4157.9  439.60  4243.0  438.22
  4278.9  436.90  4336.2  436.06  4365.2  434.85  4450.3  435.40  4500.1  435.09
  4529.1  434.06  4557.0  435.33  4643.2  435.24  4731.5  434.21  4935.8  433.10
  4986.2  432.27  4986.7  431.47  4991.7  431.47  4992.2  432.27  5067.7  433.63
  5117.3  433.53  5136.1  434.28  5170.9  433.49  5359.4  436.08  5419.9  438.22
  5519.7  439.74  5608.4  440.79  5623.3  441.51  5644.3  441.05  5667.5  441.45
#Mann=5,-1,0
  3863.9     0.1       0  4986.2    0.07       0  4992.2     0.1       0
  5170.9    0.05       0  5519.7     0.1       0
Bank Sta=4986.2,4992.2
Exp/Cntr=0.3,0.1

Type RM Length L Ch R = 1,6547,383,383,383
BEGIN DESCRIPTION:
Mapping XS 3b1da60d
END DESCRIPTION:
XS GIS Cut Line= 4
      2052571.65     13461880.29      2052695.37     13461615.50
      2052589.03     13460879.82      2052421.92     13460656.28
#Sta/Elev= 30
  4346.5  433.46  4396.5  434.05  4510.2  432.90  4555.9  433.10  4562.1  432.72
  4699.9  430.81  4740.3  431.72  4816.1  431.09  4951.7  431.32  5000.0  430.42
  5000.5  429.62  5005.5  429.62  5006.0  430.42  5033.3  430.80  5063.6  430.56
  5092.3  431.29  5184.9  431.27  5245.5  432.67  5296.0  432.33  5326.3  433.14
  5346.5  433.18  5356.7  433.84  5366.8  433.15  5382.0  432.89  5431.2  433.29
  5460.4  434.11  5495.8  434.33  5545.8  435.37  5616.7  435.66  5661.2  436.62
#Mann=3,-1,0
  4346.5     0.1       0  5000.0    0.07       0  5006.0     0.1       0
Bank Sta=5000,5006
Exp/Cntr=0.3,0.1

Type RM Length L Ch R = 1,6164,743,743,743
BEGIN DESCRIPTION:
Mapping XS cdc006f6
END DESCRIPTION:
XS GIS Cut Line= 4
      2052873.34     13461936.64      2053014.38     13461630.69
      2052975.32     13460901.52      2052851.61     13460591.18
#Sta/Elev= 30
  4140.5  432.30  4219.4  431.87  4254.9  431.08  4323.8  430.75  4352.3  429.96
  4392.7  429.92  4461.5  428.88  4503.1  429.15  4553.2  428.62  4583.2  428.94
  4623.3  428.62  4893.7  429.10  4930.9  428.88  4953.8  428.17  5000.7  428.08
  5001.2  427.28  5006.5  427.28  5007.0  428.08  5104.0  429.46  5124.5  429.28
  5184.1  430.41  5245.3  430.53  5304.6  431.15  5328.8  432.26  5358.5  432.53
  5412.4  434.13  5483.8  437.07  5505.3  438.29  5526.8  438.90  5541.7  438.67
#Mann=3,-1,0
  4140.5     0.1       0  5000.7    0.07       0  5007.0     0.1       0
Bank Sta=5000.7,5007
Exp/Cntr=0.3,0.1

Type RM Length L Ch R = 1,5421,122,122,122
BEGIN DESCRIPTION:
Mapping XS 32e9b1c9
END DESCRIPTION:
XS GIS Cut Line= 4
      2053383.28     13461865.11      2053608.19     13461506.98
      2053769.65     13460914.97      2053676.27     13460560.80
#Sta/Elev= 30
  4149.6  427.81  4195.5  427.06  4216.7  427.30  4237.9  426.71  4353.3  425.94
  4362.3  425.97  4368.6  426.54  4486.8  424.67  4502.1  424.30  4502.6  423.50
  4508.0  423.50  4508.5  424.30  4561.5  424.89  4595.3  424.52  4664.1  425.07
  4808.1  425.61  4968.3  425.44  5069.6  426.15  5115.1  426.27  5149.6  426.63
  5165.4  427.39  5188.7  427.36  5258.3  430.05  5268.8  429.41  5392.9  430.45
  5413.6  431.00  5419.4  430.52  5517.0  431.17  5527.4  431.73  5552.4  431.60
#Mann=9,-1,0
  4149.6     0.1       0  4486.8    0.08       0  4502.1    0.04       0
  4508.5    0.08       0  4561.5    0.05       0  4664.1     0.1       0
  4808.1    0.08       0  4968.3    0.05       0  5069.6     0.1       0
Bank Sta=4502.1,4508.5
Exp/Cntr=0.3,0.1

Type RM Length L Ch R = 1,5299,500,500,500
BEGIN DESCRIPTION:
Mapping XS 74a6cbb6
END DESCRIPTION:
XS GIS Cut Line= 5
      2053810.82     13461899.79      2053740.13     13461406.29
      2053899.85     13460928.85      2054135.04     13460706.21
      2054138.50     13460706.21
#Sta/Elev= 30
  4238.8  425.41  4458.5  423.65  4513.2  421.03  4513.7  420.23  4519.1  420.23
  4519.6  421.03  4529.1  421.22  4546.7  423.13  4577.0  422.82  4594.7  421.33
  4621.4  421.38  4637.6  421.58  4657.8  423.22  4718.4  424.02  4759.8  423.54
  4822.2  423.80  4907.4  423.70  4939.1  423.04  4956.2  423.53  4970.7  423.09
  5029.8  423.60  5051.0  424.50  5163.6  424.90  5192.1  425.73  5214.1  425.12
  5275.4  425.81  5367.5  425.90  5388.5  426.45  5480.7  425.78  5568.1  426.62
#Mann=7,-1,0
  4238.8    0.05       0  4513.2    0.07       0  4519.6    0.05       0
  4621.4    0.08       0  4822.2     0.1       0  5029.8    0.08       0
  5163.6    0.05       0
Bank Sta=4513.2,4519.6
Exp/Cntr=0.3,0.1

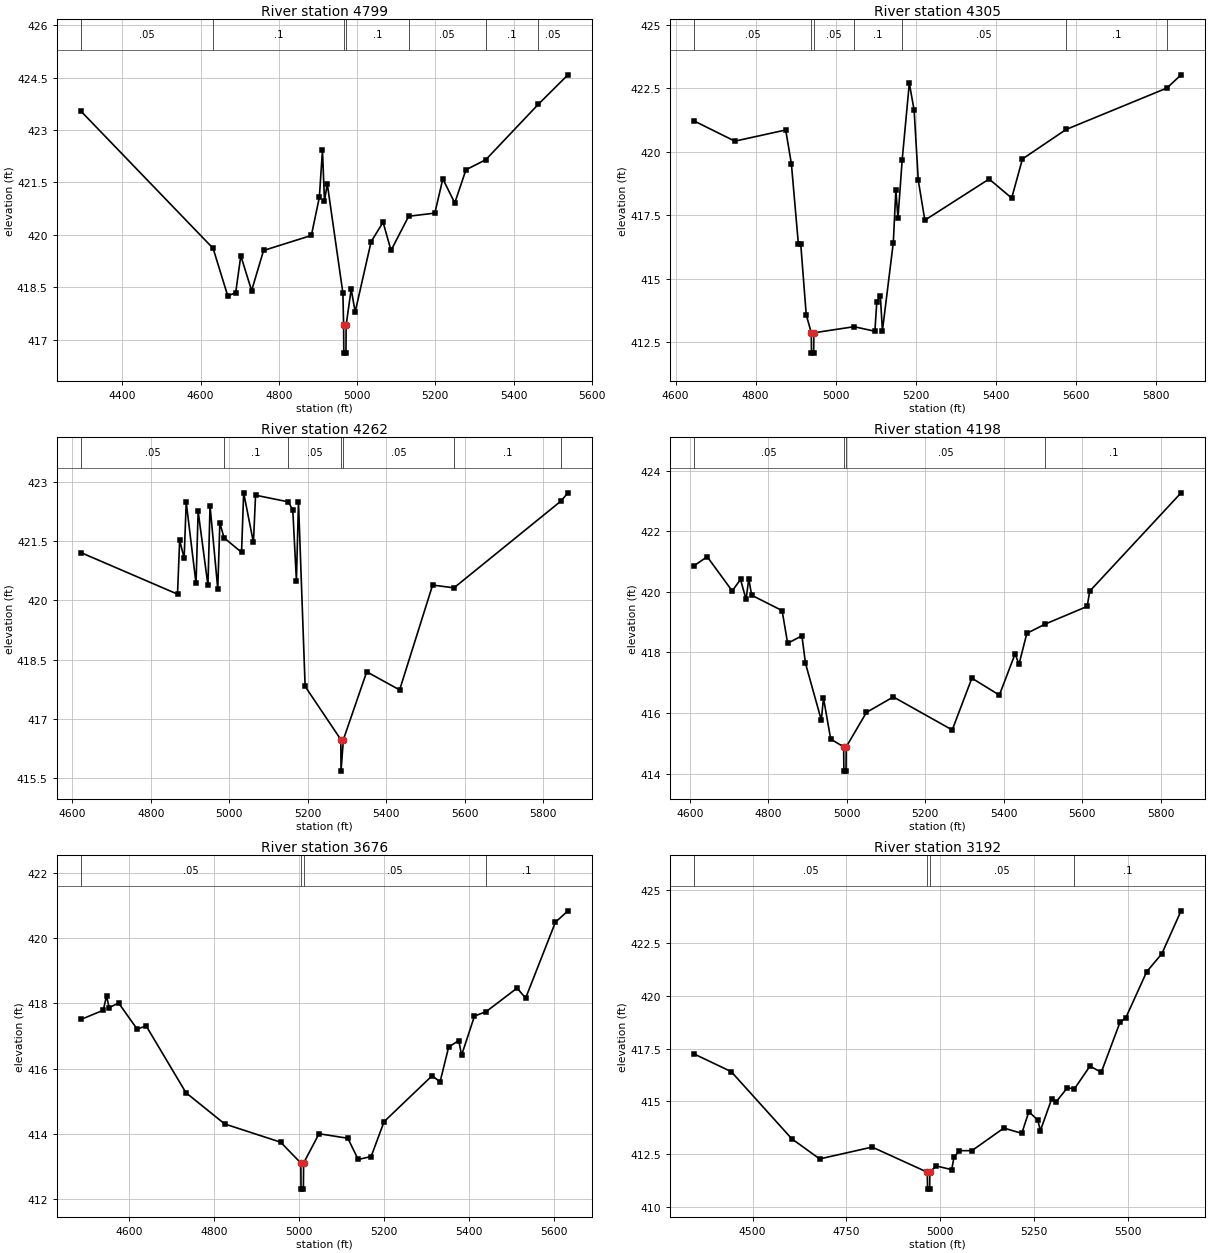
Type RM Length L Ch R = 1,4799,494,494,494
BEGIN DESCRIPTION:
Mapping XS 2d02362e
END DESCRIPTION:
XS GIS Cut Line= 4
      2053973.57     13461912.82      2054188.42     13461717.50
      2054318.63     13461033.90      2054241.05     13460788.22
#Sta/Elev= 30
  4295.0  423.53  4632.0  419.61  4669.4  418.25  4689.7  418.34  4702.8  419.40
  4730.4  418.40  4761.0  419.55  4883.1  419.98  4903.5  421.07  4911.5  422.42
  4916.6  420.97  4923.8  421.46  4963.7  418.33  4965.5  417.41  4966.0  416.61
  4971.5  416.61  4972.0  417.41  4984.9  418.44  4995.1  417.79  5035.8  419.80
  5066.4  420.36  5086.7  419.55  5131.8  420.53  5198.7  420.62  5219.1  421.60
  5249.6  420.91  5278.2  421.86  5329.0  422.15  5463.5  423.74  5538.9  424.58
#Mann=7,-1,0
  4295.0    0.05       0  4632.0     0.1       0  4965.5    0.07       0
  4972.0     0.1       0  5131.8    0.05       0  5329.0     0.1       0
  5463.5    0.05       0
Bank Sta=4965.5,4972
Exp/Cntr=0.3,0.1

Type RM Length L Ch R = 1,4305,43,43,43
BEGIN DESCRIPTION:
Mapping XS 16b7de12
END DESCRIPTION:
XS GIS Cut Line= 4
      2054430.62     13461892.87      2054604.21     13461695.42
      2054672.57     13461510.96      2054461.86     13460784.32
#Sta/Elev= 30
  4646.8  421.20  4747.9  420.41  4875.0  420.85  4889.2  419.52  4906.7  416.36
  4912.6  416.36  4926.3  413.58  4938.9  412.87  4939.4  412.07  4944.9  412.07
  4945.4  412.87  5046.0  413.11  5097.9  412.93  5102.7  414.10  5111.5  414.32
  5116.7  412.95  5143.9  416.42  5150.3  418.49  5155.5  417.37  5166.1  419.68
  5183.9  422.69  5195.9  421.63  5206.3  418.87  5222.7  417.30  5383.3  418.92
  5439.7  418.17  5466.6  419.71  5575.7  420.87  5827.6  422.50  5863.0  423.02
#Mann=7,-1,0
  4646.8    0.05       0  4938.9    0.03       0  4945.4    0.05       0
  5046.0     0.1       0  5166.1    0.05       0  5575.7     0.1       0
  5827.6    0.05       0
Bank Sta=4938.9,4945.4
Exp/Cntr=0.3,0.1

Type RM Length L Ch R = 1,4262,64,64,64
BEGIN DESCRIPTION:
Mapping XS 207cc932
END DESCRIPTION:
XS GIS Cut Line= 4
      2054454.44     13461911.38      2054635.68     13461732.31
      2054718.14     13461510.96      2054496.58     13460795.16
#Sta/Elev= 30
  4622.5  421.21  4867.8  420.16  4873.3  421.53  4884.7  421.07  4890.0  422.49
  4915.0  420.43  4920.4  422.26  4945.4  420.38  4950.7  422.40  4970.4  420.29
  4975.7  421.97  4986.3  421.59  5031.0  421.22  5036.4  422.73  5061.3  421.47
  5066.7  422.67  5150.4  422.50  5161.6  422.29  5170.8  420.50  5176.1  422.50
  5193.0  417.82  5284.0  416.47  5284.5  415.67  5290.5  416.47  5350.0  418.19
  5433.8  417.73  5517.9  420.39  5572.4  420.32  5844.9  422.52  5862.8  422.73
#Mann=7,-1,0
  4622.5    0.05       0  4986.3     0.1       0  5150.4    0.05       0
  5284.0    0.07       0  5290.5    0.05       0  5572.4     0.1       0
  5844.9    0.05       0
Bank Sta=5284,5290.5
Exp/Cntr=0.3,0.1

Type RM Length L Ch R = 1,4198,522,522,522
BEGIN DESCRIPTION:
Mapping XS 3635133e
END DESCRIPTION:
XS GIS Cut Line= 4
      2054516.10     13461932.36      2054691.01     13461760.52
      2054779.99     13461527.23      2054750.49     13460782.20
#Sta/Elev= 30
  4611.9  420.87  4644.6  421.16  4708.3  420.03  4729.5  420.41  4743.6  419.75
  4750.6  420.43  4757.8  419.89  4835.5  419.38  4849.6  418.30  4886.0  418.55
  4895.1  417.64  4935.5  415.76  4940.9  416.50  4959.3  415.14  4992.4  414.88
  4992.9  414.08  4998.4  414.08  4998.9  414.88  5050.5  416.02  5119.0  416.53
  5269.1  415.44  5319.2  417.15  5389.2  416.59  5429.3  417.95  5439.3  417.61
  5459.3  418.63  5506.8  418.94  5613.2  419.52  5619.4  420.02  5852.4  423.27
#Mann=4,-1,0
  4611.9    0.05       0  4992.4    0.03       0  4998.9    0.05       0
  5506.8     0.1       0
Bank Sta=4992.4,4998.9
Exp/Cntr=0.3,0.1

Type RM Length L Ch R = 1,3676,484,484,484
BEGIN DESCRIPTION:
Mapping XS 859f0e65
END DESCRIPTION:
XS GIS Cut Line= 4
      2055085.97     13462198.00      2055192.33     13462039.55
      2055307.35     13461306.04      2055311.69     13461095.49
#Sta/Elev= 30
  4488.5  417.51  4540.3  417.79  4547.9  418.23  4554.0  417.87  4576.4  418.01
  4619.9  417.21  4641.0  417.31  4734.5  415.26  4825.6  414.30  4957.2  413.74
  5004.6  413.10  5005.1  412.30  5010.6  412.30  5011.1  413.10  5047.4  414.00
  5115.1  413.86  5139.4  413.21  5169.8  413.30  5200.2  414.37  5313.2  415.78
  5331.8  415.59  5352.0  416.66  5375.8  416.86  5382.4  416.41  5412.7  417.61
  5440.5  417.75  5512.9  418.47  5532.9  418.16  5602.9  420.49  5632.4  420.84
#Mann=4,-1,0
  4488.5    0.05       0  5004.6    0.03       0  5011.1    0.05       0
  5440.5     0.1       0
Bank Sta=5004.6,5011.1
Exp/Cntr=0.3,0.1

Type RM Length L Ch R = 1,3192,382,382,382
BEGIN DESCRIPTION:
Mapping XS 9bc4a2e1
END DESCRIPTION:
XS GIS Cut Line= 4
      2055472.29     13462336.83      2055639.38     13462043.89
      2055782.61     13461429.74      2055741.38     13461104.22
#Sta/Elev= 30
  4345.1  417.24  4443.2  416.41  4604.6  413.23  4678.8  412.28  4818.5  412.84
  4965.4  411.65  4965.9  410.85  4971.6  410.85  4972.1  411.65  4988.7  411.95
  5030.3  411.77  5036.4  412.36  5050.9  412.67  5084.1  412.67  5169.2  413.74
  5216.9  413.49  5235.7  414.51  5259.4  414.12  5266.5  413.62  5296.8  415.13
  5307.6  414.96  5338.3  415.65  5356.9  415.59  5398.4  416.67  5428.6  416.38
  5479.0  418.77  5493.5  418.94  5549.6  421.14  5589.9  421.99  5641.1  424.02
#Mann=4,-1,0
  4345.1    0.05       0  4965.4    0.03       0  4972.1    0.05       0
  5356.9     0.1       0
Bank Sta=4965.4,4972.1
Exp/Cntr=0.3,0.1

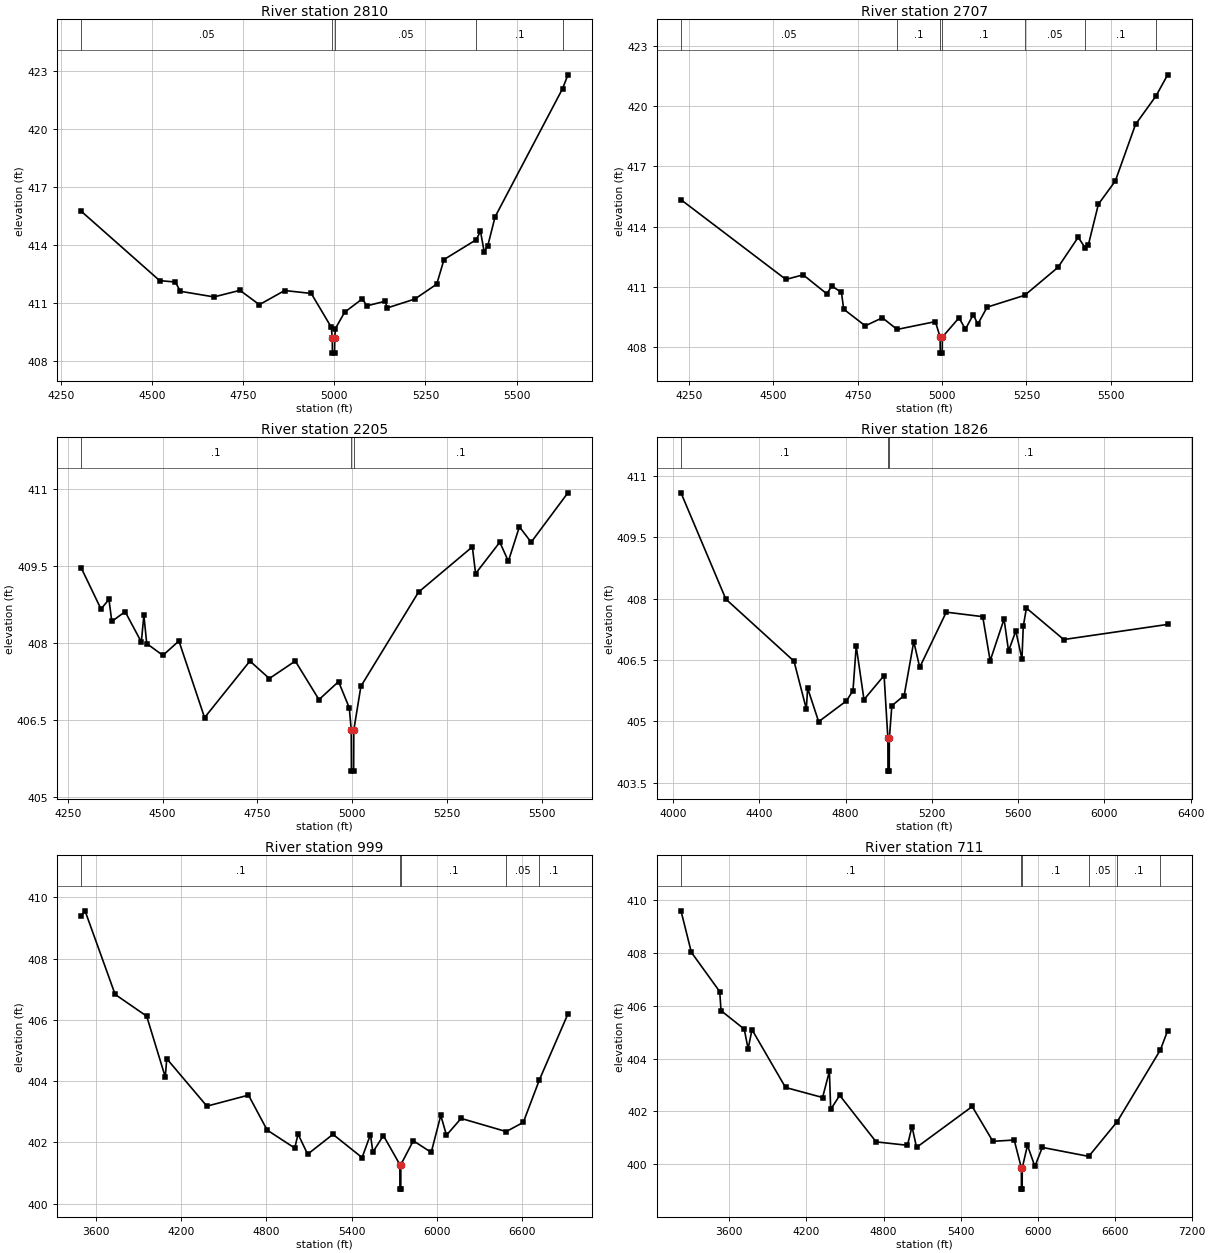
Type RM Length L Ch R = 1,2810,103,103,103
BEGIN DESCRIPTION:
Mapping XS f788358d
END DESCRIPTION:
XS GIS Cut Line= 4
      2055691.48     13462395.43      2055985.50     13462060.00
      2056120.05     13461691.08      2056129.83     13461195.32
#Sta/Elev= 30
  4306.2  415.75  4521.3  412.17  4564.0  412.10  4578.2  411.62  4670.3  411.33
  4741.4  411.67  4794.7  410.93  4864.0  411.66  4936.9  411.51  4991.8  409.77
  4994.6  409.23  4995.1  408.43  5000.9  408.43  5001.4  409.23  5003.3  409.70
  5028.5  410.54  5076.9  411.23  5089.6  410.87  5140.1  411.11  5144.9  410.76
  5221.0  411.22  5281.1  411.99  5301.1  413.26  5389.3  414.28  5401.1  414.72
  5411.1  413.67  5421.1  413.97  5441.1  415.46  5626.3  422.08  5640.8  422.79
#Mann=5,-1,0
  4306.2    0.05       0  4994.6    0.03       0  5001.4    0.05       0
  5389.3     0.1       0  5626.3    0.05       0
Bank Sta=4994.6,5001.4
Exp/Cntr=0.3,0.1

Type RM Length L Ch R = 1,2707,502,502,502
BEGIN DESCRIPTION:
Mapping XS 6cfa782d
END DESCRIPTION:
XS GIS Cut Line= 4
      2055739.20     13462497.45      2056107.03     13462039.39
      2056202.52     13461757.27      2056207.96     13461199.81
#Sta/Elev= 30
  4225.8  415.34  4536.8  411.37  4588.0  411.60  4658.4  410.65  4672.8  411.05
  4701.6  410.72  4708.1  409.89  4772.1  409.06  4822.9  409.46  4866.5  408.88
  4980.0  409.27  4994.0  408.50  4994.5  407.70  5000.3  407.70  5000.8  408.50
  5050.2  409.46  5069.0  408.89  5092.4  409.62  5105.7  409.14  5133.4  409.99
  5244.8  410.58  5343.4  411.97  5403.4  413.47  5424.0  412.95  5433.4  413.08
  5463.4  415.12  5513.4  416.27  5573.4  419.09  5634.2  420.51  5668.6  421.56
#Mann=7,-1,0
  4225.8    0.05       0  4866.5     0.1       0  4994.0    0.07       0
  5000.8     0.1       0  5244.8    0.05       0  5424.0     0.1       0
  5634.2    0.05       0
Bank Sta=4994,5000.8
Exp/Cntr=0.3,0.1

Type RM Length L Ch R = 1,2205,379,379,379
BEGIN DESCRIPTION:
Mapping XS a862899e
END DESCRIPTION:
XS GIS Cut Line= 4
      2056223.11     13462586.45      2056427.14     13462404.13
      2056720.11     13461781.30      2056639.90     13461471.32
#Sta/Elev= 30
  4285.8  409.46  4337.9  408.66  4358.8  408.85  4366.3  408.42  4401.4  408.61
  4444.1  408.02  4450.8  408.54  4458.3  407.99  4500.9  407.76  4543.1  408.04
  4610.7  406.55  4730.2  407.65  4781.3  407.31  4849.7  407.65  4912.1  406.90
  4963.7  407.25  4992.0  406.74  4997.1  406.31  4997.6  405.51  5003.4  405.51
  5003.9  406.31  5022.6  407.16  5174.4  408.99  5316.2  409.87  5324.7  409.35
  5388.5  409.96  5411.1  409.59  5440.1  410.26  5471.1  409.96  5567.9  410.92
#Mann=3,-1,0
  4285.8     0.1       0  4997.1    0.07       0  5003.9     0.1       0
Bank Sta=4997.1,5003.9
Exp/Cntr=0.3,0.1

Type RM Length L Ch R = 1,1826,827,827,827
BEGIN DESCRIPTION:
Mapping XS 3e427b1c
END DESCRIPTION:
XS GIS Cut Line= 4
      2056159.30     13462706.47      2056664.55     13462591.87
      2057117.24     13461913.68      2056873.14     13461023.53
#Sta/Elev= 30
  4036.6  410.59  4244.5  407.99  4560.7  406.47  4617.8  405.30  4623.8  405.81
  4674.9  404.99  4804.0  405.50  4834.1  405.75  4849.1  406.84  4885.1  405.53
  4978.3  406.12  4995.9  404.58  4996.4  403.78  5002.2  403.78  5002.7  404.58
  5014.3  405.38  5071.4  405.63  5116.0  406.95  5143.5  406.32  5266.6  407.67
  5435.7  407.56  5470.2  406.48  5534.6  407.50  5555.4  406.72  5589.1  407.21
  5617.6  406.52  5623.6  407.32  5638.3  407.77  5811.4  407.00  6293.1  407.37
#Mann=3,-1,0
  4036.6     0.1       0  4995.9    0.07       0  5002.7     0.1       0
Bank Sta=4995.9,5002.7
Exp/Cntr=0.3,0.1

Type RM Length L Ch R = 1,999,288,288,288
BEGIN DESCRIPTION:
Mapping XS 60374692
END DESCRIPTION:
XS GIS Cut Line= 4
      2056268.67     13462758.55      2057579.48     13462584.25
      2057852.92     13462065.59      2057206.48     13460695.41
#Sta/Elev= 30
  3497.1  409.38  3523.7  409.56  3735.5  406.83  3957.4  406.12  4088.3  404.13
  4098.7  404.73  4381.1  403.18  4673.7  403.54  4804.8  402.40  4999.5  401.81
  5022.1  402.27  5089.9  401.61  5268.0  402.26  5472.8  401.50  5531.7  402.25
  5548.9  401.68  5622.8  402.22  5738.8  401.27  5739.3  400.47  5745.1  400.47
  5745.6  401.27  5833.3  402.05  5959.3  401.67  6026.6  402.88  6066.6  402.23
  6169.4  402.78  6486.7  402.35  6607.0  402.65  6720.3  404.04  6920.8  406.19
#Mann=5,-1,0
  3497.1     0.1       0  5738.8    0.07       0  5745.6     0.1       0
  6486.7    0.05       0  6720.3     0.1       0
Bank Sta=5738.8,5745.6
Exp/Cntr=0.3,0.1

Type RM Length L Ch R = 1,711,352,352,352
BEGIN DESCRIPTION:
Mapping XS 77f92f05
END DESCRIPTION:
XS GIS Cut Line= 4
      2056294.74     13462826.25      2057766.12     13462684.08
      2058092.70     13462247.00      2057555.42     13460565.17
#Sta/Elev= 30
  3223.0  409.60  3303.6  408.03  3524.7  406.54  3534.7  405.82  3715.5  405.12
  3745.7  404.37  3775.8  405.10  4037.0  402.91  4325.5  402.53  4378.6  403.52
  4388.7  402.08  4459.0  402.61  4742.4  400.85  4986.3  400.72  5021.8  401.43
  5057.2  400.64  5490.7  402.19  5651.6  400.87  5817.7  400.92  5873.4  399.86
  5873.9  399.06  5879.7  399.06  5880.2  399.86  5920.8  400.72  5978.6  399.92
  6036.3  400.64  6398.0  400.30  6620.3  401.62  6955.7  404.33  7012.4  405.06
#Mann=6,-1,0
  3223.0     0.1       0  5873.4    0.07       0  5880.2     0.1       0
  6398.0    0.05       0  6620.3     0.1       0  6955.7    0.05       0
Bank Sta=5873.4,5880.2
Exp/Cntr=0.3,0.1

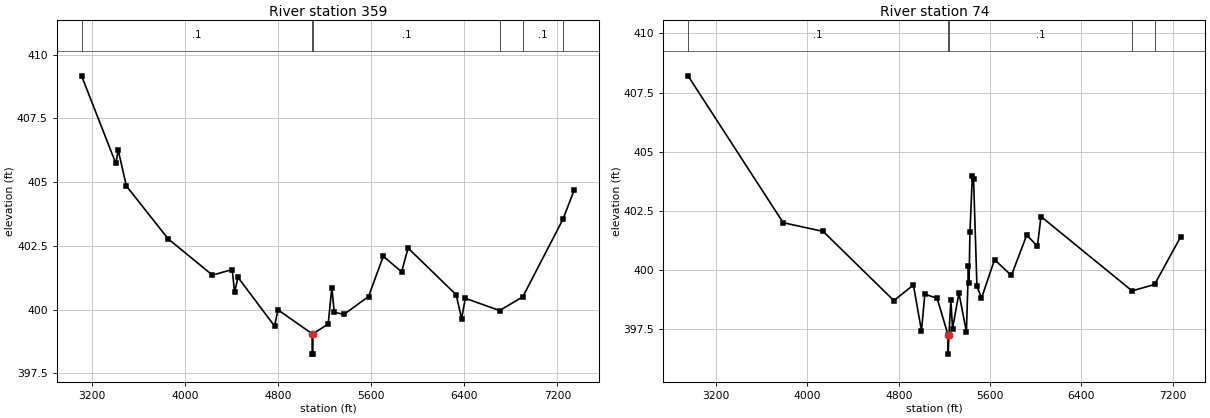
Type RM Length L Ch R = 1,359,285,285,285
BEGIN DESCRIPTION:
Mapping XS 5e7f32f8
END DESCRIPTION:
XS GIS Cut Line= 4
      2056299.97     13462950.00      2057800.84     13462964.02
      2058280.00     13462553.43      2057623.13     13460554.76
#Sta/Elev= 30
  3109.4  409.17  3404.4  405.73  3424.4  406.26  3494.4  404.85  3854.5  402.77
  4234.5  401.35  4404.5  401.57  4424.5  400.69  4454.5  401.26  4768.7  399.35
  4797.3  399.99  5091.3  399.05  5091.8  398.25  5097.6  398.25  5098.1  399.05
  5229.7  399.43  5260.8  400.86  5281.8  399.89  5365.1  399.81  5576.5  400.51
  5702.9  402.09  5860.7  401.48  5916.3  402.41  6329.7  400.58  6376.5  399.64
  6408.1  400.44  6703.0  399.96  6902.6  400.50  7248.4  403.55  7345.2  404.70
#Mann=6,-1,0
  3109.4     0.1       0  5091.3    0.07       0  5098.1     0.1       0
  6703.0    0.05       0  6902.6     0.1       0  7248.4    0.05       0
Bank Sta=5091.3,5098.1
Exp/Cntr=0.3,0.1

Type RM Length L Ch R = 1,74,0,0,0
BEGIN DESCRIPTION:
Mapping XS 404b2582
END DESCRIPTION:
XS GIS Cut Line= 4
      2056253.12     13463086.67      2057980.38     13463162.95
      2058386.63     13462636.91      2057883.54     13460783.88
#Sta/Elev= 30
  2955.6  408.21  3788.3  402.01  4138.6  401.64  4757.8  398.72  4928.8  399.38
  4999.5  397.44  5028.5  398.99  5136.3  398.82  5232.5  397.26  5233.0  396.46
  5239.3  397.26  5256.7  398.73  5271.2  397.54  5327.3  399.04  5392.6  397.40
  5410.4  400.16  5415.6  399.47  5423.7  401.62  5444.4  403.96  5455.4  403.84
  5484.8  399.34  5524.7  398.82  5638.9  400.45  5786.4  399.78  5921.1  401.49
  6014.3  401.01  6045.4  402.27  6842.9  399.13  7039.6  399.40  7269.3  401.42
#Mann=5,-1,0
  2955.6     0.1       0  5232.5    0.07       0  5239.3     0.1       0
  6842.9    0.05       0  7039.6     0.1       0
Bank Sta=5232.5,5239.3
Exp/Cntr=0.3,0.1

Chan Stop Cuts=-1