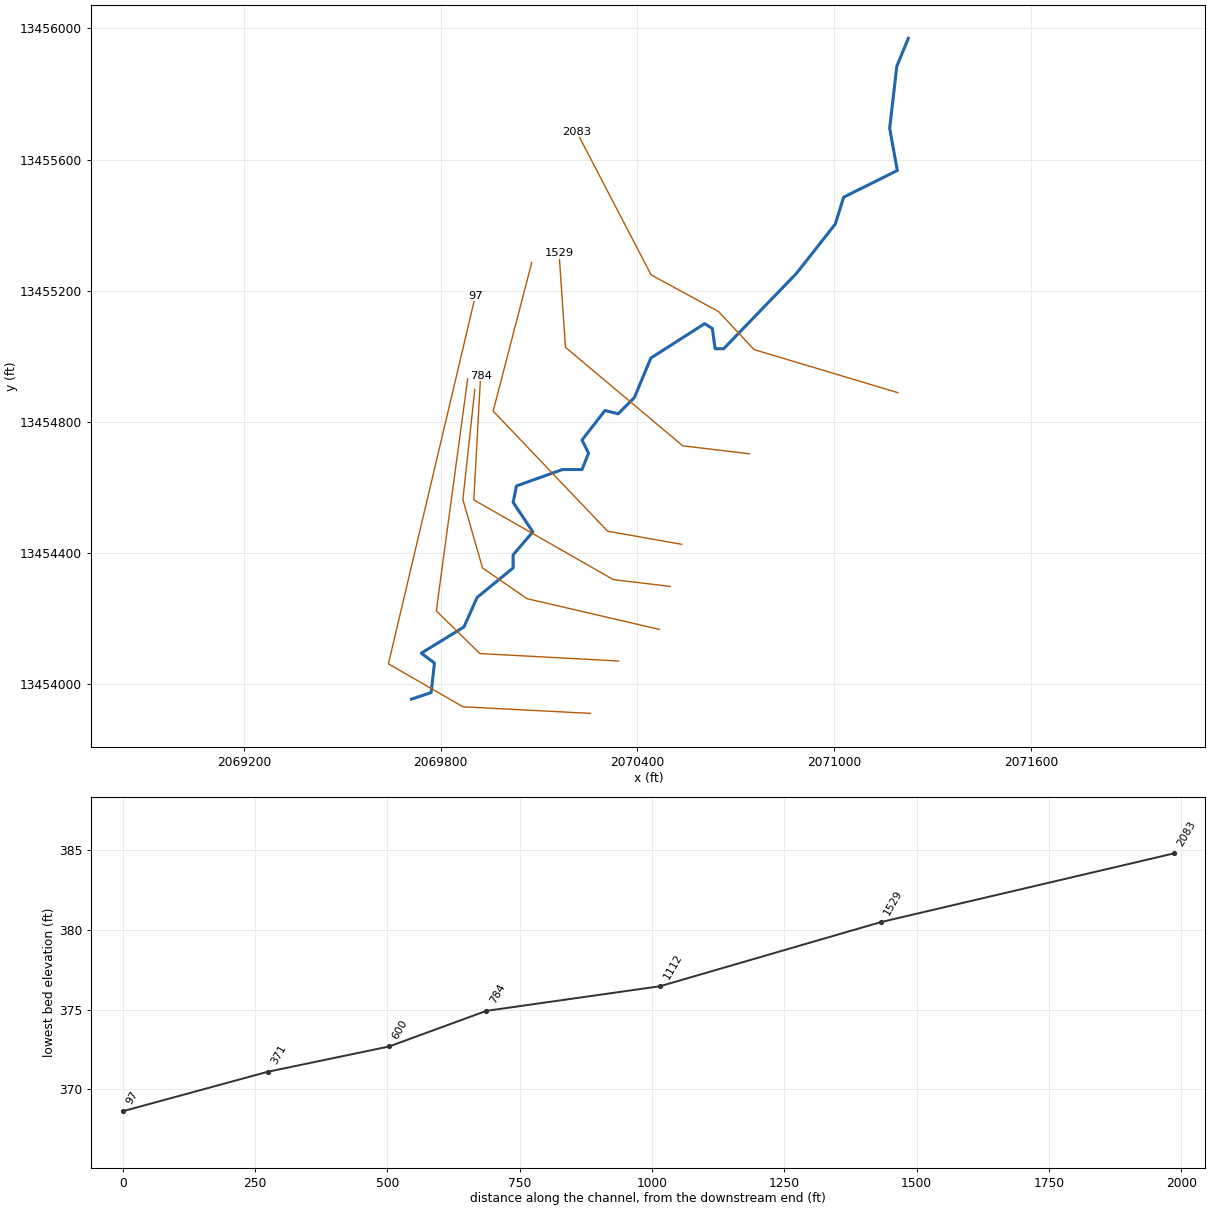
--- UNT 91 in Lagunillas Cr Wtrshd.prj (project) ---

Proj Title=UNT 91 in Lagunillas Cr Wtrshd Base Level Engineering
Current Plan=p01
Default Exp/Contr=0.3,0.1
English Units
Geom File=g01
Flow File=f01
Plan File=p01
BEGIN DESCRIPTION:
UNT 91 in Lagunillas Cr Wtrshd
END DESCRIPTION:

--- UNT 91 in Lagunillas Cr Wtrshd.p01 (plan) ---

Plan Title=Multiple Run
Short Identifier=Multiple
Geom File=g01
Flow File=f01
Subcritical Flow
K Sum by GR= 0
Std Step Tol= 0.01
Critical Tol= 0.01
Num of Std Step Trials= 20
Max Error Tol= 0.3
Flow Tol Ratio= 0.001
Split Flow NTrial= 30
Split Flow Tol= 0.02
Split Flow Ratio= 0.02
Log Output Level= 0
Friction Slope Method= 1
Unsteady Friction Slope Method= 2
Unsteady Bridges Friction Slope Method= 1
Parabolic Critical Depth
Global Vel Dist=  1 , 1 , 1
Global Log Level= 0
CheckData=True
Encroach Param= -1, 0, 0, 0
BEGIN DESCRIPTION:
Multiple Run
END DESCRIPTION:

--- UNT 91 in Lagunillas Cr Wtrshd.f01 (steady flow) ---

Flow Title=Multiple
Number of Profiles=7
Profile Names=10-year,25-year,50-year,1pct_min,100-year,1pct_plu,500-year
River Rch & RM= UNT 91 in Laguni,Reach-1,2083
      60      76      88      51     102     203     138
Boundary for River Rch & Prof#=UNT 91 in Laguni,Reach-1,1
Up Type=0
Dn Type=3
Dn Slope=0.005
Boundary for River Rch & Prof#=UNT 91 in Laguni,Reach-1,2
Up Type=0
Dn Type=3
Dn Slope=0.005
Boundary for River Rch & Prof#=UNT 91 in Laguni,Reach-1,3
Up Type=0
Dn Type=3
Dn Slope=0.005
Boundary for River Rch & Prof#=UNT 91 in Laguni,Reach-1,4
Up Type=0
Dn Type=3
Dn Slope=0.005
Boundary for River Rch & Prof#=UNT 91 in Laguni,Reach-1,5
Up Type=0
Dn Type=3
Dn Slope=0.005
Boundary for River Rch & Prof#=UNT 91 in Laguni,Reach-1,6
Up Type=0
Dn Type=3
Dn Slope=0.005
Boundary for River Rch & Prof#=UNT 91 in Laguni,Reach-1,7
Up Type=0
Dn Type=3
Dn Slope=0.005

--- UNT 91 in Lagunillas Cr Wtrshd.g01 (geometry) ---

Geom Title=Existing Conditions

River Reach=UNT 91 in Laguni,Reach-1
Reach XY= 30
      2071225.80     13455969.54      2071190.80     13455884.54
      2071168.96     13455694.96      2071192.39     13455566.49
      2071028.66     13455485.07      2071003.16     13455403.30
      2070885.10     13455253.12      2070662.88     13455023.09
      2070636.84     13455023.09      2070628.16     13455084.72
      2070604.72     13455099.48      2070440.80     13454994.54
      2070390.80     13454874.54      2070340.80     13454824.54
      2070300.80     13454834.54      2070230.80     13454744.54
      2070250.80     13454704.54      2070230.80     13454654.54
      2070170.80     13454654.54      2070030.80     13454604.54
      2070020.80     13454554.54      2070080.80     13454464.54
      2070020.80     13454394.54      2070020.80     13454354.54
      2069910.80     13454264.54      2069870.80     13454174.54
      2069740.80     13454094.54      2069780.80     13454064.54
      2069770.80     13453974.54      2069710.80     13453954.54

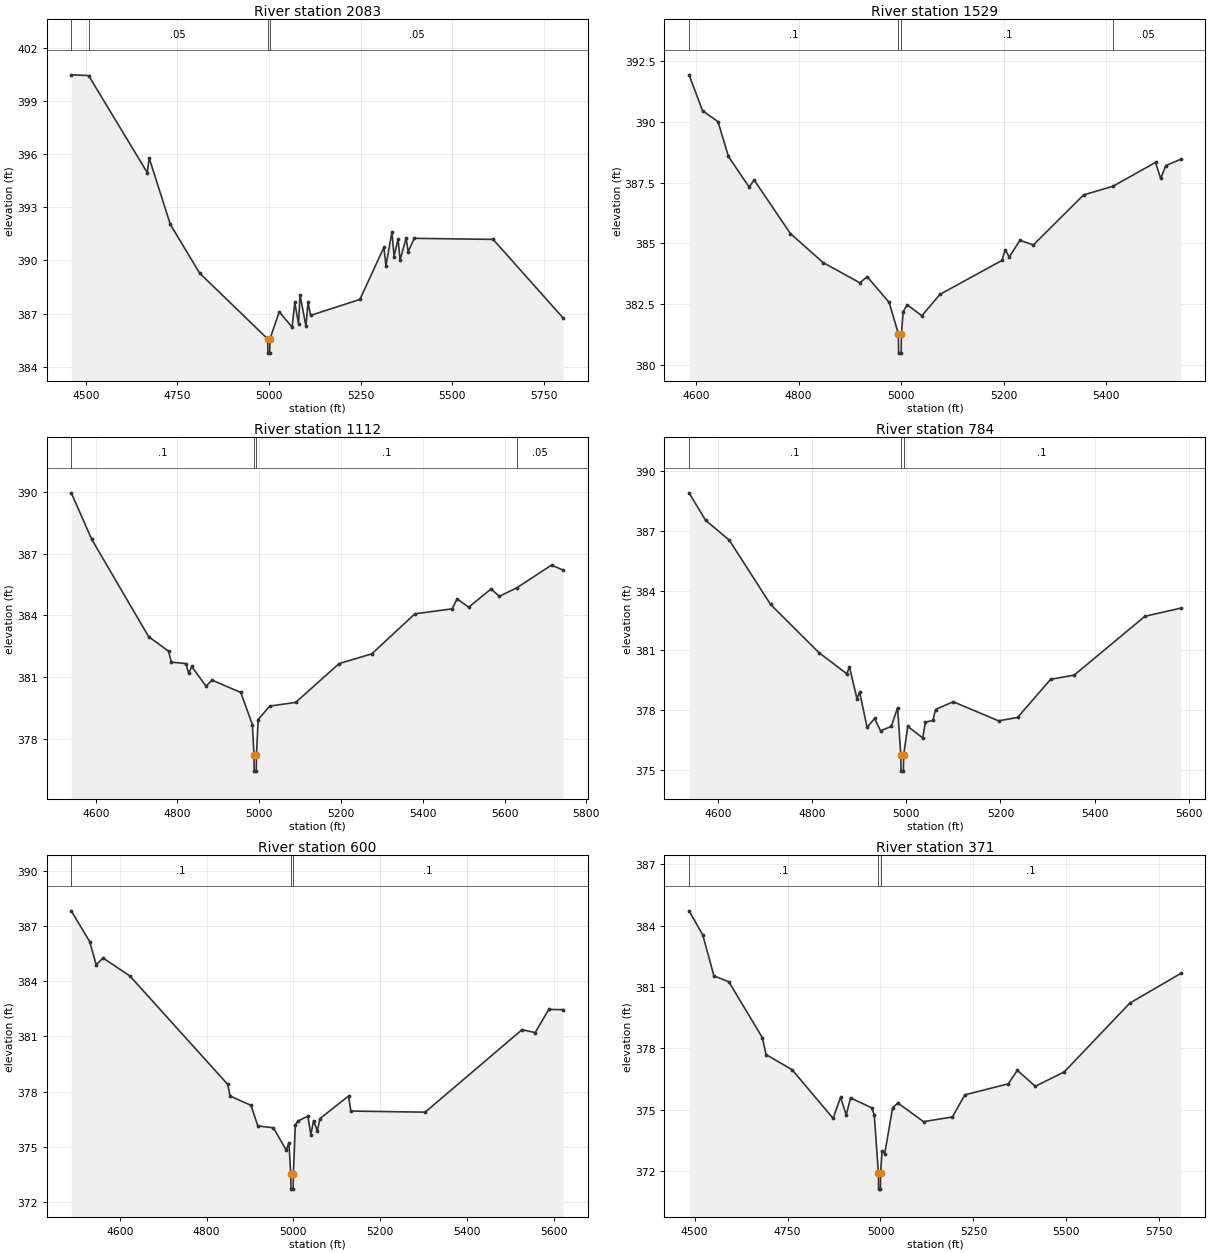
Type RM Length L Ch R = 1,2083,554,554,554
BEGIN DESCRIPTION:
Mapping XS f3e0edd8
END DESCRIPTION:
XS GIS Cut Line= 5
      2071193.90     13454889.02      2070755.20     13455020.51
      2070647.13     13455136.40      2070441.40     13455248.38
      2070214.70     13455684.17
#Sta/Elev= 30
  4460.6  400.48  4507.9  400.44  4668.0  394.96  4673.2  395.79  4730.9  392.04
  4810.7  389.29  4996.7  385.57  4997.2  384.77  5002.2  384.77  5002.7  385.57
  5028.1  387.10  5063.2  386.24  5070.6  387.63  5080.8  386.42  5084.9  388.06
  5101.0  386.29  5106.7  387.65  5113.6  386.90  5248.2  387.80  5313.7  390.74
  5319.3  389.71  5335.8  391.62  5341.4  390.22  5352.3  391.21  5357.9  390.03
  5374.4  391.27  5380.0  390.49  5396.5  391.25  5611.8  391.19  5802.5  386.76
#Mann=4,-1,0
  4460.6     0.1       0  4507.9    0.05       0  4996.7    0.03       0
  5002.7    0.05       0
Bank Sta=4996.7,5002.7
Exp/Cntr=0.3,0.1

Type RM Length L Ch R = 1,1529,417,417,417
BEGIN DESCRIPTION:
Mapping XS b64c7711
END DESCRIPTION:
XS GIS Cut Line= 4
      2070741.16     13454702.70      2070538.00     13454727.01
      2070180.36     13455027.35      2070160.78     13455314.26
#Sta/Elev= 30
  4586.2  391.94  4612.5  390.46  4642.7  390.01  4662.9  388.58  4703.2  387.32
  4713.3  387.60  4783.8  385.40  4847.8  384.20  4919.3  383.37  4933.6  383.62
  4976.5  382.56  4994.4  381.27  4994.9  380.47  4999.9  380.47  5000.4  381.27
  5003.9  382.18  5011.7  382.46  5040.3  382.01  5075.4  382.89  5196.4  384.29
  5202.9  384.73  5210.7  384.43  5231.5  385.12  5257.8  384.93  5355.7  386.99
  5413.3  387.35  5496.0  388.33  5506.1  387.67  5516.1  388.20  5545.4  388.46
#Mann=4,-1,0
  4586.2     0.1       0  4994.4    0.07       0  5000.4     0.1       0
  5413.3    0.05       0
Bank Sta=4994.4,5000.4
Exp/Cntr=0.3,0.1

Type RM Length L Ch R = 1,1112,328,328,328
BEGIN DESCRIPTION:
Mapping XS a530730c
END DESCRIPTION:
XS GIS Cut Line= 4
      2070534.56     13454426.65      2070308.84     13454466.59
      2069959.88     13454832.91      2070077.45     13455285.64
#Sta/Elev= 30
  4540.2  389.94  4590.5  387.68  4729.6  382.97  4778.2  382.27  4785.1  381.74
  4820.6  381.67  4827.6  381.19  4834.8  381.53  4870.0  380.57  4884.2  380.87
  4954.9  380.27  4983.3  378.71  4987.2  377.26  4987.7  376.46  4992.7  376.46
  4993.2  377.26  4997.4  378.96  5025.7  379.61  5089.2  379.79  5195.4  381.67
  5275.3  382.14  5380.8  384.08  5471.7  384.32  5484.1  384.80  5512.3  384.40
  5566.8  385.28  5587.5  384.93  5630.1  385.34  5715.0  386.44  5743.1  386.20
#Mann=4,-1,0
  4540.2     0.1       0  4987.2    0.07       0  4993.2     0.1       0
  5630.1    0.05       0
Bank Sta=4987.2,4993.2
Exp/Cntr=0.3,0.1

Type RM Length L Ch R = 1,784,184,184,184
BEGIN DESCRIPTION:
Mapping XS 0d74dbc3
END DESCRIPTION:
XS GIS Cut Line= 4
      2070499.84     13454298.18      2070326.20     13454319.02
      2069900.85     13454562.08      2069921.62     13454941.13
#Sta/Elev= 30
  4538.6  388.92  4573.7  387.54  4624.0  386.54  4711.6  383.31  4814.5  380.88
  4873.5  379.82  4879.3  380.16  4895.1  378.57  4900.9  378.89  4916.7  377.12
  4932.6  377.57  4945.2  376.95  4968.2  377.17  4981.5  378.12  4988.3  375.72
  4988.8  374.92  4993.8  374.92  4994.3  375.72  5003.1  377.17  5034.8  376.59
  5040.5  377.38  5056.4  377.47  5062.1  378.02  5099.6  378.41  5196.0  377.45
  5236.4  377.62  5306.5  379.54  5356.5  379.75  5506.8  382.71  5583.0  383.12
#Mann=3,-1,0
  4538.6     0.1       0  4988.3    0.07       0  4994.3     0.1       0
Bank Sta=4988.3,4994.3
Exp/Cntr=0.3,0.1

Type RM Length L Ch R = 1,600,229,229,229
BEGIN DESCRIPTION:
Mapping XS 353c3ca7
END DESCRIPTION:
XS GIS Cut Line= 5
      2070466.49     13454167.16      2070062.82     13454260.91
      2069927.40     13454354.66      2069867.51     13454563.00
      2069903.97     13454898.94
#Sta/Elev= 30
  4488.1  387.84  4530.7  386.16  4545.5  384.91  4561.5  385.27  4623.1  384.30
  4848.9  378.39  4854.2  377.76  4902.5  377.25  4918.3  376.13  4954.1  376.03
  4983.8  374.81  4989.9  375.22  4994.2  373.49  4994.7  372.69  4999.7  372.69
  5000.2  373.49  5004.8  376.19  5010.9  376.40  5033.6  376.66  5040.6  375.65
  5046.7  376.42  5055.5  375.86  5061.5  376.53  5127.5  377.76  5132.7  376.94
  5304.1  376.88  5527.4  381.37  5557.6  381.21  5589.0  382.47  5621.9  382.46
#Mann=3,-1,0
  4488.1     0.1       0  4994.2    0.07       0  5000.2     0.1       0
Bank Sta=4994.2,5000.2
Exp/Cntr=0.3,0.1

Type RM Length L Ch R = 1,371,274,274,274
BEGIN DESCRIPTION:
Mapping XS 144825c9
END DESCRIPTION:
XS GIS Cut Line= 4
      2070341.83     13454070.76      2069919.26     13454093.43
      2069786.45     13454223.64      2069882.04     13454930.74
#Sta/Elev= 30
  4485.2  384.72  4522.1  383.54  4552.1  381.54  4592.2  381.25  4682.3  378.52
  4692.3  377.69  4762.4  376.95  4872.6  374.57  4892.6  375.60  4908.0  374.74
  4919.6  375.57  4976.1  375.09  4983.3  374.75  4994.4  371.91  4994.9  371.11
  4999.9  371.11  5000.4  371.91  5004.4  372.96  5011.6  372.85  5032.7  375.09
  5046.9  375.32  5115.9  374.41  5193.6  374.64  5226.9  375.72  5343.9  376.26
  5368.2  376.92  5416.5  376.14  5494.2  376.84  5670.9  380.21  5807.9  381.66
#Mann=3,-1,0
  4485.2     0.1       0  4994.4    0.07       0  5000.4     0.1       0
Bank Sta=4994.4,5000.4
Exp/Cntr=0.3,0.1

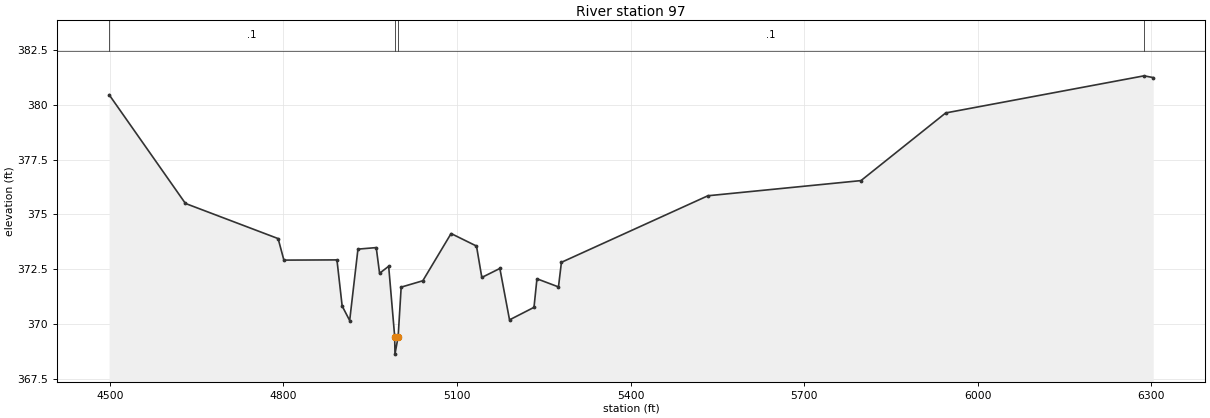
Type RM Length L Ch R = 1,97,0,0,0
BEGIN DESCRIPTION:
Mapping XS 1b4154bd
END DESCRIPTION:
XS GIS Cut Line= 4
      2070256.72     13453911.04      2069868.16     13453931.03
      2069640.43     13454062.08      2069905.58     13455184.06
#Sta/Elev= 30
  4498.6  380.45  4630.5  375.50  4790.7  373.90  4800.7  372.92  4892.4  372.93
  4901.4  370.83  4914.4  370.17  4928.7  373.42  4960.3  373.49  4966.1  372.32
  4981.8  372.64  4992.2  369.44  4992.7  368.64  4998.2  369.44  5003.4  371.69
  5040.8  371.98  5089.7  374.13  5133.6  373.56  5142.8  372.13  5174.0  372.54
  5190.7  370.20  5233.0  370.77  5238.1  372.07  5275.3  371.70  5280.4  372.82
  5533.6  375.85  5798.2  376.54  5944.6  379.62  6287.5  381.31  6303.3  381.23
#Mann=4,-1,0
  4498.6     0.1       0  4992.2    0.07       0  4998.2     0.1       0
  6287.5    0.05       0
Bank Sta=4992.2,4998.2
Exp/Cntr=0.3,0.1

Chan Stop Cuts=-1