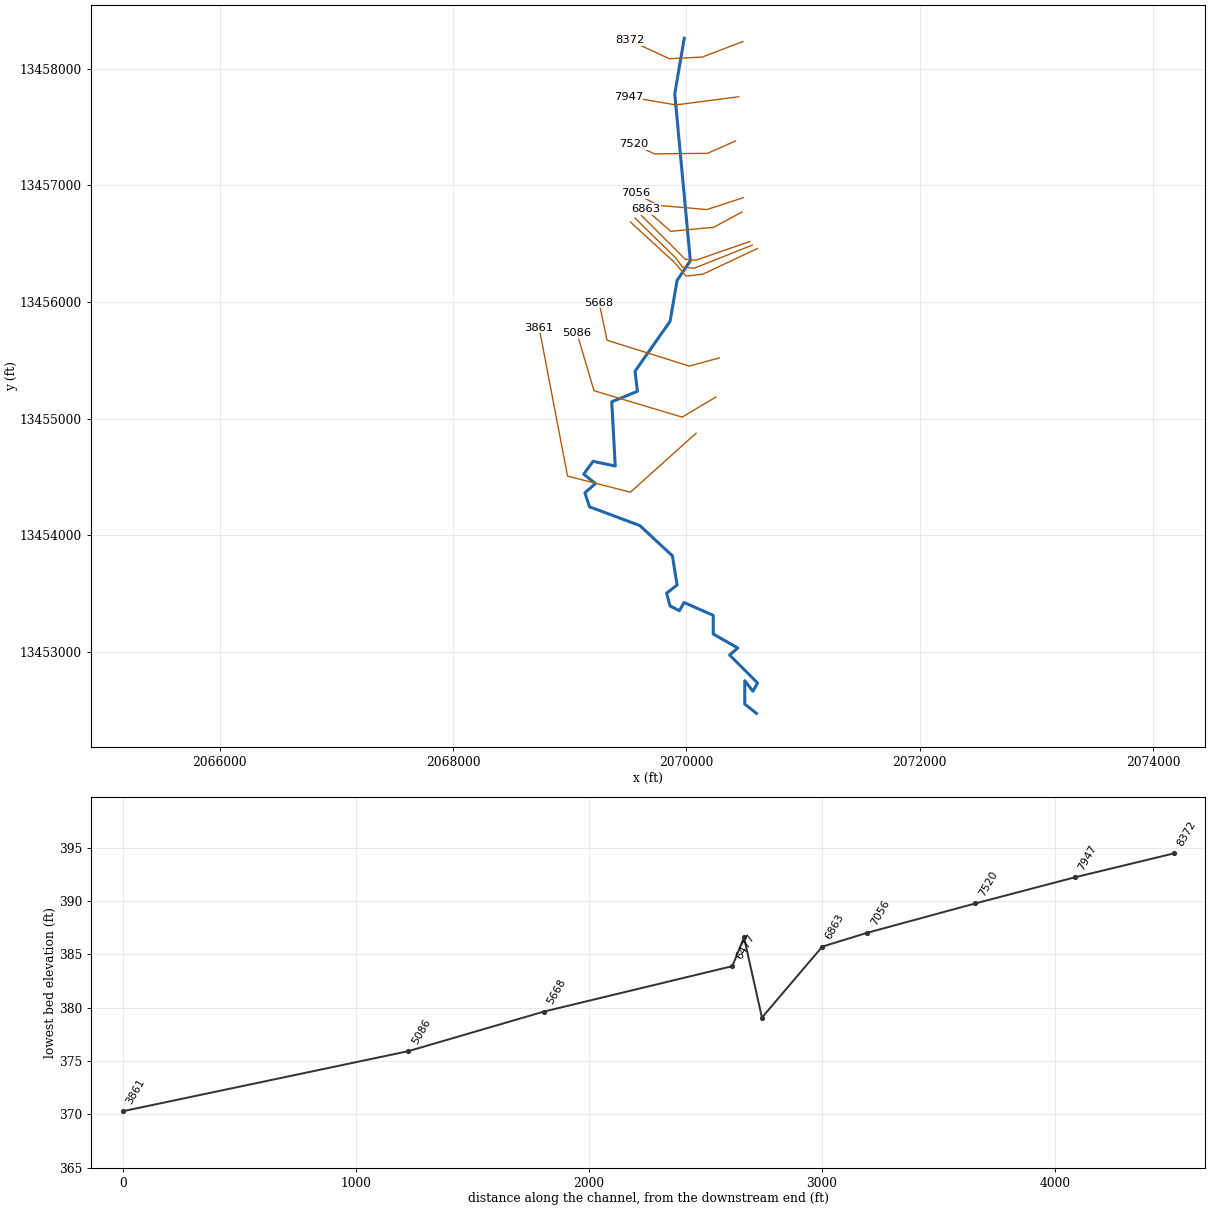
--- UNT 92 in Lagunillas Cr Wtrshd.prj (project) ---

Proj Title=UNT 92 in Lagunillas Cr Wtrshd Base Level Engineering
Current Plan=p01
Default Exp/Contr=0.3,0.1
English Units
Geom File=g01
Flow File=f01
Plan File=p01
BEGIN DESCRIPTION:
UNT 92 in Lagunillas Cr Wtrshd
END DESCRIPTION:

--- UNT 92 in Lagunillas Cr Wtrshd.p01 (plan) ---

Plan Title=Multiple Run
Short Identifier=Multiple
Geom File=g01
Flow File=f01
Subcritical Flow
K Sum by GR= 0
Std Step Tol= 0.01
Critical Tol= 0.01
Num of Std Step Trials= 20
Max Error Tol= 0.3
Flow Tol Ratio= 0.001
Split Flow NTrial= 30
Split Flow Tol= 0.02
Split Flow Ratio= 0.02
Log Output Level= 0
Friction Slope Method= 1
Unsteady Friction Slope Method= 2
Unsteady Bridges Friction Slope Method= 1
Parabolic Critical Depth
Global Vel Dist=  1 , 1 , 1
Global Log Level= 0
CheckData=True
Encroach Param= -1, 0, 0, 0
BEGIN DESCRIPTION:
Multiple Run
END DESCRIPTION:

--- UNT 92 in Lagunillas Cr Wtrshd.f01 (steady flow) ---

Flow Title=Multiple
Number of Profiles=7
Profile Names=10-year,25-year,50-year,1pct_min,100-year,1pct_plu,500-year
River Rch & RM= UNT 92 in Laguni,Reach-1,8372
     132     176     211     126     252     503     366
Boundary for River Rch & Prof#=UNT 92 in Laguni,Reach-1,1
Up Type=0
Dn Type=3
Dn Slope=0.005
Boundary for River Rch & Prof#=UNT 92 in Laguni,Reach-1,2
Up Type=0
Dn Type=3
Dn Slope=0.005
Boundary for River Rch & Prof#=UNT 92 in Laguni,Reach-1,3
Up Type=0
Dn Type=3
Dn Slope=0.005
Boundary for River Rch & Prof#=UNT 92 in Laguni,Reach-1,4
Up Type=0
Dn Type=3
Dn Slope=0.005
Boundary for River Rch & Prof#=UNT 92 in Laguni,Reach-1,5
Up Type=0
Dn Type=3
Dn Slope=0.005
Boundary for River Rch & Prof#=UNT 92 in Laguni,Reach-1,6
Up Type=0
Dn Type=3
Dn Slope=0.005
Boundary for River Rch & Prof#=UNT 92 in Laguni,Reach-1,7
Up Type=0
Dn Type=3
Dn Slope=0.005

--- UNT 92 in Lagunillas Cr Wtrshd.g01 (geometry) ---

Geom Title=Existing Conditions

River Reach=UNT 92 in Laguni,Reach-1
Reach XY= 30
      2069982.20     13458259.63      2069900.80     13457784.54
      2070034.41     13456353.82      2069920.80     13456184.54
      2069860.80     13455834.54      2069560.45     13455406.77
      2069580.80     13455234.54      2069360.80     13455144.54
      2069390.80     13454594.54      2069200.80     13454634.54
      2069120.80     13454524.54      2069220.80     13454444.54
      2069130.80     13454364.54      2069170.80     13454244.54
      2069600.80     13454084.54      2069880.80     13453824.54
      2069920.80     13453574.54      2069830.80     13453504.54
      2069860.80     13453394.54      2069940.80     13453354.54
      2069980.80     13453424.54      2070230.80     13453314.54
      2070230.80     13453154.54      2070440.80     13453034.54
      2070370.80     13452974.54      2070610.80     13452734.54
      2070570.80     13452664.54      2070500.80     13452754.54
      2070500.80     13452554.54      2070600.80     13452474.54

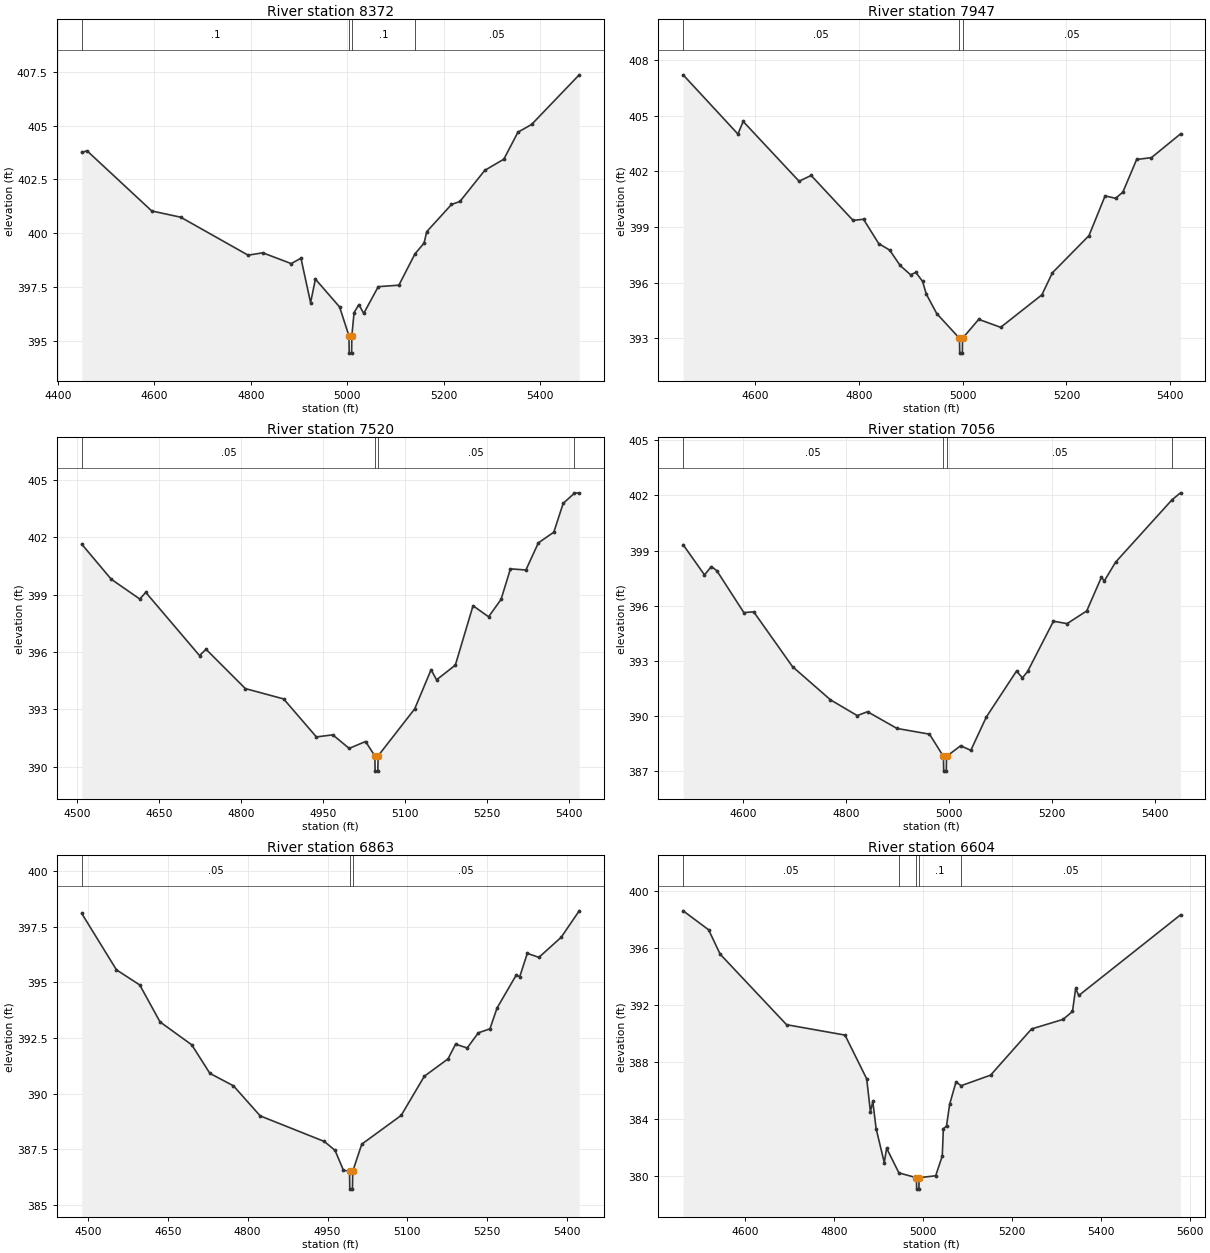
Type RM Length L Ch R = 1,8372,425,425,425
BEGIN DESCRIPTION:
Mapping XS a6245095
END DESCRIPTION:
XS GIS Cut Line= 4
      2070484.55     13458232.14      2070137.87     13458099.53
      2069854.89     13458084.77      2069513.20     13458242.55
#Sta/Elev= 30
  4449.8  403.75  4460.6  403.83  4594.8  401.04  4654.9  400.75  4794.5  398.99
  4824.9  399.10  4883.9  398.60  4904.0  398.85  4924.0  396.79  4934.0  397.88
  4984.1  396.59  5003.5  395.25  5004.0  394.45  5009.0  394.45  5009.5  395.25
  5014.1  396.33  5024.1  396.70  5034.1  396.29  5064.2  397.53  5107.0  397.60
  5140.3  399.05  5159.2  399.55  5164.7  400.08  5216.0  401.34  5233.5  401.48
  5284.9  402.92  5324.5  403.44  5353.7  404.69  5382.1  405.05  5480.7  407.35
#Mann=4,-1,0
  4449.8     0.1       0  5003.5    0.07       0  5009.5     0.1       0
  5140.3    0.05       0
Bank Sta=5003.5,5009.5
Exp/Cntr=0.3,0.1

Type RM Length L Ch R = 1,7947,427,427,427
BEGIN DESCRIPTION:
Mapping XS b81b165e
END DESCRIPTION:
XS GIS Cut Line= 3
      2070449.70     13457758.93      2069910.31     13457689.09
      2069501.63     13457758.94
#Sta/Elev= 30
  4461.4  407.20  4567.0  404.01  4577.1  404.69  4684.8  401.47  4708.1  401.78
  4788.8  399.36  4809.0  399.42  4838.3  398.11  4859.4  397.76  4879.6  396.93
  4899.7  396.43  4909.8  396.56  4922.7  396.08  4930.0  395.39  4950.1  394.34
  4993.9  393.01  4994.4  392.21  4999.4  392.21  4999.9  393.01  5031.0  394.03
  5073.3  393.60  5152.7  395.35  5173.0  396.54  5243.5  398.54  5274.5  400.68
  5294.7  400.55  5308.7  400.88  5335.3  402.64  5363.8  402.74  5419.9  404.02
#Mann=3,-1,0
  4461.4    0.05       0  4993.9    0.03       0  4999.9    0.05       0
Bank Sta=4993.9,4999.9
Exp/Cntr=0.3,0.1

Type RM Length L Ch R = 1,7520,464,464,464
BEGIN DESCRIPTION:
Mapping XS 4ad2ed53
END DESCRIPTION:
XS GIS Cut Line= 4
      2070422.03     13457380.56      2070182.14     13457274.01
      2069726.41     13457269.67      2069552.30     13457351.91
#Sta/Elev= 30
  4508.8  401.64  4562.6  399.81  4615.0  398.77  4625.9  399.12  4724.4  395.81
  4736.3  396.14  4808.4  394.08  4878.4  393.54  4938.4  391.55  4968.4  391.66
  4998.4  390.95  5028.4  391.31  5045.4  390.56  5045.9  389.76  5050.9  389.76
  5051.4  390.56  5118.4  393.02  5148.4  395.07  5158.4  394.54  5192.8  395.31
  5225.2  398.42  5253.7  397.84  5276.5  398.75  5293.7  400.35  5322.0  400.29
  5344.8  401.71  5373.1  402.27  5390.3  403.78  5410.8  404.31  5419.6  404.33
#Mann=4,-1,0
  4508.8    0.05       0  5045.4    0.03       0  5051.4    0.05       0
  5410.8     0.1       0
Bank Sta=5045.4,5051.4
Exp/Cntr=0.3,0.1

Type RM Length L Ch R = 1,7056,193,193,193
BEGIN DESCRIPTION:
Mapping XS 4621a324
END DESCRIPTION:
XS GIS Cut Line= 4
      2070487.15     13456893.60      2070176.07     13456792.24
      2069762.00     13456827.83      2069562.75     13456930.02
#Sta/Elev= 30
  4483.6  399.32  4525.1  397.68  4538.5  398.13  4549.0  397.91  4601.6  395.63
  4620.8  395.67  4696.2  392.69  4769.8  390.89  4821.9  390.03  4842.0  390.24
  4899.3  389.33  4962.4  389.02  4989.5  387.81  4990.0  387.01  4995.0  387.01
  4995.5  387.81  5022.9  388.39  5042.7  388.14  5072.8  389.95  5131.5  392.45
  5143.1  392.08  5153.1  392.43  5203.3  395.16  5229.9  395.03  5268.0  395.72
  5296.5  397.55  5302.1  397.35  5324.3  398.38  5434.0  401.77  5450.3  402.14
#Mann=4,-1,0
  4483.6    0.05       0  4989.5    0.03       0  4995.5    0.05       0
  5434.0     0.1       0
Bank Sta=4989.5,4995.5
Exp/Cntr=0.3,0.1

Type RM Length L Ch R = 1,6863,259,259,259
BEGIN DESCRIPTION:
Mapping XS b571bd9a
END DESCRIPTION:
XS GIS Cut Line= 4
      2070476.77     13456771.22      2070234.23     13456640.33
      2069866.17     13456605.60      2069649.31     13456796.63
#Sta/Elev= 30
  4488.4  398.09  4553.5  395.56  4597.3  394.88  4635.4  393.22  4695.0  392.19
  4729.0  390.91  4773.3  390.35  4823.5  389.00  4944.0  387.85  4964.1  387.45
  4979.8  386.56  4991.3  386.51  4991.8  385.71  4996.8  385.71  4997.3  386.51
  5014.3  387.73  5088.3  389.02  5131.8  390.78  5176.3  391.56  5190.5  392.22
  5212.3  392.05  5233.2  392.73  5255.0  392.91  5268.5  393.85  5304.3  395.32
  5311.0  395.25  5325.2  396.30  5347.0  396.12  5388.8  397.02  5422.7  398.21
#Mann=3,-1,0
  4488.4    0.05       0  4991.3    0.03       0  4997.3    0.05       0
Bank Sta=4991.3,4997.3
Exp/Cntr=0.3,0.1

Type RM Length L Ch R = 1,6604,77,77,77
BEGIN DESCRIPTION:
Mapping XS 5d86ac9a
END DESCRIPTION:
XS GIS Cut Line= 4
      2070544.44     13456518.59      2070078.84     13456357.34
      2069990.30     13456366.89      2069612.13     13456745.19
#Sta/Elev= 30
  4461.4  398.59  4518.6  397.26  4544.5  395.55  4693.6  390.60  4824.8  389.87
  4873.5  386.80  4881.9  384.49  4887.2  385.22  4894.7  383.30  4913.0  380.92
  4918.3  381.93  4945.8  380.20  4985.2  379.86  4985.7  379.06  4990.7  379.06
  4991.2  379.86  5028.4  380.00  5043.2  381.39  5045.6  383.30  5052.7  383.49
  5059.7  385.01  5073.9  386.57  5085.7  386.32  5151.7  387.06  5243.6  390.30
  5314.3  390.97  5335.5  391.53  5342.6  393.14  5349.7  392.65  5578.1  398.31
#Mann=5,-1,0
  4461.4    0.05       0  4945.8     0.1       0  4985.2    0.07       0
  4991.2     0.1       0  5085.7    0.05       0
Bank Sta=4985.2,4991.2
Exp/Cntr=0.3,0.1

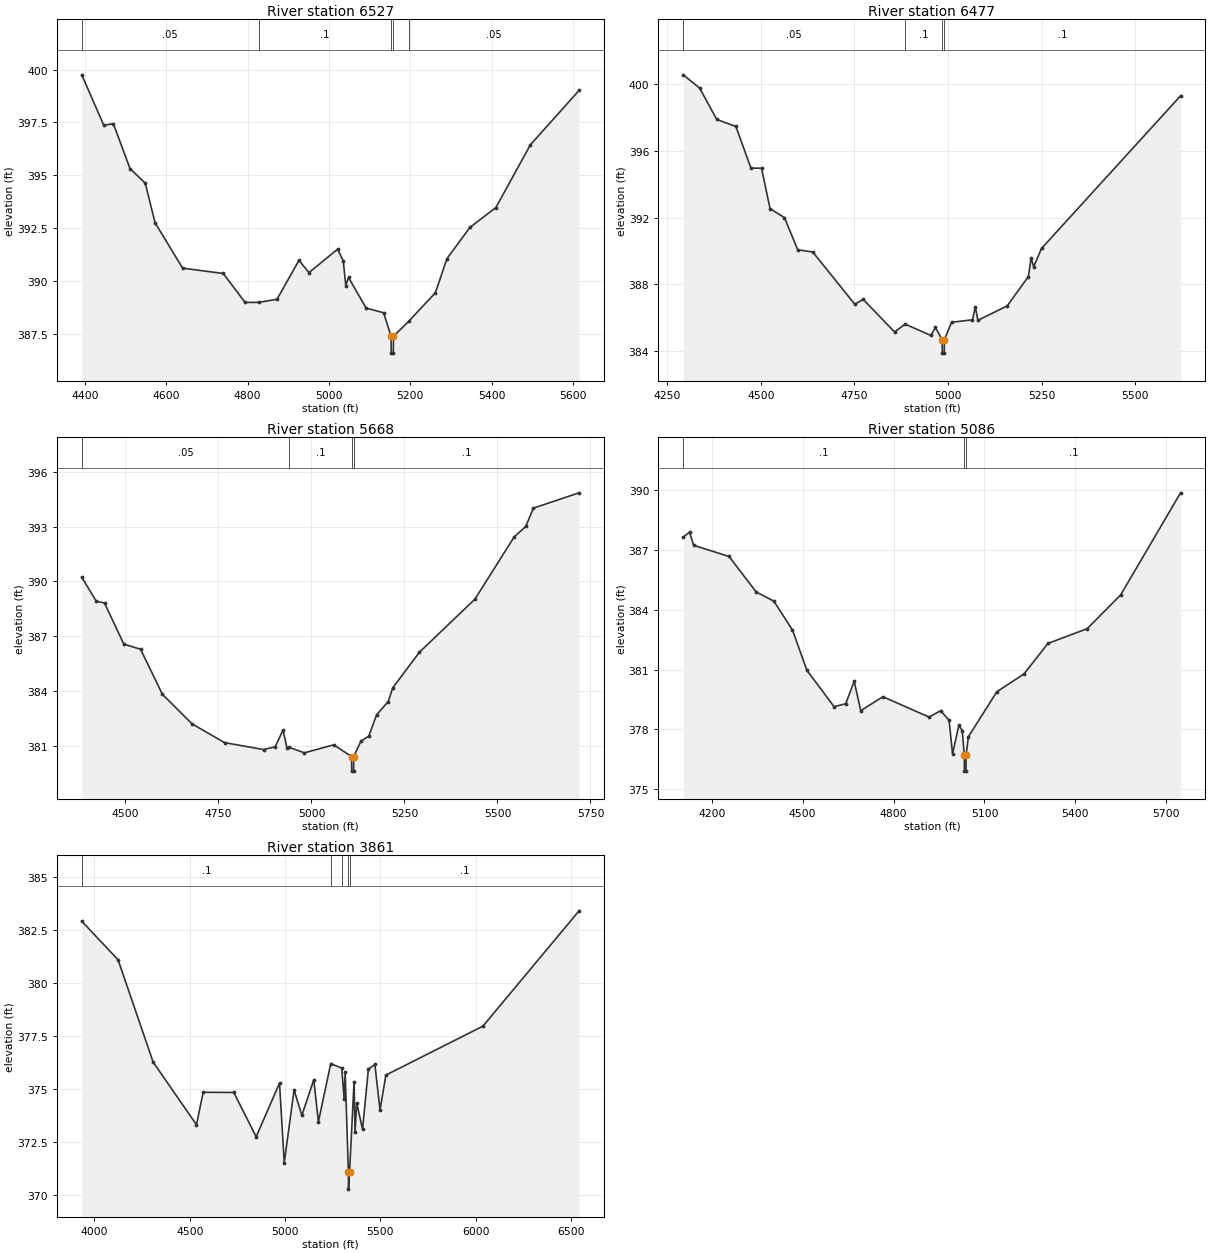
Type RM Length L Ch R = 1,6527,50,50,50
BEGIN DESCRIPTION:
Mapping XS c7b57f46
END DESCRIPTION:
XS GIS Cut Line= 5
      2070565.27     13456487.34      2070067.56     13456289.63
      2069966.86     13456300.05      2069909.57     13456377.31
      2069560.08     13456719.11
#Sta/Elev= 30
  4392.8  399.75  4446.9  397.36  4470.3  397.44  4511.4  395.31  4548.6  394.63
  4572.9  392.75  4640.6  390.60  4740.3  390.35  4794.2  388.98  4827.5  388.98
  4872.5  389.13  4926.5  390.97  4951.0  390.39  5021.4  391.50  5035.3  390.94
  5041.5  389.78  5048.2  390.16  5091.6  388.71  5134.4  388.49  5152.7  387.38
  5153.2  386.58  5158.2  386.58  5158.7  387.38  5195.9  388.08  5261.7  389.44
  5290.0  391.05  5346.5  392.53  5410.3  393.47  5495.1  396.44  5614.6  399.01
#Mann=5,-1,0
  4392.8    0.05       0  4827.5     0.1       0  5152.7    0.07       0
  5158.7     0.1       0  5195.9    0.05       0
Bank Sta=5152.7,5158.7
Exp/Cntr=0.3,0.1

Type RM Length L Ch R = 1,6477,809,809,809
BEGIN DESCRIPTION:
Mapping XS e9ab2945
END DESCRIPTION:
XS GIS Cut Line= 5
      2070609.53     13456458.69      2070141.34     13456238.42
      2069997.25     13456221.92      2069898.29     13456339.11
      2069521.04     13456685.23
#Sta/Elev= 30
  4293.2  400.58  4337.0  399.78  4382.6  397.90  4433.7  397.48  4473.8  394.98
  4502.1  394.98  4524.9  392.55  4563.4  392.01  4598.8  390.08  4638.9  389.95
  4751.3  386.81  4773.4  387.11  4857.3  385.15  4885.7  385.62  4954.3  384.94
  4966.5  385.42  4984.4  384.68  4984.9  383.88  4989.9  383.88  4990.4  384.68
  5009.4  385.73  5065.4  385.88  5073.2  386.66  5079.7  385.85  5157.9  386.71
  5214.6  388.47  5222.0  389.59  5228.8  389.06  5249.7  390.16  5621.0  399.32
#Mann=4,-1,0
  4293.2    0.05       0  4885.7     0.1       0  4984.4    0.07       0
  4990.4     0.1       0
Bank Sta=4984.4,4990.4
Exp/Cntr=0.3,0.1

Type RM Length L Ch R = 1,5668,582,582,582
BEGIN DESCRIPTION:
Mapping XS 403f203d
END DESCRIPTION:
XS GIS Cut Line= 4
      2070284.01     13455521.20      2070026.22     13455450.89
      2069320.49     13455672.24      2069252.78     13455995.18
#Sta/Elev= 30
  4382.5  390.23  4421.4  388.92  4443.7  388.82  4495.5  386.57  4540.6  386.29
  4599.1  383.83  4678.7  382.21  4766.3  381.18  4871.1  380.80  4902.5  380.95
  4923.5  381.87  4934.0  380.91  4940.1  380.92  4981.0  380.62  5059.7  381.06
  5107.7  380.42  5108.2  379.62  5113.2  379.62  5113.7  380.42  5133.1  381.27
  5154.0  381.53  5175.0  382.70  5206.4  383.43  5218.5  384.18  5290.3  386.13
  5439.3  389.03  5545.4  392.45  5576.1  393.01  5596.5  394.01  5719.3  394.85
#Mann=4,-1,0
  4382.5    0.05       0  4940.1     0.1       0  5107.7    0.07       0
  5113.7     0.1       0
Bank Sta=5107.7,5113.7
Exp/Cntr=0.3,0.1

Type RM Length L Ch R = 1,5086,1225,1225,1225
BEGIN DESCRIPTION:
Mapping XS e3f8ce67
END DESCRIPTION:
XS GIS Cut Line= 4
      2070252.77     13455185.26      2069963.72     13455013.39
      2069208.51     13455239.95      2069062.67     13455734.75
#Sta/Elev= 30
  4106.3  387.64  4127.0  387.89  4140.3  387.23  4257.2  386.67  4346.8  384.89
  4405.2  384.43  4466.5  382.98  4514.3  380.96  4603.9  379.14  4642.2  379.29
  4670.1  380.41  4691.8  378.94  4764.9  379.64  4917.2  378.62  4955.4  378.94
  4983.3  378.45  4994.6  376.77  5015.5  378.21  5026.8  377.94  5033.4  376.71
  5033.9  375.91  5038.9  375.91  5039.4  376.71  5046.8  377.63  5140.8  379.89
  5230.3  380.78  5309.3  382.31  5438.8  383.05  5549.2  384.74  5746.9  389.86
#Mann=3,-1,0
  4106.3     0.1       0  5033.4    0.07       0  5039.4     0.1       0
Bank Sta=5033.4,5039.4
Exp/Cntr=0.3,0.1

Type RM Length L Ch R = 1,3861,0,0,0
BEGIN DESCRIPTION:
Mapping XS da81f64e
END DESCRIPTION:
XS GIS Cut Line= 4
      2070083.54     13454875.39      2069521.01     13454370.16
      2068981.95     13454508.18      2068738.38     13455779.91
#Sta/Elev= 30
  3934.0  382.92  4124.3  381.10  4308.4  376.27  4535.4  373.32  4570.6  374.85
  4731.1  374.84  4848.4  372.75  4970.8  375.28  4995.7  371.53  5047.2  374.96
  5088.0  373.76  5150.5  375.44  5174.8  373.46  5239.4  376.20  5297.1  375.99
  5309.8  374.51  5314.9  375.82  5332.0  371.08  5332.5  370.28  5338.0  371.08
  5361.8  375.35  5366.9  372.99  5375.7  374.34  5406.2  373.10  5436.8  375.94
  5471.0  376.16  5497.9  374.01  5528.4  375.66  6037.5  377.97  6541.4  383.41
#Mann=5,-1,0
  3934.0     0.1       0  5239.4    0.12       0  5297.1     0.1       0
  5332.0    0.07       0  5338.0     0.1       0
Bank Sta=5332,5338
Exp/Cntr=0.3,0.1

Chan Stop Cuts=-1