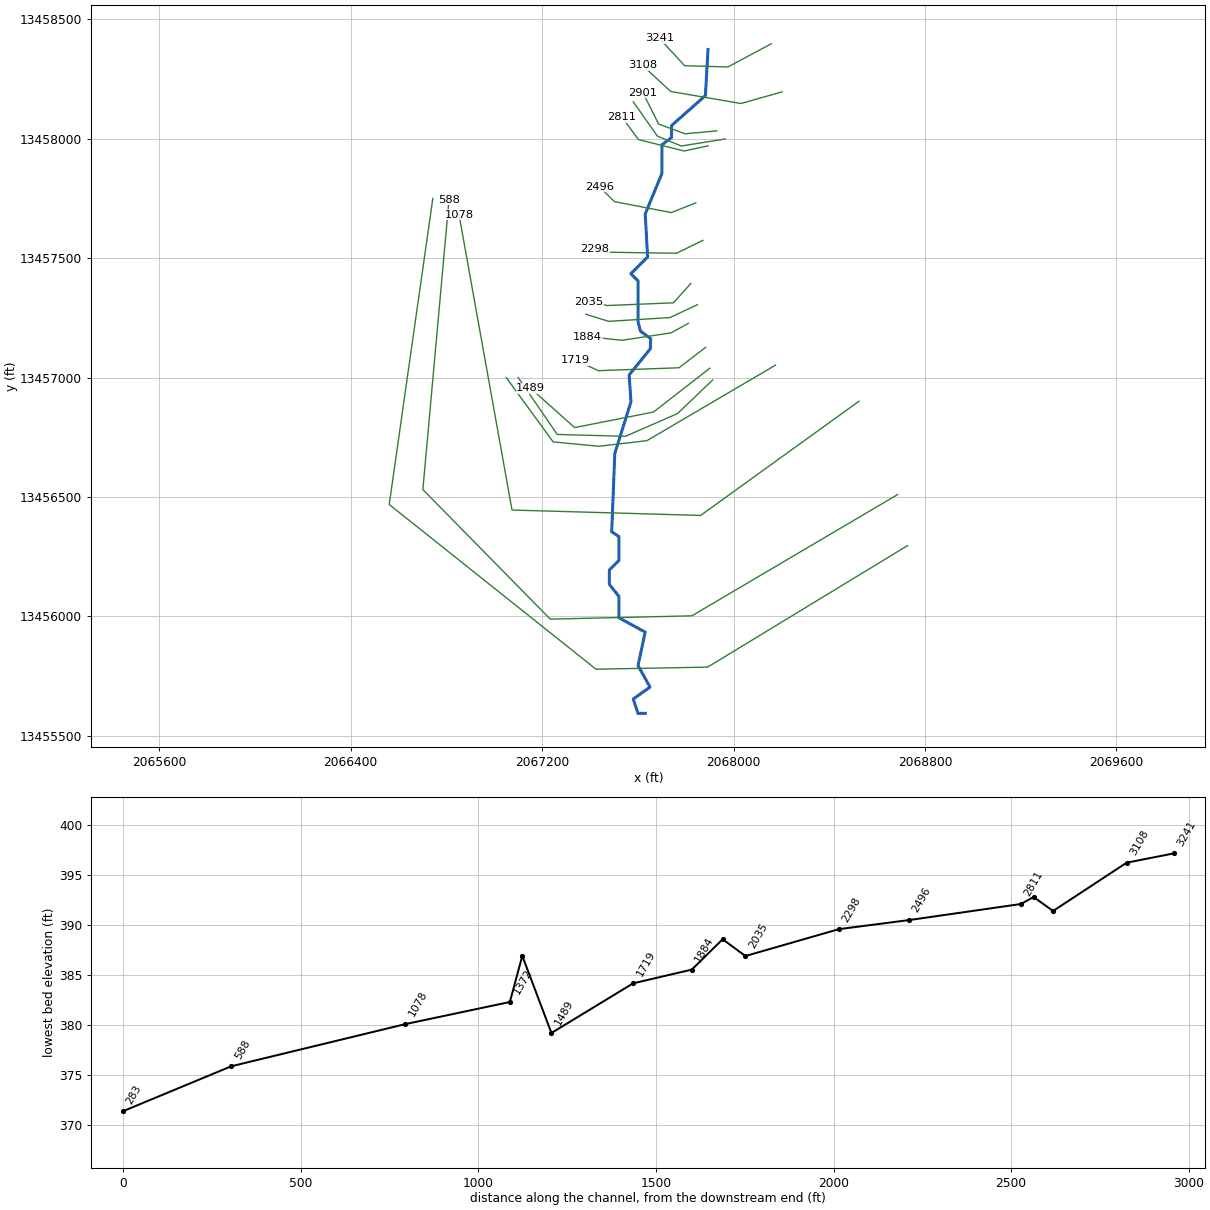
--- UNT 93 in Lagunillas Cr Wtrshd.prj (project) ---

Proj Title=UNT 93 in Lagunillas Cr Wtrshd Base Level Engineering
Current Plan=p01
Default Exp/Contr=0.3,0.1
English Units
Geom File=g01
Flow File=f01
Plan File=p01
Y Axis Title=Elevation
X Axis Title(PF)=Main Channel Distance
X Axis Title(XS)=Station
BEGIN DESCRIPTION:
UNT 93 in Lagunillas Cr Wtrshd
END DESCRIPTION:
DSS Export Rating Curves= 0
DSS Export Rating Curve Sorted= 0
DSS Export Volume Flow Curves= 0
DXF OffsetX= 0
DXF OffsetY= 0
DXF ScaleX= 1
DXF ScaleY= 10

--- UNT 93 in Lagunillas Cr Wtrshd.p01 (plan) ---

Plan Title=Multiple Run
Short Identifier=Multiple
Geom File=g01
Flow File=f01
Subcritical Flow
K Sum by GR= 0
Std Step Tol= 0.01
Critical Tol= 0.01
Num of Std Step Trials= 20
Max Error Tol= 0.3
Flow Tol Ratio= 0.001
Split Flow NTrial= 30
Split Flow Tol= 0.02
Split Flow Ratio= 0.02
Log Output Level= 0
Friction Slope Method= 1
Unsteady Friction Slope Method= 2
Unsteady Bridges Friction Slope Method= 1
Parabolic Critical Depth
Global Vel Dist=  1 , 1 , 1
Global Log Level= 0
CheckData=True
Encroach Param= -1, 0, 0, 0
BEGIN DESCRIPTION:
Multiple Run
END DESCRIPTION:

--- UNT 93 in Lagunillas Cr Wtrshd.f01 (steady flow) ---

Flow Title=Multiple
Number of Profiles=7
Profile Names=10-year,25-year,50-year,1pct_min,100-year,1pct_plu,500-year
River Rch & RM= UNT 93 in Laguni,Reach-1,3241
      62      79      92      54     107     214     147
Boundary for River Rch & Prof#=UNT 93 in Laguni,Reach-1,1
Up Type=0
Dn Type=3
Dn Slope=0.005
Boundary for River Rch & Prof#=UNT 93 in Laguni,Reach-1,2
Up Type=0
Dn Type=3
Dn Slope=0.005
Boundary for River Rch & Prof#=UNT 93 in Laguni,Reach-1,3
Up Type=0
Dn Type=3
Dn Slope=0.005
Boundary for River Rch & Prof#=UNT 93 in Laguni,Reach-1,4
Up Type=0
Dn Type=3
Dn Slope=0.005
Boundary for River Rch & Prof#=UNT 93 in Laguni,Reach-1,5
Up Type=0
Dn Type=3
Dn Slope=0.005
Boundary for River Rch & Prof#=UNT 93 in Laguni,Reach-1,6
Up Type=0
Dn Type=3
Dn Slope=0.005
Boundary for River Rch & Prof#=UNT 93 in Laguni,Reach-1,7
Up Type=0
Dn Type=3
Dn Slope=0.005

--- UNT 93 in Lagunillas Cr Wtrshd.g01 (geometry) ---

Geom Title=Existing Conditions
Program Version=5.05

River Reach=UNT 93 in Laguni,Reach-1
Reach XY= 30
      2067893.27     13458373.28      2067882.42     13458180.13
       2067740.8     13458054.54       2067740.8     13458004.54
       2067700.8     13457974.54       2067700.8     13457854.54
       2067630.8     13457684.54       2067640.8     13457504.54
       2067570.8     13457434.54       2067600.8     13457404.54
       2067600.8     13457234.54       2067610.8     13457194.54
      2067653.81     13457162.84      2067652.08     13457120.31
      2067563.54     13457010.93      2067571.35     13456898.96
      2067503.64     13456681.94       2067490.8     13456354.54
       2067520.8     13456334.54       2067520.8     13456234.54
       2067480.8     13456194.54       2067480.8     13456134.54
       2067520.8     13456084.54       2067520.8     13455994.54
       2067630.8     13455934.54       2067600.8     13455794.54
       2067650.8     13455704.54       2067580.8     13455654.54
       2067600.8     13455594.54       2067630.8     13455594.54

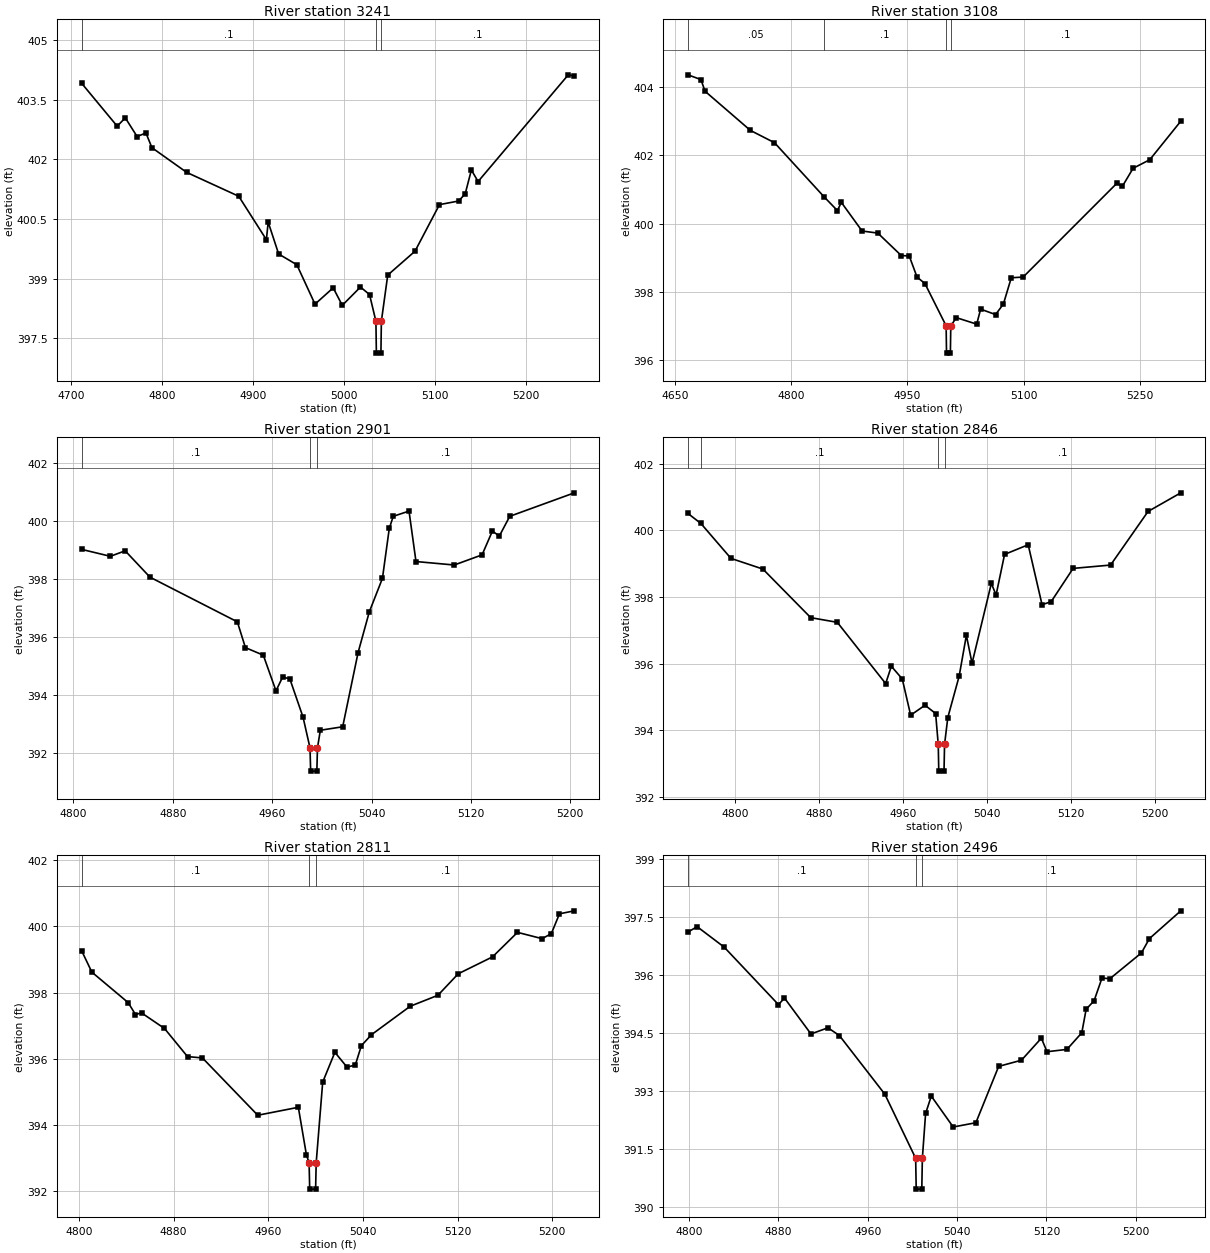
Type RM Length L Ch R = 1 ,3241    ,133,133,133
BEGIN DESCRIPTION:
UNT 93 in Lagunillas Cr Wtrshd 6.0
END DESCRIPTION:
XS GIS Cut Line= 4
      2068157.42     13458396.93      2067976.38     13458299.98
      2067795.75     13458305.05      2067689.96     13458419.74
#Sta/Elev= 30
  4711.2  403.91  4750.4  402.83  4759.3  403.04  4772.3  402.57    4782  402.66
  4788.6  402.29  4826.8  401.67  4884.1  401.07  4914.5  399.98  4916.5  400.42
    4928  399.62    4948  399.35    4968  398.36    4988  398.77    4998  398.33
    5018  398.79    5028   398.6    5035  397.93  5035.5  397.13  5040.5  397.13
    5041  397.93    5048  399.09    5078  399.69  5104.9  400.86  5125.9  400.95
  5133.2  401.13    5140  401.73  5147.4  401.44  5246.6  404.12  5253.3  404.09
#Mann= 3 ,-1 , 0
  4711.2      .1       0    5035     .07       0    5041      .1       0
Bank Sta=5035,5041
XS Rating Curve= 0 ,0
Exp/Cntr=0.3,0.1

Type RM Length L Ch R = 1 ,3108    ,207,207,207
BEGIN DESCRIPTION:
Mapping XS 8cb87a3c
END DESCRIPTION:
XS GIS Cut Line= 4
      2068202.61     13458195.56      2068030.72     13458146.95
      2067737.32     13458197.29       2067619.6     13458306.36
#Sta/Elev= 30
  4666.4  404.36  4683.2  404.22  4688.4  403.88  4747.1  402.73  4778.2  402.37
  4842.4  400.78  4859.5  400.38  4864.6  400.62  4891.4  399.78  4911.7  399.72
  4942.1  399.06  4952.3  399.05  4962.4  398.43  4972.6  398.24    5000     397
  5000.5   396.2  5005.5   396.2    5006     397  5013.2  397.24  5039.5  397.05
  5044.6  397.49  5063.9  397.33    5074  397.64  5084.2  398.41  5099.5  398.43
  5220.6  401.18  5227.7  401.09  5241.6  401.62  5263.1  401.87  5303.2     403
#Mann= 4 ,-1 , 0
  4666.4     .05       0  4842.4      .1       0    5000     .07       0
    5006      .1       0
Bank Sta=5000,5006
XS Rating Curve= 0 ,0
Exp/Cntr=0.3,0.1

Type RM Length L Ch R = 1 ,2901    ,55,55,55
BEGIN DESCRIPTION:
Mapping XS 76cc6a26
END DESCRIPTION:
XS GIS Cut Line= 4
      2067929.91      13458032.4      2067797.13     13458020.25
      2067686.89     13458061.05      2067621.68     13458191.47
#Sta/Elev= 30
  4806.6  399.02  4829.8  398.78  4841.7  398.97  4861.7  398.06    4932  396.52
  4938.5  395.63  4952.9  395.37  4963.1  394.14  4968.4  394.61  4974.2  394.56
  4984.9  393.23  4990.5  392.17    4991  391.37    4996  391.37  4996.5  392.17
  4998.8  392.78  5016.8   392.9  5029.2  395.46  5038.2  396.86  5048.8  398.02
  5054.3  399.74  5057.5  400.16  5070.2  400.34  5075.8   398.6  5106.6  398.48
    5129  398.83  5137.3  399.65  5142.9  399.48  5151.3  400.16  5203.3  400.97
#Mann= 3 ,-1 , 0
  4806.6      .1       0  4990.5     .07       0  4996.5      .1       0
Bank Sta=4990.5,4996.5
XS Rating Curve= 0 ,0
Exp/Cntr=0.3,0.1

Type RM Length L Ch R = 1 ,2846    ,35,35,35
BEGIN DESCRIPTION:
Mapping XS 804a5b59
END DESCRIPTION:
XS GIS Cut Line= 4
      2067965.49     13457998.54       2067781.5     13457969.04
      2067681.68      13458010.7      2067580.98     13458153.94
#Sta/Elev= 30
  4755.4  400.51  4767.7  400.21  4796.4  399.16  4826.8  398.84  4872.4  397.38
  4897.7  397.24  4943.8   395.4  4949.2  395.92  4959.6  395.54  4967.6  394.45
  4981.3  394.75  4991.4   394.5  4993.9  393.57  4994.4  392.77  4999.4  392.77
  4999.9  393.57    5003  394.38  5013.8  395.62  5020.7  396.85  5026.1  396.01
  5044.5  398.41    5049  398.06  5057.1  399.28  5079.6  399.57  5092.8  397.77
  5101.5  397.86  5122.4  398.86  5158.1  398.96  5193.8  400.57    5225  401.13
#Mann= 4 ,-1 , 0
  4755.4     .05       0  4767.7      .1       0  4993.9     .07       0
  4999.9      .1       0
Bank Sta=4993.9,4999.9
XS Rating Curve= 0 ,0
Exp/Cntr=0.3,0.1

Type RM Length L Ch R = 1 ,2811    ,315,315,315
BEGIN DESCRIPTION:
Mapping XS baa42be8
END DESCRIPTION:
XS GIS Cut Line= 4
      2067893.51     13457969.91      2067793.66      13457948.2
      2067602.68     13457995.94      2067532.91     13458090.69
#Sta/Elev= 30
  4802.1  399.27  4810.8  398.62  4841.5   397.7  4847.7  397.34  4852.8  397.39
  4872.2  396.92  4891.7  396.07  4904.3  396.03  4951.1   394.3  4985.4  394.54
  4992.3  393.09  4994.5  392.87    4995  392.07    5000  392.07  5000.5  392.87
    5006   395.3  5016.3   396.2  5026.6  395.75  5033.6  395.82  5038.7   396.4
  5047.2  396.73    5080  397.59  5103.4  397.92  5120.6  398.57  5149.6  399.08
  5170.7  399.82  5191.5  399.63  5199.3  399.78  5206.2  400.38  5218.8  400.47
#Mann= 3 ,-1 , 0
  4802.1      .1       0  4994.5     .07       0  5000.5      .1       0
Bank Sta=4994.5,5000.5
XS Rating Curve= 0 ,0
Exp/Cntr=0.3,0.1

Type RM Length L Ch R = 1 ,2496    ,198,198,198
BEGIN DESCRIPTION:
Mapping XS 44c2b500
END DESCRIPTION:
XS GIS Cut Line= 4
      2067842.23     13457731.17      2067739.84     13457690.39
      2067501.99      13457736.4      2067439.32     13457799.07
#Sta/Elev= 30
  4799.1  397.12  4807.3  397.26  4831.5  396.73  4880.1  395.24  4885.5  395.41
  4909.2  394.48  4924.4  394.64  4934.6  394.44  4975.3  392.92  5002.9  391.26
  5003.4  390.46  5008.4  390.46  5008.9  391.26  5011.8  392.42  5016.9  392.87
  5036.5  392.07  5056.8  392.18  5077.2  393.64  5097.6   393.8  5115.4  394.37
  5120.5  394.02  5138.3  394.08  5151.6  394.51  5155.5  395.12  5162.6  395.34
  5169.7  395.93  5176.7  395.91    5205  396.58  5212.1  396.95  5240.2  397.67
#Mann= 3 ,-1 , 0
  4799.1      .1       0  5002.9     .07       0  5008.9      .1       0
Bank Sta=5002.9,5008.9
XS Rating Curve= 0 ,0
Exp/Cntr=0.3,0.1

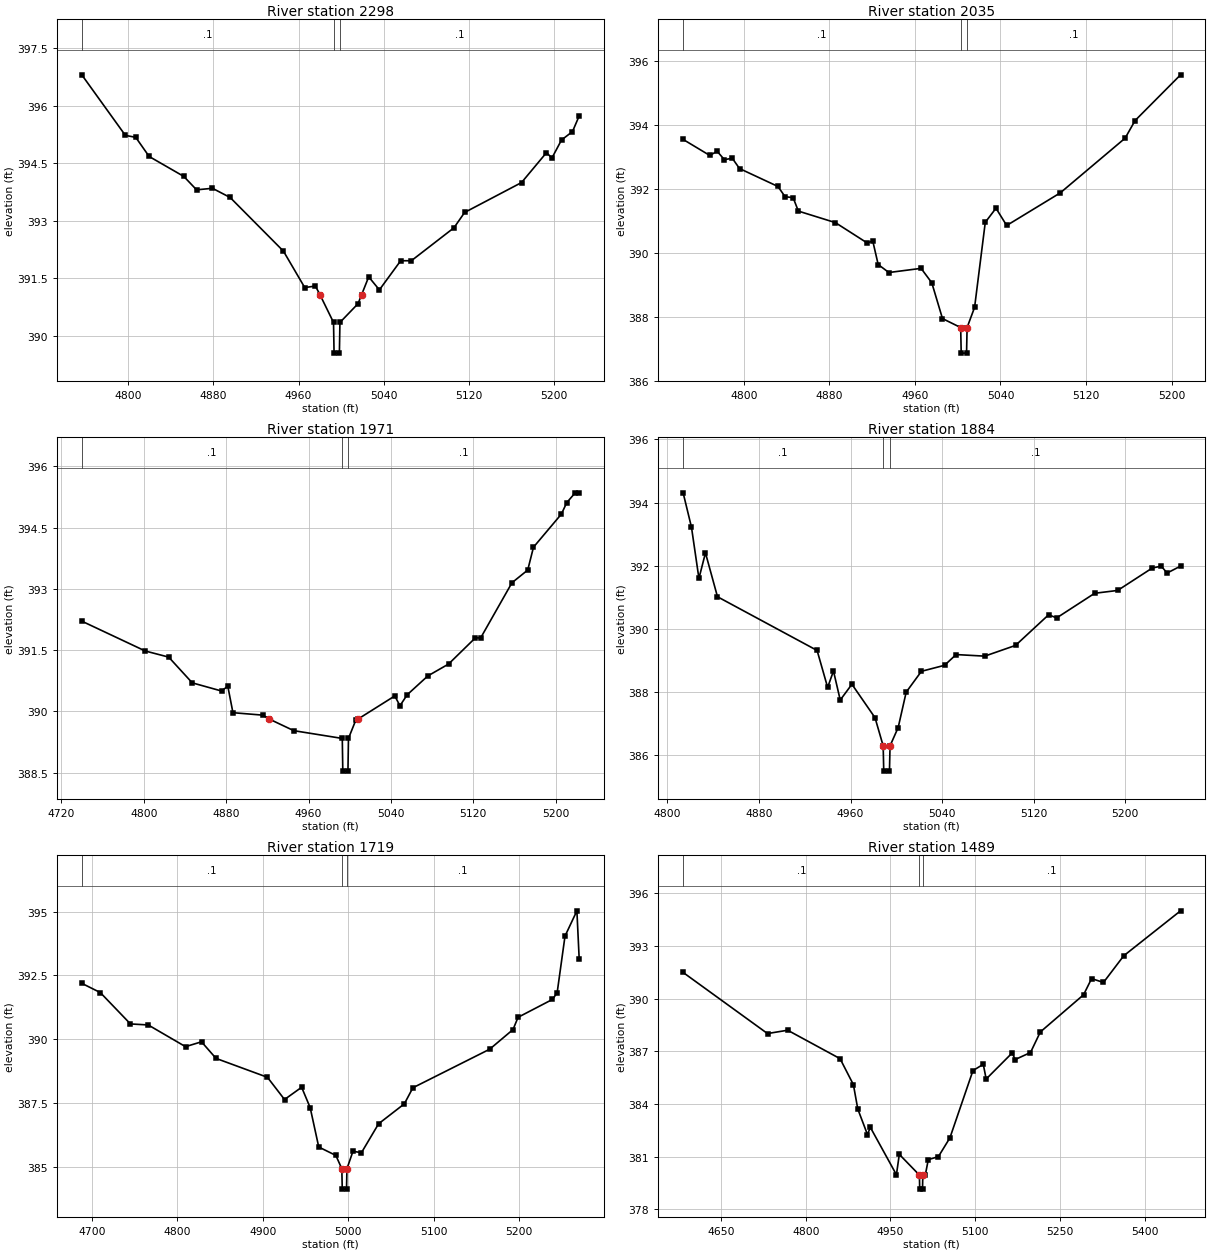
Type RM Length L Ch R = 1 ,2298    ,263,263,263
BEGIN DESCRIPTION:
Mapping XS e57a9d6b
END DESCRIPTION:
XS GIS Cut Line= 4
      2067871.75     13457574.06      2067761.54     13457520.25
      2067471.61     13457524.59      2067418.85      13457536.5
#Sta/Elev= 30
  4756.6  396.81  4797.5  395.23  4807.2  395.18  4819.8  394.68  4852.3  394.16
  4864.3  393.81  4879.2  393.85  4895.8  393.61  4945.8  392.21  4965.8  391.26
  4975.8   391.3 4980.11391.0716  4992.8  390.35  4993.3  389.55  4998.3  389.55
  4998.8  390.35  5015.8  390.84  5019.1 391.071  5025.8  391.54  5035.8   391.2
  5055.8  391.96  5065.8  391.96  5105.8  392.82  5115.8  393.22  5169.2     394
  5192.6  394.78  5197.7  394.64  5206.7  395.11    5217  395.33  5223.3  395.74
#Mann= 3 ,-1 , 0
  4756.6      .1       0  4992.8     .07       0  4998.8      .1       0
Bank Sta=4980.11,5019.1
XS Rating Curve= 0 ,0
Exp/Cntr=0.3,0.1

Type RM Length L Ch R = 1 ,2035    ,64,64,64
BEGIN DESCRIPTION:
Mapping XS 93573604
END DESCRIPTION:
XS GIS Cut Line= 4
      2067821.42     13457393.49      2067748.52     13457312.79
      2067471.61      13457301.5      2067394.35     13457317.99
#Sta/Elev= 30
  4743.4  393.54  4768.3  393.04  4775.2  393.17  4781.9  392.91  4789.4  392.95
  4796.1  392.63    4832  392.07  4838.7  391.75  4846.2  391.72  4851.1   391.3
  4885.7  390.94  4915.6   390.3  4920.6  390.37  4925.7  389.63  4935.7  389.38
  4965.8  389.51  4975.8  389.06  4985.8  387.94  5002.8  387.66  5003.3  386.86
  5008.3  386.86  5008.8  387.66  5015.8  388.29  5025.8  390.95  5035.8  391.39
  5045.8  390.85  5095.9  391.87  5156.5  393.58  5165.8  394.13  5208.3  395.56
#Mann= 3 ,-1 , 0
  4743.4      .1       0  5002.8     .07       0  5008.8      .1       0
Bank Sta=5002.8,5008.8
XS Rating Curve= 0 ,0
Exp/Cntr=0.3,0.1

Type RM Length L Ch R = 1 ,1971    ,87,87,87
BEGIN DESCRIPTION:
Mapping XS 1c525133
END DESCRIPTION:
XS GIS Cut Line= 4
      2067848.74     13457304.82      2067734.11     13457250.98
      2067478.03     13457235.35      2067382.58     13457264.86
#Sta/Elev= 30
  4739.8  392.21  4801.4  391.48  4824.2  391.33  4847.1   390.7  4875.6   390.5
  4881.6  390.62  4886.6  389.97  4915.6  389.91 4921.63 389.817  4945.7  389.53
  4992.8  389.34  4993.3  388.54  4998.3  388.54  4998.8  389.34  5005.8  389.78
 5008.26389.8169  5043.8  390.38  5048.8  390.14  5055.9  390.41  5075.9  390.87
    5096  391.16    5122   391.8  5127.2   391.8  5157.6  393.15  5172.9  393.46
  5178.5  394.02  5205.6  394.83  5210.8  395.11    5219  395.35  5222.9  395.35
#Mann= 3 ,-1 , 0
  4739.8      .1       0  4992.8     .07       0  4998.8      .1       0
Bank Sta=4921.63,5008.26
XS Rating Curve= 0 ,0
Exp/Cntr=0.3,0.1

Type RM Length L Ch R = 1 ,1884    ,165,165,165
BEGIN DESCRIPTION:
Mapping XS 2700478d
END DESCRIPTION:
XS GIS Cut Line= 4
      2067811.42     13457227.05      2067738.54     13457187.13
      2067533.67     13457155.88      2067390.45     13457171.51
#Sta/Elev= 30
  4813.8  394.31  4821.1  393.22  4827.6   391.6  4833.3  392.41  4843.8  391.02
  4930.8  389.32    4940  388.15  4945.1  388.67    4951  387.75  4961.2  388.25
  4981.4  387.19  4988.5   386.3    4989   385.5    4994   385.5  4994.5   386.3
  5001.6  386.88  5008.6     388  5021.9  388.66  5042.1  388.85  5052.2  389.19
  5077.2  389.14  5104.1  389.48    5133  390.45    5140  390.35  5173.2  391.13
  5193.3  391.22  5223.5  391.93  5231.4  391.99  5236.4  391.77  5248.2  391.99
#Mann= 3 ,-1 , 0
  4813.8      .1       0  4988.5     .07       0  4994.5      .1       0
Bank Sta=4988.5,4994.5
XS Rating Curve= 0 ,0
Exp/Cntr=0.3,0.1

Type RM Length L Ch R = 1 ,1719    ,230,230,230
BEGIN DESCRIPTION:
Mapping XS 9681271b
END DESCRIPTION:
XS GIS Cut Line= 4
      2067883.17     13457126.13      2067772.04     13457041.04
      2067435.24     13457028.89      2067339.91     13457072.22
#Sta/Elev= 30
  4688.4  392.19    4710  391.83  4745.3   390.6  4766.1  390.56  4809.7  389.71
  4828.4   389.9  4845.4  389.25  4905.5  388.51  4925.5  387.64  4945.5  388.12
  4955.5  387.32  4965.5  385.78  4985.5  385.45  4992.5  384.93    4993  384.13
    4998  384.13  4998.5  384.93  5005.5  385.61  5015.5  385.56  5035.5  386.69
  5065.6  387.47  5075.6   388.1  5165.4  389.61  5192.7  390.38  5198.6  390.86
  5238.8  391.56  5244.3  391.82  5253.5  394.04  5267.4  395.03  5270.1  393.13
#Mann= 3 ,-1 , 0
  4688.4      .1       0  4992.5     .07       0  4998.5      .1       0
Bank Sta=4992.5,4998.5
XS Rating Curve= 0 ,0
Exp/Cntr=0.3,0.1

Type RM Length L Ch R = 1 ,1489    ,82,82,82
BEGIN DESCRIPTION:
Mapping XS a1370627
END DESCRIPTION:
XS GIS Cut Line= 4
      2067901.04     13457039.31      2067665.36     13456855.71
      2067335.93     13456790.61      2067152.32     13456954.68
#Sta/Elev= 30
  4582.8   391.5  4732.2  388.02  4767.9  388.21  4860.7  386.59  4884.3  385.11
  4892.1  383.72  4909.2  382.27  4914.3  382.68  4960.5  379.98  4965.6  381.14
  5001.2  379.96  5001.7  379.16  5006.7  379.16  5007.2  379.96  5011.8  379.99
  5016.9  380.84  5034.8  381.01  5055.2  382.08    5096  385.91  5114.3  386.27
  5119.4  385.43  5165.6  386.92  5170.7  386.54  5197.9  386.94  5215.3  388.11
  5291.9  390.23  5306.1  391.15  5327.1  390.93    5363  392.45  5463.6  395.01
#Mann= 3 ,-1 , 0
  4582.8      .1       0  5001.2     .07       0  5007.2      .1       0
Bank Sta=5001.2,5007.2
XS Rating Curve= 0 ,0
Exp/Cntr=0.3,0.1

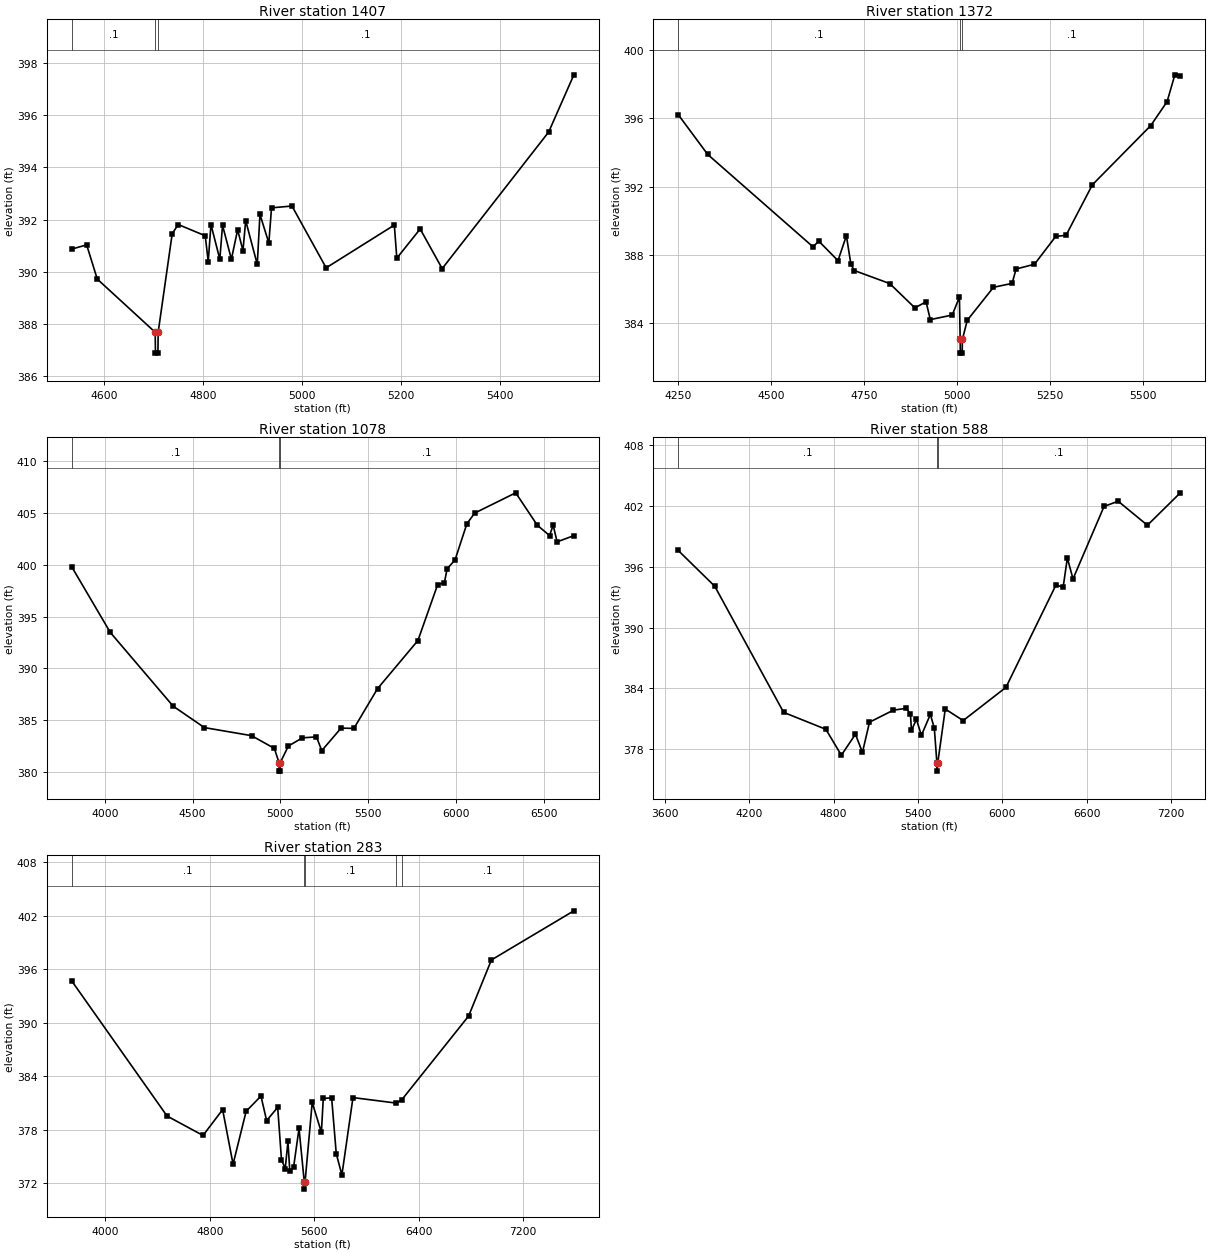
Type RM Length L Ch R = 1 ,1407    ,35,35,35
BEGIN DESCRIPTION:
Mapping XS 4ab2c5fd
END DESCRIPTION:
XS GIS Cut Line= 5
      2067912.78     13456989.85      2067765.62      13456849.2
      2067548.17     13456754.15      2067263.01     13456761.96
      2067099.97     13457000.04
#Sta/Elev= 30
    4534  390.87  4564.1  391.03  4585.5  389.72  4702.6  387.68  4703.1  386.88
  4708.1  386.88  4708.6  387.68    4737  391.46  4749.2  391.81  4803.7  391.38
  4809.8  390.39  4815.3  391.81  4833.2  390.48  4838.7  391.78  4856.6  390.48
  4869.2  391.61    4880  390.81  4885.5  391.96  4908.9  390.28  4914.3   392.2
  4932.3   391.1  4937.7  392.45    4979  392.52  5048.1  390.15  5185.9  391.79
  5190.9  390.52  5238.1  391.64  5282.6  390.12  5497.9  395.36  5548.7  397.55
#Mann= 3 ,-1 , 0
    4534      .1       0  4702.6     .07       0  4708.6      .1       0
Bank Sta=4702.6,4708.6
XS Rating Curve= 0 ,0
Exp/Cntr=0.3,0.1

Type RM Length L Ch R = 1 ,1372    ,294,294,294
BEGIN DESCRIPTION:
Mapping XS a02ced93
END DESCRIPTION:
XS GIS Cut Line= 5
      2068175.42     13457052.07      2067638.01     13456735.92
      2067437.49     13456712.48      2067246.09     13456730.71
      2067049.99     13457000.02
#Sta/Elev= 30
  4250.4  396.21  4329.8  393.88  4612.9  388.48  4628.6  388.81  4680.2  387.67
  4702.8  389.13    4715  387.45  4724.3  387.09  4819.4  386.33    4887  384.91
  4917.2  385.26  4928.6  384.22  4987.7  384.49  5006.9  385.54  5008.9  383.06
  5009.4  382.26  5014.4  382.26  5014.9  383.06    5028  384.18  5098.4  386.11
  5148.6  386.34  5159.4  387.18  5208.9  387.46  5266.1  389.09  5293.7  389.15
  5364.7  392.11  5521.6  395.57  5565.6  396.97  5586.5  398.54  5601.2  398.48
#Mann= 3 ,-1 , 0
  4250.4      .1       0  5008.9     .07       0  5014.9      .1       0
Bank Sta=5008.9,5014.9
XS Rating Curve= 0 ,0
Exp/Cntr=0.3,0.1

Type RM Length L Ch R = 1 ,1078    ,490,490,490
BEGIN DESCRIPTION:
Mapping XS 44500d8c
END DESCRIPTION:
XS GIS Cut Line= 4
       2068524.4     13456901.04      2067862.32     13456422.99
      2067074.13     13456445.56      2066852.73     13457681.14
#Sta/Elev= 30
  3811.7   399.8  4031.2  393.46  4389.4  386.33  4567.3  384.26  4835.7  383.48
  4965.8  382.25  4992.8  380.85  4993.3  380.05  4998.3  380.05  4998.8  380.85
  5045.8  382.48  5125.9  383.27  5205.9  383.36  5235.9  382.03  5345.9  384.21
  5419.1  384.18  5553.5  388.02  5783.8  392.68  5896.3  398.09  5934.4  398.26
  5950.1  399.61  5995.4  400.48  6062.7  403.97  6107.1     405  6340.8  406.96
  6464.3  403.82  6533.8  402.83  6554.1  403.83  6576.9  402.22  6672.1  402.82
#Mann= 3 ,-1 , 0
  3811.7      .1       0  4992.8     .07       0  4998.8      .1       0
Bank Sta=4992.8,4998.8
XS Rating Curve= 0 ,0
Exp/Cntr=0.3,0.1

Type RM Length L Ch R = 1 ,588     ,305,305,305
BEGIN DESCRIPTION:
Mapping XS d4eef873
END DESCRIPTION:
XS GIS Cut Line= 5
       2068685.9     13456510.44      2067825.86     13456002.85
      2067233.85     13455988.96      2066701.48     13456531.25
      2066810.86     13457744.78
#Sta/Elev= 30
  3696.2  397.61  3955.7  394.08  4445.4  381.63  4745.7  379.96  4855.8   377.4
  4955.8  379.47  5005.8  377.68  5055.8  380.66  5225.9  381.85  5318.8  382.03
  5347.1  381.44  5354.1  379.85  5389.5  380.94  5424.8  379.36  5488.5  381.43
  5516.8  380.06    5535  376.63  5535.5  375.83    5541  376.63  5594.5  381.96
  5721.8  380.82  6025.9   384.1  6382.1  394.22  6432.3  393.97  6462.4  396.87
  6502.5   394.8  6723.4  401.96  6823.8  402.47  7031.4   400.1  7265.4   403.3
#Mann= 3 ,-1 , 0
  3696.2      .1       0    5535     .07       0    5541      .1       0
Bank Sta=5535,5541
XS Rating Curve= 0 ,0
Exp/Cntr=0.3,0.1

Type RM Length L Ch R = 1 ,283     ,0,0,0
BEGIN DESCRIPTION:
UNT 93 in Lagunillas Cr Wtrshd 1.0
END DESCRIPTION:
XS GIS Cut Line= 5
       2068727.5     13456296.86      2067891.71     13455788.12
      2067425.13     13455779.44      2066560.86     13456468.75
      2066743.16     13457750.05
#Sta/Elev= 30
  3742.2  394.68  4471.9  379.53  4747.4  377.35  4897.4  380.25  4977.4  374.13
  5077.4  380.06    5191  381.77  5234.3  379.02  5319.1   380.5    5348  374.65
  5376.8  373.63  5397.6  376.68    5412  373.33  5440.9   373.8  5482.5  378.14
  5522.7  372.13  5523.2  371.33  5528.7  372.13  5583.4  381.05  5653.8   377.7
  5668.2  381.52  5732.3  381.56  5767.5  375.32  5810.8  372.92  5895.6   381.6
  6227.9  380.98  6270.2  381.37  6781.3  390.75  6955.7  397.04    7587  402.55
#Mann= 5 ,-1 , 0
  3742.2      .1       0  5522.7     .07       0  5528.7      .1       0
  6227.9     .12       0  6270.2      .1       0
Bank Sta=5522.7,5528.7
XS Rating Curve= 0 ,0
Exp/Cntr=0.3,0.1
LCMann Table=0

Chan Stop Cuts=-1
Use User Specified Reach Order=0
Composite Channel Slope=5