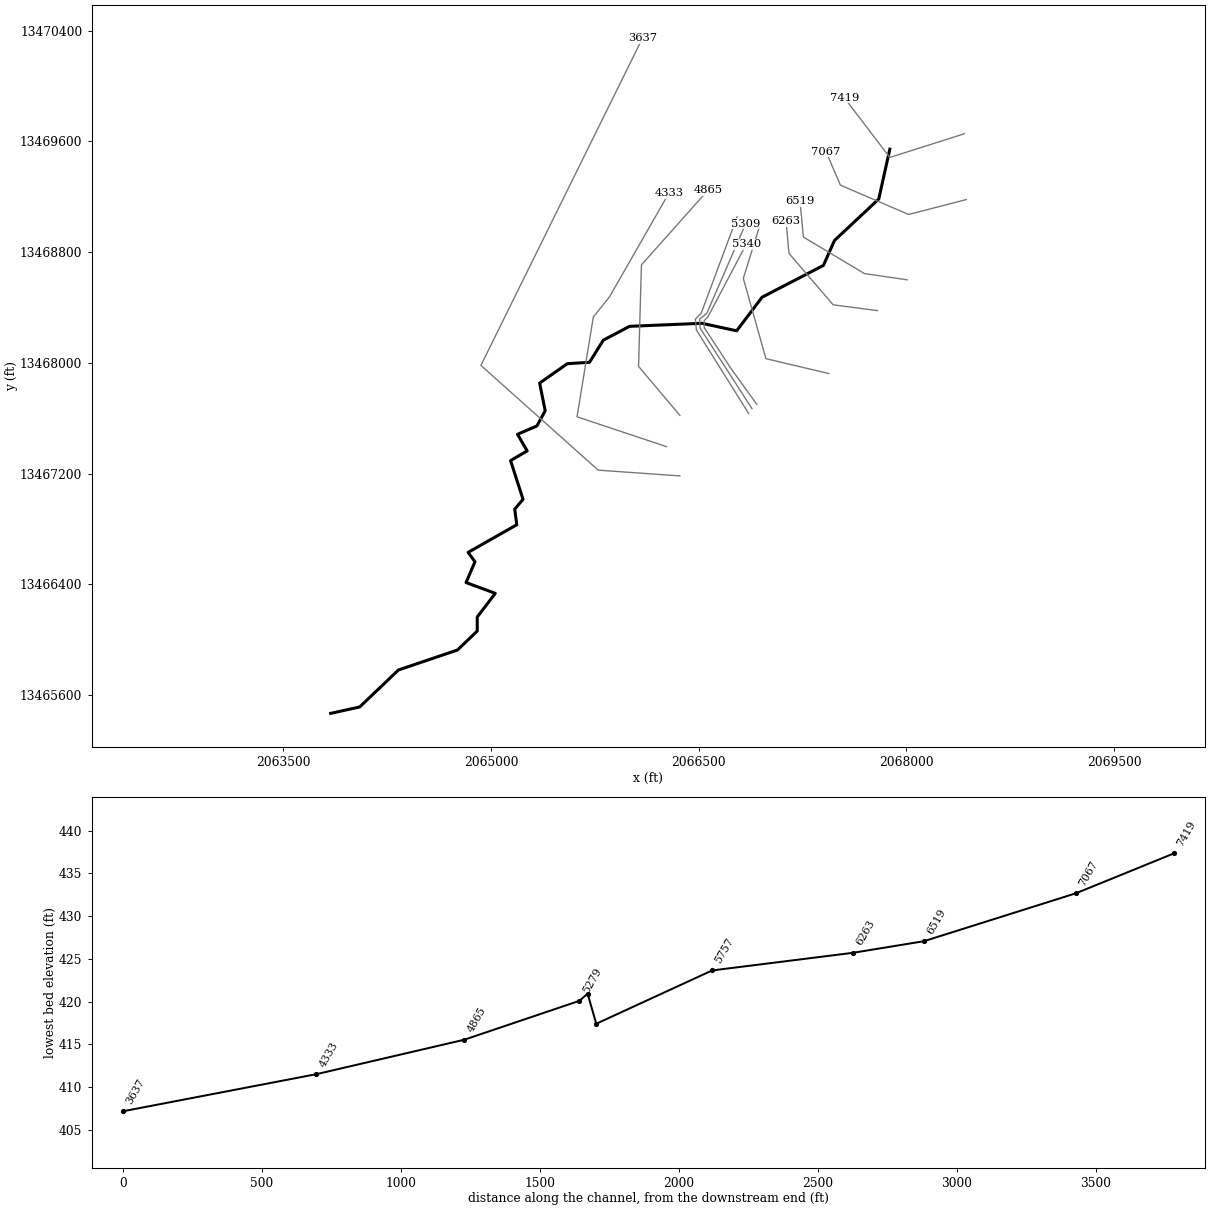
--- UNT 95 in Lagunillas Cr Wtrshd.prj (project) ---

Proj Title=UNT 95 in Lagunillas Cr Wtrshd Base Level Engineering
Current Plan=p01
Default Exp/Contr=0.3,0.1
English Units
Geom File=g01
Flow File=f01
Plan File=p01
BEGIN DESCRIPTION:
UNT 95 in Lagunillas Cr Wtrshd
END DESCRIPTION:

--- UNT 95 in Lagunillas Cr Wtrshd.p01 (plan) ---

Plan Title=Multiple Run
Short Identifier=Multiple
Geom File=g01
Flow File=f01
Subcritical Flow
K Sum by GR= 0
Std Step Tol= 0.01
Critical Tol= 0.01
Num of Std Step Trials= 20
Max Error Tol= 0.3
Flow Tol Ratio= 0.001
Split Flow NTrial= 30
Split Flow Tol= 0.02
Split Flow Ratio= 0.02
Log Output Level= 0
Friction Slope Method= 1
Unsteady Friction Slope Method= 2
Unsteady Bridges Friction Slope Method= 1
Parabolic Critical Depth
Global Vel Dist=  1 , 1 , 1
Global Log Level= 0
CheckData=True
Encroach Param= -1, 0, 0, 0
BEGIN DESCRIPTION:
Multiple Run
END DESCRIPTION:

--- UNT 95 in Lagunillas Cr Wtrshd.f01 (steady flow) ---

Flow Title=Multiple
Number of Profiles=7
Profile Names=10-year,25-year,50-year,1pct_min,100-year,1pct_plu,500-year
River Rch & RM= UNT 95 in Laguni,Reach-1,7419
     103     136     161      96     191     382     274
River Rch & RM= UNT 95 in Laguni,Reach-1,3637
     190     259     315     192     382     763     570
Boundary for River Rch & Prof#=UNT 95 in Laguni,Reach-1,1
Up Type=0
Dn Type=3
Dn Slope=0.005
Boundary for River Rch & Prof#=UNT 95 in Laguni,Reach-1,2
Up Type=0
Dn Type=3
Dn Slope=0.005
Boundary for River Rch & Prof#=UNT 95 in Laguni,Reach-1,3
Up Type=0
Dn Type=3
Dn Slope=0.005
Boundary for River Rch & Prof#=UNT 95 in Laguni,Reach-1,4
Up Type=0
Dn Type=3
Dn Slope=0.005
Boundary for River Rch & Prof#=UNT 95 in Laguni,Reach-1,5
Up Type=0
Dn Type=3
Dn Slope=0.005
Boundary for River Rch & Prof#=UNT 95 in Laguni,Reach-1,6
Up Type=0
Dn Type=3
Dn Slope=0.005
Boundary for River Rch & Prof#=UNT 95 in Laguni,Reach-1,7
Up Type=0
Dn Type=3
Dn Slope=0.005

--- UNT 95 in Lagunillas Cr Wtrshd.g01 (geometry) ---

Geom Title=Existing Conditions

River Reach=UNT 95 in Laguni,Reach-1
Reach XY= 30
      2067880.80     13469544.54      2067800.80     13469184.54
      2067480.80     13468884.54      2067400.80     13468704.54
      2066957.60     13468474.58      2066774.16     13468232.04
      2066523.57     13468286.39      2066000.80     13468264.54
      2065810.80     13468164.54      2065710.80     13468004.54
      2065550.80     13467994.54      2065350.80     13467854.54
      2065390.80     13467654.54      2065330.80     13467544.54
      2065190.80     13467484.54      2065260.80     13467364.54
      2065140.80     13467294.54      2065230.80     13467014.54
      2065170.80     13466944.54      2065185.47     13466830.95
      2064833.90     13466631.30      2064883.38     13466563.59
      2064819.15     13466413.42      2065030.08     13466335.29
      2064899.87     13466164.29      2064899.87     13466062.73
      2064756.82     13465925.92      2064330.80     13465781.65
      2064050.80     13465514.54      2063840.80     13465468.15

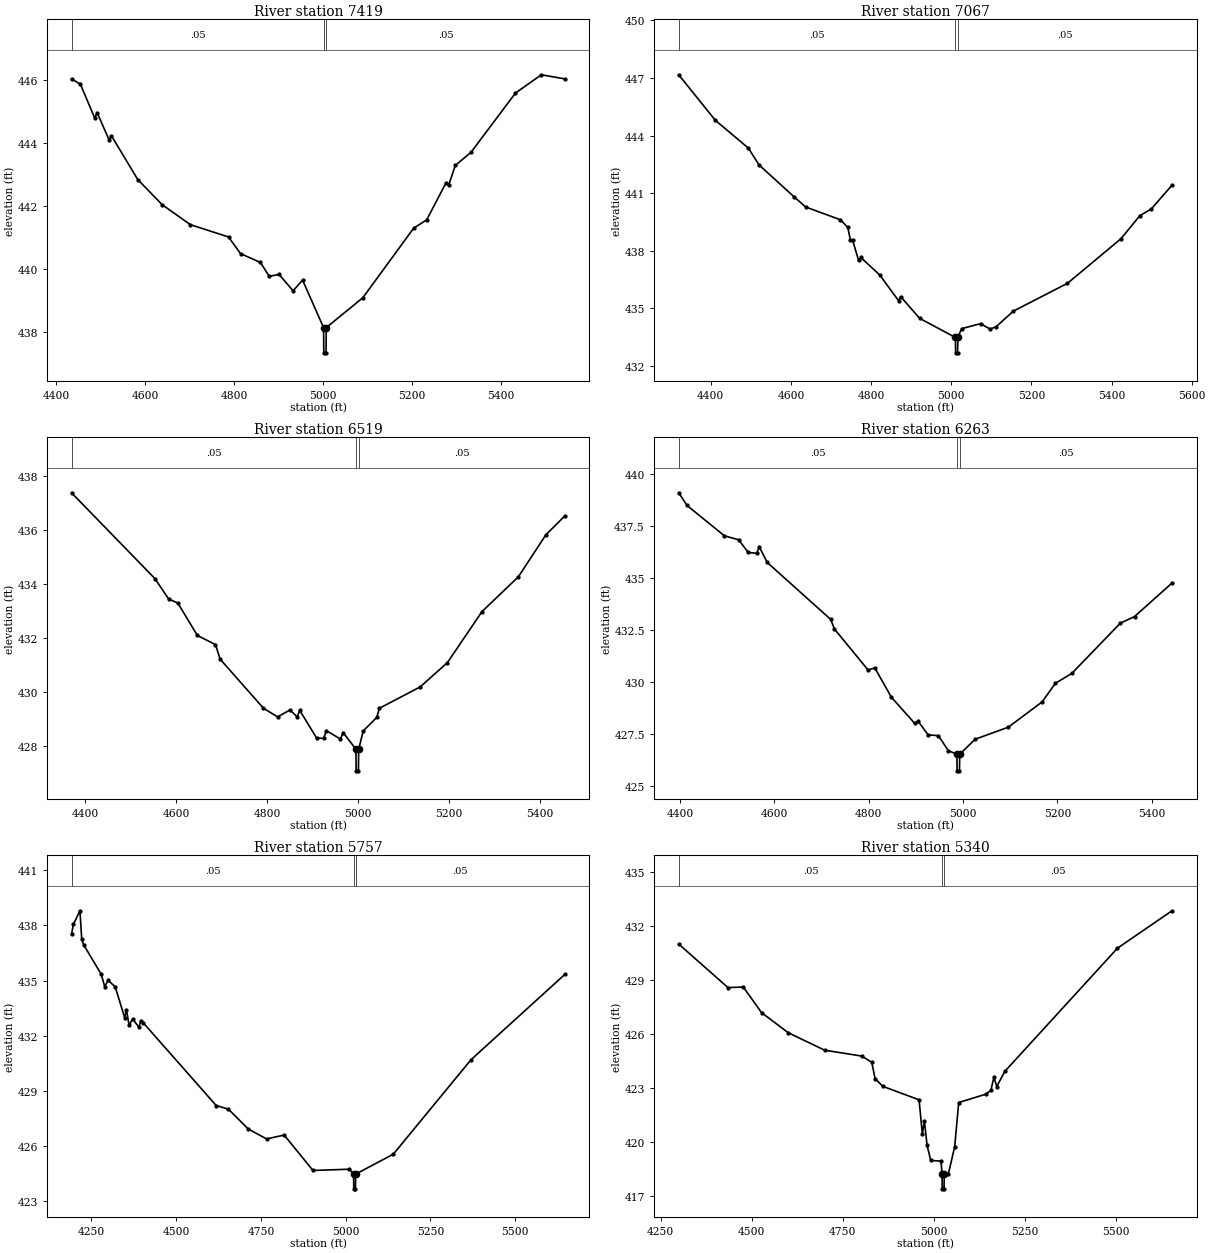
Type RM Length L Ch R = 1,7419,352,352,352
BEGIN DESCRIPTION:
UNT 95 in Lagunillas Cr Wtrshd 5.0
END DESCRIPTION:
XS GIS Cut Line= 3
      2068419.48     13469655.96      2067880.80     13469484.54
      2067551.46     13469916.39
#Sta/Elev= 30
  4434.7  446.05  4454.7  445.88  4487.0  444.80  4492.2  444.98  4519.2  444.11
  4524.5  444.24  4583.7  442.85  4638.8  442.05  4701.8  441.42  4787.5  441.03
  4814.5  440.50  4859.2  440.22  4879.0  439.78  4901.1  439.84  4932.6  439.32
  4953.9  439.66  5001.1  438.15  5001.6  437.35  5006.6  437.35  5007.1  438.15
  5089.3  439.10  5203.6  441.31  5232.7  441.57  5276.3  442.75  5282.6  442.69
  5297.1  443.30  5332.5  443.72  5432.3  445.60  5490.4  446.18  5543.1  446.05
#Mann=3,-1,0
  4434.7    0.05       0  5001.1    0.03       0  5007.1    0.05       0
Bank Sta=5001.1,5007.1
Exp/Cntr=0.3,0.1

Type RM Length L Ch R = 1,7067,548,548,548
BEGIN DESCRIPTION:
Mapping XS e684bb55
END DESCRIPTION:
XS GIS Cut Line= 4
      2068433.37     13469180.26      2068016.74     13469072.63
      2067523.68     13469284.44      2067419.74     13469526.97
#Sta/Elev= 30
  4320.1  447.17  4411.4  444.80  4494.0  443.35  4520.4  442.48  4607.6  440.82
  4637.2  440.28  4723.7  439.62  4741.9  439.22  4748.7  438.55  4754.1  438.55
  4768.8  437.51  4774.3  437.66  4821.4  436.75  4868.5  435.41  4873.9  435.62
  4921.0  434.49  5010.5  433.49  5011.0  432.69  5016.0  432.69  5016.5  433.49
  5026.1  433.95  5073.2  434.21  5096.8  433.93  5111.5  434.04  5155.0  434.86
  5290.1  436.31  5423.5  438.63  5470.6  439.83  5499.6  440.19  5550.9  441.42
#Mann=3,-1,0
  4320.1    0.05       0  5010.5    0.03       0  5016.5    0.05       0
Bank Sta=5010.5,5016.5
Exp/Cntr=0.3,0.1

Type RM Length L Ch R = 1,6519,256,256,256
BEGIN DESCRIPTION:
Mapping XS 91980934
END DESCRIPTION:
XS GIS Cut Line= 4
      2068006.31     13468600.41      2067697.29     13468645.55
      2067256.32     13468909.44      2067232.02     13469166.39
#Sta/Elev= 30
  4370.2  437.38  4553.4  434.20  4583.8  433.44  4604.0  433.29  4646.8  432.09
  4686.7  431.75  4696.9  431.21  4792.2  429.39  4823.3  429.07  4850.6  429.33
  4866.1  429.07  4871.9  429.31  4908.9  428.29  4924.5  428.27  4930.3  428.56
  4961.4  428.25  4967.2  428.49  4995.4  427.87  4995.9  427.07  5000.9  427.07
  5001.4  427.87  5011.5  428.55  5041.2  429.05  5047.0  429.39  5136.5  430.18
  5196.4  431.08  5272.3  432.97  5352.7  434.27  5412.9  435.82  5454.5  436.52
#Mann=3,-1,0
  4370.2    0.05       0  4995.4    0.03       0  5001.4    0.05       0
Bank Sta=4995.4,5001.4
Exp/Cntr=0.3,0.1

Type RM Length L Ch R = 1,6263,506,506,506
BEGIN DESCRIPTION:
Mapping XS 4f42923a
END DESCRIPTION:
XS GIS Cut Line= 4
      2067791.05     13468378.19      2067471.60     13468419.86
      2067152.16     13468791.38      2067131.32     13469024.02
#Sta/Elev= 30
  4397.4  439.08  4415.0  438.47  4494.3  437.01  4524.5  436.82  4544.7  436.21
  4562.9  436.17  4568.0  436.49  4585.0  435.73  4719.6  432.99  4727.5  432.53
  4798.8  430.56  4813.1  430.66  4848.2  429.25  4897.8  427.99  4905.2  428.09
  4926.1  427.44  4948.0  427.40  4968.9  426.68  4987.1  426.51  4987.6  425.71
  4992.6  425.71  4993.1  426.51  5025.9  427.23  5096.2  427.81  5167.5  429.02
  5196.0  429.92  5231.0  430.40  5333.6  432.81  5363.8  433.13  5443.1  434.74
#Mann=3,-1,0
  4397.4    0.05       0  4987.1    0.03       0  4993.1    0.05       0
Bank Sta=4987.1,4993.1
Exp/Cntr=0.3,0.1

Type RM Length L Ch R = 1,5757,417,417,417
BEGIN DESCRIPTION:
Mapping XS 57407dc7
END DESCRIPTION:
XS GIS Cut Line= 4
      2067440.32     13467923.33      2066985.49     13468030.97
      2066822.29     13468610.83      2066936.89     13468978.92
#Sta/Elev= 30
  4191.1  437.52  4196.6  438.06  4216.0  438.80  4221.2  437.24  4227.4  436.93
  4278.8  435.34  4289.1  434.67  4299.3  435.01  4319.9  434.66  4347.9  432.98
  4353.1  433.41  4361.0  432.55  4371.3  432.91  4390.2  432.45  4395.4  432.81
  4402.1  432.71  4617.9  428.19  4654.1  427.99  4712.6  426.91  4766.6  426.37
  4818.5  426.58  4903.5  424.65  5010.8  424.72  5023.3  424.45  5023.8  423.65
  5028.8  423.65  5029.3  424.45  5140.6  425.54  5370.0  430.69  5646.4  435.33
#Mann=3,-1,0
  4191.1    0.05       0  5023.3    0.03       0  5029.3    0.05       0
Bank Sta=5023.3,5029.3
Exp/Cntr=0.3,0.1

Type RM Length L Ch R = 1,5340,31,31,31
BEGIN DESCRIPTION:
Mapping XS dc93b08d
END DESCRIPTION:
XS GIS Cut Line= 6
      2066919.50     13467701.12      2066732.02     13467961.52
      2066539.91     13468255.15      2066539.91     13468306.37
      2066565.08     13468329.80      2066843.12     13468857.35
#Sta/Elev= 30
  4299.6  431.02  4434.7  428.60  4476.9  428.63  4526.8  427.21  4600.1  426.09
  4699.8  425.12  4802.4  424.79  4829.4  424.44  4838.5  423.54  4859.6  423.11
  4959.2  422.36  4968.2  420.46  4973.8  421.18  4981.2  419.83  4991.2  418.99
  5019.4  418.95  5022.3  418.21  5022.8  417.41  5027.8  417.41  5028.3  418.21
  5039.5  418.23  5057.0  419.76  5068.0  422.21  5142.0  422.67  5156.1  422.88
  5164.6  423.61  5172.5  423.10  5194.5  423.94  5503.7  430.79  5653.3  432.87
#Mann=3,-1,0
  4299.6    0.05       0  5022.3    0.03       0  5028.3    0.05       0
Bank Sta=5022.3,5028.3
Exp/Cntr=0.3,0.1

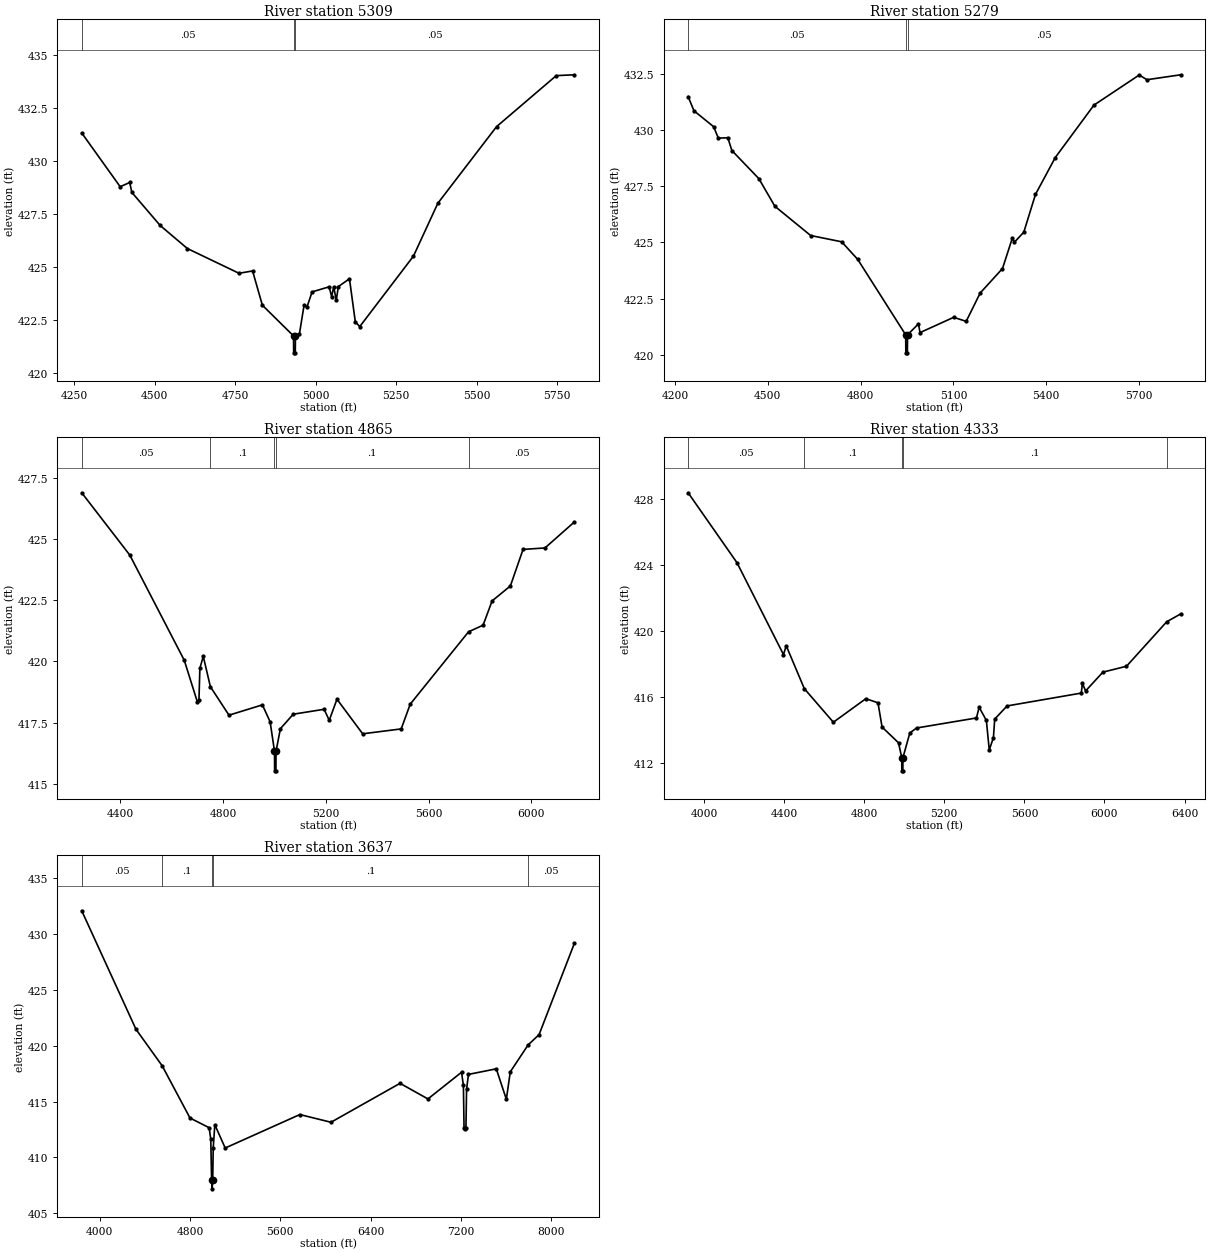
Type RM Length L Ch R = 1,5309,30,30,30
BEGIN DESCRIPTION:
Mapping XS a34d96f1
END DESCRIPTION:
XS GIS Cut Line= 5
      2066884.80     13467669.85      2066510.39     13468250.81
      2066506.92     13468316.78      2066559.01     13468359.32
      2066839.65     13469006.64
#Sta/Elev= 30
  4273.9  431.32  4393.3  428.78  4422.8  428.98  4429.6  428.51  4517.4  426.95
  4601.9  425.86  4762.3  424.69  4804.5  424.80  4834.9  423.18  4931.6  421.73
  4932.1  420.93  4937.1  420.93  4937.6  421.73  4949.8  421.81  4964.6  423.20
  4973.4  423.09  4989.3  423.81  5042.1  424.05  5050.0  423.59  5056.5  424.05
  5064.4  423.41  5070.8  424.06  5105.4  424.43  5123.5  422.40  5137.3  422.17
  5304.1  425.50  5379.9  428.00  5562.3  431.62  5747.6  434.03  5803.9  434.07
#Mann=3,-1,0
  4273.9    0.05       0  4931.6    0.03       0  4937.6    0.05       0
Bank Sta=4931.6,4937.6
Exp/Cntr=0.3,0.1

Type RM Length L Ch R = 1,5279,414,414,414
BEGIN DESCRIPTION:
Mapping XS 13be7be7
END DESCRIPTION:
XS GIS Cut Line= 5
      2066860.51     13467635.11      2066483.48     13468237.79
      2066475.67     13468315.92      2066518.21     13468359.32
      2066777.14     13469055.23
#Sta/Elev= 30
  4242.3  431.49  4261.0  430.86  4324.7  430.15  4340.0  429.64  4370.6  429.66
  4383.7  429.09  4470.9  427.84  4522.7  426.61  4638.3  425.31  4738.5  425.03
  4790.4  424.25  4945.6  420.89  4946.1  420.09  4951.1  420.09  4951.6  420.89
  4986.9  421.38  4991.9  420.99  5100.8  421.67  5141.2  421.49  5186.4  422.75
  5258.6  423.84  5290.6  425.20  5297.1  425.01  5327.5  425.46  5365.3  427.14
  5429.3  428.78  5554.2  431.11  5700.6  432.45  5725.6  432.24  5835.0  432.46
#Mann=3,-1,0
  4242.3    0.05       0  4945.6    0.03       0  4951.6    0.05       0
Bank Sta=4945.6,4951.6
Exp/Cntr=0.3,0.1

Type RM Length L Ch R = 1,4865,532,532,532
BEGIN DESCRIPTION:
Mapping XS e76d53da
END DESCRIPTION:
XS GIS Cut Line= 4
      2066363.96     13467621.24      2066065.35     13467975.41
      2066086.18     13468708.05      2066565.36     13469246.26
#Sta/Elev= 30
  4250.2  426.88  4437.1  424.34  4649.1  420.05  4699.8  418.36  4706.3  418.44
  4709.9  419.72  4723.0  420.21  4750.8  418.97  4823.1  417.81  4953.1  418.23
  4983.2  417.54  5000.2  416.34  5000.7  415.54  5005.7  415.54  5006.2  416.34
  5023.2  417.26  5073.2  417.85  5193.2  418.05  5213.2  417.60  5243.3  418.46
  5343.3  417.05  5493.2  417.25  5528.3  418.26  5755.2  421.21  5811.8  421.48
  5846.9  422.47  5918.0  423.08  5967.3  424.57  6052.6  424.63  6167.0  425.69
#Mann=5,-1,0
  4250.2    0.05       0  4750.8     0.1       0  5000.2    0.07       0
  5006.2     0.1       0  5755.2    0.05       0
Bank Sta=5000.2,5006.2
Exp/Cntr=0.3,0.1

Type RM Length L Ch R = 1,4333,696,696,696
BEGIN DESCRIPTION:
Mapping XS 1ab3203b
END DESCRIPTION:
XS GIS Cut Line= 5
      2066266.75     13467395.55      2065620.91     13467610.83
      2065738.79     13468332.67      2065854.86     13468476.76
      2066284.26     13469226.26
#Sta/Elev= 30
  3920.3  428.39  4164.6  424.14  4396.5  418.57  4410.5  419.10  4500.6  416.50
  4645.8  414.46  4808.0  415.89  4868.7  415.64  4889.0  414.17  4971.4  413.21
  4987.3  412.31  4987.8  411.51  4992.8  411.51  4993.3  412.31  5027.8  413.81
  5061.3  414.11  5360.5  414.72  5374.0  415.37  5410.1  414.57  5424.5  412.78
  5445.3  413.52  5451.7  414.65  5513.6  415.45  5884.2  416.23  5890.0  416.82
  5905.8  416.36  5992.1  417.50  6110.1  417.86  6311.0  420.56  6381.3  421.04
#Mann=5,-1,0
  3920.3    0.05       0  4500.6     0.1       0  4987.3    0.07       0
  4993.3     0.1       0  6311.0    0.05       0
Bank Sta=4987.3,4993.3
Exp/Cntr=0.3,0.1

Type RM Length L Ch R = 1,3637,0,0,0
BEGIN DESCRIPTION:
Mapping XS 8be379d5
END DESCRIPTION:
XS GIS Cut Line= 4
      2066363.93     13467183.75      2065773.68     13467225.41
      2064926.46     13467982.36      2066093.12     13470345.20
#Sta/Elev= 30
  3841.2  432.10  4321.3  421.48  4553.7  418.20  4800.0  413.52  4969.7  412.65
  4983.9  411.62  4991.4  407.98  4995.1  407.97  4995.6  407.17  5001.1  407.97
  5005.6  410.82  5019.8  412.92  5111.8  410.83  5772.7  413.83  6048.7  413.14
  6660.3  416.63  6907.2  415.23  7204.6  417.62  7221.4  416.45  7227.0  412.61
  7233.7  412.51  7243.9  412.66  7249.5  416.11  7266.3  417.43  7512.5  417.93
  7601.7  415.20  7636.6  417.66  7794.2  420.07  7891.7  421.00  8204.2  429.18
#Mann=5,-1,0
  3841.2    0.05       0  4553.7     0.1       0  4995.1    0.07       0
  5001.1     0.1       0  7794.2    0.05       0
Bank Sta=4995.1,5001.1
Exp/Cntr=0.3,0.1

Chan Stop Cuts=-1