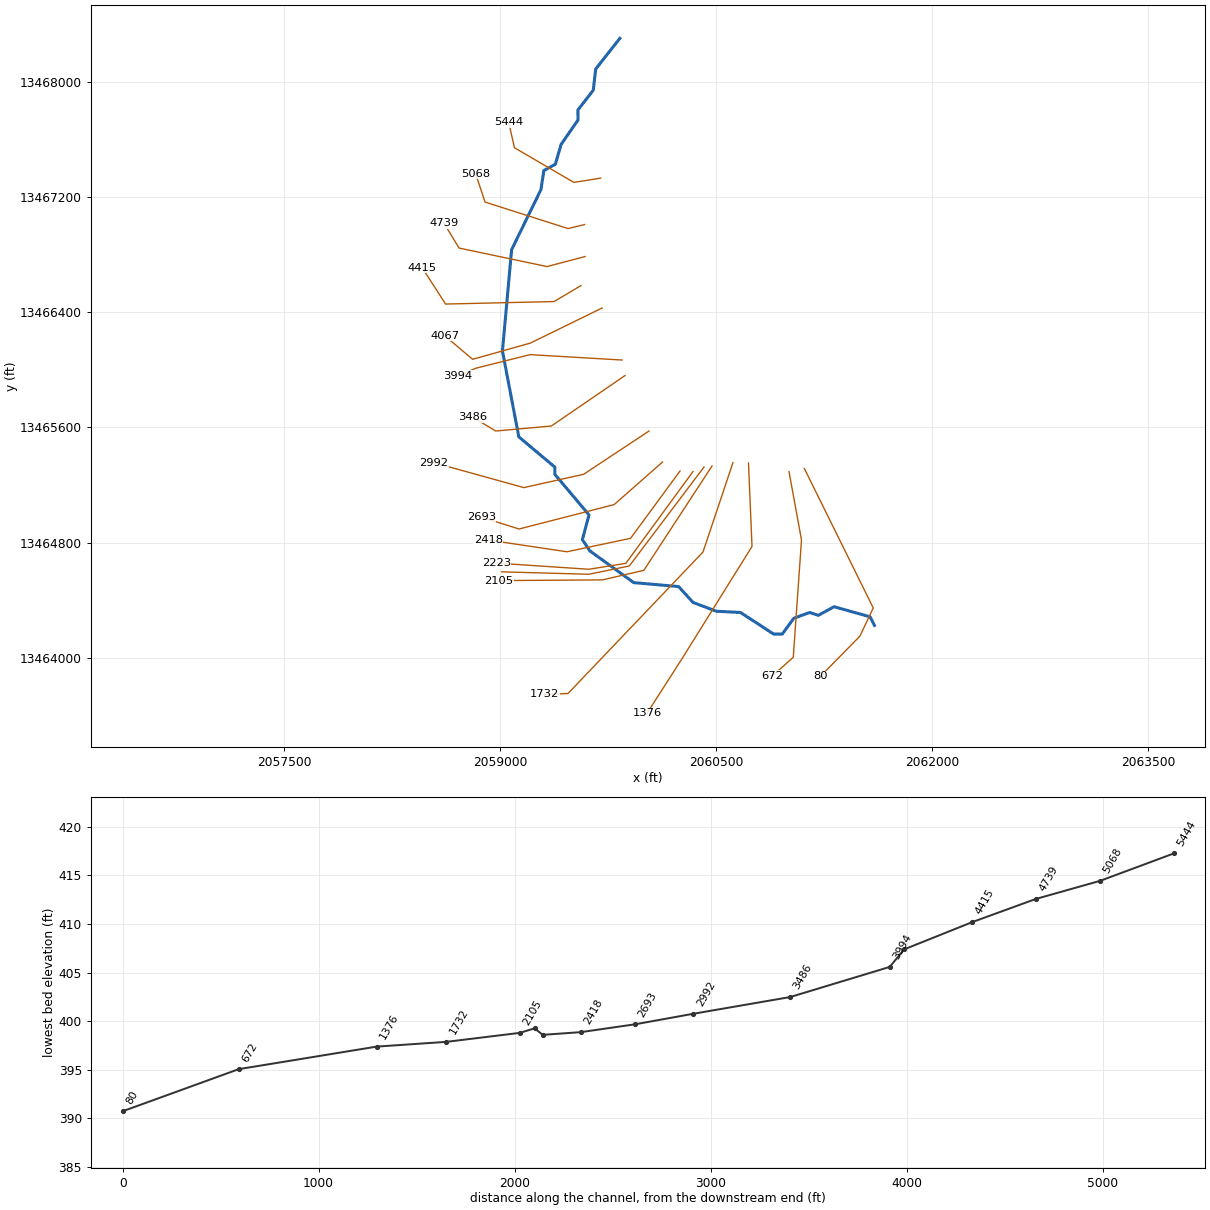
--- UNT 96 in Lagunillas Cr Wtrshd.prj (project) ---

Proj Title=UNT 96 in Lagunillas Cr Wtrshd Base Level Engineering
Current Plan=p01
Default Exp/Contr=0.3,0.1
English Units
Geom File=g01
Flow File=f01
Plan File=p01
BEGIN DESCRIPTION:
UNT 96 in Lagunillas Cr Wtrshd
END DESCRIPTION:

--- UNT 96 in Lagunillas Cr Wtrshd.p01 (plan) ---

Plan Title=Multiple Run
Short Identifier=Multiple
Geom File=g01
Flow File=f01
Subcritical Flow
K Sum by GR= 0
Std Step Tol= 0.01
Critical Tol= 0.01
Num of Std Step Trials= 20
Max Error Tol= 0.3
Flow Tol Ratio= 0.001
Split Flow NTrial= 30
Split Flow Tol= 0.02
Split Flow Ratio= 0.02
Log Output Level= 0
Friction Slope Method= 1
Unsteady Friction Slope Method= 2
Unsteady Bridges Friction Slope Method= 1
Parabolic Critical Depth
Global Vel Dist=  1 , 1 , 1
Global Log Level= 0
CheckData=True
Encroach Param= -1, 0, 0, 0
BEGIN DESCRIPTION:
Multiple Run
END DESCRIPTION:

--- UNT 96 in Lagunillas Cr Wtrshd.f01 (steady flow) ---

Flow Title=Multiple
Number of Profiles=7
Profile Names=10-year,25-year,50-year,1pct_min,100-year,1pct_plu,500-year
River Rch & RM= UNT 96 in Laguni,Reach-1,5444
      84     109     127      74     149     296     206
Boundary for River Rch & Prof#=UNT 96 in Laguni,Reach-1,1
Up Type=0
Dn Type=3
Dn Slope=0.005
Boundary for River Rch & Prof#=UNT 96 in Laguni,Reach-1,2
Up Type=0
Dn Type=3
Dn Slope=0.005
Boundary for River Rch & Prof#=UNT 96 in Laguni,Reach-1,3
Up Type=0
Dn Type=3
Dn Slope=0.005
Boundary for River Rch & Prof#=UNT 96 in Laguni,Reach-1,4
Up Type=0
Dn Type=3
Dn Slope=0.005
Boundary for River Rch & Prof#=UNT 96 in Laguni,Reach-1,5
Up Type=0
Dn Type=3
Dn Slope=0.005
Boundary for River Rch & Prof#=UNT 96 in Laguni,Reach-1,6
Up Type=0
Dn Type=3
Dn Slope=0.005
Boundary for River Rch & Prof#=UNT 96 in Laguni,Reach-1,7
Up Type=0
Dn Type=3
Dn Slope=0.005

--- UNT 96 in Lagunillas Cr Wtrshd.g01 (geometry) ---

Geom Title=Existing Conditions

River Reach=UNT 96 in Laguni,Reach-1
Reach XY= 30
      2059832.51     13468302.60      2059664.97     13468089.28
      2059648.05     13467942.49      2059541.28     13467804.99
      2059541.85     13467735.14      2059424.61     13467565.74
      2059384.38     13467427.71      2059304.73     13467383.98
      2059284.59     13467251.77      2059080.80     13466834.54
      2059017.16     13466130.90      2059130.80     13465534.54
      2059380.80     13465324.54      2059380.80     13465274.54
      2059618.34     13464992.39      2059572.33     13464820.52
      2059624.41     13464742.39      2059929.10     13464521.91
      2060240.80     13464494.54      2060340.80     13464384.54
      2060502.89     13464323.12      2060670.66     13464314.68
      2060900.80     13464164.54      2060960.80     13464164.54
      2061040.80     13464274.54      2061150.80     13464314.54
      2061210.80     13464294.54      2061320.80     13464354.54
      2061570.80     13464284.54      2061600.80     13464224.54

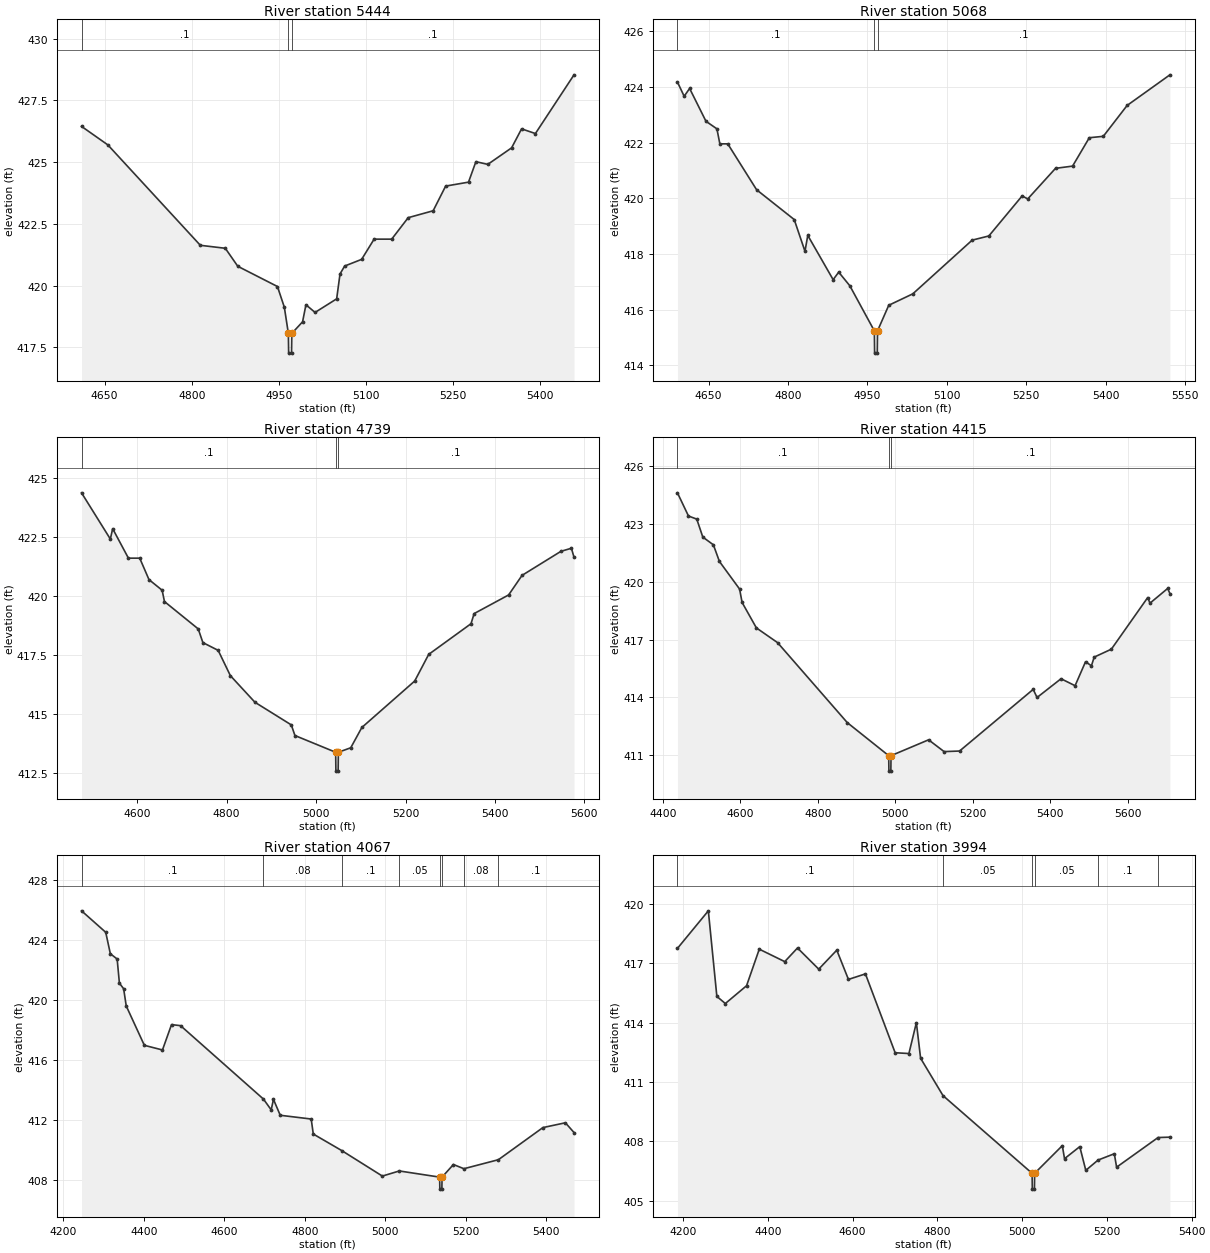
Type RM Length L Ch R = 1,5444,376,376,376
BEGIN DESCRIPTION:
Mapping XS 1841bc09
END DESCRIPTION:
XS GIS Cut Line= 4
      2059699.71     13467331.75      2059513.46     13467301.80
      2059100.70     13467542.68      2059060.33     13467719.79
#Sta/Elev= 30
  4610.2  426.45  4655.5  425.70  4814.8  421.63  4857.8  421.51  4879.3  420.78
  4947.6  419.96  4959.5  419.12  4966.4  418.06  4966.9  417.26  4971.9  417.26
  4972.4  418.06  4990.9  418.53  4996.7  419.22  5012.4  418.91  5049.6  419.46
  5055.4  420.47  5063.4  420.79  5092.6  421.06  5114.1  421.88  5144.4  421.88
  5172.8  422.75  5215.8  423.03  5237.3  424.03  5276.7  424.19  5289.4  425.02
  5309.9  424.91  5350.9  425.58  5368.1  426.35  5391.9  426.16  5458.4  428.54
#Mann=3,-1,0
  4610.2     0.1       0  4966.4    0.07       0  4972.4     0.1       0
Bank Sta=4966.4,4972.4
Exp/Cntr=0.3,0.1

Type RM Length L Ch R = 1,5068,329,329,329
BEGIN DESCRIPTION:
Mapping XS 3dc82652
END DESCRIPTION:
XS GIS Cut Line= 4
      2059587.37     13467009.01      2059472.81     13466981.24
      2058896.42     13467165.26      2058830.97     13467361.61
#Sta/Elev= 30
  4591.3  424.18  4604.0  423.67  4614.3  423.95  4645.2  422.77  4665.8  422.50
  4671.4  421.96  4686.3  421.96  4740.8  420.31  4811.8  419.24  4832.1  418.10
  4837.4  418.67  4885.3  417.08  4895.8  417.35  4916.8  416.86  4963.1  415.24
  4963.6  414.44  4968.6  414.44  4969.1  415.24  4990.3  416.16  5035.7  416.57
  5147.8  418.50  5179.3  418.65  5242.2  420.09  5252.7  419.98  5305.2  421.08
  5337.4  421.16  5369.0  422.18  5395.4  422.23  5440.4  423.34  5521.2  424.44
#Mann=3,-1,0
  4591.3     0.1       0  4963.1    0.07       0  4969.1     0.1       0
Bank Sta=4963.1,4969.1
Exp/Cntr=0.3,0.1

Type RM Length L Ch R = 1,4739,324,324,324
BEGIN DESCRIPTION:
Mapping XS 78cb9d14
END DESCRIPTION:
XS GIS Cut Line= 4
      2059590.83     13466786.78      2059326.98     13466717.35
      2058715.87     13466845.82      2058610.01     13467019.96
#Sta/Elev= 30
  4475.6  424.37  4540.0  422.41  4545.2  422.85  4580.4  421.60  4605.7  421.60
  4626.4  420.69  4655.8  420.24  4661.0  419.76  4736.5  418.60  4746.9  418.02
  4781.1  417.69  4808.3  416.62  4863.3  415.49  4944.6  414.53  4952.7  414.08
  5043.8  413.37  5044.3  412.57  5049.3  412.57  5049.8  413.37  5077.5  413.56
  5102.3  414.42  5220.5  416.39  5251.8  417.52  5346.4  418.82  5353.4  419.25
  5430.5  420.04  5460.5  420.87  5547.5  421.89  5570.9  422.02  5576.7  421.64
#Mann=3,-1,0
  4475.6     0.1       0  5043.8    0.07       0  5049.8     0.1       0
Bank Sta=5043.8,5049.8
Exp/Cntr=0.3,0.1

Type RM Length L Ch R = 1,4415,348,348,348
BEGIN DESCRIPTION:
Mapping XS 31e84510
END DESCRIPTION:
XS GIS Cut Line= 4
      2059563.06     13466585.39      2059375.59     13466474.29
      2058622.12     13466456.93      2058459.60     13466709.35
#Sta/Elev= 30
  4437.2  424.59  4465.7  423.39  4487.1  423.23  4502.7  422.30  4530.0  421.90
  4545.6  421.04  4597.7  419.61  4604.1  418.92  4641.1  417.60  4695.7  416.84
  4875.8  412.70  4982.8  410.99  4983.3  410.19  4988.3  410.19  4988.8  410.99
  5085.8  411.81  5125.8  411.20  5165.8  411.23  5355.9  414.42  5365.9  414.00
  5427.8  414.97  5464.1  414.61  5491.1  415.85  5506.3  415.64  5513.5  416.09
  5557.8  416.50  5651.6  419.17  5657.5  418.88  5703.1  419.64  5709.0  419.38
#Mann=3,-1,0
  4437.2     0.1       0  4982.8    0.07       0  4988.8     0.1       0
Bank Sta=4982.8,4988.8
Exp/Cntr=0.3,0.1

Type RM Length L Ch R = 1,4067,73,73,73
BEGIN DESCRIPTION:
Mapping XS b73005fc
END DESCRIPTION:
XS GIS Cut Line= 4
      2059708.96     13466429.17      2059211.45     13466185.93
      2058809.97     13466073.08      2058616.83     13466236.46
#Sta/Elev= 30
  4245.0  425.92  4305.1  424.49  4316.6  423.06  4333.5  422.71  4339.1  421.10
  4349.6  420.73  4356.1  419.58  4401.1  416.96  4446.1  416.65  4468.6  418.34
  4491.1  418.27  4697.0  413.38  4716.3  412.66  4721.9  413.36  4738.8  412.30
  4815.7  412.05  4820.9  411.05  4891.5  409.95  4992.5  408.25  5034.7  408.59
  5134.9  408.18  5135.4  407.38  5140.4  407.38  5140.9  408.18  5169.1  409.02
  5195.2  408.74  5280.9  409.34  5391.5  411.48  5447.4  411.80  5468.8  411.15
#Mann=8,-1,0
  4245.0     0.1       0  4697.0    0.08       0  4891.5     0.1       0
  5034.7    0.05       0  5134.9    0.07       0  5140.9    0.05       0
  5195.2    0.08       0  5280.9     0.1       0
Bank Sta=5134.9,5140.9
Exp/Cntr=0.3,0.1

Type RM Length L Ch R = 1,3994,508,508,508
BEGIN DESCRIPTION:
Mapping XS 4f72fdc4
END DESCRIPTION:
XS GIS Cut Line= 4
      2059847.81     13466068.04      2059209.28     13466105.64
      2058832.76     13466011.24      2058709.18     13465958.68
#Sta/Elev= 30
  4186.6  417.76  4259.5  419.66  4279.6  415.33  4299.6  414.97  4349.7  415.87
  4379.7  417.72  4439.8  417.09  4469.9  417.78  4520.0  416.71  4562.6  417.67
  4590.1  416.19  4630.2  416.47  4700.3  412.48  4732.8  412.44  4750.4  414.00
  4760.4  412.20  4813.3  410.31  5023.5  406.38  5024.0  405.58  5029.0  405.58
  5029.5  406.38  5094.8  407.78  5100.0  407.12  5136.0  407.73  5150.2  406.53
  5179.1  407.05  5217.5  407.37  5222.9  406.69  5320.7  408.19  5348.7  408.21
#Mann=6,-1,0
  4186.6     0.1       0  4813.3    0.05       0  5023.5    0.04       0
  5029.5    0.05       0  5179.1     0.1       0  5320.7    0.05       0
Bank Sta=5023.5,5029.5
Exp/Cntr=0.3,0.1

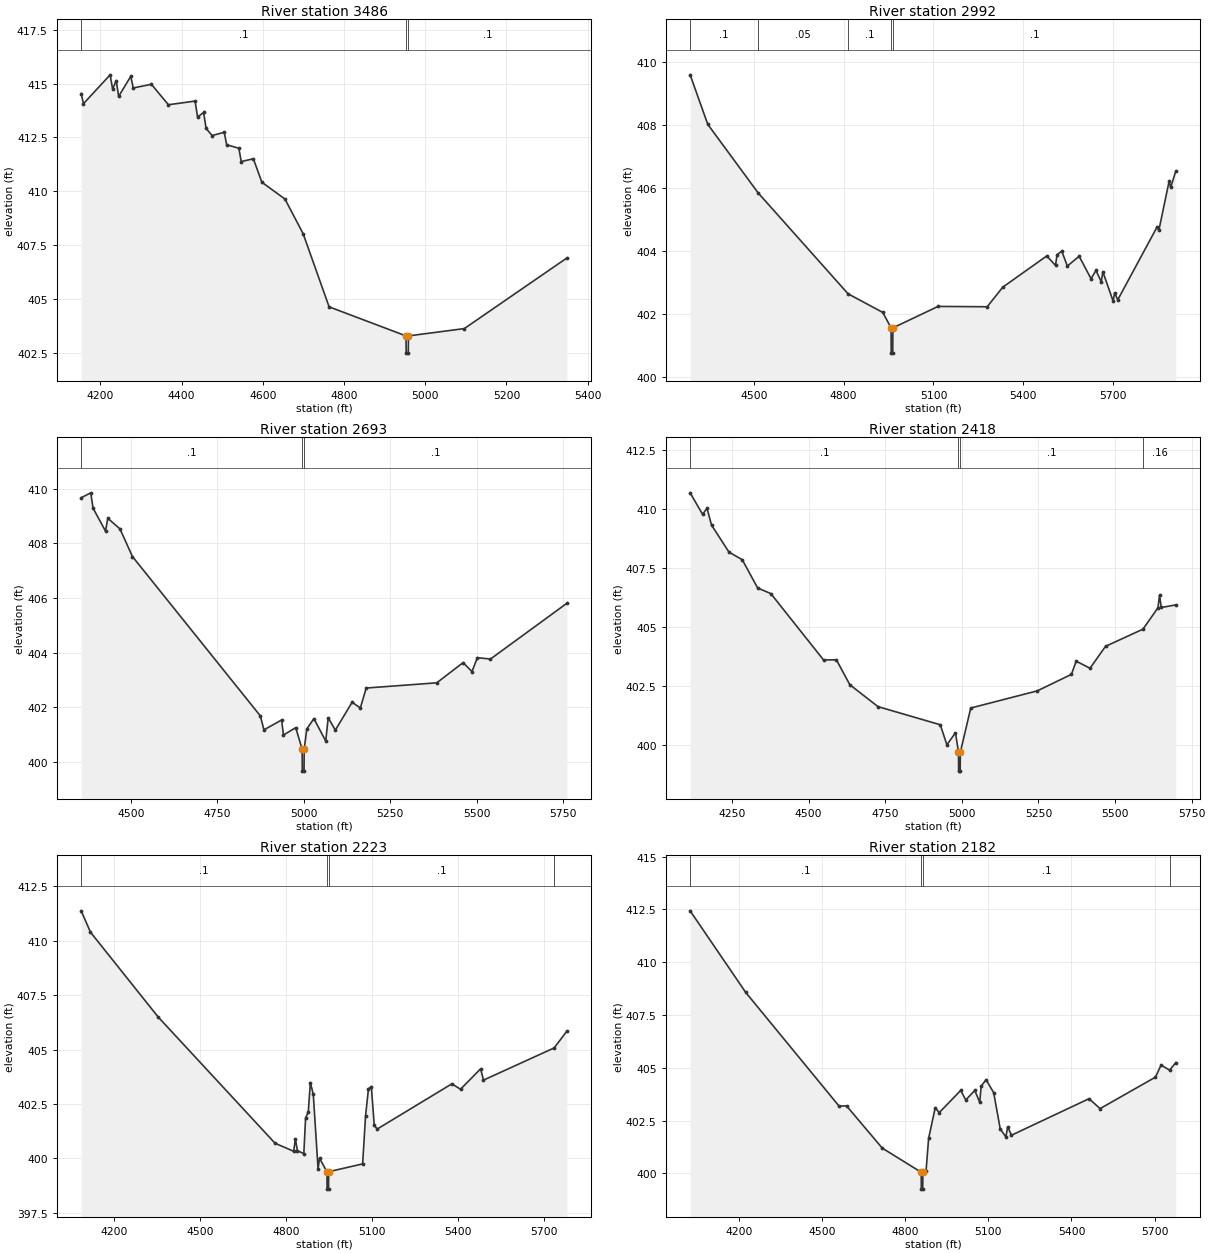
Type RM Length L Ch R = 1,3486,494,494,494
BEGIN DESCRIPTION:
Mapping XS 2388829f
END DESCRIPTION:
XS GIS Cut Line= 4
      2059868.68     13465960.43      2059356.85     13465609.76
      2058970.56     13465575.04      2058809.54     13465671.91
#Sta/Elev= 30
  4152.6  414.54  4158.2  414.07  4223.9  415.41  4230.0  414.75  4238.8  415.14
  4244.9  414.41  4274.7  415.34  4280.8  414.80  4325.5  414.97  4367.4  414.02
  4433.1  414.19  4439.2  413.45  4454.1  413.66  4460.2  412.92  4475.1  412.59
  4504.9  412.74  4510.9  412.16  4540.8  412.00  4546.8  411.38  4576.6  411.51
  4597.6  410.42  4654.4  409.64  4699.2  408.03  4763.2  404.63  4952.6  403.28
  4953.1  402.48  4958.1  402.48  4958.6  403.28  5096.2  403.62  5348.8  406.90
#Mann=3,-1,0
  4152.6     0.1       0  4952.6    0.07       0  4958.6     0.1       0
Bank Sta=4952.6,4958.6
Exp/Cntr=0.3,0.1

Type RM Length L Ch R = 1,2992,299,299,299
BEGIN DESCRIPTION:
Mapping XS 46273a6e
END DESCRIPTION:
XS GIS Cut Line= 4
      2060035.30     13465574.98      2059581.17     13465274.46
      2059165.80     13465182.01      2058538.25     13465355.90
#Sta/Elev= 30
  4287.6  409.58  4346.5  408.01  4514.5  405.84  4814.8  402.64  4930.7  402.05
  4958.4  401.56  4958.9  400.76  4963.9  400.76  4964.4  401.56  5115.1  402.24
  5279.3  402.23  5331.2  402.85  5478.2  403.84  5507.3  403.54  5512.5  403.88
  5528.3  403.99  5546.8  403.52  5586.3  403.83  5625.8  403.12  5642.5  403.38
  5660.1  403.02  5665.3  403.34  5699.6  402.41  5704.7  402.67  5715.1  402.45
  5847.1  404.77  5852.3  404.65  5886.6  406.21  5891.8  406.01  5908.9  406.53
#Mann=5,-1,0
  4287.6     0.1       0  4514.5    0.05       0  4814.8     0.1       0
  4958.4    0.07       0  4964.4     0.1       0
Bank Sta=4958.4,4964.4
Exp/Cntr=0.3,0.1

Type RM Length L Ch R = 1,2693,275,275,275
BEGIN DESCRIPTION:
Mapping XS e285861f
END DESCRIPTION:
XS GIS Cut Line= 4
      2060129.04     13465359.69      2059793.05     13465063.97
      2059132.53     13464894.43      2058870.65     13464976.62
#Sta/Elev= 30
  4356.8  409.67  4384.4  409.85  4391.0  409.29  4427.1  408.45  4433.7  408.92
  4468.9  408.53  4504.9  407.52  4874.7  401.69  4885.0  401.18  4936.2  401.54
  4941.4  400.99  4977.0  401.26  4995.5  400.47  4996.0  399.67  5001.0  399.67
  5001.5  400.47  5008.9  401.21  5029.5  401.59  5063.7  400.77  5070.8  401.62
  5091.5  401.17  5140.0  402.19  5163.7  401.98  5180.8  402.71  5384.6  402.90
  5460.9  403.64  5486.3  403.31  5502.2  403.82  5539.9  403.77  5760.8  405.81
#Mann=3,-1,0
  4356.8     0.1       0  4995.5    0.07       0  5001.5     0.1       0
Bank Sta=4995.5,5001.5
Exp/Cntr=0.3,0.1

Type RM Length L Ch R = 1,2418,195,195,195
BEGIN DESCRIPTION:
Mapping XS 1de2465f
END DESCRIPTION:
XS GIS Cut Line= 4
      2060250.62     13465297.25      2059906.98     13464829.60
      2059465.36     13464736.28      2058918.12     13464817.93
#Sta/Elev= 30
  4113.3  410.69  4153.8  409.78  4168.5  410.03  4183.1  409.32  4240.2  408.17
  4283.4  407.85  4333.6  406.65  4376.7  406.41  4548.8  403.59  4590.5  403.60
  4634.5  402.54  4726.3  401.61  4929.6  400.84  4951.2  399.99  4979.3  400.50
  4989.1  399.67  4989.6  398.87  4994.6  398.87  4995.1  399.67  5029.1  401.55
  5246.5  402.28  5357.7  402.98  5373.2  403.54  5418.4  403.24  5468.9  404.17
  5591.2  404.90  5640.2  405.81  5645.2  406.35  5650.9  405.82  5698.3  405.93
#Mann=4,-1,0
  4113.3     0.1       0  4989.1    0.07       0  4995.1     0.1       0
  5591.2    0.16       0
Bank Sta=4989.1,4995.1
Exp/Cntr=0.3,0.1

Type RM Length L Ch R = 1,2223,41,41,41
BEGIN DESCRIPTION:
Mapping XS 6a418ab5
END DESCRIPTION:
XS GIS Cut Line= 4
      2060340.85     13465293.71      2059874.43     13464655.98
      2059617.27     13464614.75      2058974.73     13464657.63
#Sta/Elev= 30
  4084.7  411.38  4117.0  410.40  4353.3  406.50  4761.0  400.70  4825.9  400.33
  4832.1  400.90  4838.8  400.36  4861.4  400.22  4867.6  401.86  4877.0  402.14
  4884.3  403.49  4894.5  402.94  4911.1  399.53  4916.2  400.01  4942.1  399.39
  4942.6  398.59  4947.6  398.59  4948.1  399.39  5066.6  399.75  5076.8  401.95
  5086.9  403.20  5097.0  403.30  5107.1  401.53  5117.3  401.35  5378.0  403.43
  5408.1  403.18  5478.3  404.12  5488.3  403.60  5734.9  405.08  5779.2  405.85
#Mann=4,-1,0
  4084.7     0.1       0  4942.1    0.07       0  4948.1     0.1       0
  5734.9    0.16       0
Bank Sta=4942.1,4948.1
Exp/Cntr=0.3,0.1

Type RM Length L Ch R = 1,2182,77,77,77
BEGIN DESCRIPTION:
Mapping XS a1b233bd
END DESCRIPTION:
XS GIS Cut Line= 4
      2060417.25     13465324.97      2059898.30     13464637.54
      2059617.27     13464580.03      2059011.68     13464596.86
#Sta/Elev= 30
  4022.9  412.43  4223.6  408.57  4560.7  403.19  4587.8  403.20  4716.8  401.20
  4857.4  400.06  4857.9  399.26  4862.9  399.26  4863.4  400.06  4874.9  400.11
  4884.2  401.66  4908.0  403.11  4922.6  402.88  4999.9  403.93  5018.4  403.48
  5050.9  403.93  5068.8  403.37  5073.9  404.13  5091.7  404.44  5119.3  403.82
  5142.8  402.11  5163.2  401.73  5169.7  402.21  5183.3  401.81  5463.5  403.54
  5503.5  403.07  5703.5  404.56  5723.6  405.13  5754.7  404.89  5776.9  405.25
#Mann=4,-1,0
  4022.9     0.1       0  4857.4    0.07       0  4863.4     0.1       0
  5754.7    0.16       0
Bank Sta=4857.4,4863.4
Exp/Cntr=0.3,0.1

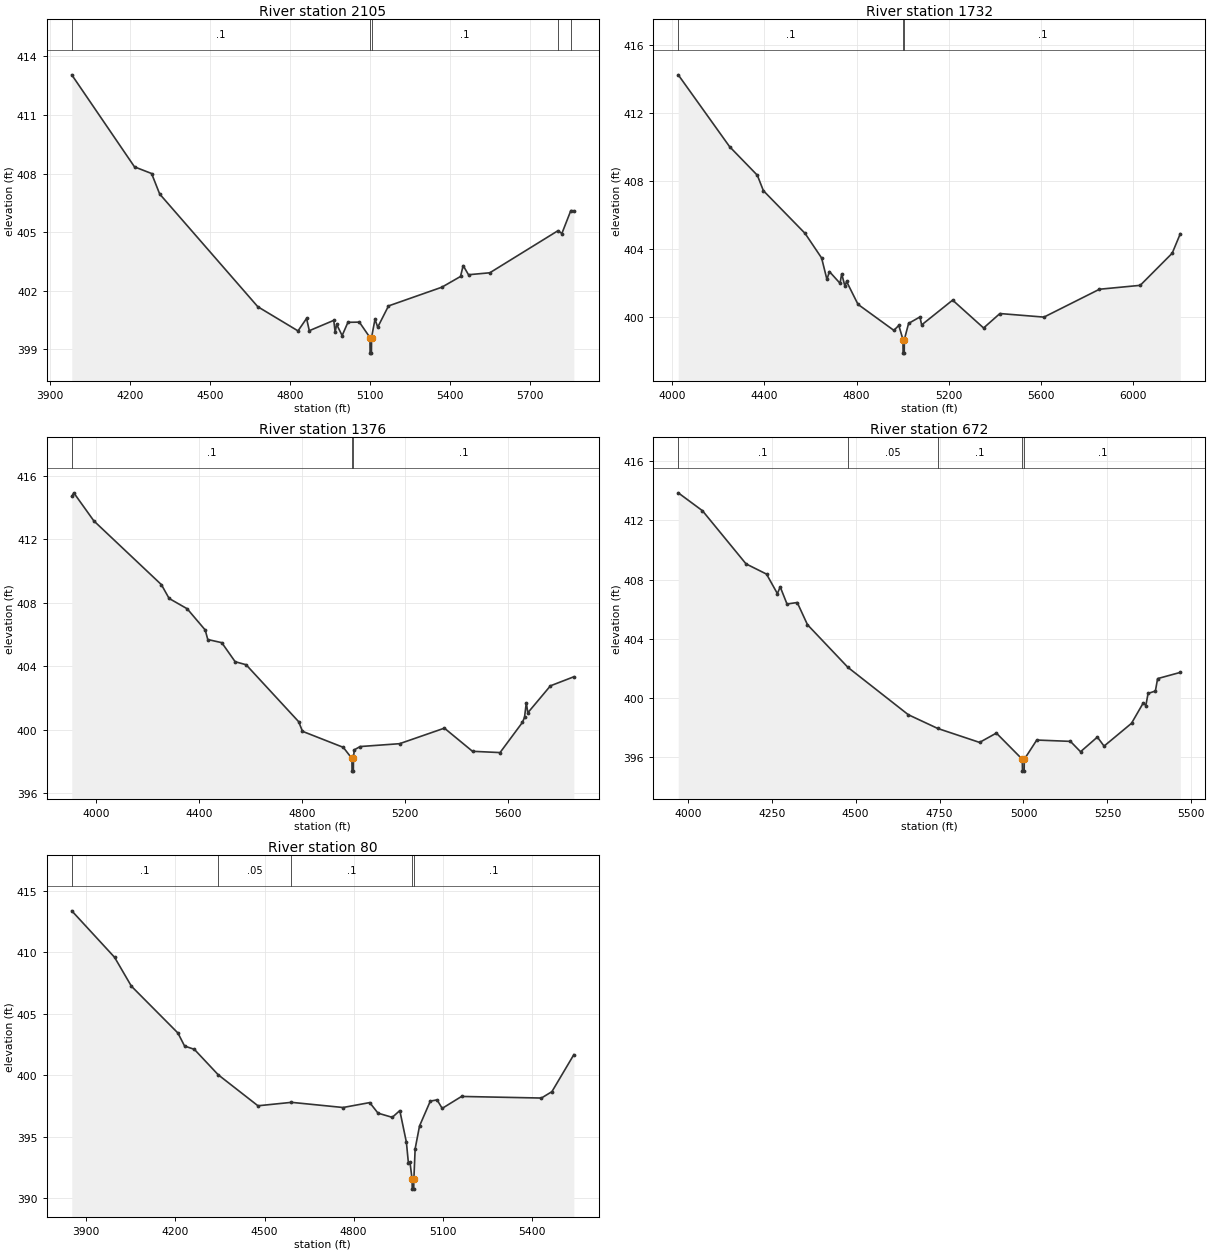
Type RM Length L Ch R = 1,2105,373,373,373
BEGIN DESCRIPTION:
Mapping XS 9a930e17
END DESCRIPTION:
XS GIS Cut Line= 4
      2060472.83     13465331.96      2059999.21     13464607.16
      2059711.67     13464540.97      2058989.98     13464536.10
#Sta/Elev= 30
  3980.8  413.06  4216.1  408.34  4280.1  408.00  4310.4  406.95  4678.3  401.17
  4829.1  399.93  4861.2  400.57  4871.5  399.94  4963.2  400.47  4968.3  399.87
  4974.1  400.26  4994.6  399.69  5016.3  400.37  5059.1  400.38  5098.9  399.59
  5099.4  398.79  5104.4  398.79  5104.9  399.59  5117.8  400.53  5128.0  400.12
  5168.4  401.21  5368.4  402.17  5438.4  402.72  5448.4  403.28  5468.4  402.81
  5548.4  402.91  5804.2  405.07  5818.4  404.92  5852.1  406.10  5863.4  406.09
#Mann=5,-1,0
  3980.8     0.1       0  5098.9    0.07       0  5104.9     0.1       0
  5804.2    0.16       0  5852.1     0.1       0
Bank Sta=5098.9,5104.9
Exp/Cntr=0.3,0.1

Type RM Length L Ch R = 1,1732,356,356,356
BEGIN DESCRIPTION:
Mapping XS 75b64fcf
END DESCRIPTION:
XS GIS Cut Line= 4
      2060618.63     13465356.20      2060410.31     13464734.71
      2059472.81     13463752.07      2059309.86     13463745.13
#Sta/Elev= 30
  4026.4  414.25  4249.2  410.02  4369.3  408.34  4395.6  407.43  4576.1  404.92
  4648.0  403.47  4671.0  402.21  4681.9  402.67  4727.8  401.98  4735.1  402.54
  4749.2  401.80  4756.1  402.09  4805.8  400.74  4961.2  399.21  4982.6  399.50
  5000.7  398.67  5001.2  397.87  5006.2  397.87  5006.7  398.67  5025.1  399.62
  5074.4  400.00  5081.7  399.53  5216.0  400.99  5350.3  399.35  5421.0  400.20
  5611.9  399.99  5852.6  401.63  6029.3  401.86  6167.9  403.75  6203.1  404.90
#Mann=3,-1,0
  4026.4     0.1       0  5000.7    0.07       0  5006.7     0.1       0
Bank Sta=5000.7,5006.7
Exp/Cntr=0.3,0.1

Type RM Length L Ch R = 1,1376,704,704,704
BEGIN DESCRIPTION:
Mapping XS 1fdc3056
END DESCRIPTION:
XS GIS Cut Line= 4
      2060726.28     13465352.81      2060750.59     13464772.90
      2060263.13     13463991.43      2060020.77     13463613.77
#Sta/Elev= 30
  3905.4  414.70  3913.2  414.93  3991.2  413.16  4253.5  409.14  4283.5  408.27
  4353.6  407.62  4423.7  406.28  4433.7  405.68  4488.1  405.48  4540.0  404.28
  4582.5  404.09  4786.6  400.50  4801.6  399.89  4960.0  398.88  4993.6  398.18
  4994.1  397.38  4999.1  397.38  4999.6  398.18  5002.5  398.72  5025.5  398.93
  5178.7  399.11  5352.8  400.09  5462.0  398.63  5569.0  398.55  5655.7  400.45
  5664.0  400.77  5670.9  401.69  5676.9  401.06  5764.7  402.76  5855.6  403.33
#Mann=3,-1,0
  3905.4     0.1       0  4993.6    0.07       0  4999.6     0.1       0
Bank Sta=4993.6,4999.6
Exp/Cntr=0.3,0.1

Type RM Length L Ch R = 1,672,592,592,592
BEGIN DESCRIPTION:
Mapping XS 4f0108c7
END DESCRIPTION:
XS GIS Cut Line= 4
      2061007.53     13465293.75      2061094.34     13464818.04
      2061037.27     13464003.55      2060891.41     13463873.31
#Sta/Elev= 30
  3971.6  413.86  4043.8  412.65  4173.6  409.06  4234.6  408.37  4267.0  407.05
  4275.3  407.51  4295.6  406.35  4326.1  406.45  4356.6  404.95  4477.1  402.07
  4657.0  398.87  4744.9  397.94  4869.2  397.00  4919.3  397.63  4996.5  395.86
  4997.0  395.06  5002.0  395.06  5002.5  395.86  5039.6  397.16  5139.9  397.07
  5170.0  396.37  5220.1  397.36  5240.1  396.75  5321.8  398.29  5356.9  399.67
  5364.5  399.49  5371.2  400.31  5392.9  400.47  5399.6  401.31  5467.2  401.73
#Mann=5,-1,0
  3971.6     0.1       0  4477.1    0.05       0  4744.9     0.1       0
  4996.5    0.07       0  5002.5     0.1       0
Bank Sta=4996.5,5002.5
Exp/Cntr=0.3,0.1

Type RM Length L Ch R = 1,80,0,0,0
BEGIN DESCRIPTION:
UNT 96 in Lagunillas Cr Wtrshd 2.0
END DESCRIPTION:
XS GIS Cut Line= 4
      2061114.12     13465314.90      2061592.67     13464345.87
      2061500.00     13464150.00      2061225.24     13463870.46
#Sta/Elev= 30
  3851.4  413.37  3995.4  409.59  4052.0  407.24  4208.6  403.43  4231.0  402.37
  4263.9  402.10  4344.3  400.03  4477.9  397.51  4590.7  397.79  4764.1  397.37
  4853.9  397.77  4881.9  396.91  4929.8  396.57  4955.2  397.12  4977.4  394.54
  4984.0  392.88  4989.6  392.90  4996.5  391.53  4997.0  390.73  5002.0  390.73
  5002.5  391.53  5006.8  394.01  5021.6  395.87  5057.8  397.89  5080.6  397.99
  5097.8  397.30  5163.0  398.27  5431.7  398.14  5467.0  398.66  5540.8  401.67
#Mann=5,-1,0
  3851.4     0.1       0  4344.3    0.05       0  4590.7     0.1       0
  4996.5    0.07       0  5002.5     0.1       0
Bank Sta=4996.5,5002.5
Exp/Cntr=0.3,0.1

Chan Stop Cuts=-1