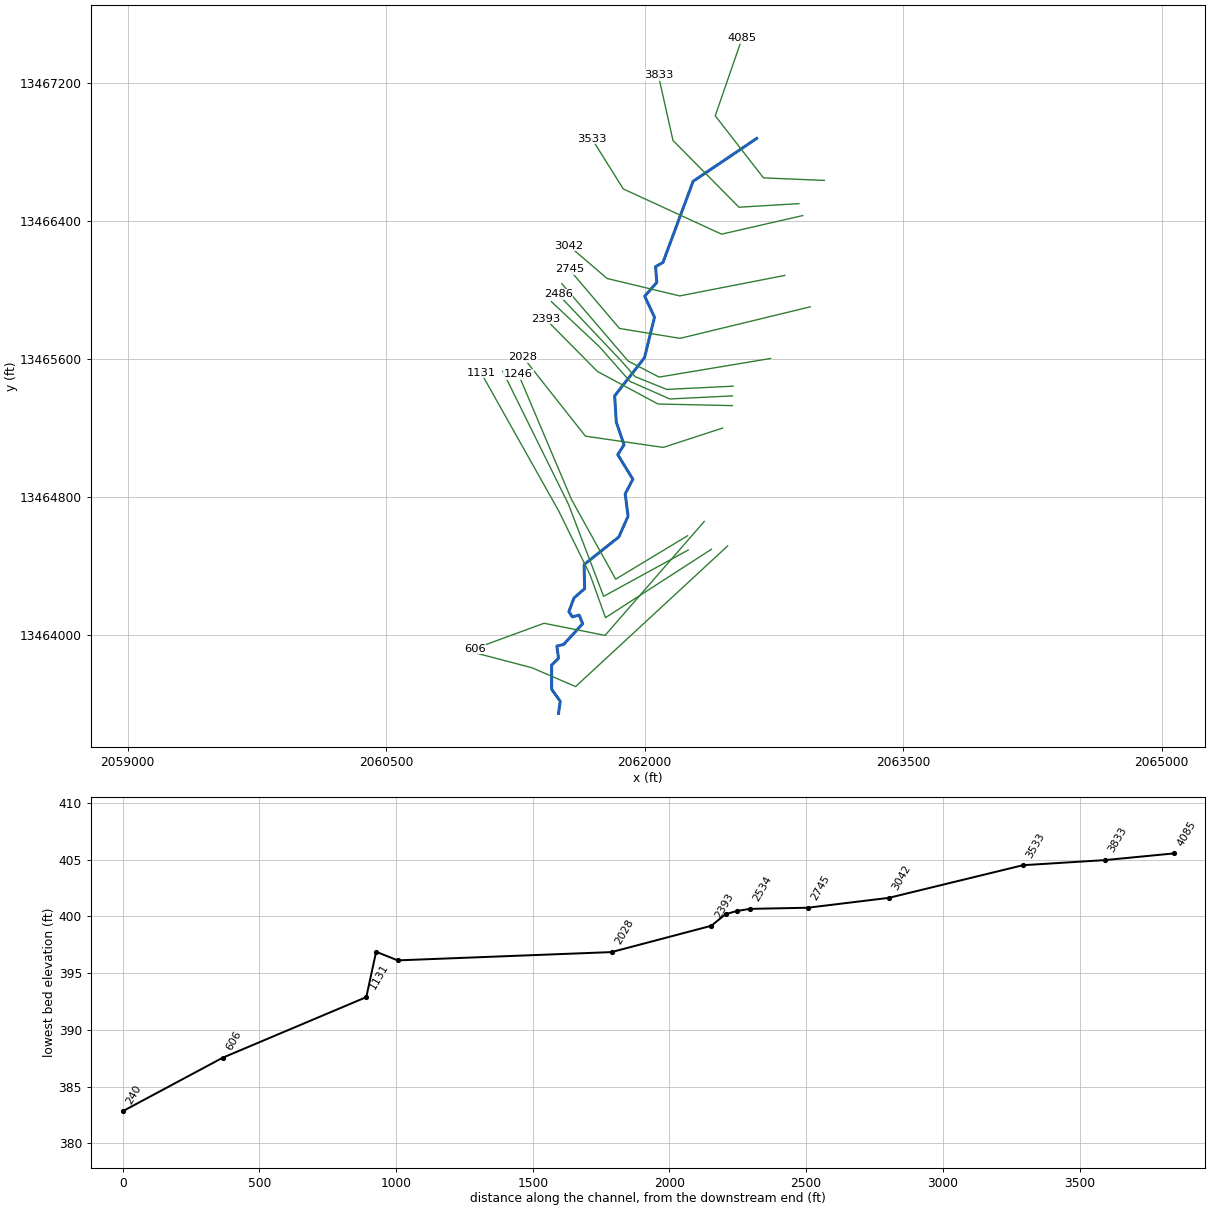
--- UNT 97 in Lagunillas Cr Wtrshd.prj (project) ---

Proj Title=UNT 97 in Lagunillas Cr Wtrshd Base Level Engineering
Current Plan=p01
Default Exp/Contr=0.3,0.1
English Units
Geom File=g01
Flow File=f01
Plan File=p01
BEGIN DESCRIPTION:
UNT 97 in Lagunillas Cr Wtrshd
END DESCRIPTION:

--- UNT 97 in Lagunillas Cr Wtrshd.p01 (plan) ---

Plan Title=Multiple Run
Short Identifier=Multiple
Geom File=g01
Flow File=f01
Subcritical Flow
K Sum by GR= 0
Std Step Tol= 0.01
Critical Tol= 0.01
Num of Std Step Trials= 20
Max Error Tol= 0.3
Flow Tol Ratio= 0.001
Split Flow NTrial= 30
Split Flow Tol= 0.02
Split Flow Ratio= 0.02
Log Output Level= 0
Friction Slope Method= 1
Unsteady Friction Slope Method= 2
Unsteady Bridges Friction Slope Method= 1
Parabolic Critical Depth
Global Vel Dist=  1 , 1 , 1
Global Log Level= 0
CheckData=True
Encroach Param= -1, 0, 0, 0
BEGIN DESCRIPTION:
Multiple Run
END DESCRIPTION:

--- UNT 97 in Lagunillas Cr Wtrshd.f01 (steady flow) ---

Flow Title=Multiple
Number of Profiles=7
Profile Names=10-year,25-year,50-year,1pct_min,100-year,1pct_plu,500-year
River Rch & RM= UNT 97 in Laguni,Reach-1,4085
     168     226     274     165     330     659     487
River Rch & RM= UNT 97 in Laguni,Reach-1,606
     230     317     389     238     475     947     717
Boundary for River Rch & Prof#=UNT 97 in Laguni,Reach-1,1
Up Type=0
Dn Type=3
Dn Slope=0.005
Boundary for River Rch & Prof#=UNT 97 in Laguni,Reach-1,2
Up Type=0
Dn Type=3
Dn Slope=0.005
Boundary for River Rch & Prof#=UNT 97 in Laguni,Reach-1,3
Up Type=0
Dn Type=3
Dn Slope=0.005
Boundary for River Rch & Prof#=UNT 97 in Laguni,Reach-1,4
Up Type=0
Dn Type=3
Dn Slope=0.005
Boundary for River Rch & Prof#=UNT 97 in Laguni,Reach-1,5
Up Type=0
Dn Type=3
Dn Slope=0.005
Boundary for River Rch & Prof#=UNT 97 in Laguni,Reach-1,6
Up Type=0
Dn Type=3
Dn Slope=0.005
Boundary for River Rch & Prof#=UNT 97 in Laguni,Reach-1,7
Up Type=0
Dn Type=3
Dn Slope=0.005

--- UNT 97 in Lagunillas Cr Wtrshd.g01 (geometry) ---

Geom Title=Existing Conditions

River Reach=UNT 97 in Laguni,Reach-1
Reach XY= 30
      2062650.49     13466879.75      2062281.74     13466631.14
      2062106.69     13466160.23      2062063.98     13466135.75
      2062070.80     13466044.54      2062000.80     13465964.54
      2062057.73     13465842.52      2061999.40     13465607.63
      2061826.48     13465386.27      2061835.85     13465234.19
      2061880.86     13465102.91      2061844.40     13465045.62
      2061931.90     13464902.91      2061887.63     13464817.49
      2061904.30     13464688.85      2061850.65     13464568.01
      2061649.09     13464407.60      2061652.26     13464267.79
      2061590.80     13464214.54      2061560.80     13464134.54
      2061580.80     13464104.54      2061620.80     13464114.54
      2061640.80     13464064.54      2061530.80     13463944.54
      2061490.80     13463934.54      2061500.80     13463864.54
      2061460.80     13463824.54      2061460.80     13463684.54
      2061510.80     13463614.54      2061500.80     13463544.54

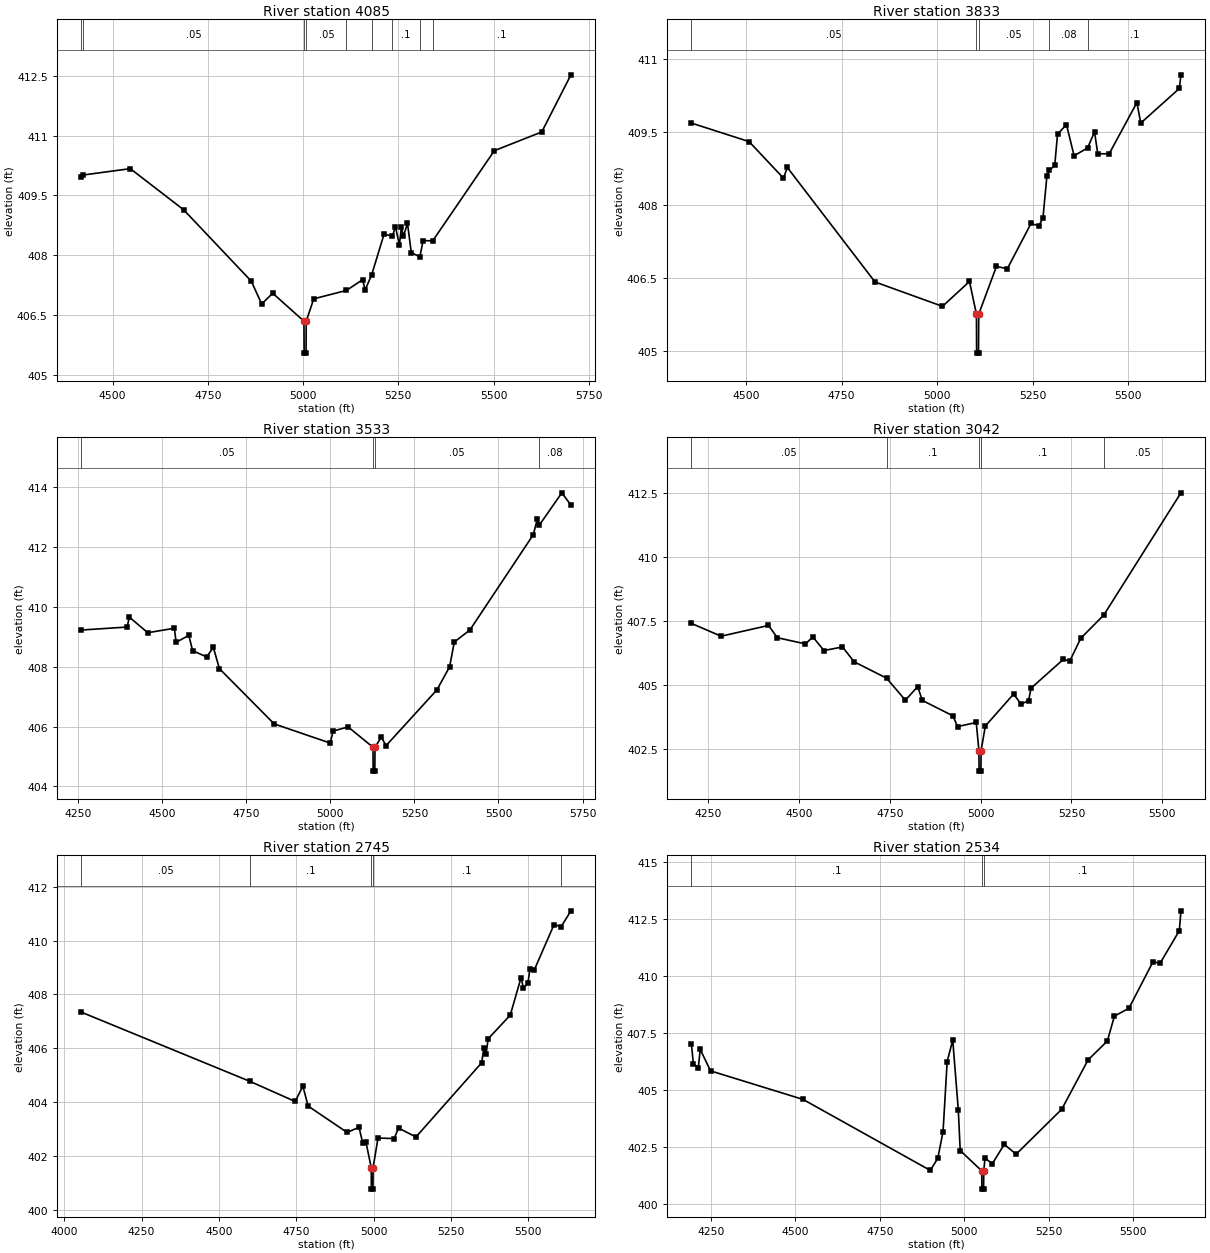
Type RM Length L Ch R = 1,4085,252,252,252
BEGIN DESCRIPTION:
UNT 97 in Lagunillas Cr Wtrshd 2.0
END DESCRIPTION:
XS GIS Cut Line= 4
      2063043.27     13466636.26      2062690.02     13466650.98
      2062410.07     13467011.22      2062565.68     13467460.44
#Sta/Elev= 30
  4418.0  409.97  4421.7  410.01  4546.4  410.17  4686.5  409.14  4864.2  407.35
  4891.3  406.78  4920.3  407.05  5002.3  406.35  5002.8  405.55  5007.8  405.55
  5008.3  406.35  5028.0  406.91  5113.8  407.12  5156.5  407.39  5162.8  407.13
  5180.1  407.51  5212.6  408.53  5234.7  408.48  5242.4  408.72  5252.9  408.26
  5258.2  408.71  5263.5  408.48  5274.1  408.80  5284.1  408.07  5306.6  407.96
  5315.2  408.37  5340.2  408.36  5502.1  410.62  5626.7  411.09  5703.2  412.52
#Mann=9,-1,0
  4418.0    0.08       0  4421.7    0.05       0  5002.3    0.03       0
  5008.3    0.05       0  5113.8    0.08       0  5180.1    0.05       0
  5234.7     0.1       0  5306.6    0.05       0  5340.2     0.1       0
Bank Sta=5002.3,5008.3
Exp/Cntr=0.3,0.1

Type RM Length L Ch R = 1,3833,300,300,300
BEGIN DESCRIPTION:
Mapping XS 8c7768eb
END DESCRIPTION:
XS GIS Cut Line= 4
      2062895.75     13466501.72      2062547.89     13466480.64
      2062164.86     13466868.01      2062079.87     13467247.65
#Sta/Elev= 30
  4356.4  409.68  4507.4  409.30  4597.6  408.55  4607.6  408.77  4837.3  406.42
  5014.1  405.92  5084.8  406.43  5103.0  405.76  5103.5  404.96  5108.5  404.96
  5109.0  405.76  5155.5  406.74  5183.8  406.69  5246.0  407.62  5266.9  407.57
  5277.3  407.74  5287.6  408.59  5293.8  408.71  5308.1  408.81  5315.4  409.45
  5338.8  409.65  5358.8  409.01  5394.2  409.17  5412.4  409.50  5420.8  409.05
  5450.7  409.05  5523.3  410.10  5533.5  409.68  5634.5  410.39  5638.7  410.67
#Mann=5,-1,0
  4356.4    0.05       0  5103.0    0.03       0  5109.0    0.05       0
  5293.8    0.08       0  5394.2     0.1       0
Bank Sta=5103,5109
Exp/Cntr=0.3,0.1

Type RM Length L Ch R = 1,3533,491,491,491
BEGIN DESCRIPTION:
Mapping XS b823b70a
END DESCRIPTION:
XS GIS Cut Line= 4
      2062917.45     13466432.28      2062446.98     13466324.39
      2061876.24     13466586.97      2061693.46     13466879.30
#Sta/Elev= 30
  4259.8  409.23  4395.7  409.33  4402.5  409.66  4457.3  409.14  4536.3  409.29
  4541.4  408.82  4579.2  409.05  4590.6  408.54  4632.3  408.33  4652.2  408.65
  4670.1  407.94  4833.0  406.09  4999.3  405.45  5008.8  405.85  5052.9  405.99
  5126.9  405.31  5127.4  404.51  5132.4  404.51  5132.9  405.31  5151.9  405.65
  5165.6  405.36  5317.1  407.23  5354.8  408.00  5368.7  408.83  5415.0  409.23
  5603.6  412.42  5616.1  412.96  5621.6  412.74  5688.5  413.82  5715.5  413.41
#Mann=4,-1,0
  4259.8    0.05       0  5126.9    0.03       0  5132.9    0.05       0
  5621.6    0.08       0
Bank Sta=5126.9,5132.9
Exp/Cntr=0.3,0.1

Type RM Length L Ch R = 1,3042,297,297,297
BEGIN DESCRIPTION:
Mapping XS 06c5f916
END DESCRIPTION:
XS GIS Cut Line= 4
      2062813.25     13466085.05      2062203.93     13465966.31
      2061782.92     13466067.23      2061559.42     13466258.21
#Sta/Elev= 30
  4203.9  407.40  4285.6  406.90  4416.1  407.32  4440.5  406.84  4517.9  406.60
  4538.3  406.87  4568.9  406.34  4619.8  406.48  4652.0  405.90  4741.2  405.26
  4793.0  404.40  4826.7  404.93  4839.8  404.39  4923.8  403.79  4936.7  403.37
  4988.1  403.53  4995.4  402.43  4995.9  401.63  5000.9  401.63  5001.4  402.43
  5013.0  403.39  5090.9  404.64  5111.5  404.25  5132.1  404.38  5139.0  404.87
  5228.2  406.00  5245.2  405.92  5275.9  406.82  5339.4  407.73  5551.6  412.50
#Mann=5,-1,0
  4203.9    0.05       0  4741.2     0.1       0  4995.4    0.07       0
  5001.4     0.1       0  5339.4    0.05       0
Bank Sta=4995.4,5001.4
Exp/Cntr=0.3,0.1

Type RM Length L Ch R = 1,2745,211,211,211
BEGIN DESCRIPTION:
Mapping XS 24ec1d2e
END DESCRIPTION:
XS GIS Cut Line= 4
      2062960.82     13465902.76      2062206.10     13465720.00
      2061854.53     13465777.51      2061563.25     13466119.76
#Sta/Elev= 30
  4055.6  407.34  4599.9  404.77  4746.5  404.02  4771.5  404.59  4788.3  403.85
  4914.3  402.87  4952.9  403.06  4965.0  402.47  4975.1  402.52  4992.4  401.56
  4992.9  400.76  4997.9  400.76  4998.4  401.56  5014.3  402.66  5066.3  402.64
  5080.7  403.03  5137.0  402.70  5349.4  405.46  5356.0  405.99  5363.7  405.80
  5370.3  406.35  5441.7  407.23  5476.8  408.63  5484.5  408.23  5498.8  408.43
  5505.4  408.94  5519.7  408.92  5583.3  410.60  5606.1  410.52  5637.8  411.11
#Mann=5,-1,0
  4055.6    0.05       0  4599.9     0.1       0  4992.4    0.07       0
  4998.4     0.1       0  5606.1    0.05       0
Bank Sta=4992.4,4998.4
Exp/Cntr=0.3,0.1

Type RM Length L Ch R = 1,2534,48,48,48
BEGIN DESCRIPTION:
Mapping XS 138d8a00
END DESCRIPTION:
XS GIS Cut Line= 4
      2062730.74     13465603.27      2062084.57     13465495.39
      2061904.45     13465588.71      2061519.95     13466037.17
#Sta/Elev= 30
  4192.4  407.01  4198.2  406.16  4212.8  405.98  4218.5  406.78  4248.9  405.84
  4522.7  404.59  4899.4  401.48  4921.5  402.01  4937.1  403.18  4949.3  406.25
  4965.8  407.19  4982.2  404.13  4987.9  402.35  5051.6  401.46  5052.1  400.66
  5057.1  400.66  5057.6  401.46  5061.2  402.01  5083.2  401.78  5118.3  402.62
  5153.4  402.19  5288.4  404.16  5366.3  406.32  5423.4  407.15  5444.3  408.24
  5487.1  408.58  5558.4  410.62  5579.3  410.55  5636.3  411.98  5641.1  412.85
#Mann=3,-1,0
  4192.4     0.1       0  5051.6    0.07       0  5057.6     0.1       0
Bank Sta=5051.6,5057.6
Exp/Cntr=0.3,0.1

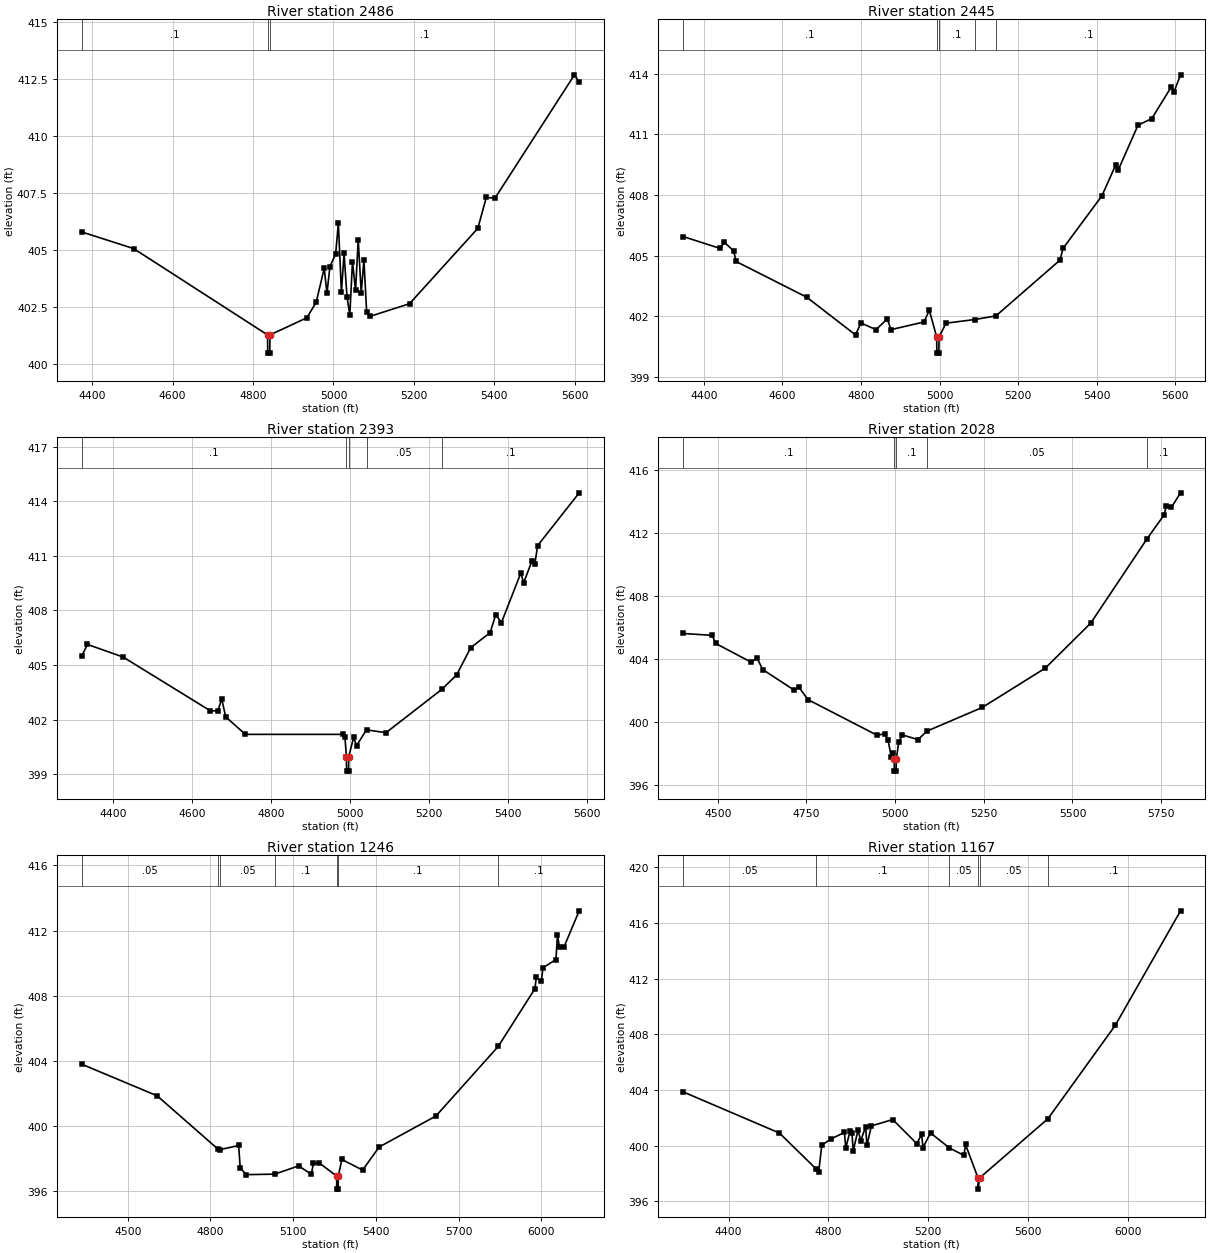
Type RM Length L Ch R = 1,2486,41,41,41
BEGIN DESCRIPTION:
Mapping XS ba441fe9
END DESCRIPTION:
XS GIS Cut Line= 5
      2062513.80     13465442.69      2062129.06     13465423.78
      2061945.68     13465497.56      2061861.04     13465593.05
      2061499.06     13465975.56
#Sta/Elev= 30
  4374.0  405.79  4503.0  405.06  4836.0  401.27  4836.5  400.47  4841.5  400.47
  4842.0  401.27  4933.6  402.02  4956.9  402.70  4977.0  404.20  4983.7  403.10
  4991.2  404.27  5005.4  404.83  5012.1  406.18  5019.7  403.15  5026.3  404.85
  5033.6  402.94  5040.6  402.15  5047.2  404.48  5054.8  403.22  5061.5  405.45
  5069.0  403.12  5075.7  404.56  5082.4  402.29  5090.0  402.08  5189.1  402.64
  5359.0  405.95  5380.1  407.31  5401.5  407.27  5599.3  412.69  5611.1  412.36
#Mann=3,-1,0
  4374.0     0.1       0  4836.0    0.07       0  4842.0     0.1       0
Bank Sta=4836,4842
Exp/Cntr=0.3,0.1

Type RM Length L Ch R = 1,2445,52,52,52
BEGIN DESCRIPTION:
Mapping XS 7a81aa3a
END DESCRIPTION:
XS GIS Cut Line= 5
      2062509.44     13465386.26      2062146.42     13465368.44
      2061915.30     13465470.44      2061739.52     13465670.09
      2061459.51     13465932.73
#Sta/Elev= 30
  4347.3  405.95  4441.9  405.36  4451.9  405.67  4476.0  405.24  4481.9  404.72
  4662.1  402.95  4786.1  401.09  4799.8  401.68  4838.2  401.35  4867.0  401.88
  4876.3  401.35  4960.3  401.73  4973.8  402.31  4992.6  400.99  4993.1  400.19
  4998.1  400.19  4998.6  400.99  5016.5  401.67  5089.4  401.85  5143.5  402.03
  5306.7  404.79  5314.0  405.36  5413.1  407.96  5448.3  409.49  5455.2  409.26
  5505.0  411.45  5540.2  411.78  5590.0  413.35  5596.8  413.11  5613.3  413.94
#Mann=5,-1,0
  4347.3     0.1       0  4992.6    0.07       0  4998.6     0.1       0
  5089.4    0.05       0  5143.5     0.1       0
Bank Sta=4992.6,4998.6
Exp/Cntr=0.3,0.1

Type RM Length L Ch R = 1,2393,365,365,365
BEGIN DESCRIPTION:
Mapping XS ac81f5a9
END DESCRIPTION:
XS GIS Cut Line= 4
      2062509.43     13465329.84      2062078.06     13465339.14
      2061726.50     13465527.95      2061424.36     13465833.31
#Sta/Elev= 30
  4321.3  405.50  4335.7  406.13  4425.8  405.44  4645.8  402.50  4665.8  402.47
  4675.8  403.14  4685.8  402.15  4735.8  401.19  4982.3  401.19  4988.0  401.04
  4991.6  399.97  4992.1  399.17  4997.1  399.17  4997.6  399.97  5009.9  401.02
  5017.3  400.57  5042.6  401.44  5091.9  401.28  5233.2  403.66  5271.0  404.46
  5306.4  405.95  5355.9  406.78  5370.0  407.77  5384.2  407.32  5433.6  410.06
  5440.7  409.52  5461.9  410.73  5469.0  410.55  5476.1  411.56  5581.4  414.46
#Mann=5,-1,0
  4321.3     0.1       0  4991.6    0.07       0  4997.6     0.1       0
  5042.6    0.05       0  5233.2     0.1       0
Bank Sta=4991.6,4997.6
Exp/Cntr=0.3,0.1

Type RM Length L Ch R = 1,2028,782,782,782
BEGIN DESCRIPTION:
Mapping XS f238d64d
END DESCRIPTION:
XS GIS Cut Line= 4
      2062452.99     13465199.63      2062108.44     13465087.41
      2061657.05     13465152.51      2061294.90     13465611.00
#Sta/Elev= 30
  4402.1  405.59  4484.1  405.47  4493.6  404.96  4594.6  403.76  4610.3  404.04
  4626.5  403.30  4715.5  401.99  4727.5  402.21  4754.2  401.39  4949.8  399.12
  4970.0  399.23  4980.1  398.81  4989.0  397.76  4994.0  398.02  4997.3  397.65
  4997.8  396.85  5002.8  396.85  5003.3  397.65  5010.4  398.71  5020.5  399.15
  5064.4  398.85  5089.6  399.39  5245.4  400.89  5423.4  403.39  5551.6  406.25
  5709.7  411.58  5758.4  413.12  5764.8  413.69  5779.2  413.60  5804.8  414.52
#Mann=5,-1,0
  4402.1     0.1       0  4997.3    0.07       0  5003.3     0.1       0
  5089.6    0.05       0  5709.7     0.1       0
Bank Sta=4997.3,5003.3
Exp/Cntr=0.3,0.1

Type RM Length L Ch R = 1,1246,79,79,79
BEGIN DESCRIPTION:
Mapping XS e65763f9
END DESCRIPTION:
XS GIS Cut Line= 4
      2062248.98     13464574.62      2061832.34     13464322.90
      2061575.87     13464785.53      2061268.55     13465511.07
#Sta/Elev= 30
  4333.3  403.79  4606.7  401.85  4826.9  398.58  4835.7  398.55  4902.1  398.80
  4907.8  397.42  4929.6  397.01  5033.1  397.04  5119.8  397.55  5165.5  397.03
  5173.4  397.71  5195.1  397.72  5257.4  396.92  5257.9  396.12  5262.9  396.12
  5263.4  396.92  5276.4  397.94  5351.5  397.29  5411.8  398.71  5617.5  400.61
  5843.2  404.88  5976.2  408.42  5981.6  409.12  5999.9  408.88  6005.3  409.71
  6052.7  410.22  6058.1  411.70  6065.2  411.01  6081.8  410.99  6137.0  413.21
#Mann=7,-1,0
  4333.3    0.05       0  4826.9     0.1       0  4835.7    0.05       0
  5033.1     0.1       0  5257.4   0.033       0  5263.4     0.1       0
  5843.2     0.1       0
Bank Sta=5257.4,5263.4
Exp/Cntr=0.3,0.1

Type RM Length L Ch R = 1,1167,36,36,36
BEGIN DESCRIPTION:
Mapping XS be4d960f
END DESCRIPTION:
XS GIS Cut Line= 4
      2062253.30     13464492.14      2061762.50     13464223.46
      2061558.51     13464757.31      2061176.97     13465529.46
#Sta/Elev= 30
  4218.1  403.87  4603.8  400.91  4749.7  398.35  4760.9  398.08  4773.4  400.03
  4809.3  400.48  4864.1  400.95  4869.5  399.84  4886.3  401.03  4894.2  400.93
  4899.5  399.63  4918.5  401.12  4929.6  400.36  4949.0  401.37  4954.3  400.02
  4972.0  401.42  5057.6  401.88  5154.1  400.15  5173.4  400.82  5178.8  399.86
  5208.9  400.92  5284.6  399.84  5343.1  399.30  5349.1  400.09  5399.3  397.68
  5399.8  396.88  5405.3  397.68  5679.3  401.94  5948.9  408.65  6210.4  416.88
#Mann=6,-1,0
  4218.1    0.05       0  4749.7     0.1       0  5284.6    0.05       0
  5399.3    0.07       0  5405.3    0.05       0  5679.3     0.1       0
Bank Sta=5399.3,5405.3
Exp/Cntr=0.3,0.1

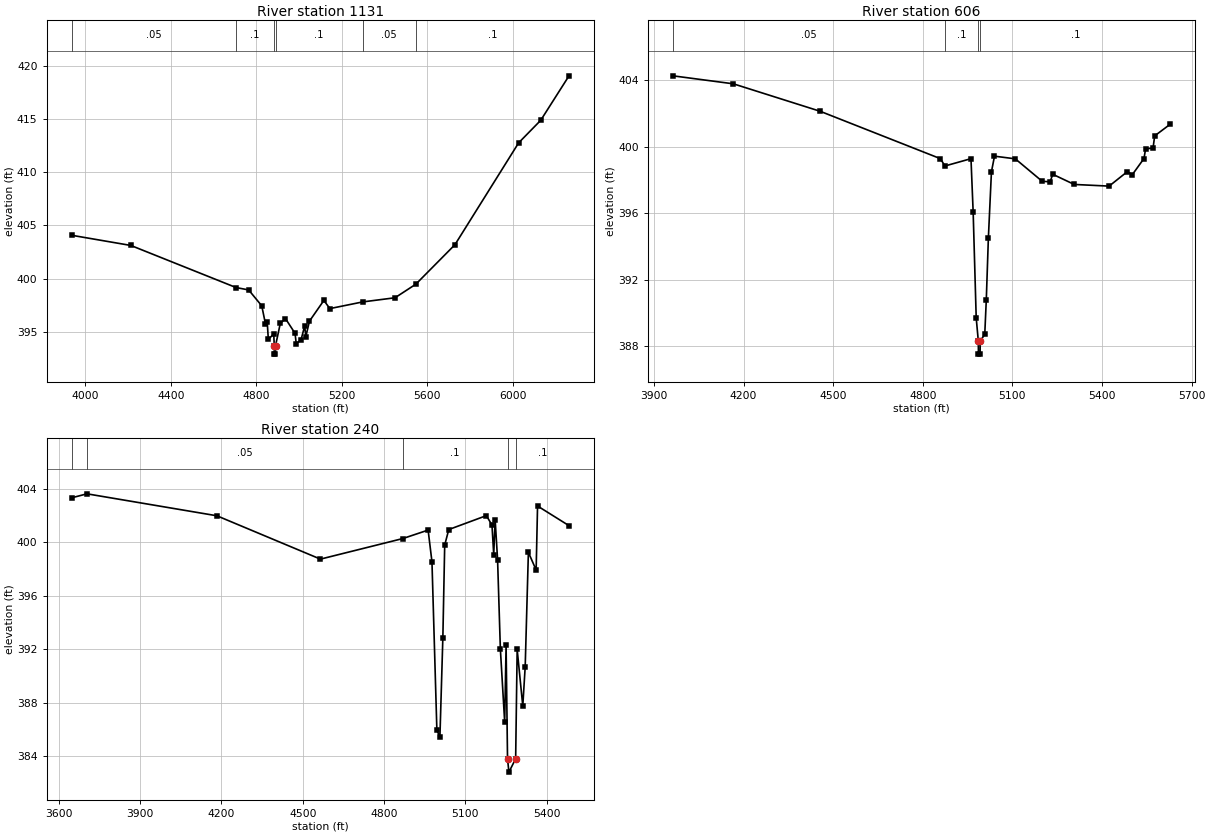
Type RM Length L Ch R = 1,1131,525,525,525
BEGIN DESCRIPTION:
Mapping XS f5c7308a
END DESCRIPTION:
XS GIS Cut Line= 5
      2062387.93     13464496.53      2061773.35     13464099.76
      2061684.37     13464347.16      2061502.08     13464718.25
      2061051.33     13465520.38
#Sta/Elev= 30
  3935.0  404.08  4212.3  403.12  4705.3  399.15  4763.8  398.93  4825.2  397.43
  4842.1  395.76  4850.6  395.94  4855.9  394.27  4881.3  394.78  4883.6  393.68
  4884.1  392.88  4889.1  392.88  4889.6  393.68  4912.0  395.78  4936.0  396.23
  4980.9  394.84  4986.5  393.87  5009.0  394.23  5025.9  395.53  5031.5  394.54
  5048.4  395.99  5115.8  397.94  5143.9  397.17  5297.9  397.80  5448.7  398.19
  5546.2  399.47  5729.2  403.19  6027.4  412.79  6130.6  414.91  6263.0  419.10
#Mann=6,-1,0
  3935.0    0.05       0  4705.3     0.1       0  4883.6    0.07       0
  4889.6     0.1       0  5297.9    0.05       0  5546.2     0.1       0
Bank Sta=4883.6,4889.6
Exp/Cntr=0.3,0.1

Type RM Length L Ch R = 1,606,366,366,366
BEGIN DESCRIPTION:
Mapping XS 2b33a62d
END DESCRIPTION:
XS GIS Cut Line= 4
      2062346.43     13464658.07      2061770.83     13463996.88
      2061416.67     13464067.19      2061015.26     13463920.17
#Sta/Elev= 30
  3963.7  404.27  4165.8  403.79  4456.3  402.14  4859.0  399.29  4874.1  398.85
  4961.3  399.29  4968.6  396.08  4978.8  389.72  4985.8  388.34  4986.3  387.54
  4991.8  387.54  4992.3  388.34  5007.4  388.72  5012.5  390.77  5019.6  394.55
  5029.8  398.50  5040.0  399.44  5109.7  399.28  5199.7  397.93  5226.1  397.90
  5235.1  398.35  5307.0  397.74  5423.7  397.64  5484.7  398.51  5501.4  398.33
  5540.4  399.30  5545.7  399.87  5570.9  399.94  5576.2  400.66  5628.9  401.37
#Mann=4,-1,0
  3963.7    0.05       0  4874.1     0.1       0  4985.8    0.07       0
  4992.3     0.1       0
Bank Sta=4985.8,4992.3
Exp/Cntr=0.3,0.1

Type RM Length L Ch R = 1,240,0,0,0
BEGIN DESCRIPTION:
UNT 97 in Lagunillas Cr Wtrshd 1.0
END DESCRIPTION:
XS GIS Cut Line= 4
      2062481.90     13464515.76      2061600.00     13463700.00
      2061345.82     13463809.47      2060999.96     13463900.01
#Sta/Elev= 30
  3647.1  403.32  3704.1  403.62  4183.3  401.98  4565.5  398.74  4869.9  400.28
  4962.8  400.91  4977.0  398.54  4995.1  385.97  5006.3  385.42  5017.2  392.88
  5024.0  399.79  5039.0  400.95  5177.7  401.99  5198.4  401.29  5204.9  399.08
  5210.1  401.70  5219.1  398.70  5229.4  392.02  5245.3  386.56  5250.5  392.29
  5255.8  383.82  5260.9  382.82  5285.8  383.82  5291.4  391.99  5312.1  387.76
  5321.0  390.70  5332.8  399.25  5361.4  397.92  5366.6  402.71  5482.7  401.24
#Mann=5,-1,0
  3647.1     0.1       0  3704.1    0.05       0  4869.9     0.1       0
  5255.8    0.07       0  5285.8     0.1       0
Bank Sta=5255.8,5285.8
Exp/Cntr=0.3,0.1

Chan Stop Cuts=-1