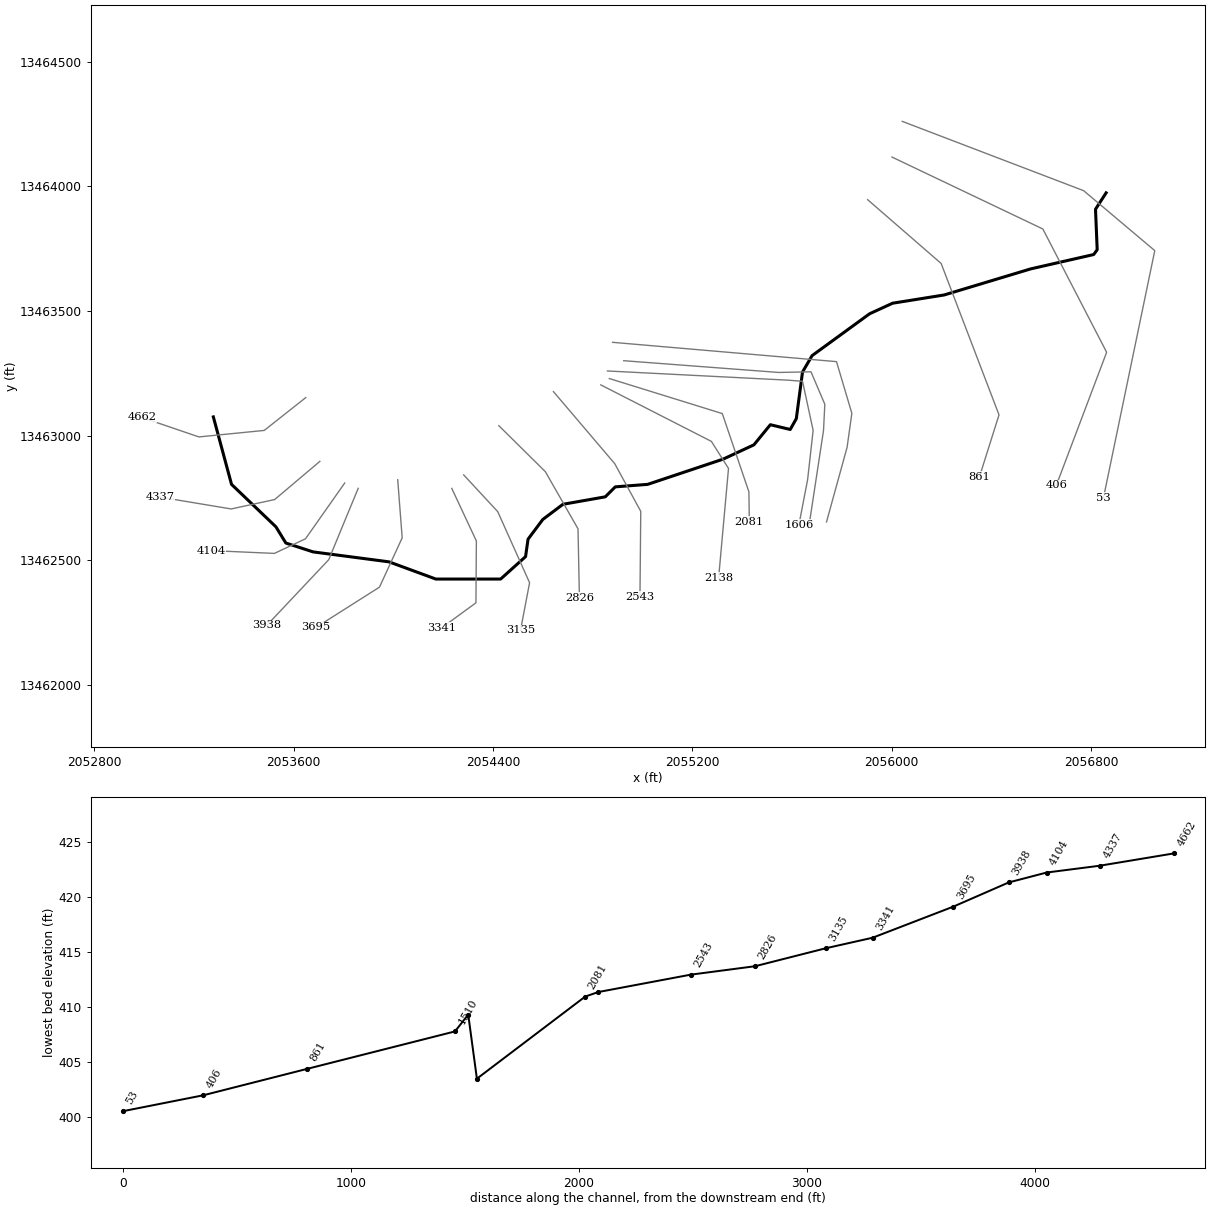
--- UNT 98 in Lagunillas Cr Wtrshd.prj (project) ---

Proj Title=UNT 98 in Lagunillas Cr Wtrshd Base Level Engineering
Current Plan=p01
Default Exp/Contr=0.3,0.1
English Units
Geom File=g01
Flow File=f01
Plan File=p01
BEGIN DESCRIPTION:
UNT 98 in Lagunillas Cr Wtrshd
END DESCRIPTION:

--- UNT 98 in Lagunillas Cr Wtrshd.p01 (plan) ---

Plan Title=Multiple Run
Short Identifier=Multiple
Geom File=g01
Flow File=f01
Subcritical Flow
K Sum by GR= 0
Std Step Tol= 0.01
Critical Tol= 0.01
Num of Std Step Trials= 20
Max Error Tol= 0.3
Flow Tol Ratio= 0.001
Split Flow NTrial= 30
Split Flow Tol= 0.02
Split Flow Ratio= 0.02
Log Output Level= 0
Friction Slope Method= 1
Unsteady Friction Slope Method= 2
Unsteady Bridges Friction Slope Method= 1
Parabolic Critical Depth
Global Vel Dist=  1 , 1 , 1
Global Log Level= 0
CheckData=True
Encroach Param= -1, 0, 0, 0
BEGIN DESCRIPTION:
Multiple Run
END DESCRIPTION:

--- UNT 98 in Lagunillas Cr Wtrshd.f01 (steady flow) ---

Flow Title=Multiple
Number of Profiles=7
Profile Names=10-year,25-year,50-year,1pct_min,100-year,1pct_plu,500-year
River Rch & RM= UNT 98 in Laguni,Reach-1,4662
      56      70      80      46      93     185     125
Boundary for River Rch & Prof#=UNT 98 in Laguni,Reach-1,1
Up Type=0
Dn Type=3
Dn Slope=0.005
Boundary for River Rch & Prof#=UNT 98 in Laguni,Reach-1,2
Up Type=0
Dn Type=3
Dn Slope=0.005
Boundary for River Rch & Prof#=UNT 98 in Laguni,Reach-1,3
Up Type=0
Dn Type=3
Dn Slope=0.005
Boundary for River Rch & Prof#=UNT 98 in Laguni,Reach-1,4
Up Type=0
Dn Type=3
Dn Slope=0.005
Boundary for River Rch & Prof#=UNT 98 in Laguni,Reach-1,5
Up Type=0
Dn Type=3
Dn Slope=0.005
Boundary for River Rch & Prof#=UNT 98 in Laguni,Reach-1,6
Up Type=0
Dn Type=3
Dn Slope=0.005
Boundary for River Rch & Prof#=UNT 98 in Laguni,Reach-1,7
Up Type=0
Dn Type=3
Dn Slope=0.005

--- UNT 98 in Lagunillas Cr Wtrshd.g01 (geometry) ---

Geom Title=Existing Conditions

River Reach=UNT 98 in Laguni,Reach-1
Reach XY= 30
      2053277.82     13463075.32      2053350.80     13462804.54
      2053528.86     13462634.21      2053568.79     13462569.11
      2053678.16     13462533.52      2053982.85     13462493.59
      2054170.80     13462424.54      2054430.80     13462424.54
      2054530.80     13462514.54      2054540.80     13462584.54
      2054600.04     13462663.72      2054680.80     13462724.54
      2054850.80     13462754.54      2054890.80     13462794.54
      2055020.80     13462804.54      2055323.99     13462905.91
      2055447.26     13462963.20      2055513.23     13463043.93
      2055593.09     13463024.84      2055617.40     13463068.24
      2055642.34     13463255.41      2055680.76     13463321.21
      2055911.66     13463489.27      2056003.89     13463531.58
      2056210.76     13463564.65      2056558.36     13463669.39
      2056810.90     13463726.91      2056824.97     13463746.18
      2056818.20     13463908.68      2056860.80     13463974.54

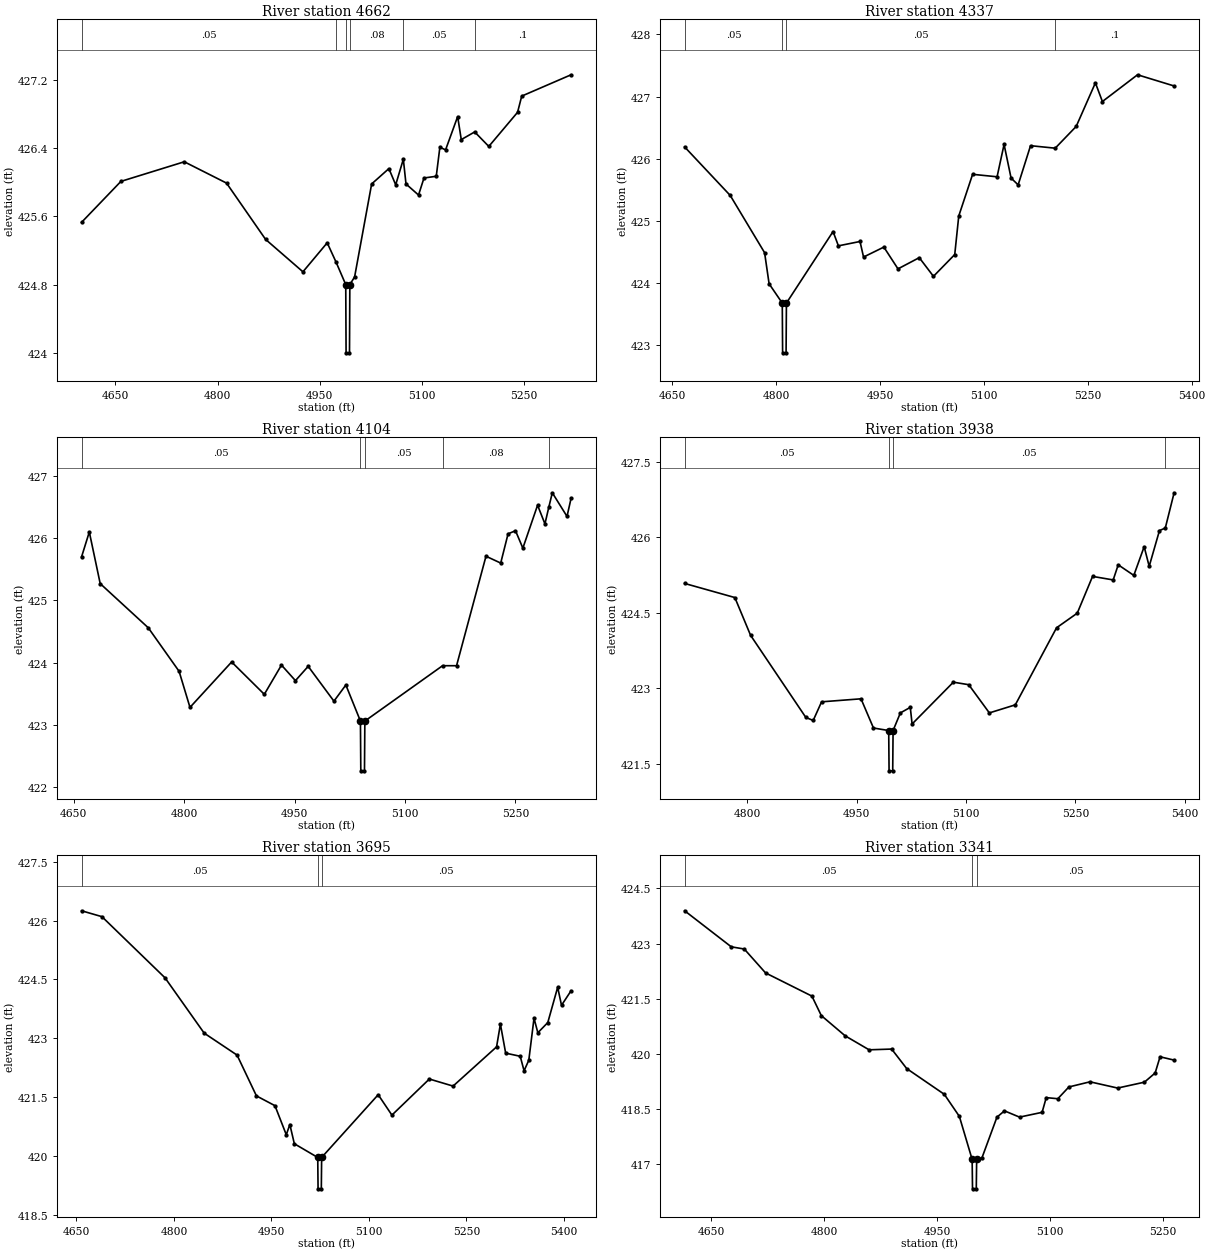
Type RM Length L Ch R = 1,4662,325,325,325
BEGIN DESCRIPTION:
UNT 98 in Lagunillas Cr Wtrshd 2.0
END DESCRIPTION:
XS GIS Cut Line= 4
      2053648.86     13463152.91      2053482.03     13463021.03
      2053219.87     13462994.99      2052990.73     13463073.11
#Sta/Elev= 30
  4600.5  425.53  4658.2  426.01  4751.2  426.24  4813.2  425.99  4870.5  425.33
  4925.3  424.95  4960.9  425.29  4974.1  425.06  4988.1  424.80  4988.6  424.00
  4993.6  424.00  4994.1  424.80  5001.1  424.89  5026.1  425.98  5051.4  426.16
  5061.4  425.97  5072.6  426.27  5076.5  425.98  5094.9  425.85  5102.9  426.05
  5120.9  426.07  5126.2  426.41  5134.6  426.38  5152.3  426.77  5157.6  426.50
  5177.3  426.59  5198.0  426.42  5240.2  426.82  5246.3  427.01  5318.7  427.26
#Mann=6,-1,0
  4600.5    0.05       0  4974.1    0.08       0  4988.1    0.07       0
  4994.1    0.08       0  5072.6    0.05       0  5177.3     0.1       0
Bank Sta=4988.1,4994.1
Exp/Cntr=0.3,0.1

Type RM Length L Ch R = 1,4337,233,233,233
BEGIN DESCRIPTION:
Mapping XS a63bcc1e
END DESCRIPTION:
XS GIS Cut Line= 4
      2053705.28     13462896.84      2053523.95     13462743.63
      2053349.47     13462705.87      2053062.92     13462753.57
#Sta/Elev= 30
  4668.2  426.19  4734.0  425.41  4783.6  424.49  4790.1  423.99  4809.1  423.68
  4809.6  422.88  4814.6  422.88  4815.1  423.68  4882.4  424.83  4890.1  424.60
  4921.3  424.67  4926.4  424.42  4955.7  424.58  4976.1  424.23  5006.8  424.41
  5027.3  424.11  5058.0  424.46  5063.8  425.08  5083.8  425.75  5119.1  425.71
  5129.2  426.23  5139.3  425.69  5149.5  425.58  5167.4  426.21  5203.0  426.17
  5233.3  426.52  5261.0  427.22  5271.1  426.92  5321.8  427.35  5374.6  427.17
#Mann=4,-1,0
  4668.2    0.05       0  4809.1    0.03       0  4815.1    0.05       0
  5203.0     0.1       0
Bank Sta=4809.1,4815.1
Exp/Cntr=0.3,0.1

Type RM Length L Ch R = 1,4104,166,166,166
BEGIN DESCRIPTION:
Mapping XS 49ab0925
END DESCRIPTION:
XS GIS Cut Line= 4
      2053805.05     13462809.97      2053647.65     13462586.08
      2053522.65     13462527.48      2053269.53     13462538.71
#Sta/Elev= 30
  4660.6  425.70  4671.1  426.10  4685.9  425.27  4751.2  424.56  4793.1  423.86
  4807.9  423.28  4864.5  424.01  4908.9  423.49  4932.2  423.96  4951.2  423.71
  4968.5  423.94  5003.5  423.38  5019.7  423.64  5039.5  423.06  5040.0  422.26
  5045.0  422.26  5045.5  423.06  5151.1  423.95  5170.1  423.95  5210.1  425.71
  5230.1  425.60  5240.1  426.07  5250.2  426.12  5260.2  425.84  5280.2  426.53
  5290.2  426.23  5295.5  426.50  5300.2  426.73  5320.2  426.35  5325.7  426.64
#Mann=5,-1,0
  4660.6    0.05       0  5039.5    0.03       0  5045.5    0.05       0
  5151.1    0.08       0  5295.5     0.1       0
Bank Sta=5039.5,5045.5
Exp/Cntr=0.3,0.1

Type RM Length L Ch R = 1,3938,243,243,243
BEGIN DESCRIPTION:
Mapping XS 3cf75125
END DESCRIPTION:
XS GIS Cut Line= 4
      2053859.18     13462788.66      2053806.14     13462660.56
      2053741.10     13462502.46      2053492.72     13462239.11
#Sta/Elev= 30
  4713.8  425.08  4782.7  424.80  4804.3  424.05  4880.1  422.42  4890.2  422.36
  4901.7  422.73  4955.8  422.79  4972.9  422.21  4993.8  422.16  4994.3  421.36
  4999.3  421.36  4999.8  422.16  5009.8  422.51  5023.4  422.62  5025.9  422.29
  5082.5  423.12  5103.6  423.07  5131.9  422.51  5167.5  422.67  5224.1  424.20
  5252.5  424.49  5273.5  425.22  5301.8  425.15  5308.7  425.45  5330.1  425.24
  5344.3  425.81  5351.2  425.42  5365.3  426.13  5373.3  426.18  5385.4  426.88
#Mann=4,-1,0
  4713.8    0.05       0  4993.8    0.03       0  4999.8    0.05       0
  5373.3    0.08       0
Bank Sta=4993.8,4999.8
Exp/Cntr=0.3,0.1

Type RM Length L Ch R = 1,3695,354,354,354
BEGIN DESCRIPTION:
Mapping XS 88c3a6dc
END DESCRIPTION:
XS GIS Cut Line= 4
      2054017.75     13462823.04      2054035.67     13462589.98
      2053944.53     13462392.07      2053690.08     13462230.59
#Sta/Elev= 30
  4658.0  426.25  4689.3  426.10  4786.4  424.54  4846.6  423.13  4897.2  422.57
  4927.0  421.53  4955.5  421.28  4972.9  420.54  4978.4  420.80  4985.3  420.31
  5021.3  419.96  5021.8  419.16  5026.8  419.16  5027.3  419.96  5114.3  421.56
  5135.4  421.04  5193.0  421.96  5229.5  421.78  5296.4  422.78  5302.3  423.36
  5310.4  422.62  5332.8  422.54  5338.7  422.17  5346.0  422.44  5354.0  423.51
  5359.9  423.14  5375.2  423.40  5390.4  424.30  5396.3  423.84  5411.0  424.21
#Mann=3,-1,0
  4658.0    0.05       0  5021.3    0.03       0  5027.3    0.05       0
Bank Sta=5021.3,5027.3
Exp/Cntr=0.3,0.1

Type RM Length L Ch R = 1,3341,206,206,206
BEGIN DESCRIPTION:
Mapping XS ea74d6c5
END DESCRIPTION:
XS GIS Cut Line= 4
      2054234.76     13462788.30      2054333.42     13462577.40
      2054331.68     13462329.13      2054194.64     13462229.22
#Sta/Elev= 30
  4614.3  423.89  4676.3  422.91  4693.6  422.85  4721.9  422.20  4783.5  421.57
  4796.0  421.04  4827.7  420.49  4859.5  420.11  4889.5  420.13  4909.5  419.60
  4959.5  418.90  4979.5  418.30  4996.5  417.13  4997.0  416.33  5002.0  416.33
  5002.5  417.13  5009.5  417.17  5029.5  418.28  5039.5  418.45  5059.5  418.28
  5089.5  418.41  5095.0  418.81  5110.4  418.78  5125.1  419.10  5153.2  419.24
  5189.9  419.07  5225.5  419.23  5239.8  419.48  5246.3  419.92  5265.0  419.83
#Mann=3,-1,0
  4614.3    0.05       0  4996.5    0.03       0  5002.5    0.05       0
Bank Sta=4996.5,5002.5
Exp/Cntr=0.3,0.1

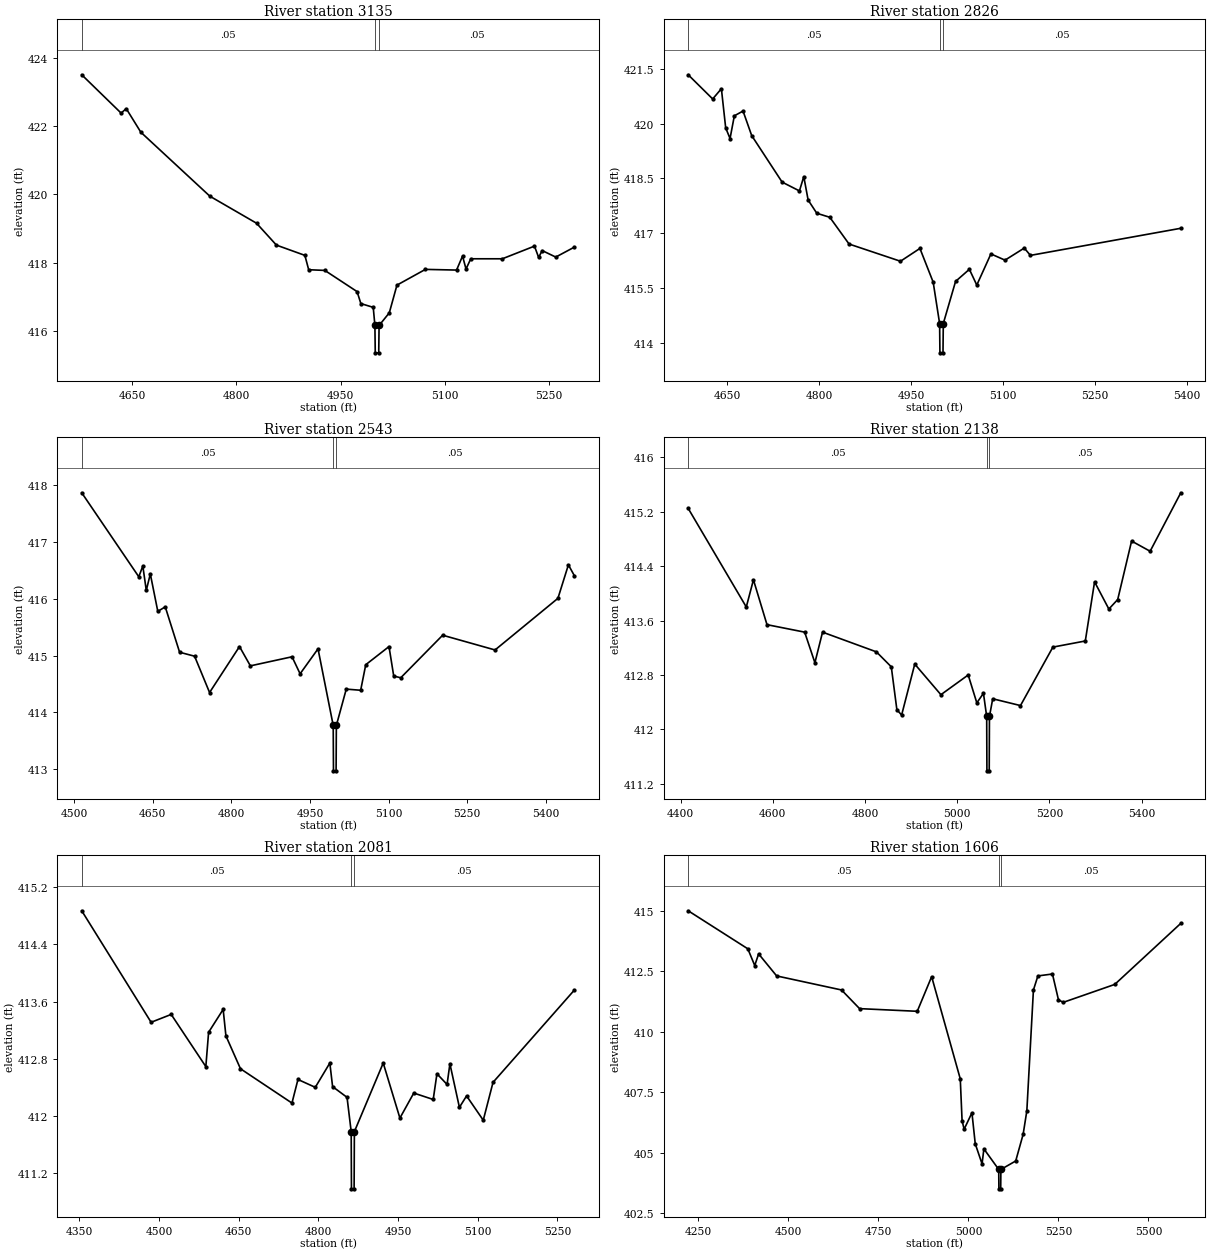
Type RM Length L Ch R = 1,3135,309,309,309
BEGIN DESCRIPTION:
Mapping XS 58641cf8
END DESCRIPTION:
XS GIS Cut Line= 4
      2054282.48     13462842.59      2054419.22     13462694.99
      2054546.96     13462409.86      2054510.59     13462218.73
#Sta/Elev= 30
  4577.8  423.50  4634.4  422.38  4641.8  422.51  4662.8  421.82  4762.0  419.95
  4829.1  419.16  4857.7  418.52  4898.6  418.22  4904.1  417.80  4927.3  417.78
  4973.7  417.16  4979.1  416.81  4996.9  416.70  4999.3  416.17  4999.8  415.37
  5004.8  415.37  5005.3  416.17  5020.0  416.54  5031.0  417.35  5071.9  417.81
  5116.7  417.79  5125.3  418.20  5130.3  417.82  5137.1  418.12  5182.5  418.12
  5228.7  418.49  5234.7  418.16  5239.8  418.36  5259.3  418.17  5286.0  418.46
#Mann=3,-1,0
  4577.8    0.05       0  4999.3    0.03       0  5005.3    0.05       0
Bank Sta=4999.3,5005.3
Exp/Cntr=0.3,0.1

Type RM Length L Ch R = 1,2826,283,283,283
BEGIN DESCRIPTION:
Mapping XS ff4f9384
END DESCRIPTION:
XS GIS Cut Line= 4
      2054423.59     13463040.01      2054610.20     13462855.58
      2054741.40     13462626.01      2054746.91     13462349.95
#Sta/Elev= 30
  4586.7  421.33  4626.6  420.67  4640.8  420.95  4647.8  419.88  4654.9  419.59
  4661.9  420.21  4676.1  420.34  4690.2  419.67  4739.8  418.40  4768.0  418.16
  4775.1  418.55  4782.2  417.91  4796.3  417.55  4817.5  417.44  4848.9  416.71
  4932.7  416.24  4964.4  416.59  4986.0  415.67  4996.5  414.54  4997.0  413.74
  5002.0  413.74  5002.5  414.54  5022.5  415.69  5045.0  416.02  5057.1  415.59
  5080.1  416.44  5103.1  416.27  5134.5  416.60  5144.5  416.40  5389.6  417.14
#Mann=3,-1,0
  4586.7    0.05       0  4996.5    0.03       0  5002.5    0.05       0
Bank Sta=4996.5,5002.5
Exp/Cntr=0.3,0.1

Type RM Length L Ch R = 1,2543,405,405,405
BEGIN DESCRIPTION:
Mapping XS f885d1bb
END DESCRIPTION:
XS GIS Cut Line= 4
      2054642.73     13463176.77      2054888.97     13462887.29
      2054993.14     13462696.32      2054989.99     13462353.71
#Sta/Elev= 30
  4514.3  417.87  4623.2  416.39  4630.9  416.58  4637.5  416.15  4645.2  416.44
  4659.5  415.78  4673.7  415.86  4701.1  415.06  4729.7  414.99  4758.3  414.35
  4815.4  415.16  4836.2  414.82  4915.7  414.98  4931.1  414.68  4965.3  415.12
  4994.3  413.77  4994.8  412.97  4999.8  412.97  5000.3  413.77  5019.2  414.41
  5046.7  414.39  5056.4  414.84  5100.8  415.16  5109.8  414.64  5123.2  414.61
  5203.2  415.36  5303.2  415.10  5423.2  416.01  5443.2  416.60  5454.5  416.41
#Mann=3,-1,0
  4514.3    0.05       0  4994.3    0.03       0  5000.3    0.05       0
Bank Sta=4994.3,5000.3
Exp/Cntr=0.3,0.1

Type RM Length L Ch R = 1,2138,57,57,57
BEGIN DESCRIPTION:
Mapping XS 17532cd9
END DESCRIPTION:
XS GIS Cut Line= 4
      2054832.76     13463203.76      2055276.62     13462977.02
      2055345.32     13462868.48      2055305.59     13462428.74
#Sta/Elev= 30
  4416.7  415.25  4542.7  413.80  4558.2  414.20  4587.6  413.54  4669.3  413.43
  4691.5  412.98  4708.1  413.43  4824.9  413.14  4857.2  412.92  4869.3  412.29
  4879.6  412.21  4908.1  412.96  4964.8  412.51  5024.0  412.80  5042.7  412.39
  5057.1  412.53  5064.1  412.19  5064.6  411.39  5069.6  411.39  5070.1  412.19
  5077.2  412.45  5137.4  412.35  5207.7  413.21  5278.0  413.30  5298.1  414.17
  5329.1  413.77  5348.3  413.91  5378.4  414.77  5418.6  414.62  5485.1  415.48
#Mann=3,-1,0
  4416.7    0.05       0  5064.1    0.03       0  5070.1    0.05       0
Bank Sta=5064.1,5070.1
Exp/Cntr=0.3,0.1

Type RM Length L Ch R = 1,2081,475,475,475
BEGIN DESCRIPTION:
Mapping XS db7c0f45
END DESCRIPTION:
XS GIS Cut Line= 4
      2054867.05     13463229.22      2055320.39     13463088.68
      2055427.17     13462774.45      2055428.90     13462653.77
#Sta/Elev= 30
  4354.7  414.87  4485.3  413.31  4523.1  413.42  4588.3  412.69  4593.5  413.17
  4620.9  413.49  4626.1  413.12  4653.5  412.66  4750.4  412.18  4761.7  412.51
  4794.3  412.40  4821.7  412.74  4826.9  412.41  4854.1  412.26  4861.9  411.78
  4862.4  410.98  4867.4  410.98  4867.9  411.78  4922.2  412.74  4953.6  411.97
  4979.7  412.32  5016.3  412.23  5023.3  412.59  5042.4  412.44  5047.7  412.73
  5065.6  412.12  5079.1  412.28  5110.5  411.94  5128.9  412.47  5281.9  413.76
#Mann=3,-1,0
  4354.7    0.05       0  4861.9    0.03       0  4867.9    0.05       0
Bank Sta=4861.9,4867.9
Exp/Cntr=0.3,0.1

Type RM Length L Ch R = 1,1606,38,38,38
BEGIN DESCRIPTION:
Mapping XS ca2e34b2
END DESCRIPTION:
XS GIS Cut Line= 6
      2054859.63     13463259.61      2055584.49     13463222.72
      2055642.44     13463218.11      2055684.98     13463021.06
      2055662.71     13462823.02      2055628.00     13462642.95
#Sta/Elev= 30
  4221.6  414.99  4387.2  413.42  4406.4  412.73  4417.2  413.21  4467.3  412.30
  4647.5  411.72  4697.6  410.95  4857.8  410.84  4897.8  412.27  4977.3  408.05
  4982.3  406.33  4988.0  405.97  5009.7  406.65  5018.9  405.37  5037.8  404.54
  5042.9  405.16  5084.1  404.31  5084.6  403.51  5089.6  403.51  5090.1  404.31
  5131.3  404.66  5151.9  405.76  5162.2  406.73  5180.5  411.72  5192.9  412.30
  5233.3  412.38  5250.1  411.31  5263.5  411.21  5406.4  411.95  5589.8  414.47
#Mann=3,-1,0
  4221.6    0.05       0  5084.1    0.03       0  5090.1    0.05       0
Bank Sta=5084.1,5090.1
Exp/Cntr=0.3,0.1

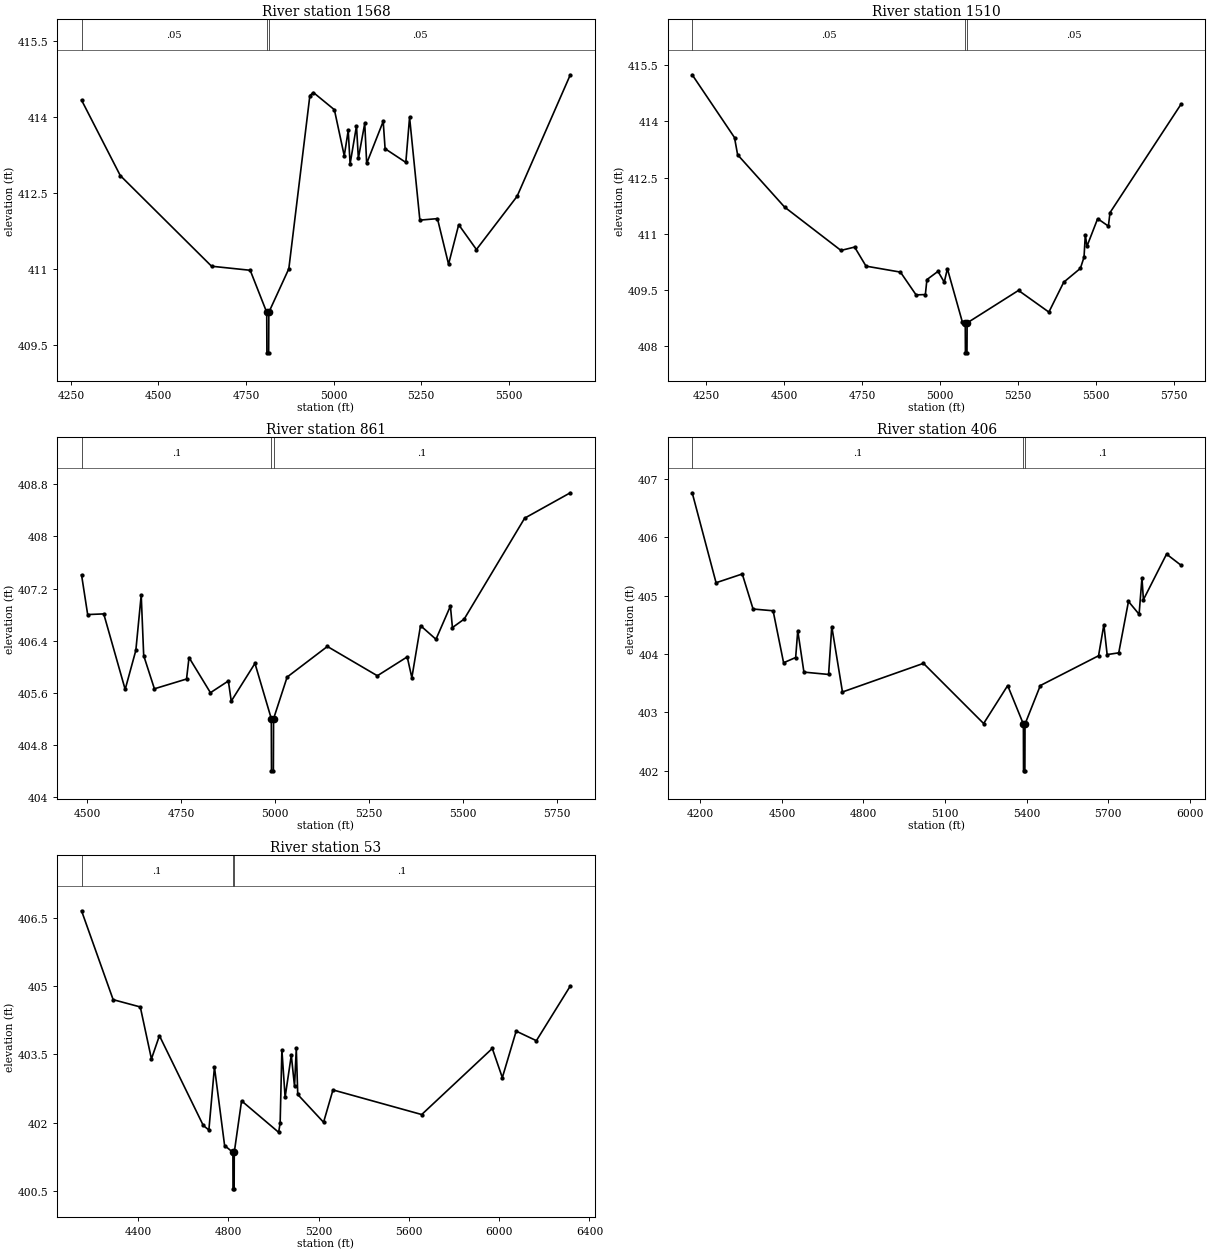
Type RM Length L Ch R = 1,1568,58,58,58
BEGIN DESCRIPTION:
Mapping XS 9bfb5fae
END DESCRIPTION:
XS GIS Cut Line= 6
      2054924.76     13463300.84      2055546.85     13463253.68
      2055676.30     13463256.30      2055731.85     13463126.10
      2055726.64     13463021.06      2055667.06     13462629.95
#Sta/Elev= 30
  4280.5  414.33  4391.1  412.84  4651.8  411.05  4762.1  410.97  4809.3  410.14
  4809.8  409.34  4814.8  409.34  4815.3  410.14  4872.4  411.00  4932.5  414.42
  4942.5  414.48  5002.5  414.14  5030.7  413.23  5042.0  413.73  5047.4  413.07
  5065.6  413.82  5071.0  413.18  5089.2  413.87  5094.7  413.08  5141.9  413.91
  5147.3  413.37  5206.5  413.10  5217.2  413.99  5246.6  411.96  5296.8  411.99
  5328.5  411.09  5357.5  411.87  5408.1  411.38  5524.2  412.43  5676.2  414.83
#Mann=3,-1,0
  4280.5    0.05       0  4809.3    0.03       0  4815.3    0.05       0
Bank Sta=4809.3,4815.3
Exp/Cntr=0.3,0.1

Type RM Length L Ch R = 1,1510,649,649,649
BEGIN DESCRIPTION:
Mapping XS 98fd0ac3
END DESCRIPTION:
XS GIS Cut Line= 5
      2054879.89     13463374.63      2055778.73     13463297.10
      2055840.36     13463089.64      2055821.26     13462953.35
      2055738.67     13462653.74
#Sta/Elev= 30
  4204.9  415.25  4340.5  413.57  4350.5  413.11  4501.1  411.71  4681.8  410.55
  4725.6  410.64  4762.1  410.13  4872.5  409.97  4922.7  409.36  4952.4  409.37
  4957.4  409.77  4992.9  409.99  5013.0  409.70  5023.0  410.06  5070.8  408.64
  5080.3  408.61  5080.8  407.81  5085.8  407.81  5086.3  408.61  5251.0  409.48
  5348.4  408.90  5396.0  409.70  5449.4  410.07  5461.1  410.37  5465.2  410.97
  5470.4  410.66  5504.8  411.40  5539.2  411.20  5544.3  411.56  5771.9  414.46
#Mann=3,-1,0
  4204.9    0.05       0  5080.3    0.03       0  5086.3    0.05       0
Bank Sta=5080.3,5086.3
Exp/Cntr=0.3,0.1

Type RM Length L Ch R = 1,861,455,455,455
BEGIN DESCRIPTION:
Mapping XS d740c3c6
END DESCRIPTION:
XS GIS Cut Line= 4
      2055903.61     13463947.15      2056198.74     13463691.08
      2056430.94     13463083.44      2056352.81     13462836.01
#Sta/Elev= 30
  4485.5  407.41  4501.8  406.80  4544.6  406.81  4601.6  405.65  4630.0  406.25
  4644.3  407.10  4650.9  406.17  4679.4  405.66  4764.9  405.81  4771.5  406.14
  4828.5  405.60  4876.2  405.78  4883.9  405.47  4947.0  406.05  4990.5  405.20
  4991.0  404.40  4996.0  404.40  4996.5  405.20  5032.6  405.84  5139.7  406.31
  5272.7  405.86  5352.2  406.15  5364.5  405.83  5387.6  406.63  5428.7  406.42
  5467.1  406.93  5472.5  406.60  5503.7  406.73  5664.7  408.28  5786.2  408.67
#Mann=3,-1,0
  4485.5     0.1       0  4990.5    0.07       0  4996.5     0.1       0
Bank Sta=4990.5,4996.5
Exp/Cntr=0.3,0.1

Type RM Length L Ch R = 1,406,353,353,353
BEGIN DESCRIPTION:
Mapping XS 282a4da2
END DESCRIPTION:
XS GIS Cut Line= 4
      2056001.39     13464118.12      2056606.83     13463829.51
      2056862.90     13463334.71      2056661.07     13462800.83
#Sta/Elev= 30
  4169.7  406.76  4257.5  405.22  4353.9  405.37  4393.7  404.77  4467.4  404.74
  4506.0  403.85  4550.4  403.94  4558.1  404.40  4580.8  403.69  4671.6  403.65
  4683.3  404.47  4722.6  403.35  5020.7  403.84  5242.1  402.81  5330.6  403.46
  5388.4  402.80  5388.9  402.00  5393.9  402.00  5394.4  402.80  5450.7  403.46
  5665.0  403.97  5684.5  404.50  5696.6  403.99  5739.3  404.02  5775.1  404.90
  5814.2  404.68  5824.7  405.30  5830.1  404.93  5915.2  405.71  5968.3  405.52
#Mann=3,-1,0
  4169.7     0.1       0  5388.4    0.07       0  5394.4     0.1       0
Bank Sta=5388.4,5394.4
Exp/Cntr=0.3,0.1

Type RM Length L Ch R = 1,53,0,0,0
BEGIN DESCRIPTION:
UNT 98 in Lagunillas Cr Wtrshd 1.0
END DESCRIPTION:
XS GIS Cut Line= 4
      2056042.62     13464261.35      2056770.65     13463983.19
      2057056.04     13463742.70      2056850.01     13462750.03
#Sta/Elev= 30
  4148.8  406.65  4288.9  404.70  4409.2  404.54  4458.6  403.40  4494.0  403.91
  4688.4  401.94  4713.2  401.84  4737.9  403.22  4782.9  401.50  4819.7  401.35
  4820.2  400.55  4825.2  400.55  4825.7  401.35  4858.1  402.48  5022.5  401.79
  5029.1  402.00  5036.8  403.60  5051.1  402.56  5078.5  403.48  5092.8  402.80
  5100.6  403.63  5107.1  402.62  5221.5  402.01  5263.2  402.72  5656.5  402.18
  5969.4  403.63  6013.9  402.99  6075.2  404.01  6164.8  403.80  6315.2  405.00
#Mann=3,-1,0
  4148.8     0.1       0  4819.7    0.07       0  4825.7     0.1       0
Bank Sta=4819.7,4825.7
Exp/Cntr=0.3,0.1

Chan Stop Cuts=-1