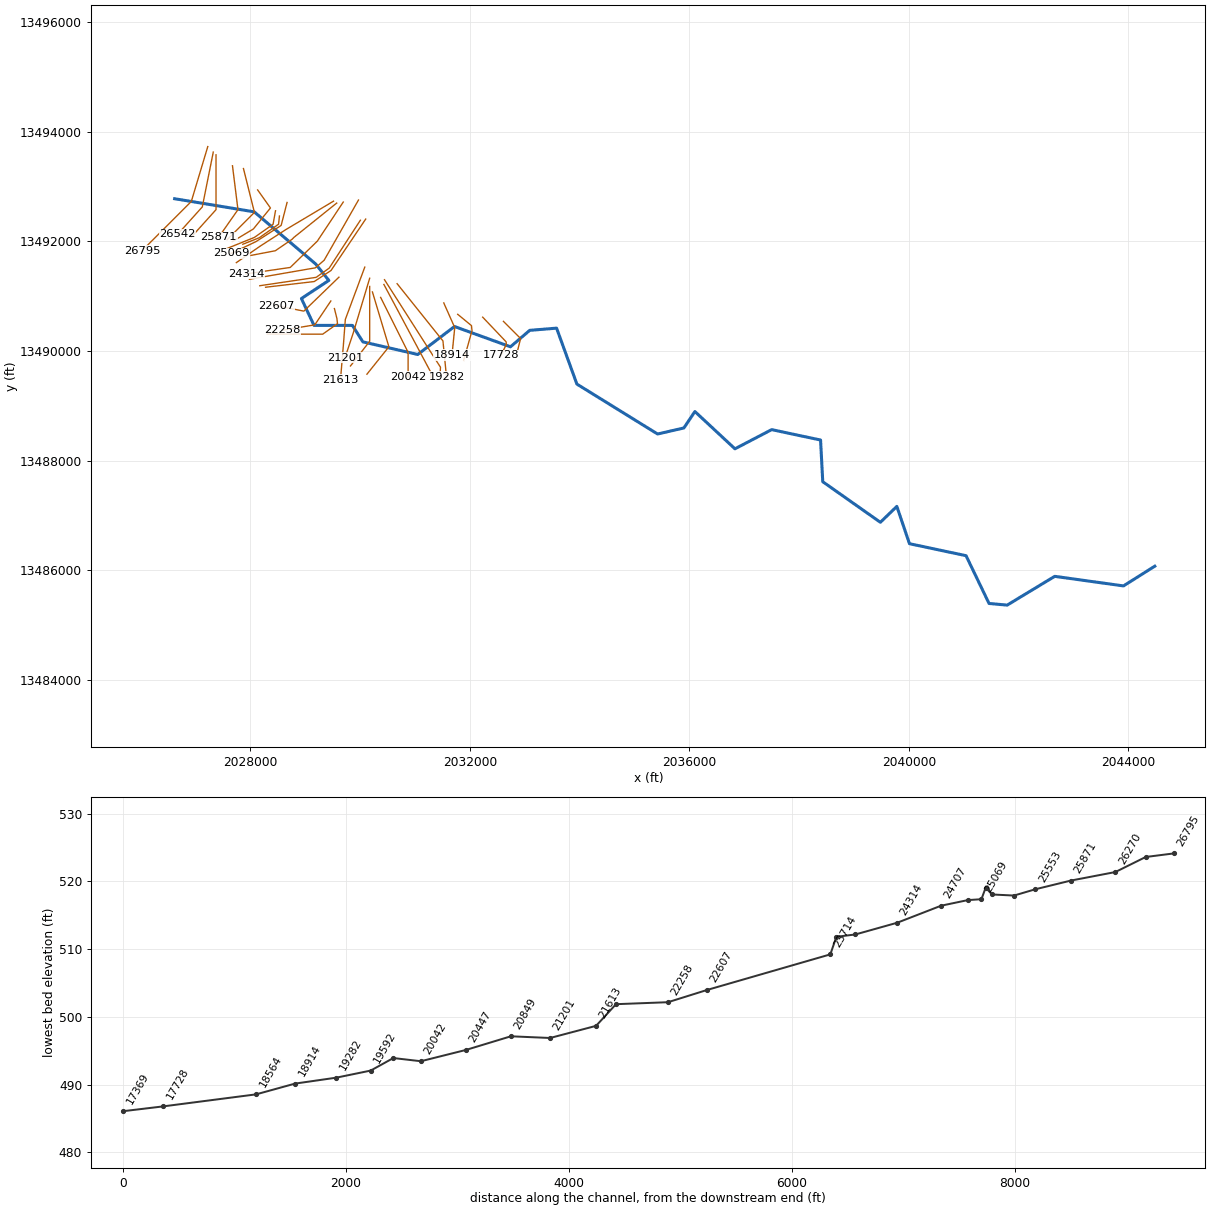
--- WEST CLEAR CREEK.prj (project) ---

Proj Title=WEST CLEAR CREEK Base Level Engineering
Current Plan=p01
Default Exp/Contr=0.3,0.1
English Units
Geom File=g01
Flow File=f01
Plan File=p01
Y Axis Title=Elevation
X Axis Title(PF)=Main Channel Distance
X Axis Title(XS)=Station
BEGIN DESCRIPTION:
WEST CLEAR CREEK
END DESCRIPTION:
DSS Export Rating Curves= 0
DSS Export Rating Curve Sorted= 0
DSS Export Volume Flow Curves= 0
DXF OffsetX= 0
DXF OffsetY= 0
DXF ScaleX= 1
DXF ScaleY= 10

--- WEST CLEAR CREEK.p01 (plan) ---

Plan Title=Multiple Run
Short Identifier=Multiple
Geom File=g01
Flow File=f01
Subcritical Flow
K Sum by GR= 0
Std Step Tol= 0.01
Critical Tol= 0.01
Num of Std Step Trials= 20
Max Error Tol= 0.3
Flow Tol Ratio= 0.001
Split Flow NTrial= 30
Split Flow Tol= 0.02
Split Flow Ratio= 0.02
Log Output Level= 0
Friction Slope Method= 1
Unsteady Friction Slope Method= 2
Unsteady Bridges Friction Slope Method= 1
Parabolic Critical Depth
Global Vel Dist=  1 , 1 , 1
Global Log Level= 0
CheckData=True
Encroach Param= -1, 0, 0, 0
BEGIN DESCRIPTION:
Multiple Run
END DESCRIPTION:

--- WEST CLEAR CREEK.f01 (steady flow) ---

Flow Title=Multiple
Program Version=5.05
Number of Profiles= 7
Profile Names=10-year,25-year,50-year,1pct_min,100-year,1pct_plu,500-year
River Rch & RM=WEST CLEAR CREEK,Reach-1         ,26795
     184     250     304     185     369     735     549
River Rch & RM=WEST CLEAR CREEK,Reach-1         ,24947
     357     504     628     390     778    1552    1212
River Rch & RM=WEST CLEAR CREEK,Reach-1         ,24314
     357     504     628     390     778    1552    1212
River Rch & RM=WEST CLEAR CREEK,Reach-1         ,21613
     474     678     852     533    1063    2120    1679
River Rch & RM=WEST CLEAR CREEK,Reach-1         ,16317
     538     772     972     609    1215    2425    1930
River Rch & RM=WEST CLEAR CREEK,Reach-1         ,9782
     574     826    1042     653    1304    2601    2076
River Rch & RM=WEST CLEAR CREEK,Reach-1         ,7312
     629     907    1146     720    1437    2866    2293
River Rch & RM=WEST CLEAR CREEK,Reach-1         ,4101
     963    1412    1805    1145    2285    4560    3723
Boundary for River Rch & Prof#=WEST CLEAR CREEK,Reach-1         , 1
Up Type= 0
Dn Type= 3
Dn Slope=0.00296
Boundary for River Rch & Prof#=WEST CLEAR CREEK,Reach-1         , 2
Up Type= 0
Dn Type= 3
Dn Slope=0.00296
Boundary for River Rch & Prof#=WEST CLEAR CREEK,Reach-1         , 3
Up Type= 0
Dn Type= 3
Dn Slope=0.00296
Boundary for River Rch & Prof#=WEST CLEAR CREEK,Reach-1         , 4
Up Type= 0
Dn Type= 3
Dn Slope=0.00296
Boundary for River Rch & Prof#=WEST CLEAR CREEK,Reach-1         , 5
Up Type= 0
Dn Type= 3
Dn Slope=0.00296
Boundary for River Rch & Prof#=WEST CLEAR CREEK,Reach-1         , 6
Up Type= 0
Dn Type= 3
Dn Slope=0.00296
Boundary for River Rch & Prof#=WEST CLEAR CREEK,Reach-1         , 7
Up Type= 0
Dn Type= 3
Dn Slope=0.00296
DSS Import GetInterval= 0
DSS Import GetPeak= 0
DSS Import FillOption= 0

--- WEST CLEAR CREEK.g01 (geometry) ---

Geom Title=Existing Conditions
Program Version=5.05

River Reach=WEST CLEAR CREEK,Reach-1
Reach XY= 30
       2026620.8     13492774.54       2028070.9      13492535.2
       2029190.8     13491584.54       2029430.8     13491284.54
       2028930.8     13490954.54       2029160.8     13490464.54
       2029860.8     13490464.54       2030050.8     13490164.54
       2031050.8     13489934.54       2031720.8     13490444.54
       2032740.8     13490074.54       2033090.8     13490374.54
       2033580.8     13490414.54       2033950.8     13489394.54
       2035420.8     13488484.54       2035900.8     13488594.54
       2036100.8     13488894.54       2036830.8     13488214.54
       2037500.8     13488564.54       2038390.8     13488374.54
       2038430.8     13487614.54       2039480.8     13486874.54
       2039780.8     13487164.54       2040010.8     13486484.54
        2041042.     13486265.71       2041460.8     13485394.54
       2041790.8     13485364.54      2042657.73     13485889.21
       2043910.8     13485714.54       2044480.8     13486074.54

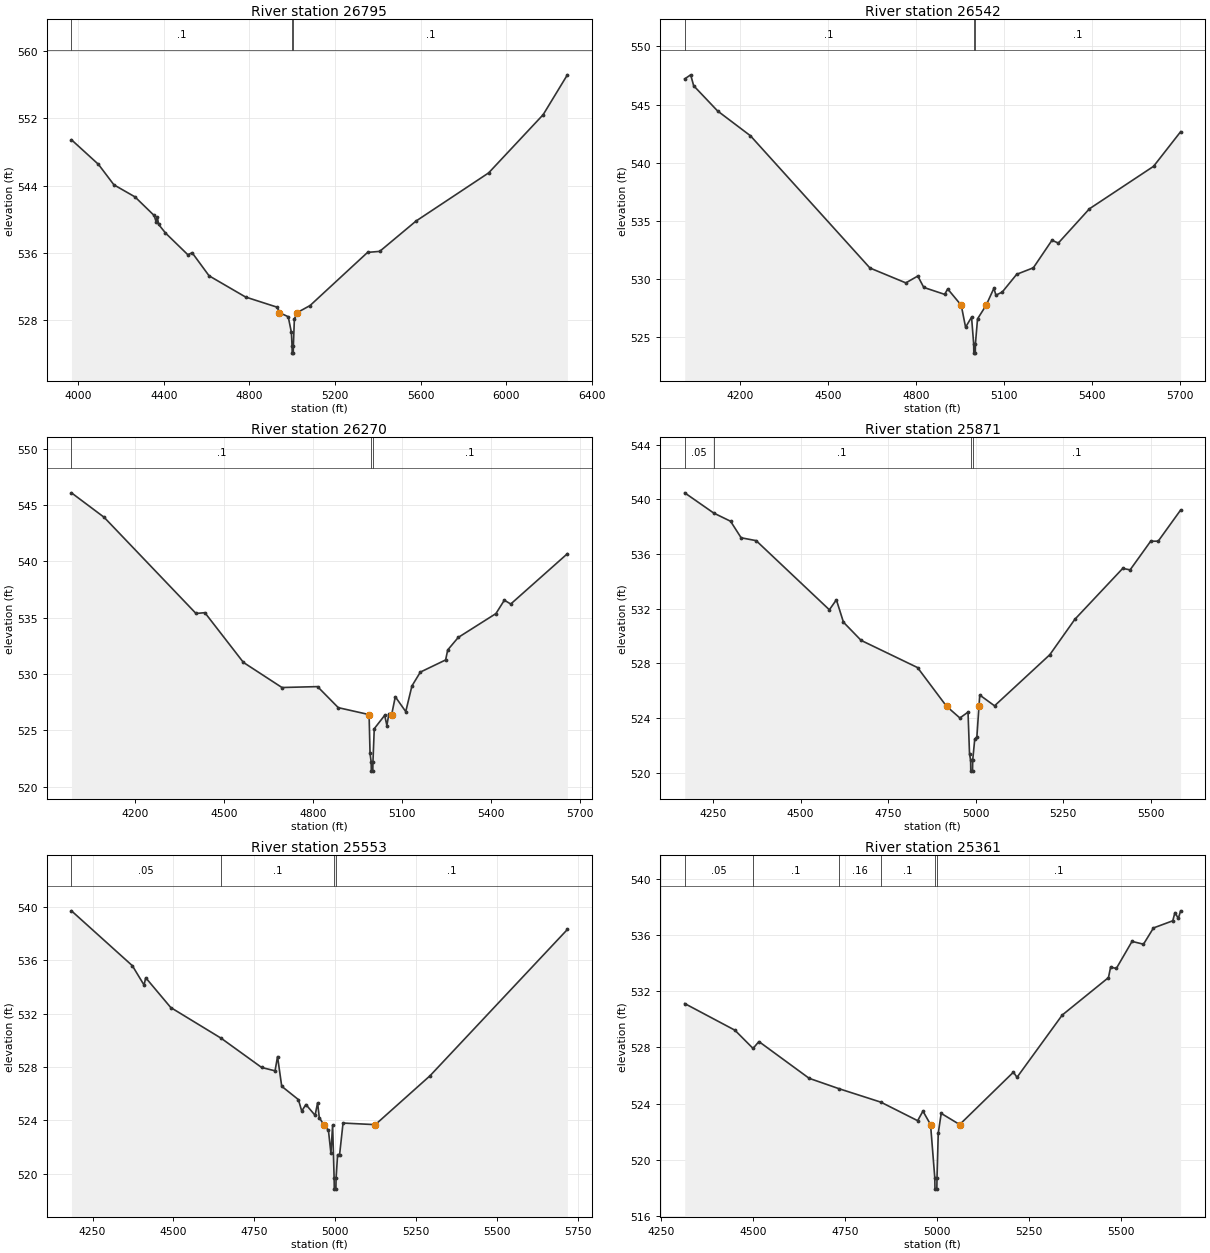
Type RM Length L Ch R = 1 ,26795   ,253,253,253
BEGIN DESCRIPTION:
WEST CLEAR CREEK 55.0
END DESCRIPTION:
XS GIS Cut Line= 3
        2027225.     13493724.99        2026925.       13492725.
      2026025.01     13491825.01
#Sta/Elev= 30
  3968.3  549.45  4094.4  546.53  4166.7   544.1    4265  542.67  4354.6  540.46
  4364.1  539.68  4369.4  540.27  4375.5   539.4  4407.6  538.38  4512.1   535.8
  4532.1  536.04  4611.2   533.3  4781.8  530.78  4929.7  529.57 4940.13528.9299
    4981  528.44  4995.8  526.58  4998.9  524.92  4999.4  524.12  5004.4  524.12
  5004.9  524.92  5009.7  528.16 5022.82528.9304    5083  529.77  5351.7  536.08
  5408.3   536.2    5578   539.8  5917.4  545.52    6172  552.43  6285.1  557.16
#Mann= 3 ,-1 , 0
  3968.3      .1       0  4998.9     .07       0  5004.9      .1       0
Bank Sta=4940.13,5022.82
XS Rating Curve= 0 ,0
Exp/Cntr=0.3,0.1

Type RM Length L Ch R = 1 ,26542   ,272,272,272
BEGIN DESCRIPTION:
WEST CLEAR CREEK 54.0
END DESCRIPTION:
XS GIS Cut Line= 3
      2027325.01     13493625.03        2027125.       13492625.
      2026675.01     13492125.01
#Sta/Elev= 30
  4010.2  547.21  4030.6  547.56  4040.8  546.62  4122.4  544.45  4234.6  542.31
  4642.5  530.92  4764.9  529.64  4805.7  530.23  4826.1  529.25  4897.5  528.65
  4907.7  529.12 4953.96527.7157  4968.8  525.82  4989.2  526.69  4996.4  524.39
  4996.9  523.59  5001.9  523.59  5002.4  524.39  5009.6  526.54    5039527.7159
  5065.5  529.18  5072.3  528.58  5093.9  528.85  5143.3  530.38  5200.1  530.94
  5263.6  533.31  5285.3  533.07  5391.4  536.02  5610.4  539.68  5702.7  542.66
#Mann= 3 ,-1 , 0
  4010.2      .1       0  4996.4     .07       0  5002.4      .1       0
Bank Sta=4953.96,5039
XS Rating Curve= 0 ,0
Exp/Cntr=0.3,0.1

Type RM Length L Ch R = 1 ,26270   ,399,399,399
BEGIN DESCRIPTION:
WEST CLEAR CREEK 53.0
END DESCRIPTION:
XS GIS Cut Line= 3
        2027375.     13493575.02        2027375.       13492575.
        2026925.       13492075.
#Sta/Elev= 30
  3985.9   546.1  4095.9  543.93  4405.9  535.38  4435.9  535.45  4565.9  531.03
  4695.9   528.8  4815.9  528.88  4885.9  527.01 4989.75526.3931    4993  522.95
  4996.8  522.17  4997.3  521.37  5002.3  521.37  5002.8  522.17  5007.2  525.14
  5042.4  526.33  5049.8  525.42  5056.6  526.48 5065.85526.3912  5078.2  527.98
  5113.4  526.66  5134.3  528.94  5162.7  530.17  5247.9  531.25    5255  532.14
  5290.5  533.25  5417.6  535.37    5446  536.56  5467.6  536.22  5658.6  540.69
#Mann= 3 ,-1 , 0
  3985.9      .1       0  4996.8     .07       0  5002.8      .1       0
Bank Sta=4989.75,5065.85
XS Rating Curve= 0 ,0
Exp/Cntr=0.3,0.1

Type RM Length L Ch R = 1 ,25871   ,318,318,318
BEGIN DESCRIPTION:
WEST CLEAR CREEK 52.0
END DESCRIPTION:
XS GIS Cut Line= 3
        2027675.       13493375.        2027775.       13492575.
      2027424.97     13492074.96
#Sta/Elev= 30
  4168.8  540.48  4251.7     539  4299.8   538.4    4330  537.19  4372.9  536.98
    4582  531.92  4602.1  532.65  4622.3  531.01  4672.7  529.68  4833.9  527.69
 4916.72524.8576  4954.9     524  4978.1  524.43  4982.4  521.37  4985.5  520.91
    4986  520.11    4991  520.11  4991.5  520.91  4997.3  522.45  5003.4  522.62
  5009.4524.8589  5011.6  525.68  5053.9  524.89  5211.7  528.63  5283.2  531.22
  5420.1  534.95  5441.1  534.84  5499.9  536.94  5521.3  536.94  5585.4  539.22
#Mann= 4 ,-1 , 0
  4168.8     .05       0  4251.7      .1       0  4985.5     .07       0
  4991.5      .1       0
Bank Sta=4916.72,5009.4
XS Rating Curve= 0 ,0
Exp/Cntr=0.3,0.1

Type RM Length L Ch R = 1 ,25553   ,192,192,192
BEGIN DESCRIPTION:
WEST CLEAR CREEK 51.0
END DESCRIPTION:
XS GIS Cut Line= 3
        2027875.       13493325.        2028075.       13492525.
      2027575.02     13492025.02
#Sta/Elev= 30
  4184.9  539.72    4373   535.6  4409.1  534.15  4414.2   534.7  4491.6  532.46
    4647  530.16  4772.4  527.96  4813.7  527.71  4821.4  528.78  4834.3  526.55
  4885.8  525.55  4896.1  524.69    4909  525.18  4937.4  524.37  4945.1  525.31
  4950.3   524.2 4964.11523.6693  4978.6  523.24  4986.3  521.52  4991.5  523.65
  4996.2  519.63  4996.7  518.83  5001.7  518.83  5002.2  519.63  5006.9  521.42
  5013.1  521.42  5023.7  523.79 5123.39523.6696  5292.4  527.34  5716.6  538.32
#Mann= 4 ,-1 , 0
  4184.9     .05       0    4647      .1       0  4996.2     .07       0
  5002.2      .1       0
Bank Sta=4964.11,5123.39
XS Rating Curve= 0 ,0
Exp/Cntr=0.3,0.1

Type RM Length L Ch R = 1 ,25361   ,197,197,197
BEGIN DESCRIPTION:
WEST CLEAR CREEK 50.0
END DESCRIPTION:
XS GIS Cut Line= 4
      2028133.54     13492934.63      2028366.83     13492605.74
      2028055.58     13492223.11      2027669.68     13491990.21
#Sta/Elev= 30
  4314.4  531.13  4450.8  529.23  4500.1  527.93    4516  528.42  4652.5   525.8
  4733.5  525.06  4847.3   524.1  4947.2  522.78  4961.6  523.46 4982.27522.5042
  4993.8   518.7  4994.3   517.9  4999.3   517.9  4999.8   518.7  5003.2  521.88
  5011.2   523.3 5061.41 522.504  5207.4  526.24  5217.1  525.87    5340  530.31
  5465.6  532.98  5471.4  533.73  5486.9  533.63  5529.6  535.56  5560.7  535.36
  5587.9  536.52  5640.3  537.03  5646.1  537.61  5655.4   537.2  5661.6  537.74
#Mann= 6 ,-1 , 0
  4314.4     .05       0  4500.1      .1       0  4733.5     .16       0
  4847.3      .1       0  4993.8     .07       0  4999.8      .1       0
Bank Sta=4982.27,5061.41
XS Rating Curve= 0 ,0
Exp/Cntr=0.3,0.1

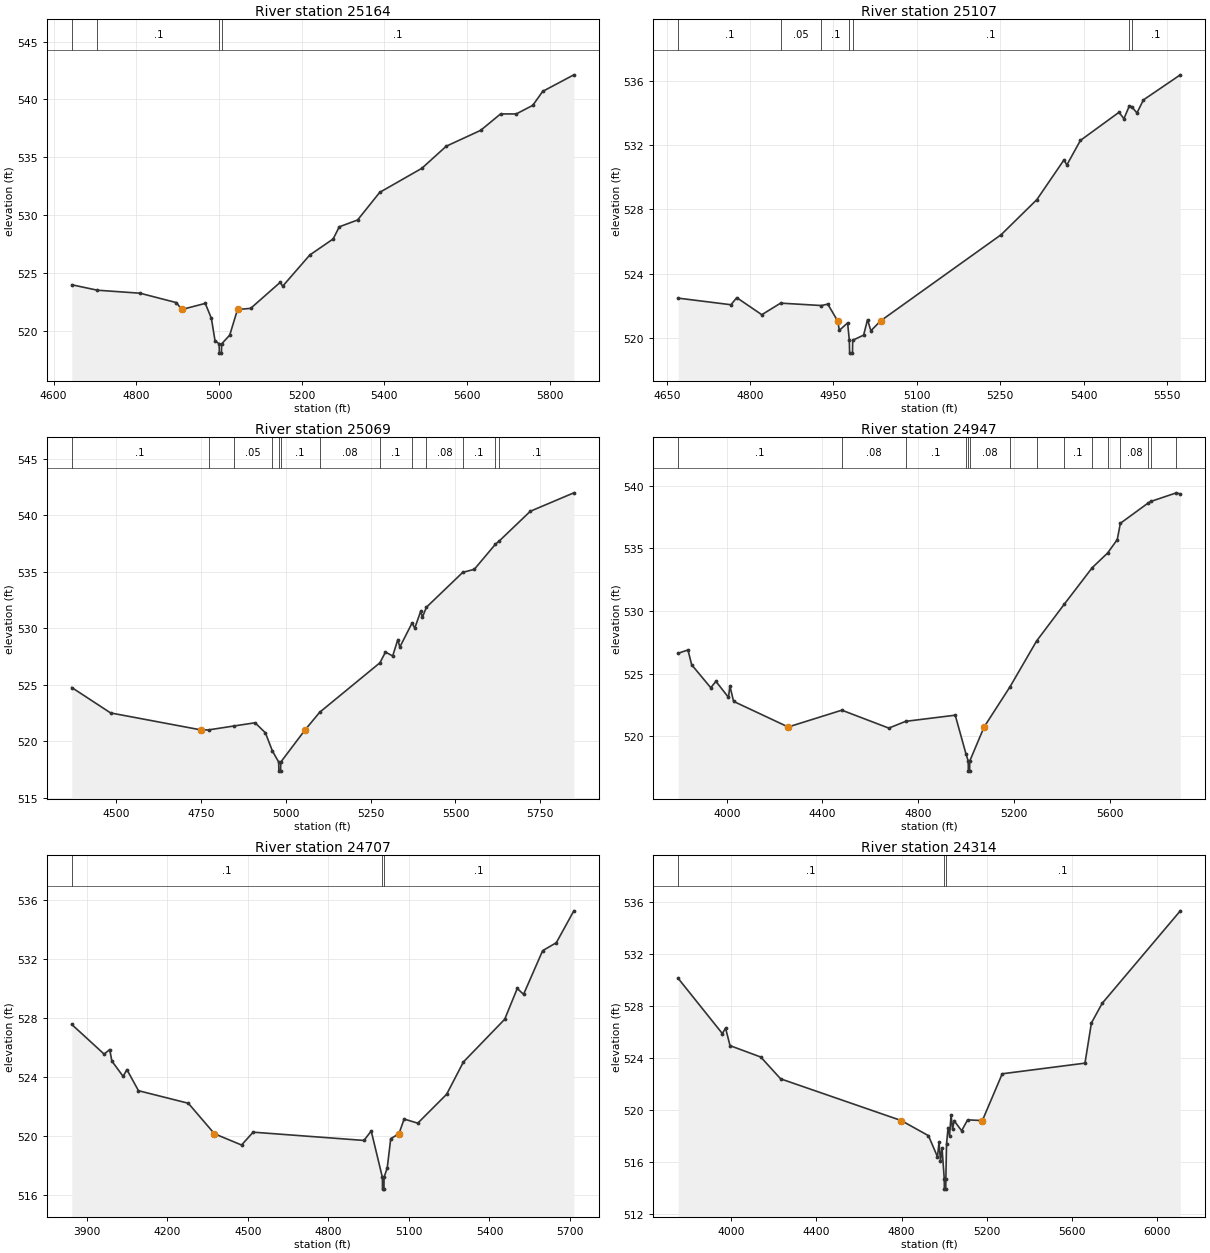
Type RM Length L Ch R = 1 ,25164   ,57,57,57
BEGIN DESCRIPTION:
WEST CLEAR CREEK 49.0
END DESCRIPTION:
XS GIS Cut Line= 4
      2028458.92     13492554.45      2028414.57     13492308.37
      2028073.42     13492068.79      2027565.88      13491863.5
#Sta/Elev= 30
    4644  523.97  4705.9   523.5  4809.1  523.24  4896.8  522.43 4910.17 521.832
  4966.9  522.36  4981.7  521.07  4990.4  519.15  5000.5  518.86    5001  518.06
    5006  518.06  5006.5  518.86  5026.1  519.62 5044.87521.8325  5076.7  521.93
  5148.1  524.18  5154.2  523.85  5219.6  526.54  5276.2  527.93    5291  528.98
  5335.3  529.57  5388.9  531.96  5490.8  534.04  5549.8  535.95    5633  537.32
  5681.2  538.74  5719.1  538.74    5759  539.48  5783.1  540.69  5858.4  542.12
#Mann= 4 ,-1 , 0
    4644     .16       0  4705.9      .1       0  5000.5     .07       0
  5006.5      .1       0
Bank Sta=4910.17,5044.87
XS Rating Curve= 0 ,0
Exp/Cntr=0.3,0.1

Type RM Length L Ch R = 1 ,25107   ,38,38,38
BEGIN DESCRIPTION:
WEST CLEAR CREEK 48.0
END DESCRIPTION:
XS GIS Cut Line= 4
      2028530.45     13492459.39      2028514.83     13492309.67
      2028164.22     13492063.58      2027862.51      13491943.8
#Sta/Elev= 30
  4670.6  522.48  4765.5  522.07  4775.9  522.51    4821  521.45  4854.8  522.17
  4928.4  522.02  4939.7  522.11 4957.39521.0641  4960.6  520.48  4975.4  520.94
  4978.5  519.86    4979  519.06  4984.1  519.06  4984.6  519.86  5004.2  520.18
  5011.2  521.14  5017.3  520.45  5034.7521.0645  5251.8  526.43    5316  528.61
  5364.6  531.07    5370  530.77  5394.3  532.29  5463.8  534.04  5472.6  533.64
  5482.4  534.44  5486.5  534.39  5496.1     534  5507.7  534.81  5574.1  536.37
#Mann= 7 ,-1 , 0
  4670.6      .1       0  4854.8     .05       0  4928.4      .1       0
  4978.5     .07       0  4984.6      .1       0  5482.4     .08       0
  5486.5      .1       0
Bank Sta=4957.39,5034.7
XS Rating Curve= 0 ,0
Exp/Cntr=0.3,0.1

Type RM Length L Ch R = 1 ,25069   ,122,122,122
BEGIN DESCRIPTION:
WEST CLEAR CREEK 47.0
END DESCRIPTION:
XS GIS Cut Line= 4
      2028669.72     13492706.49      2028561.69     13492287.24
      2028105.43     13491993.63      2027650.09      13491776.9
#Sta/Elev= 30
  4369.1  524.76  4483.6  522.51 4751.23521.0014  4772.5  521.01  4845.8  521.35
  4909.4  521.64  4939.8  520.75  4960.4  519.15    4979  518.16  4979.5  517.36
  4984.6  517.36  4985.1  518.16 5056.54521.0015  5099.8  522.57  5277.4  526.95
  5293.7   527.9  5314.9  527.55  5330.1     529    5336  528.34  5372.1  530.47
  5380.1  530.02  5397.3  531.49  5402.8  530.99  5414.2  531.86  5521.4  534.95
  5555.5  535.22  5617.7  537.44  5628.7  537.72  5720.7  540.36  5848.9  541.99
#Mann= 13 ,-1 , 0
  4369.1      .1       0  4772.5     .08       0  4845.8     .05       0
  4960.4      .1       0    4979     .07       0  4985.1      .1       0
  5099.8     .08       0  5277.4      .1       0  5372.1     .05       0
  5414.2     .08       0  5521.4      .1       0  5617.7     .08       0
  5628.7      .1       0
Bank Sta=4751.23,5056.54
XS Rating Curve= 0 ,0
Exp/Cntr=0.3,0.1

Type RM Length L Ch R = 1 ,24947   ,240,240,240
BEGIN DESCRIPTION:
WEST CLEAR CREEK 46.0
END DESCRIPTION:
XS GIS Cut Line= 4
      2029516.08     13492730.04      2028647.47     13492211.89
      2028180.09     13491910.29      2027745.04     13491609.09
#Sta/Elev= 30
  3797.6  526.63  3838.2  526.89  3853.7  525.71  3933.5  523.88  3954.9  524.39
  4007.5  523.11  4013.3  524.02  4028.9  522.79 4256.73 520.749  4480.9  522.09
    4677  520.66  4747.5   521.2  4954.4  521.69  4998.9  518.63  5008.7  518.03
  5009.2  517.23  5014.5  517.23    5015  518.03 5074.94520.7491  5183.3  523.96
  5294.3  527.61  5409.4  530.53  5526.9  533.46  5590.8  534.62  5631.1  535.69
    5644  536.99    5761  538.62  5772.3  538.74  5878.1  539.42  5894.4  539.33
#Mann= 15 ,-1 , 0
  3797.6      .1       0  4480.9     .08       0  4747.5      .1       0
  4998.9     .08       0  5008.7     .07       0    5015     .08       0
  5183.3      .1       0  5294.3     .05       0  5409.4      .1       0
  5526.9     .05       0  5590.8      .1       0    5644     .08       0
    5761     .05       0  5772.3      .1       0  5878.1     .05       0
Bank Sta=4256.73,5074.94
XS Rating Curve= 0 ,0
Exp/Cntr=0.3,0.1

Type RM Length L Ch R = 1 ,24707   ,393,393,393
BEGIN DESCRIPTION:
WEST CLEAR CREEK 45.0
END DESCRIPTION:
XS GIS Cut Line= 5
      2029574.24     13492695.31      2028795.61     13492070.32
      2028757.44     13492032.44      2028455.35     13491825.84
      2028010.91     13491740.77
#Sta/Elev= 30
  3843.8  527.56  3964.4  525.55  3985.2  525.86  3993.2  525.08  4035.2  524.04
  4049.2   524.5  4092.4  523.07    4278  522.22 4375.47520.1514  4476.4  519.39
  4519.6  520.26  4932.5   519.7  4959.5  520.34  5001.1   517.2  5001.6   516.4
  5006.9   516.4  5007.4   517.2  5019.2  517.84  5032.2  519.82 5062.81520.1517
  5082.1  521.15  5132.9  520.87  5240.6  522.83  5303.1  525.02  5456.8  527.91
  5503.7     530  5527.1   529.6  5598.3  532.56  5649.2   533.1  5714.5  535.26
#Mann= 3 ,-1 , 0
  3843.8      .1       0  5001.1     .07       0  5007.4      .1       0
Bank Sta=4375.47,5062.81
XS Rating Curve= 0 ,0
Exp/Cntr=0.3,0.1

Type RM Length L Ch R = 1 ,24314   ,375,375,375
BEGIN DESCRIPTION:
WEST CLEAR CREEK 44.0
END DESCRIPTION:
XS GIS Cut Line= 4
      2029693.66     13492713.89      2029220.63     13492000.61
      2028727.58     13491521.44      2027921.99     13491403.38
#Sta/Elev= 30
    3751  530.13  3958.2  525.88  3973.2   526.3  3994.2  524.95  4138.6  524.07
  4231.8  522.39 4798.44 519.174  4925.9  518.01  4968.4  516.38  4975.6  517.51
  4982.5  516.06  4989.7  517.07  5000.1  514.69  5000.7  513.89  5007.1  513.89
  5007.7  514.69  5010.8  517.34    5018  518.63    5025  518.01  5032.1  519.59
  5039.1  518.49  5046.3  519.17  5081.6  518.39  5109.9  519.23 5179.08 519.174
  5272.4  522.78  5660.9   523.6  5691.2   526.7  5741.7  528.21  6108.6  535.34
#Mann= 3 ,-1 , 0
    3751      .1       0  5000.1     .07       0  5007.7      .1       0
Bank Sta=4798.44,5179.08
XS Rating Curve= 0 ,0
Exp/Cntr=0.3,0.1

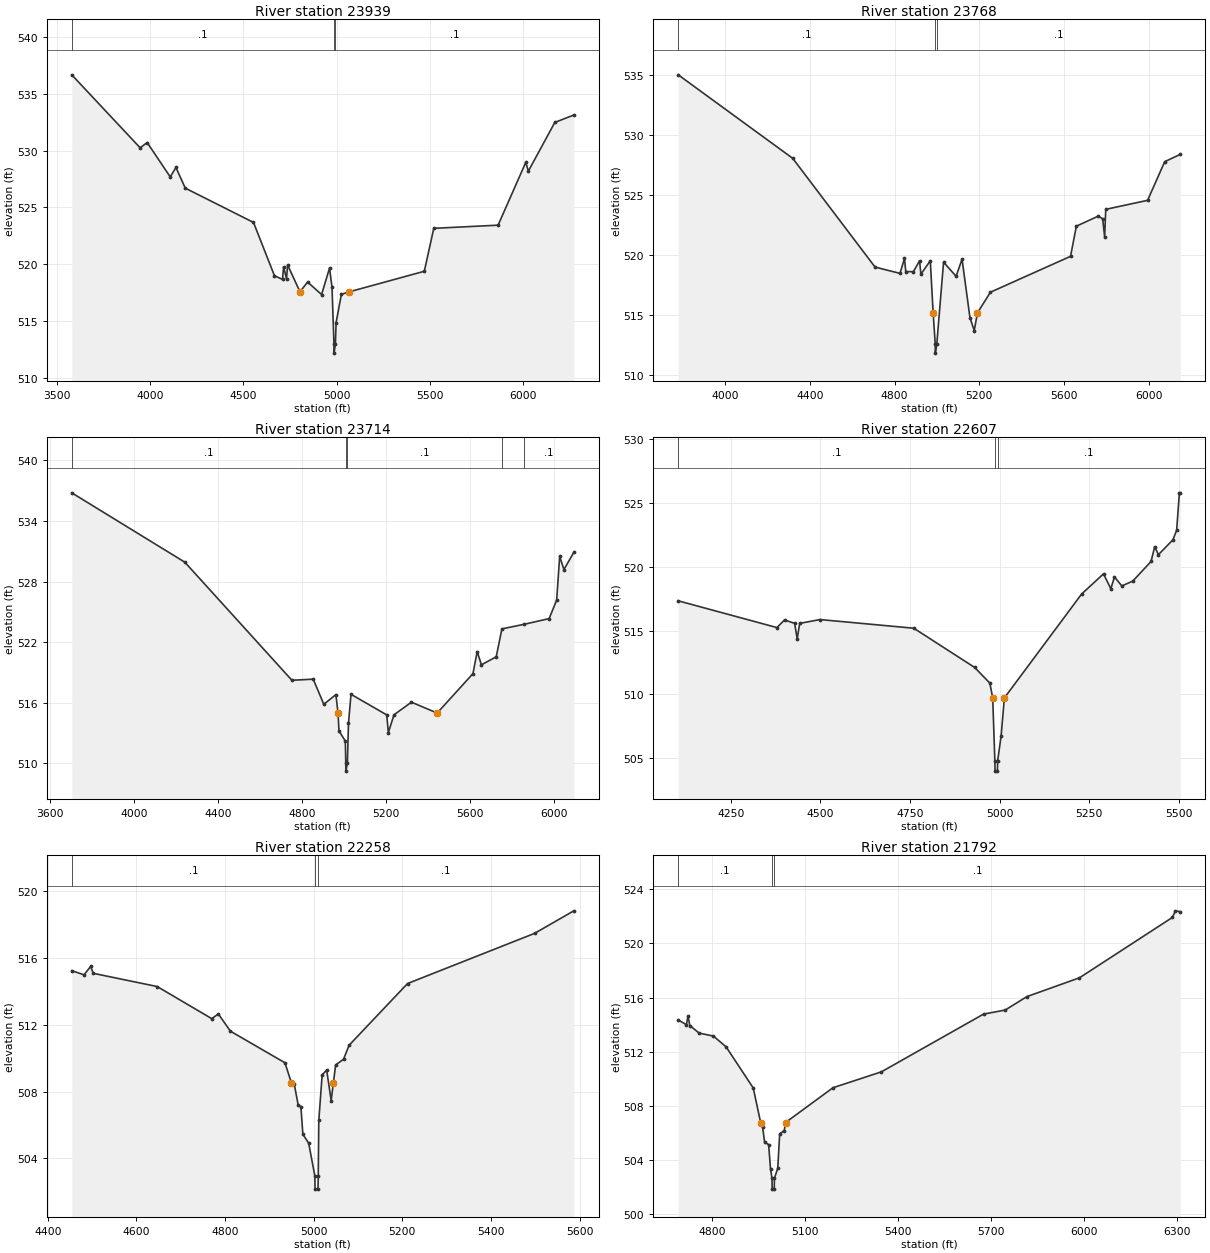
Type RM Length L Ch R = 1 ,23939   ,171,171,171
BEGIN DESCRIPTION:
WEST CLEAR CREEK 43.0
END DESCRIPTION:
XS GIS Cut Line= 4
      2029970.63     13492750.61      2029345.63     13491653.39
      2029185.91      13491514.5      2027984.55     13491306.17
#Sta/Elev= 30
  3578.7  536.67  3945.7  530.24  3983.1  530.71    4107  527.68  4137.6  528.51
  4187.7  526.69  4553.7  523.67  4666.1  518.98  4709.3  518.65  4715.1  519.76
  4730.9  518.71  4736.7  519.93 4803.01517.5605    4844  518.42    4919  517.32
  4961.6  519.65    4975  517.96  4985.4  512.96    4986  512.16  4993.1  512.96
  4996.8  514.84  5025.3  517.34  5067.6517.5608  5470.2  519.37  5520.9  523.15
    5866  523.43  6014.5  528.96  6028.4  528.19  6170.4  532.48  6272.4  533.13
#Mann= 3 ,-1 , 0
  3578.7      .1       0  4985.4     .07       0  4993.1      .1       0
Bank Sta=4803.01,5067.6
XS Rating Curve= 0 ,0
Exp/Cntr=0.3,0.1

Type RM Length L Ch R = 1 ,23768   ,54,54,54
BEGIN DESCRIPTION:
WEST CLEAR CREEK 42.0
END DESCRIPTION:
XS GIS Cut Line= 4
      2030005.34     13492382.54      2029435.91     13491507.56
       2029199.8     13491340.89      2028172.06     13491188.12
#Sta/Elev= 30
    3778  534.98  4318.7  528.03  4708.1  518.97  4825.6  518.45  4846.9  519.69
    4853   518.6  4888.7  518.59  4918.3   519.5  4924.4  518.38  4968.8   519.5
 4982.36515.1572    4992  512.61  4992.6  511.81  4999.7  512.61  5031.5  519.38
  5090.7  518.21  5118.9  519.63  5156.3  514.75  5176.5  513.69 5191.55515.1559
  5252.7  516.88  5631.4  519.87  5658.9  522.38  5762.8  523.22  5783.1  522.99
  5792.6  521.48  5797.7  523.78  5995.4  524.53  6076.3  527.75    6150  528.36
#Mann= 3 ,-1 , 0
    3778      .1       0    4992     .07       0  4999.7      .1       0
Bank Sta=4982.36,5191.55
XS Rating Curve= 0 ,0
Exp/Cntr=0.3,0.1

Type RM Length L Ch R = 1 ,23714   ,1107,1107,1107
BEGIN DESCRIPTION:
WEST CLEAR CREEK 41.0
END DESCRIPTION:
XS GIS Cut Line= 4
      2030102.57     13492403.39      2029470.63     13491465.89
      2029165.08      13491264.5       2028278.1     13491160.56
#Sta/Elev= 30
  3703.4  536.79  4241.4  529.92  4751.2  518.22  4852.7  518.33  4902.9  515.84
  4960.5   516.8 4970.65514.9746  4975.2   513.2  5005.3   512.2  5007.5  510.02
  5008.1  509.22  5015.2  510.02  5020.4  513.94  5032.4  516.83  5202.5  514.79
  5210.1  513.03  5236.9   514.8  5320.2  516.05 5442.38514.9724  5612.8  518.88
    5633  521.06  5653.1  519.75  5723.6  520.55  5750.6  523.31  5857.5  523.77
  5975.3  524.33  6011.2  526.16  6025.6   530.5  6045.8  529.19    6093   530.9
#Mann= 5 ,-1 , 0
  3703.4      .1       0  5007.5     .07       0  5015.2      .1       0
  5750.6     .08       0  5857.5      .1       0
Bank Sta=4970.65,5442.38
XS Rating Curve= 0 ,0
Exp/Cntr=0.3,0.1

Type RM Length L Ch R = 1 ,22607   ,349,349,349
BEGIN DESCRIPTION:
WEST CLEAR CREEK 40.0
END DESCRIPTION:
XS GIS Cut Line= 3
      2029614.88     13491344.24        2028975.       13490725.
      2028474.96     13490825.01
#Sta/Elev= 30
  4103.6  517.33  4378.9  515.23    4400  515.83  4428.3  515.56  4435.4  514.35
  4442.4  515.56    4499  515.86  4760.6  515.18  4930.4   512.1  4972.8  510.87
 4980.75509.7065  4986.7  504.76  4987.3  503.96  4993.8  503.96  4994.5  504.76
  5004.3  506.75 5013.25 509.707  5228.6  517.86  5289.8  519.45  5310.2  518.28
  5320.4  519.21  5340.8   518.5  5371.4  518.88  5422.4  520.42  5432.6  521.59
  5442.8  520.95  5483.6  522.13  5493.8  522.88  5501.4  525.81    5504  525.81
#Mann= 3 ,-1 , 0
  4103.6      .1       0  4986.7     .07       0  4994.5      .1       0
Bank Sta=4980.75,5013.25
XS Rating Curve= 0 ,0
Exp/Cntr=0.3,0.1

Type RM Length L Ch R = 1 ,22258   ,466,466,466
BEGIN DESCRIPTION:
WEST CLEAR CREEK 39.0
END DESCRIPTION:
XS GIS Cut Line= 3
      2029467.32     13490910.21        2029175.       13490475.
      2028575.04     13490375.01
#Sta/Elev= 30
  4454.3  515.23    4482  514.98  4496.7  515.48    4503  515.07    4647  514.28
    4770  512.36    4785  512.64  4812.1  511.61  4935.1  509.72 4949.68508.5237
  4956.1  508.45    4965  507.19  4971.1   507.1  4975.6  505.44  4988.7  504.91
  5002.5  502.96  5003.1  502.16  5009.7  502.16  5010.3  502.96  5011.5  506.27
  5019.1     509  5029.3  509.28  5039.4  507.46 5044.44508.5229  5049.5  509.59
  5067.3  509.93  5079.9  510.77  5211.7  514.46  5498.1  517.46  5586.8  518.81
#Mann= 3 ,-1 , 0
  4454.3      .1       0  5002.5     .07       0  5010.3      .1       0
Bank Sta=4949.68,5044.44
XS Rating Curve= 0 ,0
Exp/Cntr=0.3,0.1

Type RM Length L Ch R = 1 ,21792   ,179,179,179
BEGIN DESCRIPTION:
WEST CLEAR CREEK 38.0
END DESCRIPTION:
XS GIS Cut Line= 5
      2029532.43     13490771.29      2029577.56     13490592.51
       2029588.8      13490496.9      2029318.59     13490304.31
      2028309.27     13490306.91
#Sta/Elev= 30
  4690.4  514.35  4716.8     514    4722  514.65  4727.8  513.94  4757.9  513.38
  4804.1  513.16  4845.2  512.36  4932.7  509.33 4956.57506.7847  4962.9  506.44
  4969.5  505.33  4982.4  505.16  4988.5  503.35  4993.2  502.67  4993.9  501.87
  5000.5  501.87  5001.1  502.67  5011.9  503.41  5018.1  505.95  5032.8  506.19
 5037.24506.7844  5190.2  509.35  5346.5  510.52  5676.5  514.78  5746.5  515.08
  5816.5  516.07  5986.5  517.46  6286.5  521.91  6296.5   522.4  6312.2  522.33
#Mann= 3 ,-1 , 0
  4690.4      .1       0  4993.2     .07       0  5001.1      .1       0
Bank Sta=4956.57,5037.24
XS Rating Curve= 0 ,0
Exp/Cntr=0.3,0.1

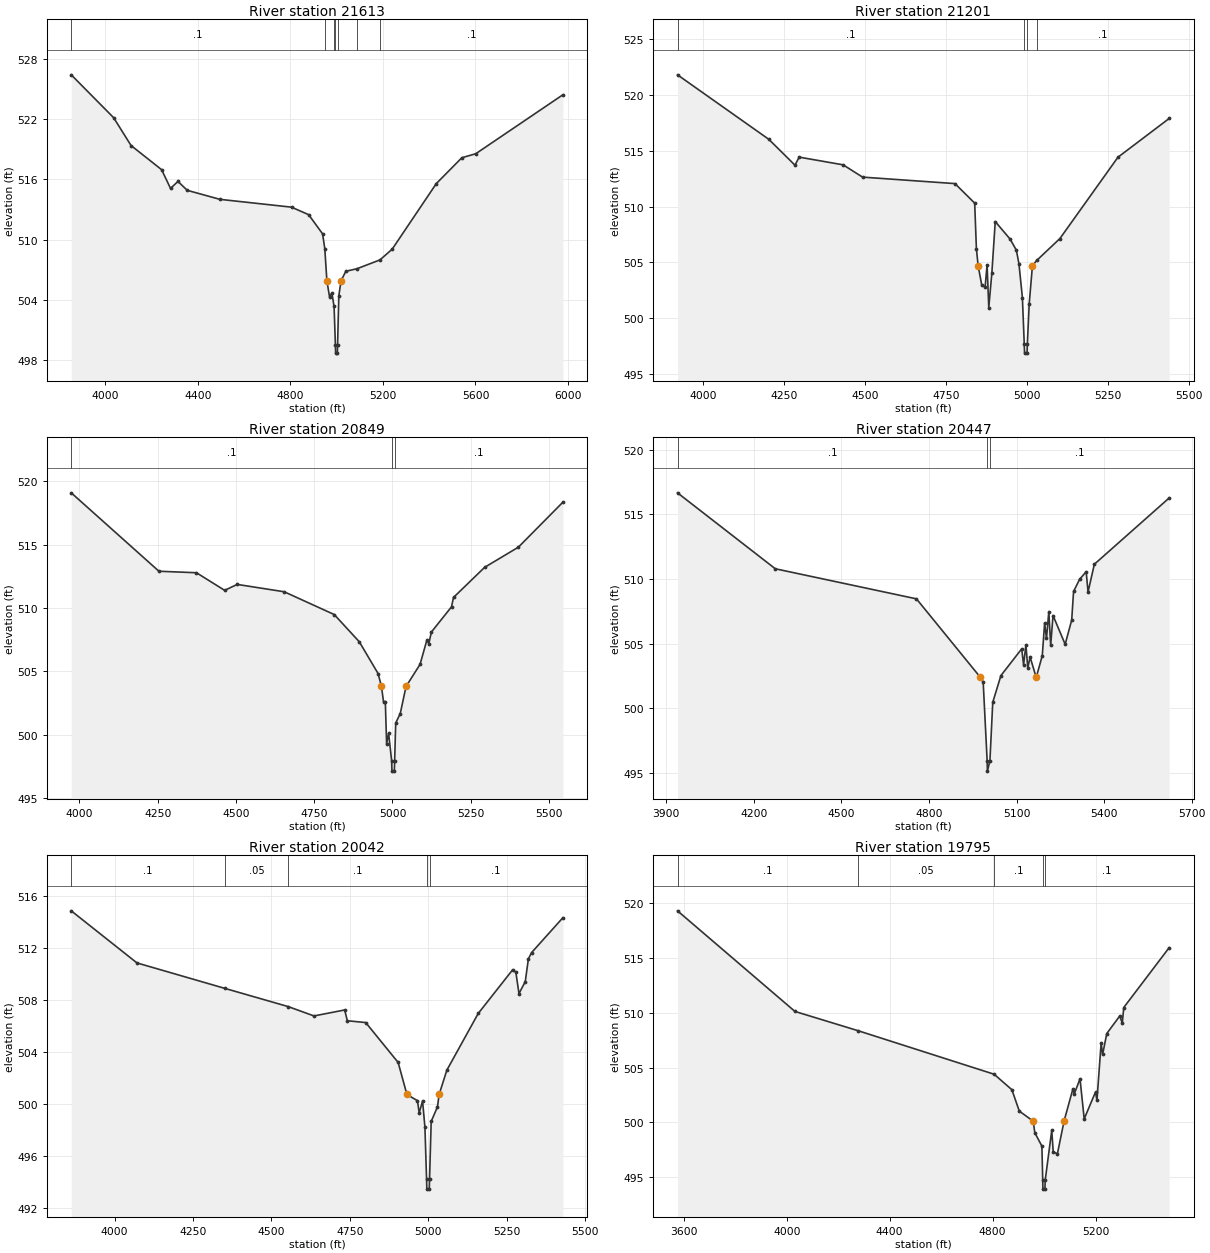
Type RM Length L Ch R = 1 ,21613   ,412,412,412
BEGIN DESCRIPTION:
WEST CLEAR CREEK 37.0
END DESCRIPTION:
XS GIS Cut Line= 4
      2030085.56     13491527.19      2029731.38     13490574.02
      2029694.92     13490094.86      2029642.84     13489469.91
#Sta/Elev= 30
  3853.3  526.43  4036.6  522.15  4111.7  519.38  4243.7  516.97  4282.4   515.1
  4314.4   515.8  4354.5  514.91  4495.6  514.01  4805.1  513.23  4879.2  512.48
  4939.4  510.57  4948.9   509.1 4958.06 505.885  4969.4  504.29  4979.5  504.66
  4989.1  503.33  4994.8  499.47  4995.7  498.67  5003.3  498.67  5004.2  499.47
  5009.6   504.4 5019.24 505.885  5039.7  506.83  5088.2  507.09  5187.4  507.97
  5240.2  509.04  5430.8  515.58  5541.2  518.16  5601.4  518.56  5977.8  524.44
#Mann= 7 ,-1 , 0
  3853.3      .1       0  4948.9     .07       0  4989.1      .1       0
  4994.8     .07       0  5004.2      .1       0  5088.2     .07       0
  5187.4      .1       0
Bank Sta=4958.06,5019.24
XS Rating Curve= 0 ,0
Exp/Cntr=0.3,0.1

Type RM Length L Ch R = 1 ,21201   ,352,352,352
BEGIN DESCRIPTION:
WEST CLEAR CREEK 36.0
END DESCRIPTION:
XS GIS Cut Line= 3
      2030174.99     13491324.96        2029875.       13490325.
      2029725.01     13489875.03
#Sta/Elev= 30
  3920.7   521.8  4202.5  516.03  4283.5  513.71  4296.5  514.43  4432.2  513.74
  4492.3  512.64  4777.6  512.06  4838.5  510.31  4843.8  506.23 4849.13504.7109
  4860.3  502.97  4870.7  502.81  4876.8  504.78    4882  500.96  4891.6  504.08
    4902  508.66  4948.2  507.08  4967.3  506.09  4975.2  504.87  4985.8  501.86
  4991.6  497.68  4992.5  496.88  5000.1  496.88  5001.1  497.68  5006.9  501.31
 5016.85 504.712  5030.8   505.2  5101.7  507.14  5280.9  514.42    5439  517.89
#Mann= 4 ,-1 , 0
  3920.7      .1       0  4991.6     .07       0  5001.1      .1       0
  5030.8      .1       0
Bank Sta=4849.13,5016.85
XS Rating Curve= 0 ,0
Exp/Cntr=0.3,0.1

Type RM Length L Ch R = 1 ,20849   ,402,402,402
BEGIN DESCRIPTION:
WEST CLEAR CREEK 35.0
END DESCRIPTION:
XS GIS Cut Line= 3
        2030175.     13491174.98        2030175.       13490175.
      2029824.98     13489724.97
#Sta/Elev= 30
  3974.1   519.1  4254.1  512.91  4374.1  512.79  4464.1   511.4  4504.1  511.87
  4654.1  511.29  4814.1  509.49  4894.1  507.34  4954.1  504.83 4964.79 503.814
  4971.6  502.57  4977.2  502.57  4981.3  499.28  4987.7  500.11  4997.4  497.93
  4998.3  497.13  5005.9  497.13  5006.9  497.93  5010.3  500.93  5024.8  501.67
 5043.31503.8133  5088.1  505.56  5109.8  507.47  5116.1   507.2  5124.3  508.11
  5188.5   510.1  5194.9  510.84  5294.4  513.22  5402.1  514.81  5544.2  518.36
#Mann= 3 ,-1 , 0
  3974.1      .1       0  4997.4     .07       0  5006.9      .1       0
Bank Sta=4964.79,5043.31
XS Rating Curve= 0 ,0
Exp/Cntr=0.3,0.1

Type RM Length L Ch R = 1 ,20447   ,405,405,405
BEGIN DESCRIPTION:
WEST CLEAR CREEK 34.0
END DESCRIPTION:
XS GIS Cut Line= 3
      2030224.99     13491075.02        2030525.       13490075.
      2030124.98     13489574.97
#Sta/Elev= 30
  3938.4  516.67  4273.4  510.79  4757.1  508.46 4976.41502.3733  4985.7  502.03
  4999.3  495.92  5000.2  495.12  5008.8  495.92  5018.5  500.45  5046.5  502.52
  5117.7  504.59  5124.1  503.35  5132.1  504.89  5138.5  503.12  5146.5  503.95
 5167.44502.3736  5188.2  504.06  5196.2  506.59  5202.6  505.39  5210.6  507.47
    5217  504.87    5225  507.17  5266.6  504.94    5289  506.82  5295.4  509.03
  5316.2  509.98  5338.6  510.56    5345  508.99  5366.6  511.14  5622.8  516.27
#Mann= 3 ,-1 , 0
  3938.4      .1       0  4999.3     .07       0  5008.8      .1       0
Bank Sta=4976.41,5167.44
XS Rating Curve= 0 ,0
Exp/Cntr=0.3,0.1

Type RM Length L Ch R = 1 ,20042   ,247,247,247
BEGIN DESCRIPTION:
WEST CLEAR CREEK 33.0
END DESCRIPTION:
XS GIS Cut Line= 3
        2030375.       13490975.        2030875.       13489975.
        2030875.     13489525.04
#Sta/Elev= 30
  3861.5  514.87  4071.1  510.86  4351.5   508.9  4553.3   507.5  4635.7  506.78
  4733.6  507.24    4742  506.41  4800.7  506.27  4904.1   503.2 4932.05500.7341
  4965.6  500.26  4971.2  499.32    4982  500.23  4989.5  498.23  4994.7  494.25
  4995.7  493.45  5003.4  493.45  5004.3  494.25  5009.5  498.66  5029.5  499.78
 5034.77500.7339  5059.5  502.61  5159.5  506.97  5269.5  510.34  5279.5  510.15
  5289.5   508.5  5309.5  509.42  5319.5  511.17  5329.5  511.65  5429.5  514.34
#Mann= 5 ,-1 , 0
  3861.5      .1       0  4351.5     .05       0  4553.3      .1       0
  4994.7     .07       0  5004.3      .1       0
Bank Sta=4932.05,5034.77
XS Rating Curve= 0 ,0
Exp/Cntr=0.3,0.1

Type RM Length L Ch R = 1 ,19795   ,203,203,203
BEGIN DESCRIPTION:
WEST CLEAR CREEK 32.0
END DESCRIPTION:
XS GIS Cut Line= 4
      2030434.15     13491211.15      2031030.96     13490093.49
      2031291.38     13489605.21      2031290.43     13489515.22
#Sta/Elev= 30
  3575.5  519.28    4032  510.11  4275.3  508.37  4805.8  504.39  4874.8  502.98
  4903.7  501.03 4957.68500.1136  4963.9  499.06  4991.5  497.84  4994.7  494.72
  4995.6  493.92  5003.3  493.92  5004.3  494.72  5029.8  499.28  5035.4  497.34
  5051.7  497.13 5077.56 500.113  5111.9  503.05  5117.6  502.61  5139.6  503.98
  5155.9  500.32  5199.8  502.77  5205.4  502.01  5221.7  507.23  5227.4   506.2
  5243.7   508.1  5294.1   509.7  5303.9  509.04  5309.6  510.47  5485.9  515.92
#Mann= 5 ,-1 , 0
  3575.5      .1       0  4275.3     .05       0  4805.8      .1       0
  4994.7     .07       0  5004.3      .1       0
Bank Sta=4957.68,5077.56
XS Rating Curve= 0 ,0
Exp/Cntr=0.3,0.1

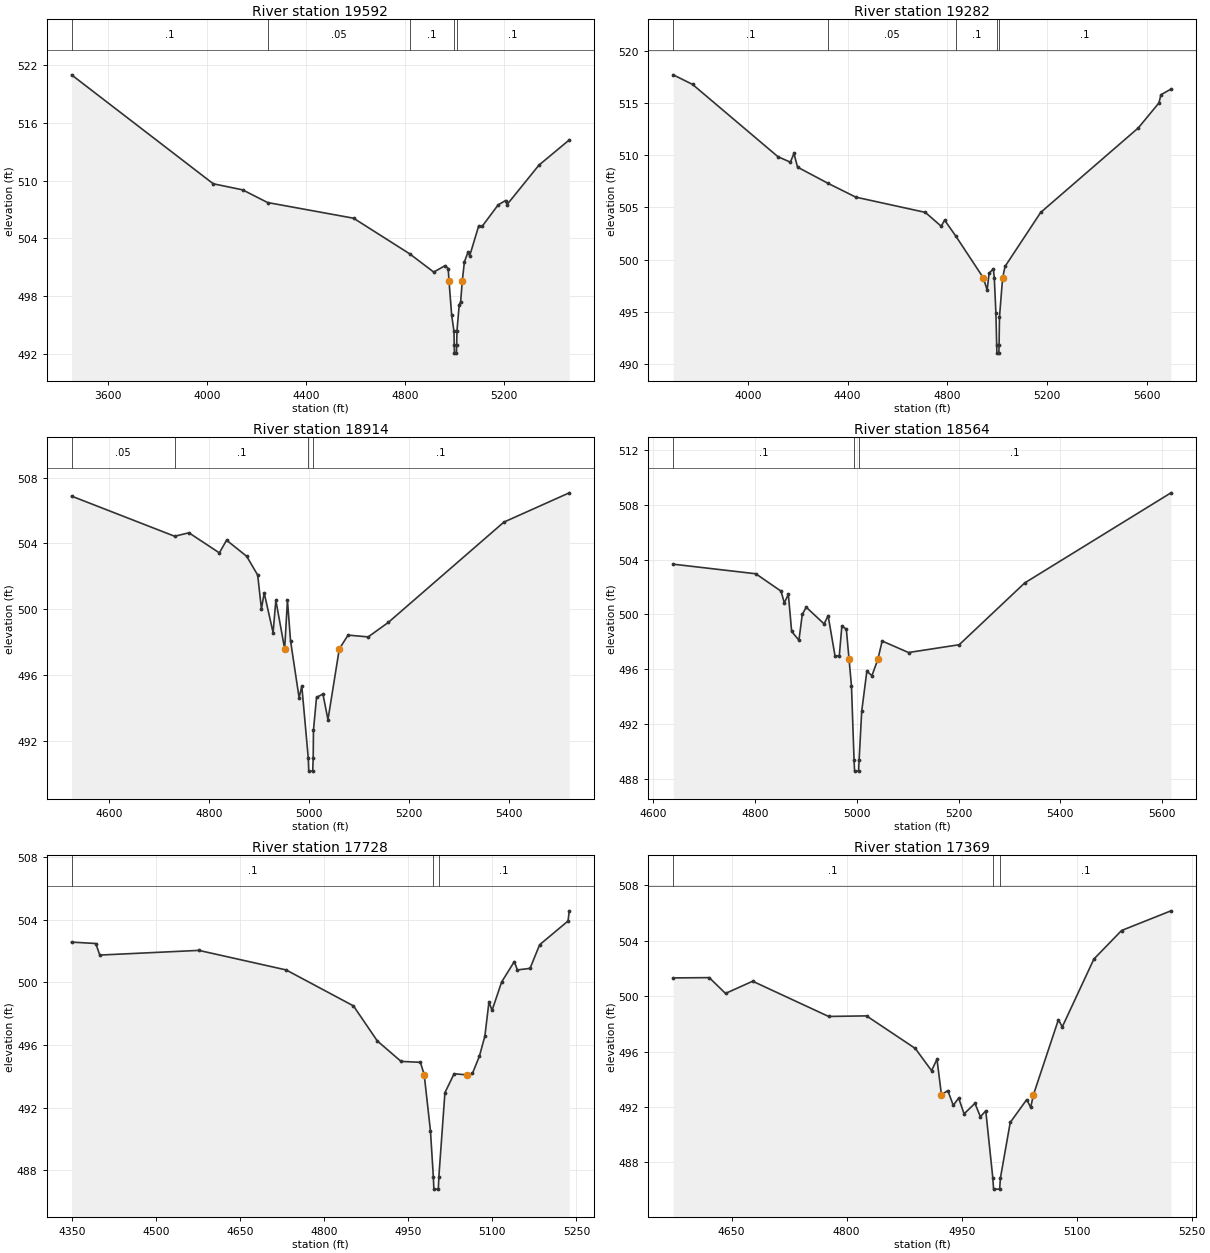
Type RM Length L Ch R = 1 ,19592   ,310,310,310
BEGIN DESCRIPTION:
WEST CLEAR CREEK 31.0
END DESCRIPTION:
XS GIS Cut Line= 4
      2030445.05     13491297.88      2031172.02      13490158.6
      2031464.99     13489702.87      2031458.83     13489584.67
#Sta/Elev= 30
  3451.1  521.01  4023.9  509.68  4142.4  509.05  4243.4  507.73  4590.9   506.1
  4818.1  502.39  4914.8   500.5  4960.4  501.16  4973.3  500.87 4976.72499.5394
  4987.4  496.02  4996.7  494.33  4997.8  492.87  4998.7  492.07  5006.5  492.07
  5007.5  492.87  5008.9  494.42  5017.8  497.07  5023.8  497.43  5030.1499.5395
  5038.9  501.57  5054.1  502.61  5060.1  502.18  5096.4  505.28  5111.6  505.29
  5175.4  507.49  5205.4  507.94  5211.3  507.52  5340.1  511.62  5462.7  514.24
#Mann= 5 ,-1 , 0
  3451.1      .1       0  4243.4     .05       0  4818.1      .1       0
  4997.8     .07       0  5007.5      .1       0
Bank Sta=4976.72,5030.1
XS Rating Curve= 0 ,0
Exp/Cntr=0.3,0.1

Type RM Length L Ch R = 1 ,19282   ,368,368,368
BEGIN DESCRIPTION:
WEST CLEAR CREEK 30.0
END DESCRIPTION:
XS GIS Cut Line= 4
        2030675.     13491225.01        2031475.       13490225.
      2031510.05     13490181.87        2031575.     13489524.98
#Sta/Elev= 30
  3700.7  517.73  3778.3  516.81  4120.9  509.87  4170.5  509.35  4184.9  510.18
  4199.4  508.87  4321.4  507.32  4433.1  505.99  4711.6  504.53  4775.6   503.2
  4789.2  503.78  4834.5  502.24 4944.59498.2421  4959.7  497.08  4967.7  498.69
  4984.6  499.11  4988.5  498.25    4995  494.83    4998  491.82    4999  491.02
  5006.8  491.02  5007.7  491.82  5009.3  494.49 5021.83498.2421  5031.6  499.34
  5174.4  504.52  5566.3  512.64    5649  515.04  5656.8  515.82    5697  516.36
#Mann= 5 ,-1 , 0
  3700.7      .1       0  4321.4     .05       0  4834.5      .1       0
    4998     .07       0  5007.7      .1       0
Bank Sta=4944.59,5021.83
XS Rating Curve= 0 ,0
Exp/Cntr=0.3,0.1

Type RM Length L Ch R = 1 ,18914   ,350,350,350
BEGIN DESCRIPTION:
WEST CLEAR CREEK 29.0
END DESCRIPTION:
XS GIS Cut Line= 3
      2031524.98     13490875.04        2031725.       13490425.
        2031675.     13489924.98
#Sta/Elev= 30
  4525.5  506.87  4731.6  504.43  4760.1  504.64    4821  503.42  4835.4  504.19
  4875.7  503.21  4897.6  502.07  4905.1  500.01  4910.6  500.99  4928.4  498.57
  4933.9  500.54 4951.52497.5815  4957.1  500.54  4963.3  498.07  4980.4  494.61
  4985.8  495.32  4998.7  490.95  4999.7  490.15  5007.6  490.15  5008.6  490.95
  5009.1  492.63  5015.2  494.63    5028  494.84  5038.1  493.28 5060.77497.5811
  5078.3  498.42  5118.5  498.31  5158.7  499.19  5389.8  505.29  5520.5  507.07
#Mann= 4 ,-1 , 0
  4525.5     .05       0  4731.6      .1       0  4998.7     .07       0
  5008.6      .1       0
Bank Sta=4951.52,5060.77
XS Rating Curve= 0 ,0
Exp/Cntr=0.3,0.1

Type RM Length L Ch R = 1 ,18564   ,836,836,836
BEGIN DESCRIPTION:
WEST CLEAR CREEK 28.0
END DESCRIPTION:
XS GIS Cut Line= 4
      2031779.18     13490667.02      2032029.64     13490460.75
      2032039.62     13490369.69      2031888.25     13489828.12
#Sta/Elev= 30
  4639.1  503.67  4801.5  502.97    4851   501.7  4857.5  500.84  4865.4  501.47
  4871.9  498.76  4886.2  498.12  4892.8     500  4900.5  500.53  4935.7  499.31
  4943.6  499.91  4957.3  496.94  4965.6     497  4970.6  499.15  4979.4  498.92
 4984.73496.7352  4989.5  494.78  4994.6  489.36  4995.6  488.56  5003.5  488.56
  5004.5  489.36  5009.6  492.93  5019.7  495.85  5029.7  495.53 5041.47496.7356
  5049.8  498.06  5101.6  497.22  5201.3  497.79    5330   502.3  5617.5  508.88
#Mann= 3 ,-1 , 0
  4639.1      .1       0  4994.6     .07       0  5004.5      .1       0
Bank Sta=4984.73,5041.47
XS Rating Curve= 0 ,0
Exp/Cntr=0.3,0.1

Type RM Length L Ch R = 1 ,17728   ,359,359,359
BEGIN DESCRIPTION:
WEST CLEAR CREEK 27.0
END DESCRIPTION:
XS GIS Cut Line= 4
      2032234.05     13490615.28      2032660.59     13490165.68
      2032664.67     13490118.63      2032568.34     13489919.47
#Sta/Elev= 30
    4349  502.58  4392.2  502.49  4399.4  501.75  4576.2  502.05  4731.9   500.8
  4852.1   498.5  4894.6  496.26    4937  494.95  4971.6  494.89 4978.34 494.088
  4989.5   490.5  4994.6  487.58  4995.6  486.78  5003.5  486.78  5004.5  487.58
  5015.3  492.95  5031.7  494.16 5053.97494.0882  5064.4  494.18  5076.9  495.29
  5086.6  496.57  5093.9  498.76  5099.4  498.21  5116.5  500.03  5139.1  501.33
  5144.6   500.8  5167.2   500.9  5184.3  502.41    5235  503.93  5237.2  504.58
#Mann= 3 ,-1 , 0
    4349      .1       0  4994.6     .07       0  5004.5      .1       0
Bank Sta=4978.34,5053.97
XS Rating Curve= 0 ,0
Exp/Cntr=0.3,0.1

Type RM Length L Ch R = 1 ,17369   ,694,694,694
BEGIN DESCRIPTION:
WEST CLEAR CREEK 26.0
END DESCRIPTION:
XS GIS Cut Line= 3
      2032612.09     13490538.57        2032925.       13490225.
      2032875.01     13490025.04
#Sta/Elev= 30
  4573.8  501.31  4620.8  501.33    4642  500.19  4677.4  501.07  4776.4  498.53
  4825.9  498.57  4889.5  496.22  4910.7  494.62  4917.8  495.44 4923.59492.8794
  4931.9  493.18    4939  492.12  4946.1  492.64  4953.1   491.5  4967.3  492.26
  4974.4  491.29  4981.4  491.72  4990.6  486.87  4991.6  486.07  4999.5  486.07
  5000.5  486.87  5013.3  490.88  5034.8  492.53    5040  491.97 5043.56492.8762
  5076.1  498.29  5081.2  497.78  5122.4  502.67  5158.5  504.73  5222.9  506.15
#Mann= 3 ,-1 , 0
  4573.8      .1       0  4990.6     .07       0  5000.5      .1       0
Bank Sta=4923.59,5043.56
XS Rating Curve= 0 ,0
Exp/Cntr=0.3,0.1