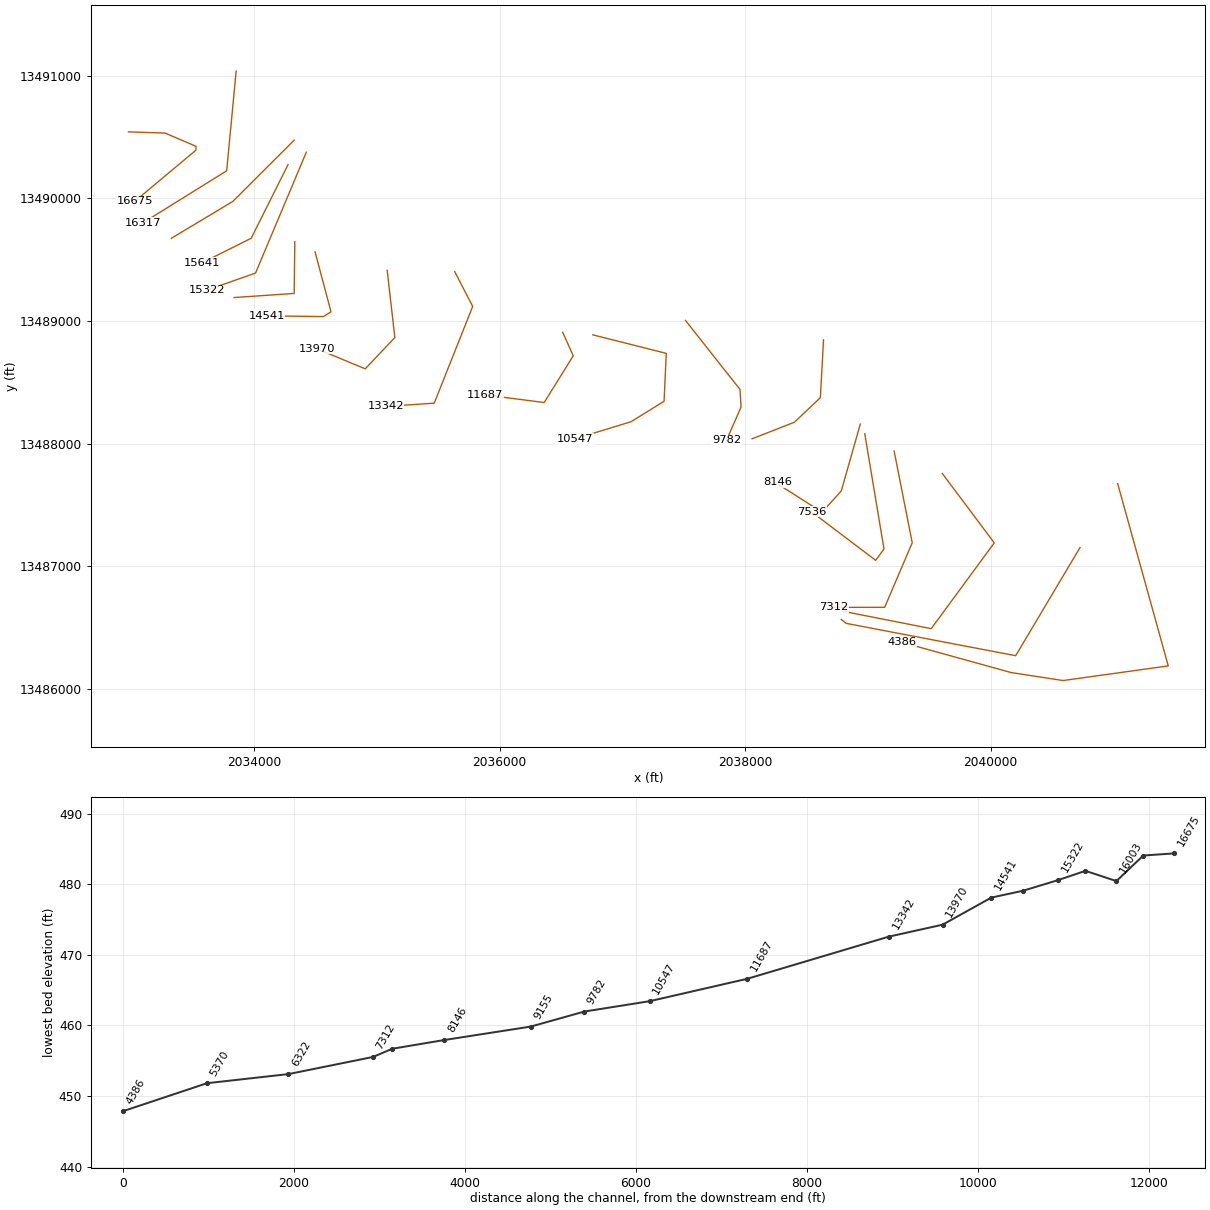
HEC-RAS study WEST CLEAR CREEK.prj: WEST CLEAR CREEK Base Level Engineering

--- WEST CLEAR CREEK.g01 (geometry) --- (continued)

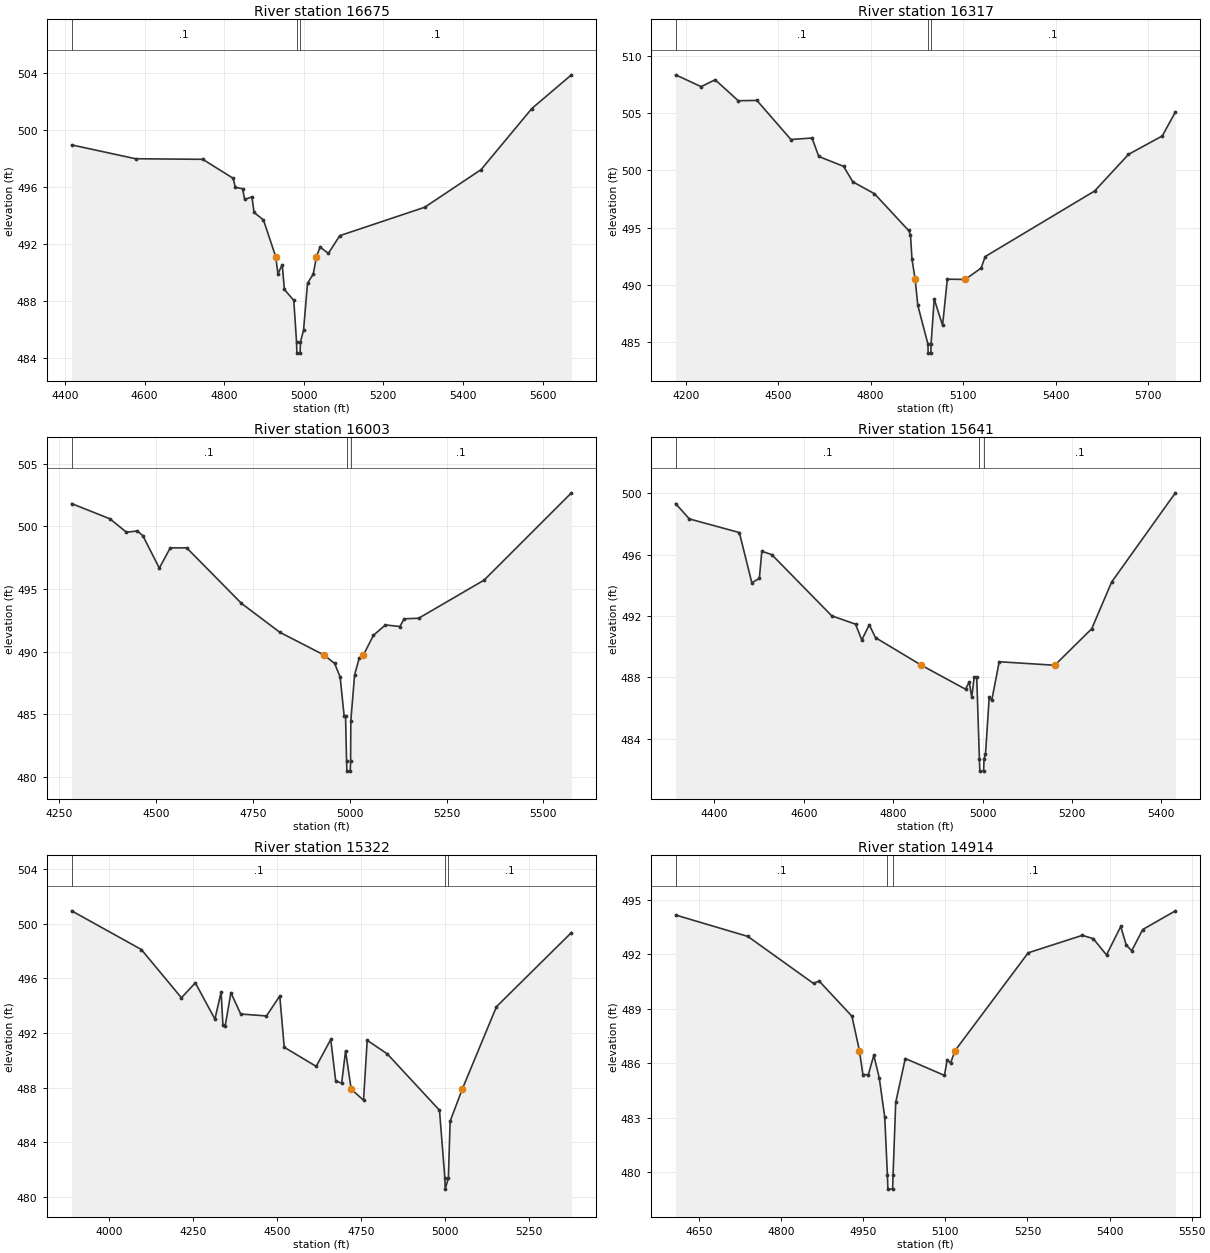
Type RM Length L Ch R = 1 ,16675   ,358,358,358
BEGIN DESCRIPTION:
WEST CLEAR CREEK 25.0
END DESCRIPTION:
XS GIS Cut Line= 5
      2032974.49     13490542.54      2033272.87     13490532.78
        2033525.       13490425.      2033524.56     13490393.54
      2033025.01     13489975.01
#Sta/Elev= 30
  4416.8  498.95  4577.4  497.98  4746.3  497.94  4822.6  496.61    4828  495.98
  4846.2  495.88  4851.6  495.13  4869.8  495.31  4875.2  494.22  4898.8  493.69
  4929.5491.1216  4935.2  489.92    4946  490.56  4951.4  488.82    4975  488.05
  4981.9  485.16  4982.8  484.36  4990.8  484.36  4991.8  485.16  4999.5  485.96
  5009.5  489.26  5023.8  489.89 5031.99491.1224    5041  491.79  5061.9  491.35
  5090.5  492.59  5303.9  494.58  5445.7  497.22  5573.2   501.5  5672.7  503.86
#Mann= 3 ,-1 , 0
  4416.8      .1       0  4981.9     .07       0  4991.8      .1       0
Bank Sta=4929.5,5031.99
XS Rating Curve= 0 ,0
Exp/Cntr=0.3,0.1

Type RM Length L Ch R = 1 ,16317   ,314,314,314
BEGIN DESCRIPTION:
WEST CLEAR CREEK 24.0
END DESCRIPTION:
XS GIS Cut Line= 3
      2033852.14     13491037.52        2033775.       13490225.
      2033090.95     13489799.44
#Sta/Elev= 30
  4167.1  508.33    4250   507.3  4295.4   507.9  4370.5  506.07  4430.8   506.1
  4541.3  502.69  4609.8  502.82  4631.7  501.21  4712.1  500.35  4742.2     499
  4812.5  497.96    4923  494.76  4929.2   494.4  4934.2  492.25 4944.46490.4837
  4953.1  488.22  4985.8  484.86  4986.7  484.06  4995.2  484.06  4996.1  484.86
  5006.3  488.78  5033.4  486.48  5048.8  490.51 5106.76490.4841  5158.6  491.48
  5171.7  492.48  5526.9   498.2  5636.6  501.39  5746.4     503  5788.9  505.09
#Mann= 3 ,-1 , 0
  4167.1      .1       0  4985.8     .07       0  4996.1      .1       0
Bank Sta=4944.46,5106.76
XS Rating Curve= 0 ,0
Exp/Cntr=0.3,0.1

Type RM Length L Ch R = 1 ,16003   ,362,362,362
BEGIN DESCRIPTION:
WEST CLEAR CREEK 23.0
END DESCRIPTION:
XS GIS Cut Line= 3
        2034325.       13490475.        2033825.       13489975.
      2033325.01       13489675.
#Sta/Elev= 30
  4282.2  501.83  4381.2  500.61  4423.6  499.54  4451.9  499.64  4466.1  499.26
  4508.5  496.67  4536.8  498.29  4579.2  498.29  4720.6  493.85  4819.6  491.54
 4933.33489.7296    4961  489.05  4975.2  487.98  4985.8  484.81  4989.3  484.81
  4991.9  481.24  4992.8  480.44  5001.3  480.44  5002.3  481.24  5002.9  484.46
  5012.6  488.13  5024.3  489.45 5035.51489.7296  5061.2   491.3  5092.3  492.13
  5129.3     492  5140.9  492.62  5177.8  492.66  5346.9  495.71  5572.4  502.69
#Mann= 3 ,-1 , 0
  4282.2      .1       0  4991.9     .07       0  5002.3      .1       0
Bank Sta=4933.33,5035.51
XS Rating Curve= 0 ,0
Exp/Cntr=0.3,0.1

Type RM Length L Ch R = 1 ,15641   ,319,319,319
BEGIN DESCRIPTION:
WEST CLEAR CREEK 22.0
END DESCRIPTION:
XS GIS Cut Line= 3
        2034275.       13490275.        2033975.       13489675.
      2033575.03     13489475.02
#Sta/Elev= 30
  4313.3  499.33    4344  498.33  4455.9  497.44  4483.8  494.17  4500.6  494.45
  4506.2  496.22  4528.5     496  4662.7  492.01  4715.8  491.47  4729.8  490.44
  4746.5  491.43  4760.5  490.59 4863.16488.7913  4961.8  487.23  4970.1   487.7
  4975.7  486.71  4981.3  488.02  4986.9  488.02  4992.9  482.69  4993.8  481.89
  5002.3  481.89  5003.3  482.69  5006.5  482.99  5014.9  486.74  5020.5   486.5
  5037.2  489.02  5161.4488.7919  5244.1  491.17  5288.8  494.22  5431.3  500.03
#Mann= 3 ,-1 , 0
  4313.3      .1       0  4992.9     .07       0  5003.3      .1       0
Bank Sta=4863.16,5161.4
XS Rating Curve= 0 ,0
Exp/Cntr=0.3,0.1

Type RM Length L Ch R = 1 ,15322   ,408,408,408
BEGIN DESCRIPTION:
WEST CLEAR CREEK 21.0
END DESCRIPTION:
XS GIS Cut Line= 3
      2034423.91     13490376.35      2034010.29     13489391.12
      2033614.43     13489251.78
#Sta/Elev= 30
  3887.5  500.94    4095  498.11  4214.3  494.58  4255.8  495.67  4314.1  493.02
  4332.5  494.99  4337.9   492.6  4344.5  492.49  4361.7  494.95  4390.9  493.39
  4467.6  493.25  4507.2  494.71  4520.5  490.96  4615.6  489.56    4659  491.53
  4673.9  488.47  4691.5  488.34  4703.1  490.69 4719.86487.8954  4756.6  487.08
  4767.5  491.47  4827.4  490.47  4982.8  486.35  4998.8  481.38  4999.7  480.58
  5009.2  481.38  5014.5  485.55  5050.6487.8946  5152.5  493.93  5375.7  499.35
#Mann= 3 ,-1 , 0
  3887.5      .1       0  4998.8     .07       0  5009.2      .1       0
Bank Sta=4719.86,5050.6
XS Rating Curve= 0 ,0
Exp/Cntr=0.3,0.1

Type RM Length L Ch R = 1 ,14914   ,373,373,373
BEGIN DESCRIPTION:
WEST CLEAR CREEK 20.0
END DESCRIPTION:
XS GIS Cut Line= 3
       2034330.2     13489647.01        2034325.       13489225.
       2033835.4     13489191.31
#Sta/Elev= 30
  4607.5  494.17  4739.5  492.99  4859.5   490.4  4869.5  490.54  4929.5   488.6
 4943.28486.7025  4949.5  485.39  4959.5  485.38  4969.5  486.45  4979.5   485.2
  4989.5  483.03  4994.3  479.88  4995.2  479.08  5003.8  479.08  5004.7  479.88
  5009.5  483.85    5027  486.27  5098.5  485.34  5103.5  486.19  5109.7  486.02
 5117.81486.7025  5251.5  492.09  5350.3  493.05  5370.3  492.87  5394.5  491.97
  5420.5  493.54  5430.5  492.52  5440.5   492.2  5460.6  493.37  5520.3   494.4
#Mann= 3 ,-1 , 0
  4607.5      .1       0  4994.3     .07       0  5004.7      .1       0
Bank Sta=4943.28,5117.81
XS Rating Curve= 0 ,0
Exp/Cntr=0.3,0.1

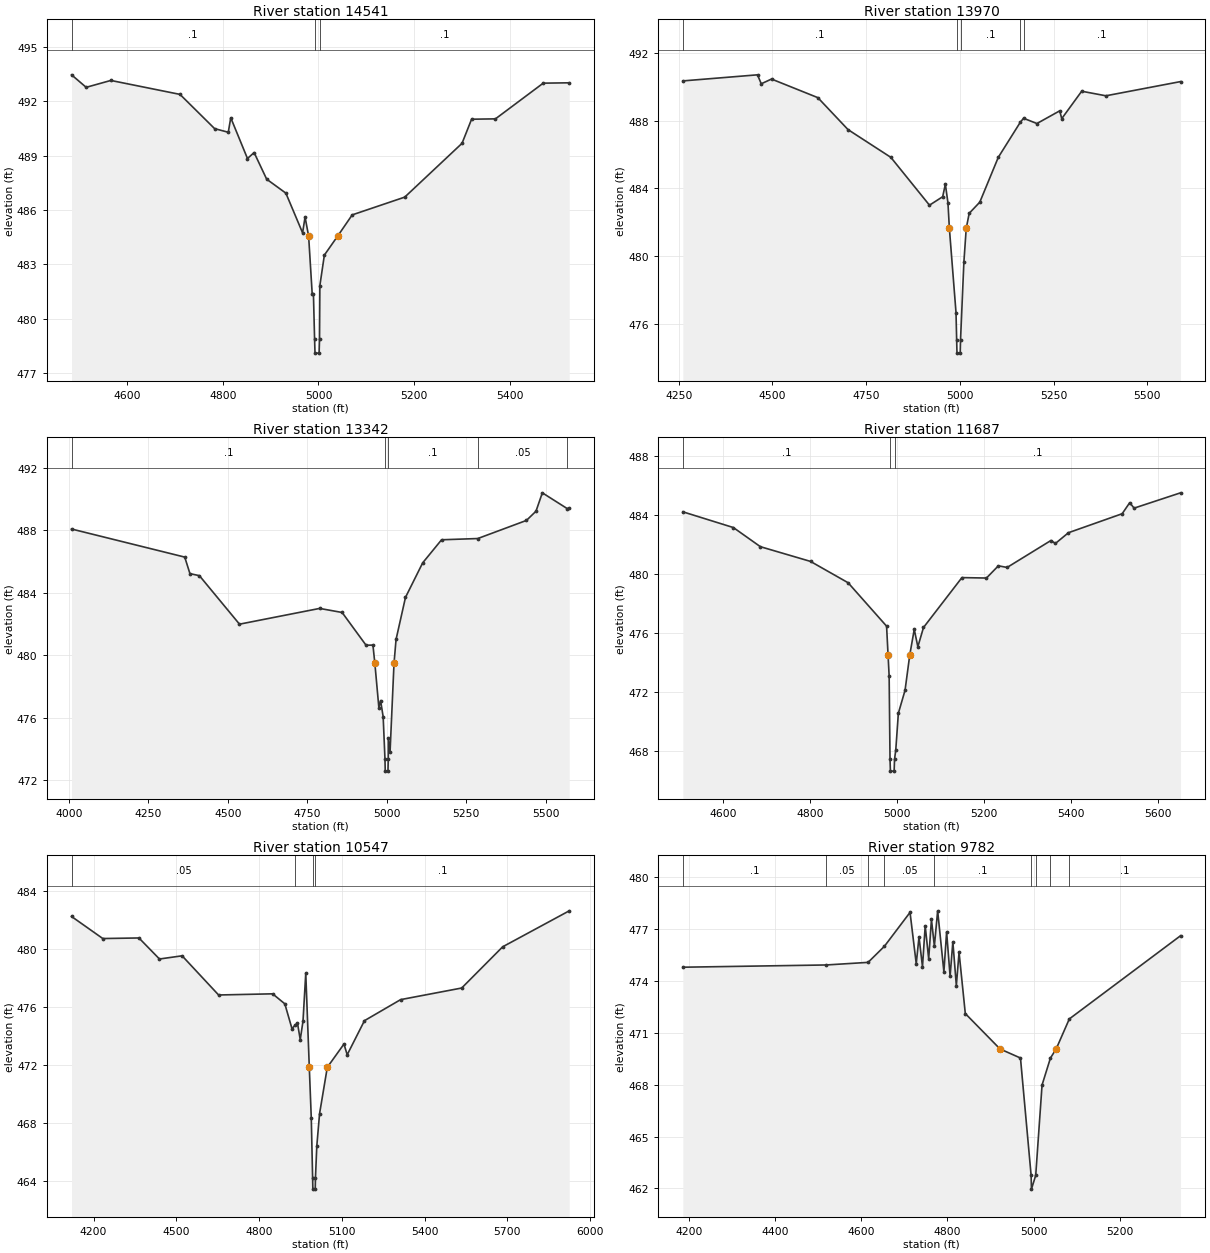
Type RM Length L Ch R = 1 ,14541   ,571,571,571
BEGIN DESCRIPTION:
WEST CLEAR CREEK 19.0
END DESCRIPTION:
XS GIS Cut Line= 4
      2034495.14     13489564.54        2034625.       13489075.
      2034563.53     13489036.21      2034100.53     13489042.11
#Sta/Elev= 30
  4482.9  493.46  4513.5  492.77  4565.2  493.15    4710  492.38  4782.5  490.49
  4811.1  490.29  4816.3  491.09  4851.3  488.84  4865.2  489.17  4891.5   487.7
  4931.7  486.93  4966.7  484.74  4971.9  485.61 4979.35484.5605  4986.8  481.38
  4989.4  481.38  4991.8   478.9  4992.7   478.1  5001.3   478.1  5002.2   478.9
  5002.9  481.83  5012.3  483.51 5040.12484.5587  5070.6  485.73  5180.6  486.71
  5300.6  489.68  5320.6  491.01  5370.6  491.03  5470.6     493  5525.1  493.02
#Mann= 3 ,-1 , 0
  4482.9      .1       0  4991.8     .07       0  5002.2      .1       0
Bank Sta=4979.35,5040.12
XS Rating Curve= 0 ,0
Exp/Cntr=0.3,0.1

Type RM Length L Ch R = 1 ,13970   ,628,628,628
BEGIN DESCRIPTION:
WEST CLEAR CREEK 18.0
END DESCRIPTION:
XS GIS Cut Line= 4
      2035082.93      13489412.9      2035145.44      13488864.9
       2034903.9     13488610.13       2034511.1     13488772.89
#Sta/Elev= 30
    4261  490.36  4460.2  490.72  4470.2  490.19  4497.6  490.47  4621.2  489.37
  4701.7  487.48  4815.9  485.84    4919  483.01  4954.2  483.51  4961.4  484.25
  4968.3  483.15 4972.11481.6365  4989.8  476.66  4991.5  475.06  4992.4  474.26
    5001  474.26  5001.9  475.06  5010.8  479.64 5017.06481.6381    5025  482.53
  5053.3  483.19  5102.6  485.84  5161.2  487.91    5170  488.15  5205.7  487.84
  5266.5  488.59  5271.9  488.13  5325.1  489.75  5389.7  489.48  5588.8  490.32
#Mann= 5 ,-1 , 0
    4261      .1       0  4991.5     .07       0  5001.9      .1       0
  5161.2     .05       0    5170      .1       0
Bank Sta=4972.11,5017.06
XS Rating Curve= 0 ,0
Exp/Cntr=0.3,0.1

Type RM Length L Ch R = 1 ,13342   ,1655,1655,1655
BEGIN DESCRIPTION:
WEST CLEAR CREEK 17.0
END DESCRIPTION:
XS GIS Cut Line= 4
      2035633.13      13489402.8      2035779.61     13489118.86
      2035466.45     13488329.92      2035070.62     13488303.88
#Sta/Elev= 30
  4008.8  488.09  4364.7  486.29  4381.1  485.23  4410.8   485.1  4536.9  481.99
  4788.9     483  4859.6  482.74  4934.9  480.64  4956.5  480.65 4962.59479.4719
  4975.2  476.63  4980.6  477.09  4988.7  476.05  4994.3  473.37  4995.2  472.57
  5003.8  472.57  5004.7  473.37  5004.9  474.69  5010.3  473.78 5022.77479.4731
  5029.2  481.01  5058.9  483.71  5112.9  485.92  5172.3   487.4  5286.2  487.48
  5439.1  488.64  5469.2  489.23  5489.2  490.41  5567.4   489.4  5573.8  489.44
#Mann= 5 ,-1 , 0
  4008.8      .1       0  4994.3     .07       0  5004.7      .1       0
  5286.2     .05       0  5567.4      .1       0
Bank Sta=4962.59,5022.77
XS Rating Curve= 0 ,0
Exp/Cntr=0.3,0.1

Type RM Length L Ch R = 1 ,11687   ,1140,1140,1140
BEGIN DESCRIPTION:
WEST CLEAR CREEK 16.0
END DESCRIPTION:
XS GIS Cut Line= 4
      2036513.31     13488908.07      2036599.05     13488716.09
      2036362.28     13488335.13      2035878.99     13488397.49
#Sta/Elev= 30
  4506.7  484.22  4623.1  483.15  4685.3  481.85  4800.7  480.85  4887.3   479.4
  4975.9  476.45 4979.29474.4963  4981.8  473.05  4983.8   467.4  4984.7   466.6
  4993.3   466.6  4994.2   467.4  4997.1  468.05    5003  470.53  5018.4  472.09
 5029.26474.4934  5039.6  476.23  5047.9  475.05  5060.9  476.36  5149.4  479.75
  5205.9  479.72  5233.3  480.55  5253.5  480.44  5354.3  482.27  5364.7  482.07
  5394.7   482.8  5518.4  484.09  5535.8  484.84  5545.9  484.47  5652.8  485.51
#Mann= 3 ,-1 , 0
  4506.7      .1       0  4983.8     .07       0  4994.2      .1       0
Bank Sta=4979.29,5029.26
XS Rating Curve= 0 ,0
Exp/Cntr=0.3,0.1

Type RM Length L Ch R = 1 ,10547   ,765,765,765
BEGIN DESCRIPTION:
WEST CLEAR CREEK 15.0
END DESCRIPTION:
XS GIS Cut Line= 5
      2036758.13     13488887.21      2037357.07     13488736.17
      2037339.19      13488345.5      2037070.62     13488178.88
      2036612.24     13488038.24
#Sta/Elev= 30
  4120.4  482.22  4233.7   480.7  4364.7  480.74  4439.1  479.29  4521.2  479.51
  4653.5  476.81  4849.4  476.89  4893.6   476.2  4919.5  474.49  4930.9  474.73
  4939.5  474.87  4949.5  473.73  4959.5  475.01  4969.5  478.31  4982.3471.8293
  4989.5  468.33  4994.3  464.23  4995.2  463.43  5003.8  463.43  5004.7  464.23
  5009.5   466.4  5019.6  468.64 5047.61 471.827    5108  473.43  5119.7  472.69
  5182.3  475.04  5313.4  476.49  5534.8  477.29  5683.3  480.13  5924.7  482.61
#Mann= 4 ,-1 , 0
  4120.4     .05       0  4930.9      .1       0  4994.3     .07       0
  5004.7      .1       0
Bank Sta=4982.3,5047.61
XS Rating Curve= 0 ,0
Exp/Cntr=0.3,0.1

Type RM Length L Ch R = 1 ,9782    ,627,627,627
BEGIN DESCRIPTION:
WEST CLEAR CREEK 14.0
END DESCRIPTION:
XS GIS Cut Line= 4
       2037513.7     13489004.66      2037957.81     13488441.74
      2037966.49     13488298.51      2037848.37     13488028.21
#Sta/Elev= 30
  4185.6  474.79  4518.5  474.92  4615.7  475.07  4653.6     476  4713.1  477.96
  4727.5  474.99  4733.9  476.54    4742  474.82  4748.3  477.18  4756.4  475.28
  4762.8  477.55  4769.6  476.01  4777.2  478.05  4791.7  474.52    4798  476.83
  4806.1  474.27  4812.5  476.26  4820.6  473.73  4826.9  475.65  4841.4  472.11
 4922.04470.0633  4969.5  469.54  4994.2  462.76    4995  461.96  5004.9  462.76
  5019.6  467.98  5039.1  469.54 5052.36470.0634  5082.9   471.8  5341.1  476.61
#Mann= 9 ,-1 , 0
  4185.6      .1       0  4518.5     .05       0  4615.7      .1       0
  4653.6     .05       0  4769.6      .1       0  4994.2     .07       0
  5004.9      .1       0  5039.1     .16       0  5082.9      .1       0
Bank Sta=4922.04,5052.36
XS Rating Curve= 0 ,0
Exp/Cntr=0.3,0.1

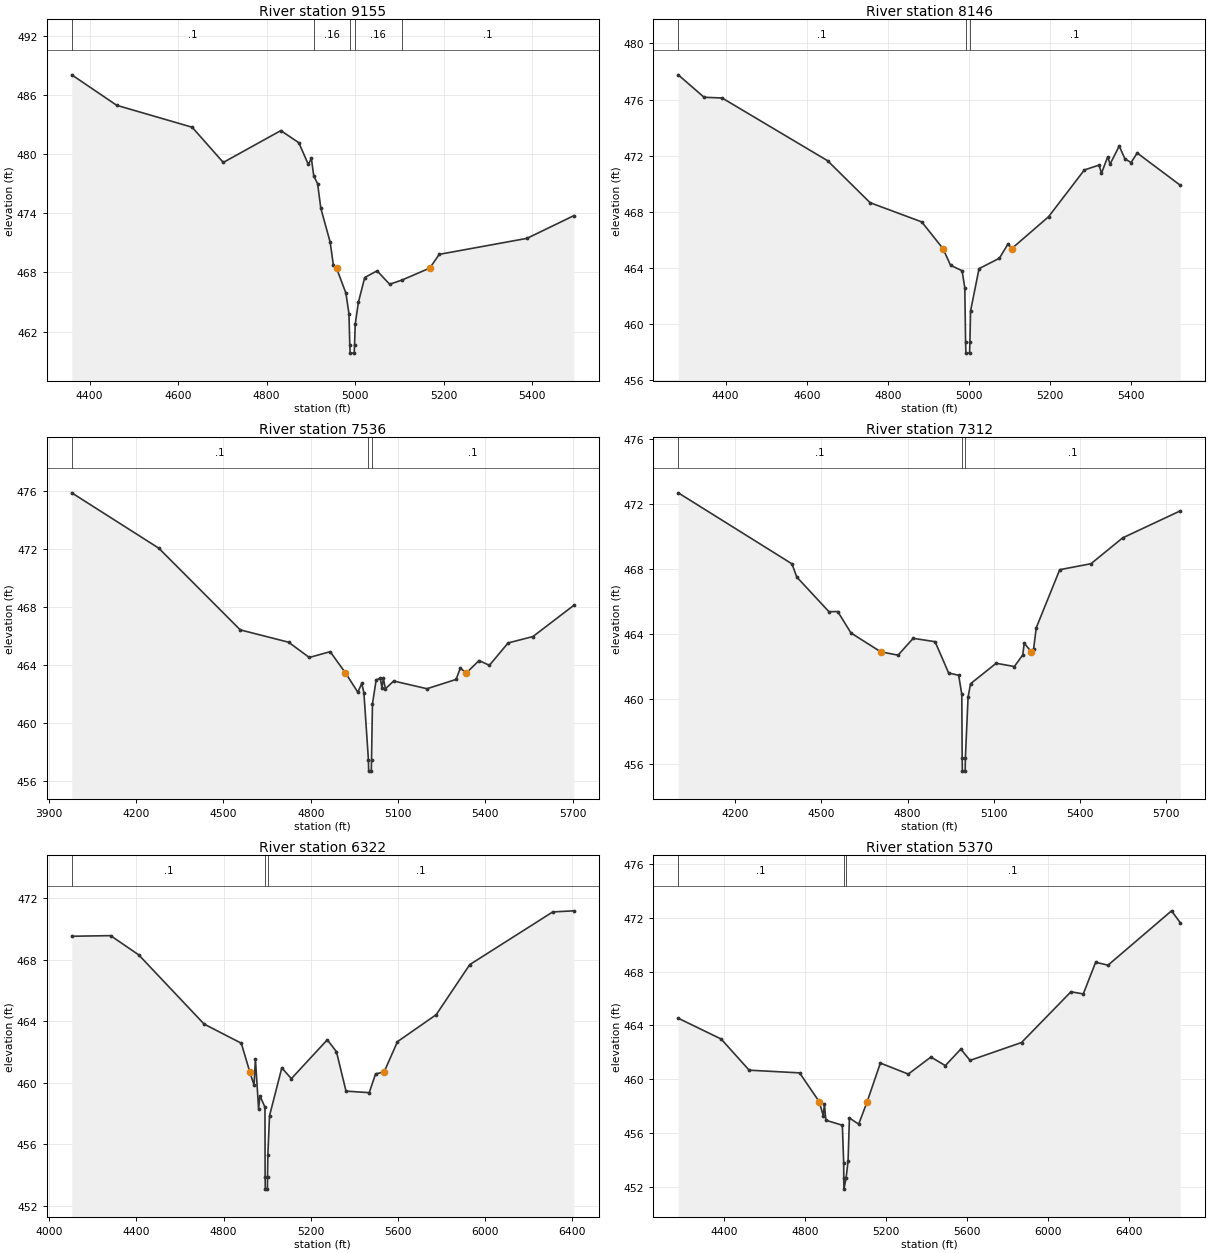
Type RM Length L Ch R = 1 ,9155    ,1009,1009,1009
BEGIN DESCRIPTION:
WEST CLEAR CREEK 13.0
END DESCRIPTION:
XS GIS Cut Line= 4
      2038638.61     13488846.47      2038612.57      13488375.1
      2038401.63     13488174.58      2038056.31     13488039.57
#Sta/Elev= 30
  4359.9  488.03  4461.5  484.94  4631.8  482.72  4702.1  479.15    4832  482.38
  4872.7  481.15  4894.1  478.95    4901  479.57  4906.4  477.79  4915.1     477
  4922.4   474.5  4943.5  471.07  4950.7  468.75 4957.81468.4454    4979  465.91
  4985.9  463.83  4987.8  460.63  4988.7  459.83  4997.7  459.83  4998.5  460.63
  5000.1  462.77  5007.3  464.99  5021.5  467.49  5049.4  468.17  5077.8  466.81
  5105.4  467.23 5168.33 468.446  5189.9  469.84    5388  471.46  5493.8  473.76
#Mann= 5 ,-1 , 0
  4359.9      .1       0  4906.4     .16       0  4987.8     .07       0
  4998.5     .16       0  5105.4      .1       0
Bank Sta=4957.81,5168.33
XS Rating Curve= 0 ,0
Exp/Cntr=0.3,0.1

Type RM Length L Ch R = 1 ,8146    ,610,610,610
BEGIN DESCRIPTION:
WEST CLEAR CREEK 12.0
END DESCRIPTION:
XS GIS Cut Line= 5
      2038938.09     13488158.97      2038783.21     13487614.31
      2038626.96      13487440.7      2038283.21     13487659.45
      2038265.87     13487683.72
#Sta/Elev= 30
  4283.5  477.76  4347.2  476.16  4391.6  476.11  4651.5  471.64  4756.2  468.65
  4883.5  467.28 4935.72465.3831  4954.5  464.19  4982.9   463.8  4989.6  462.58
  4991.5  458.73  4992.3  457.93  5001.3  457.93  5002.2  458.73  5003.8  460.94
  5024.7  463.95  5074.8  464.69  5096.1  465.71 5105.44465.3836    5196  467.65
  5284.1  470.98  5320.5  471.33  5326.4  470.75  5341.6  471.91  5347.6   471.4
  5370.1  472.69    5384  471.78  5399.2  471.51  5414.4  472.19  5520.6  469.89
#Mann= 3 ,-1 , 0
  4283.5      .1       0  4991.5     .07       0  5002.2      .1       0
Bank Sta=4935.72,5105.44
XS Rating Curve= 0 ,0
Exp/Cntr=0.3,0.1

Type RM Length L Ch R = 1 ,7536    ,224,224,224
BEGIN DESCRIPTION:
WEST CLEAR CREEK 11.0
END DESCRIPTION:
XS GIS Cut Line= 4
      2038974.54     13488079.99      2039131.23     13487141.16
       2039063.5     13487048.02      2038538.96     13487445.65
#Sta/Elev= 30
  3978.7  475.84  4277.8  472.03  4557.6  466.41  4723.9  465.56  4794.8  464.51
  4866.6  464.91 4919.14463.4488  4961.7  462.12  4975.2  462.73  4982.5  462.09
    4998  457.49  4998.9  456.69  5007.9  456.69  5008.7  457.49  5011.9  461.32
  5024.7  462.97  5038.9  463.07  5044.5  462.44  5049.5  463.07  5056.3  462.36
  5084.9  462.89  5199.3  462.36  5299.2     463  5313.7  463.77 5334.71463.4491
  5378.2   464.3  5413.6  463.97    5478  465.51  5563.3  465.95  5703.9   468.1
#Mann= 3 ,-1 , 0
  3978.7      .1       0    4998     .07       0  5008.7      .1       0
Bank Sta=4919.14,5334.71
XS Rating Curve= 0 ,0
Exp/Cntr=0.3,0.1

Type RM Length L Ch R = 1 ,7312    ,990,990,990
BEGIN DESCRIPTION:
WEST CLEAR CREEK 10.0
END DESCRIPTION:
XS GIS Cut Line= 4
      2039213.69     13487939.81      2039361.27     13487191.07
      2039136.43     13486664.67      2038724.07     13486664.67
#Sta/Elev= 30
  4001.4  472.69  4397.4  468.31    4414   467.5  4526.1  465.36  4556.7  465.37
  4602.7  464.05 4706.18462.8887  4766.7  462.68  4819.4  463.72  4895.6  463.51
  4942.8  461.58  4977.7  461.44  4988.6  460.26  4989.9  456.33  4990.6  455.53
  5000.3  455.53    5001  456.33  5010.4  460.09  5019.1  460.92  5108.2  462.18
  5171.6  461.98  5200.6  462.69  5206.1  463.42 5230.47462.8888  5238.7  463.09
  5247.8  464.37  5329.5  467.95  5438.4  468.32  5548.4  469.91  5749.3  471.58
#Mann= 3 ,-1 , 0
  4001.4      .1       0  4989.9     .07       0    5001      .1       0
Bank Sta=4706.18,5230.47
XS Rating Curve= 0 ,0
Exp/Cntr=0.3,0.1

Type RM Length L Ch R = 1 ,6322    ,952,952,952
BEGIN DESCRIPTION:
WEST CLEAR CREEK 9.0
END DESCRIPTION:
XS GIS Cut Line= 4
      2039606.06     13487756.61      2040029.67     13487190.64
       2039516.2     13486491.06      2038800.09     13486632.11
#Sta/Elev= 30
  4103.5  469.51  4281.8  469.55    4411   468.3  4711.1  463.81  4881.6  462.57
 4920.91460.6982  4940.2  459.85  4946.4  461.55    4961  458.31  4967.2  459.15
  4990.3  458.42    4991   453.9  4991.7   453.1  5001.4   453.1  5002.1   453.9
  5003.5  455.29  5011.2  457.86  5067.6  460.97  5111.5  460.27  5276.4  462.79
  5318.4  462.02  5362.3  459.46  5468.8  459.36  5498.1  460.58 5536.97 460.698
  5598.5  462.67  5776.3  464.42  5930.3  467.67  6311.4  471.09  6408.1  471.16
#Mann= 3 ,-1 , 0
  4103.5      .1       0    4991     .07       0  5002.1      .1       0
Bank Sta=4920.91,5536.97
XS Rating Curve= 0 ,0
Exp/Cntr=0.3,0.1

Type RM Length L Ch R = 1 ,5370    ,984,984,984
BEGIN DESCRIPTION:
WEST CLEAR CREEK 8.0
END DESCRIPTION:
XS GIS Cut Line= 4
      2040728.57     13487152.44      2040204.24     13486270.45
      2038822.29     13486534.34      2038784.12     13486565.57
#Sta/Elev= 30
  4171.4  464.54  4383.7  462.99    4522  460.67  4771.4  460.47 4868.89458.3122
  4888.3  457.28  4894.1  458.15  4901.3  456.94  4982.8  456.57  4989.5  453.73
  4989.8  452.61  4990.5  451.81  5000.9  452.61    5011  453.87  5017.7  457.11
  5063.6  456.65 5105.17458.3123  5170.7   461.2  5308.7  460.38  5420.7  461.65
  5491.9  461.01  5568.3  462.24  5614.1   461.4  5868.6  462.73    6113  466.51
    6174  466.35  6235.1  468.71  6296.2  468.49  6610.3  472.54  6653.7  471.65
#Mann= 3 ,-1 , 0
  4171.4      .1       0  4989.8     .07       0  5000.9      .1       0
Bank Sta=4868.89,5105.17
XS Rating Curve= 0 ,0
Exp/Cntr=0.3,0.1

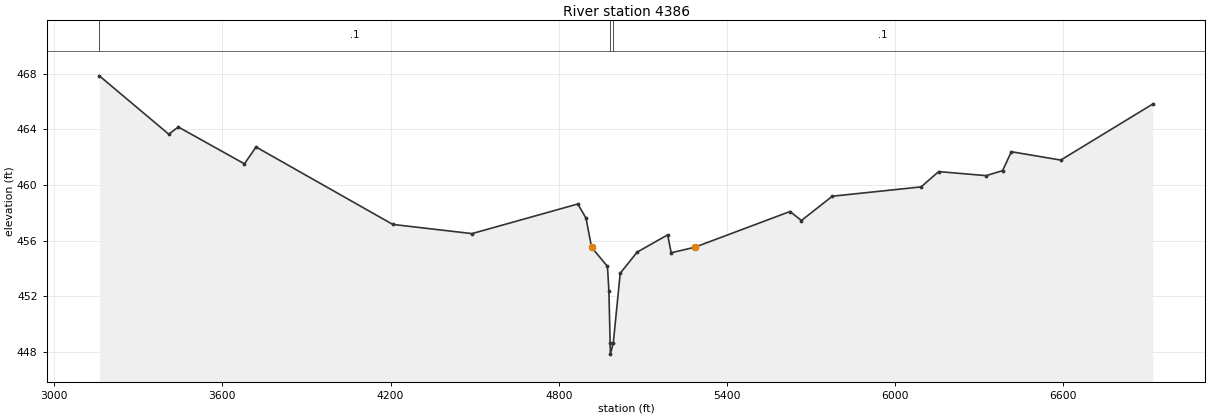
Type RM Length L Ch R = 1 ,4386    ,285,285,285
BEGIN DESCRIPTION:
WEST CLEAR CREEK 7.0
END DESCRIPTION:
XS GIS Cut Line= 5
       2041035.3     13487673.79      2041447.63     13486187.24
      2040590.42     13486067.89      2040167.25     13486132.99
      2039278.79     13486379.02
#Sta/Elev= 30
  3161.1  467.86  3408.9  463.66  3442.9  464.18  3678.7  461.53  3720.2  462.74
    4208  457.17  4490.8  456.51    4868  458.64  4897.3  457.63  4917.2455.5286
  4973.9  454.15    4979  452.41  4983.5  448.64  4984.3  447.84  4994.7  448.64
  5019.4  453.66    5080  455.18  5188.7  456.42  5201.2  455.13 5285.38455.5286
  5625.3   458.1  5665.8  457.45  5776.2   459.2  6093.1  459.87  6155.4  460.97
    6325  460.68  6383.7  461.04  6414.8   462.4  6591.2   461.8  6919.3  465.83
#Mann= 3 ,-1 , 0
  3161.1      .1       0  4983.5     .07       0  4994.7      .1       0
Bank Sta=4917.2,5285.38
XS Rating Curve= 0 ,0
Exp/Cntr=0.3,0.1