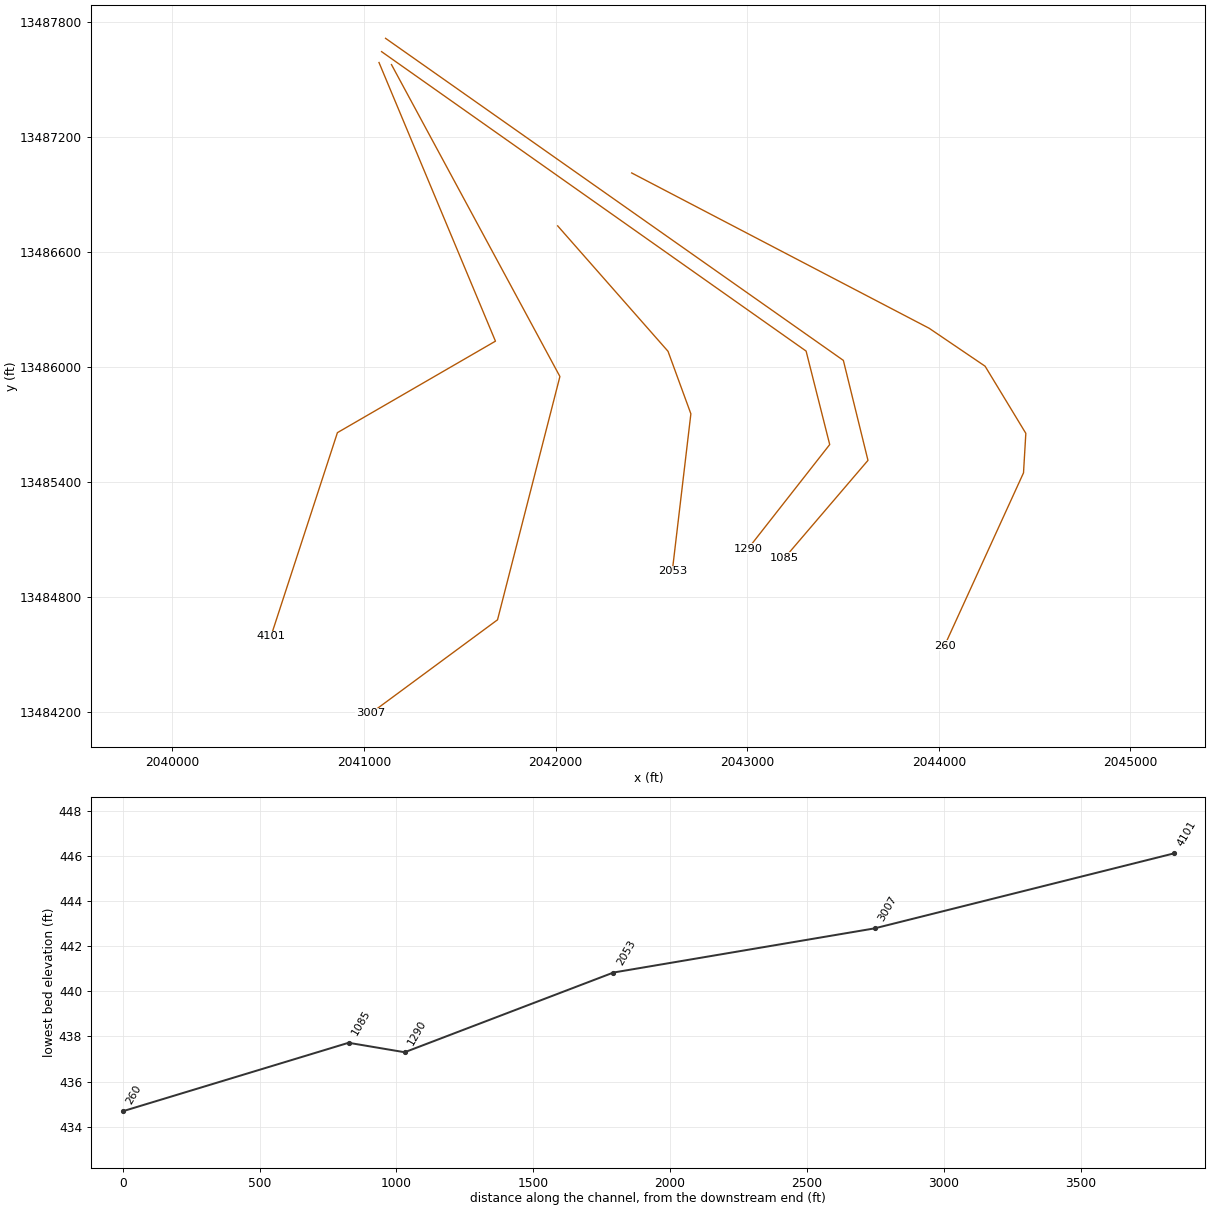
HEC-RAS study WEST CLEAR CREEK.prj: WEST CLEAR CREEK Base Level Engineering

--- WEST CLEAR CREEK.g01 (geometry) --- (continued)

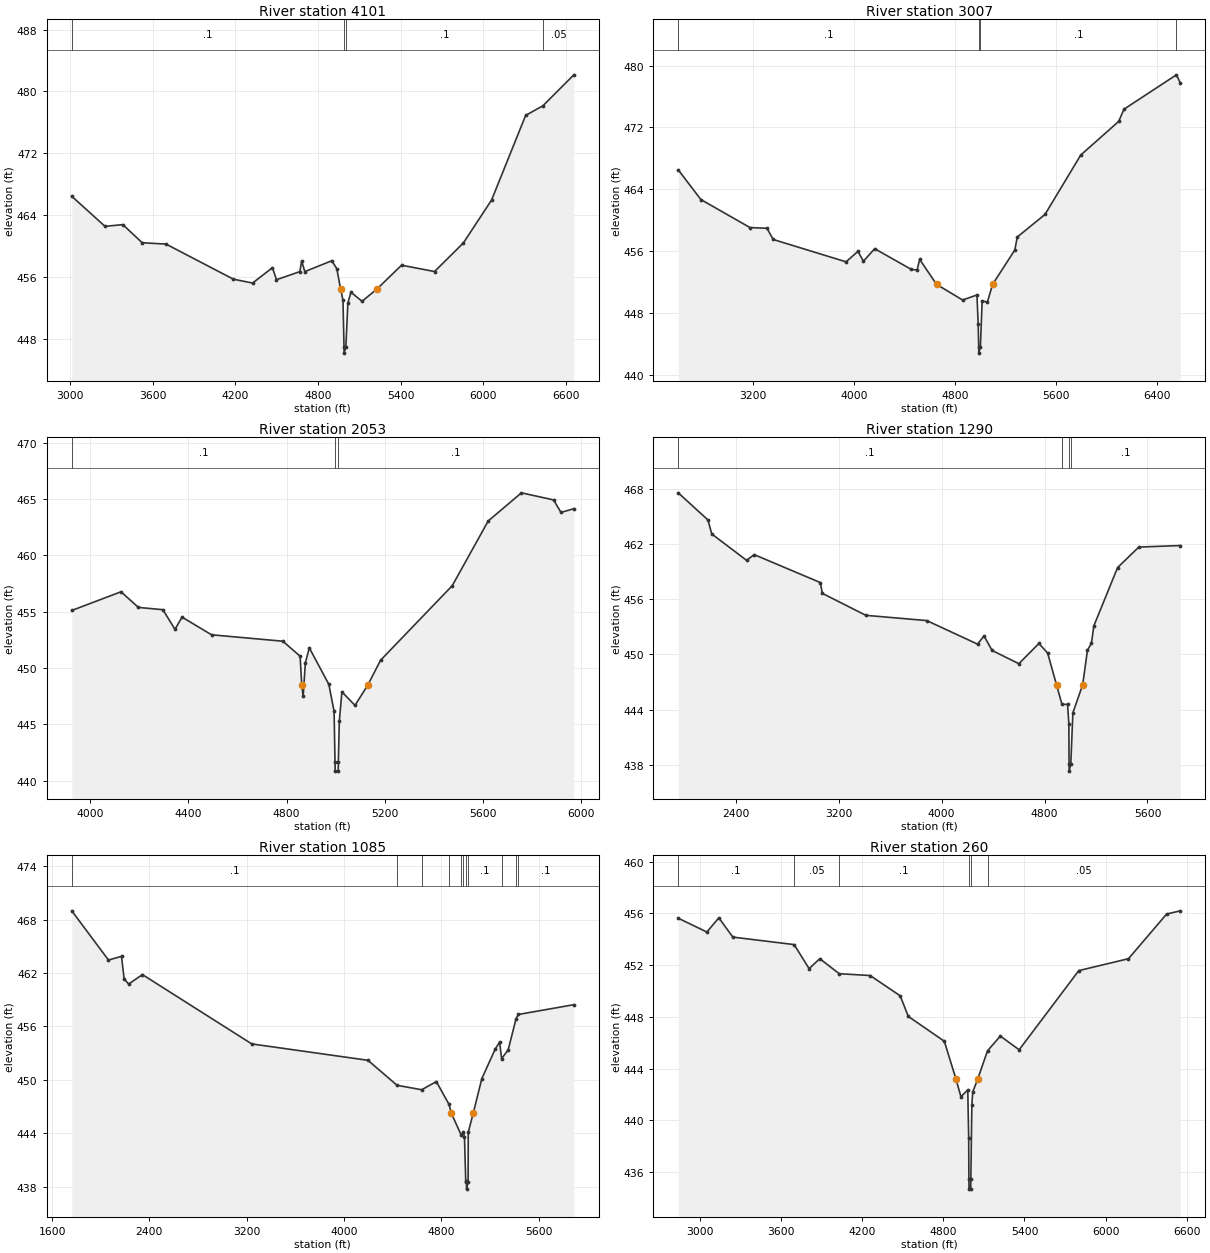
Type RM Length L Ch R = 1 ,4101    ,1094,1094,1094
BEGIN DESCRIPTION:
WEST CLEAR CREEK 6.0
END DESCRIPTION:
XS GIS Cut Line= 4
       2041078.7     13487586.99      2041686.34     13486132.99
      2040861.69     13485655.56      2040514.46     13484592.16
#Sta/Elev= 30
  3011.4  466.43  3252.8  462.54  3382.7  462.76  3522.9  460.42  3696.4  460.24
  4185.6   455.7    4325   455.2  4469.2  457.19  4498.4  455.63  4668.5  456.68
  4681.2  458.05  4704.4  456.68  4900.8  458.09  4936.9  457.05 4964.41454.4223
  4981.7  452.97  4989.1  446.93  4989.7  446.13  5002.4  446.93  5017.2  452.62
  5039.5  454.01  5120.3  452.84 5227.91454.4224  5407.5  457.51  5646.7  456.69
  5856.3  460.39  6061.3  465.95  6308.7   476.9  6434.5  478.15  6658.8  482.15
#Mann= 4 ,-1 , 0
  3011.4      .1       0  4989.1     .07       0  5002.4      .1       0
  6434.5     .05       0
Bank Sta=4964.41,5227.91
XS Rating Curve= 0 ,0
Exp/Cntr=0.3,0.1

Type RM Length L Ch R = 1 ,3007    ,954,954,954
BEGIN DESCRIPTION:
WEST CLEAR CREEK 5.0
END DESCRIPTION:
XS GIS Cut Line= 4
       2041143.8     13487576.15      2042022.71     13485948.53
      2041697.19       13484679.      2041035.28      13484190.7
#Sta/Elev= 30
  2605.9  466.51  2785.3  462.67  3175.4  459.04  3309.8  458.95  3359.3   457.5
  3936.9  454.61  4031.3  455.96    4075  454.69  4164.2  456.31  4454.8  453.63
  4500.6  453.55  4521.3  454.92 4655.48451.6906  4861.9  449.67  4975.5  450.32
  4985.3  446.55  4989.4   443.6  4990.1   442.8  5002.8   443.6  5016.8  449.57
  5058.1  449.39 5099.67451.6904  5275.9  456.14  5295.5  457.82  5515.4  460.74
  5799.2  468.43  6099.9  472.77  6141.8  474.35  6557.9   478.8  6588.8  477.74
#Mann= 4 ,-1 , 0
  2605.9      .1       0  4989.4     .07       0  5002.8      .1       0
  6557.9     .05       0
Bank Sta=4655.48,5099.67
XS Rating Curve= 0 ,0
Exp/Cntr=0.3,0.1

Type RM Length L Ch R = 1 ,2053    ,763,763,763
BEGIN DESCRIPTION:
WEST CLEAR CREEK 4.0
END DESCRIPTION:
XS GIS Cut Line= 5
      2042011.06     13486734.57      2042586.89       13486080.
      2042706.11     13485753.86      2042609.39     13484935.12
      2042609.39     13484932.91
#Sta/Elev= 30
  3924.7  455.11  4125.2  456.77  4196.4  455.38    4296  455.18  4345.3  453.43
  4373.8  454.52  4494.3  452.95  4784.6  452.38  4855.1  451.05 4861.73448.4738
  4867.4  447.48  4876.4  450.45  4892.6  451.79  4972.2  448.54  4993.5  446.15
  4997.3  441.64  4998.1  440.84  5010.2  440.84  5010.9  441.64  5014.8  445.28
  5025.4  447.88  5078.7  446.68 5130.59448.4737  5182.9  450.69  5474.9  457.31
  5621.5  463.06  5756.8  465.56  5887.8  464.93    5918  463.82  5970.4  464.15
#Mann= 3 ,-1 , 0
  3924.7      .1       0  4997.3     .07       0  5010.9      .1       0
Bank Sta=4861.73,5130.59
XS Rating Curve= 0 ,0
Exp/Cntr=0.3,0.1

Type RM Length L Ch R = 1 ,1290    ,205,205,205
BEGIN DESCRIPTION:
WEST CLEAR CREEK 3.0
END DESCRIPTION:
XS GIS Cut Line= 4
      2041092.13     13487643.75      2043307.38     13486081.27
      2043430.59     13485593.42      2043005.25     13485050.89
#Sta/Elev= 30
    1952  467.56    2183  464.61  2212.5  463.09  2483.4  460.22  2542.6  460.84
  3057.3   457.8    3072  456.63  3410.7  454.24  3883.6  453.67  4278.9  451.11
  4329.4     452  4392.1  450.42  4600.3  448.98  4756.1  451.18    4824  450.14
 4893.08446.6697  4935.3  444.56  4978.7  444.56    4989  442.46  4990.4   438.1
  4991.2   437.3  5004.1   438.1    5020  443.64 5096.01446.6692  5133.4  450.43
  5164.8  451.23  5183.1  453.09  5367.6  459.43  5532.5  461.66  5855.4  461.83
#Mann= 4 ,-1 , 0
    1952      .1       0  4935.3     .05       0  4990.4     .07       0
  5004.1      .1       0
Bank Sta=4893.08,5096.01
XS Rating Curve= 0 ,0
Exp/Cntr=0.3,0.1

Type RM Length L Ch R = 1 ,1085    ,825,825,825
BEGIN DESCRIPTION:
WEST CLEAR CREEK 2.0
END DESCRIPTION:
XS GIS Cut Line= 4
      2041112.95     13487713.21      2043501.82     13486032.66
      2043630.24     13485510.95       2043196.2     13485003.13
#Sta/Elev= 30
  1761.9     469  2063.4  463.47  2170.6  463.88  2192.3  461.35    2229  460.77
  2343.1  461.83  3241.2  454.04    4196   452.2    4435  449.39  4637.6  448.89
  4758.1  449.81  4862.4  447.24 4881.75446.2383  4963.2  443.77  4980.5  444.13
  4989.2  443.59  4999.5  438.68  5005.5  438.52  5006.3  437.72  5019.2  438.52
  5020.1  444.11 5060.98446.2386  5131.8  450.14  5241.6  453.45  5277.9  454.25
  5294.2  452.38  5348.1  453.37  5413.6  456.89    5432  457.35    5888  458.45
#Mann= 11 ,-1 , 0
  1761.9      .1       0    4435     .05       0  4637.6      .1       0
  4862.4     .08       0  4963.2     .05       0  4980.5      .1       0
  5005.5     .07       0  5019.2      .1       0  5294.2     .08       0
  5413.6     .05       0    5432      .1       0
Bank Sta=4881.75,5060.98
XS Rating Curve= 0 ,0
Exp/Cntr=0.3,0.1

Type RM Length L Ch R = 1 ,260     ,0,0,0
BEGIN DESCRIPTION:
WEST CLEAR CREEK 1.0
END DESCRIPTION:
XS GIS Cut Line= 6
      2042397.32     13487010.69        2043950.       13486200.
      2044241.37     13486002.37        2044454.     13485651.93
      2044441.88     13485445.85      2044029.79      13484543.6
#Sta/Elev= 30
  2840.4  455.62  3052.1  454.55  3140.6  455.65  3243.9  454.16  3697.3  453.58
    3808  451.72  3886.9  452.49  4030.7  451.33  4259.2  451.19  4481.6  449.62
  4541.2  448.03  4807.6  446.11 4893.94443.1787  4930.4  441.82  4980.9  442.35
  4987.8  438.64  4989.2  435.48  4990.3  434.68  5002.6  434.68  5003.7  435.48
  5011.2   441.2  5017.8   442.2 5054.21443.1786  5126.9  445.37  5221.7  446.51
  5360.9  445.45  5801.7  451.57  6169.1  452.49  6450.9  455.94  6552.3  456.19
#Mann= 6 ,-1 , 0
  2840.4      .1       0  3697.3     .05       0  4030.7      .1       0
  4989.2     .07       0  5003.7      .1       0  5126.9     .05       0
Bank Sta=4893.94,5054.21
XS Rating Curve= 0 ,0
Exp/Cntr=0.3,0.1
LCMann Table=0

Chan Stop Cuts=-1
Use User Specified Reach Order=0
Composite Channel Slope=5