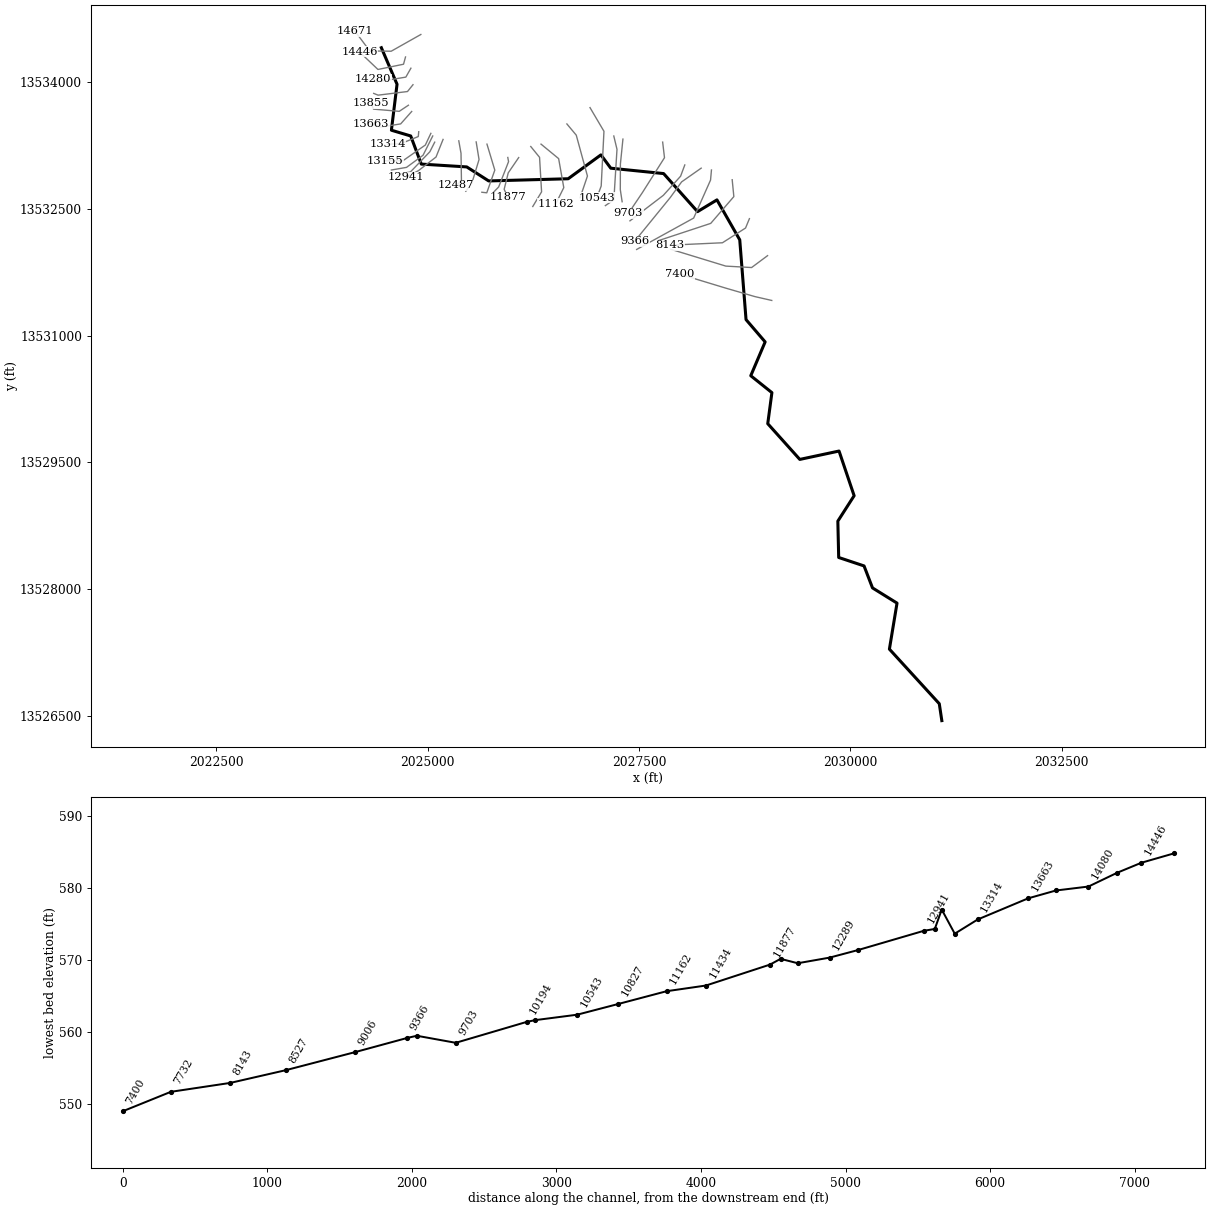
--- WEST FORK ELLIS Br.prj (project) ---

Proj Title=WEST FORK ELLIS Br Base Level Engineering
Current Plan=p01
Default Exp/Contr=0.3,0.1
English Units
Geom File=g01
Flow File=f01
Plan File=p01
BEGIN DESCRIPTION:
WEST FORK ELLIS Br
END DESCRIPTION:

--- WEST FORK ELLIS Br.p01 (plan) ---

Plan Title=Multiple Run
Short Identifier=Multiple
Geom File=g01
Flow File=f01
Subcritical Flow
K Sum by GR= 0
Std Step Tol= 0.01
Critical Tol= 0.01
Num of Std Step Trials= 20
Max Error Tol= 0.3
Flow Tol Ratio= 0.001
Split Flow NTrial= 30
Split Flow Tol= 0.02
Split Flow Ratio= 0.02
Log Output Level= 0
Friction Slope Method= 1
Unsteady Friction Slope Method= 2
Unsteady Bridges Friction Slope Method= 1
Parabolic Critical Depth
Global Vel Dist=  1 , 1 , 1
Global Log Level= 0
CheckData=True
Encroach Param= -1, 0, 0, 0
BEGIN DESCRIPTION:
Multiple Run
END DESCRIPTION:

--- WEST FORK ELLIS Br.f01 (steady flow) ---

Flow Title=Multiple
Number of Profiles=7
Profile Names=10-year,25-year,50-year,1pct_min,100-year,1pct_plu,500-year
River Rch & RM= WEST FORK ELLIS ,Reach-1,14671
     164     221     267     161     321     641     471
River Rch & RM= WEST FORK ELLIS ,Reach-1,12487
     248     342     418     255     509    1016     766
River Rch & RM= WEST FORK ELLIS ,Reach-1,7400
     295     409     503     308     615    1227     934
Boundary for River Rch & Prof#=WEST FORK ELLIS ,Reach-1,1
Up Type=0
Dn Type=3
Dn Slope=0.005
Boundary for River Rch & Prof#=WEST FORK ELLIS ,Reach-1,2
Up Type=0
Dn Type=3
Dn Slope=0.005
Boundary for River Rch & Prof#=WEST FORK ELLIS ,Reach-1,3
Up Type=0
Dn Type=3
Dn Slope=0.005
Boundary for River Rch & Prof#=WEST FORK ELLIS ,Reach-1,4
Up Type=0
Dn Type=3
Dn Slope=0.005
Boundary for River Rch & Prof#=WEST FORK ELLIS ,Reach-1,5
Up Type=0
Dn Type=3
Dn Slope=0.005
Boundary for River Rch & Prof#=WEST FORK ELLIS ,Reach-1,6
Up Type=0
Dn Type=3
Dn Slope=0.005
Boundary for River Rch & Prof#=WEST FORK ELLIS ,Reach-1,7
Up Type=0
Dn Type=3
Dn Slope=0.005

--- WEST FORK ELLIS Br.g01 (geometry) ---

Geom Title=Existing Conditions

River Reach=WEST FORK ELLIS ,Reach-1
Reach XY= 30
      2024450.80     13534404.54      2024636.37     13533972.47
      2024569.70     13533428.72      2024798.17     13533360.67
      2024923.17     13533028.03      2025460.80     13532994.54
      2025720.39     13532828.72      2026660.80     13532854.54
      2027048.17     13533137.06      2027164.82     13532979.42
      2027789.65     13532915.83      2028191.13     13532465.53
      2028420.80     13532604.54      2028690.43     13532131.94
      2028764.87     13531188.10      2028990.80     13530924.54
      2028820.80     13530524.54      2029070.80     13530324.54
      2029021.64     13529957.24      2029400.80     13529534.54
      2029865.06     13529633.53      2030043.51     13529104.98
      2029850.80     13528804.54      2029860.80     13528374.54
      2030160.80     13528274.54      2030260.80     13528014.54
      2030550.80     13527834.54      2030460.80     13527290.22
      2031050.80     13526644.54      2031080.80     13526444.54

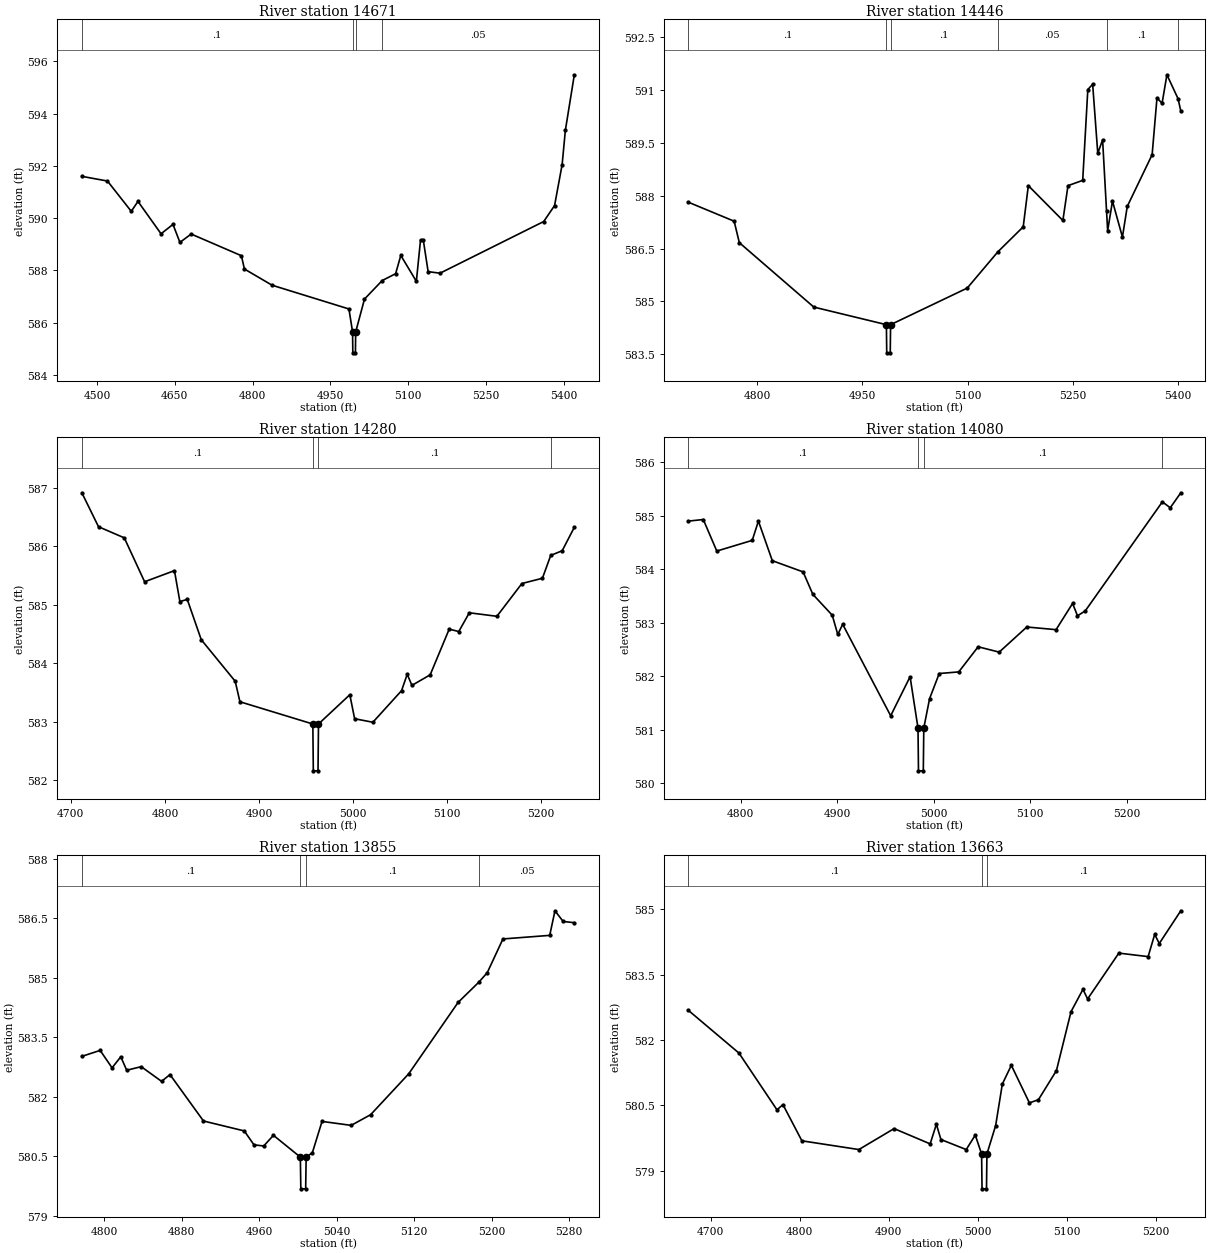
Type RM Length L Ch R = 1,14671,225,225,225
BEGIN DESCRIPTION:
WEST FORK ELLIS Br 17.0
END DESCRIPTION:
XS GIS Cut Line= 4
      2024917.99     13534561.07      2024567.30     13534363.16
      2024313.83     13534366.63      2024137.78     13534601.36
#Sta/Elev= 30
  4470.8  591.60  4520.2  591.42  4566.1  590.26  4579.0  590.64  4623.5  589.40
  4646.5  589.76  4659.9  589.07  4681.6  589.39  4778.4  588.56  4784.3  588.05
  4837.6  587.43  4985.8  586.52  4992.8  585.64  4993.3  584.84  4998.3  584.84
  4998.8  585.64  5015.8  586.90  5050.0  587.61  5075.8  587.87  5085.8  588.57
  5115.8  587.58  5123.9  589.17  5129.1  589.17  5138.5  587.95  5161.4  587.89
  5361.4  589.87  5382.3  590.48  5396.9  592.05  5403.1  593.36  5420.4  595.49
#Mann=4,-1,0
  4470.8     0.1       0  4992.8    0.07       0  4998.8     0.1       0
  5050.0    0.05       0
Bank Sta=4992.8,4998.8
Exp/Cntr=0.3,0.1

Type RM Length L Ch R = 1,14446,166,166,166
BEGIN DESCRIPTION:
Mapping XS 970b8906
END DESCRIPTION:
XS GIS Cut Line= 4
      2024736.65     13534295.20      2024713.22     13534209.28
      2024410.48     13534147.35      2024189.59     13534357.41
#Sta/Elev= 30
  4701.5  587.82  4766.9  587.28  4774.3  586.67  4880.6  584.84  4984.2  584.34
  4984.7  583.54  4989.7  583.54  4990.2  584.34  5099.6  585.38  5143.3  586.41
  5179.5  587.12  5186.8  588.29  5236.1  587.30  5243.4  588.29  5264.4  588.44
  5271.7  591.02  5278.6  591.17  5285.9  589.21  5292.8  589.59  5298.4  587.58
  5300.0  587.01  5306.9  587.85  5321.1  586.83  5328.0  587.70  5363.5  589.17
  5370.4  590.78  5377.7  590.63  5384.6  591.44  5400.5  590.76  5404.4  590.41
#Mann=6,-1,0
  4701.5     0.1       0  4984.2    0.07       0  4990.2     0.1       0
  5143.3    0.05       0  5298.4     0.1       0  5400.5    0.05       0
Bank Sta=4984.2,4990.2
Exp/Cntr=0.3,0.1

Type RM Length L Ch R = 1,14280,200,200,200
BEGIN DESCRIPTION:
Mapping XS 0c236e79
END DESCRIPTION:
XS GIS Cut Line= 4
      2024800.44     13534162.36      2024740.56     13534056.93
      2024395.51     13533999.64      2024352.54     13534029.59
#Sta/Elev= 30
  4711.7  586.91  4729.4  586.33  4756.8  586.14  4778.4  585.39  4810.1  585.58
  4815.9  585.05  4823.7  585.09  4838.6  584.40  4874.7  583.69  4879.7  583.34
  4957.2  582.96  4957.7  582.16  4962.7  582.16  4963.2  582.96  4996.5  583.46
  5001.6  583.05  5021.0  582.99  5051.5  583.53  5057.5  583.81  5062.5  583.62
  5081.9  583.80  5102.1  584.58  5112.3  584.54  5123.5  584.86  5152.8  584.80
  5179.4  585.36  5201.2  585.45  5210.0  585.84  5222.2  585.92  5235.1  586.32
#Mann=4,-1,0
  4711.7     0.1       0  4957.2    0.07       0  4963.2     0.1       0
  5210.0    0.08       0
Bank Sta=4957.2,4963.2
Exp/Cntr=0.3,0.1

Type RM Length L Ch R = 1,14080,225,225,225
BEGIN DESCRIPTION:
Mapping XS 63a6a120
END DESCRIPTION:
XS GIS Cut Line= 4
      2024825.17     13533967.06      2024760.09     13533886.36
      2024412.44     13533843.39      2024360.32     13533864.24
#Sta/Elev= 30
  4745.9  584.90  4761.4  584.93  4775.4  584.34  4812.1  584.54  4818.5  584.90
  4832.9  584.16  4864.8  583.95  4874.9  583.53  4895.0  583.14  4900.7  582.78
  4905.8  582.97  4955.5  581.26  4975.6  581.99  4983.8  581.03  4984.3  580.23
  4989.3  580.23  4989.8  581.03  4995.8  581.58  5005.8  582.05  5026.0  582.08
  5046.1  582.55  5067.9  582.45  5096.5  582.92  5126.8  582.87  5143.9  583.36
  5149.0  583.13  5157.0  583.22  5236.9  585.26  5245.1  585.15  5256.0  585.43
#Mann=4,-1,0
  4745.9     0.1       0  4983.8    0.07       0  4989.8     0.1       0
  5236.9    0.05       0
Bank Sta=4983.8,4989.8
Exp/Cntr=0.3,0.1

Type RM Length L Ch R = 1,13855,192,192,192
BEGIN DESCRIPTION:
Mapping XS 96c03b43
END DESCRIPTION:
XS GIS Cut Line= 4
      2024770.72     13533724.17      2024662.44     13533651.99
      2024357.75     13533678.03      2024331.70     13533745.76
#Sta/Elev= 30
  4777.0  583.02  4795.9  583.17  4808.2  582.73  4817.2  583.01  4823.3  582.67
  4838.3  582.76  4859.3  582.39  4868.0  582.56  4902.6  581.39  4944.7  581.14
  4954.7  580.79  4964.8  580.76  4974.8  581.03  5002.6  580.48  5003.1  579.68
  5008.1  579.68  5008.6  580.48  5015.0  580.59  5025.0  581.38  5055.1  581.28
  5075.2  581.55  5114.5  582.58  5165.5  584.38  5186.9  584.89  5195.6  585.13
  5211.8  585.98  5260.1  586.07  5265.5  586.69  5274.0  586.42  5285.5  586.39
#Mann=4,-1,0
  4777.0     0.1       0  5002.6    0.07       0  5008.6     0.1       0
  5186.9    0.05       0
Bank Sta=5002.6,5008.6
Exp/Cntr=0.3,0.1

Type RM Length L Ch R = 1,13663,349,349,349
BEGIN DESCRIPTION:
Mapping XS 38837ba9
END DESCRIPTION:
XS GIS Cut Line= 4
      2024809.77     13533650.37      2024679.36     13533503.55
      2024447.59     13533465.79      2024329.53     13533496.92
#Sta/Elev= 30
  4674.7  582.68  4731.6  581.70  4774.3  580.40  4781.0  580.52  4802.3  579.69
  4866.3  579.49  4905.9  579.97  4946.4  579.62  4953.4  580.07  4958.5  579.72
  4986.9  579.49  4997.1  579.82  5004.2  579.39  5004.7  578.59  5009.7  578.59
  5010.2  579.39  5020.0  580.04  5027.5  580.99  5037.6  581.42  5057.9  580.56
  5068.0  580.63  5088.3  581.30  5104.7  582.65  5118.1  583.16  5123.3  582.94
  5158.4  583.99  5191.3  583.91  5198.7  584.42  5203.8  584.21  5228.0  584.96
#Mann=3,-1,0
  4674.7     0.1       0  5004.2    0.07       0  5010.2     0.1       0
Bank Sta=5004.2,5010.2
Exp/Cntr=0.3,0.1

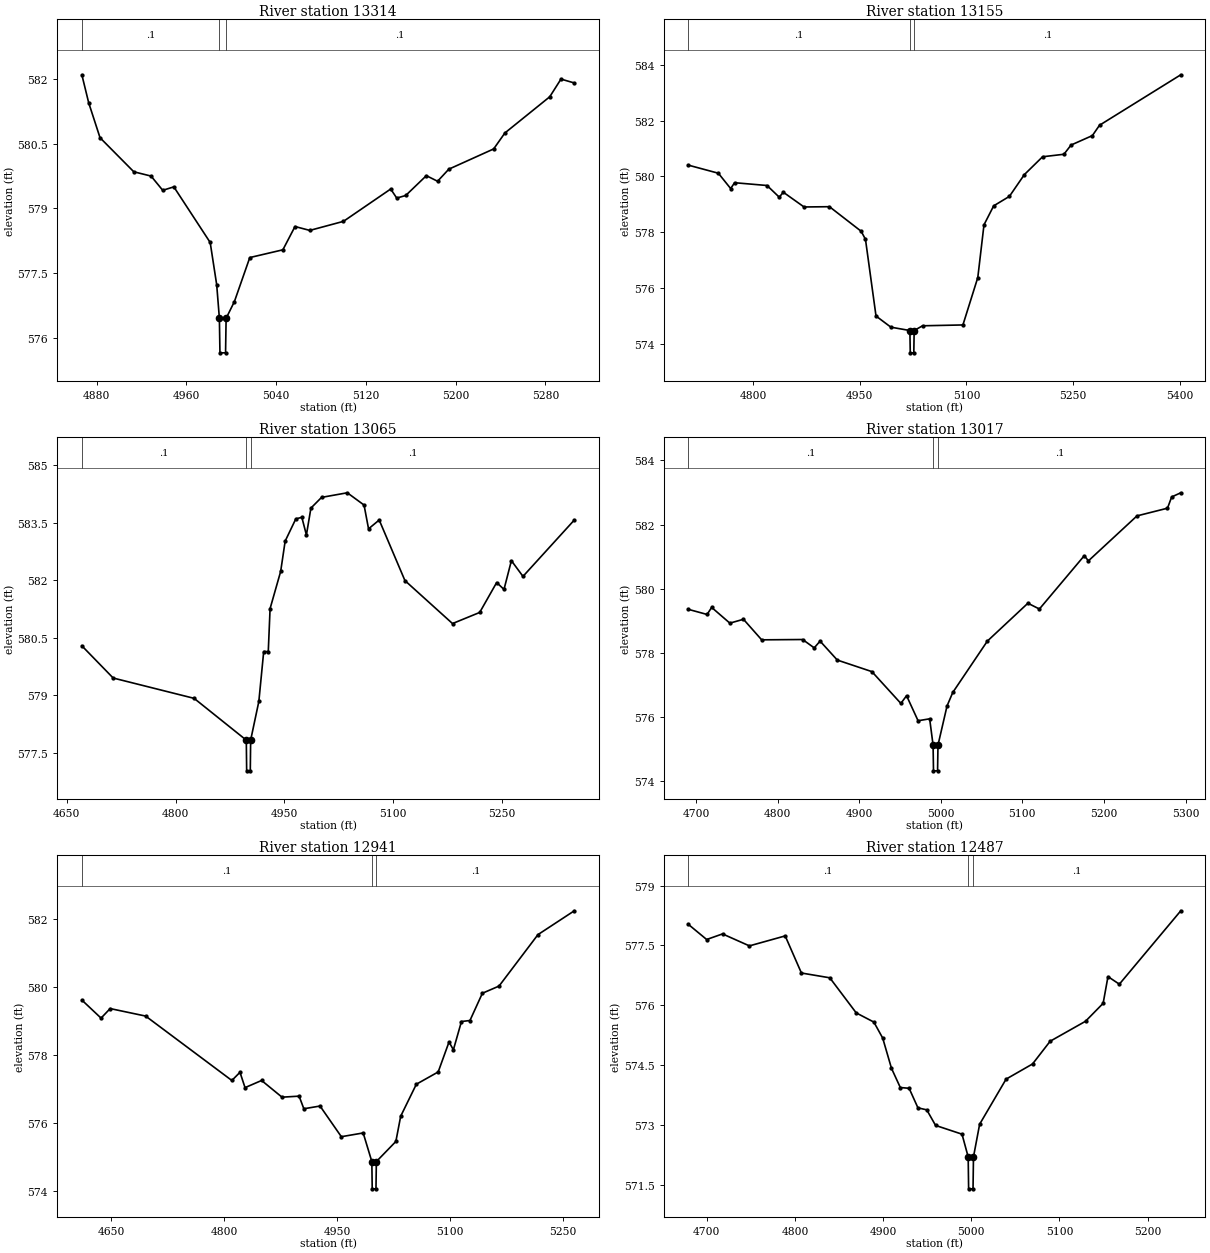
Type RM Length L Ch R = 1,13314,159,159,159
BEGIN DESCRIPTION:
Mapping XS 0a973612
END DESCRIPTION:
XS GIS Cut Line= 4
      2024892.91     13533411.10      2024887.70     13533353.81
      2024676.76     13533267.87      2024523.10     13533263.96
#Sta/Elev= 30
  4866.8  582.10  4872.9  581.45  4883.0  580.64  4913.1  579.85  4928.5  579.75
  4938.9  579.42  4948.8  579.50  4981.2  578.21  4987.0  577.23  4989.4  576.45
  4989.9  575.65  4994.9  575.65  4995.4  576.45  5002.8  576.84  5016.5  577.86
  5046.0  578.04  5056.8  578.58  5070.0  578.49  5100.0  578.70  5142.1  579.45
  5147.5  579.24  5155.5  579.30  5173.9  579.76  5183.9  579.63  5193.9  579.91
  5233.9  580.38  5243.9  580.75  5283.9  581.59  5293.9  582.00  5305.8  581.91
#Mann=3,-1,0
  4866.8     0.1       0  4989.4    0.07       0  4995.4     0.1       0
Bank Sta=4989.4,4995.4
Exp/Cntr=0.3,0.1

Type RM Length L Ch R = 1,13155,90,90,90
BEGIN DESCRIPTION:
Mapping XS 7b1487b4
END DESCRIPTION:
XS GIS Cut Line= 4
      2025036.44     13533391.55      2024971.32     13533253.49
      2024705.70     13533067.29      2024490.83     13533067.29
#Sta/Elev= 30
  4709.2  580.40  4751.4  580.11  4768.7  579.56  4774.2  579.77  4819.8  579.67
  4837.0  579.25  4842.6  579.43  4871.8  578.90  4907.5  578.91  4952.0  578.03
  4958.1  577.74  4972.9  574.99  4993.8  574.59  5020.5  574.47  5021.0  573.67
  5026.0  573.67  5026.5  574.47  5038.3  574.64  5095.0  574.67  5115.9  576.37
  5124.6  578.26  5138.2  578.94  5160.3  579.28  5181.3  580.06  5206.9  580.70
  5236.9  580.79  5246.9  581.12  5276.9  581.46  5286.9  581.83  5401.1  583.64
#Mann=3,-1,0
  4709.2     0.1       0  5020.5    0.07       0  5026.5     0.1       0
Bank Sta=5020.5,5026.5
Exp/Cntr=0.3,0.1

Type RM Length L Ch R = 1,13065,48,48,48
BEGIN DESCRIPTION:
Mapping XS cd86b9f6
END DESCRIPTION:
XS GIS Cut Line= 4
      2025058.57     13533360.29      2024943.98     13533132.40
      2024748.66     13532989.17      2024569.44     13532958.00
#Sta/Elev= 30
  4670.8  580.29  4714.0  579.45  4825.6  578.92  4897.6  577.83  4898.1  577.03
  4903.1  577.03  4903.6  577.83  4914.9  578.84  4921.6  580.14  4927.9  580.14
  4930.4  581.26  4945.0  582.23  4951.2  583.02  4965.9  583.60  4974.2  583.64
  4980.5  583.18  4986.7  583.88  5001.4  584.16  5036.9  584.28  5060.0  583.96
  5066.2  583.34  5080.9  583.57  5116.4  581.99  5182.0  580.87  5219.5  581.16
  5242.9  581.94  5253.0  581.76  5263.2  582.51  5279.2  582.10  5350.0  583.57
#Mann=3,-1,0
  4670.8     0.1       0  4897.6    0.07       0  4903.6     0.1       0
Bank Sta=4897.6,4903.6
Exp/Cntr=0.3,0.1

Type RM Length L Ch R = 1,13017,76,76,76
BEGIN DESCRIPTION:
Mapping XS 5f8267b0
END DESCRIPTION:
XS GIS Cut Line= 4
      2025082.01     13533287.36      2025024.71     13533174.06
      2024795.54     13532935.78      2024652.34     13532907.14
#Sta/Elev= 30
  4690.6  579.36  4713.6  579.20  4719.2  579.42  4741.5  578.93  4758.2  579.05
  4780.5  578.41  4830.7  578.42  4844.9  578.16  4852.1  578.37  4873.2  577.78
  4915.6  577.42  4951.1  576.43  4958.1  576.67  4972.2  575.89  4986.4  575.95
  4990.6  575.13  4991.1  574.33  4996.1  574.33  4996.6  575.13  5007.7  576.35
  5014.7  576.77  5057.1  578.37  5106.8  579.55  5120.9  579.37  5175.9  581.03
  5181.0  580.87  5240.5  582.27  5277.9  582.51  5283.0  582.86  5294.2  582.99
#Mann=3,-1,0
  4690.6     0.1       0  4990.6    0.07       0  4996.6     0.1       0
Bank Sta=4990.6,4996.6
Exp/Cntr=0.3,0.1

Type RM Length L Ch R = 1,12941,454,454,454
BEGIN DESCRIPTION:
Mapping XS b9758ece
END DESCRIPTION:
XS GIS Cut Line= 4
      2025180.97     13533319.94      2025097.62     13533111.56
      2024889.29     13532950.10      2024742.14     13532873.28
#Sta/Elev= 30
  4611.1  579.61  4636.6  579.08  4648.7  579.36  4695.8  579.14  4810.3  577.25
  4821.1  577.49  4827.8  577.04  4849.8  577.25  4876.9  576.76  4899.6  576.79
  4905.9  576.42  4927.4  576.50  4955.7  575.60  4984.7  575.71  4996.2  574.87
  4996.7  574.07  5001.7  574.07  5002.2  574.87  5028.1  575.46  5034.5  576.20
  5055.3  577.14  5084.3  577.50  5098.7  578.38  5104.5  578.15  5115.2  578.98
  5126.5  579.01  5143.0  579.81  5165.1  580.02  5216.8  581.53  5265.1  582.23
#Mann=3,-1,0
  4611.1     0.1       0  4996.2    0.07       0  5002.2     0.1       0
Bank Sta=4996.2,5002.2
Exp/Cntr=0.3,0.1

Type RM Length L Ch R = 1,12487,198,198,198
BEGIN DESCRIPTION:
Mapping XS 471f7d80
END DESCRIPTION:
XS GIS Cut Line= 4
      2025366.82     13533303.17      2025393.20     13533155.83
      2025398.40     13532829.01      2025335.94     13532775.65
#Sta/Elev= 30
  4679.0  578.03  4699.8  577.65  4717.8  577.79  4748.3  577.49  4788.9  577.74
  4807.3  576.81  4839.5  576.69  4869.5  575.81  4889.5  575.58  4899.5  575.18
  4909.5  574.42  4919.5  573.94  4929.5  573.92  4939.5  573.43  4949.5  573.38
  4959.5  572.99  4989.5  572.77  4996.5  572.20  4997.0  571.40  5002.0  571.40
  5002.5  572.20  5009.5  573.02  5039.5  574.15  5069.5  574.53  5089.5  575.10
  5129.6  575.60  5149.6  576.05  5155.1  576.72  5168.0  576.53  5237.7  578.37
#Mann=3,-1,0
  4679.0     0.1       0  4996.5    0.07       0  5002.5     0.1       0
Bank Sta=4996.5,5002.5
Exp/Cntr=0.3,0.1

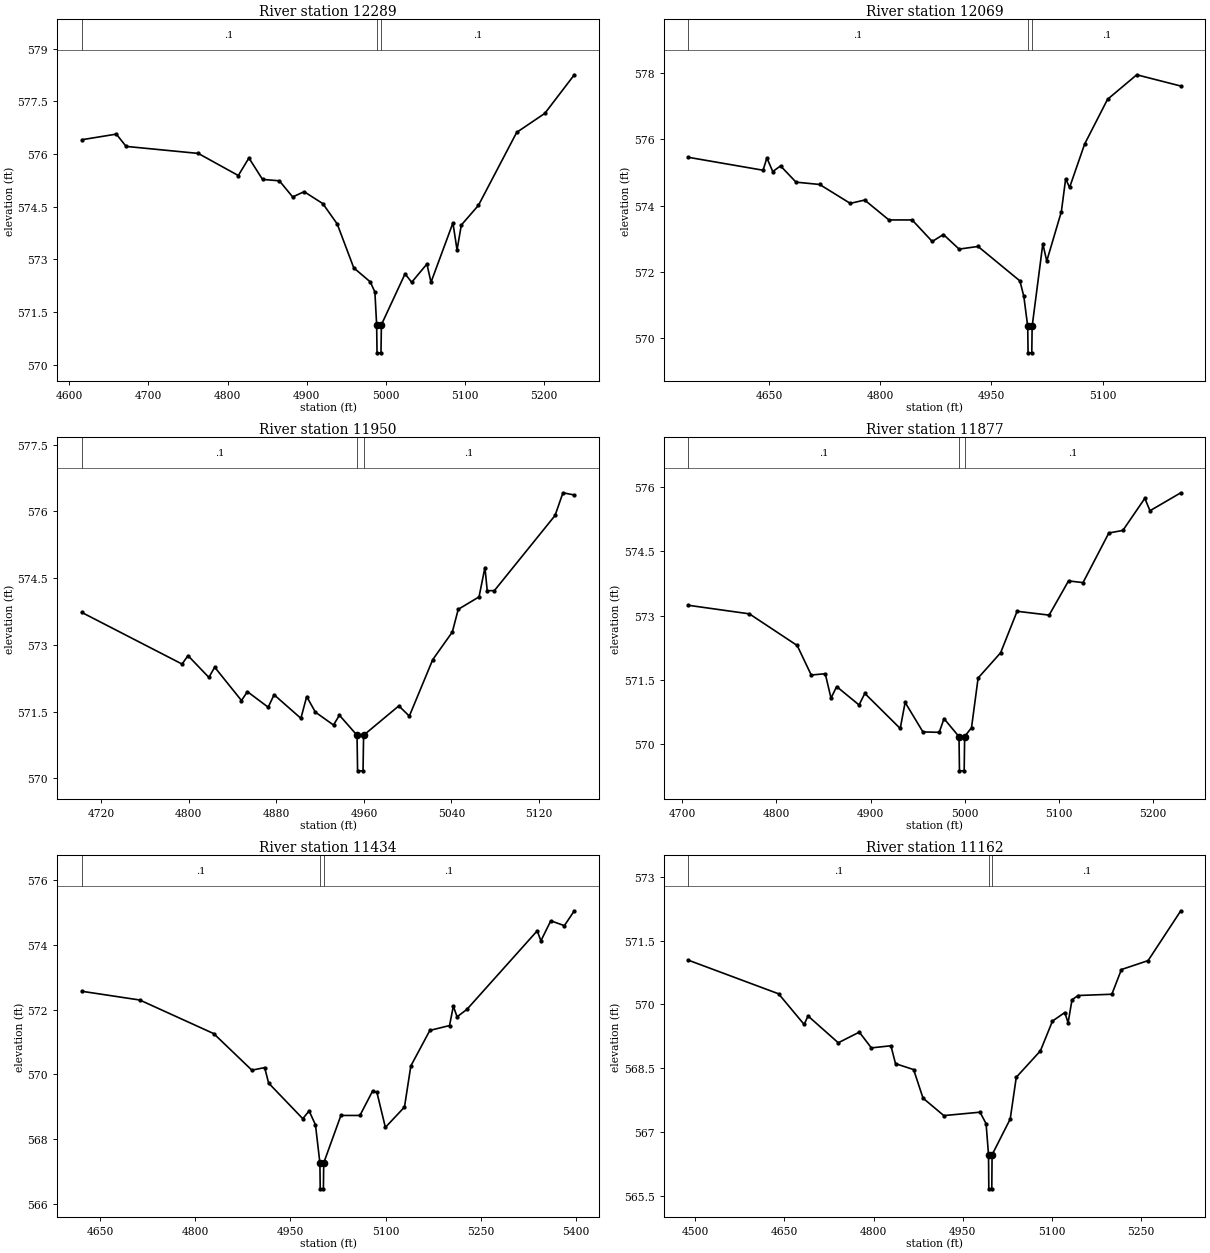
Type RM Length L Ch R = 1,12289,220,220,220
BEGIN DESCRIPTION:
Mapping XS 527acce0
END DESCRIPTION:
XS GIS Cut Line= 4
      2025572.54     13533290.16      2025606.41     13533081.78
      2025522.10     13532804.27      2025450.16     13532706.79
#Sta/Elev= 30
  4615.9  576.41  4659.5  576.57  4671.8  576.22  4763.0  576.02  4813.6  575.39
  4827.0  575.89  4844.2  575.28  4865.5  575.24  4882.3  574.78  4896.8  574.93
  4920.4  574.59  4938.6  574.01  4959.5  572.76  4980.4  572.36  4986.2  572.07
  4988.4  571.14  4988.9  570.34  4993.9  570.34  4994.4  571.14  5024.3  572.59
  5032.7  572.35  5051.9  572.87  5057.1  572.35  5084.8  574.04  5090.0  573.27
  5095.4  573.98  5117.0  574.54  5165.4  576.62  5200.9  577.16  5238.2  578.26
#Mann=3,-1,0
  4615.9     0.1       0  4988.4    0.07       0  4994.4     0.1       0
Bank Sta=4988.4,4994.4
Exp/Cntr=0.3,0.1

Type RM Length L Ch R = 1,12069,119,119,119
BEGIN DESCRIPTION:
Mapping XS 94c3d8d9
END DESCRIPTION:
XS GIS Cut Line= 4
      2025700.16     13533264.07      2025792.93     13532956.62
      2025697.88     13532688.39      2025639.66     13532694.86
#Sta/Elev= 30
  4541.2  575.46  4642.0  575.07  4647.2  575.44  4655.1  575.03  4665.6  575.20
  4686.5  574.71  4718.4  574.64  4759.6  574.07  4779.1  574.17  4811.8  573.57
  4843.1  573.57  4870.2  572.92  4885.3  573.13  4906.5  572.69  4932.0  572.77
  4988.5  571.73  4993.8  571.26  4999.0  570.36  4999.5  569.56  5004.5  569.56
  5005.0  570.36  5019.4  572.85  5024.7  572.33  5044.4  573.82  5050.2  574.81
  5055.5  574.55  5075.8  575.86  5106.7  577.21  5146.1  577.95  5205.5  577.61
#Mann=3,-1,0
  4541.2     0.1       0  4999.0    0.07       0  5005.0     0.1       0
Bank Sta=4999,5005
Exp/Cntr=0.3,0.1

Type RM Length L Ch R = 1,11950,73,73,73
BEGIN DESCRIPTION:
Mapping XS 08ddbf94
END DESCRIPTION:
XS GIS Cut Line= 4
      2025946.59     13533106.31      2025955.70     13533056.88
      2025838.51     13532757.40      2025783.84     13532701.42
#Sta/Elev= 30
  4702.2  573.73  4793.8  572.57  4799.2  572.76  4818.3  572.27  4823.6  572.50
  4848.1  571.75  4853.5  571.95  4872.5  571.60  4877.9  571.88  4902.4  571.35
  4907.7  571.84  4915.6  571.49  4932.2  571.20  4937.6  571.42  4953.7  570.97
  4954.2  570.17  4959.2  570.17  4959.7  570.97  4991.9  571.63  5001.5  571.40
  5022.9  572.67  5040.8  573.29  5046.2  573.80  5065.2  574.08  5070.6  574.74
  5072.7  574.22  5079.2  574.22  5134.7  575.91  5141.9  576.42  5152.3  576.37
#Mann=3,-1,0
  4702.2     0.1       0  4953.7    0.07       0  4959.7     0.1       0
Bank Sta=4953.7,4959.7
Exp/Cntr=0.3,0.1

Type RM Length L Ch R = 1,11877,443,443,443
BEGIN DESCRIPTION:
Mapping XS dbfdad91
END DESCRIPTION:
XS GIS Cut Line= 4
      2026075.47     13533105.03      2025951.79     13532924.06
      2025903.61     13532730.05      2025945.29     13532634.98
#Sta/Elev= 30
  4706.5  573.24  4771.3  573.04  4822.1  572.30  4837.0  571.61  4851.9  571.64
  4858.0  571.07  4864.0  571.34  4887.8  570.91  4893.9  571.18  4931.5  570.36
  4936.7  570.97  4955.6  570.28  4972.9  570.27  4978.0  570.59  4993.9  570.17
  4994.4  569.37  4999.4  569.37  4999.9  570.17  5007.2  570.38  5014.2  571.54
  5038.1  572.13  5055.6  573.10  5089.6  573.01  5110.2  573.81  5125.6  573.77
  5153.0  574.93  5167.9  574.99  5191.2  575.74  5196.7  575.45  5229.4  575.87
#Mann=3,-1,0
  4706.5     0.1       0  4993.9    0.07       0  4999.9     0.1       0
Bank Sta=4993.9,4999.9
Exp/Cntr=0.3,0.1

Type RM Length L Ch R = 1,11434,272,272,272
BEGIN DESCRIPTION:
Mapping XS cd8025e9
END DESCRIPTION:
XS GIS Cut Line= 4
      2026218.22     13533235.86      2026322.37     13533107.85
      2026346.24     13532699.86      2026242.06     13532526.23
#Sta/Elev= 30
  4621.3  572.57  4712.6  572.30  4829.2  571.26  4889.3  570.13  4909.4  570.21
  4915.7  569.73  4969.5  568.63  4979.5  568.87  4989.5  568.44  4996.5  567.26
  4997.0  566.46  5002.0  566.46  5002.5  567.26  5029.6  568.73  5059.6  568.73
  5079.7  569.49  5086.4  569.44  5099.7  568.36  5129.8  568.99  5139.8  570.26
  5169.8  571.36  5200.8  571.51  5206.8  572.11  5212.7  571.78  5228.2  572.01
  5339.0  574.44  5344.8  574.13  5360.4  574.75  5381.8  574.60  5397.5  575.06
#Mann=3,-1,0
  4621.3     0.1       0  4996.5    0.07       0  5002.5     0.1       0
Bank Sta=4996.5,5002.5
Exp/Cntr=0.3,0.1

Type RM Length L Ch R = 1,11162,335,335,335
BEGIN DESCRIPTION:
Mapping XS 25725f1a
END DESCRIPTION:
XS GIS Cut Line= 4
      2026339.76     13533264.08      2026548.06     13533092.66
      2026608.83     13532749.78      2026515.51     13532560.97
#Sta/Elev= 30
  4488.4  571.04  4640.3  570.25  4683.3  569.53  4689.8  569.73  4740.7  569.10
  4776.1  569.35  4796.4  568.98  4829.3  569.03  4837.0  568.61  4867.5  568.47
  4883.3  567.80  4918.3  567.39  4979.2  567.47  4989.4  567.20  4993.5  566.47
  4994.0  565.67  4999.0  565.67  4999.5  566.47  5030.0  567.31  5040.2  568.29
  5080.8  568.91  5101.1  569.61  5121.8  569.81  5127.4  569.57  5134.0  570.11
  5144.2  570.21  5201.0  570.24  5217.1  570.82  5262.0  571.03  5317.0  572.20
#Mann=3,-1,0
  4488.4     0.1       0  4993.5    0.07       0  4999.5     0.1       0
Bank Sta=4993.5,4999.5
Exp/Cntr=0.3,0.1

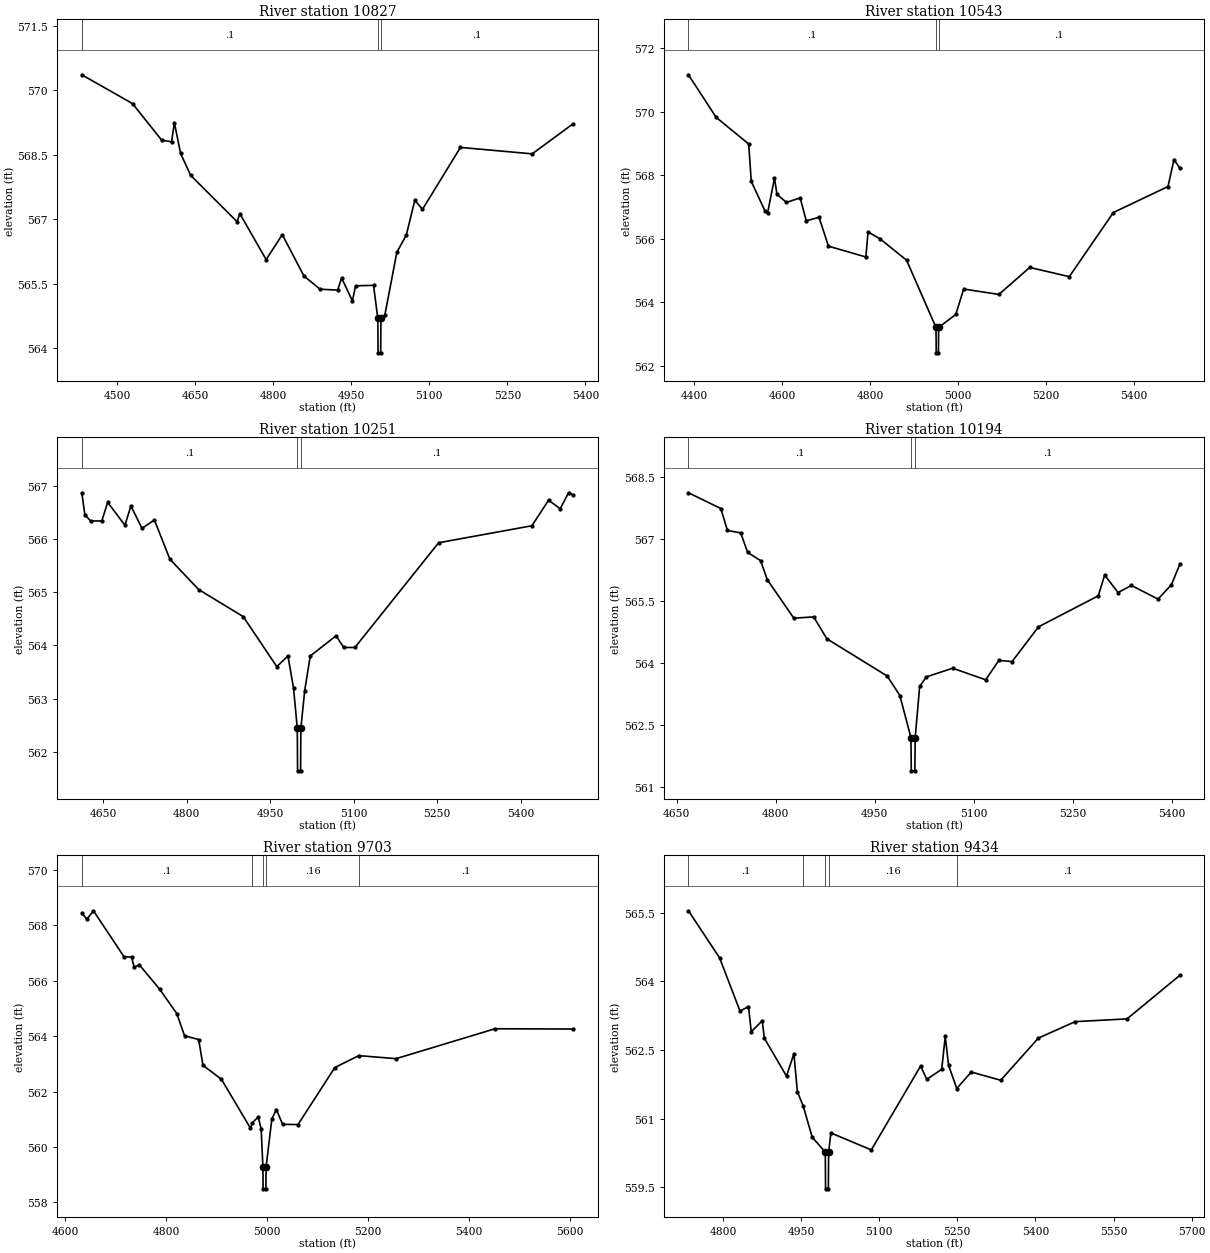
Type RM Length L Ch R = 1,10827,284,284,284
BEGIN DESCRIPTION:
Mapping XS 4cc54619
END DESCRIPTION:
XS GIS Cut Line= 4
      2026645.74     13533502.79      2026756.40     13533370.44
      2026888.78     13532886.49      2026801.98     13532630.44
#Sta/Elev= 30
  4431.8  570.36  4529.3  569.69  4585.3  568.84  4604.3  568.80  4609.9  569.24
  4621.7  568.53  4641.1  568.02  4730.4  566.94  4735.6  567.13  4786.2  566.06
  4817.3  566.64  4858.8  565.68  4889.9  565.37  4923.7  565.35  4931.3  565.63
  4952.1  565.10  4958.2  565.45  4992.7  565.46  5000.9  564.69  5001.4  563.89
  5006.4  563.89  5006.9  564.69  5014.3  564.76  5037.5  566.23  5055.7  566.63
  5072.0  567.44  5086.8  567.23  5159.8  568.67  5297.7  568.52  5376.4  569.22
#Mann=3,-1,0
  4431.8     0.1       0  5000.9    0.07       0  5006.9     0.1       0
Bank Sta=5000.9,5006.9
Exp/Cntr=0.3,0.1

Type RM Length L Ch R = 1,10543,292,292,292
BEGIN DESCRIPTION:
Mapping XS 564d3106
END DESCRIPTION:
XS GIS Cut Line= 4
      2026919.14     13533695.98      2027084.09     13533416.01
      2027051.54     13532769.31      2027001.63     13532632.60
#Sta/Elev= 30
  4387.0  571.16  4449.9  569.82  4524.1  568.98  4529.9  567.80  4561.2  566.87
  4567.0  566.80  4582.7  567.90  4588.5  567.39  4609.9  567.14  4641.2  567.28
  4655.1  566.56  4684.1  566.67  4705.6  565.76  4790.7  565.42  4795.7  566.21
  4823.1  565.99  4883.2  565.32  4950.3  563.20  4950.8  562.40  4955.8  562.40
  4956.3  563.20  4995.3  563.61  5013.3  564.41  5093.4  564.24  5163.5  565.09
  5253.6  564.80  5353.8  566.82  5478.2  567.64  5491.8  568.49  5505.0  568.22
#Mann=3,-1,0
  4387.0     0.1       0  4950.3    0.07       0  4956.3     0.1       0
Bank Sta=4950.3,4956.3
Exp/Cntr=0.3,0.1

Type RM Length L Ch R = 1,10251,57,57,57
BEGIN DESCRIPTION:
Mapping XS 9ff09a52
END DESCRIPTION:
XS GIS Cut Line= 4
      2027200.49     13533360.24      2027238.25     13533202.71
      2027201.31     13532604.99      2027100.98     13532536.90
#Sta/Elev= 30
  4611.8  566.87  4617.2  566.46  4627.5  566.34  4647.7  566.34  4658.3  566.69
  4689.2  566.26  4700.0  566.62  4720.0  566.20  4742.1  566.36  4770.0  565.62
  4821.6  565.05  4901.7  564.54  4961.9  563.60  4981.9  563.80  4991.9  563.20
  4998.7  562.44  4999.2  561.64  5004.6  561.64  5005.1  562.44  5012.0  563.15
  5022.0  563.80  5068.3  564.18  5082.1  563.96  5102.1  563.96  5252.4  565.93
  5419.9  566.25  5449.8  566.73  5470.7  566.57  5485.7  566.87  5493.9  566.83
#Mann=3,-1,0
  4611.8     0.1       0  4998.7    0.07       0  5005.1     0.1       0
Bank Sta=4998.7,5005.1
Exp/Cntr=0.3,0.1

Type RM Length L Ch R = 1,10194,491,491,491
BEGIN DESCRIPTION:
Mapping XS 78ffcbea
END DESCRIPTION:
XS GIS Cut Line= 4
      2027308.56     13533323.77      2027278.61     13533028.23
      2027277.50     13532725.78      2027299.21     13532582.52
#Sta/Elev= 30
  4667.7  568.12  4716.7  567.74  4726.8  567.21  4746.9  567.15  4757.3  566.68
  4777.0  566.48  4787.1  566.02  4827.3  565.09  4857.4  565.12  4877.5  564.59
  4968.9  563.69  4988.0  563.22  5004.8  562.20  5005.3  561.40  5010.7  561.40
  5011.2  562.20  5018.0  563.44  5028.0  563.67  5068.0  563.88  5118.0  563.60
  5138.0  564.07  5158.0  564.04  5198.0  564.88  5288.6  565.63  5298.3  566.13
  5318.6  565.71  5338.8  565.88  5379.2  565.55  5399.5  565.90  5412.1  566.39
#Mann=3,-1,0
  4667.7     0.1       0  5004.8    0.07       0  5011.2     0.1       0
Bank Sta=5004.8,5011.2
Exp/Cntr=0.3,0.1

Type RM Length L Ch R = 1,9703,269,269,269
BEGIN DESCRIPTION:
Mapping XS 672ff031
END DESCRIPTION:
XS GIS Cut Line= 4
      2027778.53     13533287.99      2027800.23     13533103.51
      2027537.65     13532689.01      2027372.24     13532443.57
#Sta/Elev= 30
  4633.2  568.44  4643.5  568.23  4656.3  568.53  4716.8  566.87  4731.6  566.86
  4736.9  566.49  4747.0  566.58  4787.2  565.70  4821.2  564.82  4836.5  564.02
  4864.5  563.88  4873.0  562.95  4909.4  562.45  4967.0  560.68  4970.9  560.88
  4982.3  561.08  4988.2  560.65  4991.6  559.29  4992.1  558.49  4997.5  558.49
  4998.0  559.29  5009.4  561.02  5018.4  561.35  5030.6  560.82  5061.1  560.81
  5134.0  562.87  5181.4  563.30  5255.2  563.19  5450.9  564.27  5605.6  564.26
#Mann=5,-1,0
  4633.2     0.1       0  4970.9    0.16       0  4991.6    0.07       0
  4998.0    0.16       0  5181.4     0.1       0
Bank Sta=4991.6,4998
Exp/Cntr=0.3,0.1

Type RM Length L Ch R = 1,9434,68,68,68
BEGIN DESCRIPTION:
Mapping XS fa39de8f
END DESCRIPTION:
XS GIS Cut Line= 4
      2028040.32     13533017.79      2027990.85     13532885.00
      2027786.42     13532658.44      2027391.77     13532356.78
#Sta/Elev= 30
  4733.7  565.54  4793.6  564.51  4832.7  563.35  4849.0  563.45  4854.3  562.90
  4875.4  563.14  4879.4  562.76  4922.0  561.93  4936.2  562.42  4942.9  561.59
  4954.3  561.27  4971.3  560.60  4996.5  560.27  4997.0  559.47  5002.4  559.47
  5002.9  560.27  5007.2  560.69  5084.9  560.32  5179.5  562.15  5191.5  561.86
  5220.1  562.08  5226.9  562.80  5233.2  562.17  5249.0  561.66  5276.8  562.02
  5333.4  561.84  5405.6  562.76  5476.3  563.12  5576.0  563.18  5677.3  564.13
#Mann=5,-1,0
  4733.7     0.1       0  4954.3    0.16       0  4996.5    0.07       0
  5002.9    0.16       0  5249.0     0.1       0
Bank Sta=4996.5,5002.9
Exp/Cntr=0.3,0.1

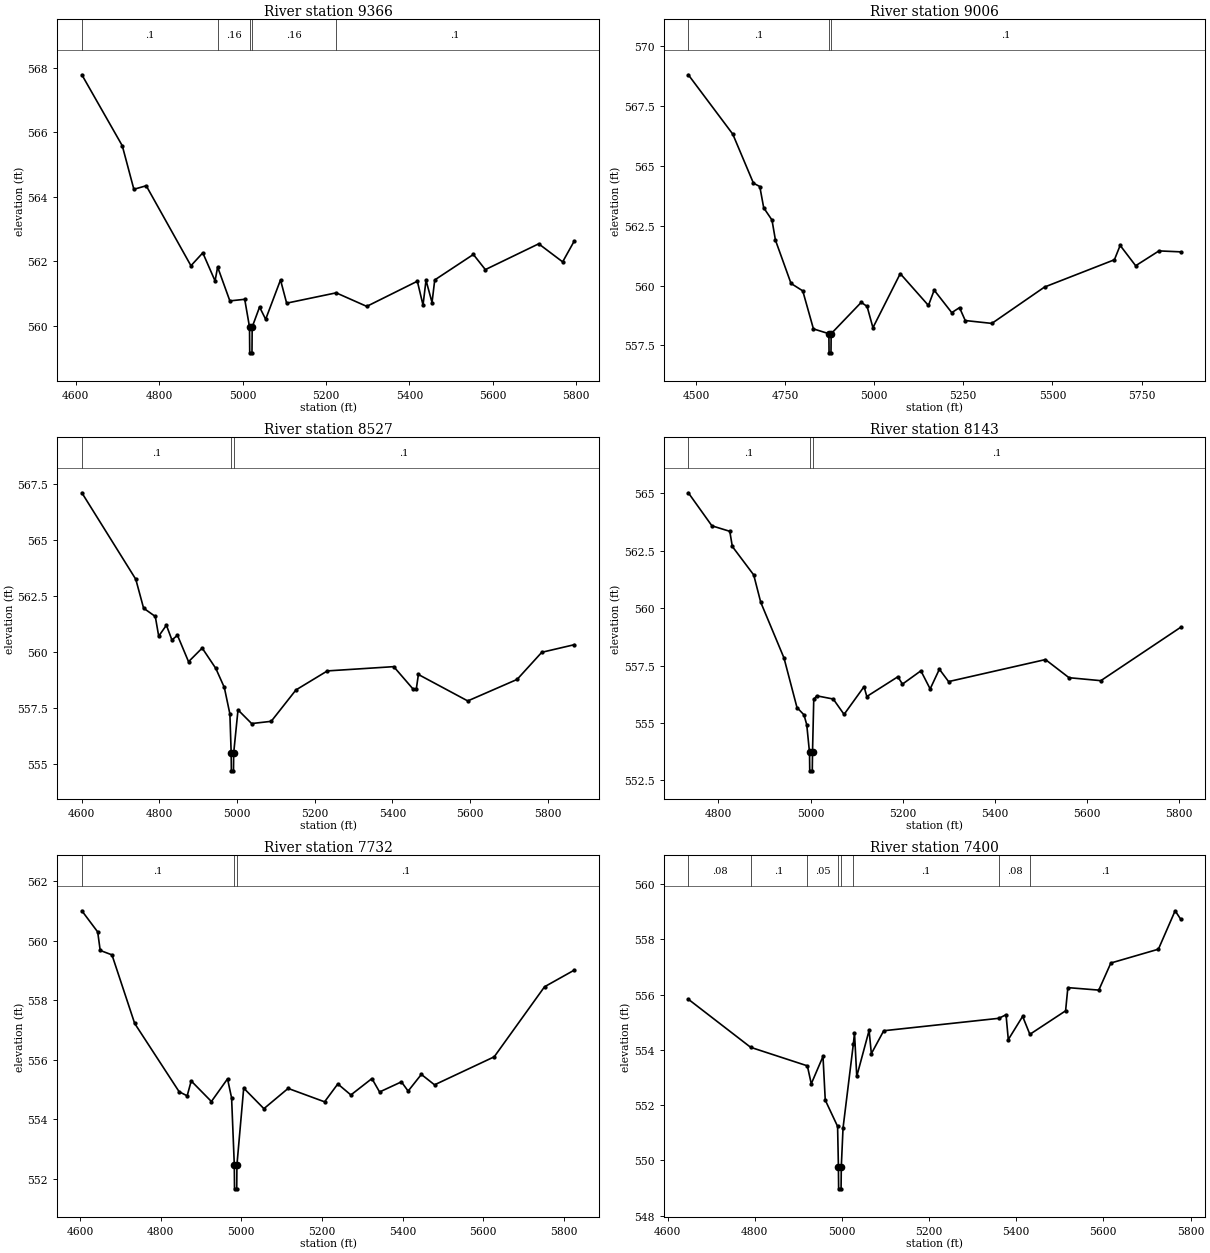
Type RM Length L Ch R = 1,9366,360,360,360
BEGIN DESCRIPTION:
Mapping XS a6b8b7f7
END DESCRIPTION:
XS GIS Cut Line= 4
      2028234.32     13532980.04      2028002.57     13532817.29
      2027868.46     13532632.40      2027446.05     13532113.75
#Sta/Elev= 30
  4614.9  567.78  4711.8  565.58  4739.6  564.23  4769.2  564.34  4876.4  561.86
  4904.8  562.26  4934.2  561.39  4940.4  561.82  4969.7  560.77  5005.3  560.82
  5016.8  559.96  5017.3  559.16  5022.7  559.16  5023.2  559.96  5040.9  560.58
  5055.5  560.20  5091.1  561.42  5105.8  560.70  5224.5  561.02  5297.8  560.60
  5419.1  561.38  5432.7  560.64  5439.9  561.41  5454.3  560.72  5460.8  561.42
  5553.4  562.21  5582.1  561.74  5710.0  562.54  5767.4  561.98  5795.4  562.63
#Mann=5,-1,0
  4614.9     0.1       0  4940.4    0.16       0  5016.8    0.07       0
  5023.2    0.16       0  5224.5     0.1       0
Bank Sta=5016.8,5023.2
Exp/Cntr=0.3,0.1

Type RM Length L Ch R = 1,9006,479,479,479
BEGIN DESCRIPTION:
Mapping XS 3972728b
END DESCRIPTION:
XS GIS Cut Line= 4
      2028355.79     13532958.14      2028344.94     13532838.75
      2028145.29     13532389.53      2027470.80     13532018.03
#Sta/Elev= 30
  4478.6  568.81  4603.3  566.33  4661.3  564.28  4679.1  564.14  4690.1  563.25
  4713.3  562.74  4723.0  561.90  4766.7  560.09  4799.6  559.78  4829.6  558.19
  4872.9  557.99  4873.4  557.19  4878.8  557.19  4879.3  557.99  4963.7  559.30
  4980.1  559.13  4996.5  558.24  5073.1  560.50  5152.2  559.17  5168.3  559.81
  5217.6  558.87  5239.4  559.08  5255.4  558.54  5330.1  558.42  5477.9  559.94
  5673.9  561.08  5690.0  561.68  5733.5  560.83  5798.9  561.45  5860.1  561.41
#Mann=3,-1,0
  4478.6     0.1       0  4872.9    0.07       0  4879.3     0.1       0
Bank Sta=4872.9,4879.3
Exp/Cntr=0.3,0.1

Type RM Length L Ch R = 1,8527,384,384,384
BEGIN DESCRIPTION:
Mapping XS 8acc476a
END DESCRIPTION:
XS GIS Cut Line= 4
      2028601.01     13532843.10      2028620.55     13532643.44
      2028347.11     13532326.60      2027731.39     13532123.44
#Sta/Elev= 30
  4600.8  567.09  4739.6  563.23  4759.7  561.94  4789.8  561.57  4798.6  560.69
  4818.4  561.18  4832.6  560.52  4846.9  560.73  4875.4  559.55  4910.5  560.16
  4945.6  559.25  4967.5  558.40  4981.8  557.22  4985.1  555.48  4985.6  554.68
  4991.1  554.68  4991.6  555.48  5002.7  557.40  5037.8  556.79  5088.2  556.89
  5151.8  558.29  5232.7  559.14  5403.5  559.33  5453.8  558.32  5461.7  558.35
  5467.0  558.98  5594.0  557.80  5721.0  558.76  5784.5  559.97  5868.3  560.31
#Mann=3,-1,0
  4600.8     0.1       0  4985.1    0.07       0  4991.6     0.1       0
Bank Sta=4985.1,4991.6
Exp/Cntr=0.3,0.1

Type RM Length L Ch R = 1,8143,411,411,411
BEGIN DESCRIPTION:
Mapping XS 45c46f71
END DESCRIPTION:
XS GIS Cut Line= 4
      2028804.65     13532382.38      2028759.08     13532271.72
      2028485.64     13532097.24      2027861.63     13532068.76
#Sta/Elev= 30
  4734.6  565.03  4785.8  563.59  4824.6  563.35  4830.1  562.69  4876.5  561.45
  4891.7  560.26  4942.2  557.83  4970.4  555.67  4985.6  555.35  4991.6  554.92
  4997.6  553.71  4998.1  552.91  5003.6  552.91  5004.1  553.71  5006.8  556.02
  5013.3  556.18  5049.1  556.04  5072.6  555.37  5116.0  556.58  5121.9  556.15
  5189.3  557.01  5199.3  556.69  5239.3  557.27  5259.4  556.48  5279.4  557.34
  5299.4  556.80  5509.6  557.76  5560.7  556.97  5629.8  556.84  5803.3  559.17
#Mann=3,-1,0
  4734.6     0.1       0  4997.6    0.07       0  5004.1     0.1       0
Bank Sta=4997.6,5004.1
Exp/Cntr=0.3,0.1

Type RM Length L Ch R = 1,7732,332,332,332
BEGIN DESCRIPTION:
Mapping XS 9c262ab5
END DESCRIPTION:
XS GIS Cut Line= 4
      2029019.53     13531944.92      2028830.70     13531804.27
      2028526.01     13531821.20      2027874.99     13532020.31
#Sta/Elev= 30
  4604.4  561.00  4643.7  560.29  4649.9  559.67  4679.1  559.52  4735.4  557.22
  4845.6  554.93  4865.6  554.79  4875.6  555.29  4925.7  554.60  4965.7  555.36
  4975.8  554.72  4982.5  552.47  4983.0  551.67  4988.5  551.67  4989.0  552.47
  5005.8  555.05  5055.9  554.36  5116.0  555.04  5206.4  554.59  5239.2  555.19
  5271.6  554.82  5323.8  555.37  5342.8  554.92  5397.0  555.26  5413.6  554.95
  5446.4  555.51  5479.1  555.16  5627.1  556.10  5751.9  558.45  5825.8  559.01
#Mann=3,-1,0
  4604.4     0.1       0  4982.5    0.07       0  4989.0     0.1       0
Bank Sta=4982.5,4989
Exp/Cntr=0.3,0.1

Type RM Length L Ch R = 1,7400,96,96,96
BEGIN DESCRIPTION:
Mapping XS 9d2f6366
END DESCRIPTION:
XS GIS Cut Line= 4
      2029068.95     13531414.96      2028869.76     13531460.52
      2028524.71     13531560.78      2027982.52     13531725.47
#Sta/Elev= 30
  4647.4  555.83  4790.5  554.09  4920.6  553.42  4929.6  552.77  4956.5  553.76
  4961.7  552.18  4990.0  551.23  4991.9  549.77  4992.4  548.97  4998.0  548.97
  4998.5  549.77  5002.5  551.17  5026.1  554.20  5028.8  554.61  5034.0  553.04
  5062.3  554.70  5067.5  553.86  5095.9  554.69  5360.3  555.14  5376.6  555.27
  5381.8  554.37  5414.7  555.21  5431.3  554.56  5513.3  555.41  5518.5  556.25
  5589.5  556.16  5617.2  557.14  5726.3  557.64  5764.7  559.03  5777.7  558.72
#Mann=8,-1,0
  4647.4    0.08       0  4790.5     0.1       0  4920.6    0.05       0
  4991.9    0.04       0  4998.5    0.05       0  5026.1     0.1       0
  5360.3    0.08       0  5431.3     0.1       0
Bank Sta=4991.9,4998.5
Exp/Cntr=0.3,0.1