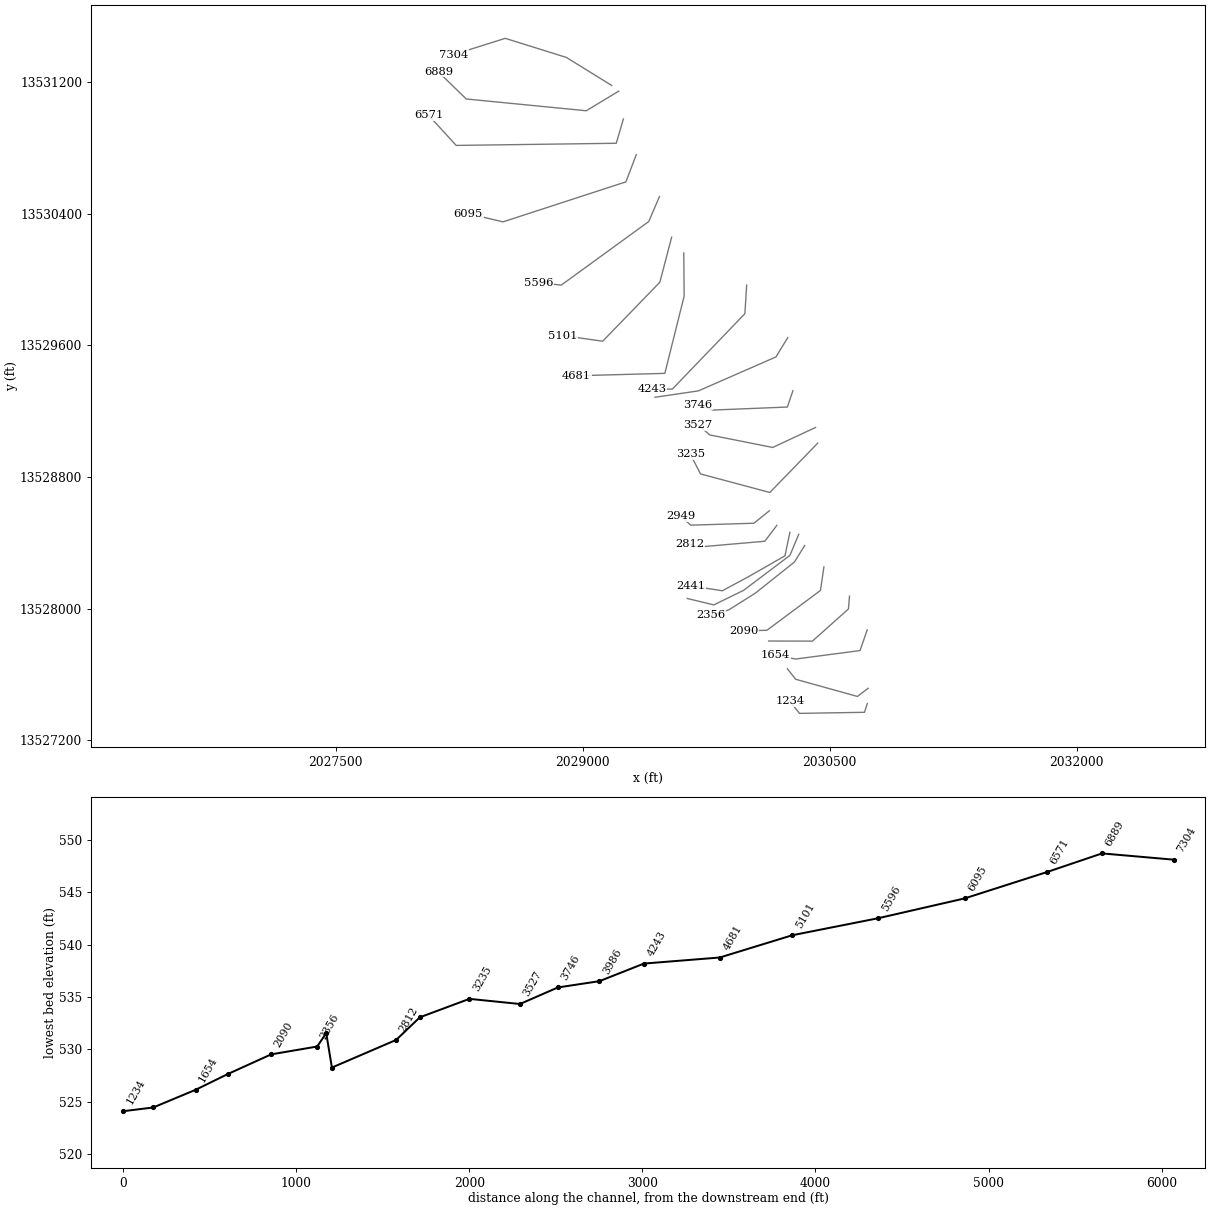
HEC-RAS study WEST FORK ELLIS Br.prj: WEST FORK ELLIS Br Base Level Engineering

--- WEST FORK ELLIS Br.g01 (geometry) --- (continued)

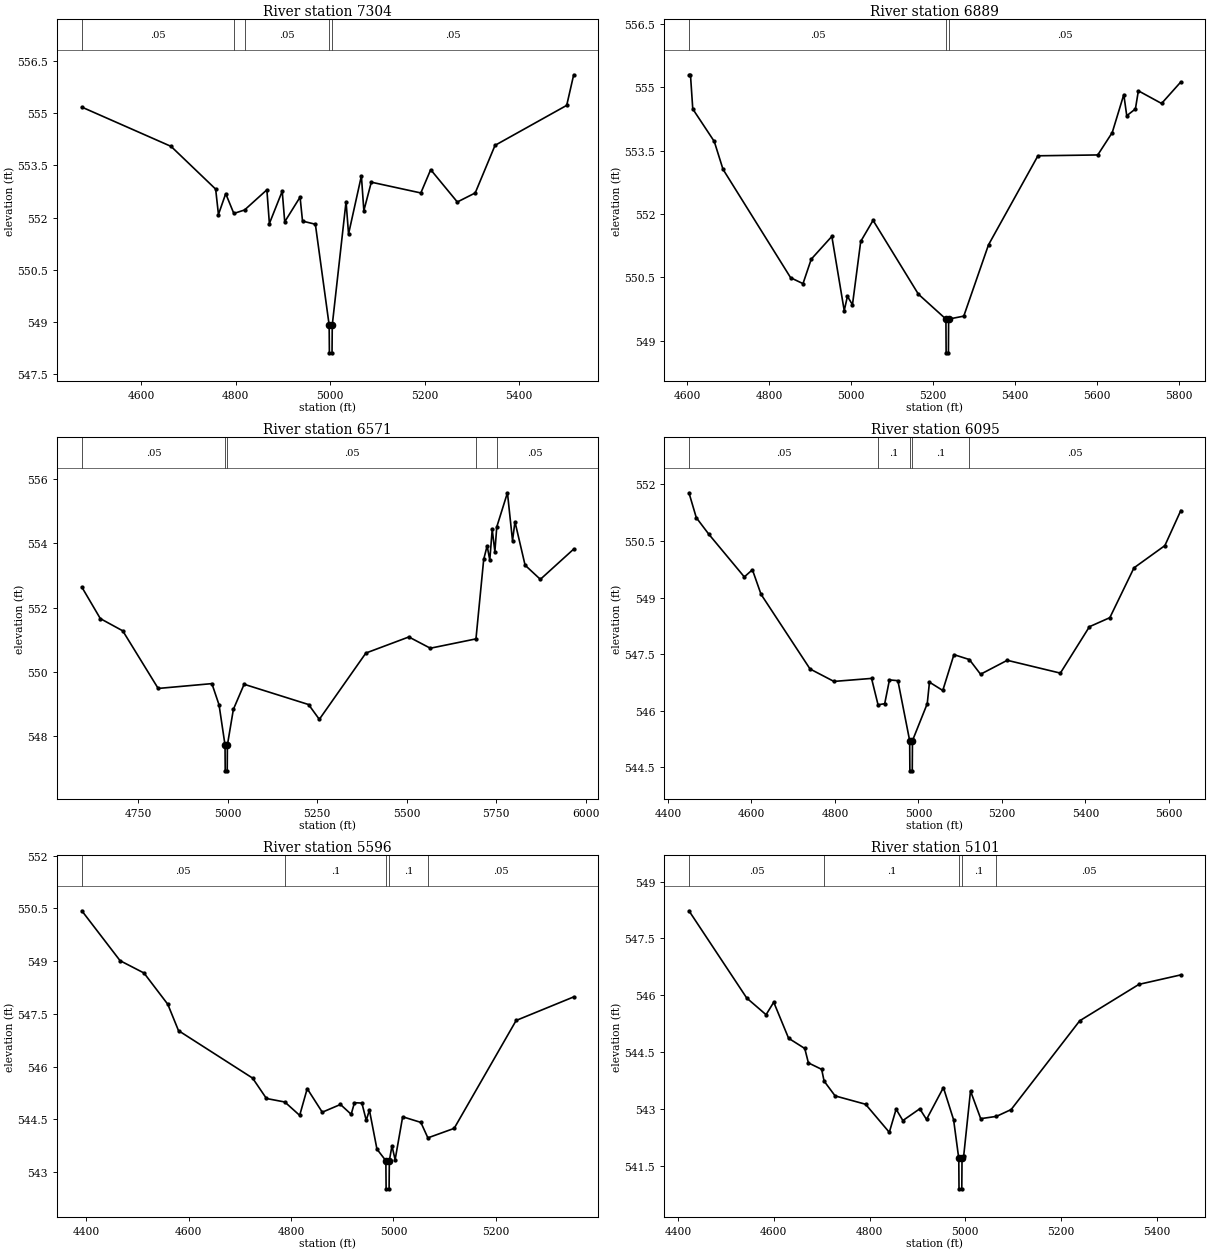
Type RM Length L Ch R = 1,7304,415,415,415
BEGIN DESCRIPTION:
Mapping XS ef543d33
END DESCRIPTION:
XS GIS Cut Line= 4
      2029176.69     13531178.15      2028901.01     13531348.54
      2028529.91     13531464.43      2028216.10     13531365.47
#Sta/Elev= 30
  4473.7  555.18  4662.7  554.05  4757.2  552.82  4763.1  552.09  4778.5  552.69
  4795.7  552.12  4818.4  552.22  4865.7  552.80  4871.0  551.83  4898.2  552.76
  4903.5  551.88  4936.0  552.59  4941.2  551.90  4968.4  551.81  4997.6  548.91
  4998.1  548.11  5003.7  548.11  5004.2  548.91  5033.4  552.46  5038.7  551.53
  5065.9  553.20  5071.1  552.20  5086.9  553.02  5191.8  552.71  5212.7  553.38
  5269.1  552.45  5307.0  552.71  5349.0  554.08  5500.8  555.23  5515.6  556.11
#Mann=5,-1,0
  4473.7    0.05       0  4795.7    0.08       0  4818.4    0.05       0
  4997.6    0.04       0  5004.2    0.05       0
Bank Sta=4997.6,5004.2
Exp/Cntr=0.3,0.1

Type RM Length L Ch R = 1,6889,318,318,318
BEGIN DESCRIPTION:
Mapping XS 39e718c8
END DESCRIPTION:
XS GIS Cut Line= 4
      2029219.50     13531143.87      2029022.02     13531024.52
      2028292.86     13531096.13      2028124.13     13531260.53
#Sta/Elev= 30
  4604.8  555.30  4608.5  555.30  4614.1  554.49  4666.5  553.72  4687.8  553.06
  4852.7  550.49  4882.8  550.35  4902.9  550.93  4953.1  551.47  4983.3  549.71
  4991.1  550.05  5003.4  549.85  5023.5  551.35  5053.6  551.85  5164.1  550.10
  5231.2  549.51  5231.7  548.71  5237.3  548.71  5237.8  549.51  5274.7  549.58
  5335.0  551.27  5455.5  553.38  5601.3  553.40  5636.6  553.93  5664.8  554.83
  5672.0  554.33  5693.1  554.49  5700.3  554.92  5756.9  554.62  5803.8  555.13
#Mann=3,-1,0
  4604.8    0.05       0  5231.2    0.03       0  5237.8    0.05       0
Bank Sta=5231.2,5237.8
Exp/Cntr=0.3,0.1

Type RM Length L Ch R = 1,6571,476,476,476
BEGIN DESCRIPTION:
Mapping XS a980a680
END DESCRIPTION:
XS GIS Cut Line= 4
      2029247.73     13530974.64      2029204.31     13530827.03
      2028232.09     13530814.01      2028064.97     13530996.33
#Sta/Elev= 30
  4592.6  552.64  4644.3  551.66  4706.9  551.28  4805.8  549.49  4955.8  549.64
  4975.8  548.98  4992.5  547.73  4993.0  546.93  4998.6  546.93  4999.1  547.73
  5015.8  548.84  5045.8  549.62  5225.8  548.99  5255.8  548.53  5385.8  550.59
  5505.8  551.09  5565.8  550.74  5693.2  551.03  5714.8  553.50  5724.4  553.92
  5731.8  553.48  5738.6  554.43  5746.0  553.74  5751.3  554.51  5781.1  555.57
  5795.3  554.08  5802.1  554.67  5830.4  553.32  5873.0  552.88  5966.1  553.82
#Mann=5,-1,0
  4592.6    0.05       0  4992.5    0.03       0  4999.1    0.05       0
  5693.2     0.1       0  5751.3    0.05       0
Bank Sta=4992.5,4999.1
Exp/Cntr=0.3,0.1

Type RM Length L Ch R = 1,6095,499,499,499
BEGIN DESCRIPTION:
Mapping XS a0e92c09
END DESCRIPTION:
XS GIS Cut Line= 4
      2029325.84     13530757.60      2029262.91     13530592.66
      2028516.38     13530349.60      2028305.85     13530399.52
#Sta/Elev= 30
  4450.4  551.78  4468.0  551.12  4498.1  550.68  4583.0  549.55  4602.4  549.74
  4623.0  549.09  4740.4  547.11  4797.6  546.78  4887.7  546.86  4903.3  546.16
  4919.2  546.19  4930.6  546.82  4950.8  546.80  4979.0  545.21  4979.5  544.41
  4985.2  544.41  4985.7  545.21  5021.1  546.19  5026.4  546.76  5058.3  546.54
  5085.0  547.49  5121.9  547.36  5148.8  546.97  5212.7  547.34  5339.9  547.00
  5409.5  548.23  5458.4  548.47  5516.2  549.79  5590.2  550.38  5628.4  551.31
#Mann=5,-1,0
  4450.4    0.05       0  4903.3     0.1       0  4979.0    0.07       0
  4985.7     0.1       0  5121.9    0.05       0
Bank Sta=4979,4985.7
Exp/Cntr=0.3,0.1

Type RM Length L Ch R = 1,5596,495,495,495
BEGIN DESCRIPTION:
Mapping XS e46d9d05
END DESCRIPTION:
XS GIS Cut Line= 4
      2029466.88     13530503.64      2029401.80     13530351.77
      2028870.11     13529965.49      2028733.37     13529980.68
#Sta/Elev= 30
  4391.7  550.43  4466.4  549.01  4513.0  548.66  4559.5  547.77  4580.4  547.02
  4725.0  545.67  4752.0  545.09  4787.9  544.99  4816.9  544.61  4831.6  545.37
  4861.0  544.70  4896.5  544.92  4917.4  544.64  4923.8  544.97  4938.3  544.96
  4946.8  544.47  4953.0  544.76  4967.7  543.65  4985.1  543.32  4985.6  542.52
  4991.4  542.52  4991.9  543.32  4997.0  543.74  5003.2  543.35  5017.9  544.57
  5053.4  544.41  5067.1  543.97  5118.4  544.24  5239.4  547.31  5351.7  547.98
#Mann=5,-1,0
  4391.7    0.05       0  4787.9     0.1       0  4985.1    0.07       0
  4991.9     0.1       0  5067.1    0.05       0
Bank Sta=4985.1,4991.9
Exp/Cntr=0.3,0.1

Type RM Length L Ch R = 1,5101,420,420,420
BEGIN DESCRIPTION:
Mapping XS afc95356
END DESCRIPTION:
XS GIS Cut Line= 4
      2029540.69     13530256.32      2029469.07     13529982.85
      2029121.85     13529624.78      2028878.35     13529659.25
#Sta/Elev= 30
  4422.7  548.23  4543.4  545.93  4583.8  545.49  4599.8  545.82  4630.8  544.87
  4664.6  544.60  4672.2  544.22  4699.9  544.05  4705.0  543.74  4728.0  543.35
  4791.6  543.13  4841.2  542.39  4855.4  543.00  4869.5  542.70  4904.8  543.01
  4918.9  542.73  4954.2  543.57  4975.5  542.72  4986.3  541.70  4986.8  540.90
  4992.6  540.90  4993.1  541.70  4996.6  541.77  5010.8  543.48  5032.1  542.75
  5064.9  542.81  5095.7  542.99  5238.9  545.33  5362.6  546.29  5450.1  546.54
#Mann=5,-1,0
  4422.7    0.05       0  4705.0     0.1       0  4986.3    0.07       0
  4993.1     0.1       0  5064.9    0.05       0
Bank Sta=4986.3,4993.1
Exp/Cntr=0.3,0.1

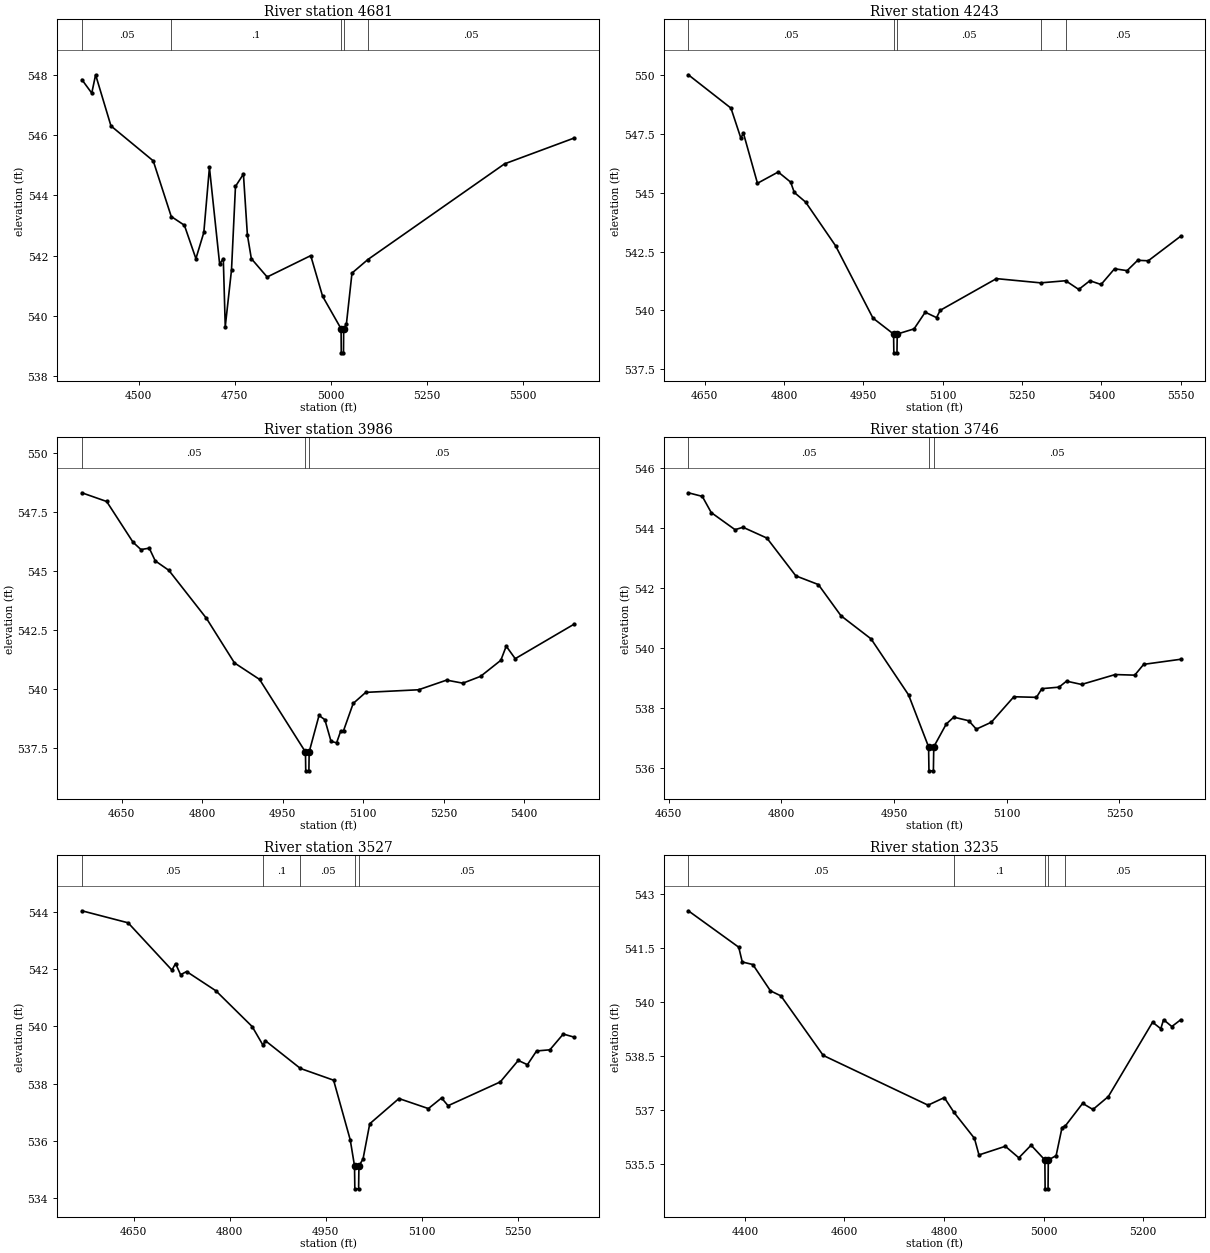
Type RM Length L Ch R = 1,4681,438,438,438
BEGIN DESCRIPTION:
Mapping XS acdd15ea
END DESCRIPTION:
XS GIS Cut Line= 4
      2029614.47     13530160.83      2029616.64     13529898.21
      2029499.45     13529429.46      2028963.45     13529414.89
#Sta/Elev= 30
  4352.2  547.85  4378.0  547.40  4388.0  548.01  4428.0  546.31  4538.0  545.15
  4584.9  543.30  4619.1  543.01  4649.1  541.90  4669.7  542.77  4684.3  544.93
  4710.9  541.72  4720.4  541.90  4725.5  539.64  4741.8  541.53  4752.1  544.30
  4772.8  544.71  4783.1  542.69  4793.4  541.90  4834.6  541.29  4948.0  542.00
  4978.9  540.65  5027.0  539.57  5027.5  538.77  5033.3  538.77  5033.8  539.57
  5040.8  539.72  5055.4  541.42  5096.7  541.87  5452.6  545.05  5634.2  545.91
#Mann=5,-1,0
  4352.2    0.05       0  4584.9     0.1       0  5027.0    0.07       0
  5033.8     0.1       0  5096.7    0.05       0
Bank Sta=5027,5033.8
Exp/Cntr=0.3,0.1

Type RM Length L Ch R = 1,4243,257,257,257
BEGIN DESCRIPTION:
Mapping XS d5817169
END DESCRIPTION:
XS GIS Cut Line= 4
      2029996.41     13529965.46      2029985.56     13529791.88
      2029545.03     13529333.98      2029423.48     13529331.81
#Sta/Elev= 30
  4619.1  550.03  4699.7  548.61  4718.3  547.34  4723.3  547.54  4749.8  545.41
  4789.0  545.89  4812.5  545.46  4819.4  545.02  4840.8  544.61  4897.4  542.75
  4968.1  539.67  5007.1  538.99  5007.6  538.19  5013.5  538.19  5014.0  538.99
  5045.8  539.21  5066.9  539.92  5088.3  539.69  5095.2  540.00  5201.5  541.35
  5285.0  541.17  5332.4  541.26  5357.1  540.89  5378.2  541.26  5399.3  541.10
  5424.8  541.77  5448.5  541.69  5468.5  542.13  5488.5  542.11  5550.0  543.16
#Mann=5,-1,0
  4619.1    0.05       0  5007.1    0.03       0  5014.0    0.05       0
  5285.0     0.1       0  5332.4    0.05       0
Bank Sta=5007.1,5014
Exp/Cntr=0.3,0.1

Type RM Length L Ch R = 1,3986,240,240,240
BEGIN DESCRIPTION:
Mapping XS 430cde2a
END DESCRIPTION:
XS GIS Cut Line= 4
      2030245.99     13529646.50      2030174.37     13529529.29
      2029703.45     13529323.13      2029439.34     13529284.16
#Sta/Elev= 30
  4575.4  548.31  4621.7  547.94  4670.9  546.21  4685.6  545.90  4701.1  545.96
  4712.3  545.42  4737.6  545.02  4807.8  542.98  4860.0  541.09  4906.8  540.39
  4992.4  537.31  4992.9  536.51  4998.8  536.51  4999.3  537.31  5017.7  538.86
  5028.6  538.68  5040.1  537.76  5050.5  537.70  5058.0  538.19  5063.5  538.22
  5081.4  539.37  5104.8  539.84  5203.3  539.95  5255.6  540.36  5285.9  540.23
  5319.0  540.52  5356.7  541.20  5366.8  541.80  5383.6  541.27  5493.8  542.74
#Mann=3,-1,0
  4575.4    0.05       0  4992.4    0.03       0  4999.3    0.05       0
Bank Sta=4992.4,4999.3
Exp/Cntr=0.3,0.1

Type RM Length L Ch R = 1,3746,219,219,219
BEGIN DESCRIPTION:
Mapping XS cecec58b
END DESCRIPTION:
XS GIS Cut Line= 4
      2030277.32     13529323.84      2030243.46     13529224.84
      2029791.63     13529206.62      2029698.27     13529238.59
#Sta/Elev= 30
  4676.3  545.18  4694.9  545.06  4706.8  544.52  4738.5  543.95  4749.1  544.03
  4780.9  543.67  4819.4  542.41  4849.4  542.12  4879.5  541.08  4919.5  540.31
  4969.5  538.44  4996.1  536.71  4996.6  535.91  5002.5  535.91  5003.0  536.71
  5019.6  537.47  5029.6  537.70  5049.6  537.58  5059.6  537.30  5079.6  537.53
  5109.6  538.38  5139.7  538.36  5146.9  538.65  5169.7  538.70  5179.7  538.90
  5199.7  538.79  5244.5  539.12  5270.5  539.10  5282.4  539.46  5331.8  539.63
#Mann=3,-1,0
  4676.3    0.05       0  4996.1    0.03       0  5003.0    0.05       0
Bank Sta=4996.1,5003
Exp/Cntr=0.3,0.1

Type RM Length L Ch R = 1,3527,292,292,292
BEGIN DESCRIPTION:
Mapping XS 89615443
END DESCRIPTION:
XS GIS Cut Line= 4
      2030414.85     13529100.86      2030154.47     13528979.35
      2029772.10     13529055.57      2029701.78     13529115.47
#Sta/Elev= 30
  4569.1  544.03  4641.4  543.61  4709.9  541.96  4715.5  542.19  4723.4  541.80
  4732.8  541.91  4778.5  541.24  4835.3  539.99  4852.2  539.34  4855.7  539.50
  4910.6  538.53  4962.5  538.12  4988.5  536.04  4995.2  535.13  4995.7  534.33
  5001.6  534.33  5002.1  535.13  5008.5  535.37  5019.0  536.60  5064.6  537.48
  5110.6  537.13  5131.2  537.50  5141.4  537.23  5223.0  538.06  5251.1  538.81
  5265.4  538.66  5279.7  539.14  5300.5  539.18  5321.4  539.73  5338.7  539.62
#Mann=5,-1,0
  4569.1    0.05       0  4852.2     0.1       0  4910.6    0.05       0
  4995.2    0.03       0  5002.1    0.05       0
Bank Sta=4995.2,5002.1
Exp/Cntr=0.3,0.1

Type RM Length L Ch R = 1,3235,286,286,286
BEGIN DESCRIPTION:
Mapping XS 575ddbd7
END DESCRIPTION:
XS GIS Cut Line= 4
      2030427.89     13529005.38      2030137.11     13528705.91
      2029716.11     13528818.59      2029653.61     13528939.69
#Sta/Elev= 30
  4286.2  542.53  4387.5  541.52  4394.6  541.11  4415.8  541.04  4451.2  540.31
  4472.3  540.17  4557.2  538.52  4767.9  537.14  4800.5  537.35  4820.0  536.94
  4861.1  536.22  4870.2  535.76  4923.2  536.00  4950.3  535.68  4974.9  536.03
  5002.6  535.62  5003.1  534.82  5009.0  534.82  5009.5  535.62  5025.2  535.74
  5037.1  536.52  5044.0  536.57  5078.5  537.19  5099.2  537.02  5130.2  537.38
  5219.0  539.44  5235.5  539.26  5241.1  539.51  5257.7  539.32  5275.7  539.51
#Mann=5,-1,0
  4286.2    0.05       0  4820.0     0.1       0  5002.6    0.07       0
  5009.5     0.1       0  5044.0    0.05       0
Bank Sta=5002.6,5009.5
Exp/Cntr=0.3,0.1

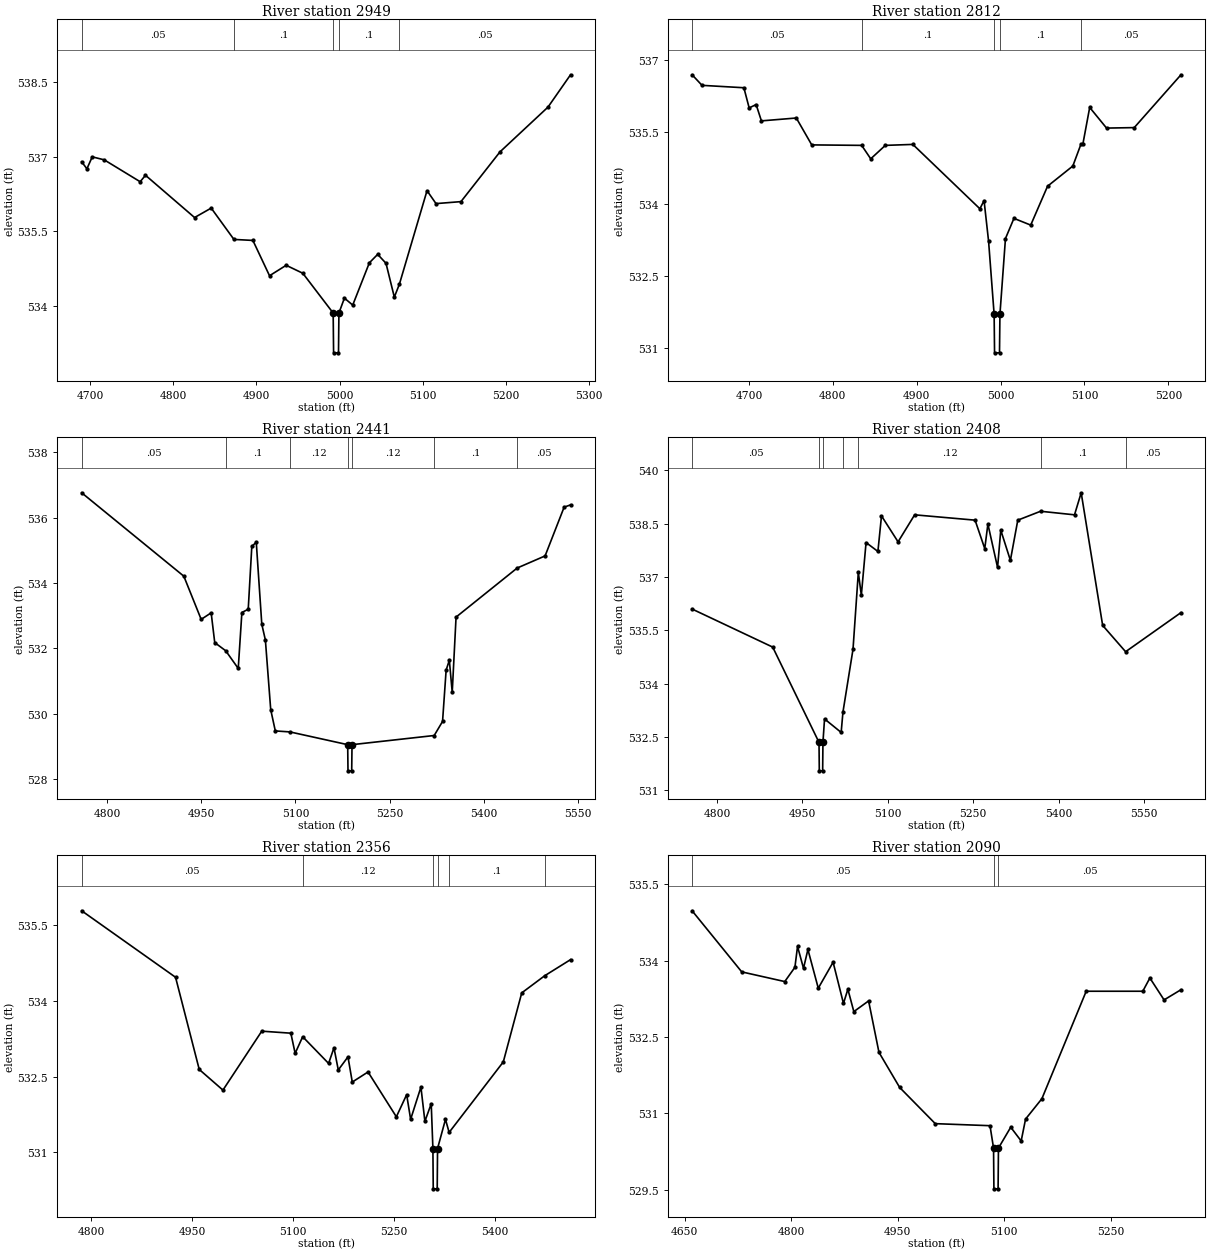
Type RM Length L Ch R = 1,2949,137,137,137
BEGIN DESCRIPTION:
Mapping XS 287e519f
END DESCRIPTION:
XS GIS Cut Line= 4
      2030134.08     13528594.63      2030040.33     13528519.12
      2029656.22     13528507.40      2029595.03     13528563.37
#Sta/Elev= 30
  4690.0  536.90  4696.3  536.76  4702.7  537.00  4717.1  536.94  4760.3  536.50
  4766.7  536.63  4825.7  535.78  4845.7  535.97  4873.0  535.34  4895.8  535.32
  4915.8  534.61  4935.8  534.82  4955.8  534.66  4992.3  533.86  4992.8  533.06
  4998.7  533.06  4999.2  533.86  5005.8  534.16  5015.8  534.02  5035.8  534.87
  5045.8  535.04  5055.8  534.86  5065.8  534.18  5071.9  534.44  5105.1  536.32
  5115.9  536.06  5145.9  536.10  5192.8  537.10  5250.5  538.00  5277.6  538.65
#Mann=5,-1,0
  4690.0    0.05       0  4873.0     0.1       0  4992.3    0.07       0
  4999.2     0.1       0  5071.9    0.05       0
Bank Sta=4992.3,4999.2
Exp/Cntr=0.3,0.1

Type RM Length L Ch R = 1,2812,371,371,371
BEGIN DESCRIPTION:
Mapping XS a19af75b
END DESCRIPTION:
XS GIS Cut Line= 4
      2030179.65     13528506.09      2030106.74     13528409.74
      2029704.39     13528374.58      2029649.24     13528392.54
#Sta/Elev= 30
  4632.3  536.69  4644.1  536.47  4694.0  536.42  4700.3  536.00  4708.6  536.07
  4714.9  535.73  4756.5  535.79  4774.9  535.23  4834.4  535.22  4845.2  534.94
  4862.6  535.22  4895.4  535.24  4975.3  533.90  4980.3  534.07  4985.7  533.22
  4992.3  531.70  4992.8  530.90  4998.7  530.90  4999.2  531.70  5005.8  533.28
  5015.9  533.70  5035.9  533.56  5056.0  534.37  5086.1  534.79  5095.9  535.25
  5098.0  535.24  5106.2  536.01  5126.3  535.58  5159.3  535.59  5215.0  536.69
#Mann=5,-1,0
  4632.3    0.05       0  4834.4     0.1       0  4992.3    0.07       0
  4999.2     0.1       0  5095.9    0.05       0
Bank Sta=4992.3,4999.2
Exp/Cntr=0.3,0.1

Type RM Length L Ch R = 1,2441,33,33,33
BEGIN DESCRIPTION:
Mapping XS 83b51ea9
END DESCRIPTION:
XS GIS Cut Line= 5
      2030259.09     13528464.46      2030229.13     13528321.20
      2030012.99     13528197.50      2029848.92     13528108.96
      2029654.95     13528138.90
#Sta/Elev= 30
  4759.7  536.76  4922.3  534.21  4949.9  532.89  4965.8  533.09  4971.5  532.18
  4989.0  531.93  5008.9  531.39  5014.7  533.10  5024.8  533.20  5030.5  535.12
  5037.6  535.25  5046.4  532.74  5052.1  532.26  5060.6  530.13  5067.9  529.48
  5091.2  529.45  5183.1  529.06  5183.6  528.26  5189.5  528.26  5190.0  529.06
  5320.8  529.34  5334.1  529.77  5339.8  531.34  5344.9  531.64  5349.5  530.66
  5355.6  532.96  5452.9  534.46  5497.3  534.83  5527.6  536.32  5537.8  536.39
#Mann=7,-1,0
  4759.7    0.05       0  4989.0     0.1       0  5091.2    0.12       0
  5183.1    0.07       0  5190.0    0.12       0  5320.8     0.1       0
  5452.9    0.05       0
Bank Sta=5183.1,5190
Exp/Cntr=0.3,0.1

Type RM Length L Ch R = 1,2408,52,52,52
BEGIN DESCRIPTION:
Mapping XS ba97c4b6
END DESCRIPTION:
XS GIS Cut Line= 5
      2030312.48     13528451.44      2030259.08     13528323.80
      2029977.83     13528111.56      2029796.84     13528023.02
      2029635.38     13528062.08
#Sta/Elev= 30
  4756.3  536.10  4897.8  535.03  4979.1  532.35  4979.6  531.55  4985.5  531.55
  4986.0  532.35  4988.8  533.01  5018.0  532.63  5021.1  533.20  5038.8  534.97
  5048.1  537.13  5053.4  536.49  5061.7  537.97  5082.5  537.72  5088.8  538.72
  5117.9  537.99  5147.0  538.75  5253.1  538.60  5270.1  537.80  5275.6  538.49
  5292.6  537.27  5298.2  538.32  5315.1  537.47  5328.1  538.60  5368.1  538.85
  5427.7  538.75  5439.4  539.37  5477.1  535.64  5517.4  534.90  5614.6  536.00
#Mann=7,-1,0
  4756.3    0.05       0  4979.1    0.03       0  4986.0    0.05       0
  5021.1     0.1       0  5048.1    0.12       0  5368.1     0.1       0
  5517.4    0.05       0
Bank Sta=4979.1,4986
Exp/Cntr=0.3,0.1

Type RM Length L Ch R = 1,2356,266,266,266
BEGIN DESCRIPTION:
Mapping XS 18833642
END DESCRIPTION:
XS GIS Cut Line= 5
      2030348.94     13528383.72      2030286.42     13528283.44
      2030049.45     13528094.64      2029887.99     13527993.07
      2029778.61     13527959.22
#Sta/Elev= 30
  4786.1  535.79  4925.6  534.47  4960.8  532.64  4996.0  532.23  5053.7  533.40
  5096.9  533.36  5103.3  532.96  5114.5  533.29  5153.0  532.76  5161.0  533.07
  5167.4  532.63  5181.8  532.89  5188.2  532.39  5211.6  532.59  5253.7  531.70
  5269.0  532.14  5274.9  531.65  5290.2  532.29  5296.1  531.61  5305.5  531.96
  5308.0  531.07  5308.5  530.27  5314.4  530.27  5314.9  531.07  5326.7  531.65
  5332.1  531.39  5412.6  532.79  5440.0  534.16  5474.1  534.50  5512.5  534.82
#Mann=6,-1,0
  4786.1    0.05       0  5114.5    0.12       0  5308.0    0.03       0
  5314.9    0.12       0  5332.1     0.1       0  5474.1    0.05       0
Bank Sta=5308,5314.9
Exp/Cntr=0.3,0.1

Type RM Length L Ch R = 1,2090,248,248,248
BEGIN DESCRIPTION:
Mapping XS 05cfb834
END DESCRIPTION:
XS GIS Cut Line= 4
      2030465.62     13528254.16      2030444.78     13528110.89
      2030119.26     13527868.70      2029981.20     13527866.09
#Sta/Elev= 30
  4660.3  534.98  4730.2  533.78  4790.8  533.59  4805.1  533.87  4808.8  534.28
  4817.2  533.85  4823.4  534.22  4838.0  533.46  4858.9  533.97  4873.5  533.16
  4879.7  533.44  4888.1  533.00  4908.9  533.21  4923.5  532.20  4952.7  531.51
  5002.8  530.80  5079.9  530.76  5084.9  530.32  5085.4  529.52  5091.3  529.52
  5091.8  530.32  5109.1  530.73  5123.8  530.46  5130.0  530.89  5153.0  531.29
  5215.4  533.40  5295.1  533.40  5305.1  533.66  5325.1  533.23  5348.9  533.43
#Mann=3,-1,0
  4660.3    0.05       0  5084.9    0.03       0  5091.8    0.05       0
Bank Sta=5084.9,5091.8
Exp/Cntr=0.3,0.1

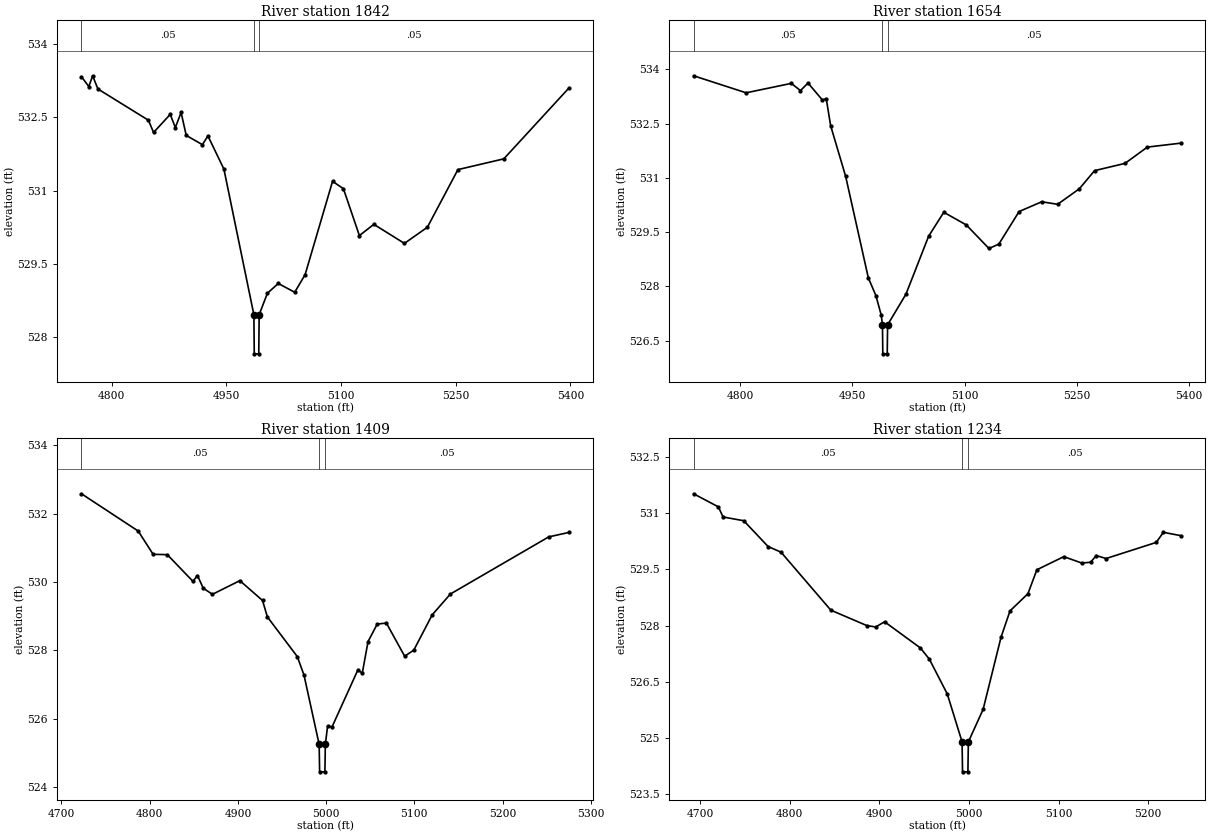
Type RM Length L Ch R = 1,1842,188,188,188
BEGIN DESCRIPTION:
Mapping XS 54412595
END DESCRIPTION:
XS GIS Cut Line= 4
      2030621.06     13528076.39      2030614.55     13527998.28
      2030395.80     13527802.97      2030129.83     13527803.60
#Sta/Elev= 30
  4760.5  533.33  4770.1  533.13  4775.1  533.35  4782.0  533.08  4848.1  532.44
  4854.8  532.19  4876.6  532.56  4883.3  532.29  4890.8  532.60  4897.5  532.13
  4918.7  531.94  4925.9  532.12  4946.8  531.44  4986.0  528.46  4986.5  527.66
  4992.4  527.66  4992.9  528.46  5003.7  528.90  5017.9  529.10  5039.4  528.92
  5053.0  529.28  5088.9  531.19  5103.1  531.04  5124.0  530.08  5142.9  530.31
  5182.9  529.92  5212.9  530.25  5252.9  531.43  5312.9  531.65  5398.1  533.10
#Mann=3,-1,0
  4760.5    0.05       0  4986.0    0.03       0  4992.9    0.05       0
Bank Sta=4986,4992.9
Exp/Cntr=0.3,0.1

Type RM Length L Ch R = 1,1654,245,245,245
BEGIN DESCRIPTION:
Mapping XS 236a7c2f
END DESCRIPTION:
XS GIS Cut Line= 4
      2030728.65     13527871.34      2030684.86     13527745.68
      2030293.74     13527694.22      2030171.33     13527717.66
#Sta/Elev= 30
  4737.5  533.82  4807.8  533.35  4868.3  533.61  4880.5  533.41  4890.6  533.62
  4909.9  533.15  4915.0  533.19  4920.9  532.44  4941.0  531.04  4971.3  528.24
  4981.4  527.75  4988.6  527.21  4990.2  526.94  4990.7  526.14  4996.6  526.14
  4997.1  526.94  5021.7  527.79  5052.0  529.39  5072.3  530.05  5102.4  529.70
  5132.7  529.05  5145.9  529.17  5173.0  530.07  5203.3  530.34  5224.6  530.27
  5253.7  530.70  5274.0  531.20  5314.7  531.40  5344.6  531.85  5389.7  531.96
#Mann=3,-1,0
  4737.5    0.05       0  4990.2    0.03       0  4997.1    0.05       0
Bank Sta=4990.2,4997.1
Exp/Cntr=0.3,0.1

Type RM Length L Ch R = 1,1409,175,175,175
BEGIN DESCRIPTION:
Mapping XS 536d76e1
END DESCRIPTION:
XS GIS Cut Line= 4
      2030734.30     13527516.48      2030669.24     13527467.03
      2030294.24     13527571.20      2030243.44     13527635.02
#Sta/Elev= 30
  4722.7  532.58  4787.0  531.49  4803.9  530.81  4820.0  530.80  4849.0  530.02
  4854.2  530.19  4860.7  529.82  4871.1  529.64  4902.2  530.04  4927.9  529.46
  4933.4  528.98  4967.3  527.82  4974.9  527.28  4992.1  525.25  4992.6  524.45
  4998.6  524.45  4999.1  525.25  5001.6  525.78  5006.8  525.77  5035.8  527.42
  5041.0  527.34  5047.5  528.26  5057.9  528.77  5068.3  528.80  5089.0  527.83
  5099.4  528.01  5120.2  529.04  5140.9  529.65  5252.3  531.32  5275.2  531.45
#Mann=3,-1,0
  4722.7    0.05       0  4992.1    0.03       0  4999.1    0.05       0
Bank Sta=4992.1,4999.1
Exp/Cntr=0.3,0.1

Type RM Length L Ch R = 1,1234,167,167,167
BEGIN DESCRIPTION:
Mapping XS 8789cfd9
END DESCRIPTION:
XS GIS Cut Line= 4
      2030729.12     13527424.02      2030712.21     13527370.68
      2030317.67     13527364.17      2030258.92     13527436.97
#Sta/Elev= 30
  4692.6  531.52  4720.3  531.17  4725.5  530.90  4748.6  530.80  4775.8  530.11
  4790.2  529.96  4845.8  528.41  4885.8  528.00  4895.8  527.96  4905.8  528.10
  4945.8  527.40  4955.8  527.10  4975.8  526.17  4992.3  524.89  4992.8  524.09
  4998.8  524.09  4999.3  524.89  5015.8  525.76  5035.8  527.69  5045.8  528.39
  5065.8  528.85  5075.8  529.49  5105.8  529.84  5125.8  529.67  5135.8  529.69
  5142.0  529.87  5153.0  529.79  5209.0  530.22  5217.0  530.49  5236.7  530.40
#Mann=3,-1,0
  4692.6    0.05       0  4992.3    0.03       0  4999.3    0.05       0
Bank Sta=4992.3,4999.3
Exp/Cntr=0.3,0.1