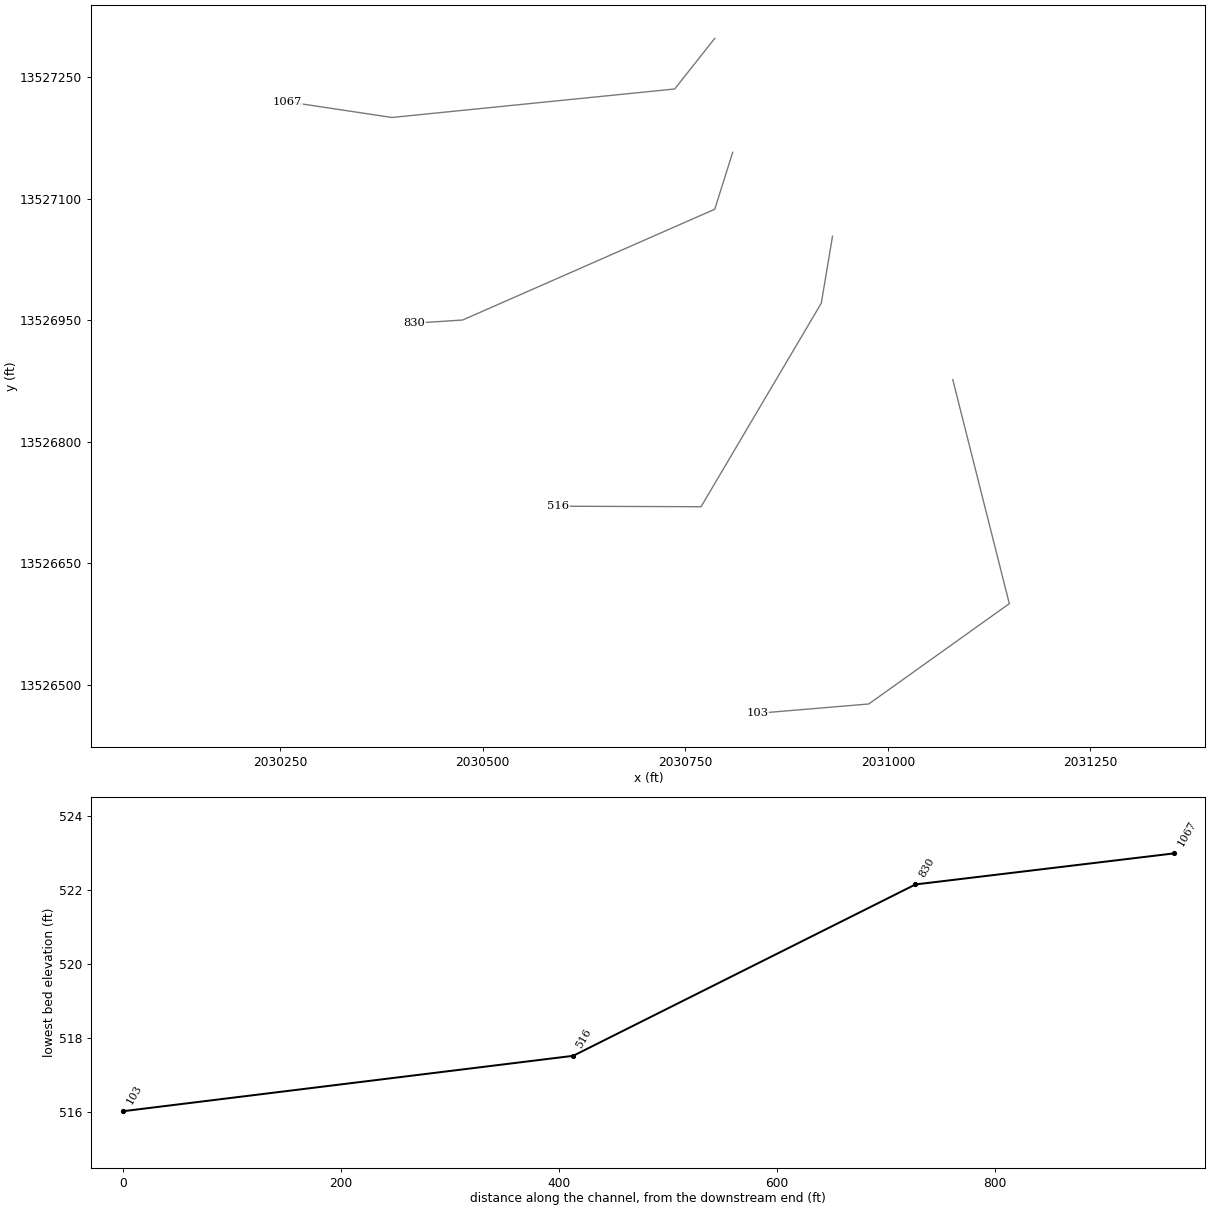
HEC-RAS study WEST FORK ELLIS Br.prj: WEST FORK ELLIS Br Base Level Engineering

--- WEST FORK ELLIS Br.g01 (geometry) --- (continued)

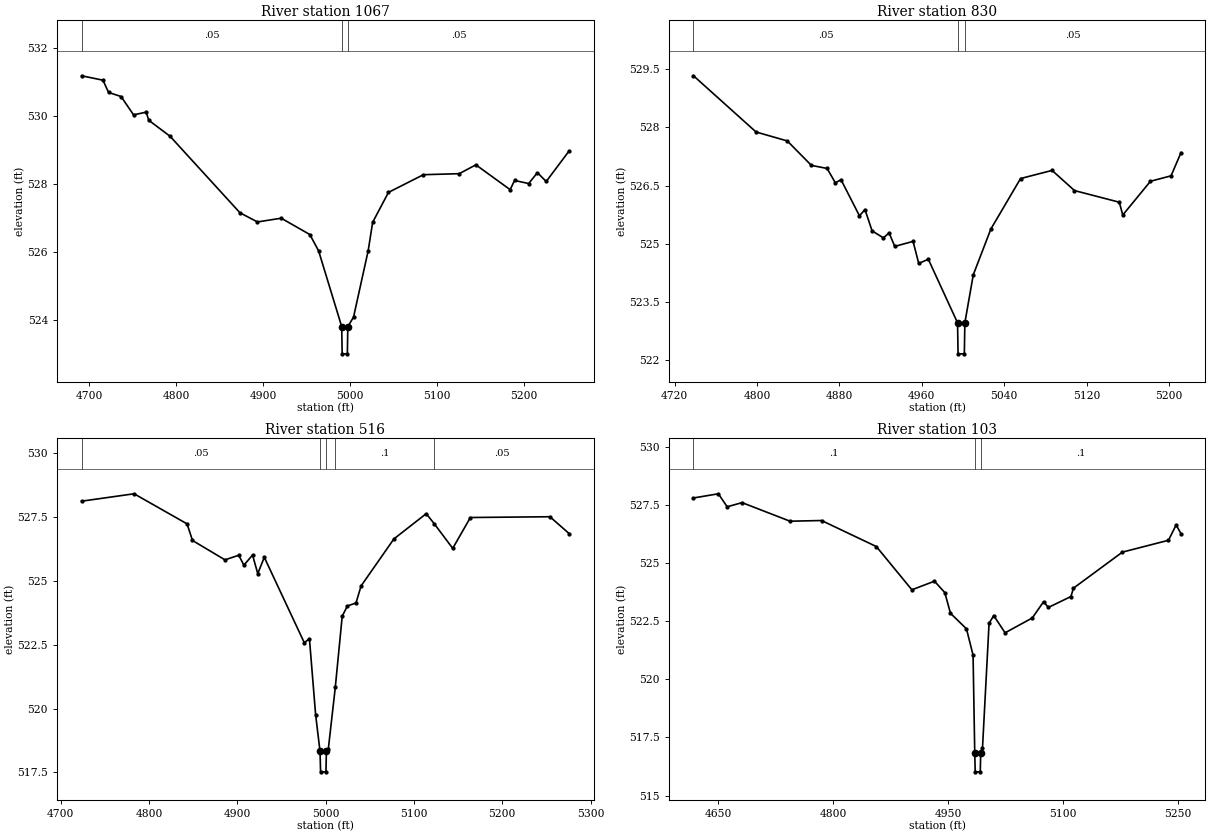
Type RM Length L Ch R = 1,1067,237,237,237
BEGIN DESCRIPTION:
Mapping XS b29fbb66
END DESCRIPTION:
XS GIS Cut Line= 4
      2030786.44     13527297.78      2030736.95     13527235.26
      2030387.99     13527200.10      2030258.90     13527219.47
#Sta/Elev= 30
  4691.1  531.18  4715.7  531.05  4722.1  530.69  4736.5  530.57  4750.9  530.03
  4765.4  530.11  4768.4  529.87  4792.9  529.40  4873.3  527.15  4893.4  526.88
  4920.8  526.99  4953.7  526.51  4963.8  526.03  4990.4  523.80  4990.9  523.00
  4996.9  523.00  4997.4  523.80  5004.0  524.08  5020.9  526.04  5026.0  526.87
  5044.2  527.75  5084.4  528.27  5125.6  528.30  5144.8  528.56  5184.2  527.83
  5189.3  528.10  5205.5  528.01  5215.6  528.33  5225.7  528.07  5252.1  528.97
#Mann=3,-1,0
  4691.1    0.05       0  4990.4    0.03       0  4997.4    0.05       0
Bank Sta=4990.4,4997.4
Exp/Cntr=0.3,0.1

Type RM Length L Ch R = 1,830,314,314,314
BEGIN DESCRIPTION:
Mapping XS c9864b3b
END DESCRIPTION:
XS GIS Cut Line= 4
      2030808.55     13527157.09      2030786.42     13527086.82
      2030475.23     13526950.10      2030415.33     13526946.20
#Sta/Elev= 30
  4738.2  529.33  4799.0  527.88  4829.3  527.65  4852.7  527.02  4868.0  526.94
  4876.0  526.57  4881.5  526.65  4899.4  525.72  4904.8  525.88  4911.7  525.33
  4922.7  525.15  4928.2  525.28  4933.7  524.93  4951.5  525.06  4957.0  524.49
  4966.3  524.60  4994.7  522.96  4995.2  522.16  5001.3  522.16  5001.8  522.96
  5010.0  524.20  5027.1  525.38  5055.9  526.68  5086.5  526.89  5108.3  526.37
  5151.8  526.07  5155.2  525.74  5182.1  526.61  5202.1  526.75  5211.8  527.35
#Mann=3,-1,0
  4738.2    0.05       0  4994.7    0.03       0  5001.8    0.05       0
Bank Sta=4994.7,5001.8
Exp/Cntr=0.3,0.1

Type RM Length L Ch R = 1,516,413,413,413
BEGIN DESCRIPTION:
Mapping XS b463210f
END DESCRIPTION:
XS GIS Cut Line= 4
      2030931.76     13527053.57      2030917.93     13526970.94
      2030769.50     13526719.64      2030593.25     13526720.26
#Sta/Elev= 30
  4723.8  528.13  4783.2  528.42  4843.2  527.24  4849.3  526.59  4886.1  525.83
  4901.7  526.01  4907.5  525.62  4917.3  526.02  4923.2  525.29  4930.6  525.93
  4975.9  522.58  4981.7  522.74  4988.7  519.76  4993.7  518.32  4994.3  517.52
  5000.4  517.52  5000.9  518.32  5003.1  518.42  5011.0  520.84  5018.8  523.62
  5024.6  524.02  5034.4  524.14  5040.2  524.81  5077.3  526.65  5113.9  527.64
  5122.9  527.25  5143.9  526.28  5163.9  527.49  5253.9  527.52  5275.7  526.86
#Mann=5,-1,0
  4723.8    0.05       0  4993.7    0.03       0  5000.9    0.05       0
  5011.0     0.1       0  5122.9    0.05       0
Bank Sta=4993.7,5000.9
Exp/Cntr=0.3,0.1

Type RM Length L Ch R = 1,103,0,0,0
BEGIN DESCRIPTION:
WEST FORK ELLIS Br 1.0
END DESCRIPTION:
XS GIS Cut Line= 4
      2031080.20     13526876.51      2031150.00     13526600.00
      2030976.53     13526476.15      2030838.65     13526464.55
#Sta/Elev= 30
  4617.5  527.80  4650.0  527.98  4661.5  527.42  4680.9  527.60  4743.6  526.80
  4784.7  526.83  4856.3  525.71  4902.7  523.85  4932.2  524.22  4945.7  523.73
  4953.1  522.84  4974.0  522.17  4982.6  521.04  4984.8  516.82  4985.4  516.02
  4992.0  516.02  4992.6  516.82  4994.9  517.03  5003.5  522.41  5009.6  522.74
  5024.4  522.00  5060.0  522.64  5074.7  523.34  5080.9  523.09  5110.4  523.56
  5113.7  523.92  5177.6  525.47  5237.8  525.98  5247.8  526.64  5254.2  526.26
#Mann=3,-1,0
  4617.5     0.1       0  4984.8    0.07       0  4992.6     0.1       0
Bank Sta=4984.8,4992.6
Exp/Cntr=0.3,0.1

Chan Stop Cuts=-1