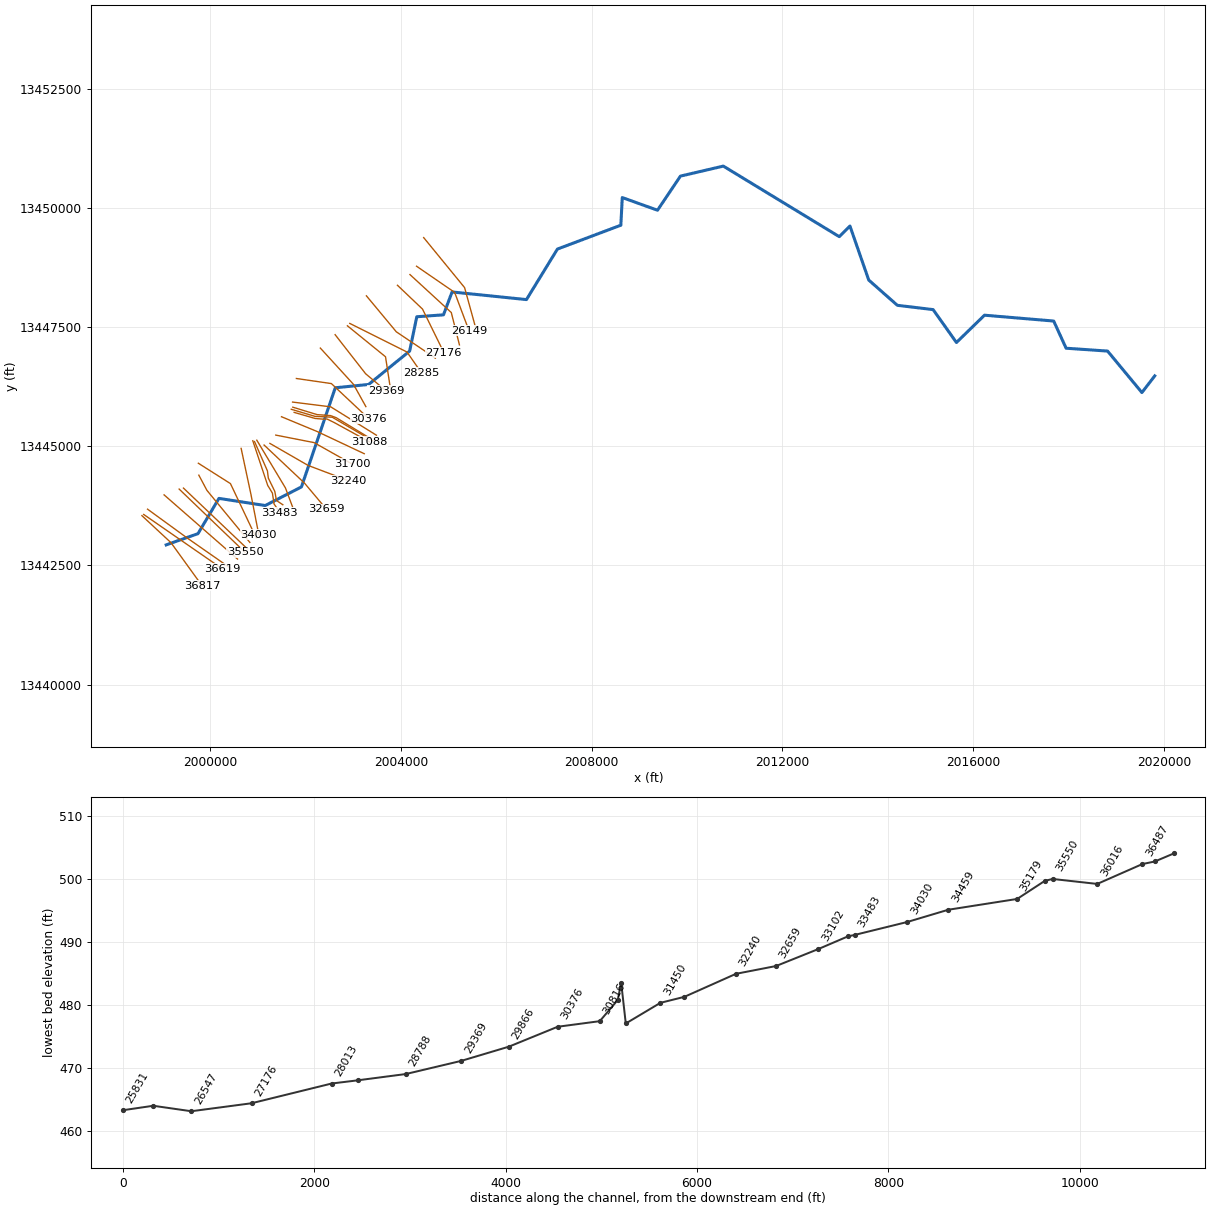
--- Calf Creek.prj (project) ---

Proj Title=Calf Creek Base Level Engineering
Current Plan=p01
Default Exp/Contr=0.3,0.1
English Units
Geom File=g01
Flow File=f01
Plan File=p01
Y Axis Title=Elevation
X Axis Title(PF)=Main Channel Distance
X Axis Title(XS)=Station
BEGIN DESCRIPTION:
Calf Creek
END DESCRIPTION:
DSS Export Rating Curves= 0
DSS Export Rating Curve Sorted= 0
DSS Export Volume Flow Curves= 0
DXF OffsetX= 0
DXF OffsetY= 0
DXF ScaleX= 1
DXF ScaleY= 10

--- Calf Creek.p01 (plan) ---

Plan Title=Multiple Run
Short Identifier=Multiple
Geom File=g01
Flow File=f01
Subcritical Flow
K Sum by GR= 0
Std Step Tol= 0.01
Critical Tol= 0.01
Num of Std Step Trials= 20
Max Error Tol= 0.3
Flow Tol Ratio= 0.001
Split Flow NTrial= 30
Split Flow Tol= 0.02
Split Flow Ratio= 0.02
Log Output Level= 0
Friction Slope Method= 1
Unsteady Friction Slope Method= 2
Unsteady Bridges Friction Slope Method= 1
Parabolic Critical Depth
Global Vel Dist=  1 , 1 , 1
Global Log Level= 0
CheckData=True
Encroach Param= -1, 0, 0, 0
BEGIN DESCRIPTION:
Multiple Run
END DESCRIPTION:

--- Calf Creek.f01 (steady flow) ---

Flow Title=Multiple
Program Version=5.05
Number of Profiles= 7
Profile Names=10-year,25-year,50-year,1pct_min,100-year,1pct_plu,500-year
River Rch & RM=Calf Creek,Reach-1         ,36817
     105     137     163      97     193     385     274
River Rch & RM=Calf Creek,Reach-1         ,36619
     193     262     318     193     385     768     570
River Rch & RM=Calf Creek,Reach-1         ,32659
     287     399     492     302     603    1203     918
River Rch & RM=Calf Creek,Reach-1         ,30376
     362     508     630     389     776    1548    1196
River Rch & RM=Calf Creek,Reach-1         ,19996
     433     613     765     475     947    1889    1475
River Rch & RM=Calf Creek,Reach-1         ,15111
     490     697     873     543    1083    2161    1697
River Rch & RM=Calf Creek,Reach-1         ,3444
     699    1011    1278     802    1601    3194    2554
Boundary for River Rch & Prof#=Calf Creek,Reach-1         , 1
Up Type= 0
Dn Type= 3
Dn Slope=0.00277
Boundary for River Rch & Prof#=Calf Creek,Reach-1         , 2
Up Type= 0
Dn Type= 3
Dn Slope=0.00277
Boundary for River Rch & Prof#=Calf Creek,Reach-1         , 3
Up Type= 0
Dn Type= 3
Dn Slope=0.00277
Boundary for River Rch & Prof#=Calf Creek,Reach-1         , 4
Up Type= 0
Dn Type= 3
Dn Slope=0.00277
Boundary for River Rch & Prof#=Calf Creek,Reach-1         , 5
Up Type= 0
Dn Type= 3
Dn Slope=0.00277
Boundary for River Rch & Prof#=Calf Creek,Reach-1         , 6
Up Type= 0
Dn Type= 3
Dn Slope=0.00277
Boundary for River Rch & Prof#=Calf Creek,Reach-1         , 7
Up Type= 0
Dn Type= 3
Dn Slope=0.00277
DSS Import GetInterval= 0
DSS Import GetPeak= 0
DSS Import FillOption= 0

--- Calf Creek.g01 (geometry) ---

Geom Title=Existing Conditions

River Reach=Calf Creek,Reach-1
Reach XY= 30
      1999073.92     13442929.23      1999740.80     13443164.54
      2000180.80     13443904.54      2001150.80     13443754.54
      2001910.80     13444144.54      2002620.80     13446224.54
      2003320.80     13446294.54      2004180.80     13446994.54
      2004330.80     13447714.54      2004890.80     13447754.54
      2005070.80     13448234.54      2006630.80     13448074.54
      2007280.80     13449134.54      2008610.80     13449634.54
      2008640.80     13450214.54      2009380.06     13449949.39
      2009860.80     13450664.54      2010760.80     13450874.54
      2013192.56     13449394.53      2013416.86     13449617.44
      2013810.80     13448484.54      2014410.80     13447954.54
      2015160.80     13447864.54      2015650.80     13447174.54
      2016238.94     13447747.14      2017690.80     13447624.54
      2017950.80     13447054.54      2018820.80     13446994.54
      2019540.80     13446124.54      2019810.80     13446474.54

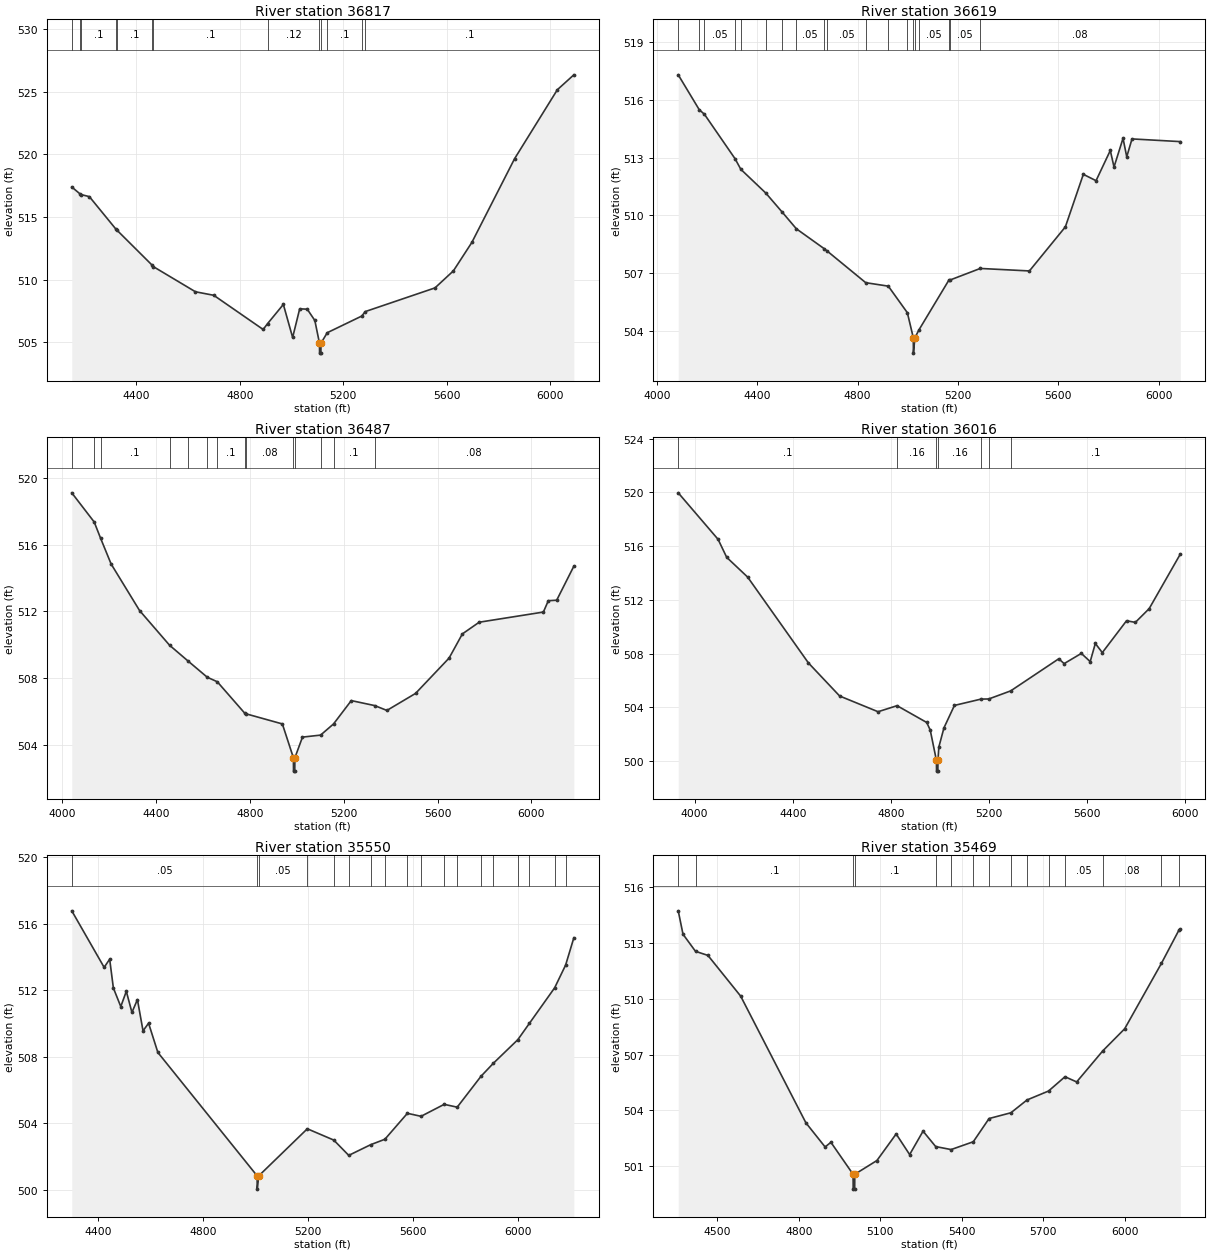
Type RM Length L Ch R = 1,36817,198,198,198
BEGIN DESCRIPTION:
Calf Creek 65.0
END DESCRIPTION:
XS GIS Cut Line= 3
      1998565.25     13443541.89      1999175.00     13442975.00
      1999824.97     13442075.04
#Sta/Elev= 30
  4150.0  517.39  4182.4  516.83  4185.3  516.79  4218.1  516.62  4320.6  514.03
  4325.4  513.93  4458.8  511.19  4465.6  511.03  4628.6  509.02  4699.4  508.74
  4890.5  506.01  4907.8  506.48  4968.7  508.01  5004.6  505.37  5031.9  507.66
  5061.1  507.63  5090.5  506.73  5108.4  504.92  5108.9  504.12  5113.9  504.12
  5114.4  504.92  5138.5  505.75  5271.9  507.08  5285.7  507.44  5555.4  509.33
  5626.6  510.69  5698.0  512.96  5863.4  519.65  6028.9  525.16  6092.7  526.35
#Mann=13,-1,0
  4150.0     0.1       0  4182.4    0.08       0  4185.3     0.1       0
  4320.6    0.05       0  4325.4     0.1       0  4458.8    0.05       0
  4465.6     0.1       0  4907.8    0.12       0  5108.4    0.07       0
  5114.4    0.12       0  5138.5     0.1       0  5271.9    0.07       0
  5285.7     0.1       0
Bank Sta=5108.4,5114.4
Exp/Cntr=0.3,0.1

Type RM Length L Ch R = 1,36619,132,132,132
BEGIN DESCRIPTION:
Mapping XS 9bb7508a
END DESCRIPTION:
XS GIS Cut Line= 2
      1998601.73     13443567.91      2000247.51     13442429.93
#Sta/Elev= 30
  4085.4  517.30  4169.0  515.49  4189.8  515.25  4311.9  512.94  4334.9  512.39
  4434.1  511.16  4500.8  510.15  4556.2  509.30  4666.7  508.27  4678.4  508.15
  4832.6  506.50  4922.6  506.32  4998.5  504.94  5022.2  503.64  5022.7  502.84
  5028.5  503.64  5044.8  504.05  5164.3  506.64  5166.9  506.63  5289.1  507.24
  5484.9  507.11  5628.2  509.40  5699.8  512.13  5750.5  511.80  5807.3  513.37
  5822.1  512.51  5858.0  514.00  5872.8  513.04  5893.8  513.97  6086.3  513.83
#Mann=19,-1,0
  4085.4    0.08       0  4169.0     0.1       0  4189.8    0.05       0
  4311.9    0.08       0  4334.9    0.05       0  4434.1    0.08       0
  4500.8     0.1       0  4556.2    0.05       0  4666.7     0.1       0
  4678.4    0.05       0  4832.6     0.1       0  4922.6    0.08       0
  4998.5    0.07       0  5022.2    0.07       0  5028.5    0.07       0
  5044.8    0.05       0  5164.3     0.1       0  5166.9    0.05       0
  5289.1    0.08       0
Bank Sta=5022.2,5028.5
Exp/Cntr=0.3,0.1

Type RM Length L Ch R = 1,36487,471,471,471
BEGIN DESCRIPTION:
Calf Creek 64.0
END DESCRIPTION:
XS GIS Cut Line= 3
      1998683.34     13443678.15      1999503.30     13443081.60
      2000428.12     13442436.83
#Sta/Elev= 30
  4040.0  519.11  4135.7  517.36  4163.1  516.38  4207.9  514.84  4329.2  512.05
  4457.1  509.97  4536.2  509.02  4617.9  508.05  4660.6  507.78  4778.6  505.88
  4785.0  505.85  4938.2  505.25  4985.3  503.22  4985.8  502.42  4991.1  502.42
  4991.6  503.22  5024.0  504.46  5101.2  504.58  5156.5  505.25  5232.2  506.65
  5332.1  506.35  5384.1  506.06  5506.2  507.08  5649.3  509.20  5706.0  510.65
  5777.6  511.35  6051.5  511.96  6072.5  512.64  6108.2  512.67  6181.4  514.71
#Mann=14,-1,0
  4040.0     0.1       0  4135.7    0.08       0  4163.1     0.1       0
  4457.1    0.08       0  4536.2     0.1       0  4617.9    0.08       0
  4660.6     0.1       0  4778.6    0.05       0  4785.0    0.08       0
  4985.3    0.07       0  4991.6    0.08       0  5101.2    0.08       0
  5156.5     0.1       0  5332.1    0.08       0
Bank Sta=4985.3,4991.6
Exp/Cntr=0.3,0.1

Type RM Length L Ch R = 1,36016,466,466,466
BEGIN DESCRIPTION:
Mapping XS 19ec0737
END DESCRIPTION:
XS GIS Cut Line= 2
      1999029.65     13443978.53      2000570.66     13442631.88
#Sta/Elev= 30
  3933.3  519.97  4095.7  516.51  4130.8  515.17  4216.2  513.70  4464.0  507.31
  4591.2  504.85  4747.8  503.68  4825.2  504.13  4946.2  502.88  4960.4  502.32
  4985.7  500.06  4986.2  499.26  4991.5  499.26  4992.0  500.06  4995.5  501.05
  5016.4  502.48  5059.1  504.15  5167.5  504.62  5199.0  504.63  5288.3  505.23
  5484.4  507.62  5506.2  507.26  5576.4  508.02  5612.5  507.41  5633.4  508.76
  5661.9  508.08  5760.6  510.45  5796.6  510.33  5852.8  511.35  5979.8  515.41
#Mann=7,-1,0
  3933.3     0.1       0  4825.2    0.16       0  4985.7    0.07       0
  4992.0    0.16       0  5167.5     0.1       0  5199.0    0.16       0
  5288.3     0.1       0
Bank Sta=4985.7,4992
Exp/Cntr=0.3,0.1

Type RM Length L Ch R = 1,35550,81,81,81
BEGIN DESCRIPTION:
Mapping XS ec7873dd
END DESCRIPTION:
XS GIS Cut Line= 2
      1999345.65     13444100.04      2000727.60     13442773.64
#Sta/Elev= 30
  4298.3  516.79  4421.8  513.39  4442.9  513.88  4457.0  512.15  4485.3  511.03
  4506.4  511.95  4527.8  510.68  4548.8  511.45  4570.2  509.57  4591.3  510.03
  4626.8  508.27  5005.4  500.85  5005.9  500.05  5011.8  500.85  5197.0  503.68
  5297.9  503.00  5355.0  502.08  5438.3  502.72  5492.9  503.05  5578.8  504.61
  5630.8  504.43  5719.2  505.15  5768.8  504.98  5859.7  506.84  5906.7  507.62
  6000.1  509.04  6044.6  510.03  6140.6  512.16  6182.5  513.53  6213.8  515.17
#Mann=18,-1,0
  4298.3    0.05       0  5005.4    0.04       0  5011.8    0.05       0
  5197.0    0.16       0  5297.9    0.05       0  5355.0     0.1       0
  5438.3    0.05       0  5492.9     0.1       0  5578.8    0.05       0
  5630.8     0.1       0  5719.2    0.08       0  5768.8     0.1       0
  5859.7    0.05       0  5906.7     0.1       0  6000.1    0.08       0
  6044.6     0.1       0  6140.6    0.05       0  6182.5     0.1       0
Bank Sta=5005.4,5011.8
Exp/Cntr=0.3,0.1

Type RM Length L Ch R = 1,35469,290,290,290
BEGIN DESCRIPTION:
Mapping XS 7b914c85
END DESCRIPTION:
XS GIS Cut Line= 2
      1999435.94     13444120.85      2000776.24     13442846.53
#Sta/Elev= 30
  4355.5  514.74  4373.1  513.48  4419.1  512.56  4464.9  512.34  4585.4  510.15
  4825.7  503.33  4896.5  502.03  4917.9  502.28  4999.5  500.56  5000.0  499.76
  5005.4  499.76  5005.9  500.56  5087.4  501.30  5158.2  502.73  5207.9  501.62
  5257.3  502.88  5303.8  502.05  5360.7  501.89  5442.3  502.31  5500.5  503.56
  5580.9  503.87  5640.3  504.56  5719.5  505.04  5780.1  505.81  5823.1  505.53
  5919.8  507.21  5999.9  508.39  6135.2  511.91  6199.4  513.69  6204.9  513.75
#Mann=15,-1,0
  4355.5    0.05       0  4419.1     0.1       0  4999.5    0.07       0
  5005.9     0.1       0  5303.8    0.05       0  5360.7     0.1       0
  5442.3    0.05       0  5500.5     0.1       0  5580.9    0.05       0
  5640.3     0.1       0  5719.5    0.08       0  5780.1    0.05       0
  5919.8    0.08       0  6135.2    0.05       0  6199.4    0.08       0
Bank Sta=4999.5,5005.9
Exp/Cntr=0.3,0.1

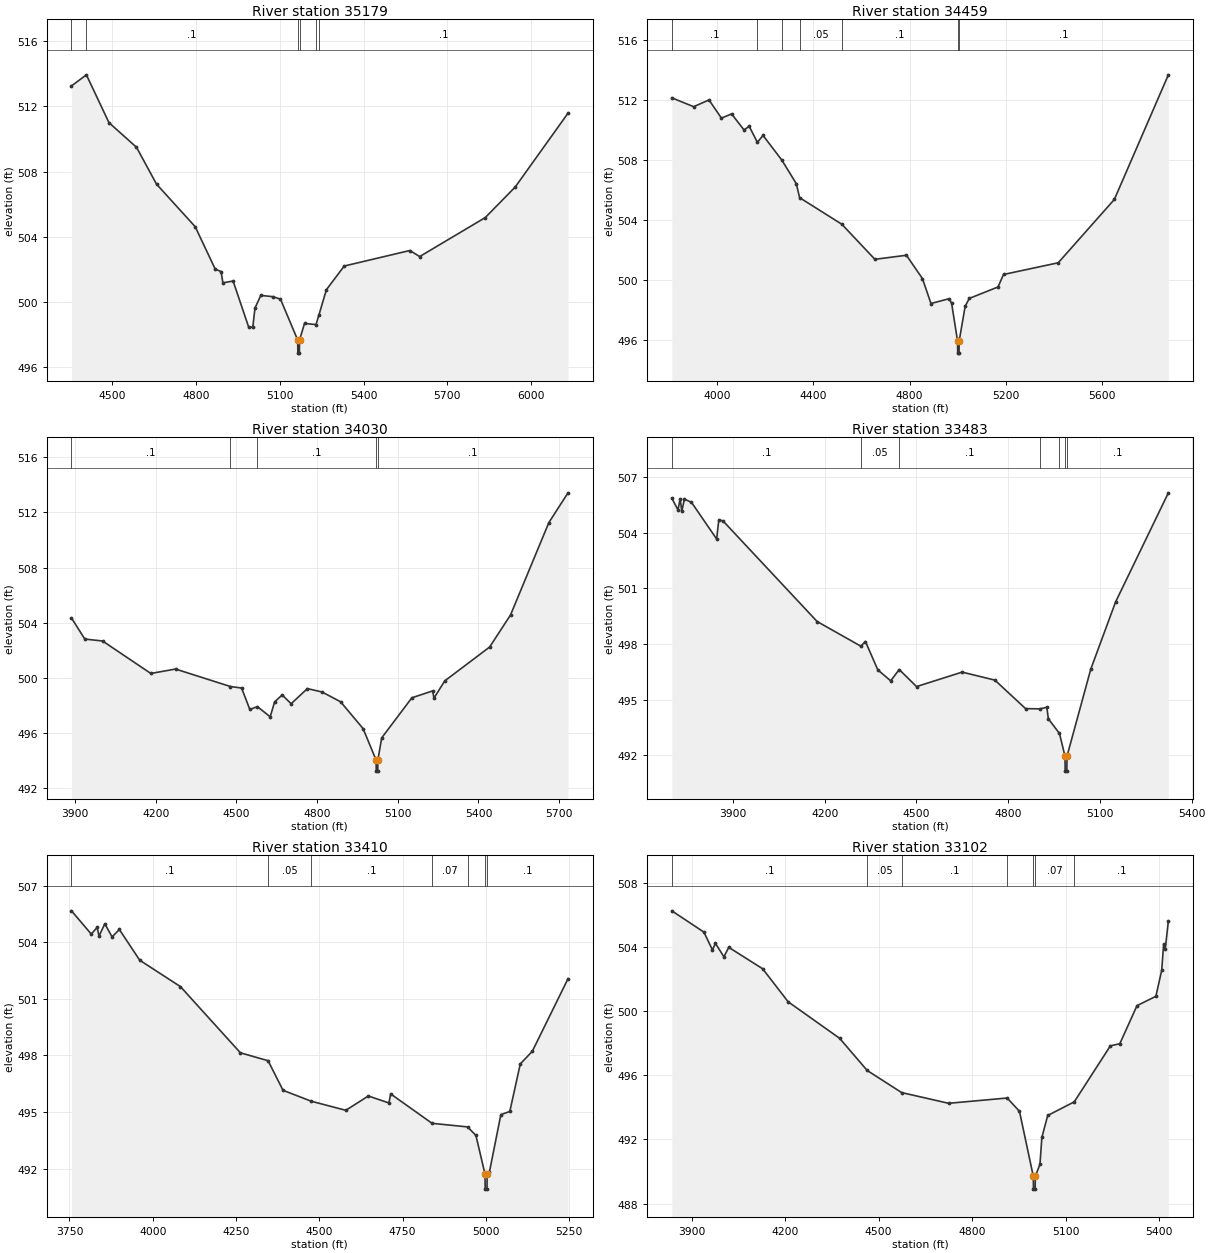
Type RM Length L Ch R = 1,35179,720,720,720
BEGIN DESCRIPTION:
Mapping XS 0a01de20
END DESCRIPTION:
XS GIS Cut Line= 3
      1999758.87     13444391.65      1999928.99     13444072.25
      2000828.30     13442981.97
#Sta/Elev= 30
  4355.9  513.25  4409.2  513.93  4489.8  511.00  4588.3  509.49  4659.9  507.23
  4798.2  504.62  4869.8  502.02  4890.7  501.87  4897.2  501.18  4933.7  501.29
  4989.7  498.45  5004.1  498.46  5011.9  499.63  5032.7  500.41  5075.8  500.33
  5103.1  500.18  5164.7  497.67  5165.2  496.87  5170.6  496.87  5171.1  497.67
  5189.1  498.69  5230.1  498.62  5240.4  499.20  5267.3  500.76  5331.1  502.21
  5565.6  503.16  5600.8  502.79  5835.3  505.18  5942.2  507.05  6131.1  511.58
#Mann=6,-1,0
  4355.9    0.08       0  4409.2     0.1       0  5164.7    0.07       0
  5171.1     0.1       0  5230.1    0.12       0  5240.4     0.1       0
Bank Sta=5164.7,5171.1
Exp/Cntr=0.3,0.1

Type RM Length L Ch R = 1,34459,429,429,429
BEGIN DESCRIPTION:
Calf Creek 62.0
END DESCRIPTION:
XS GIS Cut Line= 3
      1999748.43     13444641.70      2000422.05     13444214.61
      2000963.73     13443072.22
#Sta/Elev= 30
  3812.9  512.13  3903.5  511.54  3967.1  511.99  4018.8  510.78  4061.1  511.06
  4112.8  509.99  4134.0  510.24  4168.0  509.17  4191.6  509.63  4269.6  507.99
  4329.8  506.42  4343.5  505.49  4519.0  503.72  4656.1  501.39  4787.0  501.66
  4853.5  500.11  4889.0  498.45  4964.2  498.77  4974.5  498.48  4999.5  495.95
  5000.0  495.15  5005.5  495.15  5006.0  495.95  5031.0  498.27  5048.2  498.79
  5167.4  499.55  5190.2  500.38  5417.5  501.16  5650.4  505.37  5874.8  513.66
#Mann=7,-1,0
  3812.9     0.1       0  4168.0    0.05       0  4269.6     0.1       0
  4343.5    0.05       0  4519.0     0.1       0  4999.5    0.07       0
  5006.0     0.1       0
Bank Sta=4999.5,5006
Exp/Cntr=0.3,0.1

Type RM Length L Ch R = 1,34030,547,547,547
BEGIN DESCRIPTION:
Calf Creek 61.0
END DESCRIPTION:
XS GIS Cut Line= 3
      2000646.00     13444953.37      2000852.60     13443985.45
      2001015.79     13443145.18
#Sta/Elev= 30
  3887.1  504.33  3936.6  502.80  4002.6  502.66  4182.0  500.30  4274.0  500.62
  4477.9  499.35  4519.4  499.24  4550.1  497.68  4578.1  497.89  4625.8  497.15
  4642.1  498.23  4670.2  498.74  4703.5  498.10  4764.1  499.20  4818.8  498.95
  4887.5  498.24  4971.1  496.29  5019.5  494.00  5020.0  493.20  5025.5  493.20
  5026.0  494.00  5040.3  495.62  5152.3  498.53  5229.5  499.03  5234.6  498.51
  5274.6  499.76  5441.4  502.22  5519.1  504.55  5661.7  511.27  5732.8  513.43
#Mann=5,-1,0
  3887.1     0.1       0  4477.9    0.05       0  4578.1     0.1       0
  5019.5    0.07       0  5026.0     0.1       0
Bank Sta=5019.5,5026
Exp/Cntr=0.3,0.1

Type RM Length L Ch R = 1,33483,73,73,73
BEGIN DESCRIPTION:
Calf Creek 60.0
END DESCRIPTION:
XS GIS Cut Line= 5
      2000890.79     13445113.95      2001203.30     13444177.29
      2001302.25     13444015.83      2001336.11     13443789.26
      2001457.48     13443608.50
#Sta/Elev= 30
  3700.2  505.87  3720.2  505.24  3727.4  505.84  3732.7  505.17  3741.3  505.82
  3764.3  505.65  3846.7  503.67  3853.8  504.71  3867.8  504.64  4175.2  499.22
  4318.1  497.89  4333.3  498.14  4373.8  496.61  4415.9  496.02  4443.7  496.63
  4500.3  495.71  4649.4  496.49  4756.3  496.06  4857.0  494.52  4903.8  494.51
  4926.4  494.59  4931.4  493.97  4967.8  493.18  4985.8  491.95  4986.3  491.15
  4991.8  491.15  4992.3  491.95  5069.9  496.64  5151.1  500.27  5323.8  506.16
#Mann=7,-1,0
  3700.2     0.1       0  4318.1    0.05       0  4443.7     0.1       0
  4903.8    0.07       0  4967.8     0.1       0  4985.8    0.07       0
  4992.3     0.1       0
Bank Sta=4985.8,4992.3
Exp/Cntr=0.3,0.1

Type RM Length L Ch R = 1,33410,308,308,308
BEGIN DESCRIPTION:
Mapping XS 94e80b3e
END DESCRIPTION:
XS GIS Cut Line= 6
      2000927.24     13445096.58      2001198.09     13444479.37
      2001216.32     13444330.93      2001351.73     13444052.29
      2001388.19     13443859.58      2001520.49     13443771.38
#Sta/Elev= 30
  3756.0  505.67  3815.2  504.44  3833.1  504.79  3838.6  504.33  3856.0  504.98
  3877.9  504.29  3899.7  504.68  3960.9  503.05  4083.1  501.65  4263.1  498.14
  4346.2  497.72  4391.1  496.15  4476.1  495.57  4579.6  495.09  4647.2  495.85
  4708.9  495.48  4714.2  495.96  4838.5  494.40  4945.0  494.21  4970.1  493.76
  4997.4  491.71  4997.9  490.91  5003.4  490.91  5003.9  491.71  5010.8  491.83
  5045.0  494.86  5071.9  495.03  5103.3  497.55  5139.4  498.22  5246.6  502.07
#Mann=7,-1,0
  3756.0     0.1       0  4346.2    0.05       0  4476.1     0.1       0
  4838.5    0.07       0  4945.0     0.1       0  4997.4    0.07       0
  5003.9     0.1       0
Bank Sta=4997.4,5003.9
Exp/Cntr=0.3,0.1

Type RM Length L Ch R = 1,33102,443,443,443
BEGIN DESCRIPTION:
Calf Creek 59.0
END DESCRIPTION:
XS GIS Cut Line= 3
      2000975.00     13445124.99      2001575.00     13444125.00
      2001725.01     13443724.99
#Sta/Elev= 30
  3836.6  506.28  3939.6  504.95  3966.8  503.84  3976.5  504.25  4003.7  503.41
  4019.3  504.00  4128.1  502.66  4209.8  500.60  4375.0  498.32  4463.5  496.31
  4574.0  494.93  4724.8  494.26  4912.7  494.59  4952.2  493.76  4996.6  489.70
  4997.1  488.90  5002.6  488.90  5003.1  489.70  5017.9  490.45  5024.1  492.13
  5042.8  493.50  5128.0  494.35  5244.0  497.85  5274.2  497.98  5329.4  500.36
  5389.9  500.94  5408.6  502.56  5414.9  504.21  5420.2  503.92  5430.0  505.65
#Mann=7,-1,0
  3836.6     0.1       0  4463.5    0.05       0  4574.0     0.1       0
  4912.7    0.07       0  4996.6    0.07       0  5003.1    0.07       0
  5128.0     0.1       0
Bank Sta=4996.6,5003.1
Exp/Cntr=0.3,0.1

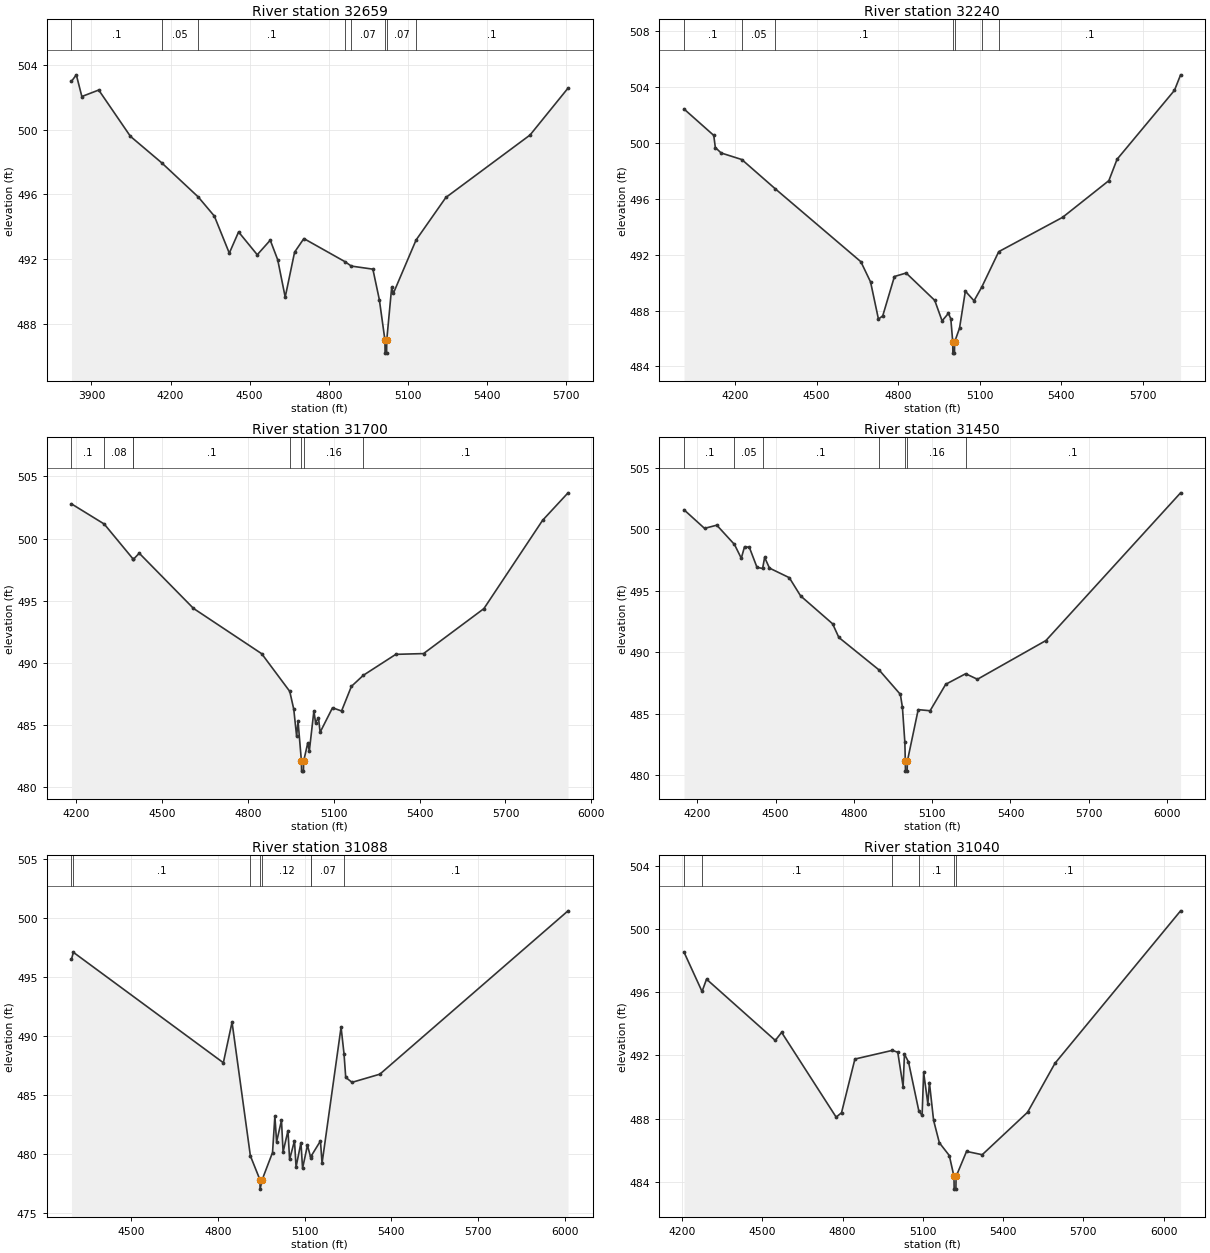
Type RM Length L Ch R = 1,32659,419,419,419
BEGIN DESCRIPTION:
Calf Creek 58.0
END DESCRIPTION:
XS GIS Cut Line= 3
      2001127.81     13445023.61      2001975.00     13444225.00
      2002437.65     13443674.70
#Sta/Elev= 30
  3824.2  502.99  3842.5  503.39  3863.5  502.05  3927.5  502.45  4047.6  499.59
  4165.8  497.96  4305.0  495.84  4366.0  494.66  4422.7  492.37  4457.9  493.68
  4528.7  492.27  4578.0  493.17  4606.3  491.96  4634.7  489.65  4670.3  492.43
  4705.5  493.27  4861.6  491.84  4885.3  491.57  4967.2  491.38  4991.7  489.50
  5013.0  486.99  5013.5  486.19  5019.3  486.19  5019.8  486.99  5038.5  490.25
  5045.0  489.89  5131.0  493.18  5244.0  495.81  5563.3  499.67  5707.4  502.57
#Mann=8,-1,0
  3824.2     0.1       0  4165.8    0.05       0  4305.0     0.1       0
  4861.6    0.12       0  4885.3    0.07       0  5013.0    0.07       0
  5019.8    0.07       0  5131.0     0.1       0
Bank Sta=5013,5019.8
Exp/Cntr=0.3,0.1

Type RM Length L Ch R = 1,32240,540,540,540
BEGIN DESCRIPTION:
Calf Creek 57.0
END DESCRIPTION:
XS GIS Cut Line= 3
      2001250.19     13445057.48      2002049.65     13444596.56
      2002896.04     13444276.23
#Sta/Elev= 30
  4011.8  502.44  4121.2  500.55  4127.0  499.68  4148.5  499.29  4224.5  498.82
  4348.4  496.71  4662.7  491.50  4698.4  490.05  4727.4  487.39  4743.2  487.62
  4786.3  490.44  4829.4  490.69  4934.6  488.73  4961.7  487.26  4984.9  487.80
  4993.8  487.41  5000.9  485.75  5001.4  484.95  5007.3  484.95  5007.8  485.75
  5025.9  486.74  5047.3  489.39  5079.3  488.70  5107.9  489.69  5170.2  492.22
  5405.3  494.68  5575.6  497.31  5605.8  498.84  5817.1  503.78  5839.6  504.89
#Mann=7,-1,0
  4011.8     0.1       0  4224.5    0.05       0  4348.4     0.1       0
  5000.9    0.07       0  5007.8     0.1       0  5107.9    0.16       0
  5170.2     0.1       0
Bank Sta=5000.9,5007.8
Exp/Cntr=0.3,0.1

Type RM Length L Ch R = 1,31700,250,250,250
BEGIN DESCRIPTION:
Calf Creek 56.0
END DESCRIPTION:
XS GIS Cut Line= 3
      2001372.57     13445231.97      2002175.00     13445075.00
      2002974.98     13444625.01
#Sta/Elev= 30
  4183.3  502.79  4297.6  501.17  4398.4  498.36  4399.7  498.33  4420.1  498.82
  4609.5  494.38  4848.1  490.73  4946.1  487.70  4960.2  486.26  4970.1  484.09
  4975.2  485.28  4986.9  482.08  4987.5  481.28  4994.0  481.28  4994.7  482.08
  5008.9  483.53  5014.6  482.91  5030.6  486.14  5036.3  485.18  5046.5  485.58
  5052.3  484.41  5095.6  486.38  5127.2  486.12  5161.6  488.10  5203.1  488.99
  5316.8  490.68  5413.7  490.74  5624.7  494.36  5829.9  501.47  5918.8  503.68
#Mann=8,-1,0
  4183.3     0.1       0  4297.6    0.08       0  4398.4    0.05       0
  4399.7     0.1       0  4946.1    0.16       0  4986.9    0.07       0
  4994.7    0.16       0  5203.1     0.1       0
Bank Sta=4986.9,4994.7
Exp/Cntr=0.3,0.1

Type RM Length L Ch R = 1,31450,362,362,362
BEGIN DESCRIPTION:
Calf Creek 55.0
END DESCRIPTION:
XS GIS Cut Line= 3
      2001492.36     13445617.39      2002239.75     13445307.49
      2003229.37     13444841.34
#Sta/Elev= 30
  4149.0  501.58  4227.6  500.07  4274.5  500.33  4342.3  498.76  4368.4  497.64
  4380.9  498.58  4399.3  498.53  4428.6  496.90  4450.1  496.81  4457.9  497.71
  4476.4  496.84  4552.4  496.06  4595.7  494.58  4718.4  492.31  4742.3  491.20
  4896.8  488.55  4978.1  486.57  4986.0  485.51  4995.3  482.66  4997.0  481.13
  4997.6  480.33  5004.1  480.33  5004.8  481.13  5046.4  485.33  5092.0  485.24
  5151.8  487.39  5228.3  488.25  5273.4  487.80  5536.0  490.95  6052.0  502.96
#Mann=7,-1,0
  4149.0     0.1       0  4342.3    0.05       0  4450.1     0.1       0
  4896.8    0.16       0  4997.0    0.07       0  5004.8    0.16       0
  5228.3     0.1       0
Bank Sta=4997,5004.8
Exp/Cntr=0.3,0.1

Type RM Length L Ch R = 1,31088,48,48,48
BEGIN DESCRIPTION:
Mapping XS f3f2af8c
END DESCRIPTION:
XS GIS Cut Line= 6
      2001757.98     13445708.54      2002198.09     13445580.93
      2002382.98     13445565.31      2002445.48     13445570.51
      2002599.13     13445494.99      2003336.12     13445091.34
#Sta/Elev= 30
  4293.3  496.49  4299.7  497.09  4818.7  487.74  4848.8  491.17  4912.2  479.86
  4945.2  477.84  4945.9  477.04  4953.0  477.84  4988.9  480.14  4997.0  483.23
  5002.9  481.04  5019.8  482.86  5025.4  480.19  5042.3  481.99  5047.9  479.55
  5064.8  481.13  5070.3  478.92  5087.2  480.97  5092.8  478.80  5109.7  480.75
  5121.4  479.68  5123.4  479.87  5154.7  481.12  5160.2  479.23  5226.0  490.75
  5236.2  488.50  5242.1  486.50  5263.9  486.08  5360.1  486.77  6011.3  500.60
#Mann=8,-1,0
  4293.3    0.05       0  4299.7     0.1       0  4912.2    0.12       0
  4945.2    0.07       0  4953.0    0.12       0  5121.4     0.1       0
  5123.4    0.07       0  5236.2     0.1       0
Bank Sta=4945.2,4953
Exp/Cntr=0.3,0.1

Type RM Length L Ch R = 1,31040,36,36,36
BEGIN DESCRIPTION:
Mapping XS 27770e25
END DESCRIPTION:
XS GIS Cut Line= 5
      2001698.10     13445773.64      2002195.48     13445625.20
      2002409.03     13445614.79      2002557.46     13445606.97
      2003398.64     13445114.77
#Sta/Elev= 30
  4207.4  498.54  4274.7  496.05  4291.5  496.83  4548.5  492.95  4572.2  493.46
  4776.0  488.09  4796.1  488.37  4846.1  491.77  4986.1  492.32  5006.3  492.20
  5026.3  490.02  5031.3  492.08  5046.4  491.59  5085.0  488.49  5097.3  488.20
  5103.1  490.92  5118.8  488.93  5124.6  490.28  5140.2  487.89  5161.7  486.47
  5198.9  485.66  5216.5  484.33  5217.1  483.53  5223.6  483.53  5224.3  484.33
  5263.4  485.92  5322.0  485.71  5491.6  488.40  5593.9  491.50  6063.5  501.16
#Mann=6,-1,0
  4207.4    0.05       0  4274.7     0.1       0  4986.1    0.12       0
  5085.0     0.1       0  5216.5    0.07       0  5224.3     0.1       0
Bank Sta=5216.5,5224.3
Exp/Cntr=0.3,0.1

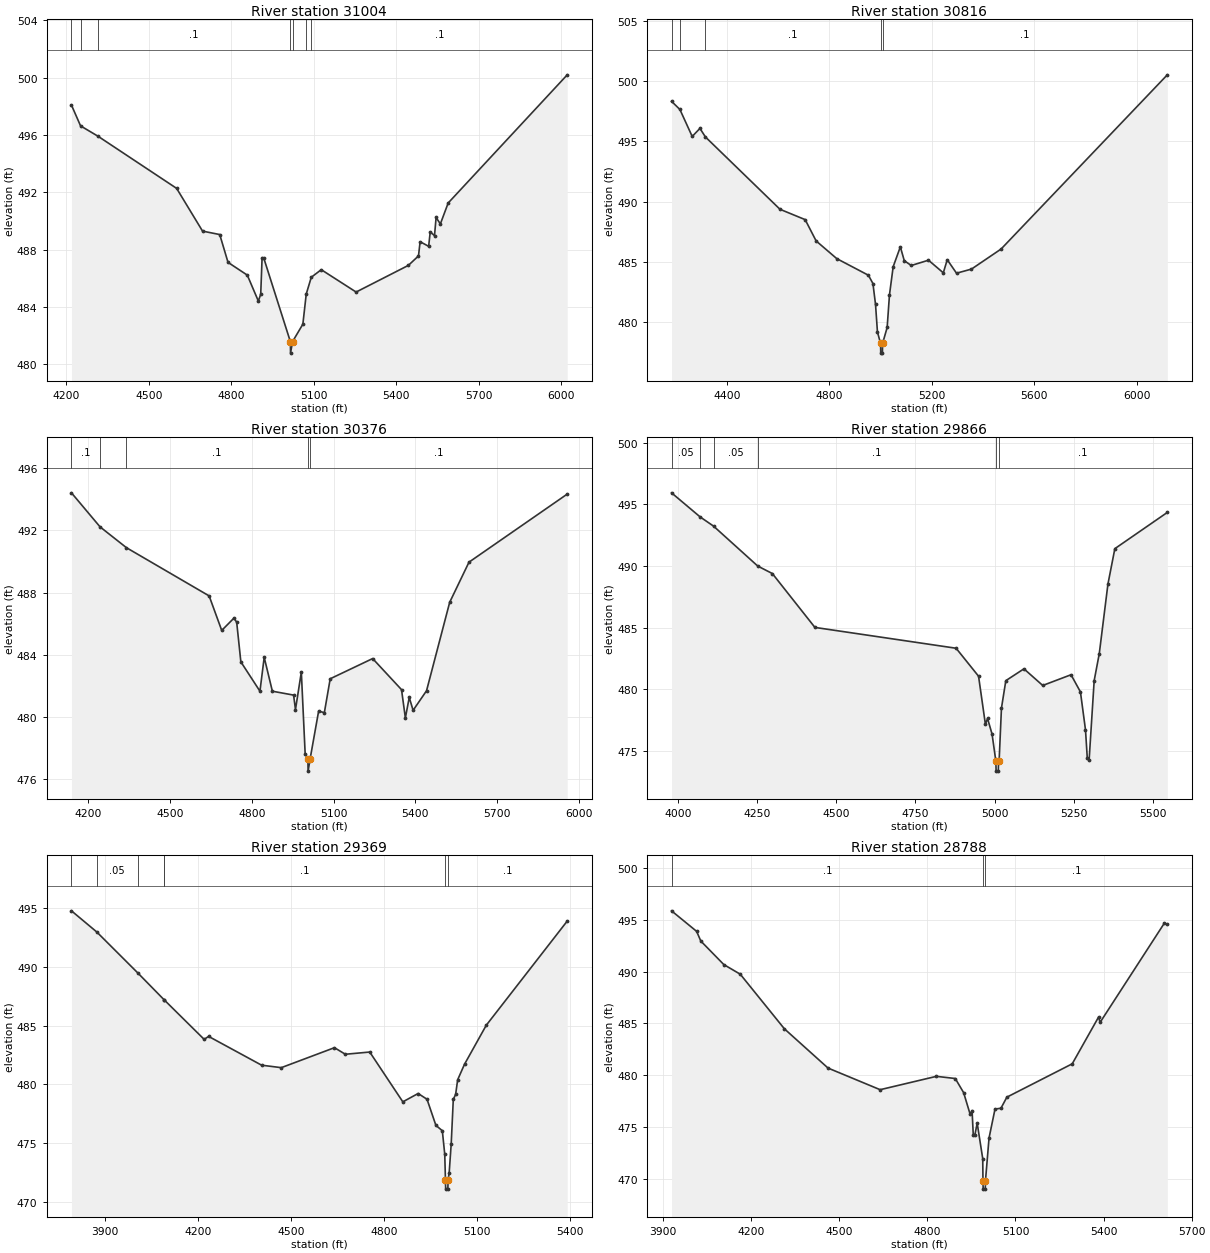
Type RM Length L Ch R = 1,31004,188,188,188
BEGIN DESCRIPTION:
Mapping XS 33a3773c
END DESCRIPTION:
XS GIS Cut Line= 6
      2001729.32     13445817.92      2002239.75     13445661.66
      2002450.69     13445646.04      2002523.61     13445640.83
      2002640.80     13445596.56      2003375.13     13445151.27
#Sta/Elev= 30
  4218.8  498.08  4251.9  496.63  4315.1  495.91  4601.2  492.27  4695.4  489.29
  4757.9  489.05  4788.0  487.11  4858.1  486.22  4898.3  484.41  4906.9  484.89
  4911.9  487.44  4918.3  487.39  5014.7  481.58  5015.3  480.78  5022.5  481.58
  5060.1  482.80  5072.4  484.90  5090.7  486.07  5127.0  486.60  5253.7  485.04
  5443.7  486.90  5480.5  487.56  5486.4  488.55  5517.4  488.23  5523.2  489.24
  5538.7  488.97  5544.5  490.24  5560.0  489.79  5588.4  491.25  6021.3  500.19
#Mann=7,-1,0
  4218.8     0.1       0  4251.9    0.05       0  4315.1     0.1       0
  5014.7    0.07       0  5022.5     0.1       0  5072.4    0.07       0
  5090.7     0.1       0
Bank Sta=5014.7,5022.5
Exp/Cntr=0.3,0.1

Type RM Length L Ch R = 1,30816,440,440,440
BEGIN DESCRIPTION:
Calf Creek 54.0
END DESCRIPTION:
XS GIS Cut Line= 3
      2001724.96     13445925.00      2002525.00     13445825.00
      2003484.08     13445229.66
#Sta/Elev= 30
  4184.1  498.33  4216.8  497.65  4264.8  495.41  4295.0  496.08  4316.3  495.37
  4607.4  489.36  4705.7  488.50  4748.5  486.73  4829.1  485.26  4952.6  483.88
  4970.2  483.19  4980.3  481.46  4987.8  479.17  5000.0  478.21  5000.7  477.41
  5007.2  477.41  5007.8  478.21  5025.7  479.54  5034.7  482.24  5049.2  484.59
  5077.2  486.24  5092.5  485.09  5119.8  484.69  5187.0  485.13  5244.9  484.08
  5260.2  485.17  5296.4  484.05  5354.7  484.39  5470.5  486.06  6119.2  500.53
#Mann=5,-1,0
  4184.1     0.1       0  4216.8    0.08       0  4316.3     0.1       0
  5000.0    0.07       0  5007.8     0.1       0
Bank Sta=5000,5007.8
Exp/Cntr=0.3,0.1

Type RM Length L Ch R = 1,30376,510,510,510
BEGIN DESCRIPTION:
Calf Creek 53.0
END DESCRIPTION:
XS GIS Cut Line= 3
      2001804.83     13446419.48      2002539.23     13446312.70
      2003324.99     13445575.01
#Sta/Elev= 30
  4137.8  494.42  4242.8  492.23  4339.8  490.89  4643.2  487.79  4689.4  485.57
  4734.2  486.36  4744.3  486.10  4759.6  483.55  4829.7  481.66  4845.3  483.84
  4875.3  481.66  4953.2  481.41  4960.1  480.48  4981.6  482.89  4995.7  477.62
  5005.7  477.32  5006.4  476.52  5014.0  477.32  5045.1  480.38  5066.1  480.28
  5087.6  482.46  5243.4  483.76  5349.4  481.76  5363.5  479.94  5377.7  481.26
  5391.9  480.43  5441.2  481.69  5526.2  487.38  5597.0  489.96  5957.7  494.34
#Mann=5,-1,0
  4137.8     0.1       0  4242.8    0.05       0  4339.8     0.1       0
  5005.7    0.07       0  5014.0     0.1       0
Bank Sta=5005.7,5014
Exp/Cntr=0.3,0.1

Type RM Length L Ch R = 1,29866,497,497,497
BEGIN DESCRIPTION:
Calf Creek 52.0
END DESCRIPTION:
XS GIS Cut Line= 3
      2002307.45     13447057.51      2003002.78     13446297.08
      2003262.74     13445829.15
#Sta/Elev= 30
  3979.7  495.93  4070.3  493.97  4112.3  493.23  4251.9  489.99  4298.1  489.38
  4432.5  485.01  4878.4  483.32  4949.3  481.05  4970.9  477.15  4977.7  477.62
  4991.9  476.36  5004.0  474.15  5004.7  473.35  5011.6  473.35  5012.3  474.15
  5014.2  474.15  5021.6  478.46  5035.4  480.69  5092.6  481.65  5152.0  480.30
  5241.3  481.17  5271.0  479.78  5287.0  476.70  5292.7  474.38  5298.5  474.27
  5314.4  480.69  5330.5  482.88  5357.9  488.53  5379.7  491.40  5545.4  494.34
#Mann=6,-1,0
  3979.7    0.05       0  4070.3     0.1       0  4112.3    0.05       0
  4251.9     0.1       0  5004.0    0.07       0  5012.3     0.1       0
Bank Sta=5004,5012.3
Exp/Cntr=0.3,0.1

Type RM Length L Ch R = 1,29369,581,581,581
BEGIN DESCRIPTION:
Calf Creek 51.0
END DESCRIPTION:
XS GIS Cut Line= 3
      2002617.34     13447338.77      2003257.98     13446518.43
      2003687.12     13446159.52
#Sta/Elev= 30
  3791.1  494.78  3872.8  492.98  4004.6  489.51  4090.4  487.20  4090.5  487.20
  4219.4  483.84  4233.9  484.09  4404.9  481.64  4468.4  481.43  4640.0  483.13
  4675.2  482.57  4753.9  482.76  4860.7  478.52  4910.1  479.23  4938.8  478.74
  4967.4  476.52  4988.2  476.06  4996.0  474.06  4998.3  471.89  4999.0  471.09
  5006.0  471.09  5006.8  471.89  5010.3  472.48  5016.8  474.92  5023.6  478.73
  5031.1  479.15  5037.7  480.40  5059.8  481.72  5130.0  485.04  5391.4  493.91
#Mann=7,-1,0
  3791.1     0.1       0  3872.8    0.05       0  4004.6     0.1       0
  4090.4    0.05       0  4090.5     0.1       0  4998.3    0.07       0
  5006.8     0.1       0
Bank Sta=4998.3,5006.8
Exp/Cntr=0.3,0.1

Type RM Length L Ch R = 1,28788,503,503,503
BEGIN DESCRIPTION:
Calf Creek 50.0
END DESCRIPTION:
XS GIS Cut Line= 3
      2002875.03     13447524.97      2003675.00     13446875.00
      2003775.00     13446224.98
#Sta/Elev= 30
  3928.7  495.86  4014.1  493.88  4028.5  492.94  4106.8  490.67  4162.8  489.74
  4313.0  484.47  4461.6  480.68  4639.1  478.59  4830.8  479.88  4895.0  479.67
  4923.5  478.30  4945.8  476.20  4952.2  476.57  4956.2  474.26  4962.0  474.26
  4969.6  475.36  4988.5  471.93  4989.3  469.79  4990.1  468.99  4997.1  468.99
  4997.8  469.79  5010.0  473.93  5030.3  476.72  5050.5  476.80  5070.7  477.87
  5293.3  481.09  5383.1  485.61  5388.2  485.09  5607.0  494.67  5617.1  494.54
#Mann=3,-1,0
  3928.7     0.1       0  4989.3    0.07       0  4997.8     0.1       0
Bank Sta=4989.3,4997.8
Exp/Cntr=0.3,0.1

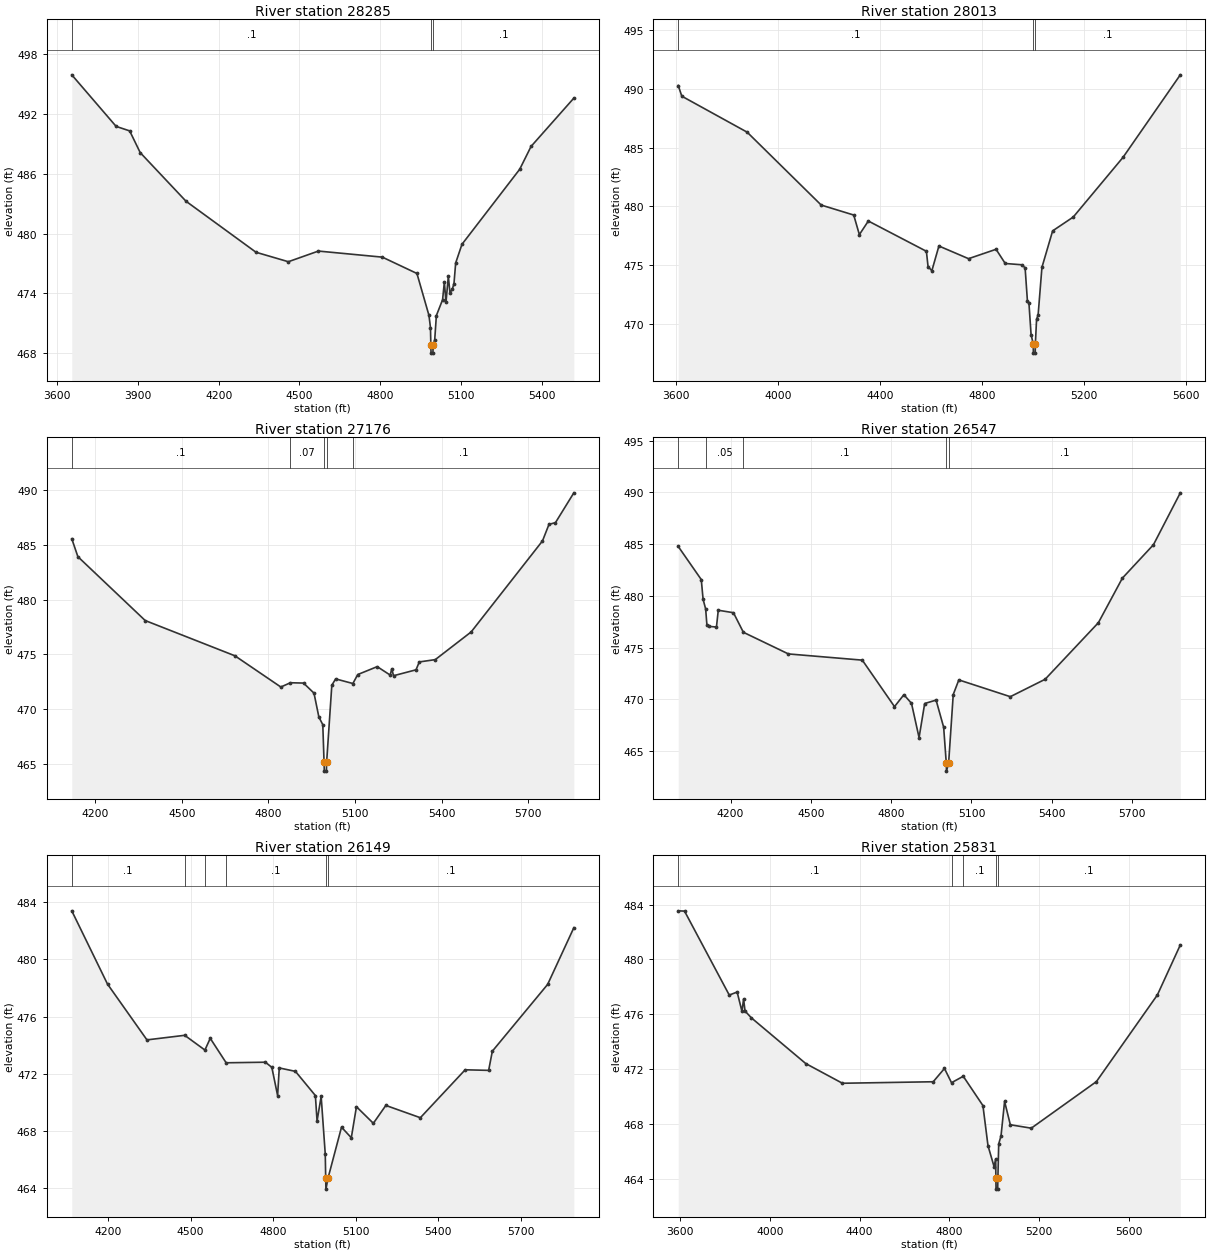
Type RM Length L Ch R = 1,28285,272,272,272
BEGIN DESCRIPTION:
Calf Creek 49.0
END DESCRIPTION:
XS GIS Cut Line= 3
      2002925.03     13447574.98      2004125.00     13446975.00
      2004424.63     13446544.51
#Sta/Elev= 30
  3653.9  495.94  3818.8  490.76  3869.1  490.31  3908.2  488.13  4078.7  483.24
  4338.7  478.12  4458.8  477.17  4570.6  478.24  4808.2  477.63  4936.8  475.99
  4981.5  471.78  4987.1  470.55  4988.5  468.79  4989.2  467.99  4996.2  467.99
  4997.0  468.79  5002.9  469.32  5009.0  471.76  5032.1  473.35  5038.7  475.12
  5044.8  473.12  5053.5  475.70  5059.6  474.04  5068.4  474.42  5074.5  474.98
  5080.8  477.05  5104.2  478.92  5318.9  486.46  5361.0  488.75  5520.0  493.60
#Mann=3,-1,0
  3653.9     0.1       0  4988.5    0.07       0  4997.0     0.1       0
Bank Sta=4988.5,4997
Exp/Cntr=0.3,0.1

Type RM Length L Ch R = 1,28013,837,837,837
BEGIN DESCRIPTION:
Calf Creek 48.0
END DESCRIPTION:
XS GIS Cut Line= 3
      2003273.60     13448153.86      2003901.21     13447398.64
      2004720.73     13446847.09
#Sta/Elev= 30
  3608.7  490.29  3622.7  489.38  3879.2  486.31  4169.6  480.10  4297.2  479.25
  4319.3  477.58  4354.5  478.74  4582.3  476.16  4588.8  474.86  4603.7  474.50
  4631.4  476.61  4747.7  475.53  4855.6  476.33  4891.6  475.12  4956.8  475.01
  4969.6  474.75  4978.6  471.95  4984.6  471.75  4993.0  469.06  5001.4  468.28
  5002.1  467.48  5009.1  467.48  5009.9  468.28  5014.6  470.37  5020.6  470.72
  5035.6  474.79  5077.6  477.90  5158.5  479.08  5353.5  484.16  5578.5  491.20
#Mann=3,-1,0
  3608.7     0.1       0  5001.4    0.07       0  5009.9     0.1       0
Bank Sta=5001.4,5009.9
Exp/Cntr=0.3,0.1

Type RM Length L Ch R = 1,27176,629,629,629
BEGIN DESCRIPTION:
Calf Creek 47.0
END DESCRIPTION:
XS GIS Cut Line= 3
      2003925.00     13448375.00      2004450.69     13447875.20
      2004898.59     13446963.78
#Sta/Elev= 30
  4117.9  485.56  4139.1  483.92  4372.5  478.09  4683.6  474.87  4842.8  472.02
  4876.1  472.41  4921.5  472.38  4957.8  471.46  4974.7  469.28  4988.3  468.58
  4992.7  465.14  4993.6  464.34  5000.8  464.34  5001.6  465.14  5019.6  472.18
  5032.9  472.76  5092.6  472.34  5109.6  473.16  5177.0  473.88  5222.0  473.11
  5227.5  473.69  5233.5  473.05  5311.5  473.59  5323.0  474.31  5378.3  474.52
  5502.8  477.05  5750.1  485.36  5772.6  486.87  5795.1  487.03  5858.8  489.75
#Mann=5,-1,0
  4117.9     0.1       0  4876.1    0.07       0  4992.7    0.07       0
  5001.6    0.07       0  5092.6     0.1       0
Bank Sta=4992.7,5001.6
Exp/Cntr=0.3,0.1

Type RM Length L Ch R = 1,26547,398,398,398
BEGIN DESCRIPTION:
Calf Creek 46.0
END DESCRIPTION:
XS GIS Cut Line= 3
      2004187.64     13448599.19      2005054.86     13447802.29
      2005225.00     13447125.00
#Sta/Elev= 30
  4004.3  484.77  4090.4  481.57  4097.2  479.66  4106.8  478.73  4111.4  477.20
  4118.7  477.05  4147.1  476.99  4153.9  478.61  4210.6  478.37  4247.7  476.48
  4415.9  474.39  4692.1  473.79  4812.4  469.30  4847.5  470.45  4875.9  469.62
  4904.2  466.31  4925.2  469.60  4967.8  469.93  4996.1  467.31  5005.8  463.87
  5006.7  463.07  5014.7  463.87  5031.9  470.47  5052.8  471.88  5245.2  470.26
  5375.2  471.94  5574.4  477.41  5663.9  481.71  5780.1  484.94  5880.4  489.95
#Mann=5,-1,0
  4004.3     0.1       0  4106.8    0.05       0  4247.7     0.1       0
  5005.8    0.07       0  5014.7     0.1       0
Bank Sta=5005.8,5014.7
Exp/Cntr=0.3,0.1

Type RM Length L Ch R = 1,26149,318,318,318
BEGIN DESCRIPTION:
Calf Creek 45.0
END DESCRIPTION:
XS GIS Cut Line= 3
      2004324.98     13448775.01      2005125.00     13448225.00
      2005424.98     13447425.04
#Sta/Elev= 30
  4067.8  483.39  4197.7  478.27  4341.1  474.37  4478.3  474.69  4551.8  473.66
  4571.2  474.48  4629.0  472.77  4771.7  472.81  4795.1  472.45  4816.1  470.48
  4822.1  472.41  4880.9  472.17  4953.4  470.48  4959.5  468.70  4974.4  470.42
  4989.3  466.39  4990.9  464.74  4991.7  463.94  4999.8  464.74  5048.4  468.27
  5084.0  467.53  5102.7  469.70  5164.1  468.54  5209.5  469.79  5335.0  468.93
  5497.9  472.28  5583.3  472.24  5596.7  473.58  5797.8  478.25  5893.0  482.21
#Mann=6,-1,0
  4067.8     0.1       0  4478.3    0.05       0  4551.8    0.08       0
  4629.0     0.1       0  4990.9    0.07       0  4999.8     0.1       0
Bank Sta=4990.9,4999.8
Exp/Cntr=0.3,0.1

Type RM Length L Ch R = 1,25831,575,575,575
BEGIN DESCRIPTION:
Calf Creek 44.0
END DESCRIPTION:
XS GIS Cut Line= 3
      2004475.01     13449374.98      2005333.50     13448325.72
      2005567.87     13447474.20
#Sta/Elev= 30
  3591.2  483.55  3619.2  483.53  3818.7  477.40  3853.9  477.62  3875.4  476.21
  3882.6  477.11  3889.1  476.23  3917.8  475.73  4159.7  472.40  4323.3  470.96
  4728.2  471.07  4778.4  472.04  4809.8  471.00  4862.2  471.47  4949.9  469.33
  4972.5  466.40  4999.5  464.88  5006.9  465.44  5007.6  464.03  5008.4  463.23
  5015.7  463.23  5016.6  464.03  5020.3  466.53  5030.6  467.12  5046.5  469.63
  5072.1  467.93  5165.5  467.68  5455.9  471.08  5727.9  477.41  5830.1  481.06
#Mann=5,-1,0
  3591.2     0.1       0  4809.8    0.05       0  4862.2     0.1       0
  5007.6    0.07       0  5016.6     0.1       0
Bank Sta=5007.6,5016.6
Exp/Cntr=0.3,0.1