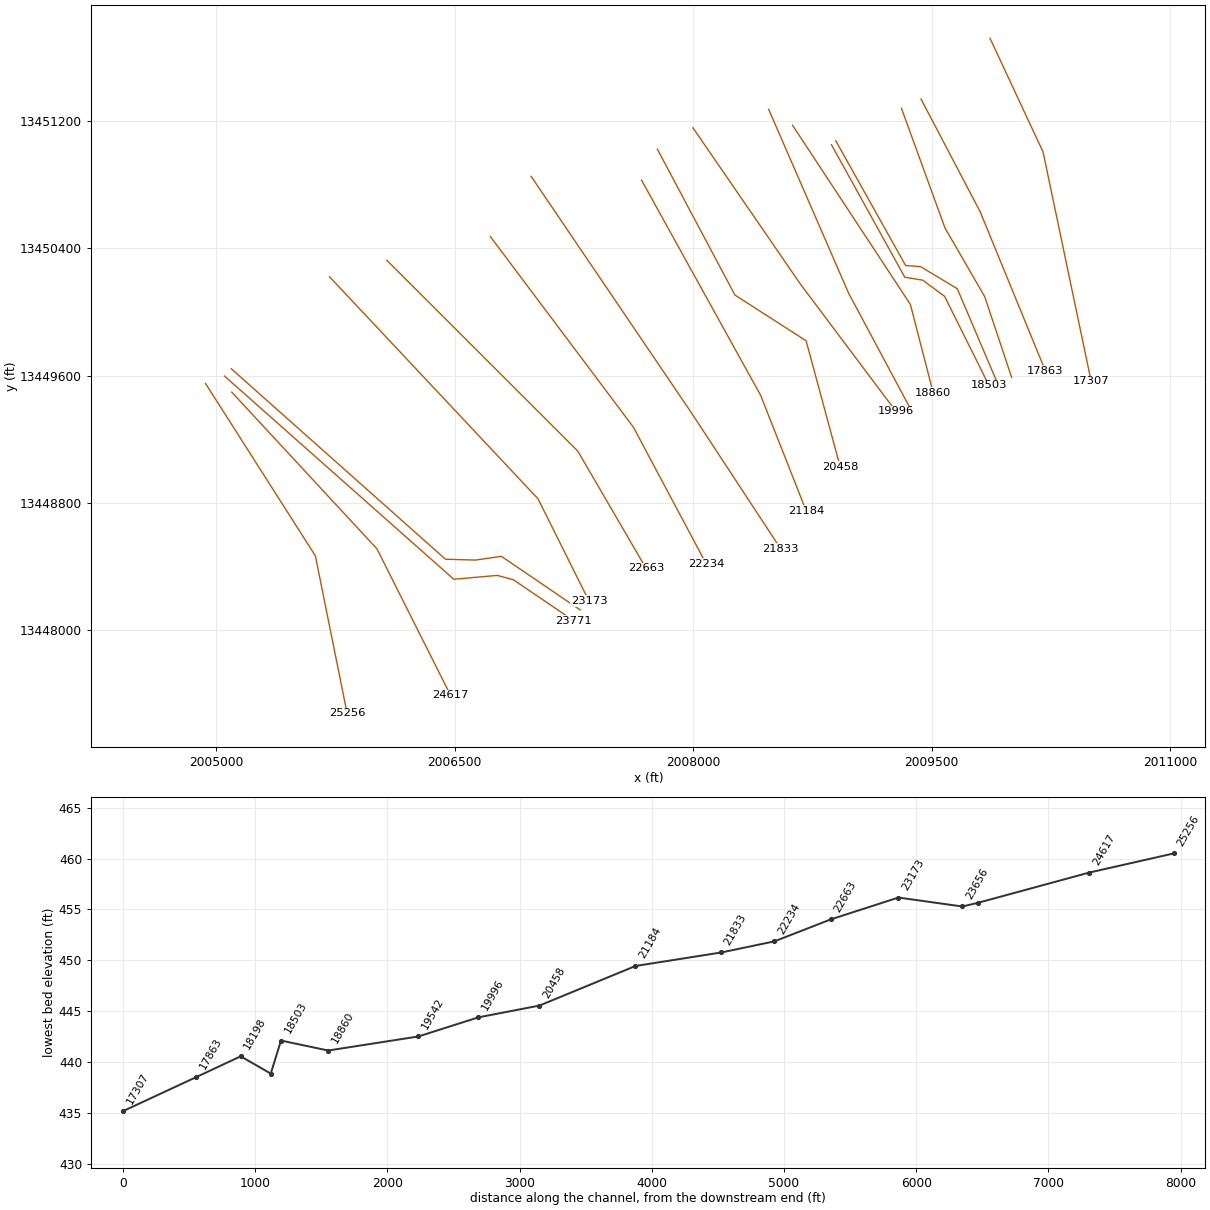
HEC-RAS study Calf Creek.prj: Calf Creek Base Level Engineering

--- Calf Creek.g01 (geometry) --- (continued)

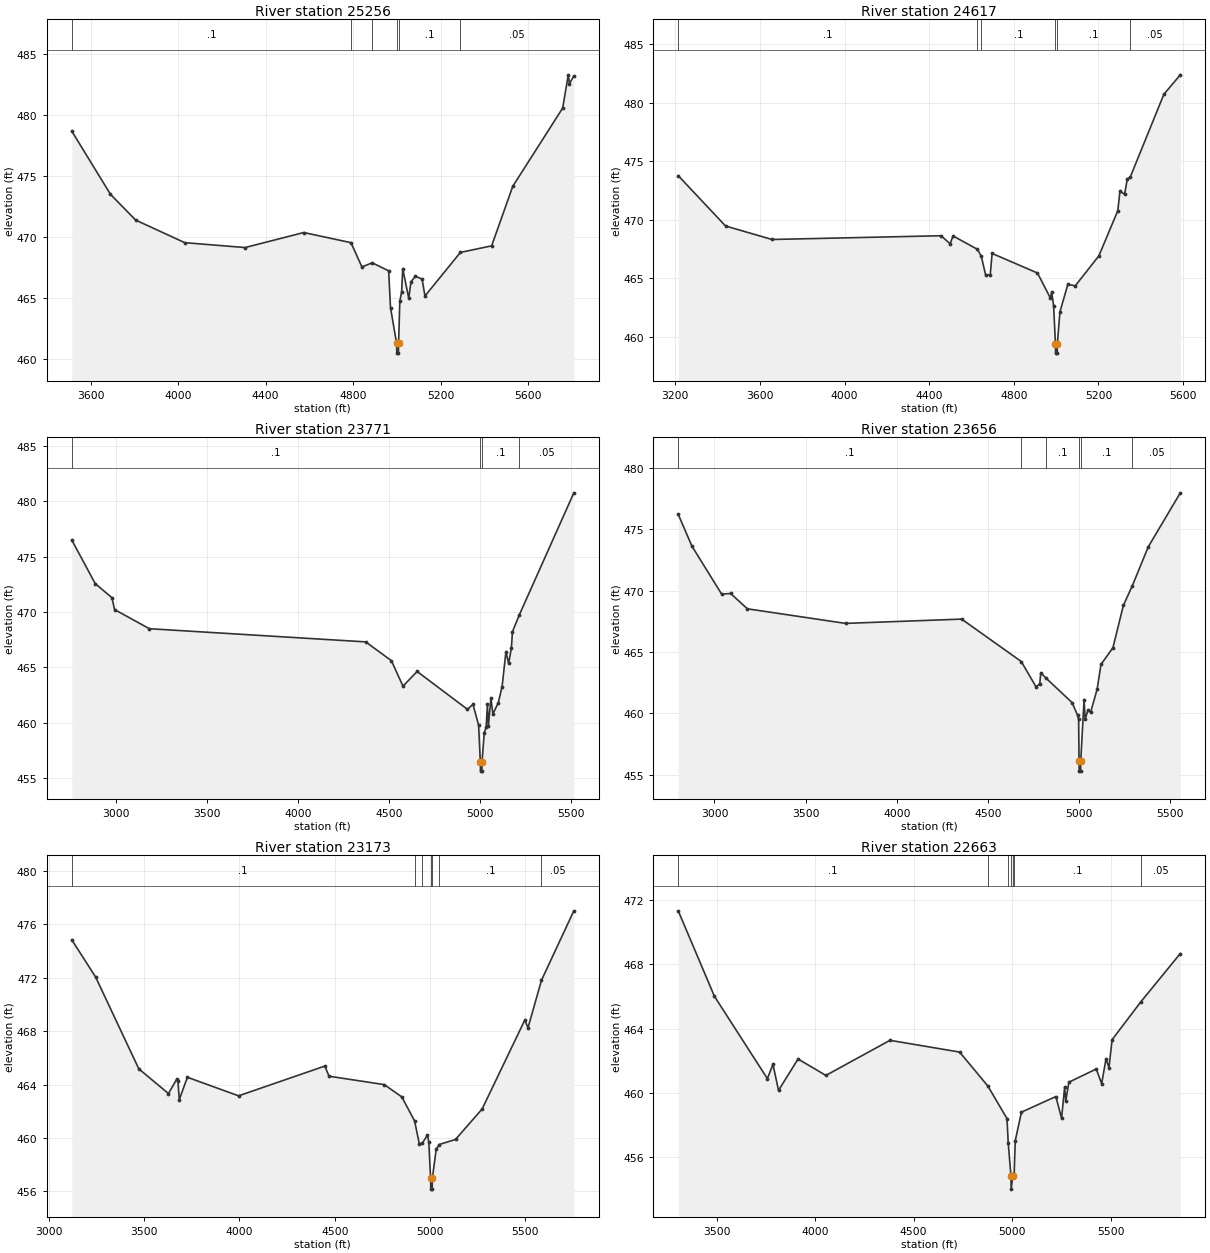
Type RM Length L Ch R = 1,25256,639,639,639
BEGIN DESCRIPTION:
Calf Creek 43.0
END DESCRIPTION:
XS GIS Cut Line= 3
      2004935.09     13449549.64      2005625.17     13448466.35
      2005825.00     13447475.01
#Sta/Elev= 30
  3514.0  478.70  3691.0  473.52  3806.2  471.41  4030.5  469.56  4306.4  469.16
  4574.7  470.39  4790.7  469.56  4840.6  467.57  4887.7  467.91  4963.0  467.25
  4971.4  464.24  4999.3  461.31  5000.1  460.51  5007.5  460.51  5008.4  461.31
  5014.0  464.77  5022.2  465.51  5027.3  467.43  5054.8  465.00  5065.0  466.36
  5085.4  466.81  5116.0  466.57  5128.9  465.19  5290.9  468.76  5433.8  469.30
  5530.3  474.17  5758.7  480.59  5784.3  483.31  5789.4  482.59  5809.7  483.21
#Mann=6,-1,0
  3514.0     0.1       0  4790.7    0.05       0  4887.7     0.1       0
  4999.3    0.07       0  5008.4     0.1       0  5290.9    0.05       0
Bank Sta=4999.3,5008.4
Exp/Cntr=0.3,0.1

Type RM Length L Ch R = 1,24617,846,846,846
BEGIN DESCRIPTION:
Mapping XS 3611166e
END DESCRIPTION:
XS GIS Cut Line= 3
      2005099.56     13449495.86      2006012.76     13448509.75
      2006474.46     13447589.82
#Sta/Elev= 30
  3213.8  473.76  3437.5  469.47  3657.0  468.32  4456.4  468.64  4498.9  467.95
  4513.1  468.62  4628.4  467.48  4646.7  466.87  4666.3  465.33  4688.6  465.29
  4697.4  467.13  4912.0  465.46  4973.4  463.31  4979.0  463.85  4988.3  462.65
  4996.8  459.43  4997.6  458.63  5005.0  458.63  5005.9  459.43  5018.0  462.14
  5055.4  464.49  5090.6  464.37  5202.3  466.93  5291.7  470.78  5301.6  472.43
  5324.0  472.18  5336.3  473.47  5350.6  473.65  5509.4  480.70  5587.1  482.36
#Mann=6,-1,0
  3213.8     0.1       0  4628.4    0.05       0  4646.7     0.1       0
  4996.8    0.07       0  5005.9     0.1       0  5350.6    0.05       0
Bank Sta=4996.8,5005.9
Exp/Cntr=0.3,0.1

Type RM Length L Ch R = 1,23771,115,115,115
BEGIN DESCRIPTION:
Mapping XS e4cfa2fb
END DESCRIPTION:
XS GIS Cut Line= 5
      2005054.44     13449596.54      2006495.40     13448318.78
      2006769.70     13448343.08      2006870.40     13448315.31
      2007247.65     13448059.19
#Sta/Elev= 30
  2756.1  476.51  2885.2  472.57  2977.2  471.30  2991.4  470.23  3182.9  468.50
  4373.0  467.31  4514.4  465.61  4577.9  463.31  4655.7  464.64  4932.6  461.22
  4962.9  461.67  4994.0  459.79  5003.5  456.44  5004.4  455.64  5011.8  455.64
  5012.6  456.44  5025.1  459.12  5035.5  459.59  5042.4  461.66  5047.6  459.71
  5061.6  462.23  5072.4  460.80  5102.2  461.81  5123.2  463.28  5144.2  466.41
  5159.2  465.39  5174.1  466.73  5180.2  468.23  5217.4  469.73  5517.8  480.77
#Mann=4,-1,0
  2756.1     0.1       0  5003.5    0.07       0  5012.6     0.1       0
  5217.4    0.05       0
Bank Sta=5003.5,5012.6
Exp/Cntr=0.3,0.1

Type RM Length L Ch R = 1,23656,483,483,483
BEGIN DESCRIPTION:
Calf Creek 42.0
END DESCRIPTION:
XS GIS Cut Line= 5
      2005096.95     13449642.57      2006443.31     13448444.65
      2006630.81     13448439.44      2006794.88     13448462.88
      2007290.51     13448125.52
#Sta/Elev= 30
  2801.1  476.24  2876.2  473.64  3039.2  469.73  3088.5  469.78  3180.5  468.53
  3719.0  467.34  4356.2  467.69  4683.5  464.23  4765.0  462.15  4785.0  462.43
  4790.4  463.31  4816.9  462.91  4962.2  460.88  4992.1  459.86  4998.1  459.52
  5000.5  456.09  5001.4  455.29  5008.8  455.29  5009.6  456.09  5028.0  461.12
  5034.0  459.51  5049.0  460.26  5063.9  460.08  5099.8  461.98  5120.8  463.99
  5186.5  465.36  5243.5  468.80  5292.8  470.41  5380.1  473.58  5556.1  477.99
#Mann=6,-1,0
  2801.1     0.1       0  4683.5    0.05       0  4816.9     0.1       0
  5000.5    0.07       0  5009.6     0.1       0  5292.8    0.05       0
Bank Sta=5000.5,5009.6
Exp/Cntr=0.3,0.1

Type RM Length L Ch R = 1,23173,510,510,510
BEGIN DESCRIPTION:
Calf Creek 41.0
END DESCRIPTION:
XS GIS Cut Line= 3
      2005714.16     13450221.54      2007025.00     13448825.00
      2007345.65     13448181.64
#Sta/Elev= 30
  3120.0  474.85  3245.5  472.05  3471.8  465.18  3627.4  463.33  3669.9  464.39
  3677.2  464.25  3684.1  462.88  3726.6  464.55  3995.2  463.16  4448.0  465.39
  4469.5  464.63  4759.6  464.00  4851.5  463.08  4918.6  461.28  4943.3  459.58
  4958.8  459.61  4985.8  460.21  4993.1  459.72  5002.7  456.97  5003.6  456.17
  5011.0  456.17  5011.9  456.97  5031.9  459.15  5047.4  459.51  5133.3  459.89
  5273.2  462.18  5497.0  468.84  5513.8  468.26  5584.4  471.82  5754.2  477.02
#Mann=7,-1,0
  3120.0     0.1       0  4918.6    0.05       0  4958.8    0.12       0
  5002.7    0.07       0  5011.9    0.12       0  5047.4     0.1       0
  5584.4    0.05       0
Bank Sta=5002.7,5011.9
Exp/Cntr=0.3,0.1

Type RM Length L Ch R = 1,22663,429,429,429
BEGIN DESCRIPTION:
Calf Creek 40.0
END DESCRIPTION:
XS GIS Cut Line= 3
      2006075.01     13450324.99      2007275.00     13449125.00
      2007703.24     13448389.07
#Sta/Elev= 30
  3305.6  471.31  3489.4  466.00  3758.1  460.89  3786.4  461.78  3814.7  460.16
  3913.7  462.11  4055.1  461.09  4380.4  463.27  4733.9  462.54  4877.3  460.43
  4974.4  458.41  4980.5  456.92  4994.5  454.83  4995.4  454.03  5003.7  454.83
  5010.8  454.99  5016.3  457.04  5047.7  458.81  5222.5  459.78  5251.3  458.43
  5267.0  460.36  5272.8  459.52  5288.5  460.67  5427.5  461.49  5454.8  460.58
  5477.0  462.12  5492.1  461.58  5507.8  463.31  5653.1  465.65  5854.1  468.66
#Mann=7,-1,0
  3305.6     0.1       0  4877.3    0.05       0  4980.5    0.12       0
  4994.5    0.07       0  5003.7    0.12       0  5010.8     0.1       0
  5653.1    0.05       0
Bank Sta=4994.5,5003.7
Exp/Cntr=0.3,0.1

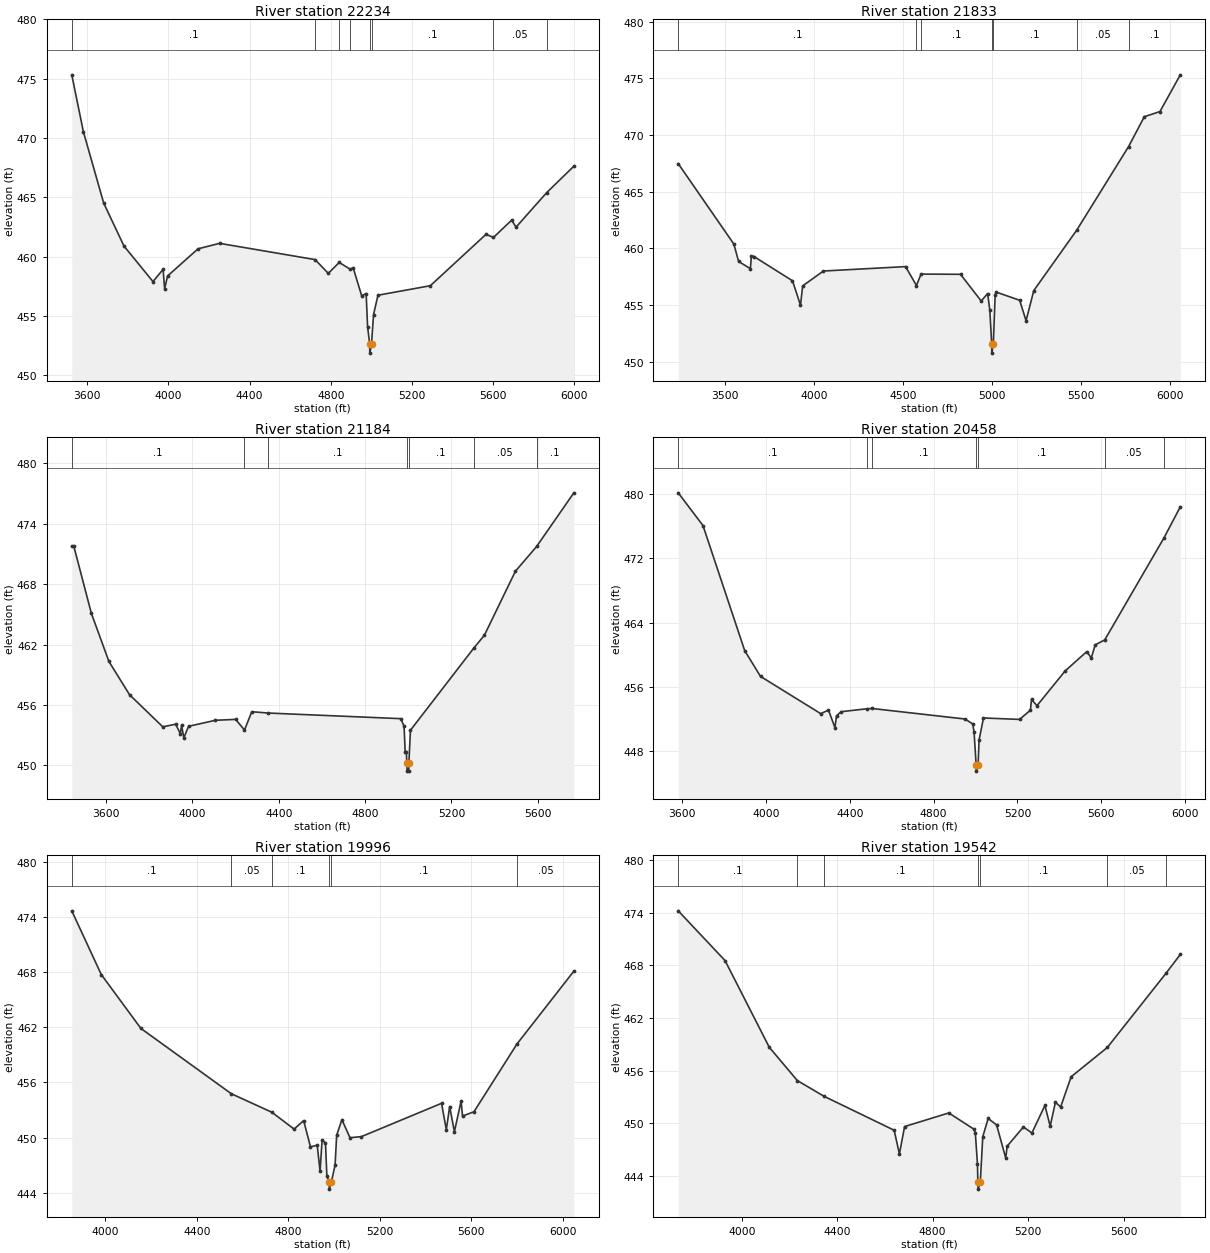
Type RM Length L Ch R = 1,22234,401,401,401
BEGIN DESCRIPTION:
Calf Creek 39.0
END DESCRIPTION:
XS GIS Cut Line= 3
      2006724.99     13450475.02      2007625.00     13449275.00
      2008082.19     13448416.02
#Sta/Elev= 30
  3524.4  475.31  3581.7  470.51  3681.7  464.50  3781.7  460.88  3924.4  457.89
  3974.4  458.92  3981.7  457.28  3996.3  458.36  4146.3  460.65  4252.5  461.11
  4723.1  459.74  4788.0  458.58  4841.6  459.50  4894.1  458.95  4910.9  459.02
  4952.5  456.69  4974.4  456.88  4981.7  454.05  4991.7  452.66  4992.5  451.86
  5000.9  452.66  5010.9  455.11  5032.6  456.74  5290.6  457.54  5564.8  461.87
  5601.5  461.61  5691.0  463.06  5713.0  462.48  5863.5  465.38  5997.5  467.61
#Mann=8,-1,0
  3524.4     0.1       0  4723.1    0.05       0  4841.6    0.12       0
  4894.1     0.1       0  4991.7    0.07       0  5000.9     0.1       0
  5601.5    0.05       0  5863.5     0.1       0
Bank Sta=4991.7,5000.9
Exp/Cntr=0.3,0.1

Type RM Length L Ch R = 1,21833,649,649,649
BEGIN DESCRIPTION:
Calf Creek 38.0
END DESCRIPTION:
XS GIS Cut Line= 3
      2006981.52     13450853.48      2007988.45     13449367.39
      2008550.38     13448510.62
#Sta/Elev= 30
  3237.7  467.48  3549.9  460.39  3576.9  458.85  3642.8  458.22  3648.8  459.36
  3663.8  459.28  3879.4  457.15  3924.3  455.00  3936.5  456.70  4053.1  458.01
  4514.4  458.40  4575.5  456.73  4601.5  457.74  4823.0  457.72  4939.0  455.37
  4975.3  456.02  4987.7  454.54  4998.1  451.57  4998.9  450.77  5007.3  451.57
  5017.6  455.92  5023.7  456.15  5155.2  455.43  5191.1  453.63  5234.6  456.29
  5476.0  461.62  5767.1  468.99  5855.5  471.62  5942.9  472.07  6057.4  475.31
#Mann=7,-1,0
  3237.7     0.1       0  4575.5    0.05       0  4601.5     0.1       0
  4998.1    0.07       0  5007.3     0.1       0  5476.0    0.05       0
  5767.1     0.1       0
Bank Sta=4998.1,5007.3
Exp/Cntr=0.3,0.1

Type RM Length L Ch R = 1,21184,726,726,726
BEGIN DESCRIPTION:
Calf Creek 37.0
END DESCRIPTION:
XS GIS Cut Line= 3
      2007675.95     13450829.20      2008425.00     13449475.00
      2008710.19     13448750.57
#Sta/Elev= 30
  3441.2  471.75  3450.6  471.78  3532.0  465.11  3613.3  460.33  3708.8  457.03
  3862.9  453.84  3922.5  454.10  3944.3  453.16  3950.0  454.01  3960.3  452.73
  3982.1  453.89  4106.9  454.49  4200.2  454.58  4241.4  453.52  4275.2  455.34
  4350.6  455.21  4965.9  454.65  4980.7  453.89  4985.9  451.32  4991.4  451.32
  4993.6  450.24  4994.5  449.44  5002.1  449.44  5003.0  450.24  5010.3  453.50
  5302.7  461.63  5353.0  462.94  5496.5  469.29  5594.8  471.75  5767.3  477.08
#Mann=7,-1,0
  3441.2     0.1       0  4241.4    0.08       0  4350.6     0.1       0
  4993.6    0.07       0  5003.0     0.1       0  5302.7    0.05       0
  5594.8     0.1       0
Bank Sta=4993.6,5003
Exp/Cntr=0.3,0.1

Type RM Length L Ch R = 1,20458,462,462,462
BEGIN DESCRIPTION:
Calf Creek 36.0
END DESCRIPTION:
XS GIS Cut Line= 4
      2007775.02     13451024.96      2008262.76     13450106.97
      2008710.68     13449818.78      2008924.99     13449025.04
#Sta/Elev= 30
  3582.3  480.16  3700.3  476.09  3899.3  460.53  3974.7  457.33  4261.7  452.70
  4298.8  453.14  4329.6  450.96  4337.1  452.43  4359.1  452.94  4480.4  453.30
  4507.1  453.34  4950.2  452.03  4986.5  451.42  4993.1  450.41  5002.9  446.35
  5003.8  445.55  5012.3  446.35  5016.9  449.42  5038.0  452.16  5210.1  451.98
  5261.8  453.13  5267.0  454.46  5293.0  453.69  5427.7  458.02  5530.8  460.42
  5552.0  459.62  5570.7  461.25  5616.2  461.87  5897.9  474.52  5976.6  478.42
#Mann=7,-1,0
  3582.3     0.1       0  4480.4    0.05       0  4507.1     0.1       0
  5002.9    0.07       0  5012.3     0.1       0  5616.2    0.05       0
  5897.9     0.1       0
Bank Sta=5002.9,5012.3
Exp/Cntr=0.3,0.1

Type RM Length L Ch R = 1,19996,454,454,454
BEGIN DESCRIPTION:
Calf Creek 35.0
END DESCRIPTION:
XS GIS Cut Line= 3
      2007998.86     13451159.07      2008675.00     13450175.00
      2009275.02     13449374.98
#Sta/Elev= 30
  3854.0  474.65  3983.0  467.72  4156.2  461.86  4551.4  454.76  4728.3  452.75
  4825.4  450.92  4867.3  451.84  4897.1  448.99  4926.6  449.16  4939.0  446.35
  4947.8  449.71  4962.7  449.43  4968.8  445.81  4978.6  445.19  4979.6  444.39
  4988.8  445.19  5004.7  447.03  5011.6  450.26  5034.5  451.94  5069.8  449.98
  5119.8  450.10  5469.8  453.72  5490.7  450.85  5505.3  453.36  5526.1  450.64
  5555.3  453.97  5561.5  452.34  5611.5  452.80  5799.7  460.18  6048.0  468.09
#Mann=6,-1,0
  3854.0     0.1       0  4551.4    0.05       0  4728.3     0.1       0
  4978.6    0.07       0  4988.8     0.1       0  5799.7    0.05       0
Bank Sta=4978.6,4988.8
Exp/Cntr=0.3,0.1

Type RM Length L Ch R = 1,19542,682,682,682
BEGIN DESCRIPTION:
Calf Creek 34.0
END DESCRIPTION:
XS GIS Cut Line= 3
      2008475.01     13451274.97      2008978.04     13450117.39
      2009375.00     13449375.01
#Sta/Elev= 30
  3733.7  474.22  3929.9  468.55  4115.3  458.67  4232.8  454.88  4346.0  453.07
  4638.6  449.22  4660.5  446.52  4682.3  449.64  4867.6  451.19  4973.4  449.33
  4978.9  448.85  4987.6  445.37  4989.3  443.31  4990.3  442.51  4999.5  443.31
  5009.9  448.49  5032.6  450.56  5068.0  449.82  5106.2  446.04  5112.0  447.40
  5180.0  449.59  5215.9  448.91  5270.4  452.05  5292.3  449.68  5314.3  452.41
  5336.2  451.87  5380.1  455.31  5531.8  458.65  5778.2  467.12  5837.7  469.25
#Mann=7,-1,0
  3733.7     0.1       0  4232.8    0.05       0  4346.0     0.1       0
  4989.3    0.07       0  4999.5     0.1       0  5531.8    0.05       0
  5778.2     0.1       0
Bank Sta=4989.3,4999.5
Exp/Cntr=0.3,0.1

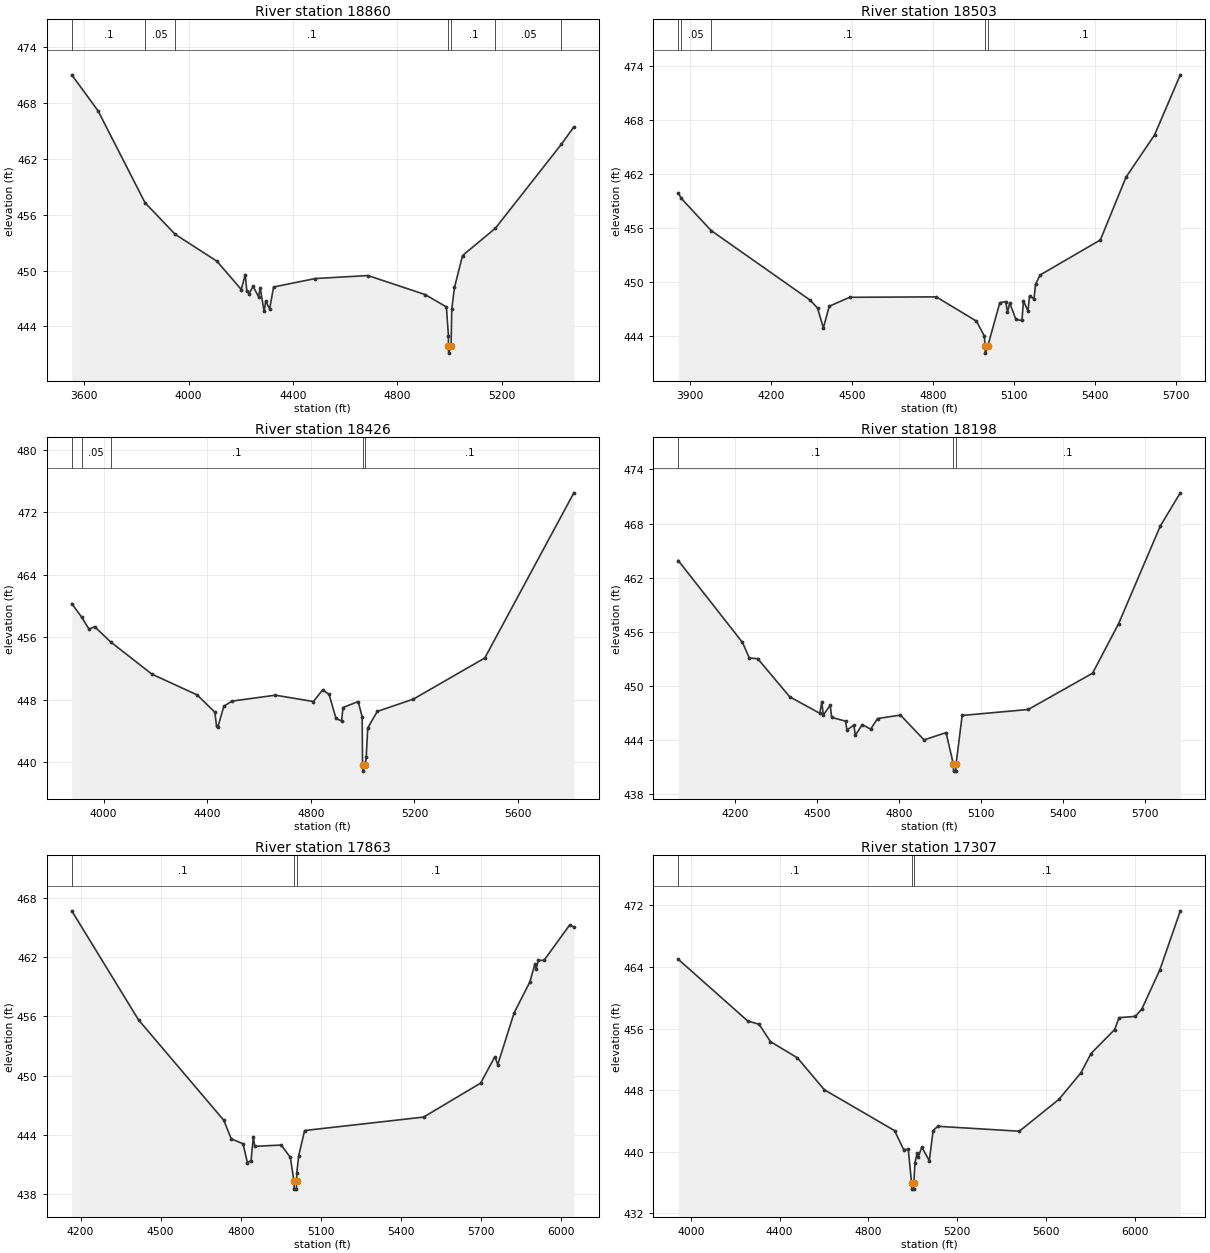
Type RM Length L Ch R = 1,18860,357,357,357
BEGIN DESCRIPTION:
Calf Creek 33.0
END DESCRIPTION:
XS GIS Cut Line= 3
      2008625.00     13451175.01      2009365.97     13450047.92
      2009509.30     13449492.35
#Sta/Elev= 30
  3552.9  471.05  3653.8  467.17  3833.4  457.30  3949.1  453.90  4108.8  451.01
  4202.1  447.97  4217.2  449.58  4223.2  447.82  4232.3  447.54  4247.0  448.31
  4268.5  447.19  4274.4  448.17  4289.5  445.61  4295.5  446.73  4310.6  445.89
  4325.7  448.24  4485.4  449.15  4687.2  449.47  4905.8  447.43  4987.4  446.10
  4995.2  443.02  4995.3  441.93  4996.2  441.13  5005.5  441.93  5008.0  445.86
  5018.4  448.19  5049.3  451.62  5175.2  454.56  5427.8  463.59  5475.5  465.45
#Mann=7,-1,0
  3552.9     0.1       0  3833.4    0.05       0  3949.1     0.1       0
  4995.3    0.07       0  5005.5     0.1       0  5175.2    0.05       0
  5427.8     0.1       0
Bank Sta=4995.3,5005.5
Exp/Cntr=0.3,0.1

Type RM Length L Ch R = 1,18503,77,77,77
BEGIN DESCRIPTION:
Mapping XS 5c222f87
END DESCRIPTION:
XS GIS Cut Line= 5
      2008869.97     13451052.00      2009330.92     13450218.65
      2009442.90     13450200.42      2009580.92     13450098.86
      2009859.32     13449539.45
#Sta/Elev= 30
  3855.8  459.94  3866.9  459.33  3977.7  455.75  4343.8  448.03  4372.4  447.13
  4394.1  444.92  4415.9  447.33  4491.5  448.32  4812.7  448.37  4961.8  445.67
  4991.1  444.00  4993.6  442.91  4994.5  442.11  5003.8  442.91  5048.4  447.72
  5070.6  447.84  5076.8  446.65  5085.2  447.68  5108.1  445.86  5130.5  445.74
  5136.1  447.92  5152.9  446.80  5158.5  448.47  5175.3  448.16  5180.8  449.75
  5197.7  450.80  5421.2  454.70  5516.7  461.70  5622.2  466.38  5717.8  473.07
#Mann=5,-1,0
  3855.8     0.1       0  3866.9    0.05       0  3977.7     0.1       0
  4993.6    0.07       0  5003.8     0.1       0
Bank Sta=4993.6,5003.8
Exp/Cntr=0.3,0.1

Type RM Length L Ch R = 1,18426,228,228,228
BEGIN DESCRIPTION:
Calf Creek 32.0
END DESCRIPTION:
XS GIS Cut Line= 5
      2008896.91     13451077.12      2009336.13     13450292.43
      2009429.88     13450285.49      2009660.78     13450146.60
      2009924.99     13449525.03
#Sta/Elev= 30
  3877.3  460.33  3915.8  458.58  3943.9  457.05  3965.6  457.37  4026.9  455.43
  4187.1  451.28  4361.1  448.63  4429.8  446.41  4436.0  444.66  4441.7  444.56
  4464.2  447.17  4495.3  447.83  4663.2  448.59  4810.0  447.78  4845.6  449.26
  4870.6  448.69  4897.3  445.61  4918.7  445.29  4924.5  447.01  4982.8  447.78
  4998.3  445.82  4999.8  439.66  5000.8  438.86  5010.0  439.66  5013.9  440.63
  5019.7  444.39  5056.6  446.51  5196.1  448.09  5471.7  453.36  5815.4  474.52
#Mann=5,-1,0
  3877.3     0.1       0  3915.8    0.05       0  4026.9     0.1       0
  4999.8    0.07       0  5010.0     0.1       0
Bank Sta=4999.8,5010
Exp/Cntr=0.3,0.1

Type RM Length L Ch R = 1,18198,335,335,335
BEGIN DESCRIPTION:
Mapping XS 2ccfbb20
END DESCRIPTION:
XS GIS Cut Line= 4
      2009310.09     13451281.14      2009583.52     13450528.54
      2009833.52     13450096.25      2010002.55     13449589.18
#Sta/Elev= 30
  3993.4  463.90  4228.0  454.83  4253.3  453.09  4283.9  453.02  4401.0  448.79
  4510.6  446.97  4518.1  448.26  4523.4  446.77  4548.7  447.87  4554.0  446.52
  4604.6  446.10  4609.9  445.12  4635.2  445.66  4640.5  444.53  4665.8  445.72
  4696.4  445.21  4721.7  446.39  4805.5  446.77  4891.7  444.02  4972.1  444.83
  4998.5  441.36  4999.4  440.56  5007.7  440.56  5008.7  441.36  5030.9  446.73
  5272.1  447.39  5507.3  451.41  5602.2  456.88  5755.0  467.73  5828.0  471.40
#Mann=3,-1,0
  3993.4     0.1       0  4998.5    0.07       0  5008.7     0.1       0
Bank Sta=4998.5,5008.7
Exp/Cntr=0.3,0.1

Type RM Length L Ch R = 1,17863,556,556,556
BEGIN DESCRIPTION:
Calf Creek 31.0
END DESCRIPTION:
XS GIS Cut Line= 3
      2009432.90     13451339.61      2009804.43     13450631.28
      2010214.14     13449631.31
#Sta/Elev= 30
  4167.1  466.68  4417.1  455.65  4736.7  445.48  4764.4  443.61  4808.5  443.11
  4824.9  441.21  4838.5  441.40  4847.0  443.77  4852.6  442.85  4951.5  442.98
  4985.8  441.73  4999.3  439.32  5000.2  438.52  5008.5  438.52  5009.5  439.32
  5009.8  440.15  5017.0  441.90  5039.2  444.45  5484.9  445.81  5698.5  449.25
  5751.9  451.92  5762.6  451.12  5823.9  456.36  5882.7  459.47  5901.3  461.26
  5906.7  460.79  5913.9  461.66  5936.1  461.68  6032.0  465.25  6047.6  465.05
#Mann=3,-1,0
  4167.1     0.1       0  4999.3    0.07       0  5009.5     0.1       0
Bank Sta=4999.3,5009.5
Exp/Cntr=0.3,0.1

Type RM Length L Ch R = 1,17307,352,352,352
BEGIN DESCRIPTION:
Calf Creek 30.0
END DESCRIPTION:
XS GIS Cut Line= 3
      2009866.91     13451721.59      2010200.26     13451006.28
      2010502.35     13449565.27
#Sta/Elev= 30
  3943.4  465.01  4256.3  457.00  4307.5  456.57  4358.9  454.31  4480.2  452.21
  4601.6  448.06  4917.8  442.76  4958.7  440.30  4979.6  440.32  4994.4  435.96
  4995.3  435.16  5003.7  435.16  5004.7  435.96  5009.7  438.60  5019.3  439.83
  5024.4  439.32  5040.4  440.62  5074.3  438.85  5091.5  442.75  5111.9  443.32
  5479.7  442.68  5657.9  446.81  5757.8  450.29  5802.6  452.77  5908.9  455.88
  5929.3  457.43  6002.2  457.59  6031.5  458.54  6113.2  463.67  6204.9  471.30
#Mann=3,-1,0
  3943.4     0.1       0  4994.4    0.07       0  5004.7     0.1       0
Bank Sta=4994.4,5004.7
Exp/Cntr=0.3,0.1