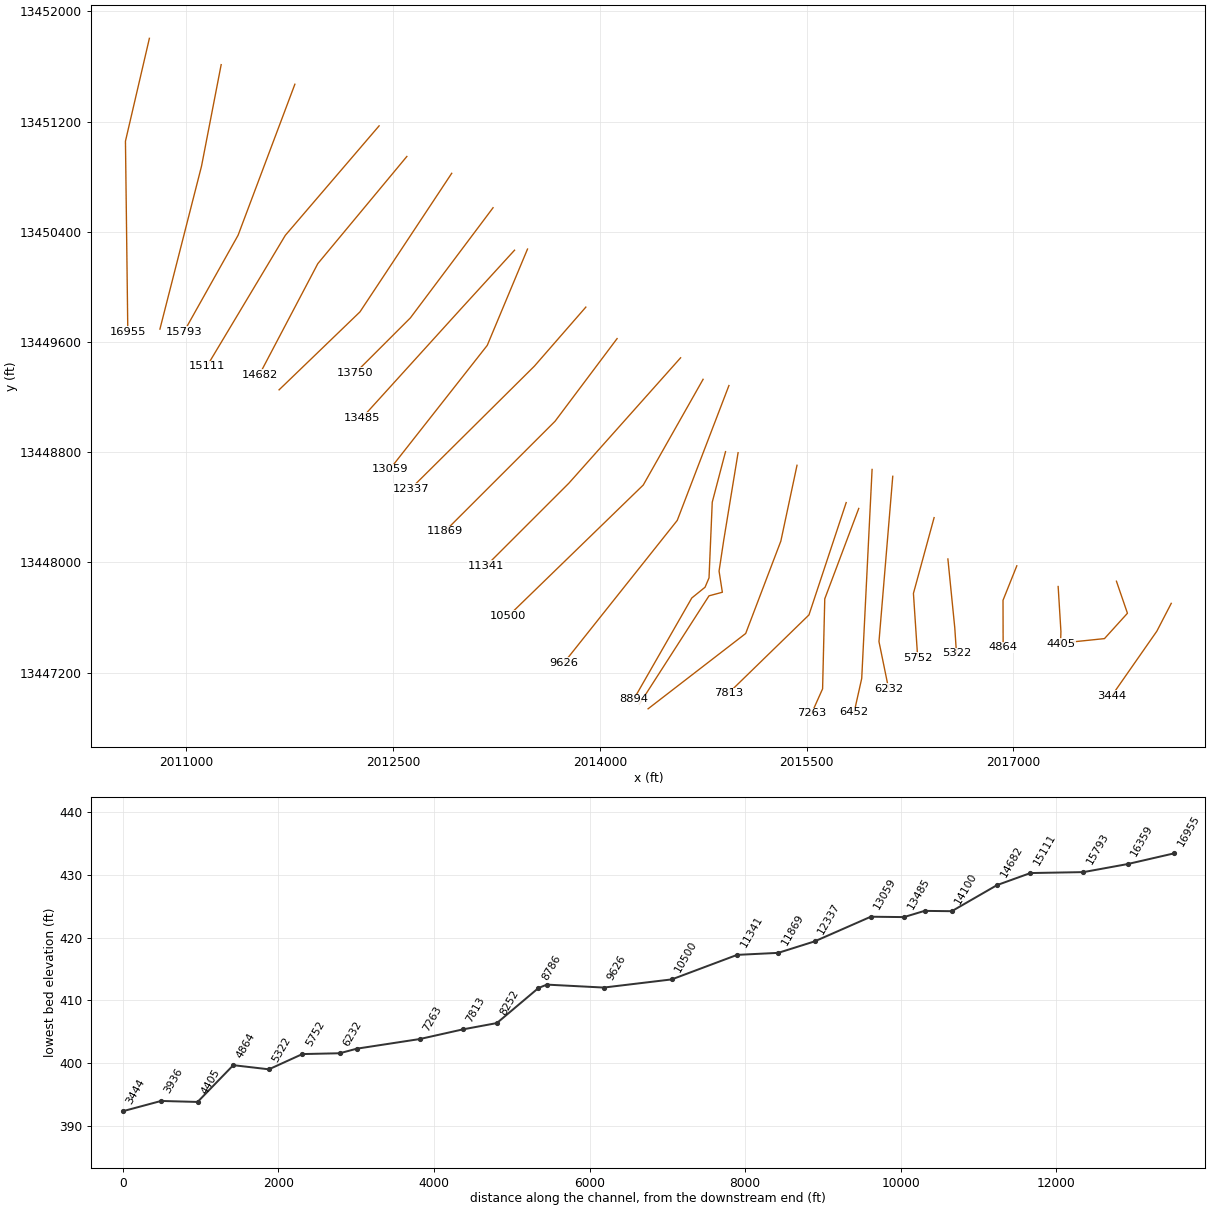
HEC-RAS study Calf Creek.prj: Calf Creek Base Level Engineering

--- Calf Creek.g01 (geometry) --- (continued)

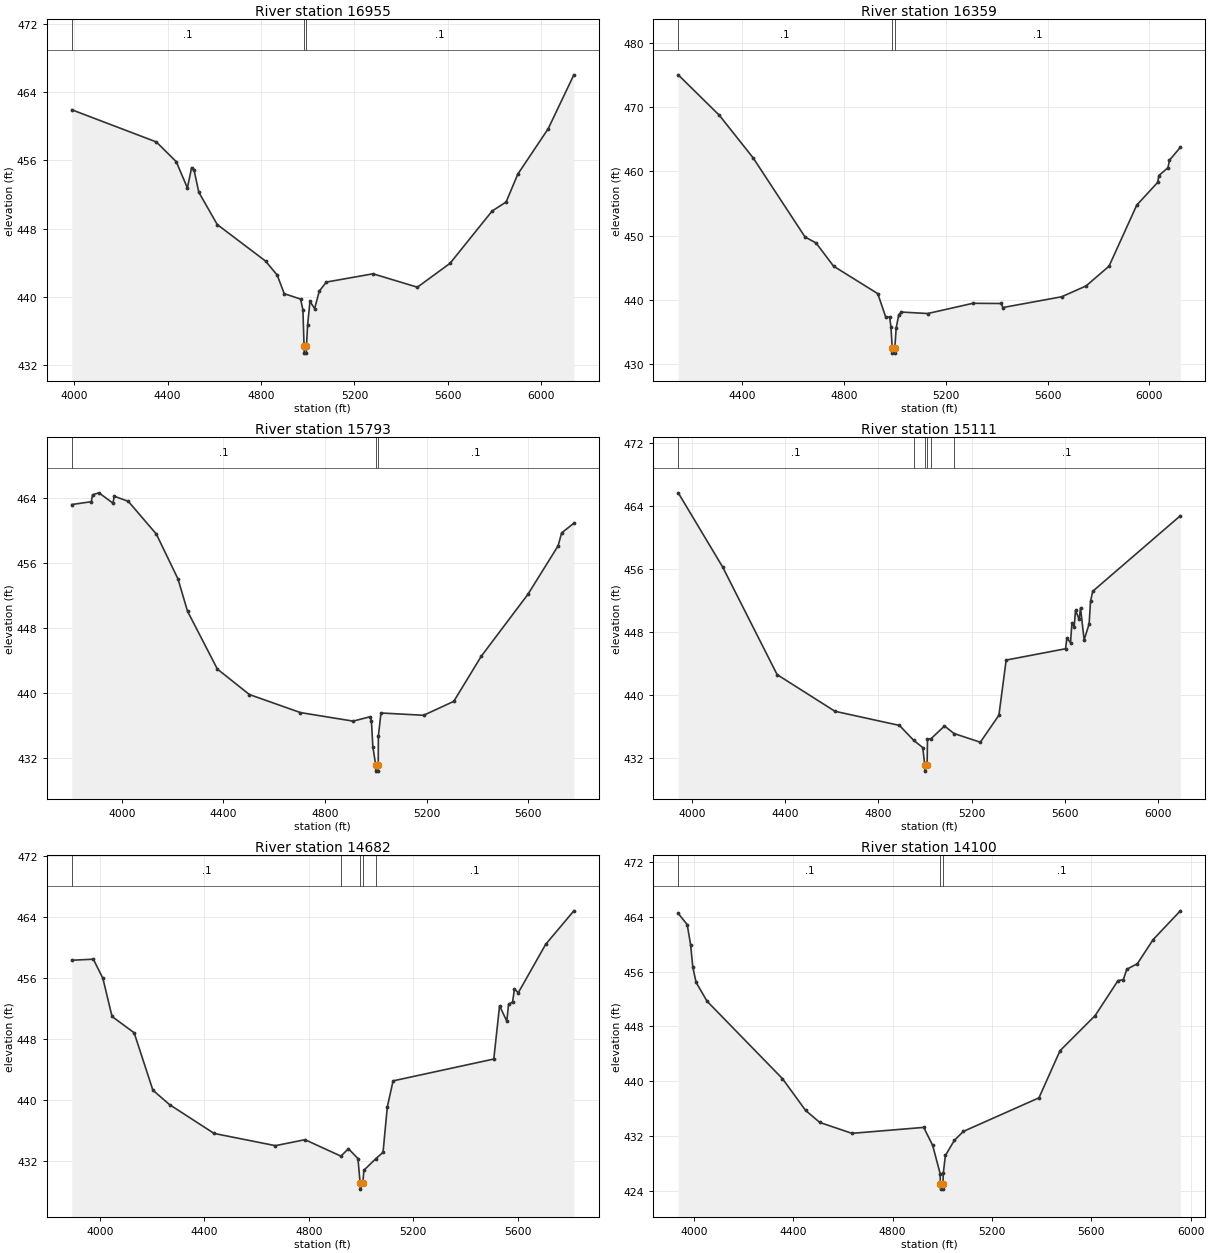
Type RM Length L Ch R = 1,16955,596,596,596
BEGIN DESCRIPTION:
Calf Creek 29.0
END DESCRIPTION:
XS GIS Cut Line= 3
      2010731.51     13451804.91      2010557.90     13451058.36
      2010575.00     13449675.04
#Sta/Elev= 30
  3989.8  461.92  4351.9  458.15  4437.1  455.84  4484.9  452.77  4503.0  455.15
  4513.3  454.87  4533.8  452.26  4612.7  448.48  4819.6  444.20  4869.6  442.55
  4899.6  440.38  4969.6  439.75  4979.6  438.49  4984.5  434.22  4985.4  433.42
  4993.8  433.42  4994.8  434.22  4999.6  436.69  5009.7  439.48  5029.7  438.64
  5049.7  440.68  5079.7  441.74  5279.7  442.71  5469.7  441.14  5609.7  443.94
  5789.7  450.06  5849.7  451.12  5899.7  454.38  6029.7  459.69  6139.7  466.01
#Mann=3,-1,0
  3989.8     0.1       0  4984.5    0.07       0  4994.8     0.1       0
Bank Sta=4984.5,4994.8
Exp/Cntr=0.3,0.1

Type RM Length L Ch R = 1,16359,566,566,566
BEGIN DESCRIPTION:
Calf Creek 28.0
END DESCRIPTION:
XS GIS Cut Line= 3
      2011252.33     13451613.88      2011109.98     13450877.81
      2010807.89     13449693.75
#Sta/Elev= 30
  4149.6  475.01  4311.4  468.70  4443.8  462.09  4647.5  449.79  4691.0  448.85
  4759.6  445.25  4933.2  440.97  4964.1  437.37  4979.9  437.32  4985.0  435.79
  4989.9  432.52  4990.9  431.72  4999.3  431.72  5000.2  432.52  5005.4  435.59
  5015.6  437.71  5026.1  438.11  5129.3  437.88  5306.8  439.47  5418.2  439.44
  5424.2  438.81  5655.6  440.49  5751.2  442.17  5841.4  445.25  5950.3  454.75
  6032.1  458.27  6037.4  459.35  6072.9  460.57  6078.7  461.74  6121.3  463.72
#Mann=3,-1,0
  4149.6     0.1       0  4989.9    0.07       0  5000.2     0.1       0
Bank Sta=4989.9,5000.2
Exp/Cntr=0.3,0.1

Type RM Length L Ch R = 1,15793,682,682,682
BEGIN DESCRIPTION:
Calf Creek 27.0
END DESCRIPTION:
XS GIS Cut Line= 3
      2011787.07     13451471.57      2011375.00     13450375.00
      2010981.53     13449672.98
#Sta/Elev= 30
  3803.1  463.23  3879.8  463.58  3885.1  464.43  3910.0  464.67  3965.2  463.40
  3970.5  464.25  4025.7  463.62  4135.9  459.60  4221.3  454.07  4258.8  450.10
  4376.3  442.99  4502.3  439.86  4703.3  437.64  4910.4  436.59  4977.4  437.13
  4982.5  436.66  4988.2  433.45  4999.1  431.24  5000.0  430.44  5008.5  430.44
  5009.4  431.24  5009.9  434.78  5020.2  437.59  5188.0  437.31  5306.6  439.02
  5415.1  444.58  5598.8  452.20  5717.5  458.16  5731.1  459.74  5779.3  460.93
#Mann=3,-1,0
  3803.1     0.1       0  4999.1    0.07       0  5009.4     0.1       0
Bank Sta=4999.1,5009.4
Exp/Cntr=0.3,0.1

Type RM Length L Ch R = 1,15111,429,429,429
BEGIN DESCRIPTION:
Calf Creek 26.0
END DESCRIPTION:
XS GIS Cut Line= 3
      2012398.15     13451169.45      2011717.62     13450374.33
      2011149.08     13449424.46
#Sta/Elev= 30
  3942.0  465.72  4132.1  456.30  4366.1  442.58  4614.2  437.91  4890.8  436.11
  4952.0  434.21  4991.1  433.28  4999.2  431.09  5000.1  430.29  5009.5  431.09
  5011.1  434.36  5026.4  434.42  5084.1  436.04  5124.8  435.08  5237.7  433.97
  5317.5  437.41  5348.6  444.43  5603.3  445.87  5609.2  447.22  5624.7  446.65
  5630.6  449.12  5640.3  448.65  5646.1  450.77  5661.7  449.61  5667.5  451.06
  5683.1  446.99  5704.5  449.04  5710.4  451.90  5720.0  453.19  6095.6  462.80
#Mann=6,-1,0
  3942.0     0.1       0  4952.0    0.12       0  4999.2    0.07       0
  5009.5    0.12       0  5026.4    0.07       0  5124.8     0.1       0
Bank Sta=4999.2,5009.5
Exp/Cntr=0.3,0.1

Type RM Length L Ch R = 1,14682,582,582,582
BEGIN DESCRIPTION:
Calf Creek 25.0
END DESCRIPTION:
XS GIS Cut Line= 3
      2012599.55     13450947.23      2011953.73     13450169.47
      2011530.11     13449363.90
#Sta/Elev= 30
  3893.1  458.33  3975.6  458.47  4012.1  455.97  4047.2  450.97  4131.8  448.84
  4203.5  441.32  4267.3  439.43  4437.8  435.66  4672.2  434.06  4785.5  434.84
  4922.9  432.69  4951.8  433.66  4988.2  432.37  4996.4  429.17  4997.3  428.37
  5006.8  429.17  5010.8  430.84  5055.4  432.32  5084.1  433.19  5100.5  439.14
  5122.5  442.54  5507.9  445.40  5530.0  452.36  5557.7  450.36  5564.4  452.56
  5579.7  452.86  5587.0  454.56  5601.8  454.09  5706.3  460.41  5814.2  464.80
#Mann=5,-1,0
  3893.1     0.1       0  4922.9    0.16       0  4996.4    0.07       0
  5006.8    0.16       0  5055.4     0.1       0
Bank Sta=4996.4,5006.8
Exp/Cntr=0.3,0.1

Type RM Length L Ch R = 1,14100,350,350,350
BEGIN DESCRIPTION:
Calf Creek 24.0
END DESCRIPTION:
XS GIS Cut Line= 3
      2012925.02     13450825.02      2012259.29     13449818.78
      2011672.48     13449252.81
#Sta/Elev= 30
  3936.9  464.48  3972.9  462.87  3986.6  459.95  3995.6  456.63  4008.9  454.42
  4052.8  451.67  4356.6  440.35  4450.0  435.70  4507.1  433.95  4636.5  432.36
  4925.4  433.23  4961.5  430.60  4991.6  426.47  4992.4  425.01  4993.3  424.21
  5001.9  424.21  5002.8  425.01  5004.1  426.50  5012.7  429.13  5048.8  431.33
  5084.9  432.64  5389.5  437.55  5474.4  444.44  5615.9  449.57  5707.8  454.68
  5729.1  454.80  5743.3  456.34  5785.7  457.14  5849.3  460.67  5958.7  464.87
#Mann=3,-1,0
  3936.9     0.1       0  4992.4    0.07       0  5002.8     0.1       0
Bank Sta=4992.4,5002.8
Exp/Cntr=0.3,0.1

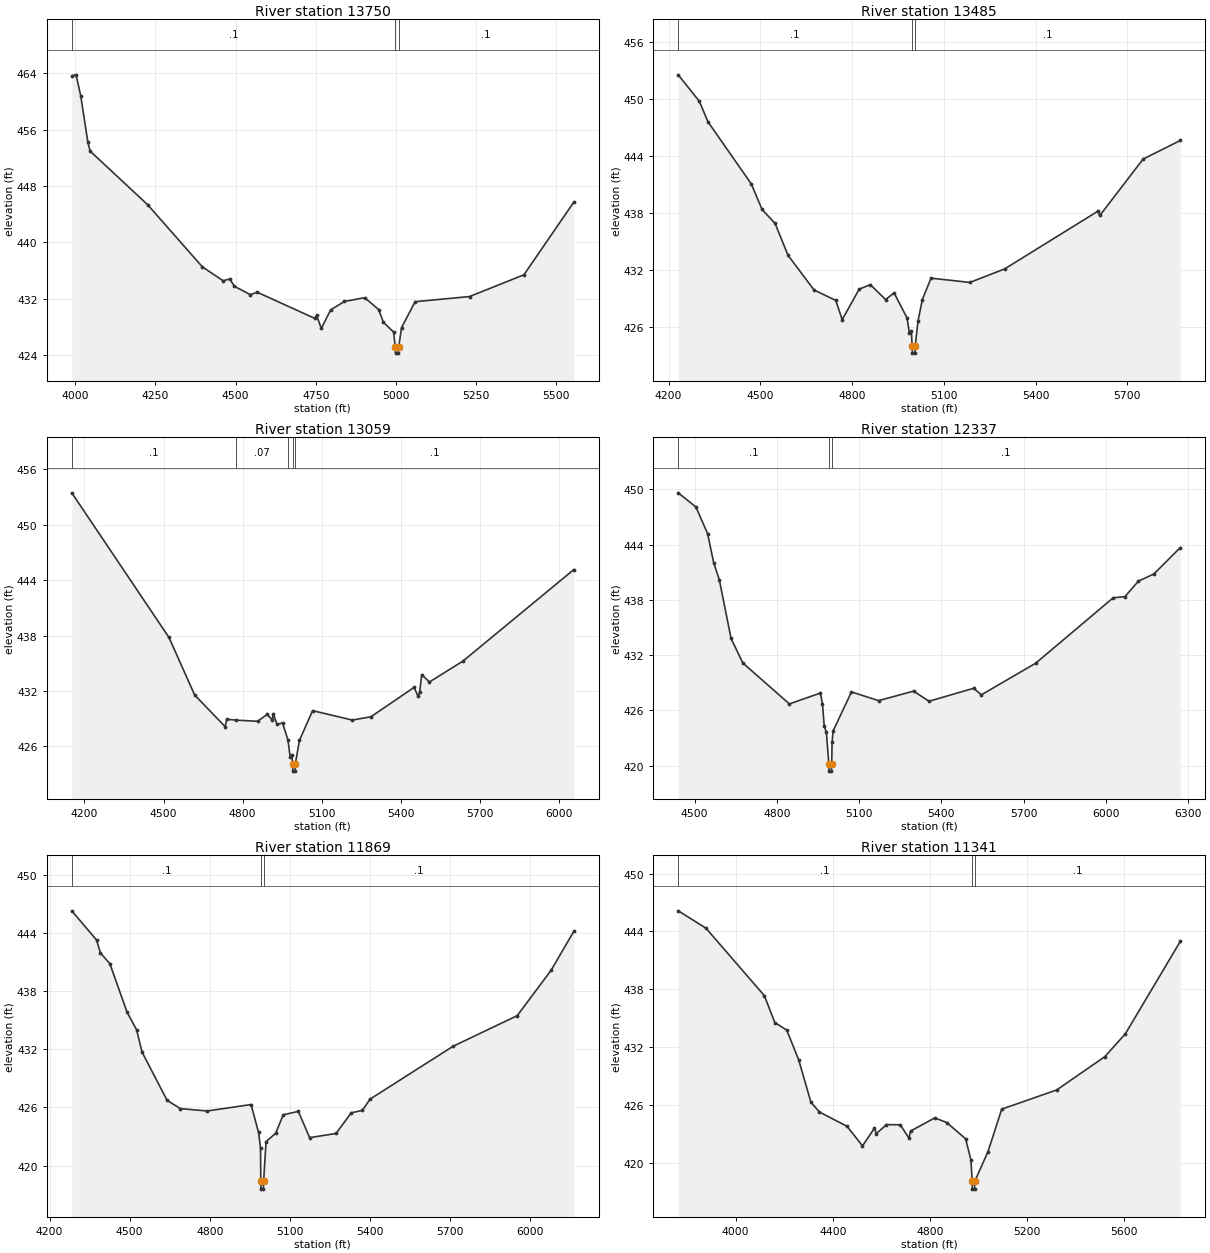
Type RM Length L Ch R = 1,13750,265,265,265
BEGIN DESCRIPTION:
Calf Creek 23.0
END DESCRIPTION:
XS GIS Cut Line= 3
      2013225.00     13450575.00      2012625.00     13449775.00
      2012224.99     13449374.99
#Sta/Elev= 30
  3989.0  463.62  4002.5  463.76  4017.1  460.74  4039.0  454.24  4046.3  452.93
  4225.5  445.33  4396.3  436.50  4460.9  434.53  4481.7  434.79  4496.3  433.74
  4546.3  432.55  4567.1  432.91  4746.3  429.20  4752.5  429.64  4767.1  427.76
  4796.3  430.39  4839.0  431.59  4902.5  432.13  4946.3  430.43  4960.9  428.63
  4992.5  427.26  4997.9  425.06  4998.8  424.26  5007.4  424.26  5008.3  425.06
  5017.3  427.87  5059.7  431.56  5229.4  432.29  5399.1  435.38  5554.7  445.70
#Mann=3,-1,0
  3989.0     0.1       0  4997.9    0.07       0  5008.3     0.1       0
Bank Sta=4997.9,5008.3
Exp/Cntr=0.3,0.1

Type RM Length L Ch R = 1,13485,426,426,426
BEGIN DESCRIPTION:
Calf Creek 22.0
END DESCRIPTION:
XS GIS Cut Line= 3
      2013380.83     13450266.71      2012981.51     13449829.20
      2012276.65     13449051.42
#Sta/Elev= 30
  4231.5  452.56  4300.8  449.76  4328.6  447.62  4470.4  441.08  4505.6  438.39
  4548.1  436.93  4590.7  433.56  4675.8  429.91  4746.7  428.82  4767.7  426.79
  4823.3  430.00  4859.6  430.48  4909.6  428.91  4937.5  429.61  4979.9  426.96
  4987.3  425.41  4994.1  425.59  4996.3  424.07  4997.2  423.27  5005.8  423.27
  5006.7  424.07  5015.7  426.65  5029.9  428.91  5058.3  431.16  5185.3  430.71
  5298.9  432.13  5603.0  438.19  5610.4  437.76  5751.7  443.69  5873.5  445.65
#Mann=3,-1,0
  4231.5     0.1       0  4996.3    0.07       0  5006.7     0.1       0
Bank Sta=4996.3,5006.7
Exp/Cntr=0.3,0.1

Type RM Length L Ch R = 1,13059,722,722,722
BEGIN DESCRIPTION:
Calf Creek 21.0
END DESCRIPTION:
XS GIS Cut Line= 3
      2013474.98     13450274.96      2013182.90     13449575.72
      2012475.00     13448675.00
#Sta/Elev= 30
  4152.1  453.47  4520.5  437.81  4618.1  431.57  4733.8  428.14  4739.2  428.95
  4775.6  428.85  4856.5  428.73  4892.9  429.47  4912.2  428.87  4915.9  429.52
  4930.3  428.40  4951.1  428.55  4971.5  426.73  4980.0  424.89  4987.1  425.11
  4989.2  424.13  4990.1  423.33  4998.8  423.33  4999.7  424.13  5015.3  426.66
  5065.0  429.88  5215.9  428.86  5286.4  429.22  5450.0  432.40  5464.4  431.46
  5470.8  431.87  5478.9  433.78  5507.8  432.98  5635.8  435.26  6055.5  445.16
#Mann=5,-1,0
  4152.1     0.1       0  4775.6    0.07       0  4971.5     0.1       0
  4989.2    0.07       0  4999.7     0.1       0
Bank Sta=4989.2,4999.7
Exp/Cntr=0.3,0.1

Type RM Length L Ch R = 1,12337,468,468,468
BEGIN DESCRIPTION:
Calf Creek 20.0
END DESCRIPTION:
XS GIS Cut Line= 3
      2013898.16     13449853.49      2013525.00     13449425.00
      2012628.65     13448535.35
#Sta/Elev= 30
  4440.2  449.63  4504.7  448.09  4547.4  445.19  4569.3  442.06  4590.2  440.16
  4632.9  433.81  4675.6  431.15  4845.6  426.70  4958.5  427.88  4966.2  426.72
  4972.8  424.25  4980.4  423.64  4989.4  420.20  4990.3  419.40  4999.0  419.40
  4999.9  420.20  5001.3  422.55  5005.1  423.77  5072.0  428.00  5171.0  427.06
  5298.3  428.09  5354.9  426.99  5517.5  428.40  5545.8  427.69  5743.8  431.12
  6026.6  438.23  6069.1  438.35  6118.6  440.04  6175.2  440.82  6271.3  443.69
#Mann=3,-1,0
  4440.2     0.1       0  4989.4    0.07       0  4999.9     0.1       0
Bank Sta=4989.4,4999.9
Exp/Cntr=0.3,0.1

Type RM Length L Ch R = 1,11869,528,528,528
BEGIN DESCRIPTION:
Calf Creek 19.0
END DESCRIPTION:
XS GIS Cut Line= 3
      2014124.99     13449624.98      2013675.00     13449025.00
      2012874.97     13448224.97
#Sta/Elev= 30
  4283.1  446.27  4375.8  443.27  4390.4  441.94  4425.8  440.82  4490.4  435.81
  4525.8  434.01  4546.6  431.70  4640.4  426.72  4690.4  425.87  4790.4  425.63
  4955.0  426.29  4983.1  423.41  4990.4  421.81  4991.4  418.37  4992.3  417.57
  5001.0  417.57  5001.9  418.37  5011.2  422.47  5047.2  423.33  5075.5  425.23
  5132.1  425.59  5174.5  422.88  5273.5  423.31  5330.1  425.43  5372.5  425.70
  5400.8  426.85  5711.9  432.30  5952.3  435.46  6079.6  440.15  6164.5  444.16
#Mann=3,-1,0
  4283.1     0.1       0  4991.4    0.07       0  5001.9     0.1       0
Bank Sta=4991.4,5001.9
Exp/Cntr=0.3,0.1

Type RM Length L Ch R = 1,11341,841,841,841
BEGIN DESCRIPTION:
Calf Creek 18.0
END DESCRIPTION:
XS GIS Cut Line= 3
      2014585.68     13449485.45      2013775.00     13448575.00
      2013174.99     13447974.99
#Sta/Elev= 30
  3763.5  446.13  3877.6  444.33  4118.4  437.32  4161.1  434.54  4210.4  433.75
  4259.7  430.65  4309.9  426.27  4345.0  425.25  4458.7  423.77  4522.3  421.74
  4571.6  423.58  4579.1  423.01  4621.0  423.94  4677.8  423.93  4713.7  422.54
  4720.4  423.28  4819.9  424.64  4869.3  424.16  4947.0  422.47  4968.8  420.28
  4974.0  418.05  4974.8  417.25  4983.6  417.25  4984.5  418.05  5039.1  421.14
  5095.7  425.55  5322.0  427.54  5520.0  430.99  5604.8  433.37  5831.1  442.96
#Mann=3,-1,0
  3763.5     0.1       0  4974.0    0.07       0  4984.5     0.1       0
Bank Sta=4974,4984.5
Exp/Cntr=0.3,0.1

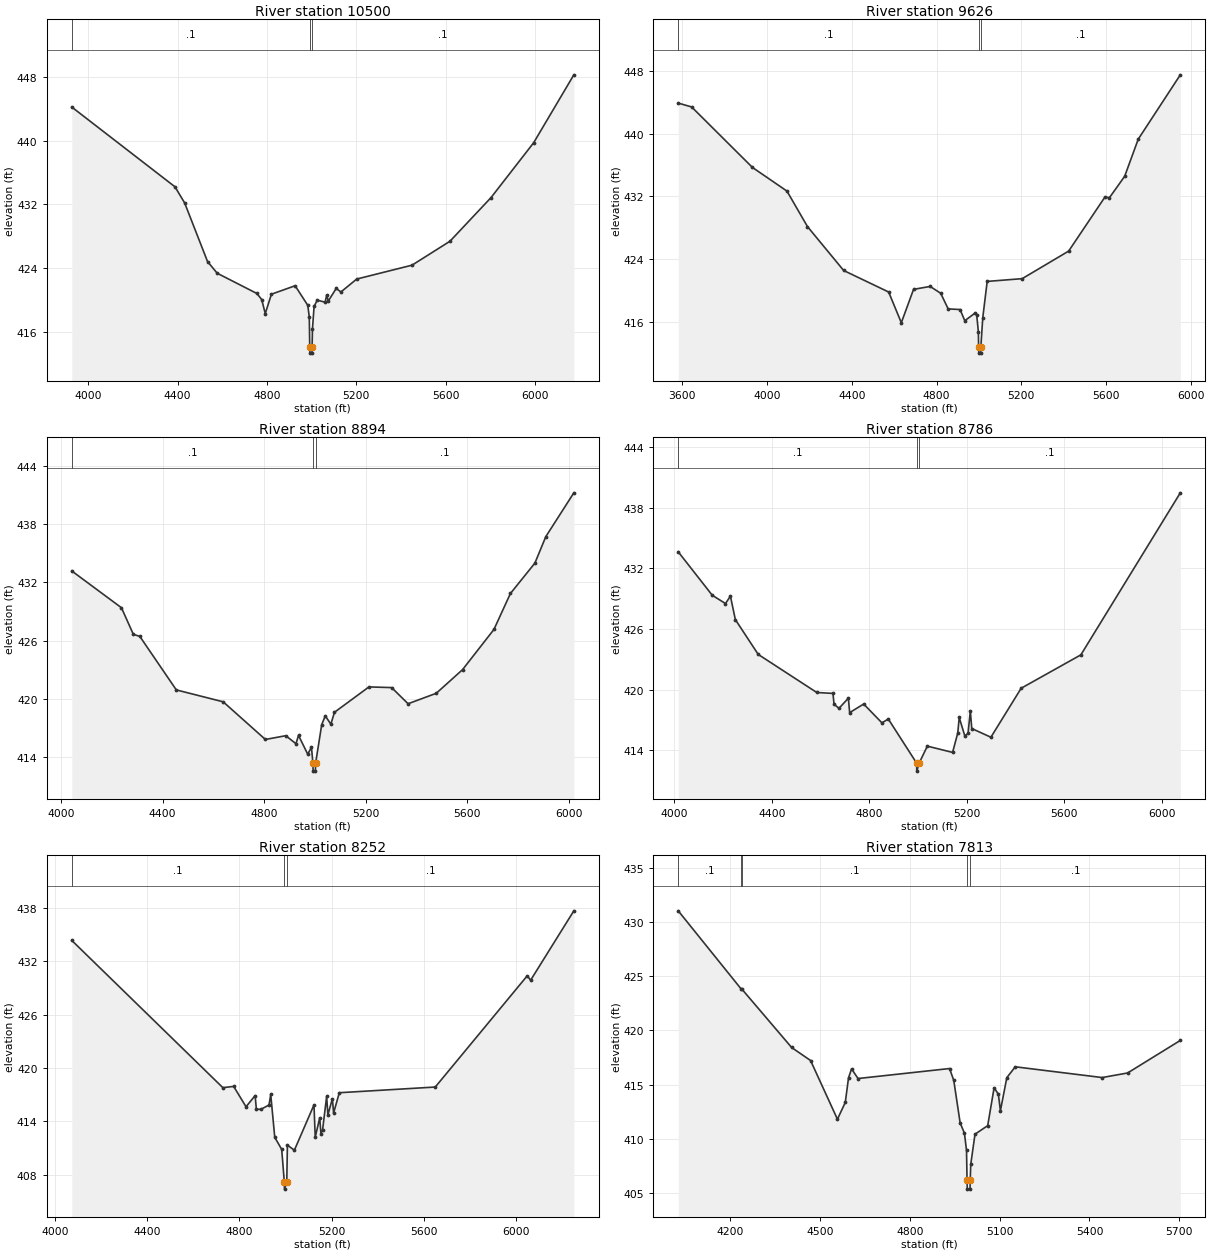
Type RM Length L Ch R = 1,10500,874,874,874
BEGIN DESCRIPTION:
Calf Creek 17.0
END DESCRIPTION:
XS GIS Cut Line= 3
      2014748.88     13449329.21      2014314.84     13448561.83
      2013335.65     13447610.42
#Sta/Elev= 30
  3926.5  444.20  4388.3  434.20  4431.6  432.18  4534.0  424.83  4577.3  423.36
  4754.9  420.82  4776.5  420.06  4792.4  418.30  4820.0  420.73  4926.0  421.79
  4982.6  419.34  4989.5  417.86  4991.4  414.14  4992.3  413.34  5001.1  413.34
  5002.0  414.14  5003.7  416.37  5010.9  419.19  5025.0  419.98  5060.3  419.73
  5067.4  420.62  5074.4  419.87  5109.9  421.45  5131.0  421.01  5201.7  422.63
  5449.3  424.37  5619.0  427.37  5802.9  432.85  5993.7  439.73  6173.4  448.24
#Mann=3,-1,0
  3926.5     0.1       0  4991.4    0.07       0  5002.0     0.1       0
Bank Sta=4991.4,5002
Exp/Cntr=0.3,0.1

Type RM Length L Ch R = 1,9626,732,732,732
BEGIN DESCRIPTION:
Calf Creek 16.0
END DESCRIPTION:
XS GIS Cut Line= 3
      2014936.39     13449284.10      2014561.37     13448304.89
      2013739.22     13447271.13
#Sta/Elev= 30
  3580.7  443.87  3644.0  443.38  3930.9  435.68  4093.7  432.67  4190.6  428.15
  4361.4  422.56  4573.7  419.82  4633.5  415.91  4691.2  420.16  4769.7  420.53
  4819.3  419.66  4854.6  417.67  4910.6  417.59  4933.0  416.17  4982.7  417.16
  4989.1  416.94  4997.1  414.76  4998.2  412.84  4999.1  412.04  5008.0  412.04
  5008.8  412.84  5017.9  416.56  5038.7  421.17  5203.8  421.52  5423.2  425.03
  5594.6  431.92  5615.4  431.82  5687.5  434.55  5751.6  439.28  5950.1  447.47
#Mann=3,-1,0
  3580.7     0.1       0  4998.2    0.07       0  5008.8     0.1       0
Bank Sta=4998.2,5008.8
Exp/Cntr=0.3,0.1

Type RM Length L Ch R = 1,8894,108,108,108
BEGIN DESCRIPTION:
Mapping XS 463493e6
END DESCRIPTION:
XS GIS Cut Line= 6
      2014911.65     13448804.15      2014815.29     13448436.96
      2014791.86     13447887.48      2014763.21     13447819.78
      2014666.86     13447741.65      2014245.00     13447004.71
#Sta/Elev= 30
  4042.1  433.19  4237.7  429.39  4284.6  426.64  4310.0  426.43  4453.8  420.90
  4638.4  419.67  4804.6  415.78  4884.9  416.17  4925.0  415.34  4935.0  416.20
  4971.3  414.26  4986.1  414.98  4991.7  413.31  4992.6  412.51  5001.5  412.51
  5002.3  413.31  5026.4  417.31  5040.4  418.22  5062.4  417.36  5076.7  418.59
  5212.4  421.21  5301.8  421.14  5366.5  419.47  5477.4  420.55  5580.9  422.99
  5704.7  427.15  5769.5  430.86  5865.9  434.00  5909.0  436.74  6019.3  441.26
#Mann=3,-1,0
  4042.1     0.1       0  4991.7    0.07       0  5002.3     0.1       0
Bank Sta=4991.7,5002.3
Exp/Cntr=0.3,0.1

Type RM Length L Ch R = 1,8786,534,534,534
BEGIN DESCRIPTION:
Calf Creek 15.0
END DESCRIPTION:
XS GIS Cut Line= 6
      2015002.80     13448796.37      2014898.63     13448160.92
      2014864.77     13447936.96      2014888.63     13447783.19
      2014791.86     13447757.28      2014286.63     13446970.79
#Sta/Elev= 30
  4015.8  433.63  4155.4  429.34  4209.7  428.52  4230.0  429.25  4250.3  426.93
  4344.3  423.49  4584.5  419.73  4650.9  419.64  4655.5  418.56  4675.8  418.17
  4714.3  419.17  4719.4  417.74  4777.0  418.59  4852.0  416.73  4878.1  417.11
  4994.2  412.76  4995.1  411.96  5004.8  412.76  5038.4  414.43  5142.0  413.81
  5163.3  415.73  5169.2  417.26  5192.3  415.43  5205.5  415.69  5214.8  417.91
  5220.7  416.17  5299.3  415.31  5423.5  420.15  5668.6  423.45  6076.8  439.46
#Mann=3,-1,0
  4015.8     0.1       0  4994.2    0.07       0  5004.8     0.1       0
Bank Sta=4994.2,5004.8
Exp/Cntr=0.3,0.1

Type RM Length L Ch R = 1,8252,439,439,439
BEGIN DESCRIPTION:
Calf Creek 14.0
END DESCRIPTION:
XS GIS Cut Line= 4
      2015430.29     13448705.03      2015313.03     13448154.62
      2015057.90     13447483.71      2014349.82     13446937.03
#Sta/Elev= 30
  4073.4  434.37  4727.9  417.80  4774.8  417.94  4828.3  415.65  4867.8  416.91
  4873.1  415.37  4892.5  415.36  4928.0  415.85  4935.3  417.04  4952.8  412.21
  4982.9  410.85  4994.2  407.18  4995.0  406.38  5004.8  407.18  5007.6  411.33
  5037.8  410.76  5122.7  415.86  5128.1  412.22  5147.5  414.40  5152.9  412.64
  5160.0  413.05  5177.6  416.81  5183.0  414.74  5202.4  416.55  5207.7  414.95
  5232.5  417.23  5648.2  417.87  6046.7  430.39  6061.2  429.89  6248.5  437.70
#Mann=3,-1,0
  4073.4     0.1       0  4994.2    0.07       0  5004.8     0.1       0
Bank Sta=4994.2,5004.8
Exp/Cntr=0.3,0.1

Type RM Length L Ch R = 1,7813,550,550,550
BEGIN DESCRIPTION:
Calf Creek 13.0
END DESCRIPTION:
XS GIS Cut Line= 3
      2015787.06     13448434.21      2015516.98     13447618.52
      2014931.98     13447049.12
#Sta/Elev= 30
  4027.5  431.01  4236.9  423.83  4239.5  423.81  4405.9  418.42  4469.1  417.22
  4558.8  411.81  4585.0  413.36  4595.8  415.62  4606.0  416.45  4627.5  415.56
  4933.0  416.48  4947.1  415.38  4968.4  411.46  4982.6  410.53  4989.6  408.94
  4991.4  406.17  4992.2  405.37  5001.2  405.37  5002.0  406.17  5003.7  407.65
  5017.9  410.43  5060.3  411.22  5081.6  414.70  5095.8  414.13  5102.7  412.59
  5124.1  415.64  5152.3  416.64  5442.2  415.65  5527.1  416.07  5703.1  419.07
#Mann=5,-1,0
  4027.5     0.1       0  4236.9    0.05       0  4239.5     0.1       0
  4991.4    0.07       0  5002.0     0.1       0
Bank Sta=4991.4,5002
Exp/Cntr=0.3,0.1

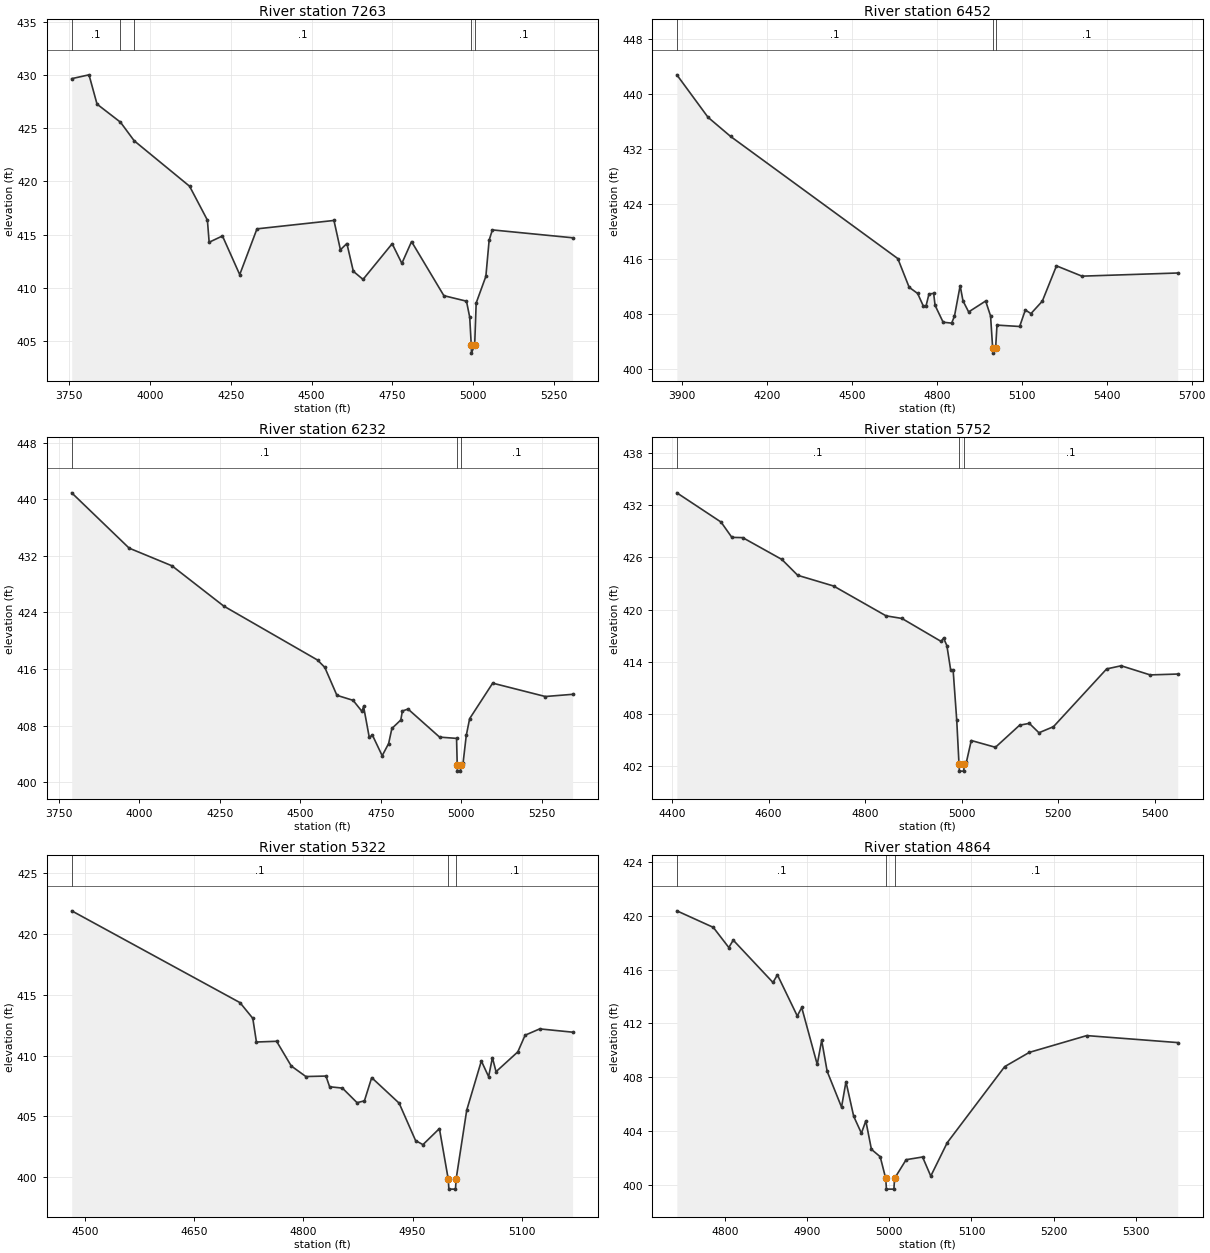
Type RM Length L Ch R = 1,7263,811,811,811
BEGIN DESCRIPTION:
Mapping XS 69faf8d7
END DESCRIPTION:
XS GIS Cut Line= 4
      2015878.21     13448391.70      2015631.68     13447735.45
      2015615.94     13447082.06      2015536.18     13446903.80
#Sta/Elev= 30
  3757.9  429.68  3811.4  430.04  3836.3  427.28  3908.8  425.58  3951.3  423.83
  4122.7  419.55  4177.8  416.36  4183.2  414.28  4224.4  414.87  4277.8  411.23
  4331.2  415.54  4569.4  416.33  4589.4  413.57  4609.4  414.16  4629.4  411.54
  4659.4  410.78  4749.5  414.14  4779.5  412.29  4809.5  414.34  4909.5  409.25
  4979.5  408.73  4989.5  407.22  4994.2  404.64  4995.0  403.84  5004.9  404.64
  5009.5  408.56  5039.5  411.07  5049.6  414.47  5059.6  415.44  5307.8  414.70
#Mann=5,-1,0
  3757.9     0.1       0  3908.8    0.05       0  3951.3     0.1       0
  4994.2    0.07       0  5004.9     0.1       0
Bank Sta=4994.2,5004.9
Exp/Cntr=0.3,0.1

Type RM Length L Ch R = 1,6452,220,220,220
BEGIN DESCRIPTION:
Calf Creek 12.0
END DESCRIPTION:
XS GIS Cut Line= 3
      2015975.00     13448674.97      2015899.80     13447157.58
      2015845.10     13446912.77
#Sta/Elev= 30
  3880.7  442.83  3990.8  436.65  4070.9  433.85  4661.6  416.07  4701.7  411.89
  4731.7  410.99  4751.7  409.16  4761.7  409.23  4771.8  410.92  4788.3  410.99
  4793.3  409.25  4821.8  406.80  4851.9  406.67  4861.9  407.70  4881.9  412.12
  4891.9  409.92  4911.9  408.30  4972.0  409.89  4989.4  407.71  4996.7  403.10
  4997.5  402.30  5007.4  403.10  5012.1  406.38  5092.2  406.18  5112.2  408.58
  5132.2  408.06  5172.3  409.87  5222.3  415.01  5312.4  413.51  5650.8  413.97
#Mann=3,-1,0
  3880.7     0.1       0  4996.7    0.07       0  5007.4     0.1       0
Bank Sta=4996.7,5007.4
Exp/Cntr=0.3,0.1

Type RM Length L Ch R = 1,6232,480,480,480
BEGIN DESCRIPTION:
Calf Creek 11.0
END DESCRIPTION:
XS GIS Cut Line= 3
      2016125.00     13448625.04      2016025.00     13447425.00
      2016095.10     13447082.09
#Sta/Elev= 30
  3790.8  440.92  3969.0  433.10  4101.9  430.60  4262.5  424.91  4553.5  417.28
  4576.1  416.24  4613.7  412.29  4663.9  411.58  4691.4  410.02  4696.5  410.71
  4714.0  406.37  4724.1  406.64  4754.2  403.75  4774.2  405.47  4784.3  407.60
  4811.9  408.80  4816.9  410.07  4834.4  410.35  4932.3  406.38  4985.0  406.20
  4987.1  402.37  4987.9  401.57  4997.0  401.57  4997.8  402.37  5005.2  402.71
  5015.1  406.61  5025.6  408.99  5097.1  414.01  5260.4  412.12  5345.0  412.43
#Mann=3,-1,0
  3790.8     0.1       0  4987.1    0.07       0  4997.8     0.1       0
Bank Sta=4987.1,4997.8
Exp/Cntr=0.3,0.1

Type RM Length L Ch R = 1,5752,430,430,430
BEGIN DESCRIPTION:
Calf Creek 10.0
END DESCRIPTION:
XS GIS Cut Line= 3
      2016425.01     13448325.02      2016275.00     13447775.00
      2016305.91     13447308.03
#Sta/Elev= 30
  4409.8  433.43  4501.4  430.07  4523.8  428.31  4546.3  428.28  4627.5  425.77
  4660.3  423.95  4734.6  422.72  4843.4  419.29  4876.3  418.99  4957.5  416.35
  4962.6  416.73  4969.5  415.86  4977.3  413.07  4982.4  413.07  4989.9  407.28
  4994.6  402.24  4995.4  401.44  5004.5  401.44  5005.3  402.24  5010.0  402.49
  5020.0  404.96  5070.1  404.18  5120.2  406.72  5140.3  406.93  5160.3  405.85
  5190.4  406.55  5300.6  413.19  5330.7  413.55  5390.8  412.50  5447.9  412.60
#Mann=3,-1,0
  4409.8     0.1       0  4994.6    0.07       0  5005.3     0.1       0
Bank Sta=4994.6,5005.3
Exp/Cntr=0.3,0.1

Type RM Length L Ch R = 1,5322,458,458,458
BEGIN DESCRIPTION:
Calf Creek 9.0
END DESCRIPTION:
XS GIS Cut Line= 3
      2016525.00     13448024.96      2016575.00     13447525.00
      2016587.29     13447339.97
#Sta/Elev= 30
  4481.8  421.90  4712.9  414.35  4730.5  413.06  4735.5  411.11  4763.2  411.17
  4783.3  409.14  4803.4  408.27  4831.0  408.31  4836.0  407.43  4853.6  407.32
  4873.7  406.12  4883.8  406.27  4893.8  408.18  4931.5  406.08  4954.1  403.00
  4964.2  402.67  4986.8  403.99  4999.0  399.81  4999.8  399.01  5008.9  399.01
  5009.7  399.81  5024.3  405.50  5044.4  409.55  5054.4  408.26  5059.6  409.82
  5064.6  408.67  5094.5  410.30  5104.5  411.67  5124.6  412.19  5169.7  411.92
#Mann=3,-1,0
  4481.8     0.1       0  4999.0    0.07       0  5009.7     0.1       0
Bank Sta=4999,5009.7
Exp/Cntr=0.3,0.1

Type RM Length L Ch R = 1,4864,459,459,459
BEGIN DESCRIPTION:
Calf Creek 8.0
END DESCRIPTION:
XS GIS Cut Line= 3
      2017025.00     13447975.00      2016925.00     13447725.00
      2016925.84     13447384.16
#Sta/Elev= 30
  4741.1  420.37  4785.5  419.14  4804.4  417.64  4809.8  418.19  4858.2  415.04
  4863.6  415.61  4887.8  412.55  4893.2  413.18  4912.1  408.94  4917.5  410.74
  4924.2  408.43  4941.7  405.77  4947.1  407.66  4956.5  405.09  4965.9  403.83
  4971.3  404.75  4978.1  402.63  4988.8  402.08  4995.5  400.47  4996.4  399.67
  5005.5  399.67  5006.3  400.47  5020.4  401.86  5040.4  402.06  5050.4  400.64
  5070.4  403.12  5140.4  408.78  5170.4  409.84  5240.4  411.09  5351.2  410.57
#Mann=3,-1,0
  4741.1     0.1       0  4995.5    0.07       0  5006.3     0.1       0
Bank Sta=4995.5,5006.3
Exp/Cntr=0.3,0.1

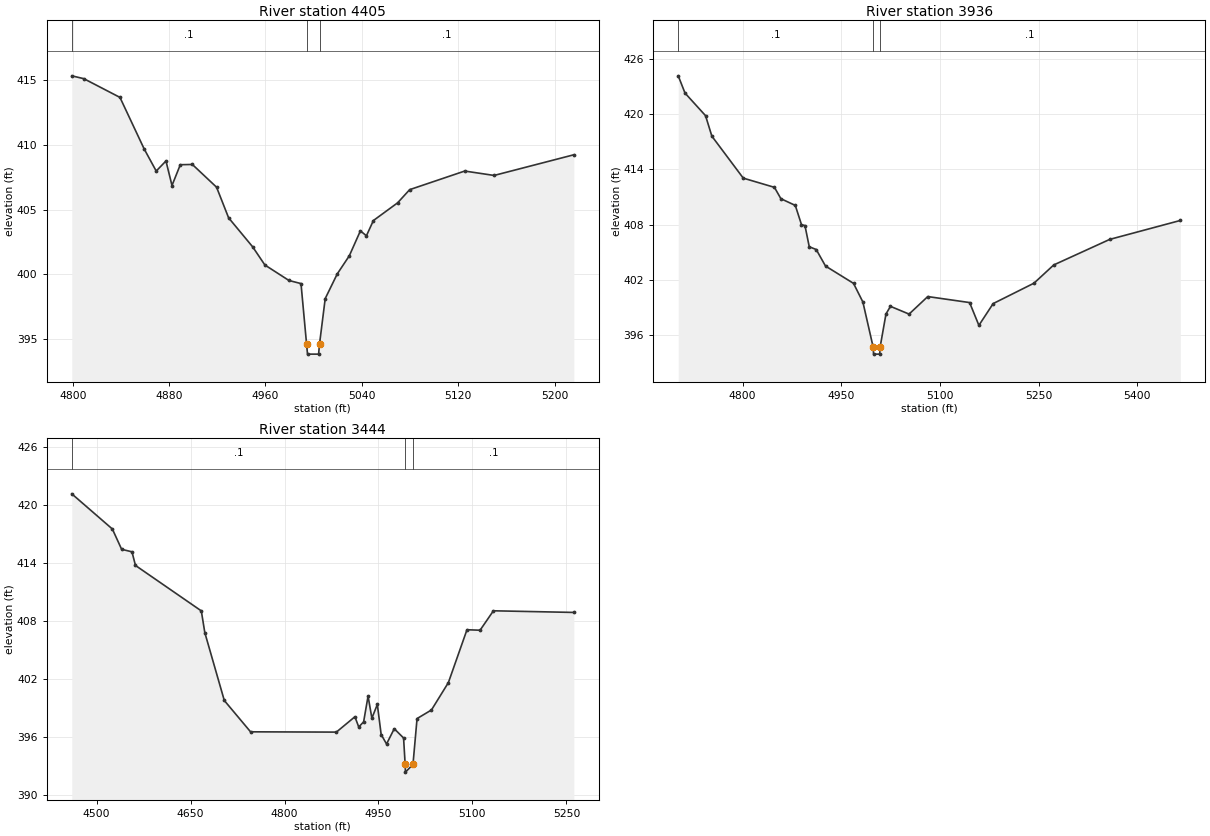
Type RM Length L Ch R = 1,4405,469,469,469
BEGIN DESCRIPTION:
Calf Creek 7.0
END DESCRIPTION:
XS GIS Cut Line= 3
      2017325.00     13447824.96      2017345.11     13447498.73
      2017342.54     13447408.81
#Sta/Elev= 30
  4799.2  415.35  4809.2  415.13  4839.2  413.68  4859.3  409.69  4869.3  407.98
  4877.4  408.76  4882.4  406.86  4889.3  408.47  4899.3  408.49  4919.4  406.73
  4929.4  404.36  4949.4  402.11  4959.5  400.71  4979.5  399.51  4989.5  399.27
  4994.1  394.61  4994.9  393.81  5004.1  393.81  5004.9  394.61  5009.6  398.11
  5019.6  400.02  5029.6  401.42  5038.8  403.35  5043.8  402.97  5049.6  404.15
  5069.7  405.52  5079.7  406.54  5125.4  407.98  5149.8  407.64  5216.0  409.24
#Mann=3,-1,0
  4799.2     0.1       0  4994.1    0.07       0  5004.9     0.1       0
Bank Sta=4994.1,5004.9
Exp/Cntr=0.3,0.1

Type RM Length L Ch R = 1,3936,492,492,492
BEGIN DESCRIPTION:
Mapping XS f2712db9
END DESCRIPTION:
XS GIS Cut Line= 4
      2017747.89     13447863.31      2017827.75     13447630.67
      2017661.08     13447446.65      2017393.76     13447418.87
#Sta/Elev= 30
  4702.3  424.14  4712.6  422.27  4743.8  419.82  4753.4  417.60  4801.1  413.05
  4848.5  412.05  4858.3  410.82  4880.2  410.09  4889.6  408.01  4894.9  407.90
  4901.4  405.61  4912.0  405.31  4926.1  403.52  4968.7  401.64  4982.9  399.62
  4998.4  394.77  4999.2  393.97  5008.4  393.97  5009.2  394.77  5018.0  398.32
  5024.8  399.15  5053.1  398.31  5081.5  400.21  5145.1  399.56  5159.2  397.09
  5180.9  399.45  5242.9  401.66  5273.0  403.64  5358.1  406.41  5465.3  408.46
#Mann=3,-1,0
  4702.3     0.1       0  4998.4    0.07       0  5009.2     0.1       0
Bank Sta=4998.4,5009.2
Exp/Cntr=0.3,0.1

Type RM Length L Ch R = 1,3444,0,0,0
BEGIN DESCRIPTION:
Calf Creek 6.0
END DESCRIPTION:
XS GIS Cut Line= 3
      2018145.58     13447702.56      2018041.40     13447501.14
      2017712.66     13447029.71
#Sta/Elev= 30
  4460.4  421.12  4525.2  417.48  4540.0  415.38  4556.5  415.12  4562.1  413.71
  4667.2  409.01  4672.8  406.76  4703.9  399.74  4745.8  396.50  4882.8  396.47
  4912.4  398.06  4918.5  397.00  4926.3  397.53  4933.4  400.19  4939.5  397.91
  4948.2  399.33  4954.3  396.22  4962.9  395.24  4975.2  396.82  4990.1  395.86
  4992.6  393.13  4993.1  392.33  5005.1  393.13  5011.6  397.87  5034.6  398.76
  5061.6  401.59  5091.3  407.06  5112.2  407.01  5133.5  409.02  5261.9  408.85
#Mann=3,-1,0
  4460.4     0.1       0  4992.6    0.07       0  5005.1     0.1       0
Bank Sta=4992.6,5005.1
Exp/Cntr=0.3,0.1

Chan Stop Cuts=-1